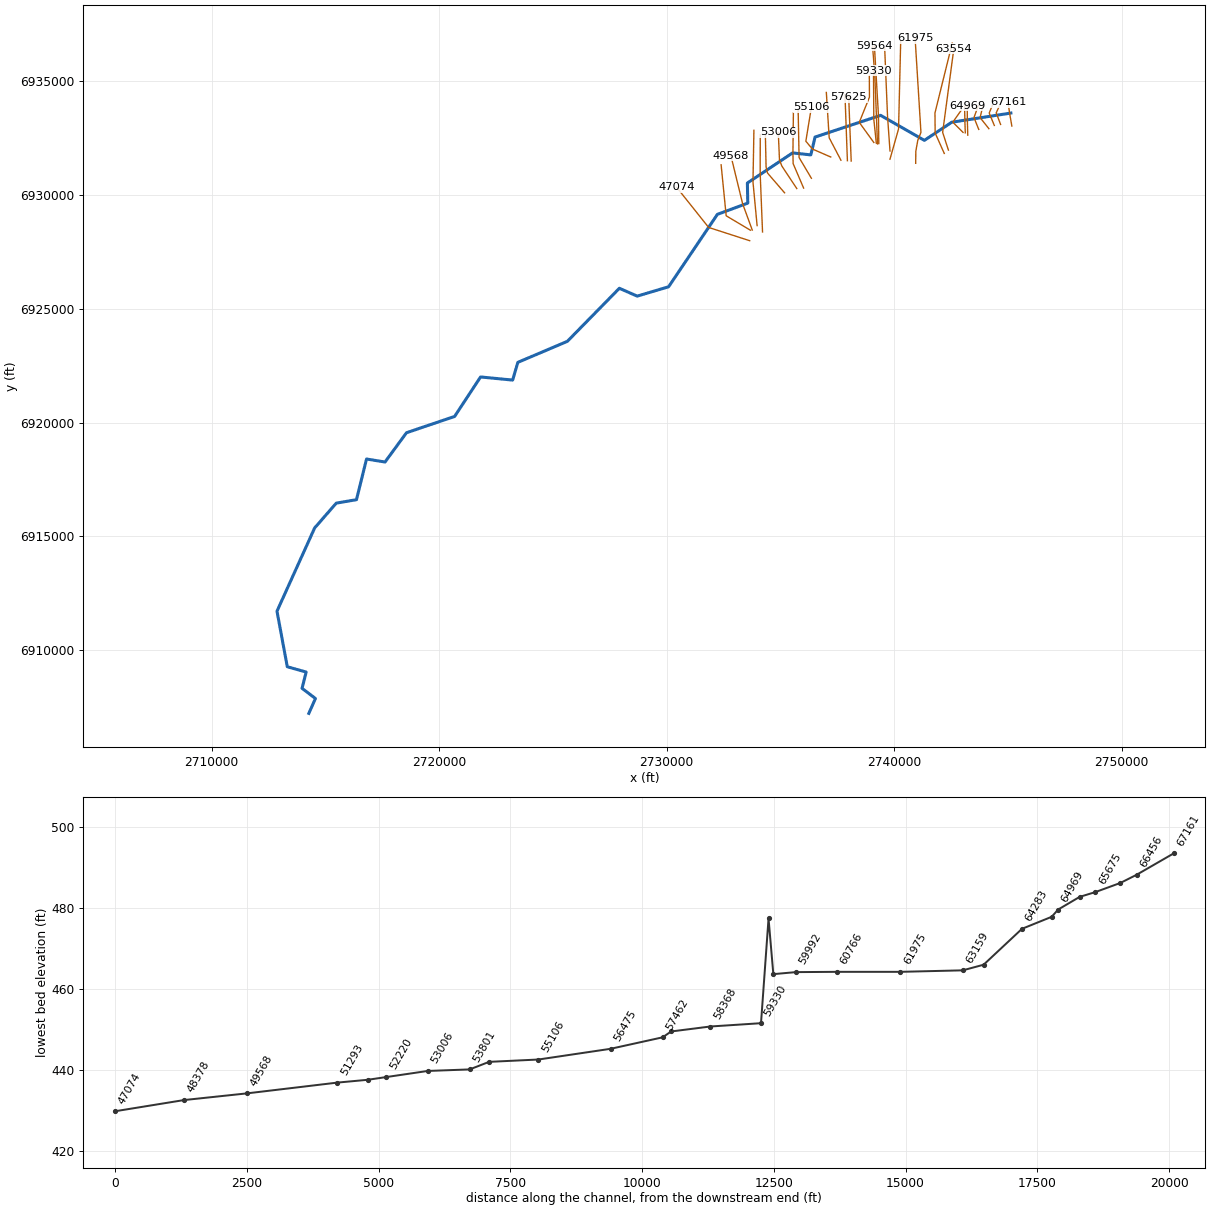
--- Allen Creek.prj (project) ---

Proj Title=Allen Creek Base Level Engineering
Current Plan=p01
Default Exp/Contr=0.3,0.1
English Units
Geom File=g01
Flow File=f01
Plan File=p01
Y Axis Title=Elevation
X Axis Title(PF)=Main Channel Distance
X Axis Title(XS)=Station
BEGIN DESCRIPTION:
Allen Creek
END DESCRIPTION:
DSS Export Rating Curves= 0
DSS Export Rating Curve Sorted= 0
DSS Export Volume Flow Curves= 0
DXF OffsetX= 0
DXF OffsetY= 0
DXF ScaleX= 1
DXF ScaleY= 10

--- Allen Creek.p01 (plan) ---

Plan Title=Multiple Run
Short Identifier=Multiple
Geom File=g01
Flow File=f01
Subcritical Flow
K Sum by GR= 0
Std Step Tol= 0.01
Critical Tol= 0.01
Num of Std Step Trials= 20
Max Error Tol= 0.3
Flow Tol Ratio= 0.001
Split Flow NTrial= 30
Split Flow Tol= 0.02
Split Flow Ratio= 0.02
Log Output Level= 0
Friction Slope Method= 1
Unsteady Friction Slope Method= 2
Unsteady Bridges Friction Slope Method= 1
Parabolic Critical Depth
Global Vel Dist=  1 , 1 , 1
Global Log Level= 0
CheckData=True
Encroach Param= -1, 0, 0, 0
BEGIN DESCRIPTION:
Multiple Run
END DESCRIPTION:

--- Allen Creek.f01 (steady flow) ---

Flow Title=Multiple
Program Version=4.10
Number of Profiles= 7
Profile Names=10-year,25-year,50-year,1pct_min,100-year,1pct_plu,500-year
River Rch & RM=Allen Creek,Reach-1         ,67161
     305     393     462     271     540    1078     739
River Rch & RM=Allen Creek,Reach-1         ,63554
    1264    1745    2146    1307    2609    5205    3865
River Rch & RM=Allen Creek,Reach-1         ,59992
    1311    1814    2233    1361    2716    5420    4032
River Rch & RM=Allen Creek,Reach-1         ,59330
    1370    1903    2349    1436    2866    5719    4278
River Rch & RM=Allen Creek,Reach-1         ,57625
    2328    3286    4098    2522    5033   10042    7592
River Rch & RM=Allen Creek,Reach-1         ,52220
    2625    3719    4650    2868    5722   11416    8666
River Rch & RM=Allen Creek,Reach-1         ,47074
    3571    5090    6389    3952    7885   15732   12010
River Rch & RM=Allen Creek,Reach-1         ,44490
    3691    5267    6616    4095    8170   16302   12461
River Rch & RM=Allen Creek,Reach-1         ,43318
    3658    5210    6537    4041    8062   16086   12265
River Rch & RM=Allen Creek,Reach-1         ,38463
    3722    5303    6654    4113    8206   16374   12485
River Rch & RM=Allen Creek,Reach-1         ,36722
    3986    5667    7100    4380    8739   17437   13242
River Rch & RM=Allen Creek,Reach-1         ,24735
    5124    7347    9257    5740   11453   22851   17531
River Rch & RM=Allen Creek,Reach-1         ,12969
    6820    9864   12504    7796   15556   31038   24072
River Rch & RM=Allen Creek,Reach-1         ,10117
    6727    9706   12284    7646   15256   30440   23526
Boundary for River Rch & Prof#=Allen Creek,Reach-1         , 1
Up Type= 0
Dn Type= 3
Dn Slope=0.00089
Boundary for River Rch & Prof#=Allen Creek,Reach-1         , 2
Up Type= 0
Dn Type= 3
Dn Slope=0.00089
Boundary for River Rch & Prof#=Allen Creek,Reach-1         , 3
Up Type= 0
Dn Type= 3
Dn Slope=0.00089
Boundary for River Rch & Prof#=Allen Creek,Reach-1         , 4
Up Type= 0
Dn Type= 3
Dn Slope=0.00089
Boundary for River Rch & Prof#=Allen Creek,Reach-1         , 5
Up Type= 0
Dn Type= 3
Dn Slope=0.00089
Boundary for River Rch & Prof#=Allen Creek,Reach-1         , 6
Up Type= 0
Dn Type= 3
Dn Slope=0.00089
Boundary for River Rch & Prof#=Allen Creek,Reach-1         , 7
Up Type= 0
Dn Type= 3
Dn Slope=0.00089
DSS Import GetInterval= 0
DSS Import GetPeak= 0
DSS Import FillOption= 0

--- Allen Creek.g01 (geometry) ---

Geom Title=Existing Conditions
Program Version=4.10

River Reach=Allen Creek     ,Reach-1
Reach XY= 30
        2745126.        6933611.      2742531.88      6933209.04
        2741326.        6932411.      2739401.31      6933511.27
      2736522.99      6932555.54      2736336.38       6931771.8
      2735534.54      6931858.42      2733548.83      6930535.48
      2733565.72      6929650.82      2732231.26      6929156.41
      2730086.11      6925971.61      2728705.97      6925560.55
      2727923.54      6925905.57      2725636.11       6923571.3
      2723462.38      6922648.07      2723232.38      6921868.35
      2721823.25      6922005.71      2720682.52      6920268.67
      2718569.15      6919553.18      2717624.54      6918264.52
      2716812.67      6918397.67      2716370.18      6916608.14
      2715484.08      6916458.18      2714533.48      6915367.07
      2712877.49      6911705.16      2713329.42      6909262.23
      2714159.81      6909027.67      2713979.08      6908312.66
      2714568.42      6907864.34        2714276.        6907211.

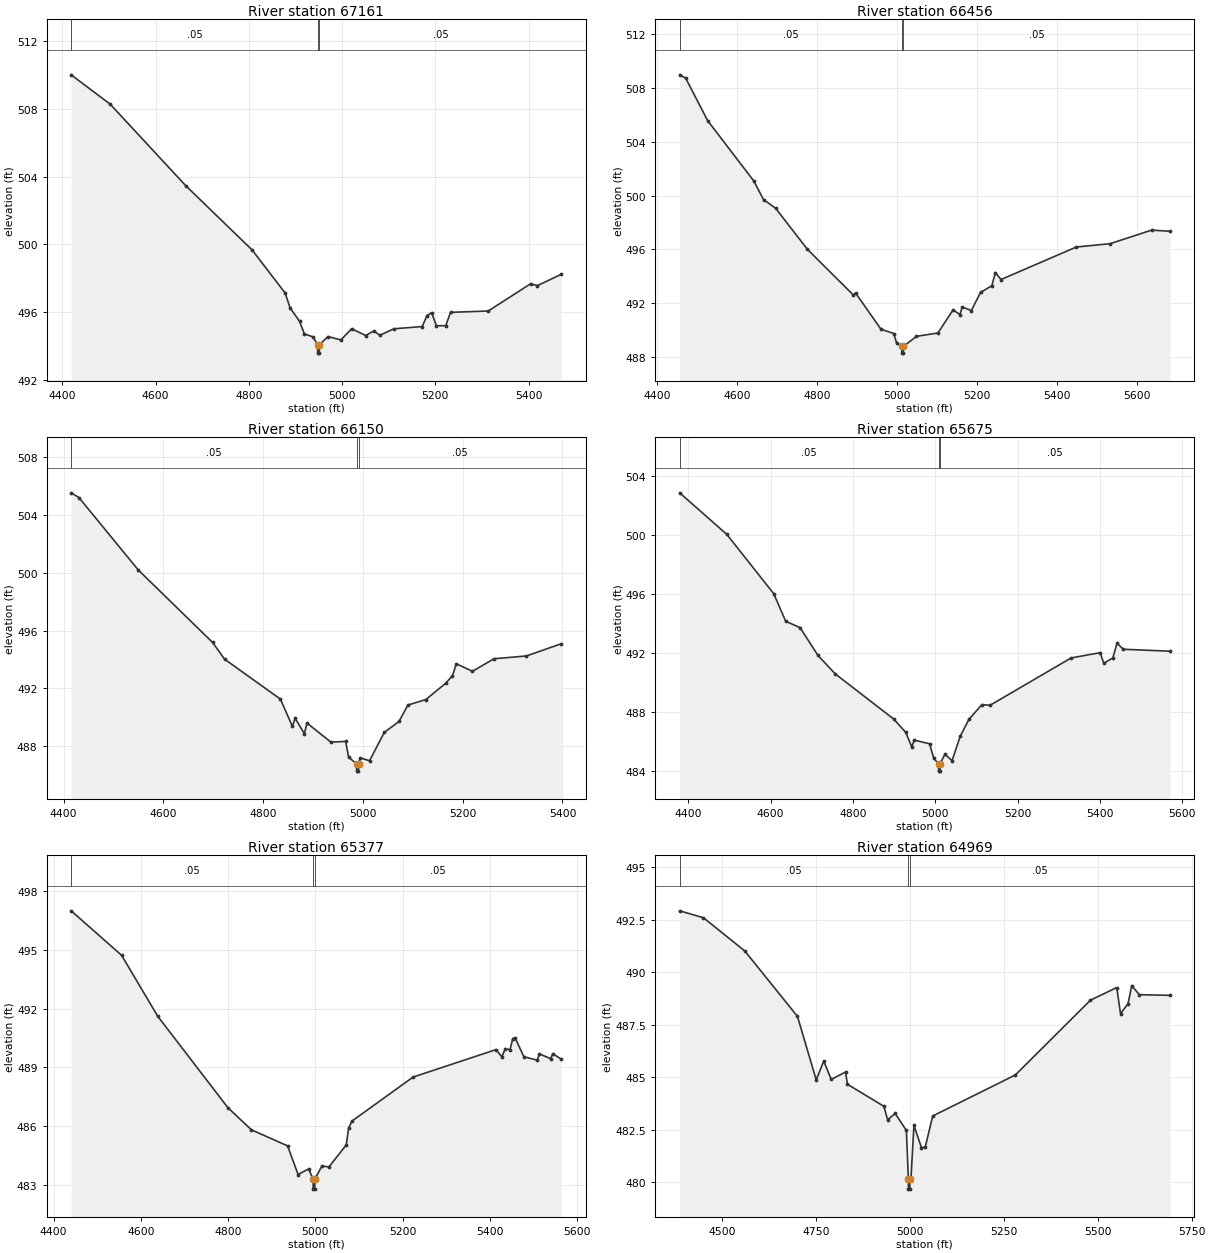
Type RM Length L Ch R = 1 ,67161   ,705,705,705
BEGIN DESCRIPTION:
Allen Creek 78.0
END DESCRIPTION:
XS GIS Cut Line= 3
      2745170.18       6933038.3      2745070.94      6933610.86
      2745003.55      6934076.21
#Sta/Elev= 30
  4418.9  510.02  4502.8  508.28  4665.2  503.45  4807.3  499.66  4877.9  497.12
  4888.5  496.24  4908.8  495.45  4918.9  494.71  4937.6  494.53  4947.4  494.07
  4947.6  493.57  4951.1  493.57  4951.4  494.07  4969.7  494.55  4997.4  494.35
  5020.3  495.01  5050.7  494.61  5067.6  494.88    5081  494.63  5111.3  495.01
  5171.9  495.14    5182  495.79  5192.1  495.96  5202.2  495.19  5222.4  495.19
  5232.5  495.98  5313.4  496.06  5404.3  497.67  5418.9  497.56  5470.2  498.23
#Mann= 3 ,-1 , 0
  4418.9     .05       0  4947.4     .04       0  4951.4     .05       0
Bank Sta=4947.4,4951.4
XS Rating Curve= 0 ,0
Exp/Cntr=0.3,0.1

Type RM Length L Ch R = 1 ,66456   ,306,306,306
BEGIN DESCRIPTION:
Allen Creek 77.0
END DESCRIPTION:
XS GIS Cut Line= 3
      2744675.99      6933111.04      2744482.19      6933618.81
      2744770.81      6934236.07
#Sta/Elev= 30
  4456.5  508.99  4471.5  508.74  4526.3  505.58  4641.3   501.1    4666   499.7
  4696.1  499.06  4775.6     496  4890.6  492.59  4895.9  492.75  4959.5  490.05
  4991.6  489.73  4998.5  489.02  5011.5  488.77  5011.7  488.27  5015.2  488.27
  5015.5  488.77  5048.2  489.52  5101.8  489.77  5139.6  491.49  5156.9  491.14
  5162.5  491.71  5185.3  491.44  5208.2  492.79  5236.5  493.29  5245.3  494.27
  5259.4  493.75  5447.6  496.17  5532.3  496.42  5635.9  497.43  5681.4  497.34
#Mann= 3 ,-1 , 0
  4456.5     .05       0  5011.5     .04       0  5015.5     .05       0
Bank Sta=5011.5,5015.5
XS Rating Curve= 0 ,0
Exp/Cntr=0.3,0.1

Type RM Length L Ch R = 1 ,66150   ,475,475,475
BEGIN DESCRIPTION:
Allen Creek 76.0
END DESCRIPTION:
XS GIS Cut Line= 3
      2744400.03      6933066.55        2744176.        6933611.
      2744323.61      6933976.15
#Sta/Elev= 30
  4415.1  505.55  4430.7  505.22  4549.7   500.2  4698.6  495.18  4722.6  494.02
  4834.6  491.25  4858.6  489.36    4864  489.93  4882.5  488.86  4887.9  489.59
  4935.8  488.27  4965.2  488.32  4971.4  487.23  4987.2  486.76  4987.4  486.26
  4990.9  486.26  4991.2  486.76  4994.6  487.18  5013.2  486.98  5042.7  488.94
  5072.2   489.7  5090.1  490.84  5125.9  491.22  5165.6  492.34  5179.5  492.88
  5187.2   493.7  5219.6  493.18  5262.7  494.05  5327.4  494.24  5397.7  495.09
#Mann= 3 ,-1 , 0
  4415.1     .05       0  4987.2     .04       0  4991.2     .05       0
Bank Sta=4987.2,4991.2
XS Rating Curve= 0 ,0
Exp/Cntr=0.3,0.1

Type RM Length L Ch R = 1 ,65675   ,298,298,298
BEGIN DESCRIPTION:
Allen Creek 75.0
END DESCRIPTION:
XS GIS Cut Line= 3
      2744160.48      6932924.15        2743776.        6933411.
        2743907.      6933965.88
#Sta/Elev= 30
  4379.3  502.84  4493.9  500.02  4607.7  496.01  4636.6  494.15  4671.8  493.71
  4715.1  491.83  4757.6  490.57  4899.4  487.52  4928.3  486.62  4942.8  485.65
  4949.1   486.1  4986.1  485.85  4996.5  484.86  5007.9   484.5  5008.2     484
  5011.7     484  5011.9   484.5  5023.4  485.14  5040.8  484.71  5060.6  486.36
  5081.9  487.51  5113.1   488.5  5133.2  488.46  5329.8  491.66  5400.4  492.02
  5409.3   491.3  5431.2  491.66  5441.5  492.66  5456.8  492.25  5569.8  492.12
#Mann= 3 ,-1 , 0
  4379.3     .05       0  5007.9     .04       0  5011.9     .05       0
Bank Sta=5007.9,5011.9
XS Rating Curve= 0 ,0
Exp/Cntr=0.3,0.1

Type RM Length L Ch R = 1 ,65377   ,408,408,408
BEGIN DESCRIPTION:
Allen Creek 74.0
END DESCRIPTION:
XS GIS Cut Line= 3
      2743716.01      6932892.94      2743505.83      6933411.46
      2743698.67      6933941.58
#Sta/Elev= 30
  4440.5  496.97    4556  494.71  4639.1   491.6  4799.9  486.95  4853.5  485.83
  4936.6  485.01  4960.7  483.55  4984.8  483.84  4995.1  483.31  4995.3  482.81
  4998.8  482.81  4999.1  483.31  5015.3  483.99  5031.4  483.94  5071.1  485.06
  5076.5  485.92  5084.6  486.28  5224.1  488.51  5414.5  489.91  5427.6  489.54
  5435.8  489.96  5446.4   489.9  5452.8  490.47  5458.1  490.51  5478.1  489.55
  5508.7  489.37    5514  489.69  5539.3  489.45  5544.6   489.7  5564.1  489.42
#Mann= 3 ,-1 , 0
  4440.5     .05       0  4995.1     .04       0  4999.1     .05       0
Bank Sta=4995.1,4999.1
XS Rating Curve= 0 ,0
Exp/Cntr=0.3,0.1

Type RM Length L Ch R = 1 ,64969   ,123,123,123
BEGIN DESCRIPTION:
Allen Creek 73.0
END DESCRIPTION:
XS GIS Cut Line= 3
      2743232.94      6932637.74      2743216.48      6933250.42
       2743208.2      6933942.37
#Sta/Elev= 30
  4387.1  492.92  4450.4  492.59  4560.4  491.01  4700.5   487.9  4750.5  484.88
  4770.5  485.77  4790.5   484.9  4828.6  485.25  4833.6  484.67  4930.6  483.62
  4940.6  482.98  4960.6  483.28  4990.6  482.47  4995.8  480.18    4996  479.68
  4999.5  479.68  4999.8  480.18  5002.8  480.18  5010.6  482.71  5030.6  481.66
  5040.6  481.67  5060.6  483.16  5280.6  485.11  5480.6  488.67  5550.6  489.27
  5560.6  488.03  5580.6   488.5  5590.6  489.36  5610.6  488.93    5692   488.9
#Mann= 3 ,-1 , 0
  4387.1     .05       0  4995.8     .05       0  4999.8     .05       0
Bank Sta=4995.8,4999.8
XS Rating Curve= 0 ,0
Exp/Cntr=0.3,0.1

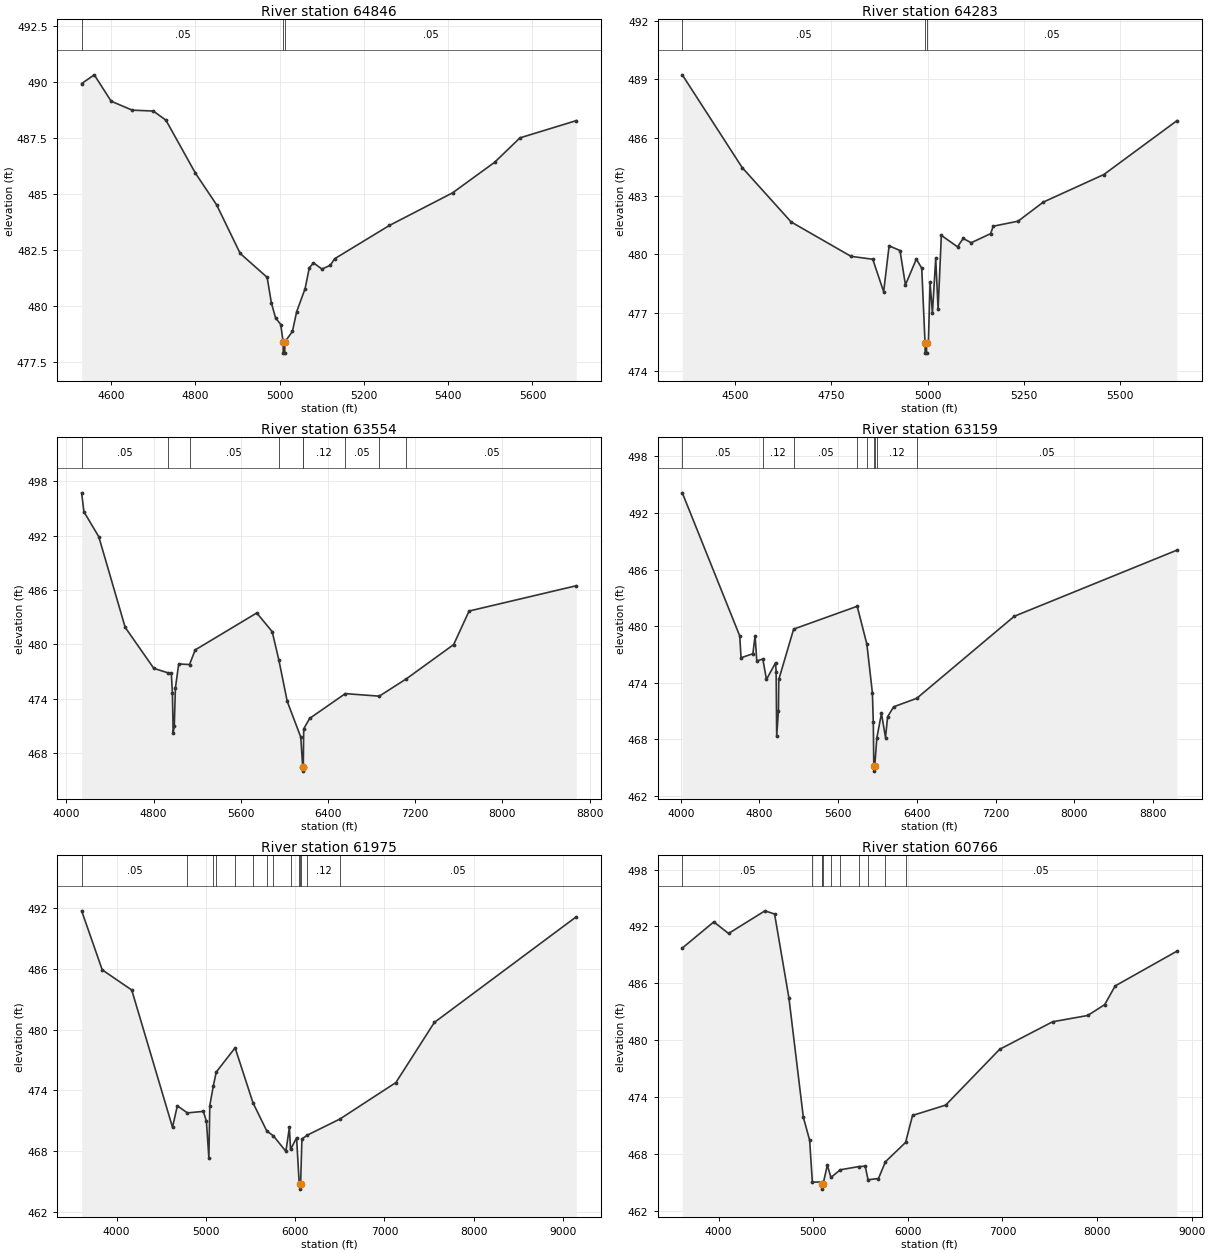
Type RM Length L Ch R = 1 ,64846   ,563,563,563
BEGIN DESCRIPTION:
Mapping XS b9161489
END DESCRIPTION:
XS GIS Cut Line= 3
      2743124.87      6932741.04      2743107.51      6933213.24
      2743093.62      6933914.58
#Sta/Elev= 30
    4530  489.94    4560  490.33    4600  489.15    4650  488.75  4700.1  488.71
  4730.1   488.3  4800.1  485.93  4850.2  484.52  4906.3  482.34  4970.3  481.27
  4980.3  480.13  4990.3  479.46  5002.5  479.16  5008.3  478.38  5008.5  477.88
    5012  477.88  5012.3  478.38  5030.3  478.85  5040.3  479.73  5060.3  480.76
  5070.3  481.69  5080.3  481.92  5100.3  481.64  5120.3  481.81  5130.3   482.1
  5260.3  483.59  5410.4  485.05  5510.4  486.42  5570.4  487.51    5704  488.28
#Mann= 3 ,-1 , 0
    4530     .05       0  5008.3     .05       0  5012.3     .05       0
Bank Sta=5008.3,5012.3
XS Rating Curve= 0 ,0
Exp/Cntr=0.3,0.1

Type RM Length L Ch R = 1 ,64283   ,729,729,729
BEGIN DESCRIPTION:
Allen Creek 72.0
END DESCRIPTION:
XS GIS Cut Line= 3
      2743025.98      6932761.02        2742576.        6933211.
      2742951.06      6933740.45
#Sta/Elev= 30
  4362.6  489.23  4518.1  484.46  4645.4  481.66    4801  479.89  4857.5  479.74
  4885.8  478.07    4900  480.43  4928.3  480.19  4942.4  478.42  4970.7  479.75
  4984.8  479.28  4993.4  475.41  4993.7  474.91  4997.2  474.91  4997.4  475.41
    5002  475.41  5006.4  478.55  5012.5  476.97  5021.1  479.78  5027.3  477.17
  5035.7  480.97  5077.7  480.38  5092.5  480.81  5113.4  480.59  5163.9  481.06
  5170.5  481.44  5235.2   481.7  5300.5  482.68    5458   484.1  5647.8  486.87
#Mann= 3 ,-1 , 0
  4362.6     .05       0  4993.4     .05       0  4997.4     .05       0
Bank Sta=4993.4,4997.4
XS Rating Curve= 0 ,0
Exp/Cntr=0.3,0.1

Type RM Length L Ch R = 1 ,63554   ,395,395,395
BEGIN DESCRIPTION:
Allen Creek 71.0
END DESCRIPTION:
XS GIS Cut Line= 3
      2742382.68      6931981.48      2742129.65      6932761.52
      2742621.79      6936445.74
#Sta/Elev= 30
  4140.7  496.72  4161.2  494.64  4297.9  491.88    4540  481.88  4802.5  477.36
  4935.5  476.85    4963  476.82  4973.2  474.69  4980.4  470.22  4990.5  470.97
  5000.6  475.18  5030.9  477.84  5130.5  477.78  5182.2  479.39  5747.2  483.47
  5888.4  481.41  5948.8  478.33  6026.5  473.72  6150.7  469.77  6168.1  466.52
  6168.9  466.02  6173.7  466.52  6177.7  470.68  6231.4  471.83  6559.4  474.57
  6870.9  474.29  7120.2  476.21  7553.1  479.98  7694.6  483.68  8677.7  486.47
#Mann= 9 ,-1 , 0
  4140.7     .05       0  4935.5     .12       0  5130.5     .05       0
  5948.8     .12       0  6168.1     .07       0  6173.7     .12       0
  6559.4     .05       0  6870.9     .12       0  7120.2     .05       0
Bank Sta=6168.1,6173.7
XS Rating Curve= 0 ,0
Exp/Cntr=0.3,0.1

Type RM Length L Ch R = 1 ,63159   ,1184,1184,1184
BEGIN DESCRIPTION:
Allen Creek 70.0
END DESCRIPTION:
XS GIS Cut Line= 4
        2742201.      6931836.01      2741799.78      6932732.77
      2741792.05      6933616.82      2742550.99      6936685.97
#Sta/Elev= 30
  4015.4  494.14  4599.5  478.96  4612.5  476.65    4733  477.08  4755.2  478.99
  4772.9  476.31  4833.9  476.52  4871.2  474.35    4963  476.11  4969.4  475.19
  4974.9  468.33  4992.6  470.98  4996.3  474.35  5147.3  479.69  5793.4  482.11
  5891.6   478.1    5948  472.92    5957  469.82  5962.2  465.18  5965.8  465.13
  5966.7  464.63  5971.5  465.13    5993  468.14  6039.9  470.75  6081.3  468.19
  6102.5   470.4  6164.2  471.45  6398.7  472.35  7390.2  481.05  9043.5  488.06
#Mann= 9 ,-1 , 0
  4015.4     .05       0  4833.9     .12       0  5147.3     .05       0
  5793.4     .12       0  5891.6      .1       0  5965.8     .05       0
  5971.5      .1       0    5993     .12       0  6398.7     .05       0
Bank Sta=5965.8,5971.5
XS Rating Curve= 0 ,0
Exp/Cntr=0.3,0.1

Type RM Length L Ch R = 1 ,61975   ,1209,1209,1209
BEGIN DESCRIPTION:
Allen Creek 68.0
END DESCRIPTION:
XS GIS Cut Line= 5
      2740944.65      6931400.58      2740950.34       6931928.9
       2741037.3      6932415.02        2741176.        6932761.
      2740919.26       6936897.3
#Sta/Elev= 30
  3608.4  491.71  3838.8  485.89  4169.4   483.9    4626  470.36  4680.1  472.48
  4792.7  471.78    4971  471.93  5005.8  470.95  5033.4  467.31  5043.4   472.5
  5083.6  474.47  5115.9  475.81  5327.1   478.2  5527.1  472.78  5682.2  469.99
  5756.3  469.51  5895.6  467.99  5935.1  470.34  5947.8  468.17  6015.3  469.32
  6044.8  464.86  6052.3  464.76  6053.5  464.26  6060.6  464.76  6075.4  469.21
  6136.5  469.59  6499.7  471.17  7127.4  474.77  7558.2   480.7  9147.6  491.12
#Mann= 14 ,-1 , 0
  3608.4     .05       0  4792.7     .12       0  5083.6     .05       0
  5115.9     .12       0  5327.1      .1       0  5527.1     .12       0
  5682.2     .05       0  5756.3      .1       0  5947.8     .12       0
  6044.8     .07       0  6052.3     .05       0  6060.6      .1       0
  6136.5     .12       0  6499.7     .05       0
Bank Sta=6052.3,6060.6
XS Rating Curve= 0 ,0
Exp/Cntr=0.3,0.1

Type RM Length L Ch R = 1 ,60766   ,774,774,774
BEGIN DESCRIPTION:
Allen Creek 66.0
END DESCRIPTION:
XS GIS Cut Line= 3
      2739813.95      6931580.75      2740191.34      6932910.95
      2740285.48       6936753.6
#Sta/Elev= 30
  3617.3  489.71  3950.2  492.47  4106.1  491.25  4490.9  493.64  4592.6   493.3
  4743.8  484.45  4896.1  471.86  4962.9  469.42  4991.7     465    5090  465.01
  5095.8  464.76  5097.1  464.26  5104.3  464.76  5150.1   466.8  5187.9  465.49
  5285.9   466.3  5481.8  466.64  5550.2  466.69  5579.8  465.25  5690.3  465.38
  5763.7  467.15  5976.6  469.19  6050.4  472.04  6400.5  473.13  6970.6  479.02
  7530.8  481.93  7900.9  482.59    8081  483.74    8191  485.71  8843.8  489.38
#Mann= 11 ,-1 , 0
  3617.3     .05       0  4991.7     .12       0    5090     .05       0
  5095.8     .07       0  5104.3     .05       0  5187.9     .12       0
  5285.9     .05       0  5481.8     .12       0  5579.8     .05       0
  5763.7     .12       0  5976.6     .05       0
Bank Sta=5095.8,5104.3
XS Rating Curve= 0 ,0
Exp/Cntr=0.3,0.1

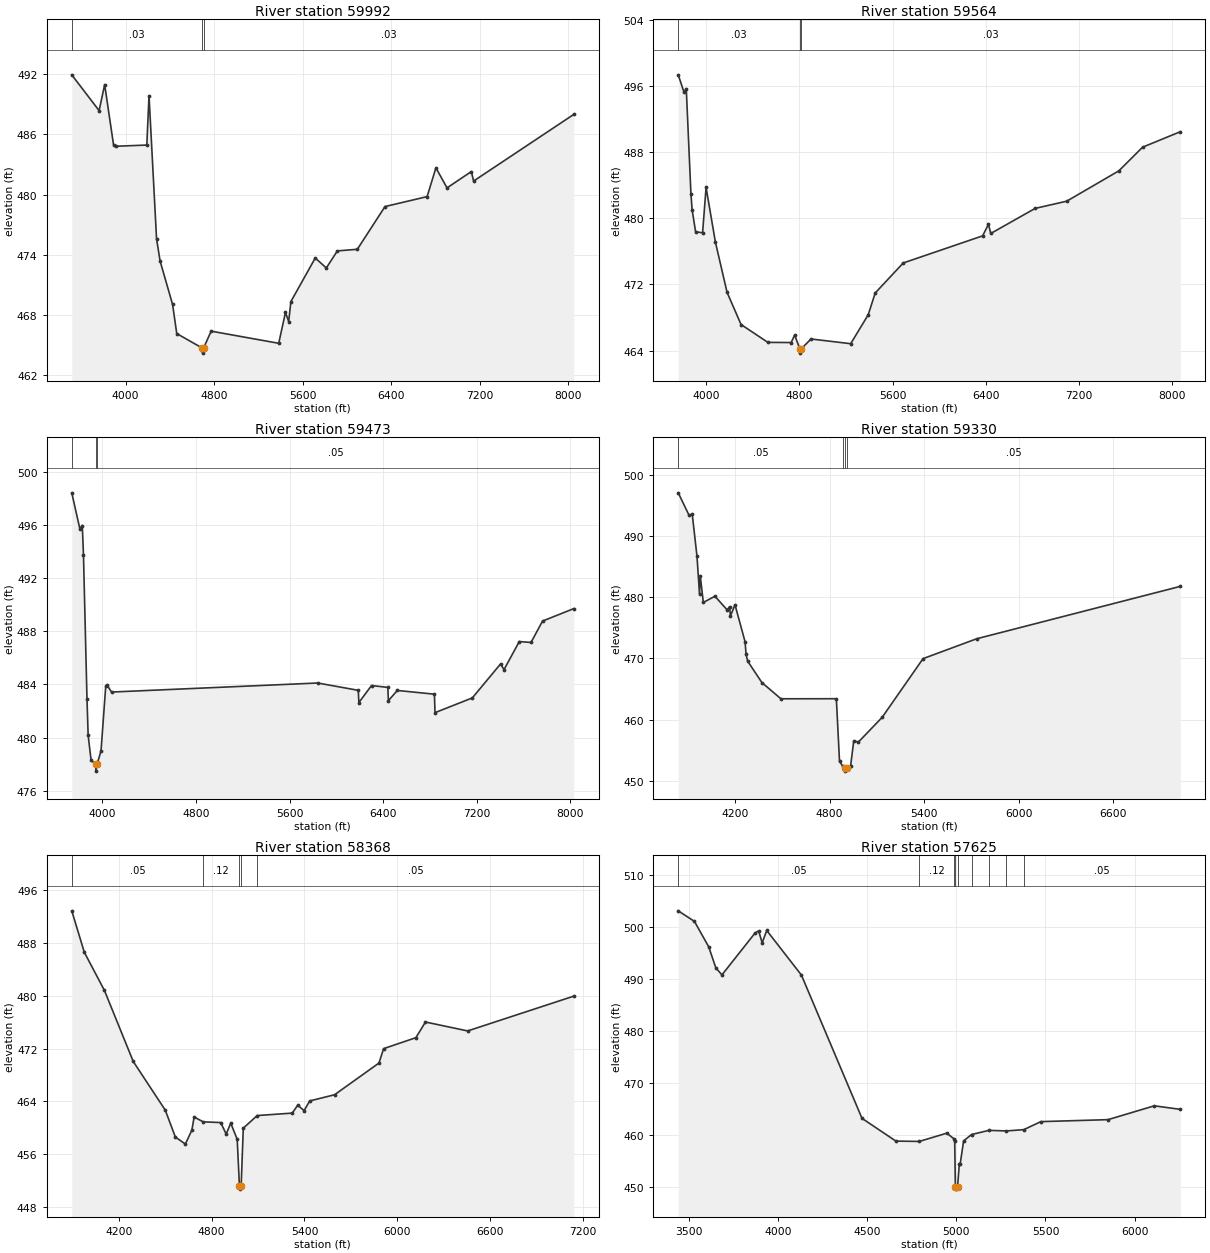
Type RM Length L Ch R = 1 ,59992   ,428,428,428
BEGIN DESCRIPTION:
Allen Creek 65.0
END DESCRIPTION:
XS GIS Cut Line= 3
      2739816.26      6931944.48      2739709.45      6933427.94
      2739581.71      6936476.47
#Sta/Elev= 30
  3512.7  491.93  3759.9  488.36    3810  490.96  3890.2  484.96  3910.2  484.81
    4191  484.93    4211  489.85  4279.2  475.57  4311.3  473.36    4424  469.04
  4461.7  466.14  4693.1  464.69  4694.6  464.19  4704.1  464.69  4772.5  466.38
  5383.4  465.17  5444.5  468.25  5473.5  467.34  5493.5  469.33  5713.7  473.67
  5813.8  472.68  5913.6  474.38    6094  474.54  6344.2   478.8  6724.6  479.79
  6804.6  482.66  6904.7  480.66  7124.9  482.29  7144.9  481.34  8051.2  487.99
#Mann= 3 ,-1 , 0
  3512.7     .03       0  4693.1     .03       0  4704.1     .03       0
Bank Sta=4693.1,4704.1
XS Rating Curve= 0 ,0
Exp/Cntr=0.3,0.1

Type RM Length L Ch R = 1 ,59564   ,91,91,91
BEGIN DESCRIPTION:
Allen Creek 64.0
END DESCRIPTION:
XS GIS Cut Line= 3
      2739323.58      6932272.15      2739309.68      6933499.07
      2739130.42      6936574.05
#Sta/Elev= 30
    3761  497.34  3809.9  495.26  3829.9  495.66  3869.9  482.96  3879.9  481.04
  3909.9  478.37  3969.9  478.24  3999.9  483.72  4079.9  477.11  4179.9  471.04
  4299.9  467.15  4529.9  464.99  4729.9  464.97  4759.9  465.88  4804.3  464.19
  4805.9  463.69  4815.5  464.19  4899.9   465.4  5240.4  464.83  5390.6  468.32
  5450.7  470.96  5691.1  474.59  6372.3  477.87  6422.4  479.27  6442.4  478.16
    6823  481.19  7093.5  482.06    7541  485.73  7744.6  488.59  8068.2  490.46
#Mann= 3 ,-1 , 0
    3761     .03       0  4804.3     .03       0  4815.5     .03       0
Bank Sta=4804.3,4815.5
XS Rating Curve= 0 ,0
Exp/Cntr=0.3,0.1

Type RM Length L Ch R = 1 ,59473   ,143,143,143
BEGIN DESCRIPTION:
Mapping XS c9bb5357
END DESCRIPTION:
XS GIS Cut Line= 5
      2739268.58      6932251.13      2739247.75      6932704.28
       2739216.5      6933542.82      2739150.22      6935228.16
        2739051.        6936536.
#Sta/Elev= 30
  3738.6  498.41  3808.5  495.67  3828.6  495.95  3838.6  493.74  3868.6  482.93
  3878.6  480.16  3903.7  478.29  3943.1  477.97  3944.6  477.47  3954.3  477.97
  3988.7     479  4028.8  483.84  4038.8  483.96  4078.8  483.42  5840.2   484.1
  6187.3  483.55  6192.3  482.63  6300.5  483.91  6439.7  483.77  6444.7  482.77
  6520.7  483.54    6838  483.26    6843  481.87  7162.1  482.98  7402.8  485.53
  7432.9  485.11  7563.3  487.22  7663.5  487.15    7762  488.76  8029.6   489.7
#Mann= 3 ,-1 , 0
  3738.6     .05       0  3943.1     .05       0  3954.3     .05       0
Bank Sta=3943.1,3954.3
XS Rating Curve= 0 ,0
Exp/Cntr=0.3,0.1

Type RM Length L Ch R = 1 ,59330   ,962,962,962
BEGIN DESCRIPTION:
Mapping XS b86bfb4a
END DESCRIPTION:
XS GIS Cut Line= 3
      2739215.17      6932282.56      2739103.54       6933345.8
      2739090.96      6935464.37
#Sta/Elev= 30
  3838.7   497.1  3907.5  493.42  3927.6  493.62  3957.8   486.7  3973.7  480.53
  3978.7  483.49    3998  479.16  4071.8  480.17  4148.8  477.95  4164.9  478.46
    4170  476.94  4199.1  478.78  4263.1  472.72  4269.5  470.64  4279.6  469.55
    4370  466.04  4490.7  463.39  4842.6   463.4  4862.7  453.14  4884.4  452.32
  4897.3  452.05  4898.8  451.55  4908.5  452.05    4933  452.39    4953  456.49
    4983  456.32    5133  460.34    5393  469.96    5733  473.21  7026.4  481.79
#Mann= 4 ,-1 , 0
  3838.7     .05       0  4884.4     .12       0  4897.3     .04       0
  4908.5     .05       0
Bank Sta=4897.3,4908.5
XS Rating Curve= 0 ,0
Exp/Cntr=0.3,0.1

Type RM Length L Ch R = 1 ,58368   ,743,743,743
BEGIN DESCRIPTION:
Mapping XS b7523157
END DESCRIPTION:
XS GIS Cut Line= 4
      2739105.45        6932316.      2738464.85      6933201.37
      2738912.77      6934310.75      2738907.57      6935267.53
#Sta/Elev= 30
  3895.7  492.83  3976.8  486.56  4106.8  480.79  4293.2  470.04  4500.4  462.67
  4565.4  458.61  4630.1  457.55  4672.1  459.65  4686.8  461.64  4745.4  460.91
  4858.5   460.8  4894.1  459.06  4923.5  460.71  4965.3  458.27  4979.6  451.23
  4981.2  450.73  4990.8  451.23  5004.6  459.95  5094.5  461.86  5321.3  462.23
  5356.2  463.42  5397.9  462.61    5434  464.07    5595  465.01  5882.1  469.81
  5911.6  471.98  6120.5  473.64  6182.5  476.01  6455.2  474.66  7141.7  479.93
#Mann= 5 ,-1 , 0
  3895.7     .05       0  4745.4     .12       0  4979.6     .07       0
  4990.8     .12       0  5094.5     .05       0
Bank Sta=4979.6,4990.8
XS Rating Curve= 0 ,0
Exp/Cntr=0.3,0.1

Type RM Length L Ch R = 1 ,57625   ,163,163,163
BEGIN DESCRIPTION:
Mapping XS 8e2f8fee
END DESCRIPTION:
XS GIS Cut Line= 3
      2738110.68      6931500.02      2738048.18      6933078.11
      2738001.34       6934316.8
#Sta/Elev= 30
  3438.1  503.02  3529.1  500.99  3609.2   496.1  3649.2  492.05  3683.5   490.7
  3869.4  498.75  3889.4  499.16  3909.4  496.87    3935  499.24  4129.6  490.67
  4469.9  463.11    4660  458.74  4791.3  458.67  4945.7  460.26    4987  459.16
  4990.3  458.74  4994.1     450  4995.8   449.5  5006.5     450  5016.4   454.4
  5021.4   454.4  5040.3  458.78  5084.9     460  5182.7   460.8  5280.6  460.69
  5378.5  460.94  5473.9  462.48  5850.9  462.86  6111.1  465.52    6257  464.84
#Mann= 9 ,-1 , 0
  3438.1     .05       0  4791.3     .12       0    4987      .1       0
  4994.1     .07       0  5006.5      .1       0  5084.9     .12       0
  5182.7     .05       0  5280.6      .1       0  5378.5     .05       0
Bank Sta=4994.1,5006.5
XS Rating Curve= 0 ,0
Exp/Cntr=0.3,0.1

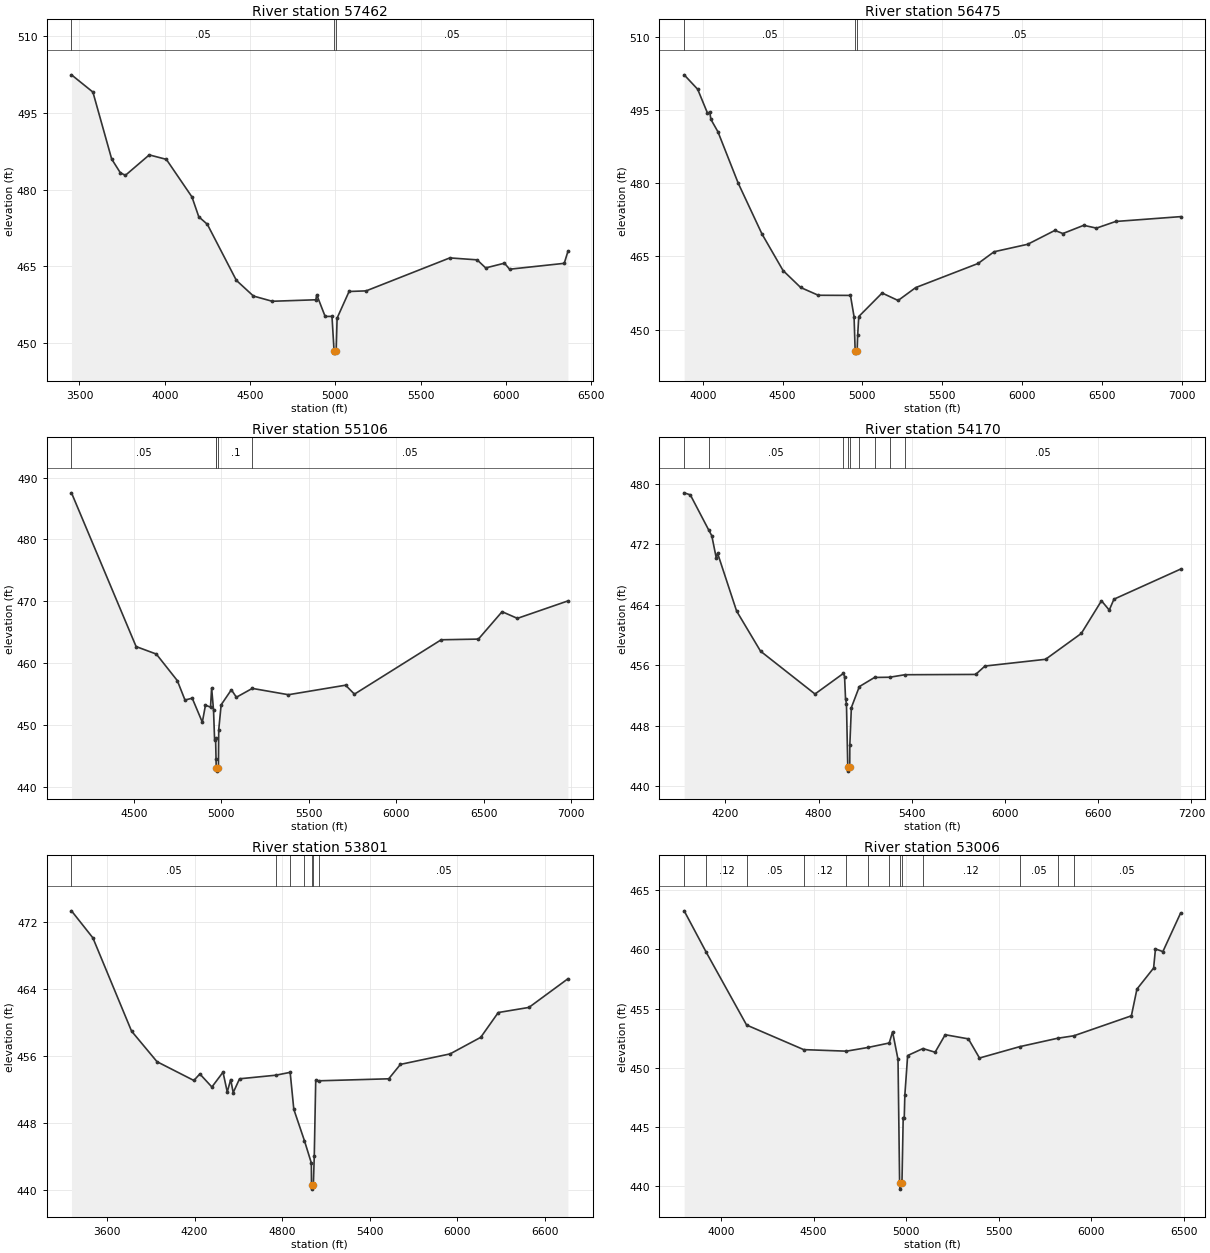
Type RM Length L Ch R = 1 ,57462   ,987,987,987
BEGIN DESCRIPTION:
Mapping XS 383228ac
END DESCRIPTION:
XS GIS Cut Line= 3
      2737944.02      6931515.62      2737886.72      6933062.48
      2737837.24      6934422.56
#Sta/Elev= 30
  3453.5  502.41    3579  499.04    3689  485.96  3739.1  483.31  3769.1  482.77
  3909.2  486.77  4009.3   485.9  4159.4  478.56  4199.4  474.68  4249.4  473.22
  4419.5  462.27  4519.6   459.2  4629.7  458.18  4885.4  458.47  4890.4  459.46
  4939.9  455.21  4979.9  455.23    4992  448.55  4993.7  448.05  5004.4  448.55
  5009.9  454.89    5080  460.09  5180.1  460.21  5670.4  466.65  5830.5  466.27
  5880.5  464.69  5990.6  465.62  6020.6  464.44  6340.8  465.59  6362.4  467.92
#Mann= 3 ,-1 , 0
  3453.5     .05       0    4992     .04       0  5004.4     .05       0
Bank Sta=4992,5004.4
XS Rating Curve= 0 ,0
Exp/Cntr=0.3,0.1

Type RM Length L Ch R = 1 ,56475   ,1369,1369,1369
BEGIN DESCRIPTION:
Mapping XS 5186036a
END DESCRIPTION:
XS GIS Cut Line= 3
      2737658.99      6931538.43      2737143.38      6932522.77
      2737018.43      6934516.75
#Sta/Elev= 30
  3883.5   502.2  3968.2  499.24  4028.8  494.42  4044.4   494.5  4050.8  493.09
    4095  490.54  4221.7  480.04  4370.5  469.63  4502.9  462.12  4613.2  458.65
  4723.5  457.06    4925  457.03  4947.6  452.65  4954.4  445.71  4956.1  445.21
  4966.8  445.71  4970.1  448.83    4977   452.7  5123.2  457.52  5223.4  455.99
  5333.6  458.63  5724.4  463.57  5824.6  465.97    6035   467.5  6205.3  470.34
  6255.4   469.7  6385.7  471.38  6465.8  470.81  6586.1  472.17  6992.6  473.16
#Mann= 3 ,-1 , 0
  3883.5     .05       0  4954.4    .035       0  4966.8     .05       0
Bank Sta=4954.4,4966.8
XS Rating Curve= 0 ,0
Exp/Cntr=0.3,0.1

Type RM Length L Ch R = 1 ,55106   ,936,936,936
BEGIN DESCRIPTION:
Mapping XS f5b26245
END DESCRIPTION:
XS GIS Cut Line= 4
       2737211.1      6931679.02        2736409.      6932027.98
      2736117.34      6932371.73      2736362.09      6933866.29
#Sta/Elev= 30
  4142.8  487.54  4512.5  462.69  4628.2  461.48  4748.2  457.19  4792.1  454.05
  4833.5  454.35  4891.3  450.47  4909.3  453.22  4938.2   452.9  4944.5  455.99
  4955.4  452.44  4961.6  447.57  4967.1  447.92  4969.8  444.47  4970.9  443.06
  4972.7  442.56  4983.4  443.06  4985.1  449.22    4999  453.28  5057.5  455.71
  5086.1   454.5  5177.3  455.93  5383.8  454.91  5710.8  456.45  5761.5     455
    6258  463.79  6470.8   463.9  6606.2  468.33  6693.7  467.25  6982.8  470.07
#Mann= 5 ,-1 , 0
  4142.8     .05       0  4969.8      .1       0  4970.9     .07       0
  4983.4      .1       0  5177.3     .05       0
Bank Sta=4970.9,4983.4
XS Rating Curve= 0 ,0
Exp/Cntr=0.3,0.1

Type RM Length L Ch R = 1 ,54170   ,369,369,369
BEGIN DESCRIPTION:
Mapping XS 48367a23
END DESCRIPTION:
XS GIS Cut Line= 3
      2736362.12      6930743.27      2735820.46      6931654.71
       2735778.8      6933790.16
#Sta/Elev= 30
  3934.3  478.79    3974  478.52  4091.9  473.89  4112.3  473.11    4141  470.16
  4149.3  470.81    4272  463.15  4425.9  457.85  4776.6  452.18  4959.8  454.91
    4967  454.48  4973.3  451.54  4979.2  450.92  4987.7  442.48  4989.5  441.98
  5000.3  442.48  5000.8  445.37  5010.8  450.39  5062.1  453.16    5160  454.37
  5257.8   454.4  5355.7  454.73    5811  454.77    5871  455.88  6261.1  456.77
  6491.1  460.19  6621.1  464.51  6671.1  463.28  6701.2  464.72  7130.4   468.7
#Mann= 9 ,-1 , 0
  3934.3     .12       0  4091.9     .05       0  4959.8     .12       0
  4987.7     .07       0  5000.3     .12       0  5062.1      .1       0
    5160     .05       0  5257.8      .1       0  5355.7     .05       0
Bank Sta=4987.7,5000.3
XS Rating Curve= 0 ,0
Exp/Cntr=0.3,0.1

Type RM Length L Ch R = 1 ,53801   ,795,795,795
BEGIN DESCRIPTION:
Mapping XS 5129a22d
END DESCRIPTION:
XS GIS Cut Line= 4
      2736019.24      6930312.72      2735559.18      6931389.09
       2735550.5      6931870.86      2735570.44      6933618.03
#Sta/Elev= 30
  3356.8  473.33  3503.4   470.1  3768.2  458.97  3942.6  455.32  4194.9  453.08
  4235.8  453.86  4318.3   452.3  4394.5  454.07  4423.5  451.71  4447.1  453.19
  4464.2  451.63  4507.7  453.28  4756.5  453.71  4854.3  454.05  4879.3  449.64
  4952.1  445.89  4999.4  443.23  5000.5  440.61  5002.2  440.11  5013.1  440.61
  5019.4  444.02  5029.4   453.1    5050  453.04  5529.4  453.28  5609.4     455
  5949.4  456.25  6159.4  458.23  6279.4  461.19  6489.5   461.8  6756.5  465.22
#Mann= 7 ,-1 , 0
  3356.8     .05       0  4756.5     .12       0  4854.3      .1       0
  4952.1     .12       0  5000.5     .07       0  5013.1     .12       0
    5050     .05       0
Bank Sta=5000.5,5013.1
XS Rating Curve= 0 ,0
Exp/Cntr=0.3,0.1

Type RM Length L Ch R = 1 ,53006   ,786,786,786
BEGIN DESCRIPTION:
Mapping XS f1b1acfe
END DESCRIPTION:
XS GIS Cut Line= 4
      2735718.74      6930292.03      2735063.34      6931281.62
      2734959.18      6931550.72      2734907.12       6932756.7
#Sta/Elev= 30
  3800.4  463.27  3919.9  459.76  4137.8  453.61  4446.3  451.53  4677.5   451.4
    4793  451.71  4908.6  452.09  4926.6  453.04    4956   450.7  4964.7  440.23
  4966.5  439.73  4977.3  440.23    4984  445.77  4989.7  445.77  4992.9  447.68
  5008.1  451.03  5090.6  451.62  5156.5  451.31    5211  452.79  5336.2  452.44
  5396.3  450.82  5613.6  451.78  5818.1  452.49  5906.1   452.7  6217.1  454.39
  6247.1  456.65  6337.2  458.43  6347.2  460.05  6387.2  459.82    6483  463.08
#Mann= 13 ,-1 , 0
  3800.4     .05       0  3919.9     .12       0  4137.8     .05       0
  4446.3     .12       0  4677.5     .05       0    4793     .12       0
  4908.6      .1       0  4964.7     .07       0  4977.3      .1       0
  5090.6     .12       0  5613.6     .05       0  5818.1     .12       0
  5906.1     .05       0
Bank Sta=4964.7,4977.3
XS Rating Curve= 0 ,0
Exp/Cntr=0.3,0.1

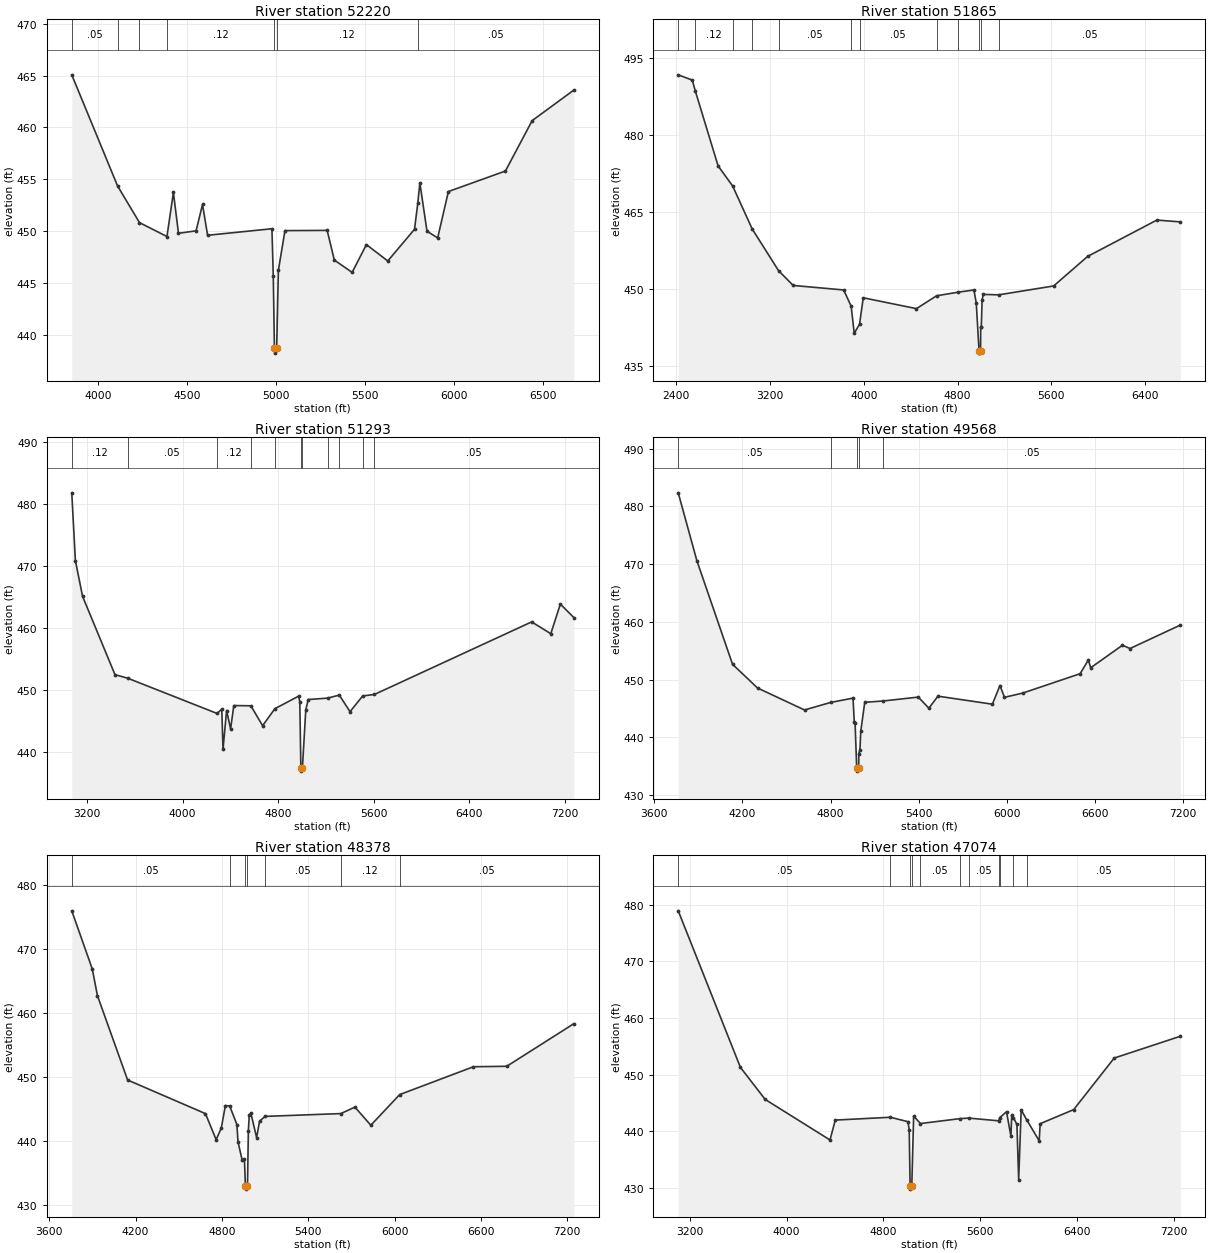
Type RM Length L Ch R = 1 ,52220   ,355,355,355
BEGIN DESCRIPTION:
Mapping XS d98864f0
END DESCRIPTION:
XS GIS Cut Line= 4
      2735183.13      6930103.68      2734433.14      6930973.46
      2734370.64      6931233.88      2734339.39      6932634.94
#Sta/Elev= 30
  3854.2  465.07  4111.2  454.35  4234.2  450.81  4388.4  449.47  4424.5  453.72
  4453.1  449.78  4551.8  450.02    4588  452.56  4616.5  449.59  4977.5  450.22
  4985.1  445.67  4991.5  438.72  4993.2  438.22  5004.1  438.72  5013.7   446.2
  5050.6  450.04  5287.6  450.06  5327.6   447.2  5427.7  446.01  5507.7  448.69
  5627.7  447.11  5777.7  450.17    5796  452.67  5807.7  454.65  5847.8  449.98
  5907.8  449.34  5967.8  453.81  6287.9  455.79  6437.9  460.65  6671.9   463.6
#Mann= 7 ,-1 , 0
  3854.2     .05       0  4111.2     .12       0  4234.2     .05       0
  4388.4     .12       0  4991.5     .07       0  5004.1     .12       0
    5796     .05       0
Bank Sta=4991.5,5004.1
XS Rating Curve= 0 ,0
Exp/Cntr=0.3,0.1

Type RM Length L Ch R = 1 ,51865   ,572,572,572
BEGIN DESCRIPTION:
Allen Creek 50.0
END DESCRIPTION:
XS GIS Cut Line= 3
      2734214.39      6928381.44      2734110.81      6930961.17
      2734115.43      6932660.96
#Sta/Elev= 30
  2418.2  491.65  2537.9  490.62  2564.5  488.46    2758  473.95  2882.4  470.03
  3048.7  461.69  3273.8  453.57  3398.5   450.7  3828.9  449.82    3893  446.67
    3919   441.4  3964.1  443.15  3996.1   448.3  4449.4  446.19  4621.4  448.69
  4799.8  449.37  4939.8  449.82  4959.8  447.27  4983.4  438.04  4985.2  437.54
  4996.2  438.04  4997.6  442.56  5002.4  442.56  5009.8  447.94  5019.8  448.96
  5150.3  448.87  5619.8   450.6  5909.8  456.35  6499.8  463.41  6699.8  463.06
#Mann= 12 ,-1 , 0
  2418.2     .05       0  2564.5     .12       0  2882.4     .05       0
  3048.7     .12       0  3273.8     .05       0    3893     .12       0
  3964.1     .05       0  4621.4     .12       0  4799.8      .1       0
  4983.4     .07       0  4996.2      .1       0  5150.3     .05       0
Bank Sta=4983.4,4996.2
XS Rating Curve= 0 ,0
Exp/Cntr=0.3,0.1

Type RM Length L Ch R = 1 ,51293   ,1725,1725,1725
BEGIN DESCRIPTION:
Allen Creek 49.0
END DESCRIPTION:
XS GIS Cut Line= 3
        2733976.      6928660.97      2733794.85      6930576.22
      2733835.65      6932853.96
#Sta/Elev= 30
  3072.7  481.79  3102.9  470.86  3163.1  465.07  3434.3  452.43  3540.2  451.86
  4287.9  446.17  4328.3  446.84  4338.4  440.37  4368.5  446.64  4401.9  443.67
  4428.8  447.44  4571.3   447.4  4669.8  444.19  4772.6  446.93  4971.2  448.96
  4981.2  448.06    4990  437.35  4991.8  436.85  5002.8  437.35  5031.3  446.76
  5051.3  448.41  5213.6  448.64  5311.6  449.13  5401.3  446.45  5507.4  448.99
  5605.4  449.23  6921.6  460.95  7081.6  459.04  7161.6  463.82  7274.6  461.65
#Mann= 11 ,-1 , 0
  3072.7     .12       0  3540.2     .05       0  4287.9     .12       0
  4571.3     .05       0  4772.6     .12       0    4990     .07       0
  5002.8     .12       0  5213.6      .1       0  5311.6     .05       0
  5507.4      .1       0  5605.4     .05       0
Bank Sta=4990,5002.8
XS Rating Curve= 0 ,0
Exp/Cntr=0.3,0.1

Type RM Length L Ch R = 1 ,49568   ,1190,1190,1190
BEGIN DESCRIPTION:
Allen Creek 48.0
END DESCRIPTION:
XS GIS Cut Line= 3
      2733763.52      6928463.88      2733339.05      6929625.13
      2732822.52      6931743.46
#Sta/Elev= 30
  3763.6  482.36  3890.5   470.6  4133.2  452.67  4303.5  448.56    4623  444.76
  4801.5  446.07    4953  446.81  4961.8  442.63  4967.1  442.51  4978.2  434.67
  4980.1  434.17  4991.8  434.67  4992.3  437.17    5000  437.84    5006  441.12
  5032.9  446.09  5155.8  446.31  5397.2  446.99  5469.2  445.07    5531  447.15
  5901.5  445.76    5953  448.99  5983.9  446.95  6107.4  447.68  6498.5  451.04
  6554.4  453.41  6570.6  452.07  6786.7  455.97  6838.2   455.4  7180.4  459.46
#Mann= 5 ,-1 , 0
  3763.6     .05       0  4801.5     .12       0  4978.2     .07       0
  4991.8     .12       0  5155.8     .05       0
Bank Sta=4978.2,4991.8
XS Rating Curve= 0 ,0
Exp/Cntr=0.3,0.1

Type RM Length L Ch R = 1 ,48378   ,1304,1304,1304
BEGIN DESCRIPTION:
Mapping XS 704cc8ba
END DESCRIPTION:
XS GIS Cut Line= 3
      2733679.28      6928460.46       2732616.8      6929092.39
      2732394.58      6931335.41
#Sta/Elev= 30
  3756.2  475.95  3898.9  466.87  3934.5  462.72  4144.3  449.55  4685.7   444.3
  4759.8  440.24  4795.5  442.04    4824  445.55    4854   445.5  4903.9   442.6
  4911.9  439.88  4940.9  437.03  4956.5  437.27  4963.2  433.02  4965.2  432.52
  4976.9  433.02  4977.9  433.17  4983.7   441.6    4990  444.06  5001.1  444.38
  5041.3  440.55  5061.3  443.11  5099.5  443.87  5626.6  444.31  5724.6  445.32
  5835.1  442.49  6035.4  447.27  6548.6  451.62  6780.2  451.69  7246.4  458.34
#Mann= 7 ,-1 , 0
  3756.2     .05       0    4854      .1       0  4963.2     .07       0
  4976.9      .1       0  5099.5     .05       0  5626.6     .12       0
  6035.4     .05       0
Bank Sta=4963.2,4976.9
XS Rating Curve= 0 ,0
Exp/Cntr=0.3,0.1

Type RM Length L Ch R = 1 ,47074   ,1886,1886,1886
BEGIN DESCRIPTION:
Allen Creek 45.0
END DESCRIPTION:
XS GIS Cut Line= 3
      2733649.77      6927997.78      2731845.94      6928581.11
      2730441.48      6930344.96
#Sta/Elev= 30
  3104.2   478.9  3618.2  451.26  3822.8   445.6  4358.8  438.44  4402.3  441.95
  4858.3  442.45  5003.1  441.67  5013.5  440.27    5021  430.26    5023  429.76
  5034.8  430.26  5050.3  442.67  5106.3  441.34    5434  442.21  5506.7   442.3
  5754.5  441.82  5761.7  442.38    5818  443.43  5854.4   439.1  5860.7  442.83
  5875.1  442.39    5904  441.18  5918.4  431.45  5939.2  443.77  5984.7  442.01
  6088.2  438.28  6096.2  441.31  6373.3   443.8    6708   452.9  7254.7  456.75
#Mann= 11 ,-1 , 0
  3104.2     .05       0  4858.3      .1       0    5021     .07       0
  5034.8      .1       0  5106.3     .05       0    5434      .1       0
  5506.7     .05       0  5754.5     .12       0  5761.7      .1       0
  5875.1     .12       0  5984.7     .05       0
Bank Sta=5021,5034.8
XS Rating Curve= 0 ,0
Exp/Cntr=0.3,0.1