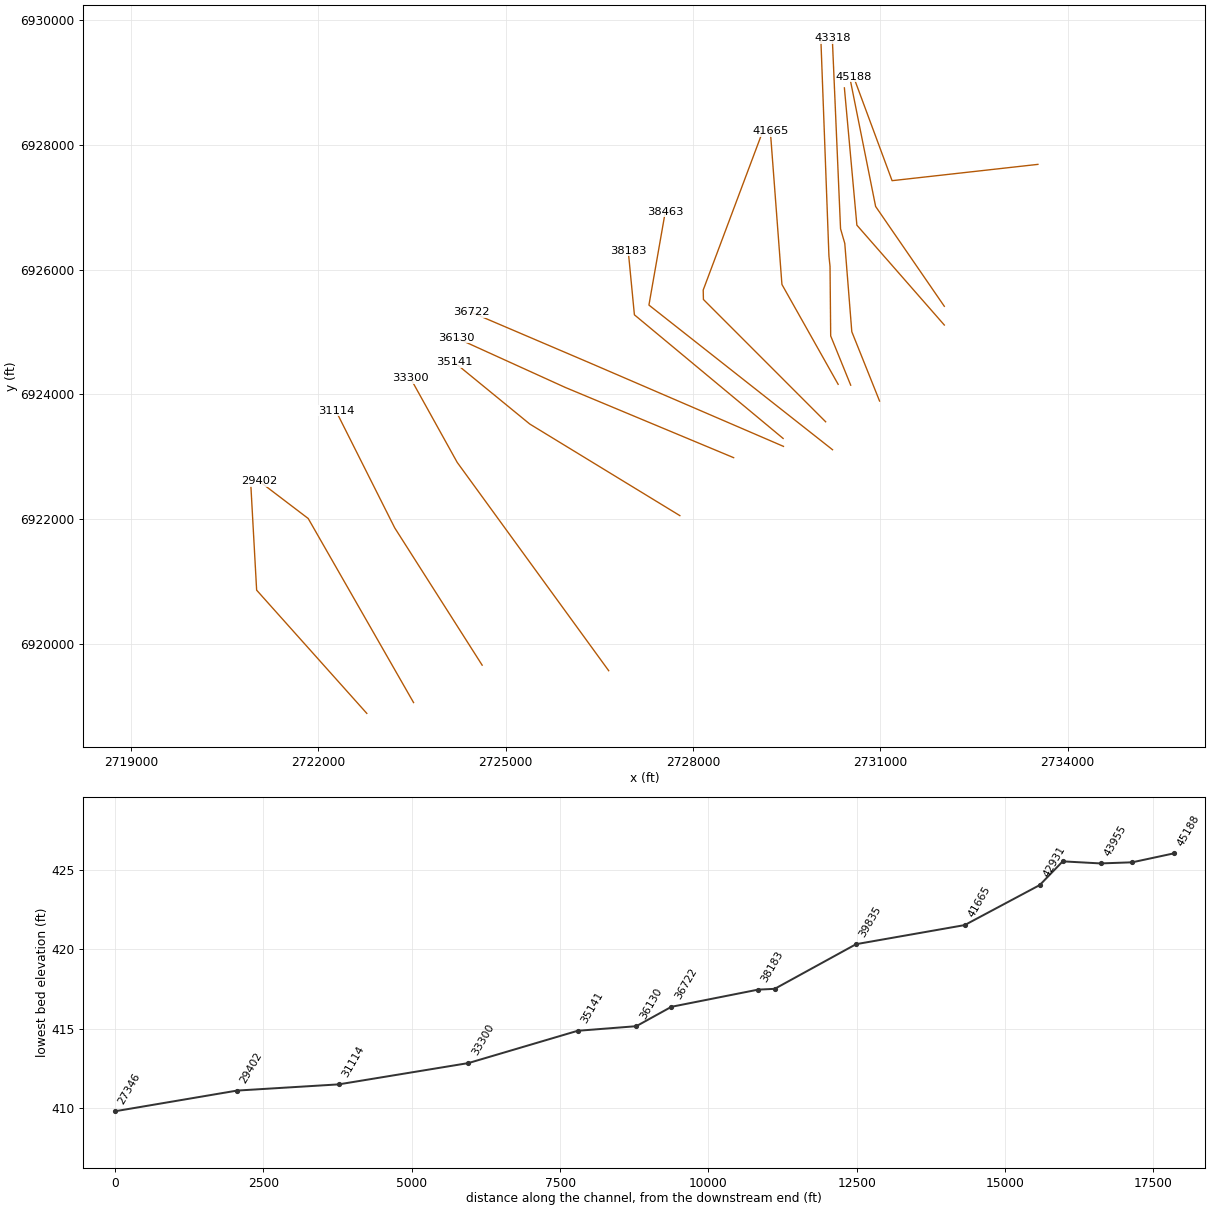
HEC-RAS study Allen Creek.prj: Allen Creek Base Level Engineering

--- Allen Creek.g01 (geometry) --- (continued)

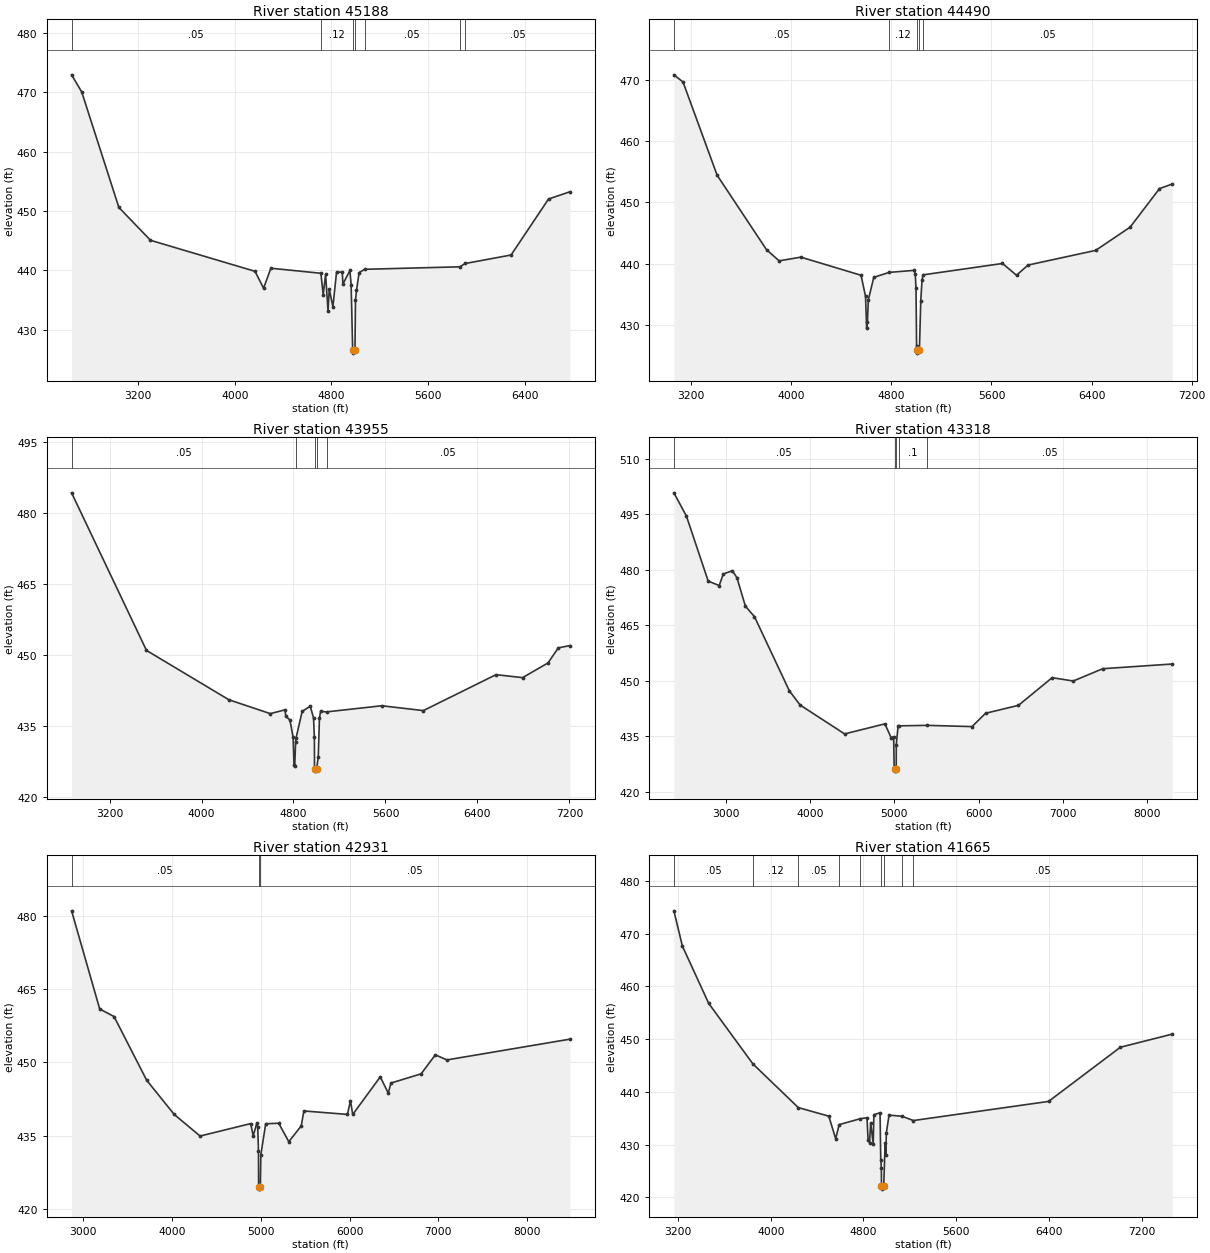
Type RM Length L Ch R = 1 ,45188   ,698,698,698
BEGIN DESCRIPTION:
Allen Creek 44.0
END DESCRIPTION:
XS GIS Cut Line= 3
      2733524.76      6927685.27      2731189.52      6927424.04
      2730573.78      6929087.01
#Sta/Elev= 30
  2650.2  472.95    2734  470.07  3041.4   450.6    3303  445.06  4168.1  439.83
  4238.8  436.98  4299.2  440.35  4713.2   439.5  4731.9  435.89    4752   439.3
  4772.1  433.13  4782.2  436.83  4812.4  433.86  4842.5  439.69  4890.1  439.69
  4895.2  437.68  4953.2  439.97  4963.3  437.52    4976  426.54    4978  426.04
  4994.9  426.54  4999.3  435.02  5007.4   436.6  5029.3  439.61  5075.7  440.17
  5862.9  440.59  5907.9  441.15  6286.7  442.58  6596.3  452.01  6773.3  453.24
#Mann= 7 ,-1 , 0
  2650.2     .05       0  4713.2     .12       0    4976     .07       0
  4994.9     .12       0  5075.7     .05       0  5862.9     .12       0
  5907.9     .05       0
Bank Sta=4976,4994.9
XS Rating Curve= 0 ,0
Exp/Cntr=0.3,0.1

Type RM Length L Ch R = 1 ,44490   ,535,535,535
BEGIN DESCRIPTION:
Allen Creek 43.0
END DESCRIPTION:
XS GIS Cut Line= 3
      2732025.99      6925411.02        2730926.        6927011.
      2730526.01      6929010.97
#Sta/Elev= 30
  3063.1  470.77  3135.9   469.6  3408.1  454.44  3803.3   442.3    3904   440.5
  4077.2   441.1  4558.2  438.15  4594.1  434.71  4602.9  429.51    4609  430.57
  4616.4  434.14  4659.7  437.81  4782.9  438.62  4982.4  438.95  4991.2  438.35
  4997.3     436  5001.7  426.68  5005.5  425.98  5007.5  425.48  5024.4  425.98
  5035.3     434  5045.5  437.42  5054.2  438.22    5688  440.07  5800.2  438.16
    5892  439.81  6432.5   442.2  6707.8  445.98  6942.4  452.25  7044.3     453
#Mann= 5 ,-1 , 0
  3063.1     .05       0  4782.9     .12       0  5005.5     .07       0
  5024.4     .12       0  5054.2     .05       0
Bank Sta=5005.5,5024.4
XS Rating Curve= 0 ,0
Exp/Cntr=0.3,0.1

Type RM Length L Ch R = 1 ,43955   ,637,637,637
BEGIN DESCRIPTION:
Allen Creek 42.0
END DESCRIPTION:
XS GIS Cut Line= 3
      2732026.02      6925110.98        2730626.        6926711.
        2730426.      6928910.97
#Sta/Elev= 30
  2869.5  484.32  3521.1  450.96  4237.7  440.52  4598.3  437.58  4726.5  438.39
  4733.1  437.02  4769.2  436.23  4796.7  432.55  4804.3  426.64    4811   426.6
  4818.5  431.66  4822.1  432.38  4875.5  438.07  4945.7  439.14  4974.2  436.71
  4981.8  432.54  4982.8  425.91  4984.8  425.41  5001.7  425.91  5015.6  428.49
  5025.7  436.63  5035.7  438.07  5087.5  437.95  5567.9  439.25  5929.4  438.22
    6562  445.83  6792.9   445.2  7013.8  448.31  7104.2   451.5  7204.6  451.99
#Mann= 5 ,-1 , 0
  2869.5     .05       0  4822.1      .1       0  4982.8     .07       0
  5001.7      .1       0  5087.5     .05       0
Bank Sta=4982.8,5001.7
XS Rating Curve= 0 ,0
Exp/Cntr=0.3,0.1

Type RM Length L Ch R = 1 ,43318   ,387,387,387
BEGIN DESCRIPTION:
Allen Creek 41.0
END DESCRIPTION:
XS GIS Cut Line= 5
      2730989.15       6923893.1      2730544.72      6925004.16
      2730432.22      6926418.74      2730364.49      6926653.41
      2730232.54      6929704.81
#Sta/Elev= 30
  2384.3  500.86  2532.8  494.56  2791.3  476.96  2921.9  475.77  2970.4   478.9
  3078.1  479.78  3131.9   477.9  3232.9  470.18  3340.6  467.34  3753.7   447.3
    3882  443.43  4410.4  435.61  4888.1  438.33  4962.1  434.61  4992.2  434.87
  4998.6  426.23  5003.1  426.04  5005.1  425.54  5022.5  426.04  5023.2  432.62
  5044.8  437.78  5052.4  437.79  5387.3  437.93  5922.5  437.59  6082.6  441.19
    6473  443.34  6873.4  450.83  7123.6  449.93  7473.9  453.26  8298.5  454.53
#Mann= 5 ,-1 , 0
  2384.3     .05       0  5003.1     .04       0  5022.5     .05       0
  5052.4      .1       0  5387.3     .05       0
Bank Sta=5003.1,5022.5
XS Rating Curve= 0 ,0
Exp/Cntr=0.3,0.1

Type RM Length L Ch R = 1 ,42931   ,1266,1266,1266
BEGIN DESCRIPTION:
Allen Creek 40.0
END DESCRIPTION:
XS GIS Cut Line= 5
      2730527.02      6924147.45       2730206.7      6924936.51
      2730195.98      6926051.69      2730178.54      6926216.75
      2730049.01      6929696.04
#Sta/Elev= 30
  2867.2  481.04    3184  460.94  3345.9  459.39  3712.8  446.36  4023.3  439.35
  4315.1  434.92    4885  437.47  4913.8  434.97    4954  437.55  4964.1  436.87
  4972.9  431.89  4974.5  424.55  4976.5  424.05  4993.9  424.55  4999.6  431.07
  5054.3  437.44  5201.1  437.54  5314.5  433.76  5454.6     437  5484.6  440.06
  5974.9  439.35  6009.5  442.16    6035  439.34  6345.2  447.04  6435.2  443.72
  6465.3  445.77  6805.5  447.66  6965.6  451.55  7095.7  450.51  8481.7  454.76
#Mann= 3 ,-1 , 0
  2867.2     .05       0  4974.5     .05       0  4993.9     .05       0
Bank Sta=4974.5,4993.9
XS Rating Curve= 0 ,0
Exp/Cntr=0.3,0.1

Type RM Length L Ch R = 1 ,41665   ,1830,1830,1830
BEGIN DESCRIPTION:
Allen Creek 38.0
END DESCRIPTION:
XS GIS Cut Line= 3
      2730325.99      6924161.02        2729426.      6925760.85
      2729240.39      6928217.45
#Sta/Elev= 30
  3164.4  474.36  3237.4  467.67  3464.3   456.8  3846.4  445.29  4237.5  437.01
  4500.7  435.38    4560   431.1    4590  433.77  4767.2  434.87  4830.2  435.09
  4839.5  430.93  4851.9  430.38  4862.1  434.13  4883.8  430.13  4889.5  435.65
  4942.8  436.03  4948.8  427.13  4954.5  425.46    4955  422.03    4957  421.53
  4974.5  422.03  4986.4   430.3  4992.1  427.99  4997.2  432.21  5020.2  435.58
  5132.5  435.36  5230.5  434.55  6396.4  438.18  7015.9  448.46  7463.6  450.96
#Mann= 9 ,-1 , 0
  3164.4     .05       0  3846.4     .12       0  4237.5     .05       0
    4590     .12       0  4767.2      .1       0    4955     .07       0
  4974.5      .1       0  5132.5     .12       0  5230.5     .05       0
Bank Sta=4955,4974.5
XS Rating Curve= 0 ,0
Exp/Cntr=0.3,0.1

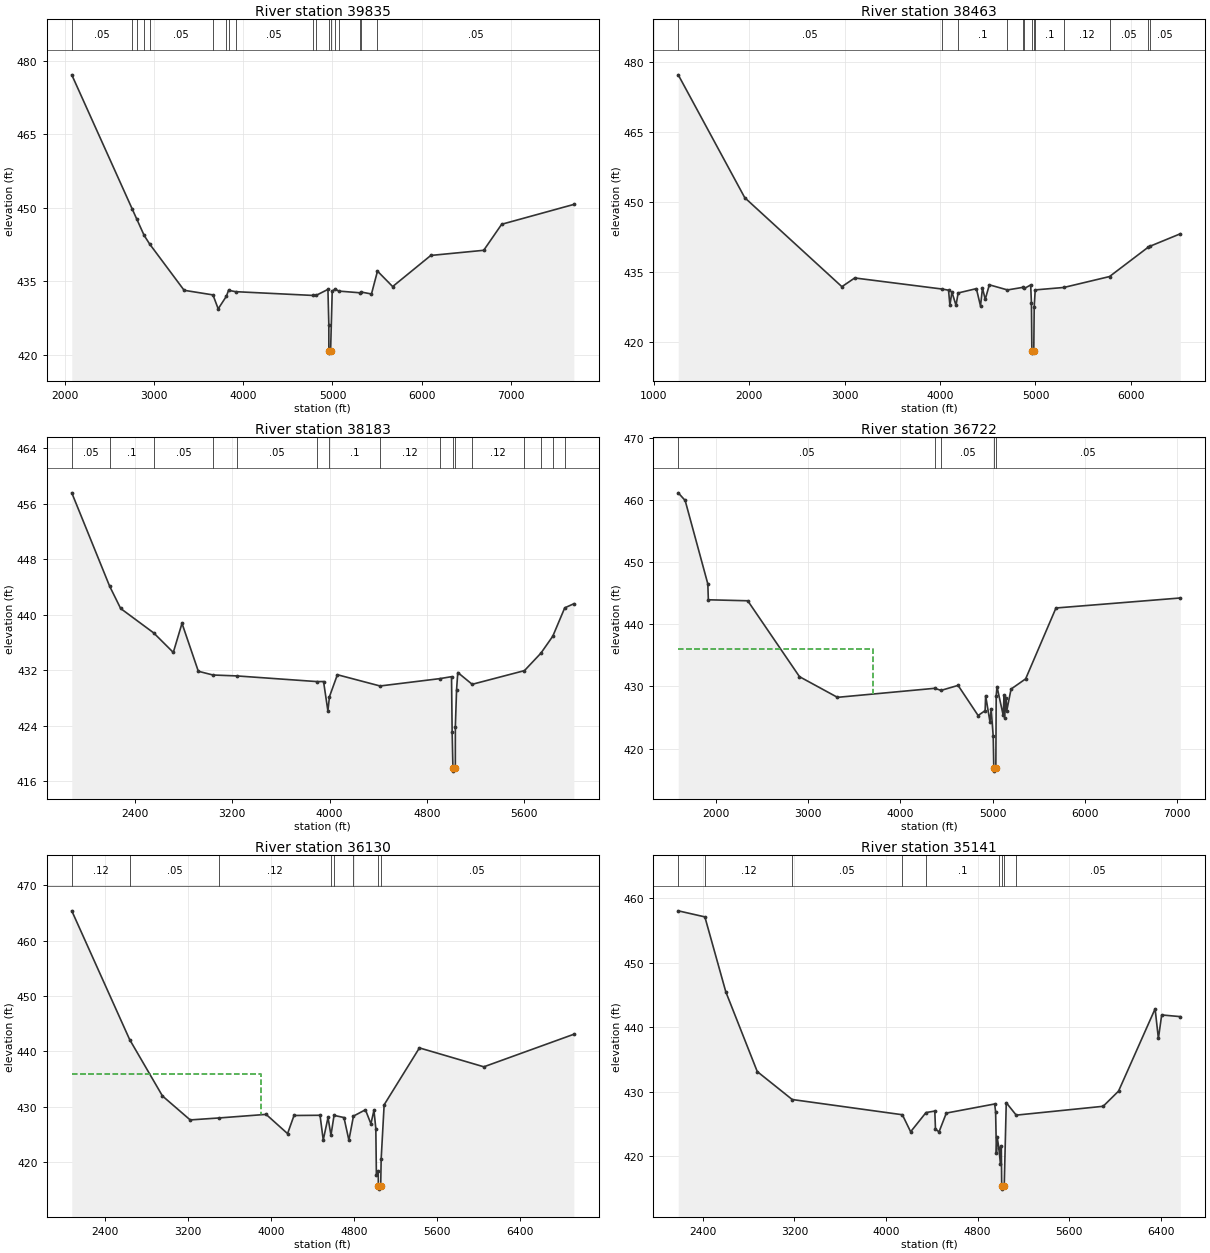
Type RM Length L Ch R = 1 ,39835   ,1372,1372,1372
BEGIN DESCRIPTION:
Allen Creek 37.0
END DESCRIPTION:
XS GIS Cut Line= 4
      2730126.02      6923560.98      2728168.81       6925520.7
      2728165.51      6925671.98      2729114.41      6928204.13
#Sta/Elev= 30
    2079  477.11  2754.4  449.81  2806.7   447.7  2889.6  444.36  2950.3  442.62
  3337.7  433.15  3660.9  432.21  3719.5  429.37  3811.5  431.94  3835.4  433.15
  3913.7  432.87  4781.2   432.1  4816.3  432.11    4949  433.33    4959   426.1
  4959.2  420.83  4961.2  420.33  4978.8  420.83    4997  432.94  5029.7   433.4
  5069.8  432.99  5308.3  432.64  5324.3  432.78  5436.8   432.4  5504.1  437.06
  5674.1  433.91  6101.4  440.26  6694.3  441.31  6895.5  446.62  7704.1  450.67
#Mann= 18 ,-1 , 0
    2079     .05       0  2754.4     .12       0  2806.7     .05       0
  2889.6     .12       0  2950.3     .05       0  3660.9     .12       0
  3811.5     .05       0  3835.4     .12       0  3913.7     .05       0
  4781.2     .12       0  4816.3      .1       0  4959.2     .07       0
  4978.8      .1       0  5029.7     .12       0  5069.8      .1       0
  5308.3     .12       0  5324.3      .1       0  5504.1     .05       0
Bank Sta=4959.2,4978.8
XS Rating Curve= 0 ,0
Exp/Cntr=0.3,0.1

Type RM Length L Ch R = 1 ,38463   ,280,280,280
BEGIN DESCRIPTION:
Allen Creek 36.0
END DESCRIPTION:
XS GIS Cut Line= 3
      2730236.54       6923112.7      2727296.43      6925430.73
      2727558.52      6926926.24
#Sta/Elev= 30
    1256   477.2  1953.3  450.85  2971.4  431.77  3106.1  433.64  4018.8  431.27
    4089  431.02  4103.4   427.8  4124.2  430.63  4167.5  427.77  4189.6  430.42
  4380.8  431.35  4424.1  427.64  4444.9  431.48  4473.8  429.05  4516.6  432.17
    4707  431.07  4866.7  431.62  4883.3  431.38  4949.9  432.14    4958  428.19
  4962.6  418.02  4964.6  417.52  4982.4  418.02  4986.9  427.41  4997.5  431.08
  5297.3   431.6  5776.2  433.94  6183.2  440.26  6198.2  440.42  6518.3  443.11
#Mann= 13 ,-1 , 0
    1256     .05       0  4018.8     .12       0  4189.6      .1       0
    4707     .12       0  4866.7      .1       0  4883.3     .12       0
  4962.6     .07       0  4982.4     .12       0  4997.5      .1       0
  5297.3     .12       0  5776.2     .05       0  6183.2     .12       0
  6198.2     .05       0
Bank Sta=4962.6,4982.4
XS Rating Curve= 0 ,0
Exp/Cntr=0.3,0.1

Type RM Length L Ch R = 1 ,38183   ,1461,1461,1461
BEGIN DESCRIPTION:
Allen Creek 35.0
END DESCRIPTION:
XS GIS Cut Line= 3
      2729444.88      6923293.86      2727063.78      6925274.78
      2726964.82      6926300.85
#Sta/Elev= 30
  1880.4  457.54  2191.2  444.12  2282.2  440.89    2554  437.37  2715.2  434.56
  2786.8  438.75  2920.9  431.85  3041.3  431.31  3236.3  431.18  3898.2  430.36
  3950.7  430.37  3986.3  426.15  3999.4   428.2  4064.3  431.35  4415.3  429.73
  4907.2  430.79  5002.9  431.07  5007.9  423.13  5014.3  417.97  5016.3  417.47
  5034.1  417.97  5034.3  423.88  5044.3  429.17  5054.3  431.67  5172.7  429.97
  5602.5  431.94  5737.5  434.45  5835.6   436.9  5933.7  440.98  6008.6  441.57
#Mann= 16 ,-1 , 0
  1880.4     .05       0  2191.2      .1       0    2554     .05       0
  3041.3     .12       0  3236.3     .05       0  3898.2     .12       0
  3999.4      .1       0  4415.3     .12       0  4907.2      .1       0
  5014.3     .07       0  5034.1      .1       0  5172.7     .12       0
  5602.5      .1       0  5737.5     .12       0  5835.6     .05       0
  5933.7     .12       0
Bank Sta=5014.3,5034.1
XS Rating Curve= 0 ,0
Exp/Cntr=0.3,0.1

Type RM Length L Ch R = 1 ,36722   ,592,592,592
BEGIN DESCRIPTION:
Allen Creek 34.0
END DESCRIPTION:
XS GIS Cut Line= 3
      2729450.53       6923166.7      2726320.41      6924516.61
      2724450.75      6925315.04
#Sta/Elev= 30
  1591.2  461.12  1666.1  459.89  1911.9  446.48  1917.6  443.93  2344.6  443.77
  2905.5  431.57  3316.8  428.25  4369.7   429.7  4440.5  429.37  4624.4  430.17
  4841.4  425.33  4917.5  426.11  4922.9  428.52  4969.9  424.31    4983  426.36
  5005.1  421.99  5011.5  416.89  5013.7  416.39  5033.6  416.89  5037.4  428.51
  5046.1  429.97  5113.5  425.35  5122.4  428.62  5127.8  424.99    5146  428.21
  5151.4  426.05  5198.6  429.58  5356.6  431.22  5685.2  442.61    7033  444.22
#Mann= 5 ,-1 , 0
  1591.2     .05       0  4369.7     .12       0  4440.5     .05       0
  5011.5     .05       0  5033.6     .05       0
#XS Ineff= 2 , 0
       0    3700     436               0
Permanent Ineff=
       F       F
Bank Sta=5011.5,5033.6
XS Rating Curve= 0 ,0
Exp/Cntr=0.3,0.1

Type RM Length L Ch R = 1 ,36130   ,989,989,989
BEGIN DESCRIPTION:
Allen Creek 29.0
END DESCRIPTION:
XS GIS Cut Line= 3
      2728652.64      6922985.73      2725955.54       6924111.7
      2724211.26      6924904.99
#Sta/Elev= 30
  2077.3  465.36  2635.2  442.14  2951.4  431.97  3218.5  427.65  3499.7  428.01
  3950.4  428.65  4157.1  425.18  4219.3  428.45    4470  428.49    4501  424.02
  4546.9  428.09  4575.3  424.89  4605.1  428.47  4700.6  428.08  4748.2  423.99
  4792.1  428.34  4907.4  429.48  4960.4  426.95  4989.6  429.39  5007.7   426.1
  5013.2  417.64  5030.8  418.46  5032.4  415.67  5034.6  415.17  5054.5  415.67
  5059.3  420.62  5087.9  430.38  5427.9  440.64  6048.8  437.23  6916.2   443.1
#Mann= 8 ,-1 , 0
  2077.3     .12       0  2635.2     .05       0  3499.7     .12       0
  4575.3      .1       0  4605.1     .12       0  4792.1      .1       0
  5032.4     .07       0  5054.5     .05       0
#XS Ineff= 2 , 0
       0    3900     436               0
Permanent Ineff=
       F       F
Bank Sta=5032.4,5054.5
XS Rating Curve= 0 ,0
Exp/Cntr=0.3,0.1

Type RM Length L Ch R = 1 ,35141   ,1841,1841,1841
BEGIN DESCRIPTION:
Allen Creek 28.0
END DESCRIPTION:
XS GIS Cut Line= 3
      2727791.46      6922057.12      2725389.21      6923524.19
       2724174.5      6924518.55
#Sta/Elev= 30
  2185.2  458.02  2417.8  457.08  2600.5  445.47  2875.4   433.1  3180.6  428.77
  4142.5  426.41  4214.8  423.77    4349  426.75  4425.8  426.98  4431.7  424.19
  4462.6  423.75  4526.5  426.67  4948.5  428.08  4956.9  426.85  4963.9  420.49
  4969.8     423    4985  421.28    4999  418.78  5006.7  421.57    5010  415.38
  5012.2  414.88  5032.1  415.38  5049.8  428.28  5136.8  426.35  5895.9  427.72
  6030.3  430.07  6349.7  442.83  6378.4  438.23  6407.1  441.88  6569.8  441.62
#Mann= 9 ,-1 , 0
  2185.2     .05       0  2417.8     .12       0  3180.6     .05       0
  4142.5     .12       0    4349      .1       0    4985     .12       0
    5010     .07       0  5032.1     .12       0  5136.8     .05       0
Bank Sta=5010,5032.1
XS Rating Curve= 0 ,0
Exp/Cntr=0.3,0.1

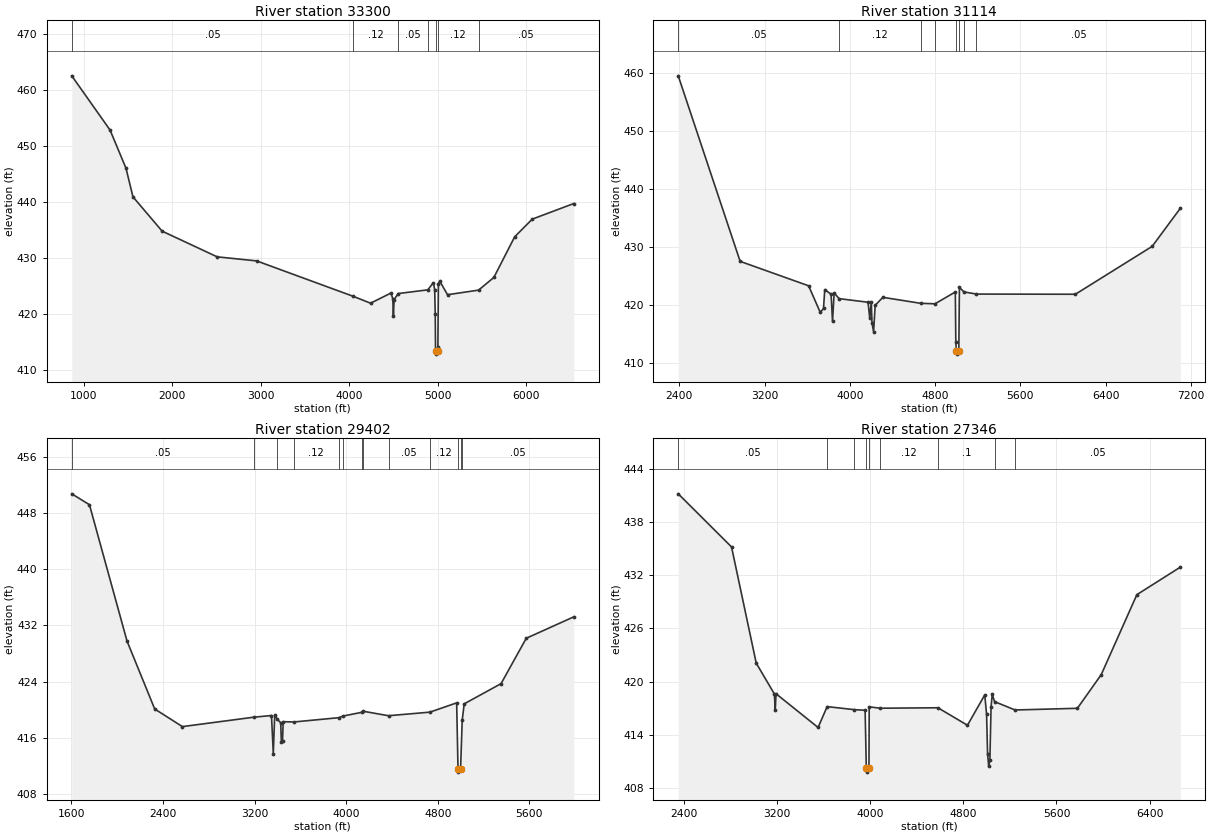
Type RM Length L Ch R = 1 ,33300   ,2186,2186,2186
BEGIN DESCRIPTION:
Allen Creek 27.0
END DESCRIPTION:
XS GIS Cut Line= 3
      2726652.31      6919571.92        2724226.        6922911.
      2723477.45      6924261.15
#Sta/Elev= 30
   866.6  462.46  1299.2  452.79  1479.3  445.98  1557.7  440.89  1887.4  434.77
  2509.5  430.19  2954.5  429.47  4044.9  423.16  4241.7  421.93    4472  423.74
  4492.9  422.73  4499.7  419.63  4507.6  422.56  4554.3  423.65  4888.6  424.31
  4951.2  425.59  4965.9  424.36  4972.1  420.05  4975.7  413.35  4977.9  412.85
  4997.8  413.35  5002.1  414.16  5007.9  425.43  5023.9  425.84  5110.9  423.44
  5461.9  424.26  5634.4  426.52  5869.7  433.77  6068.9  436.92  6537.9   439.7
#Mann= 7 ,-1 , 0
   866.6     .05       0  4044.9     .12       0  4554.3     .05       0
  4888.6     .12       0  4975.7     .07       0  4997.8     .12       0
  5461.9     .05       0
Bank Sta=4975.7,4997.8
XS Rating Curve= 0 ,0
Exp/Cntr=0.3,0.1

Type RM Length L Ch R = 1 ,31114   ,1712,1712,1712
BEGIN DESCRIPTION:
Allen Creek 24.0
END DESCRIPTION:
XS GIS Cut Line= 3
      2724625.99      6919661.02        2723226.        6921861.
      2722282.01      6923740.84
#Sta/Elev= 30
    2389  459.57  2969.8  427.53  3612.4  423.31  3721.6  418.72  3752.1  419.39
  3763.9  422.64  3823.2  421.86  3836.7  417.15    3852  422.09  3898.6  421.09
  4170.3  420.47  4185.6  417.75  4200.8  420.54  4206.7  416.94    4222  415.38
  4237.2  419.95  4309.2  421.32  4662.4  420.29  4798.1   420.2    4989  422.24
  4993.7  413.52  4999.5  412.01  5001.7  411.51  5021.8  412.01  5027.4  423.02
    5071  422.25  5187.3  421.88  6115.7  421.85  6836.2  430.12  7100.2  436.69
#Mann= 8 ,-1 , 0
    2389     .05       0  3898.6     .12       0  4662.4      .1       0
  4798.1     .12       0  4999.5     .07       0  5021.8     .12       0
    5071      .1       0  5187.3     .05       0
Bank Sta=4999.5,5021.8
XS Rating Curve= 0 ,0
Exp/Cntr=0.3,0.1

Type RM Length L Ch R = 1 ,29402   ,2056,2056,2056
BEGIN DESCRIPTION:
Allen Creek 21.0
END DESCRIPTION:
XS GIS Cut Line= 3
      2723527.69      6919061.99      2721841.06      6922010.81
      2721053.73      6922610.16
#Sta/Elev= 30
  1602.9  450.74  1757.3  449.19  2085.6  429.78  2327.5  420.11  2569.5   417.6
  3192.7  418.94  3347.8  419.18  3363.6  413.75  3375.9  419.28  3399.1  418.62
  3428.4  418.16  3434.2  415.38  3444.2   415.6    3450   418.3    3543  418.26
  3935.7  418.87    3975  419.11  4141.3  419.65  4150.9  419.78  4370.3  419.15
  4732.1  419.66  4965.7  420.98  4977.4  411.62  4979.6  411.12    5000  411.62
  5014.2  418.52  5031.5  420.84  5353.6  423.72    5574  430.18  5989.5  433.23
#Mann= 13 ,-1 , 0
  1602.9     .05       0  3192.7     .12       0  3399.1      .1       0
    3543     .12       0  3935.7      .1       0    3975     .12       0
  4141.3      .1       0  4150.9     .12       0  4370.3     .05       0
  4732.1     .12       0  4977.4     .07       0    5000     .12       0
  5014.2     .05       0
Bank Sta=4977.4,5000
XS Rating Curve= 0 ,0
Exp/Cntr=0.3,0.1

Type RM Length L Ch R = 1 ,27346   ,750,750,750
BEGIN DESCRIPTION:
Allen Creek 20.0
END DESCRIPTION:
XS GIS Cut Line= 3
      2722778.98      6918888.39      2721015.25      6920862.72
      2720923.52      6922523.39
#Sta/Elev= 30
  2352.6  441.17  2810.1  435.19  3022.4  422.09  3177.9  418.63  3185.4  416.83
  3192.2  418.65  3553.3  414.85  3631.1   417.2  3862.6  416.86  3957.1  416.79
  3967.3  410.32  3969.5  409.82    3990  410.32  3992.2  417.18  4083.7  417.02
  4582.4  417.07  4835.7   415.1  4984.3  418.52    5000  416.33  5008.3   411.9
  5018.3  410.46  5028.3  411.19  5038.3  417.14  5048.4  418.58  5068.7  417.76
  5244.8  416.82  5779.5  417.01  5984.2   420.8  6290.2  429.81  6663.2  432.91
#Mann= 9 ,-1 , 0
  2352.6     .05       0  3631.1     .12       0  3862.6      .1       0
  3967.3     .07       0    3990      .1       0  4083.7     .12       0
  4582.4      .1       0  5068.7     .12       0  5244.8     .05       0
Bank Sta=3967.3,3990
XS Rating Curve= 0 ,0
Exp/Cntr=0.3,0.1