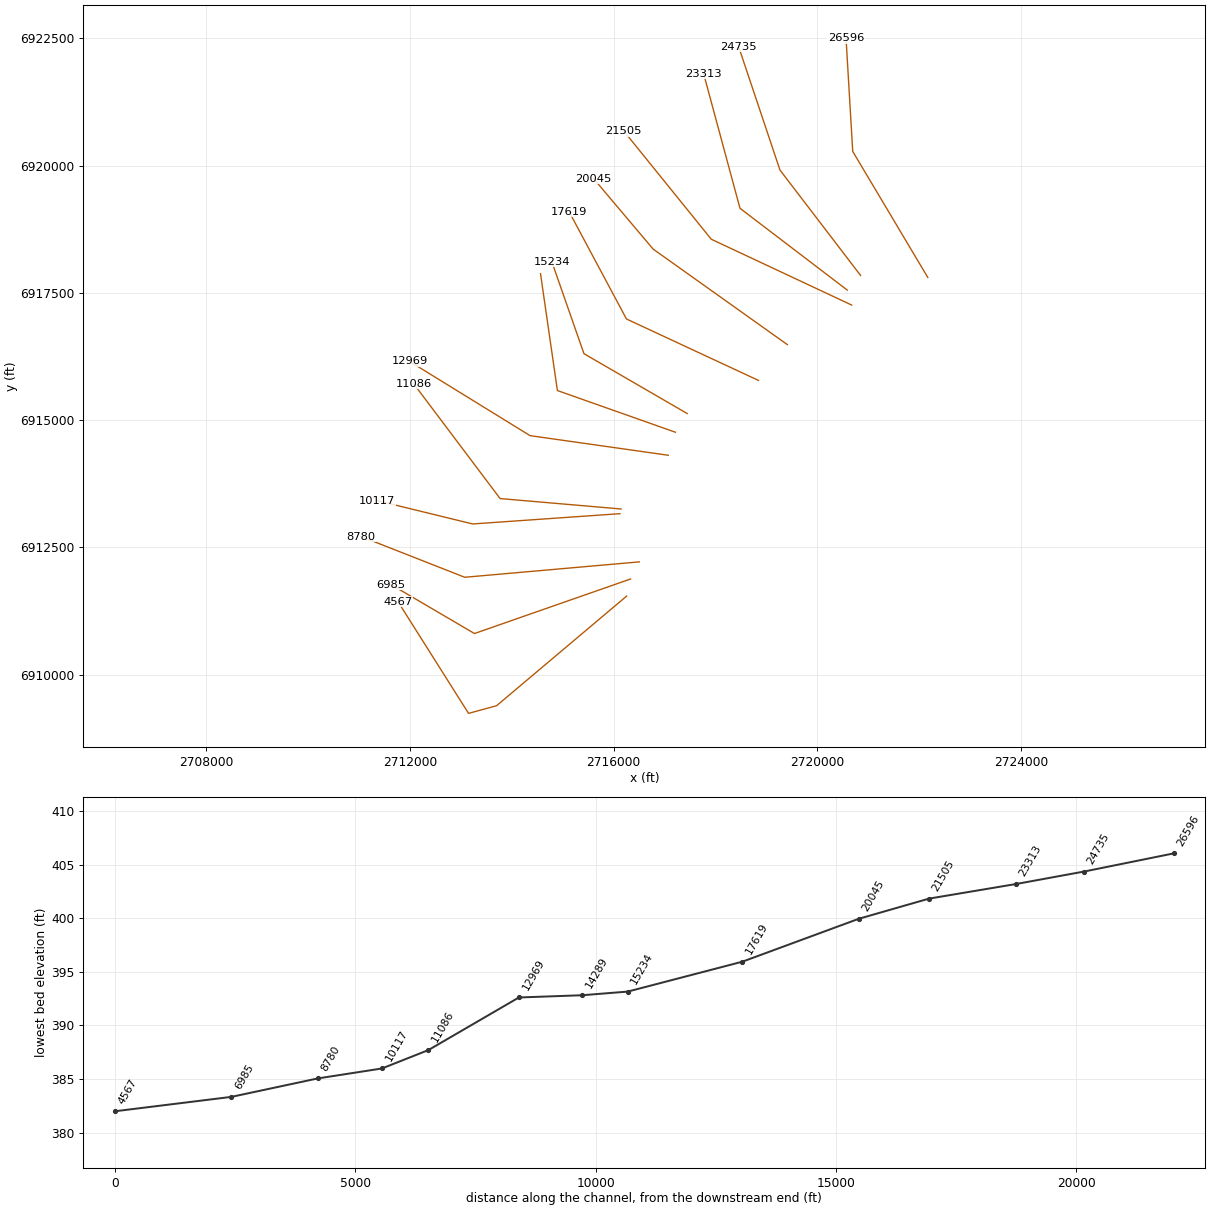
HEC-RAS study Allen Creek.prj: Allen Creek Base Level Engineering

--- Allen Creek.g01 (geometry) --- (continued)

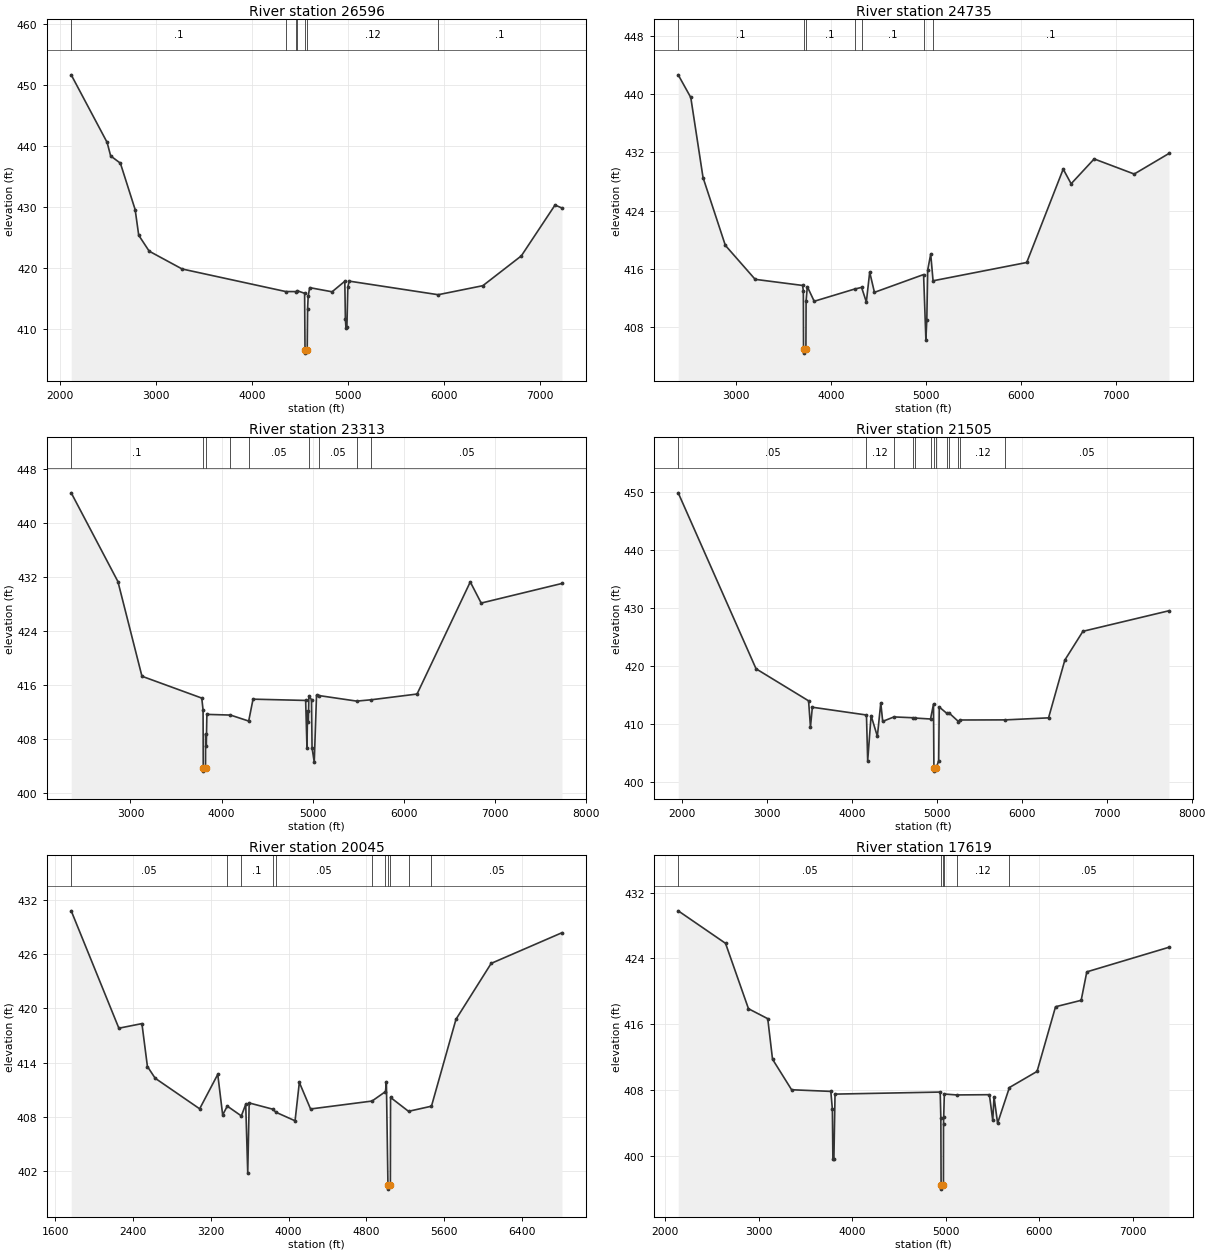
Type RM Length L Ch R = 1 ,26596   ,1861,1861,1861
BEGIN DESCRIPTION:
Allen Creek 19.0
END DESCRIPTION:
XS GIS Cut Line= 3
      2722171.34      6917803.33      2720696.66       6920280.4
      2720565.45      6922502.93
#Sta/Elev= 30
  2117.2   451.7    2491  440.62    2528   438.4  2629.2  437.21  2783.1  429.59
  2820.1  425.39  2929.1  422.78  3271.8  419.86  4350.7  416.16  4460.6  416.15
  4468.8   416.3  4547.3  415.87  4551.5  406.56  4553.8  406.06  4574.2  406.56
  4578.5  413.33  4584.3  415.36  4599.9   416.8  4833.5  416.12  4965.8  417.85
  4971.8  411.65  4977.6  410.21  4987.4  410.27  4997.4  416.87  5010.6  417.87
  5937.6  415.64    6403  417.12  6803.7  422.01  7154.3  430.34  7226.4  429.86
#Mann= 7 ,-1 , 0
  2117.2      .1       0  4350.7     .12       0  4460.6      .1       0
  4468.8     .12       0  4551.5     .07       0  4574.2     .12       0
  5937.6      .1       0
Bank Sta=4551.5,4574.2
XS Rating Curve= 0 ,0
Exp/Cntr=0.3,0.1

Type RM Length L Ch R = 1 ,24735   ,1422,1422,1422
BEGIN DESCRIPTION:
Allen Creek 18.0
END DESCRIPTION:
XS GIS Cut Line= 3
       2720851.9      6917841.51      2719267.55      6919914.48
      2718456.42      6922336.99
#Sta/Elev= 30
  2390.9  442.69  2523.3  439.57  2652.1  428.55  2886.9  419.21  3200.7  414.53
  3699.4  413.69  3707.7  412.95  3709.7  404.87  3712.2  404.37  3734.7  404.87
  3736.7  411.56  3749.6  413.52  3821.9  411.51  4246.3  413.19  4320.8  413.42
  4370.6  411.41  4405.9  415.52  4455.8  412.74    4973  415.19  4997.2  406.24
  5006.9  408.99  5016.4  415.83    5048  418.01  5072.6  414.33  6058.1  416.85
  6442.1  429.71  6525.5  427.69    6768  431.11  7189.2  429.03  7554.7  431.86
#Mann= 7 ,-1 , 0
  2390.9      .1       0  3709.7     .07       0  3734.7      .1       0
  4246.3     .12       0  4320.8      .1       0    4973     .12       0
  5072.6      .1       0
Bank Sta=3709.7,3734.7
XS Rating Curve= 0 ,0
Exp/Cntr=0.3,0.1

Type RM Length L Ch R = 1 ,23313   ,1808,1808,1808
BEGIN DESCRIPTION:
Allen Creek 17.0
END DESCRIPTION:
XS GIS Cut Line= 3
       2720589.3      6917555.05       2718482.1      6919163.13
      2717768.49      6921807.23
#Sta/Elev= 30
  2349.3   444.5  2862.4  431.33  3126.3  417.28  3783.1  414.04  3797.6  412.26
  3799.6   403.7  3802.1   403.2  3824.6   403.7  3825.2  408.75    3833  406.91
  3839.2  411.62  4098.6  411.52  4298.5  410.63  4346.3  413.88  4924.1  413.69
  4938.6  406.67  4944.9  412.16  4953.2  410.54  4959.5  414.32  4988.5  413.81
  4994.4  406.66  5018.5  404.53  5043.5  414.48    5072  414.41  5485.1  413.59
  5644.8  413.79  6147.5  414.64    6732  431.28  6851.8  428.14  7738.7  431.05
#Mann= 9 ,-1 , 0
  2349.3      .1       0  3799.6     .07       0  3824.6      .1       0
  4098.6     .12       0  4298.5     .05       0  4959.5     .12       0
    5072     .05       0  5485.1     .12       0  5644.8     .05       0
Bank Sta=3799.6,3824.6
XS Rating Curve= 0 ,0
Exp/Cntr=0.3,0.1

Type RM Length L Ch R = 1 ,21505   ,1460,1460,1460
BEGIN DESCRIPTION:
Allen Creek 14.0
END DESCRIPTION:
XS GIS Cut Line= 3
      2720676.04      6917260.98      2717918.32      6918554.48
      2716201.32      6920680.02
#Sta/Elev= 30
    1954  449.79  2870.8  419.47  3489.3  413.95  3511.4  409.44  3533.5  412.85
  4170.8  411.51  4185.2  403.62  4225.2   411.4  4299.2  407.84  4339.3   413.6
  4361.9  410.41  4494.9  411.18  4714.2  411.04  4747.6  410.98  4925.1  410.82
  4960.2  413.39    4965  402.34  4967.5  401.84    4990  402.34  5021.2  403.61
  5027.6  412.89  5117.3  411.79  5145.1  411.84  5254.4  410.38  5268.5  410.65
  5807.9  410.67  6314.9  411.02  6506.8  420.98  6719.5  425.93  7732.4  429.47
#Mann= 13 ,-1 , 0
    1954     .05       0  4170.8     .12       0  4494.9     .05       0
  4714.2     .12       0  4747.6     .05       0  4925.1     .12       0
    4965     .07       0    4990     .12       0  5117.3     .05       0
  5145.1     .12       0  5254.4      .1       0  5268.5     .12       0
  5807.9     .05       0
Bank Sta=4965,4990
XS Rating Curve= 0 ,0
Exp/Cntr=0.3,0.1

Type RM Length L Ch R = 1 ,20045   ,2426,2426,2426
BEGIN DESCRIPTION:
Allen Creek 13.0
END DESCRIPTION:
XS GIS Cut Line= 3
      2719413.08      6916483.01      2716775.69      6918361.34
      2715605.79      6919747.54
#Sta/Elev= 30
  1762.1  430.83  2252.8  417.81  2490.1  418.32  2546.7  413.56  2626.6  412.26
  3084.4  408.87  3270.8  412.69  3321.3  408.19  3368.8  409.17  3513.5  408.08
  3558.6  409.36  3579.5  401.75  3594.2  409.52    3836  408.83  3871.1  408.48
  4066.6  407.54  4110.6   411.8  4226.2  408.85  4859.1  409.73  4997.5  410.78
  5006.7  411.88  5022.8  400.46  5025.3  399.96  5047.8  400.46  5049.6  410.13
  5234.8  408.59  5470.8  409.16  5723.1   418.8  6085.6     425  6813.9   428.4
#Mann= 11 ,-1 , 0
  1762.1     .05       0  3368.8     .12       0  3513.5      .1       0
    3836     .12       0  3871.1     .05       0  4859.1     .12       0
  4997.5     .05       0  5022.8     .07       0  5047.8     .05       0
  5234.8     .12       0  5470.8     .05       0
Bank Sta=5022.8,5047.8
XS Rating Curve= 0 ,0
Exp/Cntr=0.3,0.1

Type RM Length L Ch R = 1 ,17619   ,2385,2385,2385
BEGIN DESCRIPTION:
Allen Creek 12.0
END DESCRIPTION:
XS GIS Cut Line= 3
      2718844.78      6915780.16      2716252.88      6916987.27
      2715127.97       6919091.9
#Sta/Elev= 30
  2140.8  429.78  2646.7  425.83    2892  417.88  3097.9  416.67  3149.1  411.74
  3352.9  408.03  3772.1  407.83  3788.8  405.67  3794.3  399.66  3805.2  399.67
  3817.2   407.5  4941.4  407.75  4948.3  404.58    4951  396.45  4953.5  395.95
    4976  396.45  4976.7  403.87  4978.7   404.7  4985.5  407.51  5117.5   407.4
  5467.1  407.43  5503.1  404.31  5516.6  407.18  5554.9  403.96    5681   408.3
  5976.8  410.26  6174.3  418.12  6448.2   418.9  6508.4  422.36  7386.4  425.35
#Mann= 6 ,-1 , 0
  2140.8     .05       0    4951     .07       0    4976     .05       0
  4978.7      .1       0  5117.5     .12       0    5681     .05       0
Bank Sta=4951,4976
XS Rating Curve= 0 ,0
Exp/Cntr=0.3,0.1

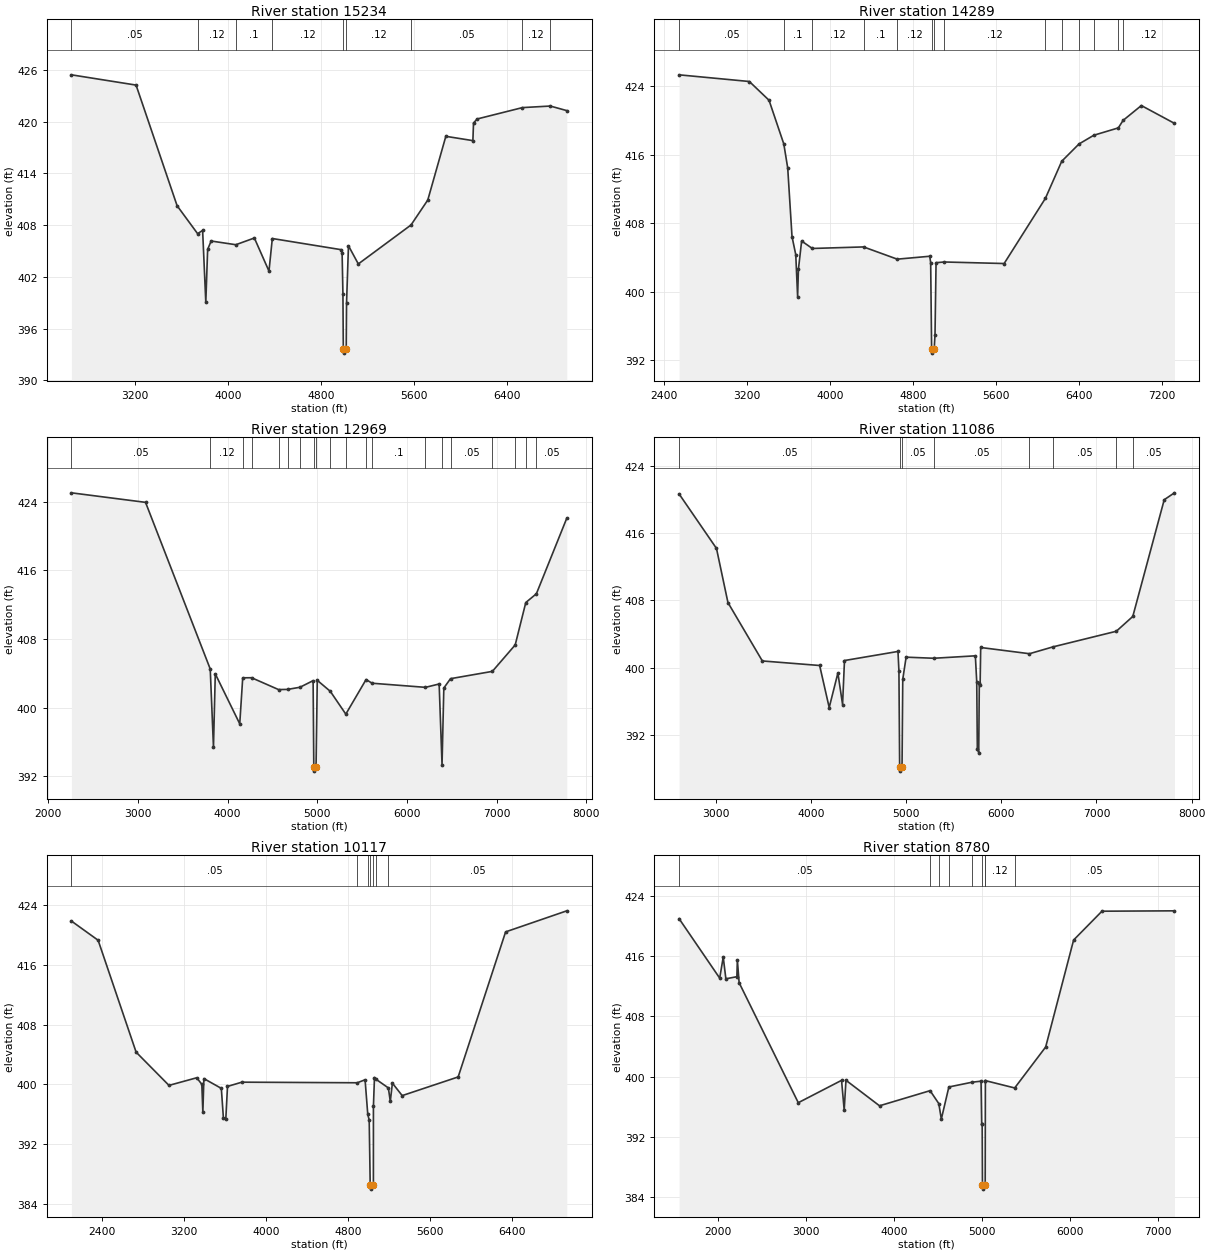
Type RM Length L Ch R = 1 ,15234   ,945,945,945
BEGIN DESCRIPTION:
Allen Creek 10.0
END DESCRIPTION:
XS GIS Cut Line= 3
      2717445.04      6915129.11      2715417.87      6916304.93
       2714786.6       6918113.1
#Sta/Elev= 30
  2656.5  425.43  3212.2  424.24    3565  410.25  3741.3  407.01  3784.4  407.39
  3811.7  399.06  3827.5  405.19  3857.7  406.16    4070  405.73  4229.1  406.51
  4354.8  402.67  4383.5  406.45  4977.7  405.15  4983.5  404.79  4990.6  400.02
  4993.9  393.66  4996.4  393.16  5018.9  393.66  5021.6  398.94  5038.2  405.61
  5122.9   403.5    5576  408.02    5720  410.91  5875.3   418.3  6107.9   417.8
  6113.2  419.84  6144.2  420.31  6533.9  421.63  6773.3  421.81  6915.2  421.28
#Mann= 9 ,-1 , 0
  2656.5     .05       0  3741.3     .12       0    4070      .1       0
  4383.5     .12       0  4993.9     .07       0  5018.9     .12       0
    5576     .05       0  6533.9     .12       0  6773.3     .05       0
Bank Sta=4993.9,5018.9
XS Rating Curve= 0 ,0
Exp/Cntr=0.3,0.1

Type RM Length L Ch R = 1 ,14289   ,1320,1320,1320
BEGIN DESCRIPTION:
Allen Creek 8.0
END DESCRIPTION:
XS GIS Cut Line= 3
      2717214.11       6914761.5      2714896.07      6915580.89
      2714564.53      6917876.88
#Sta/Elev= 30
  2541.4  425.34  3219.3  424.56  3409.1  422.37  3551.7  417.26  3589.4  414.45
  3630.8  406.44    3667  404.32  3684.9  399.43  3692.6  402.61  3723.6  405.92
  3826.6  405.05  4321.1  405.23  4645.8   403.8  4959.1  404.14  4968.3  403.41
  4977.5  393.32    4980  392.82  5002.5  393.32  5010.2  394.99  5020.3  403.39
  5100.6  403.47  5677.1  403.29  6075.2  410.91  6232.6  415.24  6399.2  417.26
  6542.2  418.28  6778.7  419.14    6824  420.01  7000.6  421.75  7319.8  419.67
#Mann= 14 ,-1 , 0
  2541.4     .05       0  3551.7      .1       0  3826.6     .12       0
  4321.1      .1       0  4645.8     .12       0  4977.5     .07       0
  5002.5     .12       0  5100.6     .12       0  6075.2      .1       0
  6232.6     .12       0  6399.2      .1       0  6542.2     .12       0
  6778.7      .1       0    6824     .12       0
Bank Sta=4977.5,5002.5
XS Rating Curve= 0 ,0
Exp/Cntr=0.3,0.1

Type RM Length L Ch R = 1 ,12969   ,1883,1883,1883
BEGIN DESCRIPTION:
Allen Creek 7.0
END DESCRIPTION:
XS GIS Cut Line= 3
      2717074.21      6914308.81      2714359.35      6914694.34
      2711991.46       6916154.3
#Sta/Elev= 30
  2257.9  425.03  3084.3  423.92  3805.6  404.51  3841.8  395.41    3862  403.94
  4134.8  398.12  4167.9  403.48  4266.5  403.49  4567.5  402.11  4667.9  402.13
  4806.2  402.38  4952.9  403.15  4960.6  393.11  4963.1  392.61  4985.6  393.11
  4999.2  403.19  5144.3  401.91  5317.6  399.25  5543.6  403.28  5610.5  402.85
  6205.3  402.37  6358.4  402.76  6390.6  393.35  6410.5  402.29  6485.1  403.38
  6951.8  404.23  7206.4  407.31  7324.5  412.25  7442.6  413.27  7781.8  422.08
#Mann= 20 ,-1 , 0
  2257.9     .05       0  3805.6     .12       0  4167.9      .1       0
  4266.5      .1       0  4567.5     .12       0  4667.9      .1       0
  4806.2     .12       0  4960.6     .07       0  4985.6     .12       0
  5144.3      .1       0  5317.6      .1       0  5543.6     .12       0
  5610.5      .1       0  6205.3     .12       0  6390.6     .12       0
  6485.1     .05       0  6951.8     .12       0  7206.4      .1       0
  7324.5     .12       0  7442.6     .05       0
Bank Sta=4960.6,4985.6
XS Rating Curve= 0 ,0
Exp/Cntr=0.3,0.1

Type RM Length L Ch R = 1 ,11086   ,969,969,969
BEGIN DESCRIPTION:
Allen Creek 6.0
END DESCRIPTION:
XS GIS Cut Line= 3
      2716147.57      6913252.82      2713770.61      6913458.01
      2712075.97      6915711.03
#Sta/Elev= 30
  2614.2  420.66  3007.2  414.18  3127.7  407.74    3489   400.8  4091.2  400.26
  4191.6  395.26    4283  399.37  4332.1  395.62  4352.2  400.85  4914.3  401.93
  4924.3   399.6  4931.9   388.2  4934.4   387.7  4956.9   388.2  4964.5  398.62
  4999.8  401.25  5290.7  401.12  5727.3  401.41  5741.9  398.31  5748.1  390.39
  5762.7  389.91  5768.9  398.17  5777.3   397.9  5783.5   402.4    6296  401.66
  6541.7  402.47  7208.4  404.33  7381.6  406.09  7711.9  419.97  7819.2  420.79
#Mann= 8 ,-1 , 0
  2614.2     .05       0  4931.9     .07       0  4956.9     .05       0
  5290.7     .05       0    6296     .12       0  6541.7     .05       0
  7208.4     .12       0  7381.6     .05       0
Bank Sta=4931.9,4956.9
XS Rating Curve= 0 ,0
Exp/Cntr=0.3,0.1

Type RM Length L Ch R = 1 ,10117   ,1337,1337,1337
BEGIN DESCRIPTION:
Allen Creek 4.0
END DESCRIPTION:
XS GIS Cut Line= 3
      2716125.98        6913161.      2713231.65      6912958.68
        2711352.      6913418.18
#Sta/Elev= 30
  2098.6  421.87  2359.2   419.3  2730.1  404.32  3050.9  399.87    3322  400.89
  3371.7  400.01  3381.7  396.27  3391.7  400.78  3562.1  399.47  3582.2  395.53
  3605.8  395.37  3622.3  399.73  3762.6   400.3  4889.1  400.22  4965.6  400.62
  4991.9  395.98  5005.8  395.23  5015.7  386.48  5018.7  385.98  5046.7  386.48
    5047  397.06  5057.3  400.92  5072.1  400.69  5192.9  399.53  5211.7  397.72
  5232.3  400.17  5327.9   398.5  5874.4     401  6337.6  420.42    6935  423.24
#Mann= 7 ,-1 , 0
  2098.6     .05       0  4889.1     .12       0  4991.9     .05       0
  5015.7     .07       0  5046.7     .05       0  5072.1     .12       0
  5192.9     .05       0
Bank Sta=5015.7,5046.7
XS Rating Curve= 0 ,0
Exp/Cntr=0.3,0.1

Type RM Length L Ch R = 1 ,8780    ,1795,1795,1795
BEGIN DESCRIPTION:
Allen Creek 2.0
END DESCRIPTION:
XS GIS Cut Line= 3
      2716506.05      6912213.75        2713076.        6911911.
      2711039.19      6912712.16
#Sta/Elev= 30
  1555.5  420.98  2017.3  413.08  2057.5  415.87  2087.6  412.99  2212.7  413.27
  2218.1   415.5  2238.2  412.47  2910.8  396.53  3402.7   399.5  3432.8  395.56
  3452.9  399.51  3834.4  396.12  4409.4  398.13  4508.6  396.41  4537.1  394.35
  4622.9  398.62  4890.1  399.26  4988.8  399.39  4996.4  393.65  5001.6  393.65
  5004.9  385.65  5007.9  385.05  5035.9  385.65  5038.2  399.44  5039.1  399.46
  5371.3  398.49  5723.5  403.93  6041.2  418.14  6363.6  421.97  7187.6  422.02
#Mann= 9 ,-1 , 0
  1555.5     .05       0  4409.4     .12       0  4508.6      .1       0
  4622.9     .12       0  4890.1      .1       0  5004.9     .07       0
  5035.9      .1       0  5039.1     .12       0  5371.3     .05       0
Bank Sta=5004.9,5035.9
XS Rating Curve= 0 ,0
Exp/Cntr=0.3,0.1

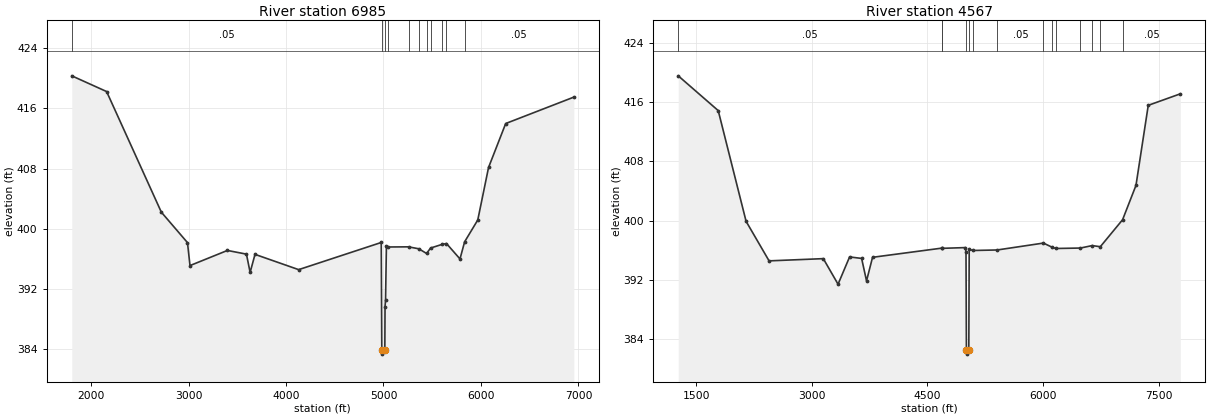
Type RM Length L Ch R = 1 ,6985    ,2418,2418,2418
BEGIN DESCRIPTION:
Mapping XS e6ae4396
END DESCRIPTION:
XS GIS Cut Line= 3
      2716333.45      6911877.14      2713267.36      6910805.37
      2711625.81      6911768.59
#Sta/Elev= 30
  1801.8  420.32  2159.3  418.23  2720.7   402.2    2989  398.15  3014.8   395.1
  3398.7  397.11    3594  396.62  3631.7  394.19  3681.8  396.59  4129.6  394.56
  4977.1  398.17  4982.8  383.93  4985.8  383.33  5013.8  383.93  5015.9  389.65
  5021.2  390.55  5030.1  397.71  5042.6  397.57  5256.7  397.59  5362.7  397.33
    5442  396.71  5483.2  397.43  5599.6  397.91  5646.3  398.03  5784.9  395.98
  5832.5  398.26  5967.4  401.16    6078  408.14  6253.9  413.98  6953.1  417.49
#Mann= 11 ,-1 , 0
  1801.8     .05       0  4982.8     .04       0  5013.8     .05       0
  5042.6      .1       0  5256.7     .12       0  5362.7      .1       0
    5442     .12       0  5483.2      .1       0  5599.6     .12       0
  5646.3      .1       0  5832.5     .05       0
Bank Sta=4982.8,5013.8
XS Rating Curve= 0 ,0
Exp/Cntr=0.3,0.1

Type RM Length L Ch R = 1 ,4567    ,0,0,0
BEGIN DESCRIPTION:
Allen Creek 1.0
END DESCRIPTION:
XS GIS Cut Line= 4
      2716256.49      6911540.99        2713701.        6909386.
        2713151.        6909236.      2711764.34      6911432.49
#Sta/Elev= 30
  1268.2  419.53  1786.7  414.84  2148.2   399.9  2446.1  394.57  3149.4  394.87
  3340.6  391.42  3490.1   395.1  3646.2   394.9  3709.9  391.87  3787.9  395.05
  4687.3  396.29  4688.2  396.26  4992.8  396.36  4999.7  395.71    5005  382.59
    5008  381.99    5036  382.59  5041.2  396.11  5093.8  395.97  5404.6  396.04
  6003.8  396.97  6117.9   396.4  6166.1  396.24  6483.4   396.3  6635.8  396.63
  6741.4  396.48  7030.2  400.12  7203.8  404.75    7363  415.55  7778.7   417.1
#Mann= 14 ,-1 , 0
  1268.2     .05       0  4687.3     .12       0  4688.2      .1       0
    5005     .07       0    5036      .1       0  5093.8     .12       0
  5404.6     .05       0  6003.8     .12       0  6117.9      .1       0
  6166.1     .12       0  6483.4      .1       0  6635.8     .12       0
  6741.4      .1       0  7030.2     .05       0
Bank Sta=5005,5036
XS Rating Curve= 0 ,0
Exp/Cntr=0.3,0.1

Chan Stop Cuts=-1
Use User Specified Reach Order=0
Composite Channel Slope=5