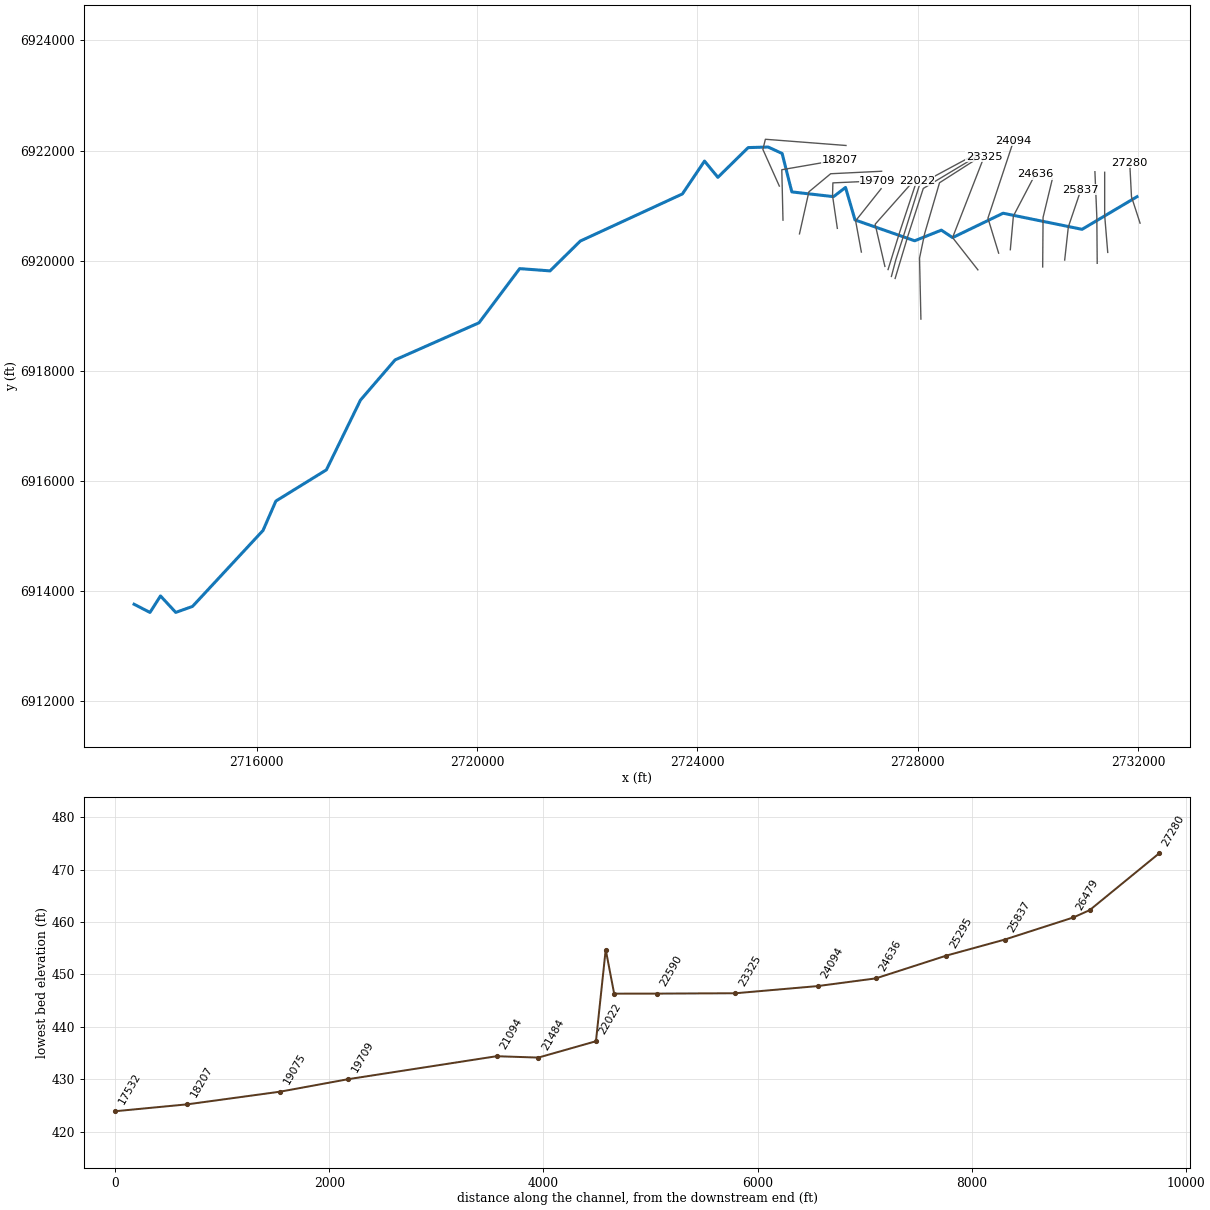
--- Allen T1.prj (project) ---

Proj Title=Allen T1 Base Level Engineering
Current Plan=p01
Default Exp/Contr=0.3,0.1
English Units
Geom File=g01
Flow File=f01
Plan File=p01
Y Axis Title=Elevation
X Axis Title(PF)=Main Channel Distance
X Axis Title(XS)=Station
BEGIN DESCRIPTION:
Allen T1
END DESCRIPTION:
DSS Export Rating Curves= 0
DSS Export Rating Curve Sorted= 0
DSS Export Volume Flow Curves= 0
DXF OffsetX= 0
DXF OffsetY= 0
DXF ScaleX= 1
DXF ScaleY= 10

--- Allen T1.p01 (plan) ---

Plan Title=Multiple Run
Short Identifier=Multiple
Geom File=g01
Flow File=f01
Subcritical Flow
K Sum by GR= 0
Std Step Tol= 0.01
Critical Tol= 0.01
Num of Std Step Trials= 20
Max Error Tol= 0.3
Flow Tol Ratio= 0.001
Split Flow NTrial= 30
Split Flow Tol= 0.02
Split Flow Ratio= 0.02
Log Output Level= 0
Friction Slope Method= 1
Unsteady Friction Slope Method= 2
Unsteady Bridges Friction Slope Method= 1
Parabolic Critical Depth
Global Vel Dist=  1 , 1 , 1
Global Log Level= 0
CheckData=True
Encroach Param= -1, 0, 0, 0
BEGIN DESCRIPTION:
Multiple Run
END DESCRIPTION:

--- Allen T1.f01 (steady flow) ---

Flow Title=Multiple
Program Version=4.10
Number of Profiles= 7
Profile Names=10-year,25-year,50-year,1pct_min,100-year,1pct_plu,500-year
River Rch & RM=Allen T1,Reach-1         ,27280
     590     784     939     559    1115    2225    1568
River Rch & RM=Allen T1,Reach-1         ,22113
     893    1214    1477     891    1777    3546    2570
Boundary for River Rch & Prof#=Allen T1,Reach-1         , 1
Up Type= 0
Dn Type= 3
Dn Slope=0.0029
Boundary for River Rch & Prof#=Allen T1,Reach-1         , 2
Up Type= 0
Dn Type= 3
Dn Slope=0.0029
Boundary for River Rch & Prof#=Allen T1,Reach-1         , 3
Up Type= 0
Dn Type= 3
Dn Slope=0.0029
Boundary for River Rch & Prof#=Allen T1,Reach-1         , 4
Up Type= 0
Dn Type= 3
Dn Slope=0.0029
Boundary for River Rch & Prof#=Allen T1,Reach-1         , 5
Up Type= 0
Dn Type= 3
Dn Slope=0.0029
Boundary for River Rch & Prof#=Allen T1,Reach-1         , 6
Up Type= 0
Dn Type= 3
Dn Slope=0.0029
Boundary for River Rch & Prof#=Allen T1,Reach-1         , 7
Up Type= 0
Dn Type= 3
Dn Slope=0.0029
DSS Import GetInterval= 0
DSS Import GetPeak= 0
DSS Import FillOption= 0

--- Allen T1.g01 (geometry) ---

Geom Title=Existing Conditions
Program Version=4.10

River Reach=Allen T1        ,Reach-1
Reach XY= 30
        2731976.        6921161.      2730979.41      6920568.77
      2729546.21      6920861.21      2728629.34       6920418.6
       2728425.9      6920553.72      2727941.36       6920360.9
      2726858.84      6920739.32      2726686.74      6921329.29
      2726468.67      6921162.08      2725711.97      6921248.25
      2725536.28      6921945.51      2725282.58      6922062.96
      2724919.92      6922052.85      2724370.28      6921512.88
      2724127.68      6921807.92        2723726.        6921211.
      2721873.29       6920355.6      2721324.36      6919814.13
      2720773.42      6919855.29      2720035.68      6918871.78
      2718512.26       6918197.8      2717883.86      6917467.19
      2717265.57      6916201.19      2716348.86      6915634.53
      2716115.65      6915100.88      2714836.42      6913721.75
      2714532.03      6913612.62      2714255.53      6913911.69
      2714064.26        6913612.        2713776.        6913761.

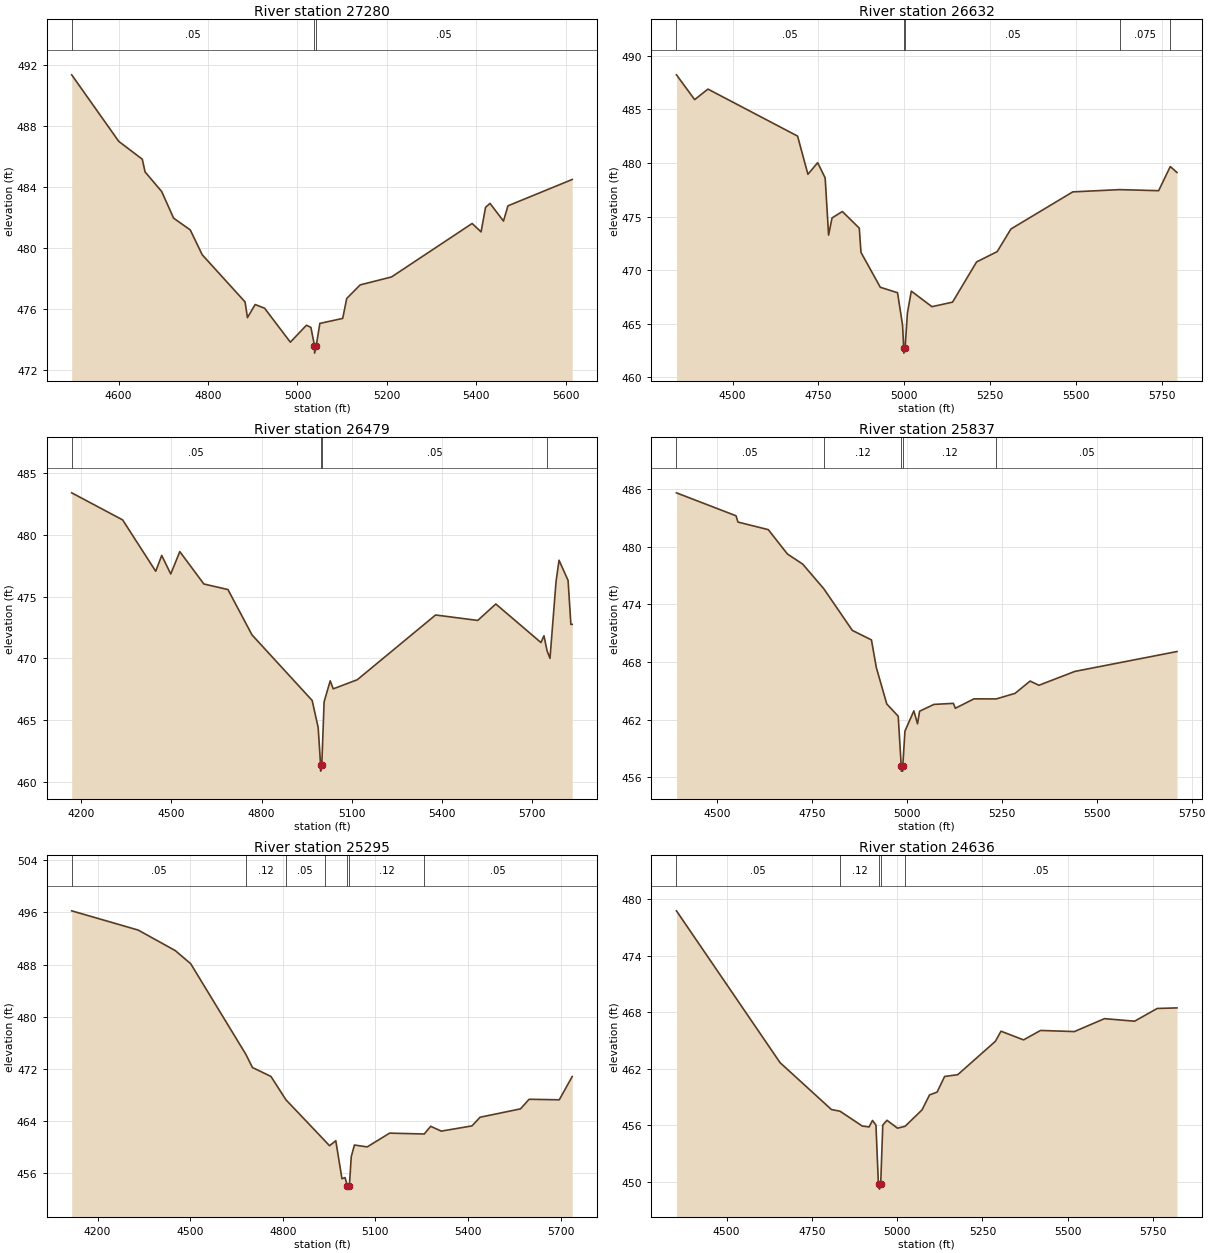
Type RM Length L Ch R = 1 ,27280   ,648,648,648
BEGIN DESCRIPTION:
Allen T1 15.0
END DESCRIPTION:
XS GIS Cut Line= 3
      2732031.88       6920680.8        2731876.        6921161.
      2731844.38      6921774.52
#Sta/Elev= 30
  4495.1  491.37  4600.4     487    4653  485.83  4659.1     485  4696.3  483.71
    4723  481.96  4760.2  481.19  4786.9  479.56  4882.8  476.46  4888.1  475.43
  4905.3  476.29  4926.4  476.05    4984  473.82    5020  474.93    5030  474.79
    5038   473.6  5038.3   473.1    5042   473.6    5050  475.05  5101.1  475.38
  5110.1  476.69  5140.2  477.58  5210.2   478.1  5390.5  481.61  5410.5  481.06
  5420.5  482.67  5430.5  482.93  5460.6  481.77  5470.6  482.77  5614.3   484.5
#Mann= 3 ,-1 , 0
  4495.1     .05       0    5038     .04       0    5042     .05       0
Bank Sta=5038,5042
XS Rating Curve= 0 ,0
Exp/Cntr=0.3,0.1

Type RM Length L Ch R = 1 ,26632   ,153,153,153
BEGIN DESCRIPTION:
Mapping XS e35fc3b8
END DESCRIPTION:
XS GIS Cut Line= 3
      2731445.07       6920149.6      2731389.51      6920823.17
      2731389.51      6921604.41
#Sta/Elev= 30
  4336.8  488.21  4389.8   485.9  4428.5  486.88  4689.4   482.5  4719.5  478.94
  4747.9  480.02  4769.7   478.6  4779.7  473.27  4789.7  474.87  4819.8  475.47
    4869  473.92    4874  471.66  4930.2  468.41  4980.4   467.9    4995  464.88
  4998.4  462.77  4998.7  462.27  5002.4  462.77  5009.1     466  5020.5  468.05
  5080.5   466.6  5140.5  467.02  5210.5  470.77  5270.5  471.73  5310.5  473.84
  5490.5   477.3  5627.1  477.51  5740.5  477.41  5774.4  479.66  5793.9  479.11
#Mann= 5 ,-1 , 0
  4336.8     .05       0  4998.4     .04       0  5002.4     .05       0
  5627.1    .075       0  5774.4     .05       0
Bank Sta=4998.4,5002.4
XS Rating Curve= 0 ,0
Exp/Cntr=0.3,0.1

Type RM Length L Ch R = 1 ,26479   ,642,642,642
BEGIN DESCRIPTION:
Mapping XS f315237c
END DESCRIPTION:
XS GIS Cut Line= 3
       2731254.1      6919951.66      2731247.15       6920795.4
      2731212.43       6921614.8
#Sta/Elev= 30
  4168.8   483.4  4338.1  481.21  4448.1  477.05  4468.1  478.33  4498.1  476.83
  4528.2  478.64  4608.2  476.02  4688.2  475.57  4768.2   471.9  4968.2  466.59
  4988.2   464.4  4996.2  461.37  4996.4  460.87  5000.2  461.37  5007.9  466.48
  5028.2  468.18  5038.2  467.53  5118.3  468.27  5378.5  473.51  5518.6  473.07
  5578.7   474.4  5728.8  471.28  5738.8  471.83  5749.2   470.6  5758.8     470
  5778.9  476.21  5788.9  477.94  5818.9  476.31  5828.3  472.75  5832.7  472.75
#Mann= 4 ,-1 , 0
  4168.8     .05       0  4996.2     .05       0  5000.2     .05       0
  5749.2    .075       0
Bank Sta=4996.2,5000.2
XS Rating Curve= 0 ,0
Exp/Cntr=0.3,0.1

Type RM Length L Ch R = 1 ,25837   ,542,542,542
BEGIN DESCRIPTION:
Mapping XS 77184f4e
END DESCRIPTION:
XS GIS Cut Line= 3
      2730663.81      6920010.64      2730729.79      6920611.37
      2730958.55      6921287.26
#Sta/Elev= 30
  4393.5  485.59  4550.4   483.2  4555.4  482.55  4635.3  481.76  4685.6  479.23
  4725.8  478.18  4781.3  475.62  4856.6  471.28  4906.9  470.29  4919.7  467.43
  4947.2  463.63  4977.4  462.35  4985.4  457.14  4985.7  456.64  4989.2  456.64
  4989.4  457.14  4995.1   460.8  5018.6  462.91  5028.3  461.56  5033.6  462.87
  5071.4  463.58  5122.6  463.69  5127.9  463.18  5176.9  464.16  5235.5  464.15
  5285.1  464.73  5324.7  466.01  5347.9  465.57  5442.2  467.01  5711.4  469.08
#Mann= 5 ,-1 , 0
  4393.5     .05       0  4781.3     .12       0  4985.4     .07       0
  4989.4     .12       0  5235.5     .05       0
Bank Sta=4985.4,4989.4
XS Rating Curve= 0 ,0
Exp/Cntr=0.3,0.1

Type RM Length L Ch R = 1 ,25295   ,659,659,659
BEGIN DESCRIPTION:
Mapping XS c276fc73
END DESCRIPTION:
XS GIS Cut Line= 3
      2730264.51      6919885.66      2730271.46      6920784.98
      2730440.83      6921486.68
#Sta/Elev= 30
  4116.3  496.25  4331.7   493.3  4451.7  490.16  4501.7  488.15  4680.4  474.26
  4701.7  472.24  4761.7  470.87  4810.1   467.3  4935.8  461.04  4951.5  460.25
  4971.7  461.02  4991.7  455.19  5001.7  455.37  5009.2   454.1  5009.4   453.6
  5013.2   454.1  5015.7   454.1  5021.8  458.57  5032.1  460.36  5073.3  460.07
    5146  462.18  5258.3  462.05    5279  463.23  5313.5  462.49  5412.8  463.29
  5439.2  464.62    5570   465.9  5597.9  467.37  5695.6  467.29  5737.5  470.86
#Mann= 7 ,-1 , 0
  4116.3     .05       0  4680.4     .12       0  4810.1     .05       0
  4935.8     .12       0  5009.2     .07       0  5013.2     .12       0
  5258.3     .05       0
Bank Sta=5009.2,5013.2
XS Rating Curve= 0 ,0
Exp/Cntr=0.3,0.1

Type RM Length L Ch R = 1 ,24636   ,542,542,542
BEGIN DESCRIPTION:
Mapping XS bd94d030
END DESCRIPTION:
XS GIS Cut Line= 3
      2729677.25      6920198.55      2729732.81      6920809.66
      2730128.49      6921566.31
#Sta/Elev= 30
  4352.9  478.75  4656.6  462.66  4807.2  457.69  4832.4  457.51  4897.6  455.94
  4917.7  455.84  4927.7  456.53  4937.8  456.04  4944.7  450.03  4947.7  449.75
  4947.9  449.25  4951.7  449.75  4957.8  456.03  4970.1  456.55    5001  455.71
  5023.3  455.91  5072.9  457.65    5095  459.24    5117  459.53  5139.1  461.19
  5177.6  461.38    5288  464.92  5304.4  465.99  5370.6  465.07  5420.4  466.07
  5519.5  465.95  5607.8  467.32  5696.1  467.05  5762.4   468.4  5820.4  468.46
#Mann= 5 ,-1 , 0
  4352.9     .05       0  4832.4     .12       0  4947.7     .07       0
  4951.7     .12       0  5023.3     .05       0
Bank Sta=4947.7,4951.7
XS Rating Curve= 0 ,0
Exp/Cntr=0.3,0.1

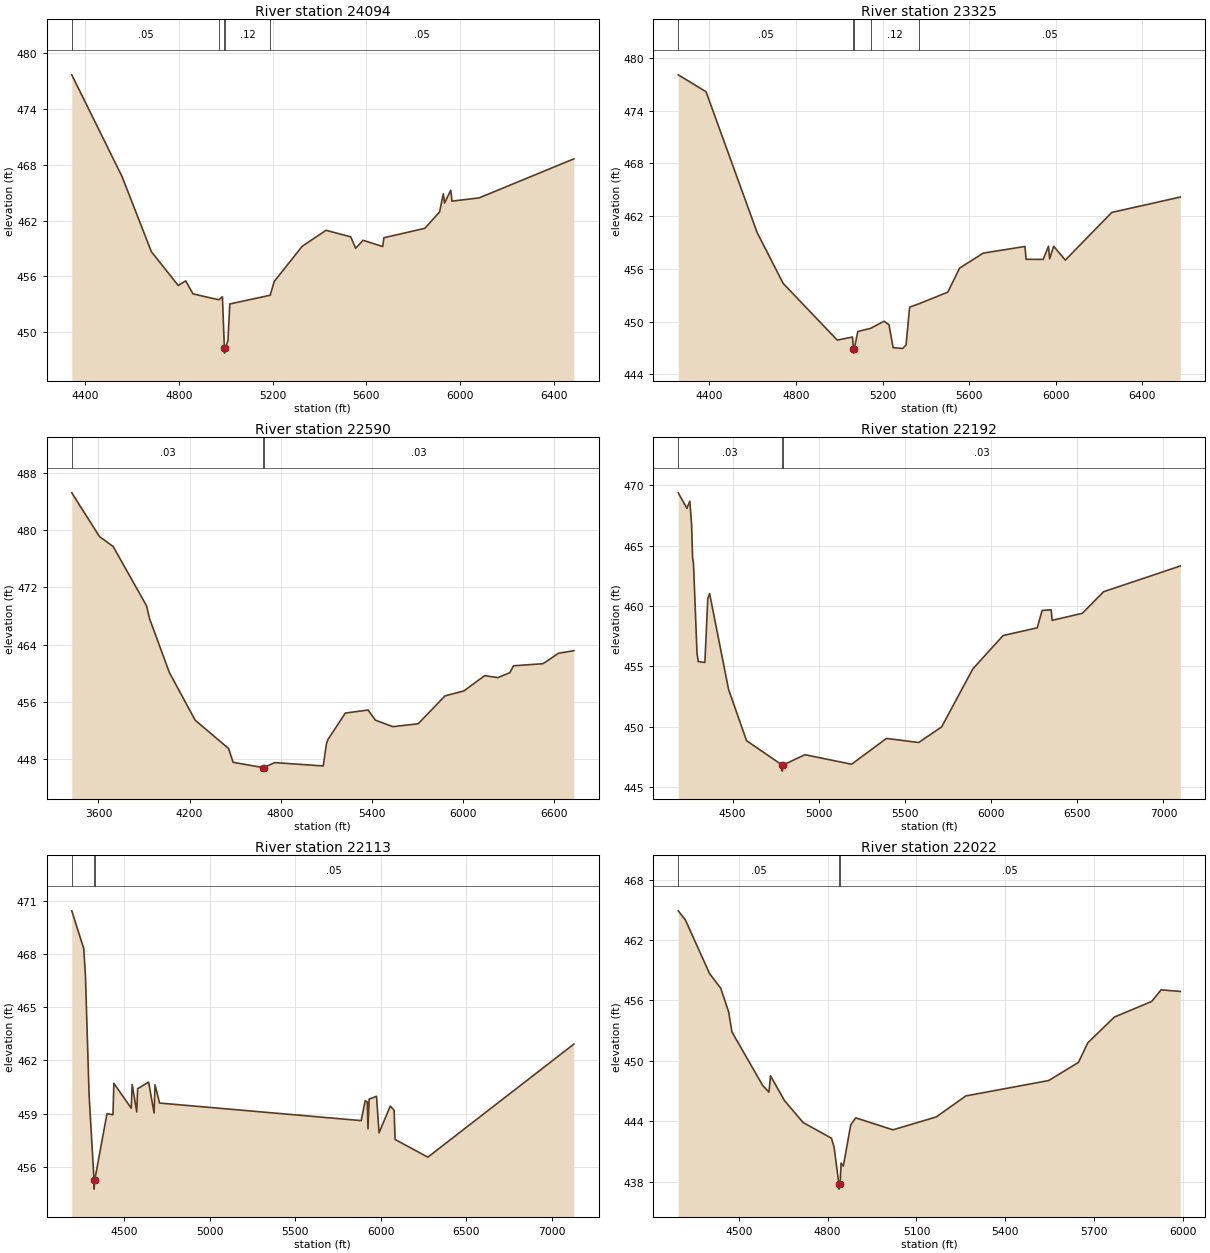
Type RM Length L Ch R = 1 ,24094   ,769,769,769
BEGIN DESCRIPTION:
Mapping XS 599b686b
END DESCRIPTION:
XS GIS Cut Line= 3
      2729465.43      6920136.09        2729271.      6920771.47
      2729736.23      6922175.12
#Sta/Elev= 30
  4342.5  477.62  4556.8  466.73  4682.3  458.66    4797  455.03  4828.7  455.53
  4860.1  454.13  4970.6   453.5  4985.6  453.83    4994  448.28  4994.3  447.78
    4998  448.28  5009.3  449.16    5017  453.05  5189.6  453.99  5206.6  455.46
  5326.3  459.24  5427.9  460.95  5533.2  460.25  5554.3  459.02  5585.9  459.88
  5669.7  459.21  5674.9  460.15  5849.3  461.16  5912.5  462.91  5928.5  464.85
  5933.8  463.87  5960.2  465.24  5965.5  464.08    6081  464.42  6485.7  468.61
#Mann= 5 ,-1 , 0
  4342.5     .05       0  4970.6     .12       0    4994     .07       0
    4998     .12       0  5189.6     .05       0
Bank Sta=4994,4998
XS Rating Curve= 0 ,0
Exp/Cntr=0.3,0.1

Type RM Length L Ch R = 1 ,23325   ,735,735,735
BEGIN DESCRIPTION:
Mapping XS 1c48ddc6
END DESCRIPTION:
XS GIS Cut Line= 3
      2729088.69      6919832.95      2728629.34       6920418.6
      2729200.99      6921885.98
#Sta/Elev= 30
  4255.7  478.06  4384.1  476.14    4620  460.13  4740.3  454.34  4990.3  447.89
  5060.6  448.24    5065  446.91  5065.2  446.41    5069  446.91  5085.1  448.87
  5144.4  449.23  5206.5  450.04  5229.1  449.64  5248.3  447.03  5292.3  446.94
    5308  447.34  5324.5  451.64  5369.7  452.04    5501  453.35  5555.4  456.08
  5664.2  457.78  5857.2  458.54  5862.5  457.08  5941.4  457.07  5965.9  458.56
  5971.3  457.14  5989.9  458.56  6043.6  456.99  6258.2  462.41  6574.8  464.16
#Mann= 5 ,-1 , 0
  4255.7     .05       0    5065     .03       0    5069     .05       0
  5144.4     .12       0  5369.7     .05       0
Bank Sta=5065,5069
XS Rating Curve= 0 ,0
Exp/Cntr=0.3,0.1

Type RM Length L Ch R = 1 ,22590   ,398,398,398
BEGIN DESCRIPTION:
Mapping XS 2d7f438d
END DESCRIPTION:
XS GIS Cut Line= 5
      2728054.79       6918938.7      2728029.68      6920046.47
      2728123.43      6920494.38      2728392.29      6921414.37
      2729050.97      6921835.98
#Sta/Elev= 30
  3424.3   485.2  3606.6   479.1  3696.7  477.71  3916.7  469.43  3936.7  467.62
  4066.8  460.12  4236.8  453.45  4456.9   449.5  4486.9  447.57  4683.2  446.84
  4683.4  446.34  4687.2  446.84  4761.7  447.53  5080.2  447.06    5101  450.14
  5111.5  450.76  5225.8  454.45  5375.3  454.87    5424  453.45  5538.6  452.55
  5705.3  452.95  5882.4  456.85  6006.7  457.54  6142.9  459.67  6230.8   459.4
  6309.4  460.09  6332.8  461.05  6527.6  461.34  6629.6   462.8  6730.5  463.16
#Mann= 3 ,-1 , 0
  3424.3     .03       0  4683.2     .03       0  4687.2     .03       0
Bank Sta=4683.2,4687.2
XS Rating Curve= 0 ,0
Exp/Cntr=0.3,0.1

Type RM Length L Ch R = 1 ,22192   ,79,79,79
BEGIN DESCRIPTION:
Mapping XS 7d8d1c83
END DESCRIPTION:
XS GIS Cut Line= 4
      2727586.96      6919676.63      2727821.35      6920457.93
      2728097.75      6921310.94      2729127.55      6921929.56
#Sta/Elev= 30
  4184.2  469.38  4234.4   468.1  4251.4  468.69  4261.8  466.73  4267.5  464.01
  4272.7  463.53  4293.2  456.09  4300.5   455.4  4338.8  455.33  4355.8  460.64
  4366.2  461.04  4476.3   453.1  4580.7  448.85  4787.5  446.83  4787.7  446.33
  4791.5  446.83  4919.6  447.69  5190.2   446.9  5392.7  449.04  5579.4   448.7
  5712.6  449.99    5894   454.8  6069.5  457.56  6267.8   458.2  6295.9  459.64
  6348.4  459.69  6354.2  458.82  6529.1   459.4  6652.8  461.19  7097.9  463.32
#Mann= 3 ,-1 , 0
  4184.2     .03       0  4787.5     .03       0  4791.5     .03       0
Bank Sta=4787.5,4791.5
XS Rating Curve= 0 ,0
Exp/Cntr=0.3,0.1

Type RM Length L Ch R = 1 ,22113   ,91,91,91
BEGIN DESCRIPTION:
Mapping XS f719e317
END DESCRIPTION:
XS GIS Cut Line= 6
      2727519.28      6919713.17        2727600.      6920017.82
      2727751.04      6920486.57      2728024.47      6921361.57
      2728122.96       6921435.8       2729080.8      6921952.24
#Sta/Elev= 30
  4192.7  470.43  4262.9   468.3  4272.8  466.75  4293.9  460.07  4322.9  455.25
  4323.2  454.75  4326.9  455.25  4398.6     459  4433.6  458.94  4438.8  460.71
  4540.6  459.31  4545.9  460.65  4572.7   459.1  4577.9  460.41    4642  460.78
  4674.1  459.04  4679.4  460.63  4706.2   459.6    5885  458.61  5908.4  459.73
  5920.8  459.66  5924.8  458.15  5931.5  459.82  5974.8  459.98  5989.4  457.92
  6055.2  459.43  6077.6  459.19  6083.3  457.55  6274.7  456.55  7128.6  462.92
#Mann= 3 ,-1 , 0
  4192.7     .05       0  4322.9     .04       0  4326.9     .05       0
Bank Sta=4322.9,4326.9
XS Rating Curve= 0 ,0
Exp/Cntr=0.3,0.1

Type RM Length L Ch R = 1 ,22022   ,538,538,538
BEGIN DESCRIPTION:
Mapping XS ae411dec
END DESCRIPTION:
XS GIS Cut Line= 3
      2727458.52      6919838.18      2727672.04      6920525.63
      2727979.32      6921452.68
#Sta/Elev= 30
  4295.1   464.9    4319  464.01  4401.1  458.66  4438.9   457.2  4465.6  454.84
  4476.7  452.86  4580.8  447.53  4601.7  446.89  4606.9   448.5  4654.1  446.05
  4716.9  443.87  4812.8  442.31  4821.6  441.43  4838.1  437.75  4838.3  437.25
  4842.1  437.75  4845.3  439.84    4853  439.54  4877.9  443.63  4894.9  444.33
  5020.6  443.14  5166.7  444.42    5267  446.51    5547  448.04  5647.4  449.84
  5679.1  451.79  5768.6  454.34    5895   455.9  5926.6  457.05  5991.6  456.89
#Mann= 3 ,-1 , 0
  4295.1     .05       0  4838.1     .04       0  4842.1     .05       0
Bank Sta=4838.1,4842.1
XS Rating Curve= 0 ,0
Exp/Cntr=0.3,0.1

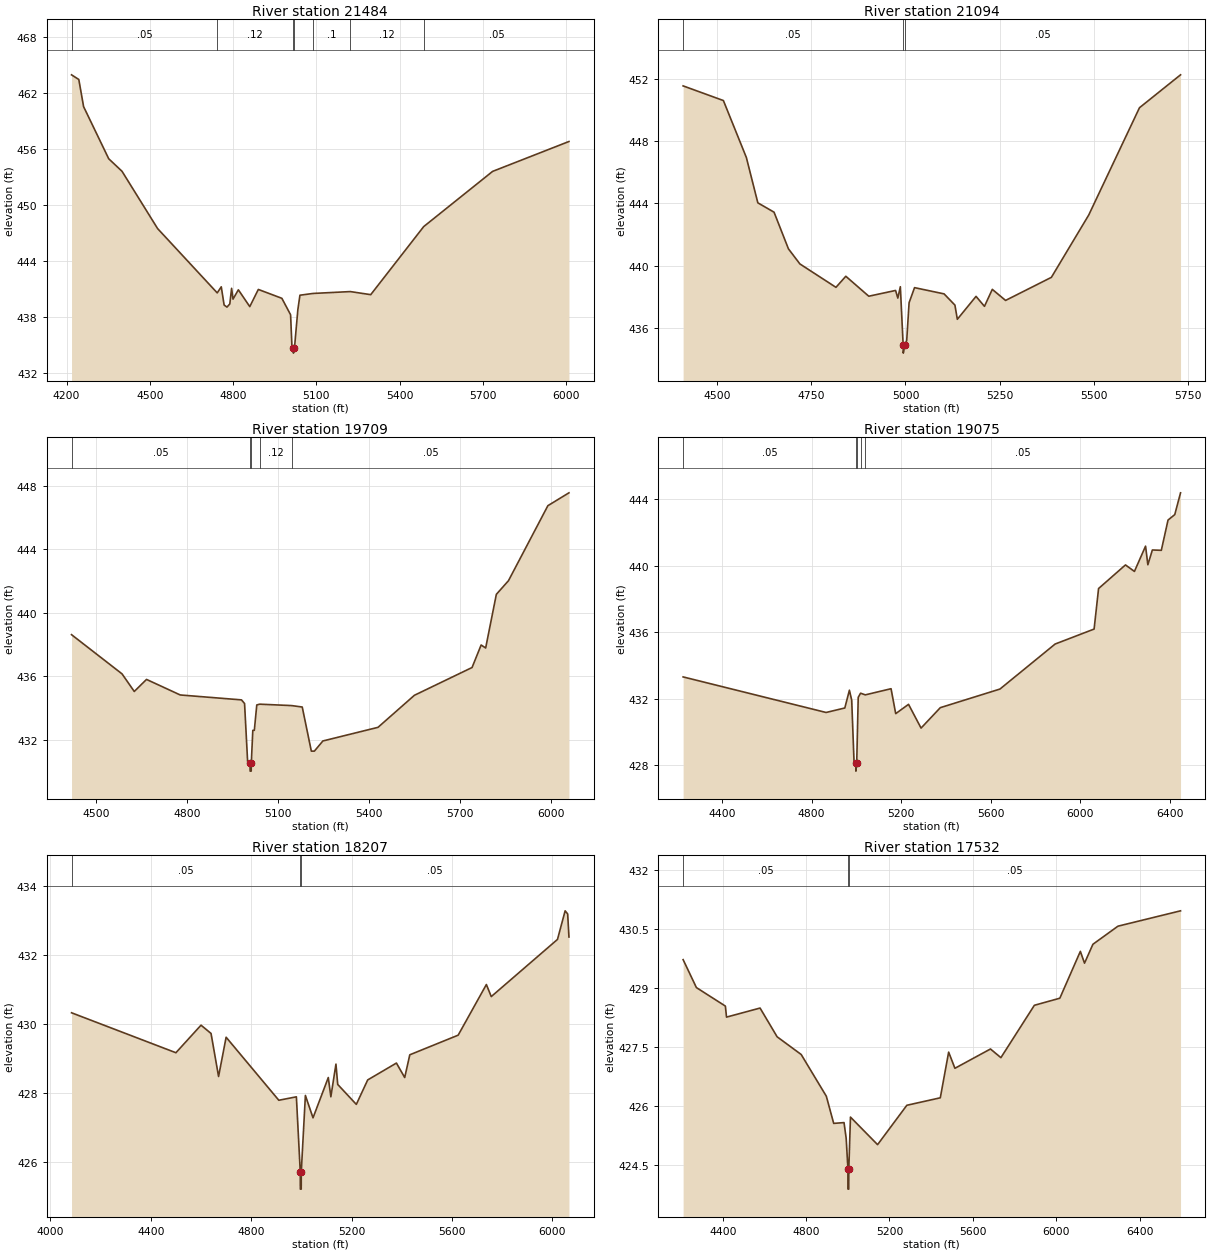
Type RM Length L Ch R = 1 ,21484   ,390,390,390
BEGIN DESCRIPTION:
Mapping XS 319e2ac6
END DESCRIPTION:
XS GIS Cut Line= 3
      2727401.21      6919895.43      2727224.13      6920661.05
      2727891.76      6921413.67
#Sta/Elev= 30
  4218.1  463.93  4244.3  463.43  4261.6  460.52  4352.1  454.94    4400   453.6
  4528.1  447.47  4742.9  440.58  4757.5  441.23  4767.8  439.28  4778.1  439.06
  4788.3   439.4  4794.7  441.07  4799.8  439.91  4819.1  440.91  4860.2  439.11
    4891  440.95  4975.8     440  5007.2  438.24  5012.4  434.64  5017.1  434.63
  5017.4  434.13  5021.1  434.63  5033.3  438.76  5040.9  440.33    5088  440.52
  5222.3  440.72  5295.9  440.39  5486.8  447.68    5735  453.59    6010  456.79
#Mann= 7 ,-1 , 0
  4218.1     .05       0  4742.9     .12       0  5017.1     .07       0
  5021.1     .12       0    5088      .1       0  5222.3     .12       0
  5486.8     .05       0
Bank Sta=5017.1,5021.1
XS Rating Curve= 0 ,0
Exp/Cntr=0.3,0.1

Type RM Length L Ch R = 1 ,21094   ,1385,1385,1385
BEGIN DESCRIPTION:
Mapping XS 6141de3c
END DESCRIPTION:
XS GIS Cut Line= 3
      2726974.13       6920155.8      2726869.96      6920723.55
      2727333.12      6921306.41
#Sta/Elev= 30
  4409.2  451.53  4516.2  450.59  4577.2  446.94  4607.7  444.03  4650.8  443.43
    4689  441.08  4719.5  440.11  4815.3  438.61  4841.5  439.32  4902.5  438.04
  4973.7  438.41  4979.7  437.92  4986.4  438.65  4993.9  434.89  4994.2  434.39
  4997.9  434.89  5003.3   435.2  5009.6  437.62  5024.1  438.59  5102.6  438.19
  5131.4  437.47  5137.8  436.56  5187.5  438.03  5209.9  437.39  5230.7  438.48
    5266  437.77  5387.7  439.25    5487  443.25  5621.8  450.13  5730.9  452.24
#Mann= 3 ,-1 , 0
  4409.2     .05       0  4993.9     .04       0  4997.9     .05       0
Bank Sta=4993.9,4997.9
XS Rating Curve= 0 ,0
Exp/Cntr=0.3,0.1

Type RM Length L Ch R = 1 ,19709   ,634,634,634
BEGIN DESCRIPTION:
Mapping XS 286b1435
END DESCRIPTION:
XS GIS Cut Line= 4
      2726538.22       6920586.2      2726451.04      6921179.85
      2726457.32      6921412.05       2727265.4      6921448.33
#Sta/Elev= 30
  4418.3  438.61  4584.9  436.14  4625.3  435.03  4665.7  435.79  4776.9  434.81
  4979.1   434.5  4989.2  434.27  4999.3  430.61  5007.4  430.51  5007.6  430.01
  5011.1  430.01  5011.4  430.51  5016.4  432.58  5021.4  432.58  5029.5  434.18
  5039.1  434.23  5144.9  434.14  5179.5  434.05  5209.5  431.27  5219.5  431.27
  5247.6  431.91  5429.5  432.77  5549.6  434.79  5739.8  436.54  5769.8  437.96
  5784.7  437.77  5819.9  441.15  5859.9  442.01    5990  446.74  6059.5  447.55
#Mann= 5 ,-1 , 0
  4418.3     .05       0  5007.4     .04       0  5011.4     .05       0
  5039.1     .12       0  5144.9     .05       0
Bank Sta=5007.4,5011.4
XS Rating Curve= 0 ,0
Exp/Cntr=0.3,0.1

Type RM Length L Ch R = 1 ,19075   ,868,868,868
BEGIN DESCRIPTION:
Mapping XS a0995822
END DESCRIPTION:
XS GIS Cut Line= 4
      2725850.99      6920485.95      2726021.51      6921249.44
      2726416.73      6921577.96      2727341.78      6921623.45
#Sta/Elev= 30
  4225.7   433.3  4864.5  431.16  4948.1  431.43  4968.6   432.5  4978.9   431.9
  4989.1  428.27  4997.3  428.13  4997.6  427.63  5001.3  428.13    5008  432.07
  5018.5  432.32  5039.7  432.22  5154.7  432.59  5175.5  431.09  5232.8  431.65
  5288.8  430.22  5374.8  431.45  5641.3  432.57  5887.9  435.28  6061.9  436.18
  6081.9  438.62    6202  440.04  6242.1  439.65  6291.8  441.17  6302.1  440.05
  6322.2  440.94  6362.2  440.92  6392.2  442.74  6422.3  443.07  6448.1  444.38
#Mann= 5 ,-1 , 0
  4225.7     .05       0  4997.3     .04       0  5001.3     .05       0
  5018.5     .12       0  5039.7     .05       0
Bank Sta=4997.3,5001.3
XS Rating Curve= 0 ,0
Exp/Cntr=0.3,0.1

Type RM Length L Ch R = 1 ,18207   ,675,675,675
BEGIN DESCRIPTION:
Mapping XS abdb4d24
END DESCRIPTION:
XS GIS Cut Line= 3
      2725551.73      6920735.12      2725530.35      6921650.97
      2726581.01       6921832.9
#Sta/Elev= 30
  4083.9  430.33  4499.9  429.17  4599.9  429.97  4639.9  429.73  4669.9  428.48
    4700  429.62    4910  427.79    4980  427.89  4995.5  425.71  4995.8  425.21
  4999.3  425.21  4999.5  425.71  5015.9  427.93  5046.3  427.28  5107.2  428.45
  5117.4  427.89  5137.7  428.84  5144.7  428.25  5218.9  427.67  5264.2  428.38
  5378.7  428.87  5411.7  428.45    5432  429.11  5624.8  429.68  5737.2  431.15
  5756.7   430.8  6020.6  432.46  6051.1  433.29  6061.2   433.2  6066.3  432.53
#Mann= 3 ,-1 , 0
  4083.9     .05       0  4995.5     .04       0  4999.5     .05       0
Bank Sta=4995.5,4999.5
XS Rating Curve= 0 ,0
Exp/Cntr=0.3,0.1

Type RM Length L Ch R = 1 ,17532   ,0,0,0
BEGIN DESCRIPTION:
Allen T1 1.0
END DESCRIPTION:
XS GIS Cut Line= 4
      2725485.35      6921354.09      2725186.94      6922019.47
      2725232.45      6922204.11       2726695.3      6922091.18
#Sta/Elev= 30
  4210.1  429.72  4273.8  429.01  4412.8  428.54  4418.3  428.26  4579.3  428.49
  4661.1  427.76  4776.6  427.31  4897.2  426.25  4932.5  425.56  4982.1  425.58
  4992.4  425.18    5001  424.39  5001.2  423.89  5004.7  423.89    5005  424.39
    5013  425.72  5143.1  425.02  5283.5  426.02    5444  426.21  5484.1  427.37
  5514.2  426.96  5684.7  427.45  5734.8  427.23  5895.3  428.56  6017.5  428.74
    6116  429.93    6136  429.63  6176.2  430.11  6296.5  430.57  6596.7  430.96
#Mann= 3 ,-1 , 0
  4210.1     .05       0    5001     .04       0    5005     .05       0
Bank Sta=5001,5005
XS Rating Curve= 0 ,0
Exp/Cntr=0.3,0.1

Chan Stop Cuts=-1
Use User Specified Reach Order=0
Composite Channel Slope=5