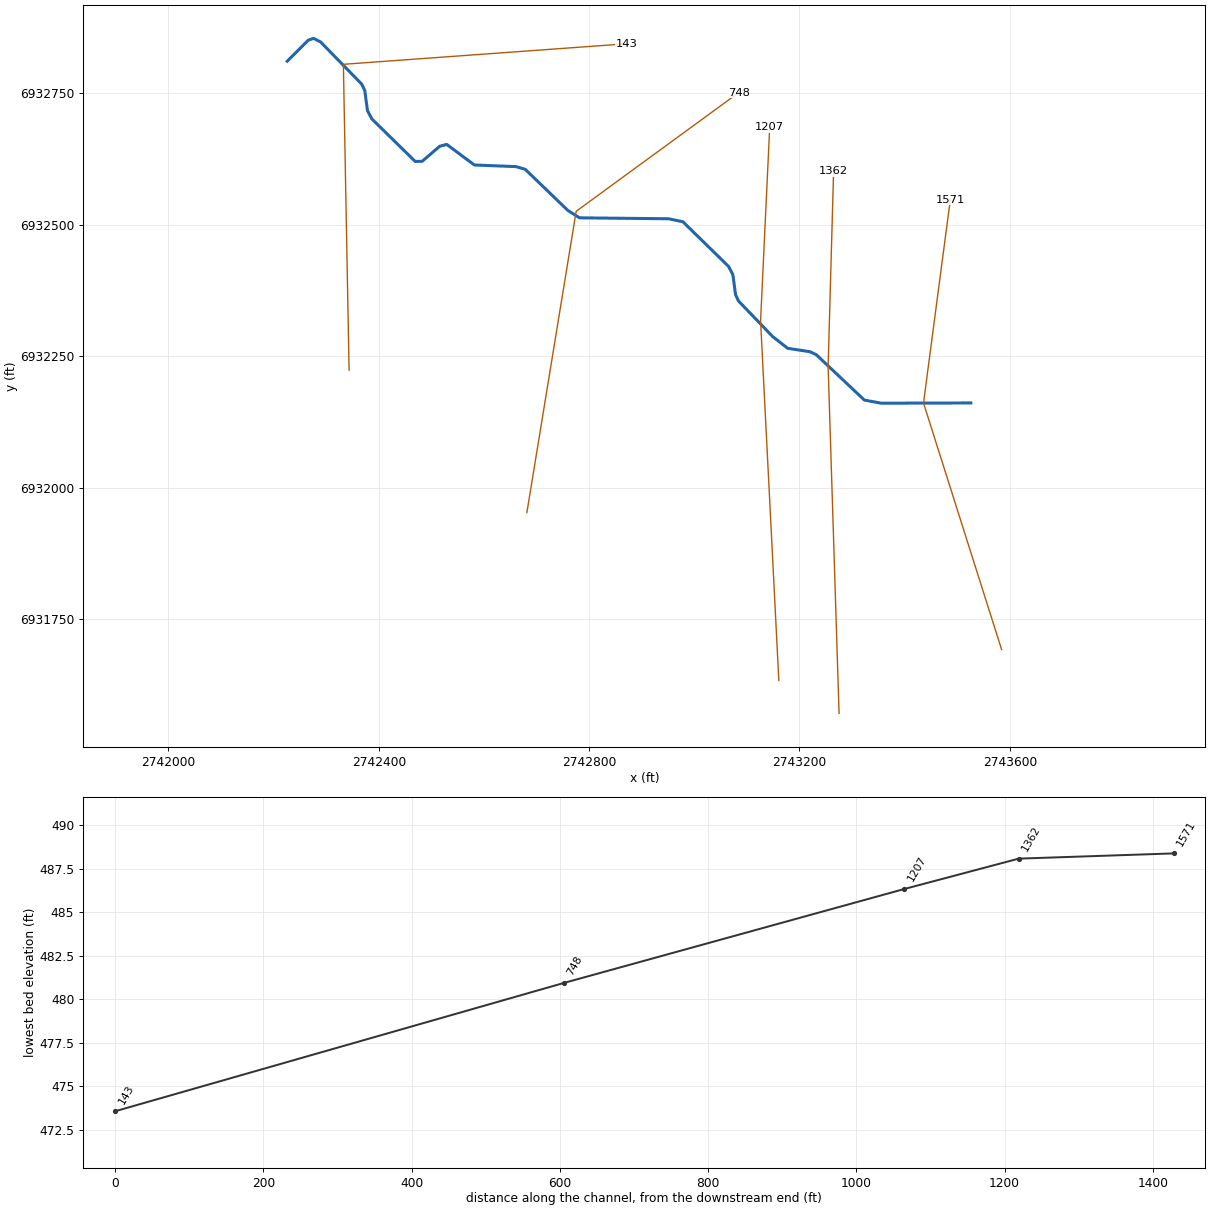
--- Allen T10.prj (project) ---

Proj Title=Allen T10 Base Level Engineering
Current Plan=p01
Default Exp/Contr=0.3,0.1
English Units
Geom File=g01
Flow File=f01
Plan File=p01
BEGIN DESCRIPTION:
Allen T10
END DESCRIPTION:

--- Allen T10.p01 (plan) ---

Plan Title=Multiple Run
Short Identifier=Multiple
Geom File=g01
Flow File=f01
Subcritical Flow
K Sum by GR= 0
Std Step Tol= 0.01
Critical Tol= 0.01
Num of Std Step Trials= 20
Max Error Tol= 0.3
Flow Tol Ratio= 0.001
Split Flow NTrial= 30
Split Flow Tol= 0.02
Split Flow Ratio= 0.02
Log Output Level= 0
Friction Slope Method= 1
Unsteady Friction Slope Method= 2
Unsteady Bridges Friction Slope Method= 1
Parabolic Critical Depth
Global Vel Dist=  1 , 1 , 1
Global Log Level= 0
CheckData=True
Encroach Param= -1, 0, 0, 0
BEGIN DESCRIPTION:
Multiple Run
END DESCRIPTION:

--- Allen T10.f01 (steady flow) ---

Flow Title=Multiple
Number of Profiles=7
Profile Names=10-year,25-year,50-year,1pct_min,100-year,1pct_plu,500-year
River Rch & RM= Allen T10,Reach-1,1571
     221     281     327     190     379     756     509
Boundary for River Rch & Prof#=Allen T10,Reach-1,1
Up Type=0
Dn Type=3
Dn Slope=0.005
Boundary for River Rch & Prof#=Allen T10,Reach-1,2
Up Type=0
Dn Type=3
Dn Slope=0.005
Boundary for River Rch & Prof#=Allen T10,Reach-1,3
Up Type=0
Dn Type=3
Dn Slope=0.005
Boundary for River Rch & Prof#=Allen T10,Reach-1,4
Up Type=0
Dn Type=3
Dn Slope=0.005
Boundary for River Rch & Prof#=Allen T10,Reach-1,5
Up Type=0
Dn Type=3
Dn Slope=0.005
Boundary for River Rch & Prof#=Allen T10,Reach-1,6
Up Type=0
Dn Type=3
Dn Slope=0.005
Boundary for River Rch & Prof#=Allen T10,Reach-1,7
Up Type=0
Dn Type=3
Dn Slope=0.005

--- Allen T10.g01 (geometry) ---

Geom Title=Existing Conditions

River Reach=Allen T10,Reach-1
Reach XY= 30
      2743526.00      6932161.00      2743355.82      6932160.55
      2743323.55      6932166.47      2743232.04      6932252.82
      2743219.94      6932258.46      2743177.64      6932264.97
      2743149.12      6932287.27      2743084.15      6932354.94
      2743078.53      6932367.04      2743073.47      6932404.96
      2743065.23      6932420.70      2742978.47      6932505.55
      2742951.12      6932511.29      2742781.86      6932513.07
      2742759.25      6932527.47      2742678.42      6932605.46
      2742660.78      6932610.48      2742581.89      6932613.55
      2742529.22      6932652.71      2742515.94      6932649.15
      2742482.65      6932620.60      2742469.31      6932620.29
      2742386.78      6932701.28      2742378.53      6932717.03
      2742373.47      6932754.96      2742367.84      6932767.08
      2742289.37      6932847.58      2742276.01      6932854.43
      2742266.01      6932850.90      2742226.00      6932811.00

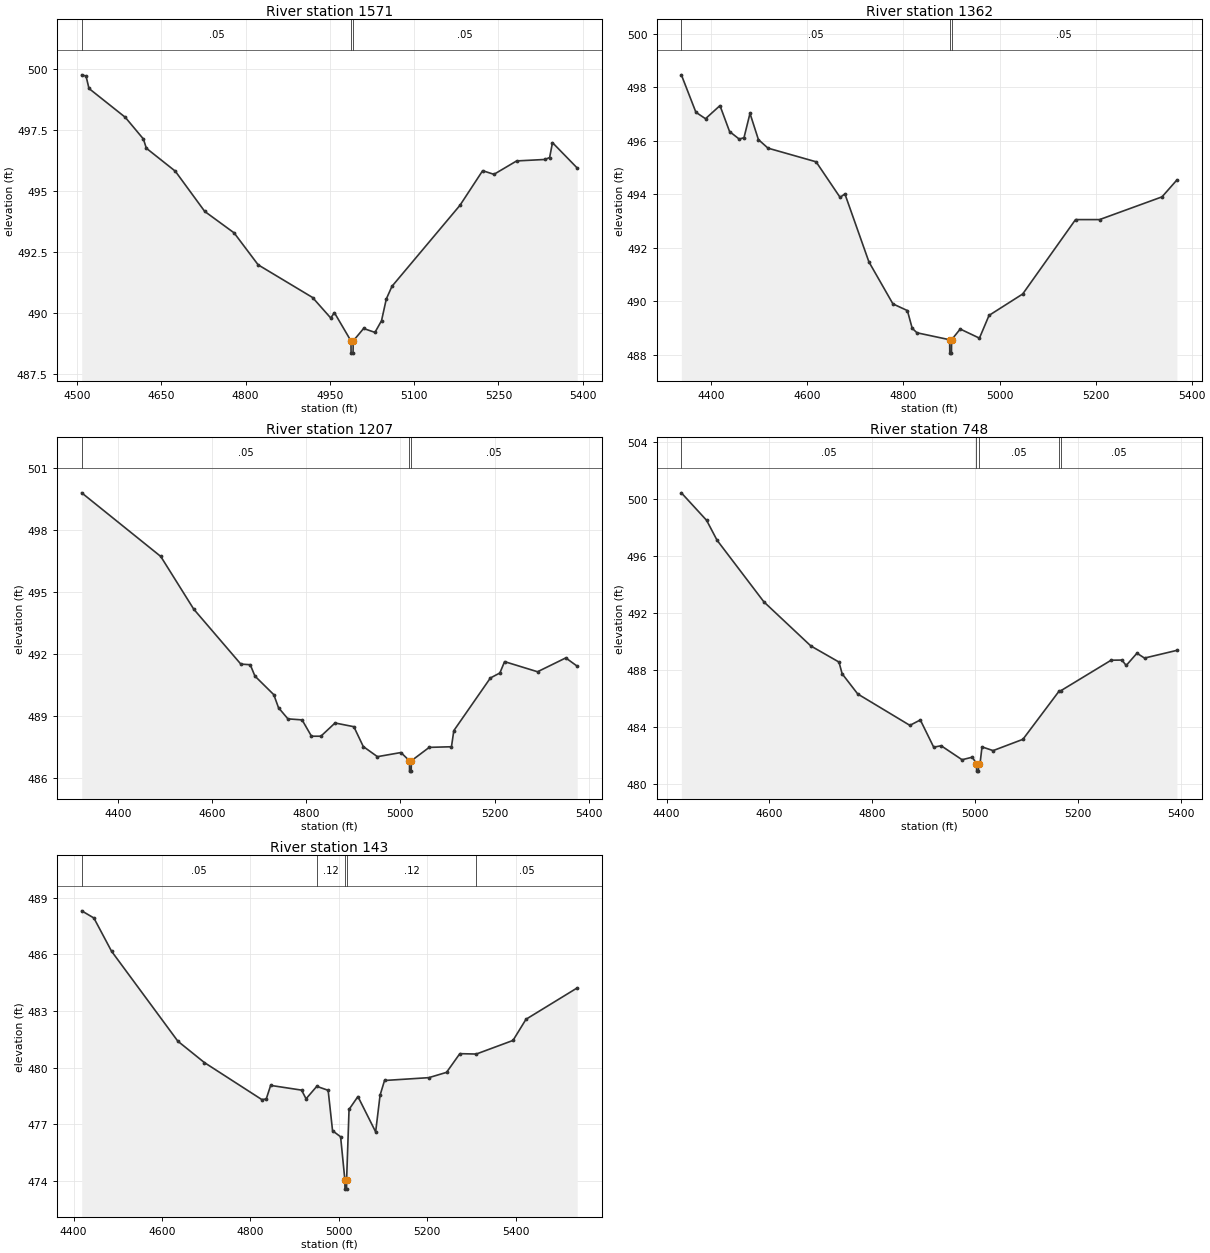
Type RM Length L Ch R = 1,1571,209,209,209
BEGIN DESCRIPTION:
Allen T10 2.0
END DESCRIPTION:
XS GIS Cut Line= 3
      2743584.45      6931692.19      2743435.97      6932160.94
      2743486.99      6932547.89
#Sta/Elev= 30
  4508.3  499.78  4516.0  499.73  4521.3  499.22  4585.8  498.04  4618.1  497.15
  4623.4  496.77  4674.9  495.83  4727.3  494.18  4779.6  493.30  4822.4  491.99
  4919.3  490.65  4951.6  489.81  4958.1  490.03  4987.6  488.87  4987.8  488.37
  4991.3  488.37  4991.6  488.87  5010.1  489.38  5030.3  489.22  5042.0  489.70
  5050.5  490.59  5060.6  491.11  5181.6  494.43  5222.0  495.85  5242.1  495.70
  5282.5  496.25  5332.9  496.31  5341.2  496.39  5346.3  497.00  5390.3  495.96
#Mann=3,-1,0
  4508.3    0.05       0  4987.6    0.04       0  4991.6    0.05       0
Bank Sta=4987.6,4991.6
Exp/Cntr=0.3,0.1

Type RM Length L Ch R = 1,1362,155,155,155
BEGIN DESCRIPTION:
Mapping XS 909c7d88
END DESCRIPTION:
XS GIS Cut Line= 3
      2743275.43      6931570.68      2743254.60      6932230.35
      2743265.02      6932601.90
#Sta/Elev= 30
  4337.6  498.47  4367.9  497.07  4387.9  496.83  4418.0  497.32  4438.0  496.35
  4458.0  496.07  4468.0  496.12  4480.5  497.03  4498.0  496.05  4518.0  495.73
  4618.1  495.22  4668.1  493.89  4678.1  494.02  4728.1  491.48  4778.1  489.91
  4808.2  489.66  4818.2  489.00  4828.2  488.83  4896.2  488.57  4896.5  488.07
  4900.0  488.07  4900.2  488.57  4918.2  488.97  4958.2  488.63  4978.2  489.48
  5048.3  490.28  5158.3  493.06  5208.3  493.06  5338.4  493.91  5369.3  494.54
#Mann=3,-1,0
  4337.6    0.05       0  4896.2    0.05       0  4900.2    0.05       0
Bank Sta=4896.2,4900.2
Exp/Cntr=0.3,0.1

Type RM Length L Ch R = 1,1207,459,459,459
BEGIN DESCRIPTION:
Mapping XS 5630381e
END DESCRIPTION:
XS GIS Cut Line= 3
      2743160.85      6931633.14      2743126.13      6932317.16
      2743143.49      6932685.25
#Sta/Elev= 30
  4322.4  499.79  4490.5  496.71  4560.6  494.16  4660.7  491.50  4680.7  491.47
  4690.7  490.92  4730.8  490.02  4740.8  489.39  4760.8  488.85  4790.9  488.80
  4810.9  488.01  4830.9  488.01  4861.0  488.65  4901.0  488.47  4921.0  487.51
  4951.1  487.02  5001.1  487.22  5019.2  486.82  5019.4  486.32  5022.9  486.32
  5023.2  486.82  5061.2  487.47  5108.5  487.50  5113.5  488.28  5191.3  490.83
  5211.4  491.07  5221.4  491.62  5291.5  491.13  5351.5  491.80  5375.8  491.40
#Mann=3,-1,0
  4322.4    0.05       0  5019.2    0.05       0  5023.2    0.05       0
Bank Sta=5019.2,5023.2
Exp/Cntr=0.3,0.1

Type RM Length L Ch R = 1,748,605,605,605
BEGIN DESCRIPTION:
Mapping XS 85401a96
END DESCRIPTION:
XS GIS Cut Line= 3
      2742681.69      6931952.59      2742775.43      6932525.49
      2743084.47      6932751.19
#Sta/Elev= 30
  4428.8  500.45  4477.9  498.52  4498.1  497.13  4589.3  492.80  4680.5  489.71
  4735.2  488.58  4741.3  487.76  4771.7  486.34  4873.0  484.14  4893.3  484.52
  4919.3  482.61  4933.8  482.71  4974.4  481.73  4994.6  481.91  5002.5  481.43
  5002.8  480.93  5006.3  480.93  5006.5  481.43  5009.3  481.43  5013.2  482.63
  5034.8  482.37  5092.7  483.16  5163.2  486.55  5166.0  486.56  5264.2  488.71
  5285.1  488.72  5293.5  488.34  5314.4  489.20  5329.1  488.86  5392.0  489.40
#Mann=5,-1,0
  4428.8    0.05       0  5002.5    0.04       0  5006.5    0.05       0
  5163.2    0.12       0  5166.0    0.05       0
Bank Sta=5002.5,5006.5
Exp/Cntr=0.3,0.1

Type RM Length L Ch R = 1,143,0,0,0
BEGIN DESCRIPTION:
Allen T10 1.0
END DESCRIPTION:
XS GIS Cut Line= 3
      2742343.58      6932223.44      2742332.72      6932805.04
      2742870.90      6932844.07
#Sta/Elev= 30
  4418.3  488.30  4445.9  487.92  4485.9  486.16  4635.9  481.40  4695.9  480.27
  4825.9  478.31  4835.9  478.34  4845.9  479.06  4915.9  478.81  4926.0  478.35
  4950.3  479.01  4976.0  478.80  4986.0  476.66  5004.2  476.34  5013.8  474.07
  5014.1  473.57  5017.6  473.57  5017.8  474.07  5023.3  477.79  5043.4  478.47
  5083.5  476.60  5093.5  478.54  5103.6  479.32  5203.8  479.47  5243.9  479.75
  5274.0  480.74  5311.2  480.72  5394.3  481.44  5423.7  482.56  5539.6  484.22
#Mann=5,-1,0
  4418.3    0.05       0  4950.3    0.12       0  5013.8    0.07       0
  5017.8    0.12       0  5311.2    0.05       0
Bank Sta=5013.8,5017.8
Exp/Cntr=0.3,0.1

Chan Stop Cuts=-1