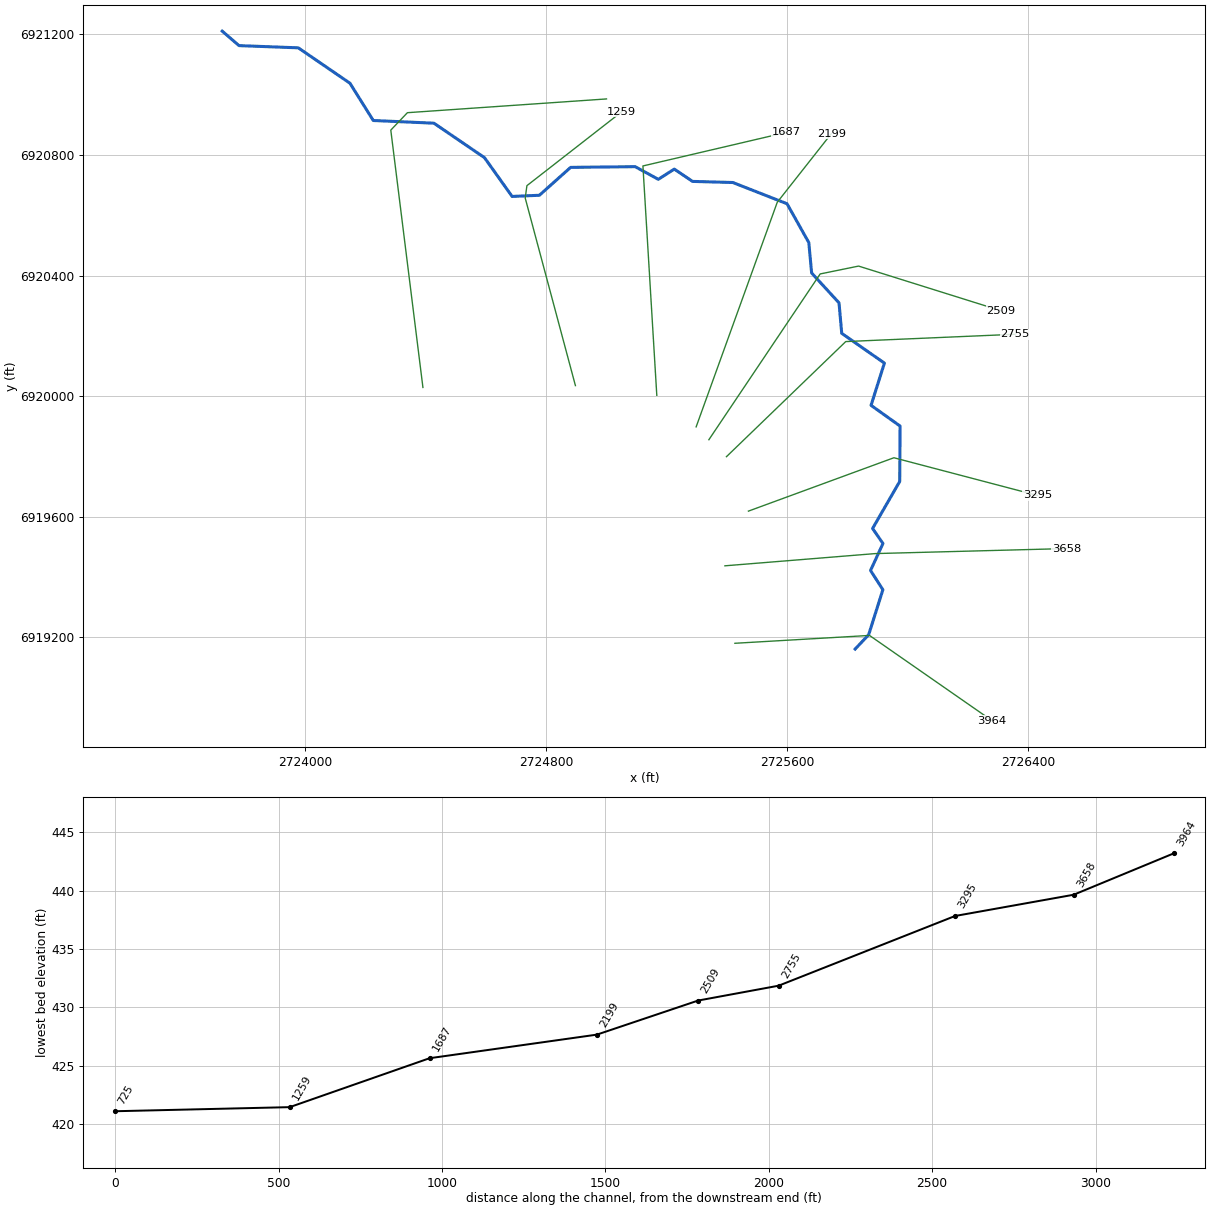
--- Allen T1_1.prj (project) ---

Proj Title=Allen T1_1 Base Level Engineering
Current Plan=p01
Default Exp/Contr=0.3,0.1
English Units
Geom File=g01
Flow File=f01
Plan File=p01
Y Axis Title=Elevation
X Axis Title(PF)=Main Channel Distance
X Axis Title(XS)=Station
BEGIN DESCRIPTION:
Allen T1_1
END DESCRIPTION:
DSS Export Rating Curves= 0
DSS Export Rating Curve Sorted= 0
DSS Export Volume Flow Curves= 0
DXF OffsetX= 0
DXF OffsetY= 0
DXF ScaleX= 1
DXF ScaleY= 10

--- Allen T1_1.p01 (plan) ---

Plan Title=Multiple Run
Short Identifier=Multiple
Geom File=g01
Flow File=f01
Subcritical Flow
K Sum by GR= 0
Std Step Tol= 0.01
Critical Tol= 0.01
Num of Std Step Trials= 20
Max Error Tol= 0.3
Flow Tol Ratio= 0.001
Split Flow NTrial= 30
Split Flow Tol= 0.02
Split Flow Ratio= 0.02
Log Output Level= 0
Friction Slope Method= 1
Unsteady Friction Slope Method= 2
Unsteady Bridges Friction Slope Method= 1
Parabolic Critical Depth
Global Vel Dist=  1 , 1 , 1
Global Log Level= 0
CheckData=True
Encroach Param= -1, 0, 0, 0
BEGIN DESCRIPTION:
Multiple Run
END DESCRIPTION:

--- Allen T1_1.f01 (steady flow) ---

Flow Title=Multiple
Number of Profiles=7
Profile Names=10-year,25-year,50-year,1pct_min,100-year,1pct_plu,500-year
River Rch & RM= Allen T1_1,Reach-1,3964
     171     209     237     134     267     533     338
Boundary for River Rch & Prof#=Allen T1_1,Reach-1,1
Up Type=0
Dn Type=3
Dn Slope=0.005
Boundary for River Rch & Prof#=Allen T1_1,Reach-1,2
Up Type=0
Dn Type=3
Dn Slope=0.005
Boundary for River Rch & Prof#=Allen T1_1,Reach-1,3
Up Type=0
Dn Type=3
Dn Slope=0.005
Boundary for River Rch & Prof#=Allen T1_1,Reach-1,4
Up Type=0
Dn Type=3
Dn Slope=0.005
Boundary for River Rch & Prof#=Allen T1_1,Reach-1,5
Up Type=0
Dn Type=3
Dn Slope=0.005
Boundary for River Rch & Prof#=Allen T1_1,Reach-1,6
Up Type=0
Dn Type=3
Dn Slope=0.005
Boundary for River Rch & Prof#=Allen T1_1,Reach-1,7
Up Type=0
Dn Type=3
Dn Slope=0.005

--- Allen T1_1.g01 (geometry) ---

Geom Title=Existing Conditions

River Reach=Allen T1_1,Reach-1
Reach XY= 30
      2725826.00      6919161.00      2725870.78      6919208.45
      2725917.90      6919357.71      2725876.98      6919421.64
      2725918.17      6919511.08      2725883.76      6919560.92
      2725973.76      6919716.93      2725974.99      6919900.71
      2725878.66      6919969.49      2725922.96      6920109.58
      2725781.42      6920208.33      2725772.37      6920309.50
      2725681.54      6920408.58      2725672.17      6920509.42
      2725599.90      6920638.28      2725420.06      6920708.73
      2725286.44      6920712.39      2725225.90      6920753.21
      2725172.78      6920719.28      2725096.18      6920761.29
      2724881.86      6920758.93      2724778.36      6920666.39
      2724687.88      6920662.51      2724596.13      6920791.22
      2724428.45      6920905.53      2724227.25      6920914.45
      2724149.83      6921038.13      2723978.45      6921155.53
      2723781.78      6921162.89      2723726.00      6921211.00

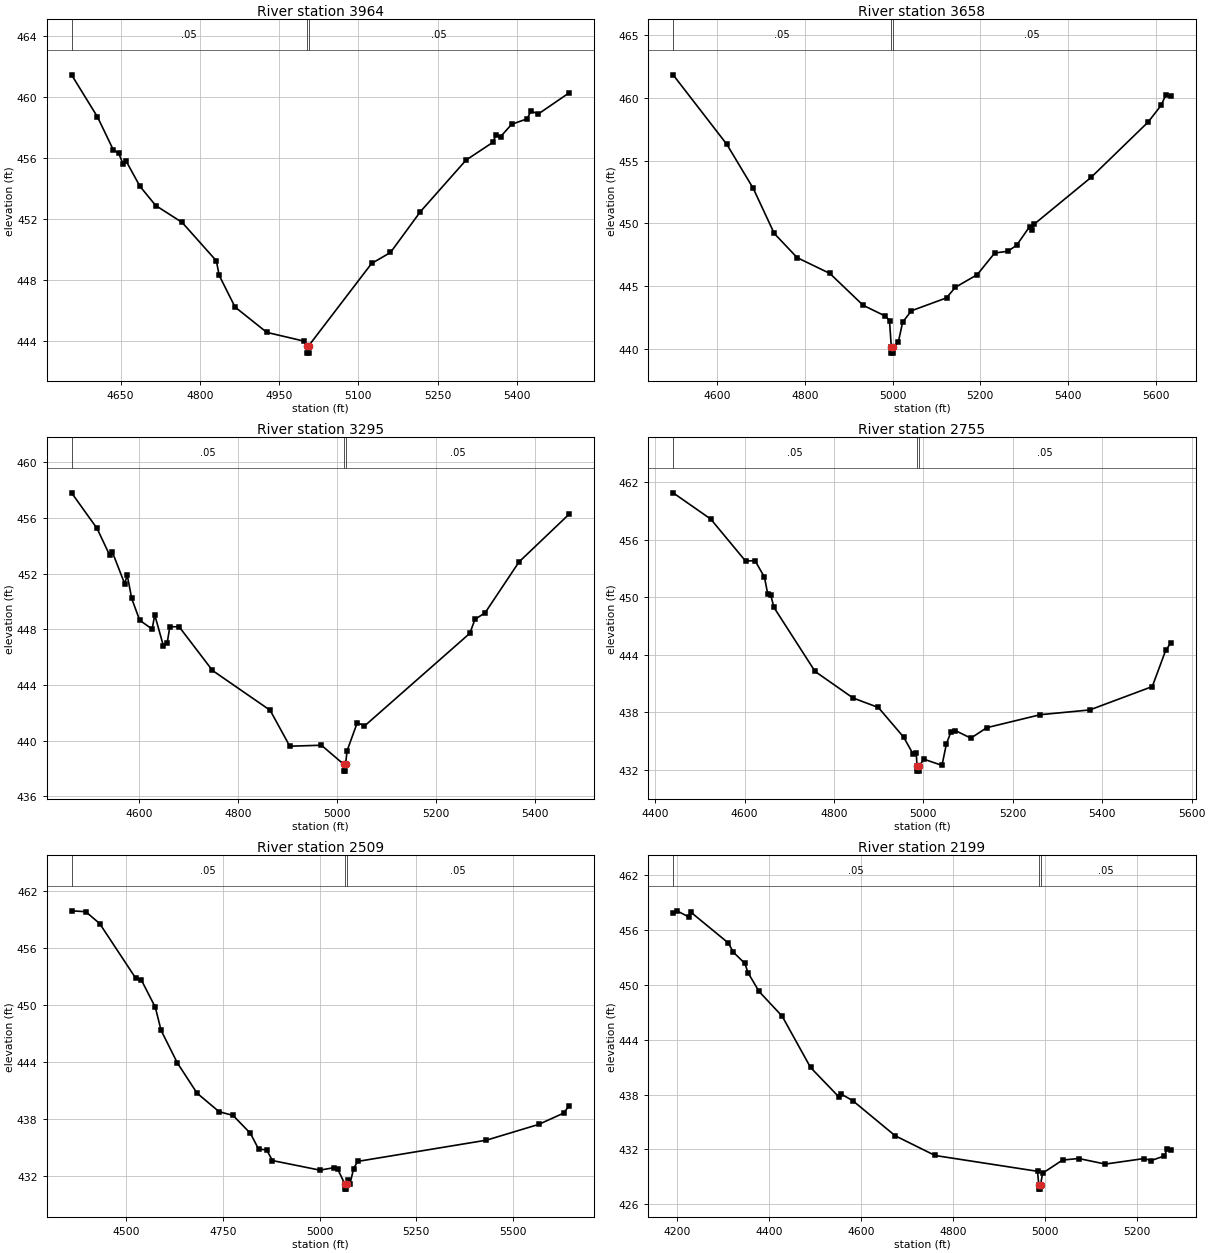
Type RM Length L Ch R = 1,3964,306,306,306
BEGIN DESCRIPTION:
Allen T1_1 2.0
END DESCRIPTION:
XS GIS Cut Line= 3
      2725426.96      6919180.06      2725873.56      6919206.10
      2726279.80      6918923.56
#Sta/Elev= 30
  4557.0  461.43  4606.1  458.67  4636.2  456.50  4646.2  456.28  4655.1  455.55
  4660.1  455.79  4686.3  454.13  4716.3  452.86  4766.4  451.75  4831.2  449.23
  4836.5  448.28  4866.6  446.20  4926.7  444.54  4996.8  443.97  5002.4  443.68
  5002.6  443.18  5006.1  443.18  5006.4  443.68  5125.1  449.06  5160.9  449.78
  5217.6  452.46  5304.0  455.84  5354.6  457.00  5360.7  457.48  5369.5  457.38
  5390.4  458.19  5420.1  458.55  5426.2  459.05  5441.1  458.87  5499.2  460.25
#Mann=3,-1,0
  4557.0    0.05       0  5002.4   0.035       0  5006.4    0.05       0
Bank Sta=5002.4,5006.4
Exp/Cntr=0.3,0.1

Type RM Length L Ch R = 1,3658,363,363,363
BEGIN DESCRIPTION:
Mapping XS f00d1d95
END DESCRIPTION:
XS GIS Cut Line= 3
      2725393.83      6919437.06      2725893.08      6919477.67
      2726527.57      6919494.35
#Sta/Elev= 30
  4499.1  461.85  4621.7  456.30  4681.9  452.79  4729.9  449.19  4782.2  447.26
  4856.7  446.00  4932.7  443.46  4983.6  442.59  4992.9  442.24  4997.0  440.14
  4997.2  439.64  5000.7  439.64  5001.0  440.14  5012.9  440.50  5022.9  442.11
  5042.9  443.02  5123.0  444.05  5143.0  444.89  5193.0  445.90  5233.0  447.63
  5263.0  447.77  5283.0  448.25  5312.4  449.72  5317.4  449.50  5323.0  449.93
  5453.1  453.67  5583.1  458.08  5613.1  459.43  5623.1  460.23  5634.7  460.13
#Mann=3,-1,0
  4499.1    0.05       0  4997.0   0.035       0  5001.0    0.05       0
Bank Sta=4997,5001
Exp/Cntr=0.3,0.1

Type RM Length L Ch R = 1,3295,540,540,540
BEGIN DESCRIPTION:
Mapping XS 63123878
END DESCRIPTION:
XS GIS Cut Line= 3
      2725471.81      6919618.51      2725954.47      6919795.60
      2726430.20      6919670.59
#Sta/Elev= 30
  4463.4  457.81  4515.0  455.25  4540.2  453.35  4545.5  453.59  4570.7  451.29
  4576.0  451.90  4585.0  450.22  4601.1  448.66  4626.3  448.02  4631.6  449.04
  4648.9  446.84  4656.8  447.04  4662.1  448.19  4680.9  448.19  4748.3  445.05
  4864.9  442.19  4904.6  439.61  4968.5  439.68  5013.3  438.32  5013.5  437.82
  5017.0  437.82  5017.3  438.32  5020.5  439.29  5041.1  441.31  5055.6  441.06
  5268.6  447.72  5278.9  448.72  5299.6  449.20  5368.1  452.85  5469.4  456.28
#Mann=3,-1,0
  4463.4    0.05       0  5013.3    0.04       0  5017.3    0.05       0
Bank Sta=5013.3,5017.3
Exp/Cntr=0.3,0.1

Type RM Length L Ch R = 1,2755,246,246,246
BEGIN DESCRIPTION:
Mapping XS d942f6dd
END DESCRIPTION:
XS GIS Cut Line= 3
      2725398.90      6919799.06      2725794.74      6920181.01
      2726357.24      6920205.32
#Sta/Elev= 30
  4440.1  460.88  4524.3  458.14  4602.2  453.76  4623.3  453.81  4644.5  452.07
  4651.6  450.36  4658.5  450.20  4665.7  448.92  4757.6  442.25  4842.5  439.48
  4899.1  438.49  4955.7  435.40  4977.0  433.62  4984.0  433.79  4985.6  432.35
  4985.8  431.85  4989.3  431.85  4989.6  432.35  5001.4  433.09  5041.5  432.45
  5051.5  434.71  5061.5  435.92  5071.5  436.08  5106.1  435.29  5141.6  436.38
  5261.7  437.74  5371.8  438.23  5511.9  440.67  5541.9  444.45  5553.2  445.21
#Mann=3,-1,0
  4440.1    0.05       0  4985.6    0.04       0  4989.6    0.05       0
Bank Sta=4985.6,4989.6
Exp/Cntr=0.3,0.1

Type RM Length L Ch R = 1,2509,310,310,310
BEGIN DESCRIPTION:
Mapping XS dfbec068
END DESCRIPTION:
XS GIS Cut Line= 4
      2725340.64      6919855.40      2725709.87      6920405.39
      2725837.36      6920431.47      2726309.75      6920283.47
#Sta/Elev= 30
  4358.3  459.91  4395.0  459.82  4431.0  458.57  4524.0  452.83  4539.0  452.61
  4575.0  449.75  4590.0  447.31  4632.1  443.88  4683.1  440.69  4740.1  438.74
  4776.1  438.35  4821.1  436.46  4842.1  434.81  4863.1  434.71  4878.1  433.59
  5001.1  432.58  5037.2  432.84  5047.4  432.66  5065.8  431.08  5066.1  430.58
  5069.6  430.58  5069.8  431.08  5073.3  431.49  5078.4  431.08  5088.2  432.74
  5098.4  433.50  5431.9  435.74  5567.0  437.40  5631.5  438.59  5645.9  439.37
#Mann=3,-1,0
  4358.3    0.05       0  5065.8    0.04       0  5069.8    0.05       0
Bank Sta=5065.8,5069.8
Exp/Cntr=0.3,0.1

Type RM Length L Ch R = 1,2199,512,512,512
BEGIN DESCRIPTION:
Mapping XS b1a0249c
END DESCRIPTION:
XS GIS Cut Line= 3
      2725298.38      6919897.99      2725567.53      6920643.22
      2725746.76      6920870.65
#Sta/Elev= 30
  4191.3  457.86  4199.4  458.11  4224.8  457.46  4230.1  457.95  4311.4  454.59
  4322.1  453.59  4347.4  452.35  4354.0  451.35  4378.1  449.29  4428.4  446.58
  4490.1  440.97  4551.5  437.76  4556.8  438.06  4582.1  437.33  4674.1  433.50
  4760.8  431.34  4983.6  429.61  4986.2  428.16  4986.5  427.66  4990.0  427.66
  4990.2  428.16  4994.6  429.40  5037.9  430.84  5073.2  431.01  5130.9  430.40
  5215.9  431.01  5230.3  430.78  5259.2  431.29  5265.6  432.03  5273.2  431.99
#Mann=3,-1,0
  4191.3    0.05       0  4986.2    0.04       0  4990.2    0.05       0
Bank Sta=4986.2,4990.2
Exp/Cntr=0.3,0.1

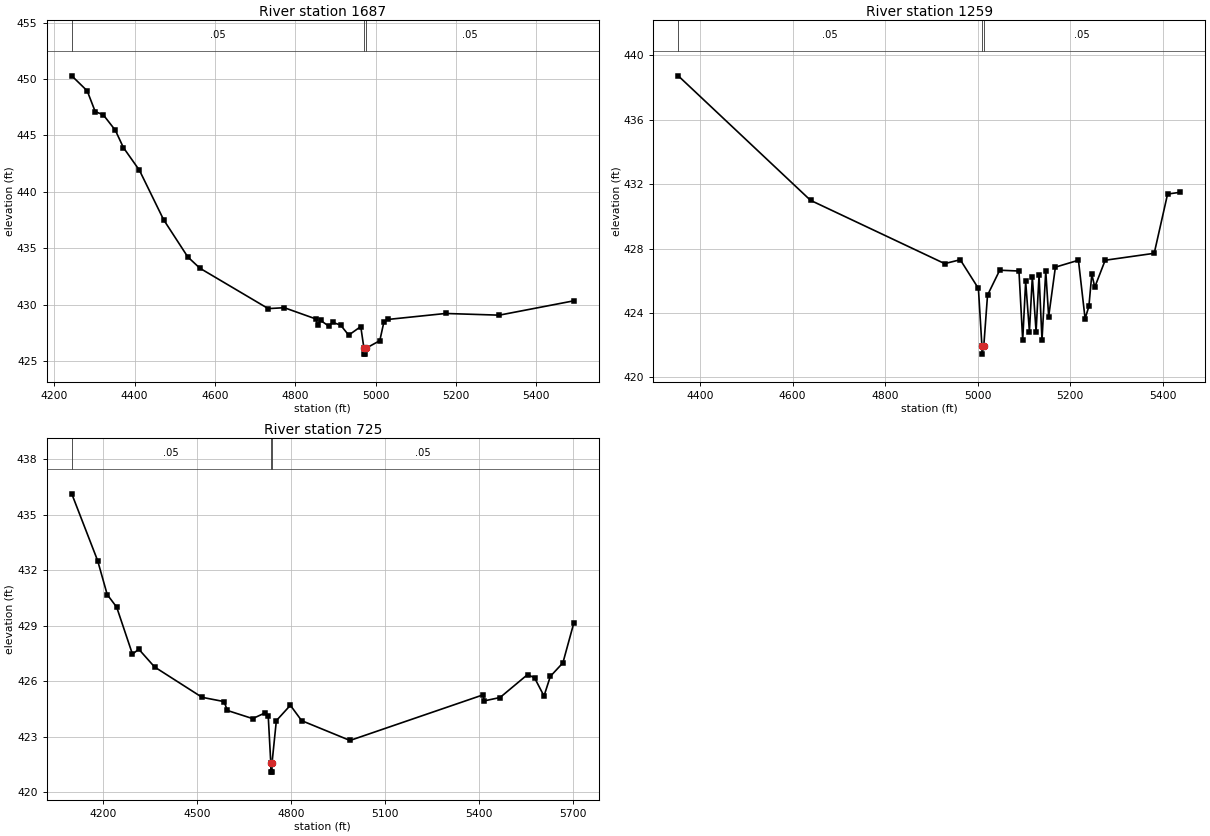
Type RM Length L Ch R = 1,1687,428,428,428
BEGIN DESCRIPTION:
Mapping XS 514cd0e0
END DESCRIPTION:
XS GIS Cut Line= 3
      2725167.86      6920002.71      2725121.83      6920763.64
      2725596.87      6920874.82
#Sta/Elev= 30
  4243.5  450.28  4281.9  448.95  4301.9  447.11  4321.9  446.83  4352.0  445.46
  4372.0  443.93  4412.1  441.91  4472.2  437.54  4532.3  434.25  4562.4  433.25
  4732.7  429.67  4772.8  429.75  4850.9  428.76  4855.9  428.25  4862.9  428.63
  4883.0  428.13  4893.0  428.45  4913.0  428.21  4933.0  427.32  4963.1  428.08
  4971.1  426.14  4971.4  425.64  4974.9  425.64  4975.1  426.14  5010.5  426.83
  5020.8  428.50  5030.6  428.71  5174.4  429.24  5307.9  429.09  5493.7  430.36
#Mann=3,-1,0
  4243.5    0.05       0  4971.1    0.04       0  4975.1    0.05       0
Bank Sta=4971.1,4975.1
Exp/Cntr=0.3,0.1

Type RM Length L Ch R = 1,1259,534,534,534
BEGIN DESCRIPTION:
Mapping XS 80b37309
END DESCRIPTION:
XS GIS Cut Line= 4
      2724897.88      6920034.93      2724731.37      6920657.01
      2724736.92      6920698.19      2725051.74      6920943.60
#Sta/Elev= 30
  4353.0  438.73  4638.8  431.00  4928.6  427.07  4962.3  427.31  5001.5  425.53
  5009.1  421.95  5009.3  421.45  5013.1  421.95  5021.2  425.11  5047.5  426.66
  5089.1  426.61  5097.2  422.32  5103.6  425.96  5111.7  422.85  5118.0  426.24
  5126.1  422.85  5132.5  426.35  5138.9  422.32  5147.0  426.61  5153.3  423.78
  5167.8  426.85  5217.6  427.28  5232.0  423.65  5240.2  424.42  5246.5  426.41
  5252.9  425.61  5275.4  427.28  5381.3  427.71  5410.2  431.39  5437.7  431.50
#Mann=3,-1,0
  4353.0    0.05       0  5009.1    0.04       0  5013.1    0.05       0
Bank Sta=5009.1,5013.1
Exp/Cntr=0.3,0.1

Type RM Length L Ch R = 1,725,0,0,0
BEGIN DESCRIPTION:
Allen T1_1 1.0
END DESCRIPTION:
XS GIS Cut Line= 4
      2724391.95      6920028.80      2724285.38      6920882.61
      2724340.47      6920940.35      2725000.96      6920986.00
#Sta/Elev= 30
  4100.5  436.13  4183.3  432.51  4213.6  430.69  4243.8  430.01  4294.2  427.47
  4314.3  427.74  4364.7  426.78  4516.4  425.14  4586.4  424.91  4597.1  424.43
  4677.8  423.99  4717.4  424.30  4727.5  424.12  4735.6  421.60  4735.9  421.10
  4739.4  421.10  4739.6  421.60  4753.4  423.88  4798.1  424.71  4834.1  423.88
  4988.4  422.81  5412.5  425.27  5417.5  424.95  5467.3  425.13  5555.2  426.37
  5577.5  426.19  5607.6  425.21  5627.7  426.27  5667.8  427.00  5702.8  429.16
#Mann=3,-1,0
  4100.5    0.05       0  4735.6    0.04       0  4739.6    0.05       0
Bank Sta=4735.6,4739.6
Exp/Cntr=0.3,0.1

Chan Stop Cuts=-1