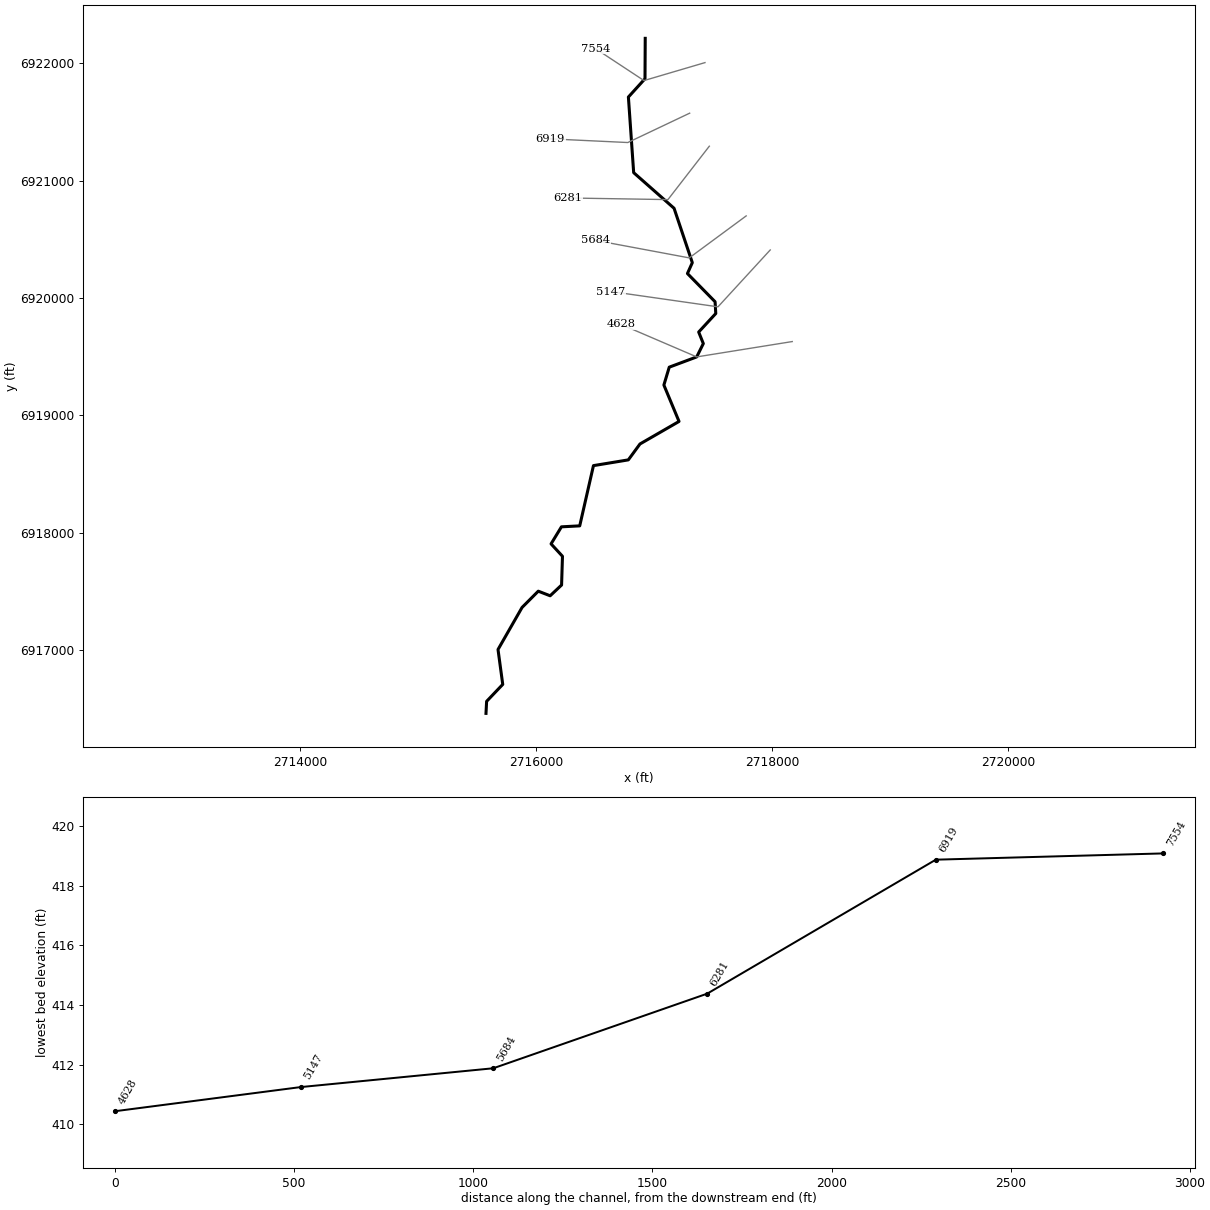
--- Allen T2.prj (project) ---

Proj Title=Allen T2 Base Level Engineering
Current Plan=p01
Default Exp/Contr=0.3,0.1
English Units
Geom File=g01
Flow File=f01
Plan File=p01
BEGIN DESCRIPTION:
Allen T2
END DESCRIPTION:

--- Allen T2.p01 (plan) ---

Plan Title=Multiple Run
Short Identifier=Multiple
Geom File=g01
Flow File=f01
Subcritical Flow
K Sum by GR= 0
Std Step Tol= 0.01
Critical Tol= 0.01
Num of Std Step Trials= 20
Max Error Tol= 0.3
Flow Tol Ratio= 0.001
Split Flow NTrial= 30
Split Flow Tol= 0.02
Split Flow Ratio= 0.02
Log Output Level= 0
Friction Slope Method= 1
Unsteady Friction Slope Method= 2
Unsteady Bridges Friction Slope Method= 1
Parabolic Critical Depth
Global Vel Dist=  1 , 1 , 1
Global Log Level= 0
CheckData=True
Encroach Param= -1, 0, 0, 0
BEGIN DESCRIPTION:
Multiple Run
END DESCRIPTION:

--- Allen T2.f01 (steady flow) ---

Flow Title=Multiple
Number of Profiles=7
Profile Names=10-year,25-year,50-year,1pct_min,100-year,1pct_plu,500-year
River Rch & RM= Allen T2,Reach-1,7554
     415     536     630     367     733    1462     991
Boundary for River Rch & Prof#=Allen T2,Reach-1,1
Up Type=0
Dn Type=3
Dn Slope=0.005
Boundary for River Rch & Prof#=Allen T2,Reach-1,2
Up Type=0
Dn Type=3
Dn Slope=0.005
Boundary for River Rch & Prof#=Allen T2,Reach-1,3
Up Type=0
Dn Type=3
Dn Slope=0.005
Boundary for River Rch & Prof#=Allen T2,Reach-1,4
Up Type=0
Dn Type=3
Dn Slope=0.005
Boundary for River Rch & Prof#=Allen T2,Reach-1,5
Up Type=0
Dn Type=3
Dn Slope=0.005
Boundary for River Rch & Prof#=Allen T2,Reach-1,6
Up Type=0
Dn Type=3
Dn Slope=0.005
Boundary for River Rch & Prof#=Allen T2,Reach-1,7
Up Type=0
Dn Type=3
Dn Slope=0.005

--- Allen T2.g01 (geometry) ---

Geom Title=Existing Conditions

River Reach=Allen T2,Reach-1
Reach XY= 30
      2716926.00      6922211.00      2716924.03      6921866.89
      2716783.32      6921711.10      2716828.05      6921066.84
      2717170.48      6920763.43      2717325.20      6920300.30
      2717283.82      6920207.59      2717518.24      6919967.17
      2717524.04      6919866.89      2717379.16      6919709.35
      2717418.44      6919611.00      2717362.54      6919497.43
      2717129.61      6919409.97      2717084.08      6919257.70
      2717212.59      6918947.66      2716881.47      6918755.74
      2716782.69      6918620.29      2716487.09      6918571.38
      2716370.64      6918058.22      2716215.63      6918050.02
      2716127.75      6917904.84      2716224.47      6917799.12
      2716216.86      6917554.25      2716119.97      6917462.66
      2716019.27      6917501.85      2715881.83      6917363.30
      2715677.97      6917005.11      2715718.01      6916707.66
      2715581.35      6916563.50      2715576.00      6916461.00

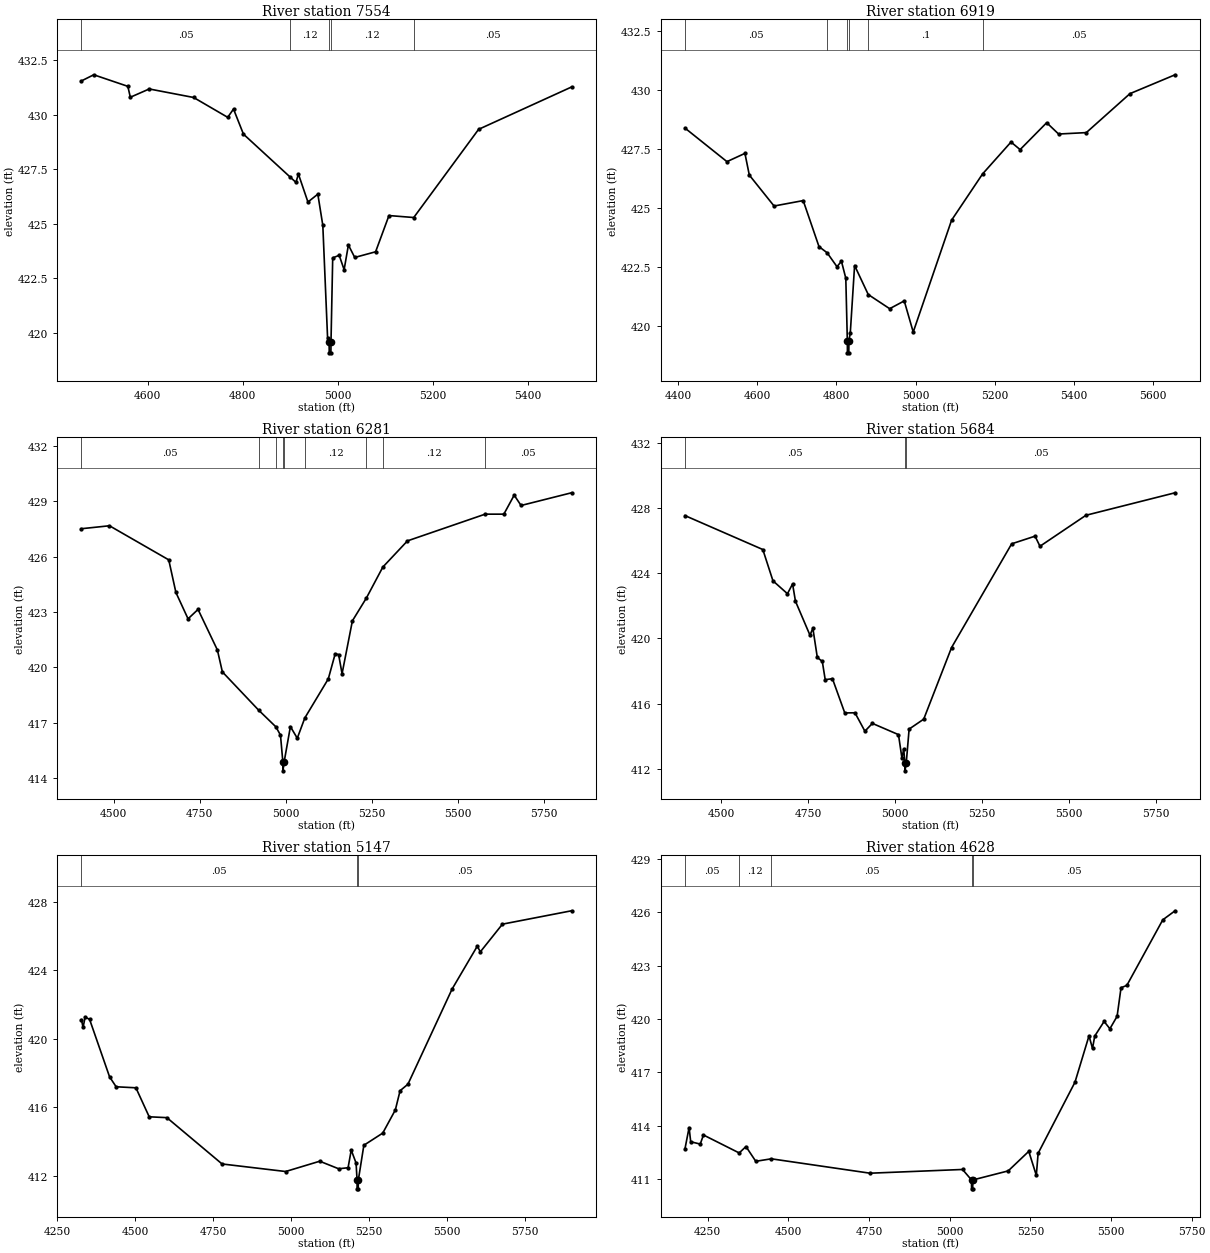
Type RM Length L Ch R = 1,7554,635,635,635
BEGIN DESCRIPTION:
Allen T2 4.0
END DESCRIPTION:
XS GIS Cut Line= 3
      2717432.60      6922004.23      2716915.56      6921851.21
      2716505.85      6922122.34
#Sta/Elev= 30
  4460.8  431.54  4486.6  431.82  4558.3  431.29  4563.5  430.79  4603.3  431.17
  4696.6  430.78  4768.3  429.87  4780.5  430.25  4801.4  429.10  4900.3  427.12
  4911.8  426.89  4917.0  427.27  4937.0  425.99  4957.8  426.35  4968.3  424.92
  4978.3  419.77  4981.5  419.58  4981.8  419.08  4985.3  419.08  4985.5  419.58
  4989.1  423.43  5002.7  423.55  5013.1  422.89  5022.1  424.02  5035.4  423.45
  5079.3  423.71  5107.4  425.37  5159.5  425.28  5295.9  429.32  5491.3  431.26
#Mann=5,-1,0
  4460.8    0.05       0  4900.3    0.12       0  4981.5    0.07       0
  4985.5    0.12       0  5159.5    0.05       0
Bank Sta=4981.5,4985.5
Exp/Cntr=0.3,0.1

Type RM Length L Ch R = 1,6919,638,638,638
BEGIN DESCRIPTION:
Mapping XS 72df81a3
END DESCRIPTION:
XS GIS Cut Line= 3
      2717302.60      6921573.45      2716778.33      6921323.47
      2716122.10      6921354.72
#Sta/Elev= 30
  4417.4  428.39  4523.3  426.97  4568.7  427.32  4579.8  426.40  4642.3  425.09
  4715.9  425.32  4755.8  423.37  4776.3  423.11  4801.2  422.52  4812.5  422.75
  4823.5  422.03  4827.4  419.37  4827.6  418.87  4831.1  418.87  4831.4  419.37
  4834.9  419.73  4845.7  422.57  4880.2  421.34  4934.3  420.74  4971.1  421.07
  4993.8  419.75  5090.7  424.49  5169.0  426.45  5240.8  427.80  5263.8  427.48
  5330.9  428.62  5361.0  428.14  5431.0  428.20  5541.2  429.85  5655.2  430.65
#Mann=6,-1,0
  4417.4    0.05       0  4776.3    0.12       0  4827.4    0.07       0
  4831.4    0.12       0  4880.2     0.1       0  5169.0    0.05       0
Bank Sta=4827.4,4831.4
Exp/Cntr=0.3,0.1

Type RM Length L Ch R = 1,6281,597,597,597
BEGIN DESCRIPTION:
Mapping XS 45d14a47
END DESCRIPTION:
XS GIS Cut Line= 3
      2717469.28      6921292.20      2717118.60      6920837.36
      2716269.45      6920851.22
#Sta/Elev= 30
  4406.5  427.52  4487.8  427.68  4660.0  425.83  4680.8  424.06  4716.1  422.63
  4745.1  423.14  4801.3  420.94  4815.8  419.75  4920.8  417.68  4971.1  416.77
  4984.6  416.32  4991.4  414.88  4991.7  414.38  4995.4  414.88  5013.4  416.78
  5033.4  416.15  5055.3  417.25  5123.5  419.37  5143.5  420.73  5153.5  420.69
  5163.5  419.65  5193.5  422.52  5234.2  423.76  5282.0  425.44  5353.5  426.86
  5579.2  428.31  5633.5  428.31  5663.5  429.34  5683.5  428.78  5830.1  429.47
#Mann=9,-1,0
  4406.5    0.05       0  4920.8    0.12       0  4971.1    0.05       0
  4991.4    0.04       0  4995.4    0.05       0  5055.3    0.12       0
  5234.2     0.1       0  5282.0    0.12       0  5579.2    0.05       0
Bank Sta=4991.4,4995.4
Exp/Cntr=0.3,0.1

Type RM Length L Ch R = 1,5684,537,537,537
BEGIN DESCRIPTION:
Mapping XS 7e12c64c
END DESCRIPTION:
XS GIS Cut Line= 3
      2717781.83      6920698.49      2717299.16      6920340.83
      2716504.00      6920490.14
#Sta/Elev= 30
  4396.1  427.53  4619.9  425.45  4649.1  423.53  4690.8  422.74  4705.5  423.34
  4713.8  422.28  4755.5  420.20  4763.9  420.62  4776.7  418.83  4791.0  418.59
  4799.4  417.47  4820.2  417.53  4855.7  415.43  4885.0  415.44  4913.6  414.31
  4935.0  414.79  5010.2  414.10  5020.1  412.66  5025.2  413.22  5028.6  412.38
  5028.8  411.88  5032.6  412.38  5040.8  414.44  5082.8  415.05  5162.9  419.44
  5335.8  425.80  5403.1  426.27  5417.2  425.65  5549.5  427.55  5805.9  428.93
#Mann=3,-1,0
  4396.1    0.05       0  5028.6    0.04       0  5032.6    0.05       0
Bank Sta=5028.6,5032.6
Exp/Cntr=0.3,0.1

Type RM Length L Ch R = 1,5147,519,519,519
BEGIN DESCRIPTION:
Mapping XS 7d8b1e46
END DESCRIPTION:
XS GIS Cut Line= 3
      2717985.62      6920408.36      2717542.91      6919923.99
      2716636.62      6920054.20
#Sta/Elev= 30
  4327.5  421.11  4332.5  420.66  4339.3  421.26  4353.5  421.13  4417.6  417.78
  4438.6  417.20  4502.1  417.14  4544.7  415.45  4601.4  415.40  4778.4  412.70
  4982.3  412.26  5091.7  412.86  5152.3  412.42  5182.6  412.48  5192.7  413.51
  5208.3  412.75  5211.4  411.75  5211.6  411.25  5215.1  411.25  5215.4  411.75
  5233.2  413.79  5293.8  414.50  5334.2  415.85  5349.4  416.97  5374.6  417.35
  5516.0  422.89  5596.8  425.39  5607.0  425.07  5677.7  426.68  5899.3  427.46
#Mann=3,-1,0
  4327.5    0.05       0  5211.4    0.04       0  5215.4    0.05       0
Bank Sta=5211.4,5215.4
Exp/Cntr=0.3,0.1

Type RM Length L Ch R = 1,4628,0,0,0
BEGIN DESCRIPTION:
Allen T2 1.0
END DESCRIPTION:
XS GIS Cut Line= 3
      2718172.46      6919628.16      2717362.54      6919497.43
      2716721.01      6919774.00
#Sta/Elev= 30
  4179.6  412.71  4192.2  413.89  4197.2  413.09  4226.7  412.96  4236.8  413.47
  4347.5  412.46  4368.5  412.82  4398.9  411.99  4447.1  412.13  4753.1  411.32
  5039.8  411.53  5067.6  410.94  5067.8  410.44  5071.3  410.44  5071.6  410.94
  5181.4  411.45  5245.1  412.55  5268.5  411.20  5274.1  412.44  5388.3  416.44
  5431.8  419.05  5442.7  418.34  5449.6  419.04  5478.6  419.86  5496.6  419.45
  5518.9  420.15  5531.1  421.76  5549.1  421.89  5660.5  425.58  5698.6  426.09
#Mann=5,-1,0
  4179.6    0.05       0  4347.5    0.12       0  4447.1    0.05       0
  5067.6    0.04       0  5071.6    0.05       0
Bank Sta=5067.6,5071.6
Exp/Cntr=0.3,0.1

Chan Stop Cuts=-1