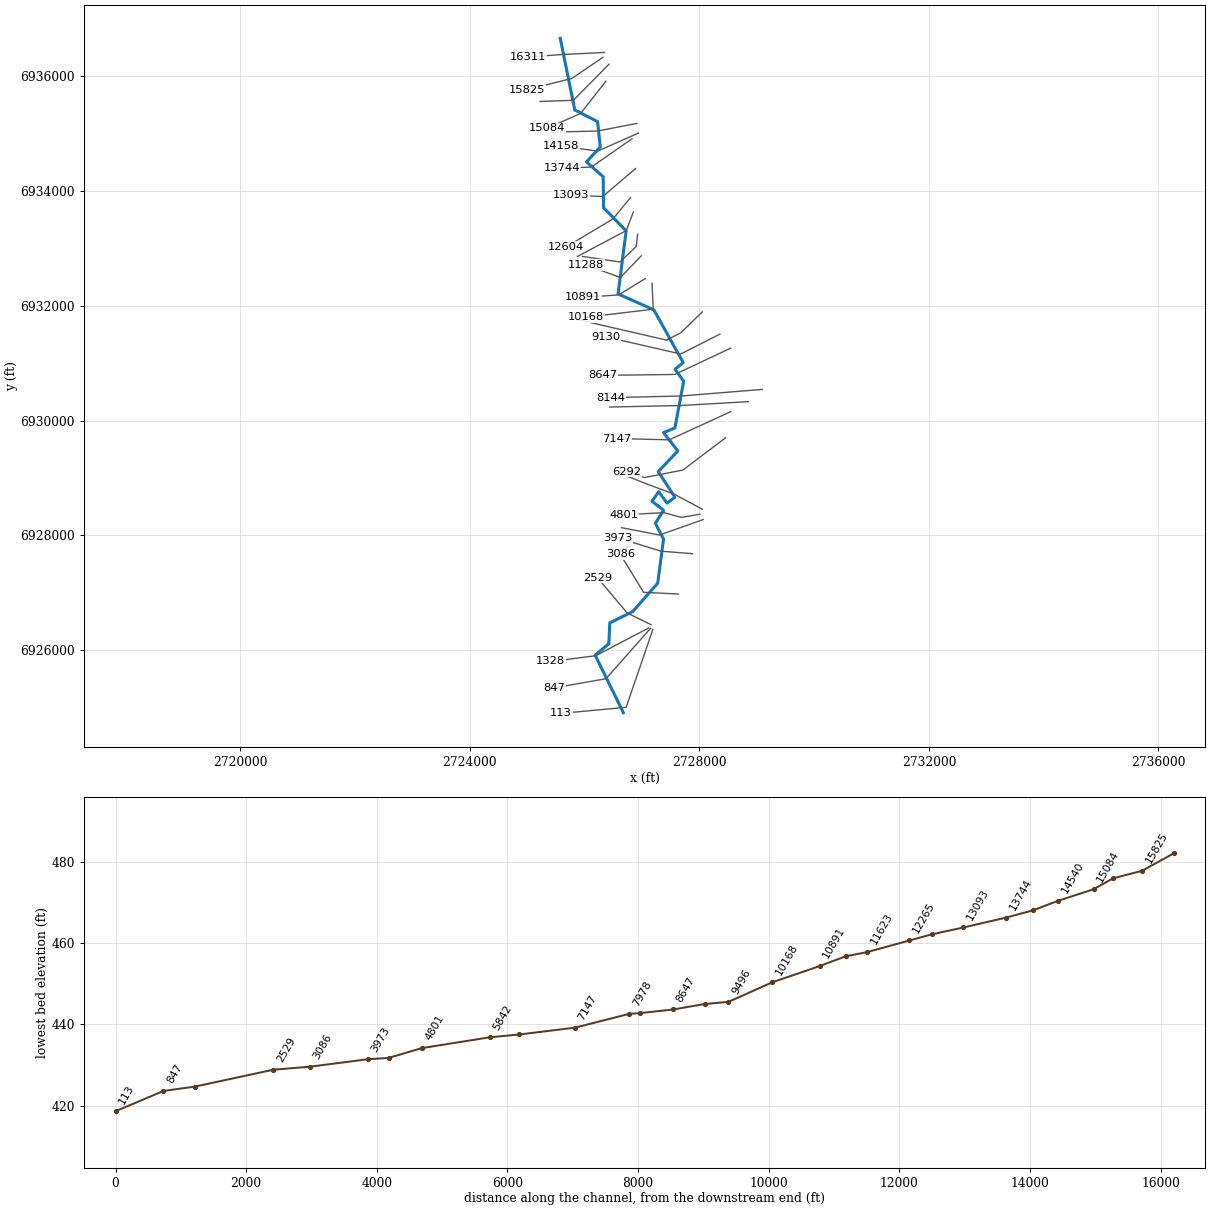
--- Allen T3.prj (project) ---

Proj Title=Allen T3 Base Level Engineering
Current Plan=p01
Default Exp/Contr=0.3,0.1
English Units
Geom File=g01
Flow File=f01
Plan File=p01
Y Axis Title=Elevation
X Axis Title(PF)=Main Channel Distance
X Axis Title(XS)=Station
BEGIN DESCRIPTION:
Allen T3
END DESCRIPTION:
DSS Export Rating Curves= 0
DSS Export Rating Curve Sorted= 0
DSS Export Volume Flow Curves= 0
DXF OffsetX= 0
DXF OffsetY= 0
DXF ScaleX= 1
DXF ScaleY= 10

--- Allen T3.p01 (plan) ---

Plan Title=Multiple Run
Short Identifier=Multiple
Geom File=g01
Flow File=f01
Subcritical Flow
K Sum by GR= 0
Std Step Tol= 0.01
Critical Tol= 0.01
Num of Std Step Trials= 20
Max Error Tol= 0.3
Flow Tol Ratio= 0.001
Split Flow NTrial= 30
Split Flow Tol= 0.02
Split Flow Ratio= 0.02
Log Output Level= 0
Friction Slope Method= 1
Unsteady Friction Slope Method= 2
Unsteady Bridges Friction Slope Method= 1
Parabolic Critical Depth
Global Vel Dist=  1 , 1 , 1
Global Log Level= 0
CheckData=True
Encroach Param= -1, 0, 0, 0
BEGIN DESCRIPTION:
Multiple Run
END DESCRIPTION:

--- Allen T3.f01 (steady flow) ---

Flow Title=Multiple
Program Version=4.10
Number of Profiles= 7
Profile Names=10-year,25-year,50-year,1pct_min,100-year,1pct_plu,500-year
River Rch & RM=Allen T3,Reach-1         ,16311
     214     265     303     172     344     686     442
River Rch & RM=Allen T3,Reach-1         ,14540
     451     587     693     407     811    1618    1109
River Rch & RM=Allen T3,Reach-1         ,9496
    1031    1403    1708    1029    2053    4096    2965
Boundary for River Rch & Prof#=Allen T3,Reach-1         , 1
Up Type= 0
Dn Type= 3
Dn Slope=0.005
Boundary for River Rch & Prof#=Allen T3,Reach-1         , 2
Up Type= 0
Dn Type= 3
Dn Slope=0.005
Boundary for River Rch & Prof#=Allen T3,Reach-1         , 3
Up Type= 0
Dn Type= 3
Dn Slope=0.005
Boundary for River Rch & Prof#=Allen T3,Reach-1         , 4
Up Type= 0
Dn Type= 3
Dn Slope=0.005
Boundary for River Rch & Prof#=Allen T3,Reach-1         , 5
Up Type= 0
Dn Type= 3
Dn Slope=0.005
Boundary for River Rch & Prof#=Allen T3,Reach-1         , 6
Up Type= 0
Dn Type= 3
Dn Slope=0.005
Boundary for River Rch & Prof#=Allen T3,Reach-1         , 7
Up Type= 0
Dn Type= 3
Dn Slope=0.005
DSS Import GetInterval= 0
DSS Import GetPeak= 0
DSS Import FillOption= 0

--- Allen T3.g01 (geometry) ---

Geom Title=Existing Conditions
Program Version=4.10

River Reach=Allen T3        ,Reach-1
Reach XY= 30
        2725576.        6936661.      2725829.45      6935412.25
        2726226.        6935211.      2726273.77      6934766.93
      2726033.51      6934507.85      2726324.39      6934249.17
      2726331.83       6933708.7      2726724.37      6933304.96
       2726583.6      6932207.63      2727206.41       6931931.2
      2727718.99      6931010.79      2727576.31      6930895.94
      2727726.54      6930686.13      2727574.52      6929872.49
      2727375.48      6929790.95       2727625.3       6929471.7
      2727283.01       6929111.2      2727574.04      6928666.88
      2727437.74        6928562.      2727292.04      6928760.83
      2727175.89      6928595.63      2727376.61      6928436.31
      2727232.95        6928211.      2727376.23      6927936.07
      2727273.95      6927166.84      2726840.02      6926674.62
      2726439.37      6926474.38      2726422.55      6926112.19
      2726184.08       6925914.3        2726676.        6924911.

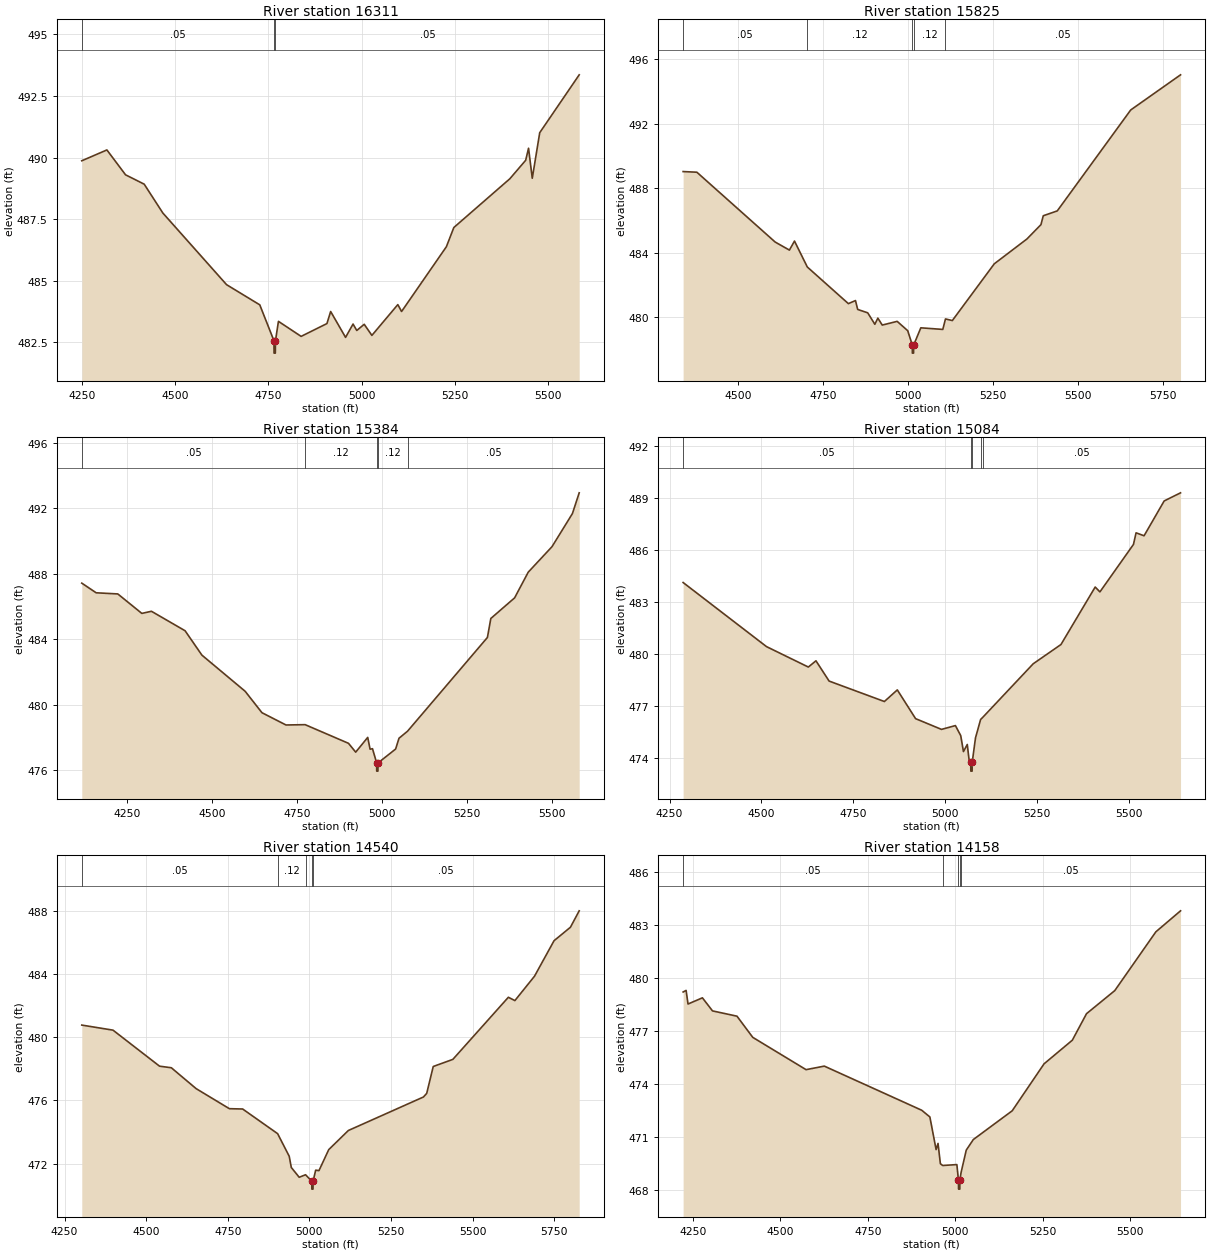
Type RM Length L Ch R = 1 ,16311   ,486,486,486
BEGIN DESCRIPTION:
Allen T3 24.0
END DESCRIPTION:
XS GIS Cut Line= 3
      2726343.35      6936415.21      2725593.18      6936377.69
      2725010.32       6936335.4
#Sta/Elev= 30
  4248.9  489.87  4316.3  490.31  4366.4   489.3  4416.5  488.92  4466.5  487.75
  4637.6  484.84  4726.8  484.02  4764.9  482.56  4765.1  482.06  4768.6  482.06
  4768.9  482.56  4776.9  483.35  4837.8  482.74  4907.1  483.26  4917.1  483.75
  4957.1   482.7  4977.2  483.24  4987.2  482.98  5007.2  483.23  5027.8  482.78
  5097.4  484.03  5107.5  483.75  5227.8  486.38  5247.8  487.16  5398.2  489.14
  5440.7  489.89  5448.4  490.38  5458.4  489.16  5478.4  491.01  5584.4  493.36
#Mann= 3 ,-1 , 0
  4248.9     .05       0  4764.9     .05       0  4768.9     .05       0
Bank Sta=4764.9,4768.9
XS Rating Curve= 0 ,0
Exp/Cntr=0.3,0.1

Type RM Length L Ch R = 1 ,15825   ,441,441,441
BEGIN DESCRIPTION:
Allen T3 23.0
END DESCRIPTION:
XS GIS Cut Line= 3
      2726321.72       6936330.6        2725776.        6935961.
      2724993.55      6935766.34
#Sta/Elev= 30
  4336.9  489.03  4377.4  488.99    4608  484.66    4650  484.16    4665  484.72
  4702.8  483.11  4823.7  480.84  4844.7  481.03  4851.1  480.48  4880.7  480.27
  4901.7  479.56  4910.6  479.94  4923.5  479.51  4967.5  479.74  4998.6  479.16
  5012.1  478.27  5012.3  477.77  5015.8  477.77  5016.1  478.27  5037.2  479.34
  5101.9  479.24  5109.8  479.89    5130  479.79  5253.6  483.31  5349.8  484.85
  5391.1  485.74  5397.9  486.29  5439.1  486.59  5655.5  492.85  5802.3  495.03
#Mann= 5 ,-1 , 0
  4336.9     .05       0  4702.8     .12       0  5012.1     .07       0
  5016.1     .12       0  5109.8     .05       0
Bank Sta=5012.1,5016.1
XS Rating Curve= 0 ,0
Exp/Cntr=0.3,0.1

Type RM Length L Ch R = 1 ,15384   ,300,300,300
BEGIN DESCRIPTION:
Allen T3 22.0
END DESCRIPTION:
XS GIS Cut Line= 3
      2726425.96      6936210.96      2725805.49      6935581.16
      2725226.05        6935561.
#Sta/Elev= 30
  4115.9  487.43  4158.2  486.84  4221.9  486.77  4292.6  485.58  4320.9  485.71
  4419.9  484.52  4469.4  483.03  4596.7  480.82  4646.2  479.51  4716.9  478.76
  4773.2  478.78  4900.8  477.64    4922   477.1  4957.4     478  4964.4  477.28
  4971.5  477.31  4983.7  476.44  4983.9  475.94  4987.4  475.94  4987.7  476.44
  5039.5  477.29  5049.5  477.95  5074.6  478.38  5309.7  484.11  5319.7  485.27
  5389.7  486.53  5429.8   488.1  5499.8  489.66  5559.8  491.68  5579.8  492.95
#Mann= 5 ,-1 , 0
  4115.9     .05       0  4773.2     .12       0  4983.7     .07       0
  4987.7     .12       0  5074.6     .05       0
Bank Sta=4983.7,4987.7
XS Rating Curve= 0 ,0
Exp/Cntr=0.3,0.1

Type RM Length L Ch R = 1 ,15084   ,544,544,544
BEGIN DESCRIPTION:
Allen T3 21.0
END DESCRIPTION:
XS GIS Cut Line= 3
       2726371.6      6935913.91      2725931.89       6935352.5
      2725345.17      6935093.62
#Sta/Elev= 30
  4286.9  484.13  4513.9  480.43  4627.8  479.25  4648.6  479.61  4684.4  478.44
  4834.9  477.26  4870.1  477.93  4919.9  476.27  4990.4  475.65  5028.3  475.87
  5042.8  475.29  5050.2  474.37  5060.6  474.78  5066.1  473.79    5070  473.74
  5070.3  473.24  5073.8  473.24    5074  473.74    5083  475.16  5096.9  476.22
  5103.4  476.36  5240.2  479.44  5315.7  480.55  5408.9  483.87  5421.8  483.59
  5513.1  486.33  5520.2     487    5542  486.83  5596.7  488.84  5641.3  489.31
#Mann= 5 ,-1 , 0
  4286.9     .05       0    5070     .04       0    5074     .05       0
  5096.9     .12       0  5103.4     .05       0
Bank Sta=5070,5074
XS Rating Curve= 0 ,0
Exp/Cntr=0.3,0.1

Type RM Length L Ch R = 1 ,14540   ,382,382,382
BEGIN DESCRIPTION:
Allen T3 20.0
END DESCRIPTION:
XS GIS Cut Line= 3
      2726909.82      6935178.24      2726225.33      6935045.73
      2725399.06      6935026.37
#Sta/Elev= 30
  4302.8  480.77  4398.4  480.45    4541  478.17  4577.1  478.07    4653  476.75
  4754.9  475.48  4795.6  475.46  4902.7   473.9  4938.2  472.47  4944.6  471.76
  4968.8  471.14  4988.3   471.3  5007.3  470.89  5007.6  470.39  5011.1  470.39
  5011.3  470.89  5019.3  471.59  5029.3  471.56  5059.3  472.89  5119.4   474.1
  5349.4  476.22  5359.4  476.45  5379.4  478.15  5439.5   478.6  5609.5  482.53
  5629.5  482.32  5689.5  483.86  5749.5  486.11  5799.6  486.96  5826.5     488
#Mann= 5 ,-1 , 0
  4302.8     .05       0  4902.7     .12       0  4988.3     .05       0
  5007.3     .04       0  5011.3     .05       0
Bank Sta=5007.3,5011.3
XS Rating Curve= 0 ,0
Exp/Cntr=0.3,0.1

Type RM Length L Ch R = 1 ,14158   ,414,414,414
BEGIN DESCRIPTION:
Allen T3 19.0
END DESCRIPTION:
XS GIS Cut Line= 3
      2726937.97      6935009.81      2726227.01      6934695.58
      2725590.06      6934785.73
#Sta/Elev= 30
  4222.7  479.22  4231.2  479.31  4236.7  478.54  4277.8  478.89  4306.6  478.15
  4376.5  477.85  4421.6  476.65  4573.8  474.82  4625.9  475.02  4904.1  472.52
  4927.4  472.14  4945.2  470.29  4950.7  470.64  4957.4  469.49    4964  469.39
  5004.5  469.44  5009.1  468.55  5009.4  468.05  5012.9  468.05  5013.1  468.55
  5016.5  468.99  5031.3  470.26  5051.5  470.86  5162.6  472.49  5253.5  475.15
  5334.3  476.49  5374.7  477.99  5455.5   479.3  5572.8  482.63  5643.3  483.82
#Mann= 5 ,-1 , 0
  4222.7     .05       0    4964     .12       0  5009.1     .07       0
  5013.1     .12       0  5016.5     .05       0
Bank Sta=5009.1,5013.1
XS Rating Curve= 0 ,0
Exp/Cntr=0.3,0.1

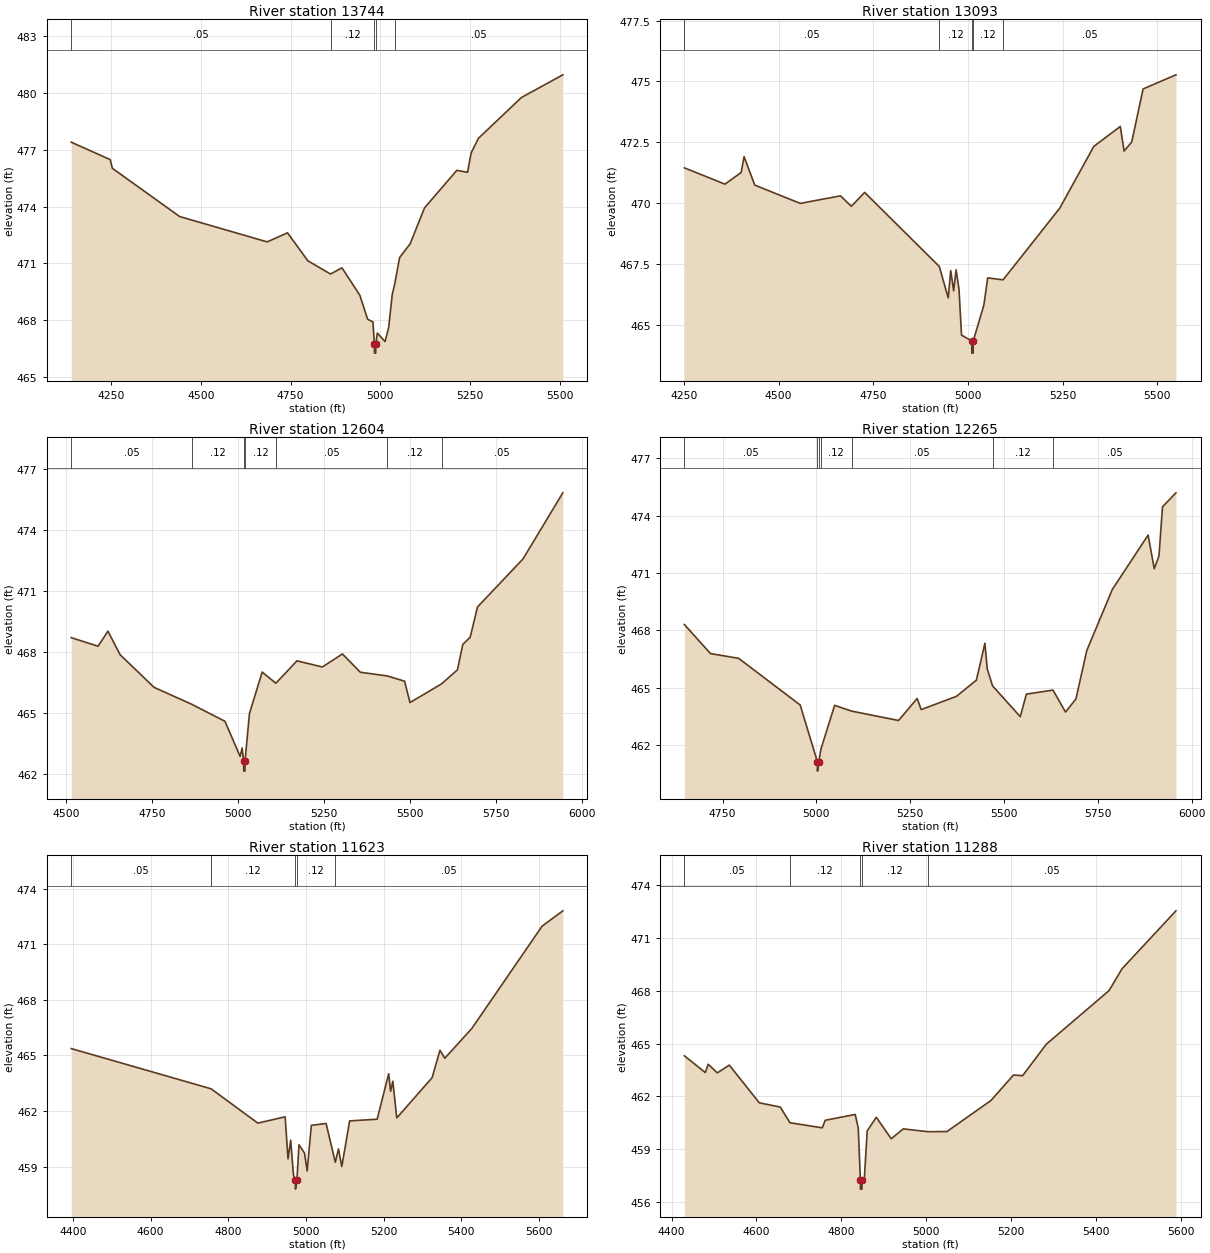
Type RM Length L Ch R = 1 ,13744   ,651,651,651
BEGIN DESCRIPTION:
Allen T3 18.0
END DESCRIPTION:
XS GIS Cut Line= 3
      2726826.03      6934911.02       2726119.3      6934417.67
      2725610.49      6934400.48
#Sta/Elev= 30
  4138.1  477.41  4246.7  476.49  4252.8  476.03  4440.4  473.48  4684.6  472.14
  4741.3  472.62    4798  471.14  4861.2  470.44  4893.1  470.77    4943  469.32
  4964.7  468.05  4979.5  467.91  4983.6  466.76  4983.8  466.26  4987.3  466.26
  4987.6  466.76  4991.8  467.32  5013.3  466.87  5023.3   467.6  5033.3  469.35
  5040.8  469.96  5053.8  471.31  5083.3  472.04  5123.4  473.94  5213.4  475.92
  5243.4  475.82  5253.4  476.84  5273.5  477.61  5393.5  479.77  5509.1  480.97
#Mann= 5 ,-1 , 0
  4138.1     .05       0  4861.2     .12       0  4983.6     .07       0
  4987.6     .12       0  5040.8     .05       0
Bank Sta=4983.6,4987.6
XS Rating Curve= 0 ,0
Exp/Cntr=0.3,0.1

Type RM Length L Ch R = 1 ,13093   ,489,489,489
BEGIN DESCRIPTION:
Allen T3 17.0
END DESCRIPTION:
XS GIS Cut Line= 3
      2726887.33      6934391.45      2726318.14      6933905.06
      2725769.24      6933926.15
#Sta/Elev= 30
  4251.3  471.45  4358.5  470.78  4401.3  471.26    4409  471.91  4437.2  470.74
  4557.2  469.99  4663.6   470.3  4692.2  469.87  4727.3  470.44  4924.4   467.4
    4948  466.11  4954.6  467.23  4962.3   466.4  4968.8  467.26  4976.5  466.46
  4983.1  464.58  5010.1  464.34  5010.4  463.84  5013.9  463.84  5014.1  464.34
  5042.2  465.82  5052.2  466.93  5092.9  466.85  5242.3  469.79  5332.4  472.33
  5402.4  473.15  5412.4  472.14  5432.5  472.51  5462.5  474.69  5549.3  475.27
#Mann= 5 ,-1 , 0
  4251.3     .05       0  4924.4     .12       0  5010.1     .07       0
  5014.1     .12       0  5092.9     .05       0
Bank Sta=5010.1,5014.1
XS Rating Curve= 0 ,0
Exp/Cntr=0.3,0.1

Type RM Length L Ch R = 1 ,12604   ,339,339,339
BEGIN DESCRIPTION:
Allen T3 16.0
END DESCRIPTION:
XS GIS Cut Line= 3
      2726800.97      6933885.96       2726491.9      6933511.81
        2725680.      6933027.45
#Sta/Elev= 30
  4514.7  468.69  4592.8  468.27  4621.5  469.01  4656.6  467.86  4755.6  466.25
  4864.9  465.42  4962.1  464.58  5006.2  462.85    5012  463.27  5016.5  462.63
  5016.8  462.13  5020.3  462.13  5020.5  462.63  5033.4  464.96  5070.4     467
  5110.2  466.45  5171.6  467.55  5245.6  467.25    5304  467.89  5356.2  466.99
  5434.3  466.81  5484.9  466.55  5500.5   465.5  5592.6  466.42  5638.7  467.11
  5654.3  468.36  5675.7  468.71  5697.1   470.2  5829.5  472.56  5945.4  475.81
#Mann= 7 ,-1 , 0
  4514.7     .05       0  4864.9     .12       0  5016.5     .07       0
  5020.5     .12       0  5110.2     .05       0  5434.3     .12       0
  5592.6     .05       0
#XS Ineff= 2 , 0
       0                    5304       0  467.89
Permanent Ineff=
       F       F
Bank Sta=5016.5,5020.5
XS Rating Curve= 0 ,0
Exp/Cntr=0.3,0.1

Type RM Length L Ch R = 1 ,12265   ,642,642,642
BEGIN DESCRIPTION:
Allen T3 15.0
END DESCRIPTION:
XS GIS Cut Line= 3
      2726851.02      6933636.04        2726726.        6933311.
      2725876.02      6932861.01
#Sta/Elev= 30
  4648.2  468.31  4717.9  466.79  4792.9  466.54  4956.8   464.1  5002.6  461.14
  5002.9  460.64  5006.6  461.14  5012.1  461.79  5048.6  464.08    5094  463.78
    5219  463.29  5268.6  464.44  5279.3  463.86    5373  464.55  5426.4   465.4
  5449.1  467.33  5455.3  465.99  5469.5   465.1  5543.3  463.49  5559.7  464.67
  5630.5  464.88    5664  463.73  5691.7  464.42  5720.6  466.95  5788.5  470.14
    5884  472.99  5900.4  471.23    5913   471.9  5922.4  474.47  5958.2   475.2
#Mann= 7 ,-1 , 0
  4648.2     .05       0  5002.6     .03       0  5006.6     .05       0
  5012.1     .12       0    5094     .05       0  5469.5     .12       0
  5630.5     .05       0
#XS Ineff= 2 , 0
       0                  5449.1       0  467.33
Permanent Ineff=
       F       F
Bank Sta=5002.6,5006.6
XS Rating Curve= 0 ,0
Exp/Cntr=0.3,0.1

Type RM Length L Ch R = 1 ,11623   ,335,335,335
BEGIN DESCRIPTION:
Allen T3 14.0
END DESCRIPTION:
XS GIS Cut Line= 4
      2726925.03      6933246.02        2726901.        6933036.
      2726617.43      6932764.33      2725963.07      6932860.61
#Sta/Elev= 30
  4395.9  465.37    4756   463.2  4876.2  461.35  4946.6  461.69  4953.9  459.42
  4960.8  460.43    4968  458.55  4972.9  458.29  4973.2  457.79  4976.9  458.29
  4982.2  460.18  4996.3  459.74  5003.2  458.77    5014  461.23    5052  461.33
  5075.7  459.24  5083.8  459.96  5092.4  459.01  5112.6  461.47  5183.4  461.56
  5213.1  464.01  5218.1  463.07  5223.8  463.61  5233.9  461.63  5324.9   463.8
  5345.1  465.28  5357.6  464.85  5427.3  466.46  5607.9  471.97  5661.4   472.8
#Mann= 5 ,-1 , 0
  4395.9     .05       0    4756     .12       0  4972.9     .07       0
  4976.9     .12       0  5075.7     .05       0
Bank Sta=4972.9,4976.9
XS Rating Curve= 0 ,0
Exp/Cntr=0.3,0.1

Type RM Length L Ch R = 1 ,11288   ,397,397,397
BEGIN DESCRIPTION:
Allen T3 13.0
END DESCRIPTION:
XS GIS Cut Line= 3
      2726986.61      6932869.99      2726624.29      6932493.86
      2726026.03      6932710.99
#Sta/Elev= 30
  4430.1  464.31  4479.4  463.36  4486.3  463.83  4507.7  463.34    4536  463.78
  4606.7  461.64  4656.1   461.4    4679  460.51  4755.1  460.22  4762.1  460.65
  4832.8  460.98    4840  460.21    4845  457.24  4845.2  456.74  4848.7  456.74
    4849  457.24  4854.2  457.31  4861.1  460.05  4882.5  460.82  4917.7   459.6
    4946  460.16  5004.6     460  5049.1  460.01  5152.7  461.77  5205.9  463.22
  5227.4  463.18  5283.3  464.97  5431.1  468.01  5461.7  469.25  5588.8  472.54
#Mann= 5 ,-1 , 0
  4430.1     .05       0    4679     .12       0    4845     .07       0
    4849     .12       0  5004.6     .05       0
Bank Sta=4845,4849
XS Rating Curve= 0 ,0
Exp/Cntr=0.3,0.1

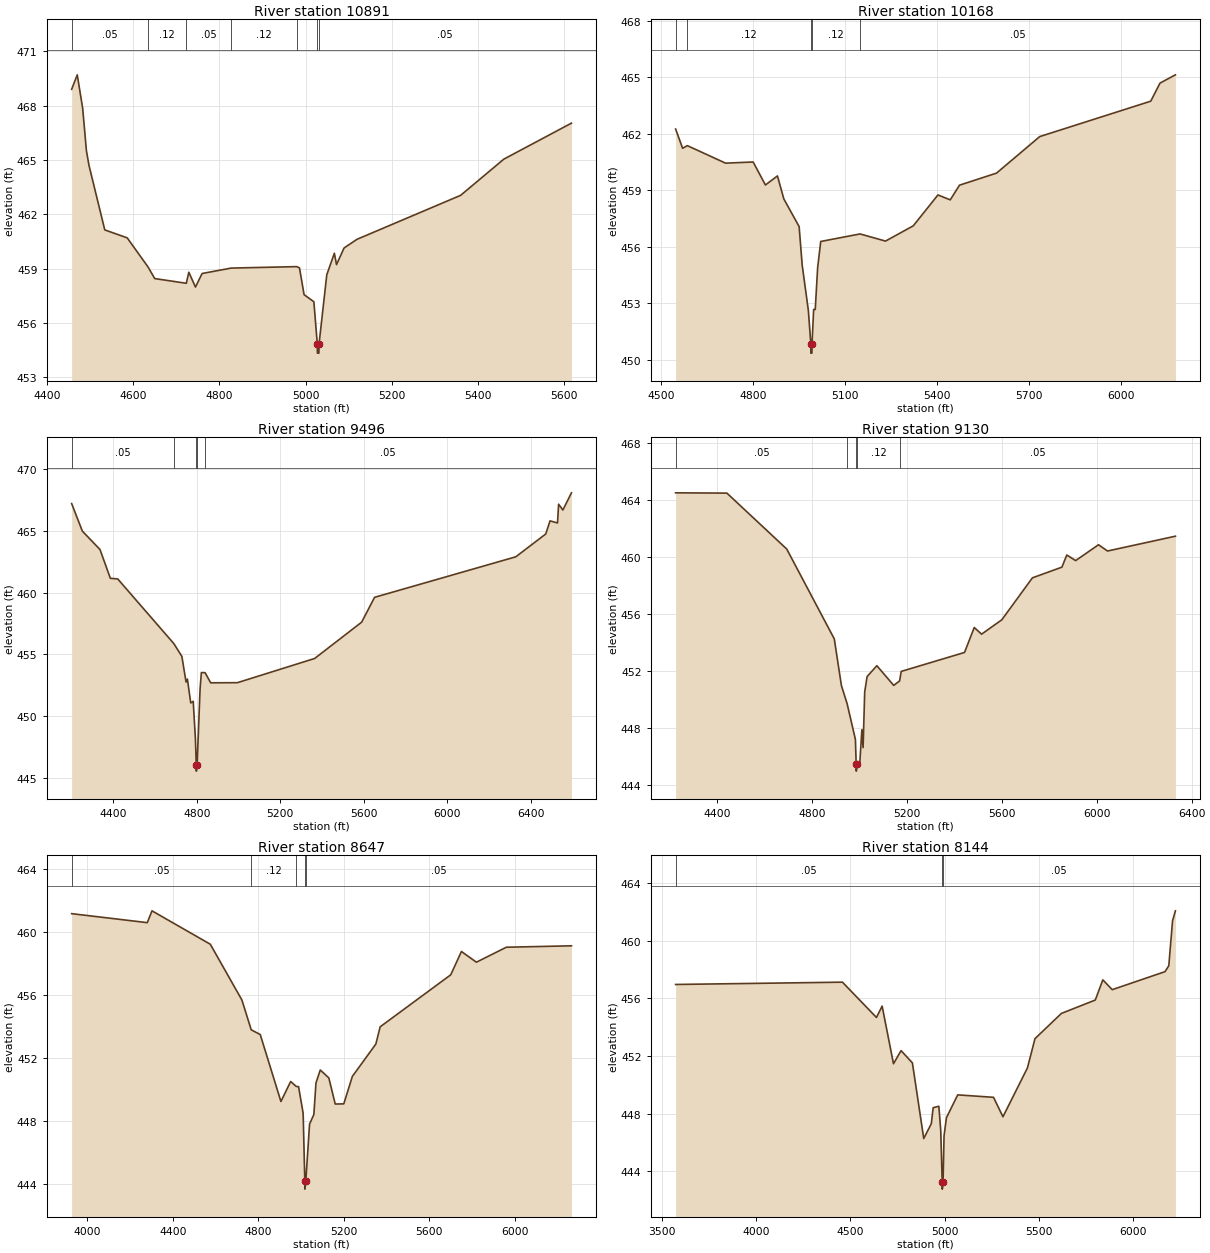
Type RM Length L Ch R = 1 ,10891   ,723,723,723
BEGIN DESCRIPTION:
Allen T3 12.0
END DESCRIPTION:
XS GIS Cut Line= 3
      2727057.77      6932475.51      2726595.21      6932190.91
      2725979.36      6932147.22
#Sta/Elev= 30
  4456.9  468.91  4469.9  469.71  4482.5  467.86  4491.2  465.51  4497.1  464.71
  4533.8  461.14  4585.9   460.7  4634.3  459.09  4649.8  458.45  4723.1  458.19
    4729   458.8  4744.4  457.98  4759.8  458.73  4827.4  459.03  4979.6  459.11
  4985.9  459.04  4996.6  457.56  5019.3  457.17  5027.3  454.83  5027.5  454.33
    5031  454.33  5031.3  454.83  5049.3  458.66  5066.9  459.85  5071.9  459.22
  5089.4  460.14  5119.5  460.62  5360.1  463.05  5460.4  465.05  5617.4  467.04
#Mann= 7 ,-1 , 0
  4456.9     .05       0  4634.3     .12       0  4723.1     .05       0
  4827.4     .12       0  4979.6     .05       0  5027.3     .04       0
  5031.3     .05       0
Bank Sta=5027.3,5031.3
XS Rating Curve= 0 ,0
Exp/Cntr=0.3,0.1

Type RM Length L Ch R = 1 ,10168   ,672,672,672
BEGIN DESCRIPTION:
Allen T3 11.0
END DESCRIPTION:
XS GIS Cut Line= 3
      2727175.02      6932393.87      2727196.52      6931941.28
      2726026.09      6931801.88
#Sta/Elev= 30
  4546.9  462.26  4569.8  461.24  4585.1  461.38  4709.9  460.45  4800.1  460.51
  4840.1  459.29  4879.4  459.77  4900.2  458.55  4950.2  457.08  4960.2  455.03
  4980.3  452.63  4988.3  450.86  4988.5  450.36    4992  450.36  4992.3  450.86
  4997.6  452.68  5002.8  452.68  5010.6  454.89  5020.7  456.29  5149.2  456.69
  5232.2  456.31  5322.8  457.12  5403.4  458.76  5443.6   458.5  5473.8  459.28
  5594.7  459.92  5735.7  461.86  6098.2  463.74  6128.4   464.7  6178.7  465.14
#Mann= 5 ,-1 , 0
  4546.9     .05       0  4585.1     .12       0  4988.3     .07       0
  4992.3     .12       0  5149.2     .05       0
Bank Sta=4988.3,4992.3
XS Rating Curve= 0 ,0
Exp/Cntr=0.3,0.1

Type RM Length L Ch R = 1 ,9496    ,366,366,366
BEGIN DESCRIPTION:
Allen T3 10.0
END DESCRIPTION:
XS GIS Cut Line= 4
      2728053.24      6931896.25      2727676.83      6931529.76
      2727426.07      6931403.51      2725875.97      6931761.01
#Sta/Elev= 30
  4199.4   467.2  4250.7  464.97  4335.4  463.48    4385  461.15  4420.3   461.1
  4689.2  455.87    4728  454.83  4748.1  452.75  4754.5  452.99  4770.5  451.06
  4782.4  451.19  4792.9  448.17  4797.1  446.04  4797.4  445.54  4801.1  446.04
  4815.3   452.2  4821.5  453.52  4839.3  453.51  4866.1  452.69  4994.4   452.7
  5364.8  454.66  5590.2   457.6  5652.1  459.61  6329.4  462.89  6473.1  464.74
  6493.6   465.8  6529.5  465.63  6534.7  467.15  6555.2  466.68  6596.3  468.07
#Mann= 5 ,-1 , 0
  4199.4     .05       0  4689.2     .12       0  4797.1     .05       0
  4801.1     .12       0  4839.3     .05       0
Bank Sta=4797.1,4801.1
XS Rating Curve= 0 ,0
Exp/Cntr=0.3,0.1

Type RM Length L Ch R = 1 ,9130    ,483,483,483
BEGIN DESCRIPTION:
Allen T3 9.0
END DESCRIPTION:
XS GIS Cut Line= 3
      2728358.52      6931508.03        2727676.        6931161.
      2726369.99      6931459.18
#Sta/Elev= 30
  4226.3  464.51  4442.3  464.49  4694.4  460.57  4894.7  454.27  4924.7     451
  4948.7  449.73  4983.7  447.22  4986.9   445.5  4987.4     445  4991.4   445.5
  5002.2   445.6  5010.9   447.9    5016  446.65  5022.8  450.55    5033  451.63
    5074  452.39    5145  451.01  5169.8  451.32  5176.6  451.99  5443.3  453.32
  5484.3  455.07  5515.1   454.6  5600.4  455.61  5729.3  458.55  5853.6   459.3
  5874.1  460.15  5911.5  459.76  6007.7  460.87  6045.6  460.43  6331.6  461.47
#Mann= 5 ,-1 , 0
  4226.3     .05       0  4948.7     .12       0  4986.9     .07       0
  4991.4     .12       0  5169.8     .05       0
Bank Sta=4986.9,4991.4
XS Rating Curve= 0 ,0
Exp/Cntr=0.3,0.1

Type RM Length L Ch R = 1 ,8647    ,503,503,503
BEGIN DESCRIPTION:
Mapping XS 31199c25
END DESCRIPTION:
XS GIS Cut Line= 3
      2728545.97       6931262.8      2727572.03      6930804.47
      2726311.62      6930788.85
#Sta/Elev= 30
  3927.2  461.14  4280.8  460.57  4302.9  461.32  4575.5   459.2  4723.3  455.66
  4766.8  453.77    4809  453.47  4905.7  449.22  4951.3  450.49  4976.8  450.18
  4988.2  450.16  5009.6  448.47  5017.4  444.16  5017.8  443.66  5021.9  444.16
  5039.6  447.79  5059.6  448.39  5069.6   450.4  5089.6  451.22  5129.6  450.72
  5159.6  449.06  5199.6  449.07  5239.6  450.81  5349.7  452.87  5369.7  453.96
  5699.7  457.26  5749.7  458.74  5819.7  458.06  5959.7  459.01  6264.1   459.1
#Mann= 5 ,-1 , 0
  3927.2     .05       0  4766.8     .12       0  4976.8     .05       0
  5017.4     .05       0  5021.9     .05       0
Bank Sta=5017.4,5021.9
XS Rating Curve= 0 ,0
Exp/Cntr=0.3,0.1

Type RM Length L Ch R = 1 ,8144    ,166,166,166
BEGIN DESCRIPTION:
Allen T3 7.0
END DESCRIPTION:
XS GIS Cut Line= 3
      2729098.54      6930544.14      2727676.01      6930428.69
      2726450.93      6930400.91
#Sta/Elev= 30
  3572.8  456.97  4458.2  457.13  4638.8  454.68  4668.9  455.47  4729.1  451.47
  4769.3  452.38  4829.5  451.53  4889.7  446.28  4929.8  447.31  4939.8  448.42
  4969.9  448.52  4979.9  446.84  4987.7  443.27  4988.2  442.77  4992.2  443.27
  4997.5  446.47    5010  447.72    5070  449.31  5260.1  449.14  5310.1  447.79
  5440.1  451.18  5480.1  453.21  5620.2  454.96  5800.2  455.89  5840.2  457.29
  5890.2  456.61  6170.3  457.86  6190.3  458.27  6210.3  461.39  6225.4  462.08
#Mann= 3 ,-1 , 0
  3572.8     .05       0  4987.7     .05       0  4992.2     .05       0
Bank Sta=4987.7,4992.2
XS Rating Curve= 0 ,0
Exp/Cntr=0.3,0.1

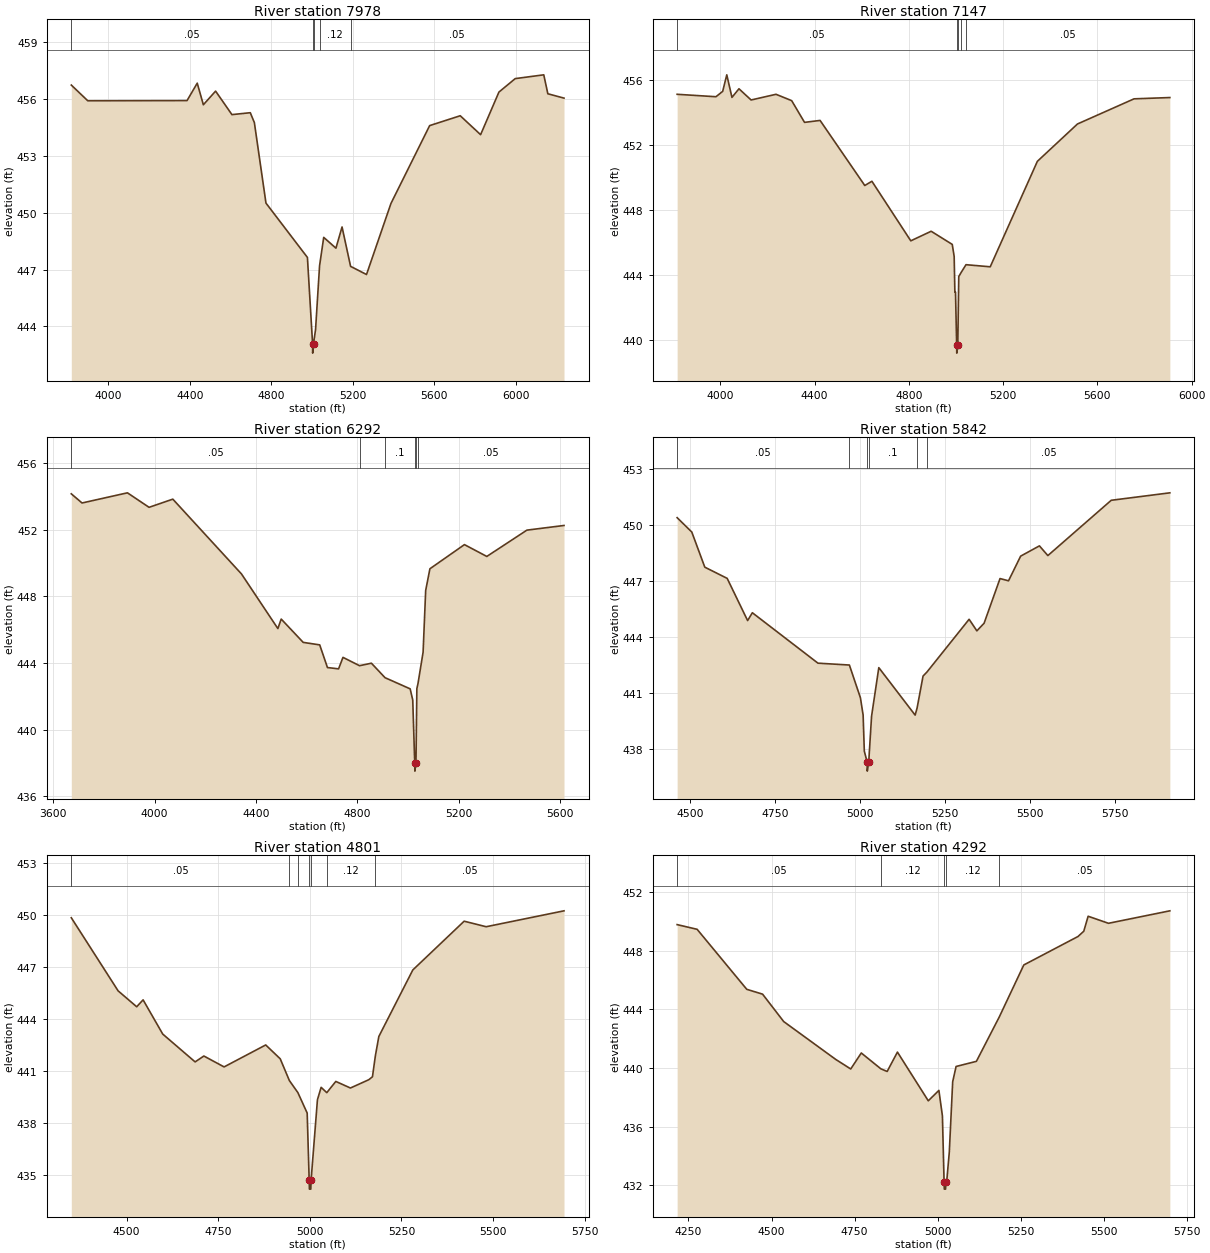
Type RM Length L Ch R = 1 ,7978    ,831,831,831
BEGIN DESCRIPTION:
Mapping XS ecdcce6c
END DESCRIPTION:
XS GIS Cut Line= 3
      2728853.28      6930330.51      2727665.78      6930262.81
      2726436.59      6930236.76
#Sta/Elev= 30
  3817.5  456.74  3898.4  455.91  4385.7  455.92  4435.8  456.84  4465.8   455.7
  4525.9  456.42  4606.1  455.18  4696.2  455.28  4716.2  454.76  4773.2  450.51
  4976.7  447.64    5002  443.09  5002.5  442.59  5006.6  443.09  5016.7  443.84
  5036.3   447.2  5056.7   448.7  5116.7  448.13  5146.7  449.25  5188.6  447.17
  5266.8  446.74  5386.8  450.49  5576.8   454.6  5726.9  455.12  5826.9  454.12
  5916.9  456.37  5996.9  457.08    6137  457.28    6157  456.28  6236.4  456.05
#Mann= 5 ,-1 , 0
  3817.5     .05       0    5002     .04       0  5006.6     .05       0
  5036.3     .12       0  5188.6     .05       0
Bank Sta=5002,5006.6
XS Rating Curve= 0 ,0
Exp/Cntr=0.3,0.1

Type RM Length L Ch R = 1 ,7147    ,855,855,855
BEGIN DESCRIPTION:
Mapping XS e5341979
END DESCRIPTION:
XS GIS Cut Line= 3
       2728547.5      6930156.03      2727475.46      6929665.58
      2726564.02      6929687.28
#Sta/Elev= 30
  3816.9  455.14  3981.6  454.99  4010.1  455.32  4027.5  456.34  4049.5  454.95
  4079.2  455.48  4130.7  454.79  4236.4  455.14  4302.8  454.75  4357.4  453.41
  4423.4  453.53    4613  449.52  4643.3  449.78  4808.3  446.11  4894.7   446.7
  4984.2  445.89  4992.3  445.15  4995.3  442.95    4998  442.95  5002.9  439.69
  5003.4  439.19  5007.7  439.69  5011.8  443.91  5021.9  444.16  5042.6  444.64
  5145.3  444.51  5345.4  451.01  5515.4  453.31  5755.5  454.86  5907.5  454.94
#Mann= 5 ,-1 , 0
  3816.9     .05       0  5002.9     .04       0  5007.7     .05       0
  5021.9     .12       0  5042.6     .05       0
Bank Sta=5002.9,5007.7
XS Rating Curve= 0 ,0
Exp/Cntr=0.3,0.1

Type RM Length L Ch R = 1 ,6292    ,450,450,450
BEGIN DESCRIPTION:
Mapping XS ecfabf57
END DESCRIPTION:
XS GIS Cut Line= 4
      2728456.37      6929700.31       2727713.8      6929139.35
      2727044.03      6929007.89      2726731.53      6929112.06
#Sta/Elev= 30
  3671.8  454.16  3714.1  453.61  3893.1  454.22  3978.4  453.35  4072.1  453.84
  4342.7  449.35  4486.2  446.07  4499.4  446.64  4586.1  445.24  4651.2  445.09
  4681.7  443.73  4725.6  443.65  4742.9  444.34  4808.3  443.84    4855  443.99
  4908.8  443.12  5007.8  442.45    5018  441.78  5025.8  438.01  5026.4  437.51
  5030.7  438.01  5034.2  442.46  5038.7  442.77  5058.8  444.65    5069  448.36
  5085.7  449.66  5221.8  451.11    5310   450.4  5468.1  451.98  5614.4  452.26
#Mann= 6 ,-1 , 0
  3671.8     .05       0  4808.3     .12       0  4908.8      .1       0
  5025.8     .07       0  5030.7      .1       0  5038.7     .05       0
Bank Sta=5025.8,5030.7
XS Rating Curve= 0 ,0
Exp/Cntr=0.3,0.1

Type RM Length L Ch R = 1 ,5842    ,1041,1041,1041
BEGIN DESCRIPTION:
Mapping XS 3d031234
END DESCRIPTION:
XS GIS Cut Line= 4
      2728050.94      6928456.69      2727564.87      6928717.09
      2727065.74      6928903.72       2726727.2      6929038.27
#Sta/Elev= 30
  4462.2  450.39  4505.3  449.62  4543.5  447.74  4609.3  447.14  4669.4  444.88
  4683.3   445.3  4876.2   442.6  4968.6   442.5    5001  440.75    5009  439.82
  5012.5  437.89  5020.6  437.32  5021.2  436.82  5025.5  437.32  5033.8  439.76
  5055.1  442.36  5161.9  439.82  5167.7   440.2  5185.2  441.91  5196.4  442.12
  5320.6  444.95  5343.4  444.33  5364.7  444.74  5411.5  447.13  5436.5  447.01
  5472.1  448.33  5527.3  448.88  5552.1  448.36  5738.4  451.32  5910.8  451.72
#Mann= 6 ,-1 , 0
  4462.2     .05       0  4968.6      .1       0  5020.6     .07       0
  5025.5      .1       0  5167.7     .12       0  5196.4     .05       0
Bank Sta=5020.6,5025.5
XS Rating Curve= 0 ,0
Exp/Cntr=0.3,0.1

Type RM Length L Ch R = 1 ,4801    ,509,509,509
BEGIN DESCRIPTION:
Mapping XS 72fb4212
END DESCRIPTION:
XS GIS Cut Line= 4
       2728011.9      6928369.86       2727686.4      6928313.44
      2727386.92      6928395.91      2726683.76      6928361.18
#Sta/Elev= 30
  4348.9  449.86  4476.7  445.63  4527.4  444.71  4544.9  445.11  4598.5  443.13
  4686.9  441.52  4710.8  441.86    4766  441.23  4879.6   442.5  4919.2   441.7
  4944.2  440.44  4967.5  439.74  4992.8  438.56  4998.3  434.66  4998.9  434.16
  5002.7  434.16  5003.4  434.66  5020.8  439.33  5030.9  440.05  5046.3  439.74
  5070.9  440.39  5110.9  440.01    5161  440.49    5171  440.66    5179  441.88
  5188.4  442.99  5281.2  446.84  5421.3  449.66  5481.4  449.34  5693.9  450.26
#Mann= 7 ,-1 , 0
  4348.9     .05       0  4944.2     .12       0  4967.5      .1       0
  4998.3     .07       0  5003.4      .1       0  5046.3     .12       0
    5179     .05       0
Bank Sta=4998.3,5003.4
XS Rating Curve= 0 ,0
Exp/Cntr=0.3,0.1

Type RM Length L Ch R = 1 ,4292    ,319,319,319
BEGIN DESCRIPTION:
Mapping XS 965cb80e
END DESCRIPTION:
XS GIS Cut Line= 3
       2728068.3      6928275.81      2727306.62      6928006.73
       2726644.7      6928134.77
#Sta/Elev= 30
    4216  449.77  4276.1  449.45  4425.4  445.36    4473  445.03  4536.6  443.16
  4693.1  440.58  4738.1  439.93  4769.9  441.02  4828.8  439.94  4847.7  439.76
  4878.6  441.08  4971.4  437.76  5003.3  438.47  5013.9  436.73  5018.9  432.24
  5019.6  431.74  5023.4  431.74    5024  432.24  5026.7  432.24  5034.6  434.26
  5044.8  439.06    5055   440.1  5116.1  440.45  5184.8  443.47  5258.7  447.02
  5421.7  448.96  5439.1  449.32  5452.2  450.34  5513.3  449.86    5698  450.71
#Mann= 5 ,-1 , 0
    4216     .05       0  4828.8     .12       0  5018.9     .07       0
    5024     .12       0  5184.8     .05       0
Bank Sta=5018.9,5024
XS Rating Curve= 0 ,0
Exp/Cntr=0.3,0.1

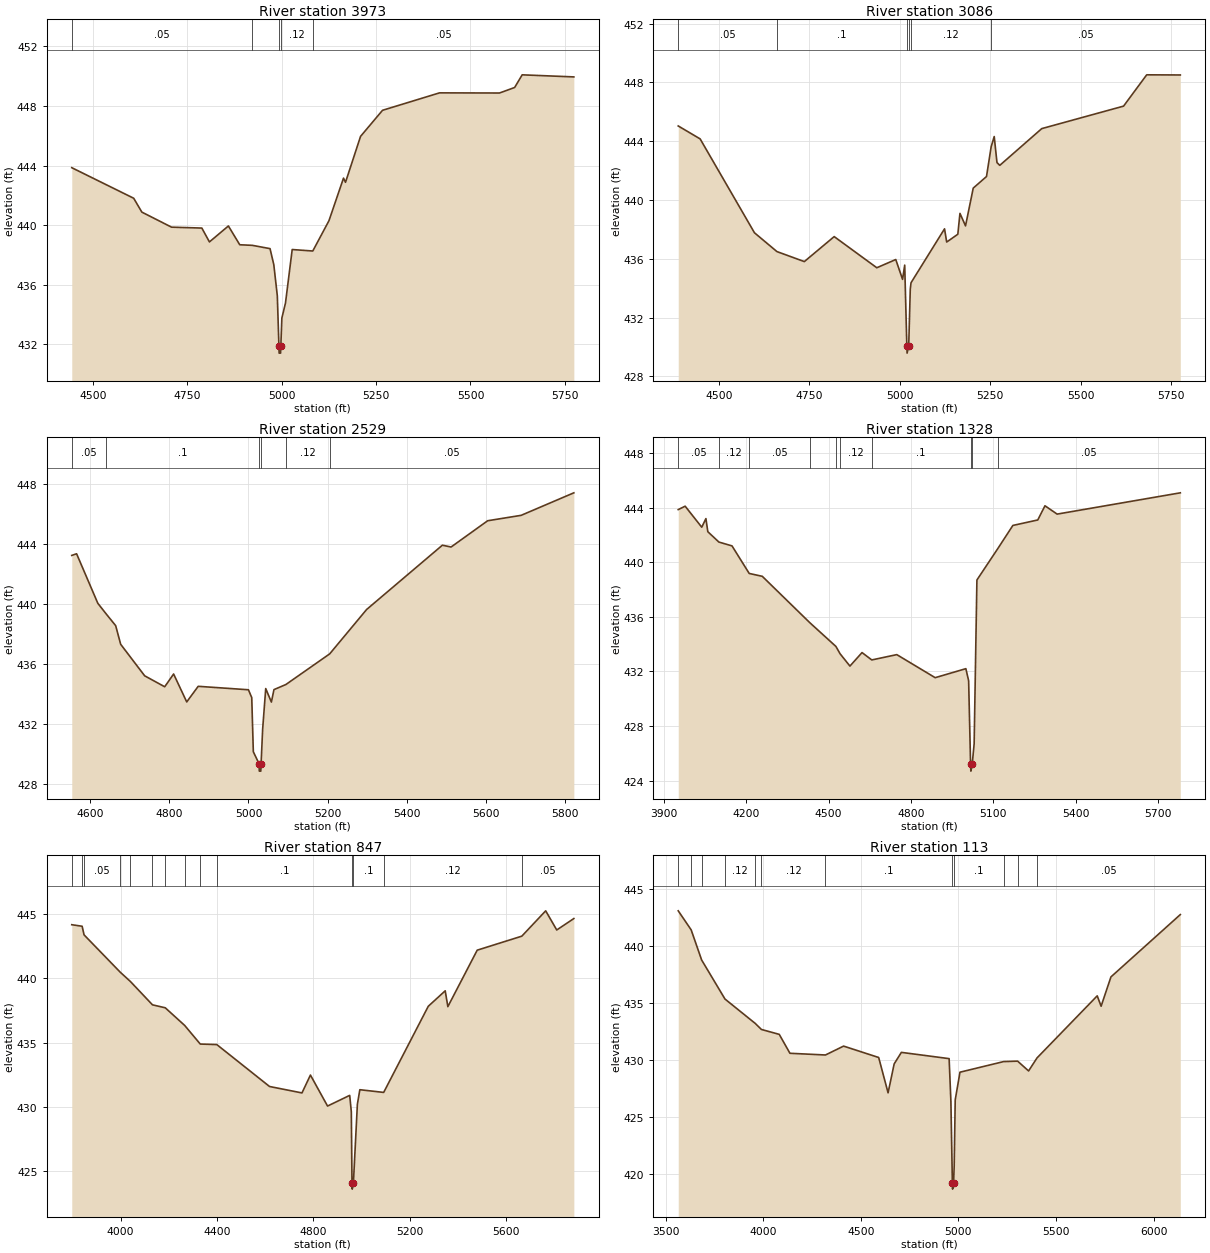
Type RM Length L Ch R = 1 ,3973    ,887,887,887
BEGIN DESCRIPTION:
Mapping XS 69037700
END DESCRIPTION:
XS GIS Cut Line= 3
      2727879.46      6927681.59       2727332.6      6927724.99
      2726586.12      6927955.01
#Sta/Elev= 30
  4444.1  443.86  4608.1  441.81  4629.7  440.88  4708.4  439.87  4788.6  439.81
  4808.7  438.88  4858.9  439.95    4889  438.69  4922.4  438.65  4969.2  438.43
  4979.2  437.35  4988.5  435.26  4992.7  431.92  4993.3  431.42  4997.1  431.42
  4997.8  431.92  5000.5  433.77  5010.1  434.78  5027.9  438.37  5082.4  438.27
  5125.2   440.3  5163.8  443.16  5169.1  442.88  5208.9  445.96  5267.1  447.71
  5418.1  448.88  5576.9  448.87    5617  449.24    5637  450.09  5773.8  449.95
#Mann= 5 ,-1 , 0
  4444.1     .05       0  4922.4     .12       0  4992.7     .07       0
  4997.8     .12       0  5082.4     .05       0
Bank Sta=4992.7,4997.8
XS Rating Curve= 0 ,0
Exp/Cntr=0.3,0.1

Type RM Length L Ch R = 1 ,3086    ,557,557,557
BEGIN DESCRIPTION:
Mapping XS 17ce7ac8
END DESCRIPTION:
XS GIS Cut Line= 3
      2727636.42      6926978.46      2727028.79      6927008.84
      2726620.89      6927672.76
#Sta/Elev= 30
  4387.5  445.04    4448  444.16  4598.2  437.77  4660.3  436.49    4736  435.81
  4818.5  437.51  4936.3  435.39  4988.7  435.95  5007.5   434.6  5013.4  435.57
  5019.3  430.08    5020  429.58  5024.5  430.08  5028.8  433.93  5030.9  434.37
  5123.5  438.04  5129.4  437.14  5160.2  437.67  5166.1  439.09  5181.5  438.24
  5202.8  440.81  5239.5   441.6  5252.3  443.62  5260.8  444.32  5268.4  442.55
  5276.2  442.36  5392.2  444.86  5618.3  446.39  5682.2  448.52  5775.1  448.51
#Mann= 6 ,-1 , 0
  4387.5     .05       0  4660.3      .1       0  5019.3     .07       0
  5024.5      .1       0  5030.9     .12       0  5252.3     .05       0
Bank Sta=5019.3,5024.5
XS Rating Curve= 0 ,0
Exp/Cntr=0.3,0.1

Type RM Length L Ch R = 1 ,2529    ,1201,1201,1201
BEGIN DESCRIPTION:
Mapping XS 9b753246
END DESCRIPTION:
XS GIS Cut Line= 3
        2727157.      6926445.63      2726743.77      6926647.04
      2726222.97      6927265.06
#Sta/Elev= 30
  4553.8  443.22    4566  443.33  4619.6  440.03  4640.5  439.33  4664.7  438.54
  4677.3   437.3  4737.9   435.2  4788.5  434.47    4811  435.32  4844.1  433.46
  4873.1   434.5  4999.9  434.27  5008.3  433.75  5012.3  430.14  5026.6  429.35
  5027.4  428.85  5031.2  428.85  5031.9  429.35  5035.8  431.63  5043.6  434.35
  5057.9  433.45  5064.4  434.28  5094.5  434.62  5205.1  436.66  5298.5  439.62
  5489.7   443.9  5511.7  443.78  5604.1  445.53  5688.6  445.89  5821.7  447.39
#Mann= 6 ,-1 , 0
  4553.8     .05       0  4640.5      .1       0  5026.6     .07       0
  5031.9      .1       0  5094.5     .12       0  5205.1     .05       0
Bank Sta=5026.6,5031.9
XS Rating Curve= 0 ,0
Exp/Cntr=0.3,0.1

Type RM Length L Ch R = 1 ,1328    ,481,481,481
BEGIN DESCRIPTION:
Mapping XS ee605ee2
END DESCRIPTION:
XS GIS Cut Line= 3
      2727115.33      6926386.63      2726195.16      6925903.98
      2725410.76      6925803.33
#Sta/Elev= 30
  3952.1  443.86  3977.3  444.11  4037.8  442.57    4053   443.2  4059.9  442.24
  4100.4  441.48  4148.1   441.2  4210.8  439.18  4258.4  438.97  4431.7  435.57
  4526.8  433.83  4542.1  433.29  4577.9  432.39    4622  433.38  4657.5  432.84
  4748.7  433.23  4888.6  431.54  5000.4   432.2  5010.5  431.32  5017.6  425.19
  5018.6  424.69  5023.5  425.19  5030.6  426.69  5040.7   438.7  5116.1  440.98
  5171.8   442.7  5262.5   443.1  5288.7  444.14  5333.1  443.53    5782  445.09
#Mann= 10 ,-1 , 0
  3952.1     .05       0  4100.4     .12       0  4210.8     .05       0
  4431.7     .12       0  4526.8     .05       0  4542.1     .12       0
  4657.5      .1       0  5017.6     .07       0  5023.5      .1       0
  5116.1     .05       0
Bank Sta=5017.6,5023.5
XS Rating Curve= 0 ,0
Exp/Cntr=0.3,0.1

Type RM Length L Ch R = 1 ,847     ,734,734,734
BEGIN DESCRIPTION:
Mapping XS bcd076e2
END DESCRIPTION:
XS GIS Cut Line= 3
      2727147.72      6926378.36       2726373.4      6925503.34
      2725470.85      6925343.66
#Sta/Elev= 30
  3797.3  444.18  3840.3  444.06  3848.4  443.39    3999  440.48    4040  439.78
  4132.5  437.95  4185.5  437.72  4266.1  436.35    4331   434.9  4399.6  434.86
  4618.6   431.6  4753.3   431.1  4788.4  432.49  4859.5  430.08  4951.5  430.91
  4958.2  429.64    4961  424.12    4962  423.62  4966.9  424.12  4983.4  430.22
  4993.6  431.35  5092.6  431.14  5277.9  437.84  5348.1  439.04  5359.1  437.81
    5481   442.2  5666.3  443.29  5765.4  445.26  5811.3  443.77  5882.3  444.66
#Mann= 14 ,-1 , 0
  3797.3     .05       0  3840.3     .12       0  3848.4     .05       0
    3999     .12       0    4040     .05       0  4132.5     .12       0
  4185.5     .05       0  4266.1     .12       0    4331     .05       0
  4399.6      .1       0    4961     .07       0  4966.9      .1       0
  5092.6     .12       0  5666.3     .05       0
Bank Sta=4961,4966.9
XS Rating Curve= 0 ,0
Exp/Cntr=0.3,0.1

Type RM Length L Ch R = 1 ,113     ,0,0,0
BEGIN DESCRIPTION:
Allen T3 1.0
END DESCRIPTION:
XS GIS Cut Line= 3
      2727189.96      6926362.34      2726724.47      6925005.04
       2725592.1      6924899.17
#Sta/Elev= 30
  3565.1  443.05  3631.3  441.38  3684.9  438.74  3804.6  435.31  3959.6  433.17
  3991.3  432.64  4082.6  432.21  4137.4  430.55  4319.4   430.4  4412.3  431.18
    4592  430.18  4640.2  427.08  4671.4  429.62  4708.3  430.63  4952.9  430.08
    4962  426.32  4969.6  419.13  4970.6  418.63  4975.6  419.13  4978.9  420.69
  4984.1  426.46  5008.5  428.89  5231.9  429.82  5303.9  429.86    5360     429
  5403.1  430.14  5711.6  435.59  5731.6  434.68  5781.9  437.25  6137.3  442.72
#Mann= 12 ,-1 , 0
  3565.1     .05       0  3631.3     .12       0  3684.9     .05       0
  3804.6     .12       0  3959.6      .1       0  3991.3     .12       0
  4319.4      .1       0  4969.6     .07       0  4975.6      .1       0
  5231.9     .12       0  5303.9      .1       0  5403.1     .05       0
Bank Sta=4969.6,4975.6
XS Rating Curve= 0 ,0
Exp/Cntr=0.3,0.1

Chan Stop Cuts=-1
Use User Specified Reach Order=0
Composite Channel Slope=5