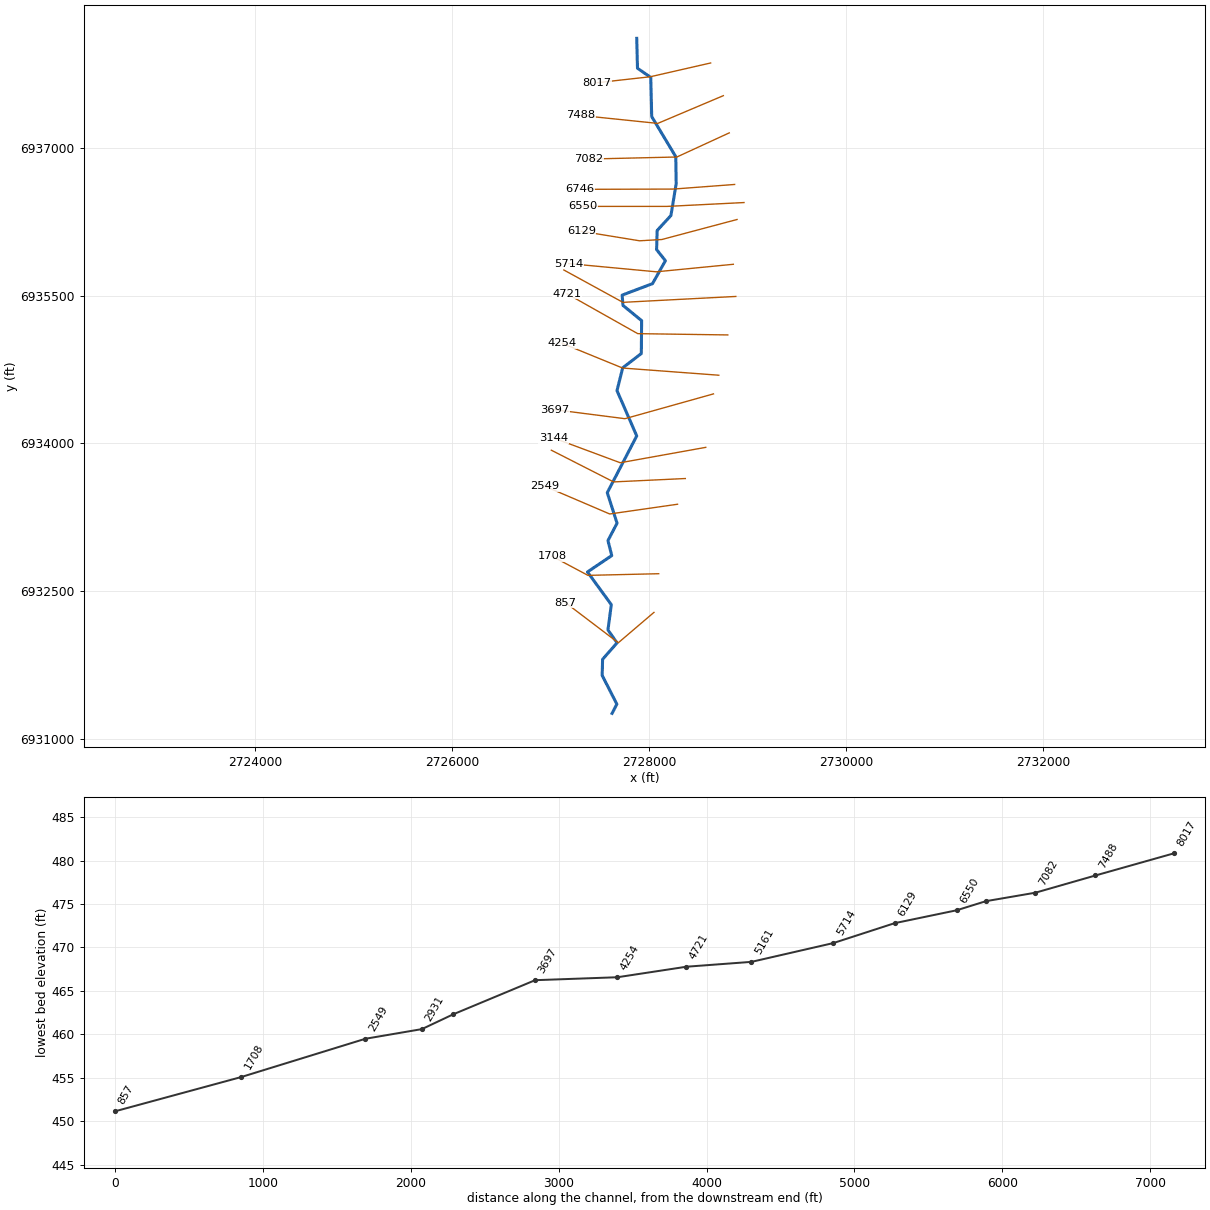
--- Allen T3_1.prj (project) ---

Proj Title=Allen T3_1 Base Level Engineering
Current Plan=p01
Default Exp/Contr=0.3,0.1
English Units
Geom File=g01
Flow File=f01
Plan File=p01
Y Axis Title=Elevation
X Axis Title(PF)=Main Channel Distance
X Axis Title(XS)=Station
BEGIN DESCRIPTION:
Allen T3_1
END DESCRIPTION:
DSS Export Rating Curves= 0
DSS Export Rating Curve Sorted= 0
DSS Export Volume Flow Curves= 0
DXF OffsetX= 0
DXF OffsetY= 0
DXF ScaleX= 1
DXF ScaleY= 10

--- Allen T3_1.p01 (plan) ---

Plan Title=Multiple Run
Short Identifier=Multiple
Geom File=g01
Flow File=f01
Subcritical Flow
K Sum by GR= 0
Std Step Tol= 0.01
Critical Tol= 0.01
Num of Std Step Trials= 20
Max Error Tol= 0.3
Flow Tol Ratio= 0.001
Split Flow NTrial= 30
Split Flow Tol= 0.02
Split Flow Ratio= 0.02
Log Output Level= 0
Friction Slope Method= 1
Unsteady Friction Slope Method= 2
Unsteady Bridges Friction Slope Method= 1
Parabolic Critical Depth
Global Vel Dist=  1 , 1 , 1
Global Log Level= 0
CheckData=True
Encroach Param= -1, 0, 0, 0
BEGIN DESCRIPTION:
Multiple Run
END DESCRIPTION:

--- Allen T3_1.f01 (steady flow) ---

Flow Title=Multiple
Program Version=4.10
Number of Profiles= 7
Profile Names=10-year,25-year,50-year,1pct_min,100-year,1pct_plu,500-year
River Rch & RM=Allen T3_1,Reach-1         ,8017
     281     354     409     236     470     938     617
River Rch & RM=Allen T3_1,Reach-1         ,5161
     442     573     677     396     791    1578    1078
Boundary for River Rch & Prof#=Allen T3_1,Reach-1         , 1
Up Type= 0
Dn Type= 3
Dn Slope=0.00529
Boundary for River Rch & Prof#=Allen T3_1,Reach-1         , 2
Up Type= 0
Dn Type= 3
Dn Slope=0.00529
Boundary for River Rch & Prof#=Allen T3_1,Reach-1         , 3
Up Type= 0
Dn Type= 3
Dn Slope=0.00529
Boundary for River Rch & Prof#=Allen T3_1,Reach-1         , 4
Up Type= 0
Dn Type= 3
Dn Slope=0.00529
Boundary for River Rch & Prof#=Allen T3_1,Reach-1         , 5
Up Type= 0
Dn Type= 3
Dn Slope=0.00529
Boundary for River Rch & Prof#=Allen T3_1,Reach-1         , 6
Up Type= 0
Dn Type= 3
Dn Slope=0.00529
Boundary for River Rch & Prof#=Allen T3_1,Reach-1         , 7
Up Type= 0
Dn Type= 3
Dn Slope=0.00529
DSS Import GetInterval= 0
DSS Import GetPeak= 0
DSS Import FillOption= 0

--- Allen T3_1.g01 (geometry) ---

Geom Title=Existing Conditions
Program Version=4.10

River Reach=Allen T3_1      ,Reach-1
Reach XY= 30
        2727876.        6938111.      2727883.72      6937807.34
      2728018.28      6937714.66      2728028.06      6937316.86
      2728272.45      6936909.53       2728276.2      6936635.92
      2728222.84      6936312.65      2728083.35      6936161.09
      2728077.64      6935967.04      2728167.02      6935854.34
      2728036.06      6935621.61      2727727.87      6935505.31
      2727736.42      6935401.19       2727925.8      6935245.91
      2727922.48      6934912.46       2727733.7      6934767.47
      2727675.77      6934536.07       2727876.1      6934076.36
      2727577.11      6933500.45       2727676.4      6933190.87
      2727584.05      6933014.32      2727622.63      6932862.28
      2727376.18      6932695.91       2727618.2      6932364.42
      2727584.01      6932107.67      2727676.11      6931976.36
      2727529.54      6931809.54      2727525.51       6931645.8
      2727674.24      6931354.94        2727626.        6931261.

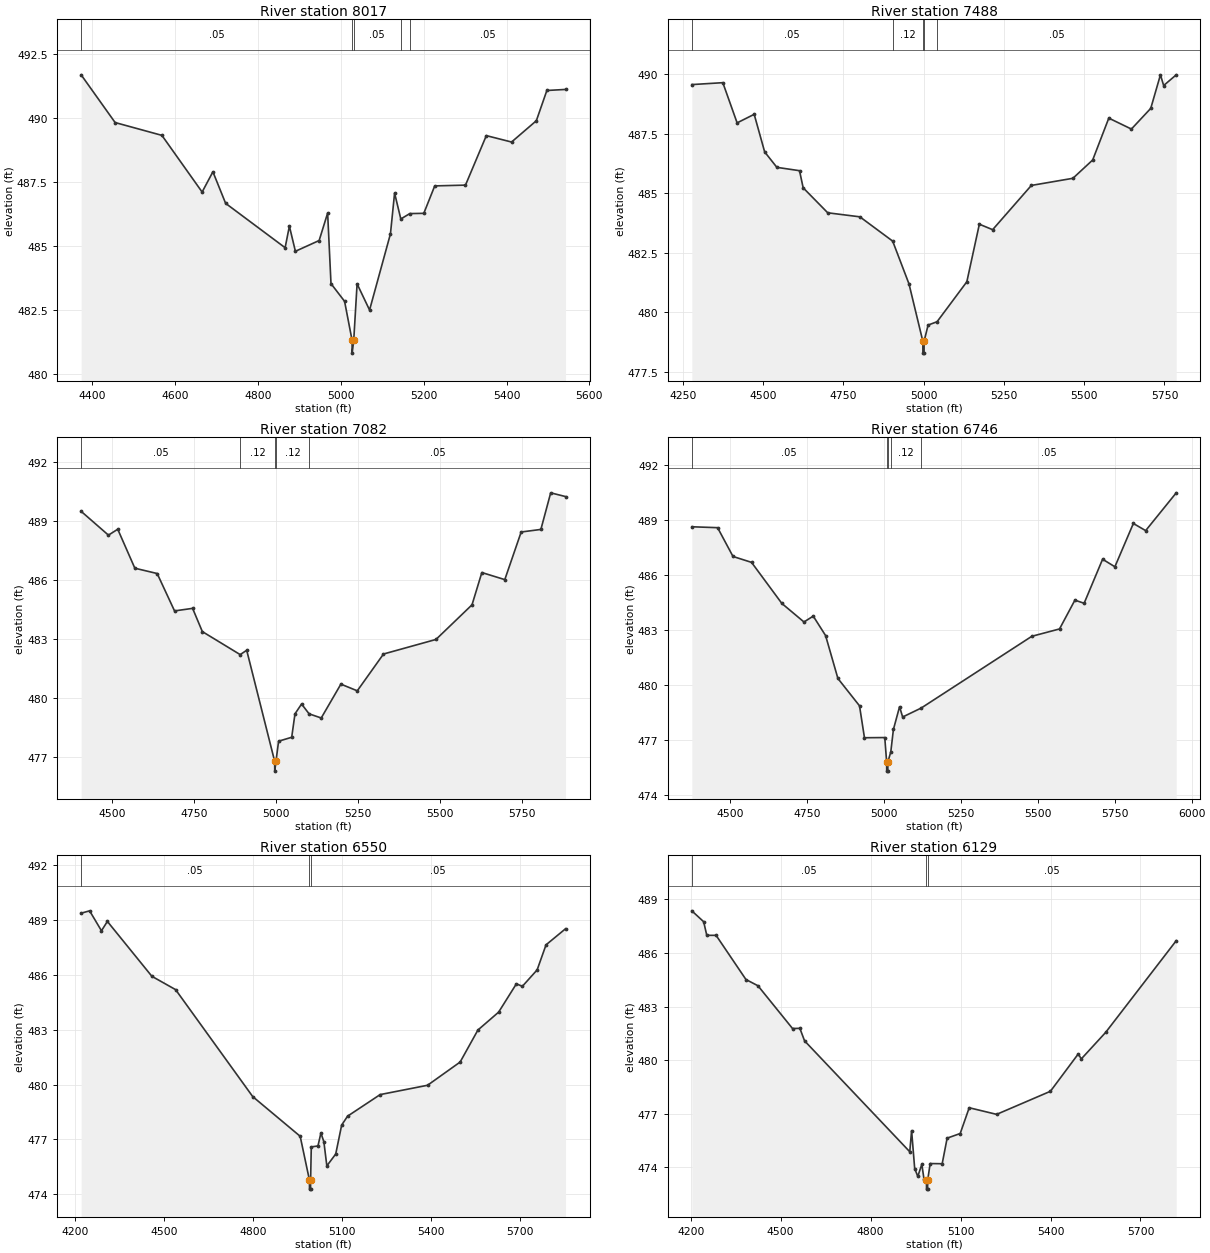
Type RM Length L Ch R = 1 ,8017    ,529,529,529
BEGIN DESCRIPTION:
Allen T3_1 9.0
END DESCRIPTION:
XS GIS Cut Line= 3
      2728625.96      6937860.99      2728015.01      6937721.37
      2727475.98        6937661.
#Sta/Elev= 30
  4373.3  491.67  4455.3  489.81  4568.2  489.31  4665.3   487.1  4691.3  487.89
    4722  486.66  4865.6  484.93  4875.9  485.77  4890.4  484.79  4947.7  485.21
  4968.2  486.28  4976.3  483.53  5009.1  482.84  5027.2  481.32  5027.4  480.82
  5031.2  481.32  5039.3  483.52  5069.4   482.5  5119.8  485.47  5129.8  487.06
  5144.8  486.05  5166.5  486.26  5200.3  486.27  5226.7  487.34  5300.9  487.37
  5351.2   489.3  5412.1  489.05  5471.9  489.88  5497.3  491.06  5542.4   491.1
#Mann= 5 ,-1 , 0
  4373.3     .05       0  5027.2     .04       0  5031.2     .05       0
  5144.8     .12       0  5166.5     .05       0
Bank Sta=5027.2,5031.2
XS Rating Curve= 0 ,0
Exp/Cntr=0.3,0.1

Type RM Length L Ch R = 1 ,7488    ,406,406,406
BEGIN DESCRIPTION:
Allen T3_1 8.0
END DESCRIPTION:
XS GIS Cut Line= 3
      2728754.96      6937529.28      2728089.57      6937247.76
      2727307.04      6937328.74
#Sta/Elev= 30
  4277.5  489.57  4374.1  489.65  4418.6  487.96  4471.8  488.32  4504.4  486.74
  4542.5  486.09    4613  485.95  4624.4  485.23  4700.9  484.18  4801.1  484.01
  4903.2  482.99  4954.1  481.19  4997.2  478.78  4997.5  478.28    5001  478.28
  5001.2  478.78  5013.6  479.46  5041.6   479.6  5134.3  481.28  5173.3   483.7
  5214.7  483.47  5335.3  485.33  5464.8  485.63  5526.4   486.4  5576.6  488.16
    5647   487.7  5707.3  488.57  5737.5  489.98  5747.5  489.53  5786.7  489.98
#Mann= 5 ,-1 , 0
  4277.5     .05       0  4903.2     .12       0  4997.2     .07       0
  5001.2     .12       0  5041.6     .05       0
Bank Sta=4997.2,5001.2
XS Rating Curve= 0 ,0
Exp/Cntr=0.3,0.1

Type RM Length L Ch R = 1 ,7082    ,336,336,336
BEGIN DESCRIPTION:
Mapping XS ebf3e6ec
END DESCRIPTION:
XS GIS Cut Line= 3
      2728814.84      6937151.67      2728283.58      6936906.87
      2727390.67      6936886.05
#Sta/Elev= 30
  4404.9   489.5  4488.2  488.29  4516.6  488.59  4568.8  486.61  4636.9  486.34
  4689.9  484.44    4745  484.57  4774.7  483.39  4890.2  482.22  4910.1  482.44
  4995.4   476.8  4995.7   476.3  4999.4   476.8  5007.4  477.82  5047.4  478.02
  5057.4  479.21  5077.5  479.71  5100.5  479.21  5137.5     479  5197.5  480.72
  5247.5  480.38  5327.5  482.25  5487.6  482.99  5597.6  484.75  5627.6  486.39
  5697.6  486.03  5747.6  488.45  5807.7  488.58  5837.7  490.44    5883  490.25
#Mann= 5 ,-1 , 0
  4404.9     .05       0  4890.2     .12       0  4995.4     .07       0
  4999.4     .12       0  5100.5     .05       0
Bank Sta=4995.4,4999.4
XS Rating Curve= 0 ,0
Exp/Cntr=0.3,0.1

Type RM Length L Ch R = 1 ,6746    ,196,196,196
BEGIN DESCRIPTION:
Allen T3_1 7.0
END DESCRIPTION:
XS GIS Cut Line= 3
      2728869.54      6936628.23      2728247.12      6936581.35
      2727296.61      6936578.75
#Sta/Elev= 30
  4375.2  488.64    4459  488.59  4509.1  487.02  4569.3   486.7  4667.9  484.46
  4739.8  483.45  4769.9  483.77    4810  482.71  4850.1  480.37  4920.3  478.88
  4936.4  477.14  5002.4  477.15  5008.5  475.82  5008.8  475.32  5012.3  475.32
  5012.5  475.82    5022  476.37  5030.5  477.59  5050.5  478.83  5060.5  478.27
    5121  478.76  5480.5  482.67  5570.5  483.07  5620.5  484.64  5650.5  484.47
  5710.5  486.87  5750.5  486.46  5810.5  488.82  5850.5  488.43  5949.9  490.49
#Mann= 5 ,-1 , 0
  4375.2     .05       0  5008.5     .04       0  5012.5     .05       0
    5022     .12       0    5121     .05       0
Bank Sta=5008.5,5012.5
XS Rating Curve= 0 ,0
Exp/Cntr=0.3,0.1

Type RM Length L Ch R = 1 ,6550    ,421,421,421
BEGIN DESCRIPTION:
Allen T3_1 6.0
END DESCRIPTION:
XS GIS Cut Line= 3
      2728964.53      6936444.63      2728185.93      6936405.57
      2727330.11      6936405.57
#Sta/Elev= 30
  4219.5  489.37  4248.1   489.5  4288.1  488.41  4308.1  488.92  4458.3  485.92
  4538.4  485.19  4798.8  479.34    4959  477.17  4990.2  474.78  4990.5  474.28
    4994  474.28  4994.2  474.78  4996.5  476.59    5019  476.64    5029  477.35
    5039  476.87    5049  475.55    5079   476.2    5099  477.78    5119  478.27
    5229  479.45    5389  479.96    5499  481.23    5559  482.98    5629  483.96
    5689  485.51    5709  485.37    5759  486.27    5789  487.64  5854.9  488.52
#Mann= 3 ,-1 , 0
  4219.5     .05       0  4990.2     .04       0  4994.2     .05       0
Bank Sta=4990.2,4994.2
XS Rating Curve= 0 ,0
Exp/Cntr=0.3,0.1

Type RM Length L Ch R = 1 ,6129    ,415,415,415
BEGIN DESCRIPTION:
Mapping XS 8f517789
END DESCRIPTION:
XS GIS Cut Line= 4
      2728894.22      6936272.75      2728131.24      6936069.63
      2727904.68      6936056.61      2727313.56      6936152.96
#Sta/Elev= 30
  4203.8  488.35  4243.3  487.74  4253.7  486.98  4284.7  486.98  4384.3  484.51
  4424.4  484.16  4539.6  481.77  4564.1  481.78  4579.8  481.08  4930.6  474.88
  4936.7  476.06    4947  473.94  4957.4   473.5  4970.8  474.18  4978.1  473.34
  4986.3  473.29  4986.5  472.79    4990  472.79  4990.3  473.29  4998.6  474.22
  5038.7  474.21  5055.2  475.64  5098.8   475.9  5128.8  477.34  5220.3  476.97
  5399.6  478.26  5492.5  480.35  5502.6  480.07  5583.7  481.55  5819.2  486.68
#Mann= 3 ,-1 , 0
  4203.8     .05       0  4986.3     .04       0  4990.3     .05       0
Bank Sta=4986.3,4990.3
XS Rating Curve= 0 ,0
Exp/Cntr=0.3,0.1

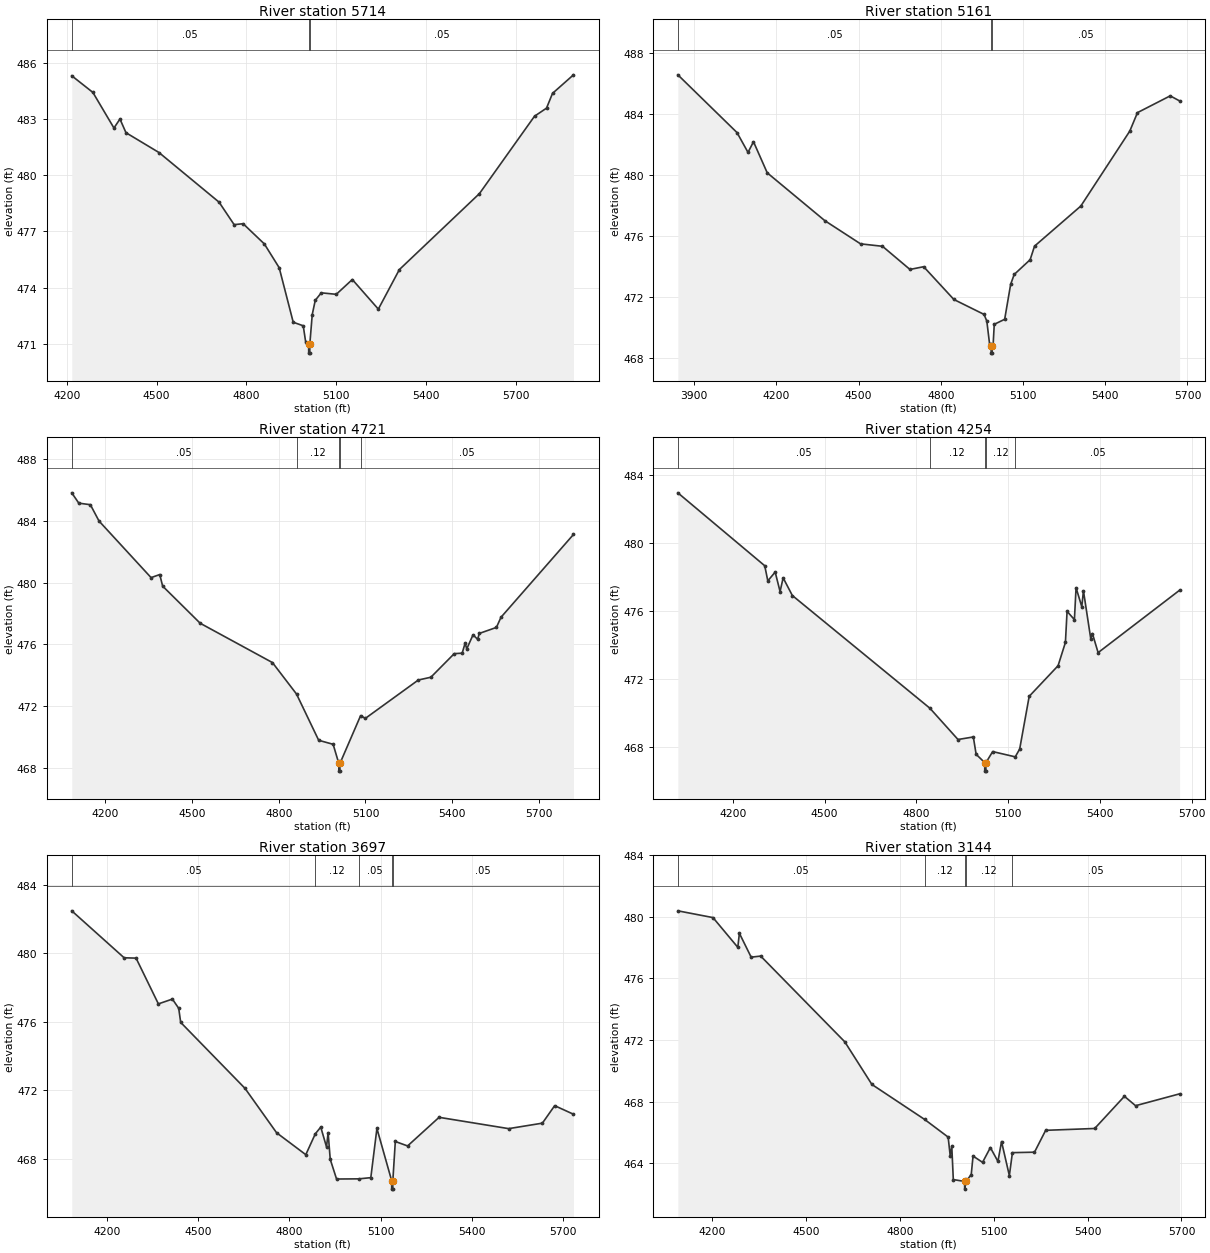
Type RM Length L Ch R = 1 ,5714    ,553,553,553
BEGIN DESCRIPTION:
Mapping XS b7406e7b
END DESCRIPTION:
XS GIS Cut Line= 3
      2728856.41      6935818.24      2728075.16      6935741.85
      2727186.23      6935825.19
#Sta/Elev= 30
  4216.1  485.31  4286.8  484.42  4357.2  482.52  4377.3     483  4397.4  482.27
  4507.9  481.21  4708.8  478.56  4759.1  477.36  4789.2  477.41  4860.2  476.33
  4909.8  475.06  4956.7  472.15  4990.2  471.96  4998.1  471.12  5008.3     471
  5008.5   470.5    5012   470.5  5012.3     471  5020.3  472.56  5030.4  473.32
  5050.5  473.72  5100.7  473.64  5154.3  474.43  5241.3  472.85  5311.6  474.96
  5579.5  479.02  5763.6  483.15  5803.7  483.58  5823.8  484.37  5893.9  485.36
#Mann= 3 ,-1 , 0
  4216.1     .05       0  5008.3     .04       0  5012.3     .05       0
Bank Sta=5008.3,5012.3
XS Rating Curve= 0 ,0
Exp/Cntr=0.3,0.1

Type RM Length L Ch R = 1 ,5161    ,440,440,440
BEGIN DESCRIPTION:
Mapping XS 54b41be5
END DESCRIPTION:
XS GIS Cut Line= 3
      2728881.62      6935491.86      2727735.75      6935431.96
      2727136.77       6935760.1
#Sta/Elev= 30
  3840.8   486.6  4056.7  482.81  4096.8  481.51  4116.8  482.21  4166.9  480.17
  4377.1  477.03  4507.3  475.51  4587.4  475.35  4687.6  473.83  4737.6  474.01
  4847.8  471.86  4957.9  470.88    4968  470.44    4978  468.95  4983.6  468.84
  4983.9  468.34  4987.4  468.34  4987.6  468.84  4990.9  468.84  4995.1  470.23
  5033.1  470.56  5054.9  472.85  5067.8   473.5    5126  474.47  5142.1  475.36
  5310.9  477.99  5489.6  482.91  5517.6  484.12    5637  485.22  5671.2  484.89
#Mann= 3 ,-1 , 0
  3840.8     .05       0  4983.6     .04       0  4987.6     .05       0
Bank Sta=4983.6,4987.6
XS Rating Curve= 0 ,0
Exp/Cntr=0.3,0.1

Type RM Length L Ch R = 1 ,4721    ,467,467,467
BEGIN DESCRIPTION:
Mapping XS 62b7eb03
END DESCRIPTION:
XS GIS Cut Line= 3
      2728800.43      6935101.23      2727886.36      6935114.25
      2727170.24      6935517.88
#Sta/Elev= 30
  4083.7  485.83  4108.1  485.16  4148.1  485.06  4178.1     484  4358.2  480.33
  4388.2  480.53  4398.2  479.78  4528.2  477.37  4778.2  474.82  4861.5  472.78
  4938.2  469.78  4988.2  469.52  5007.8  468.28    5008  467.78  5011.5  467.78
  5011.8  468.28  5083.3  471.38  5099.6   471.2    5283  473.69  5326.4  473.87
  5407.3   475.4  5434.7  475.43  5444.9  476.08  5450.6  475.71  5472.3  476.62
  5488.2  476.33  5493.9  476.71  5553.2   477.1  5569.1  477.76  5819.9  483.13
#Mann= 5 ,-1 , 0
  4083.7     .05       0  4861.5     .12       0  5007.8     .07       0
  5011.8     .12       0  5083.3     .05       0
Bank Sta=5007.8,5011.8
XS Rating Curve= 0 ,0
Exp/Cntr=0.3,0.1

Type RM Length L Ch R = 1 ,4254    ,557,557,557
BEGIN DESCRIPTION:
Mapping XS 21df5f28
END DESCRIPTION:
XS GIS Cut Line= 3
      2728709.28      6934692.38      2727732.71      6934765.29
      2727120.88      6935015.23
#Sta/Elev= 30
  4020.4  482.94  4304.5  478.65  4314.5  477.76  4338.6  478.28  4354.6  477.13
  4364.6  477.94  4394.7   476.9  4844.4  470.27  4936.2  468.43  4986.4  468.58
  4995.5  467.56  5023.6  467.07  5023.8  466.57  5027.3  466.57  5027.6  467.07
  5049.6  467.72  5123.4  467.41  5137.9  467.87    5169  470.97  5263.4  472.77
  5287.4  474.14  5292.8  475.97  5316.8  475.48  5322.2  477.36  5340.9  476.24
  5346.3  477.18  5370.3  474.35  5375.7  474.66  5394.3  473.54  5660.6  477.21
#Mann= 5 ,-1 , 0
  4020.4     .05       0  4844.4     .12       0  5023.6     .07       0
  5027.6     .12       0  5123.4     .05       0
Bank Sta=5023.6,5027.6
XS Rating Curve= 0 ,0
Exp/Cntr=0.3,0.1

Type RM Length L Ch R = 1 ,3697    ,553,553,553
BEGIN DESCRIPTION:
Mapping XS c8178fc5
END DESCRIPTION:
XS GIS Cut Line= 3
      2728654.86      6934503.05      2727756.39      6934251.31
      2727044.58      6934342.45
#Sta/Elev= 30
  4084.1  482.47  4256.4  479.73  4295.7  479.71  4369.1  477.04  4415.2  477.32
    4436  476.78  4442.5  475.96  4654.1  472.11    4758  469.52  4854.1  468.24
  4885.5  469.46  4903.3  469.85  4922.3  468.69  4927.5  469.53  4934.5  467.97
  4955.3  466.82    5029  466.83    5068   466.9  5088.1  469.77  5136.5  466.73
  5136.8  466.23  5140.3  466.23  5140.5  466.73  5148.6  469.01    5189  468.75
  5292.6  470.42  5521.6  469.76  5632.5  470.08  5672.9   471.1  5734.8   470.6
#Mann= 5 ,-1 , 0
  4084.1     .05       0  4885.5     .12       0    5029     .05       0
  5136.5     .07       0  5140.5     .05       0
Bank Sta=5136.5,5140.5
XS Rating Curve= 0 ,0
Exp/Cntr=0.3,0.1

Type RM Length L Ch R = 1 ,3144    ,213,213,213
BEGIN DESCRIPTION:
Mapping XS c09eb091
END DESCRIPTION:
XS GIS Cut Line= 3
      2728576.67       6933960.5      2727708.64      6933804.26
       2727031.6      6934055.98
#Sta/Elev= 30
  4089.6  480.39    4202  479.95  4281.3  478.02  4286.4  478.93    4324  477.38
  4354.5  477.45  4623.4  471.88  4710.1  469.11  4878.5  466.84  4953.9  465.69
  4960.4  464.49  4965.5   465.1  4970.4  462.93  5006.5  462.81  5006.8  462.31
  5010.5  462.81  5027.7  463.25  5033.5  464.46  5063.9  464.05  5088.9  465.01
  5113.1  464.11  5124.6   465.4  5149.6  463.19  5159.4  464.68    5230  464.71
  5265.7  466.13  5422.5  466.25  5517.5  468.34  5553.2  467.73  5693.9   468.5
#Mann= 5 ,-1 , 0
  4089.6     .05       0  4878.5     .12       0  5006.5     .07       0
  5010.5     .12       0  5159.4     .05       0
Bank Sta=5006.5,5010.5
XS Rating Curve= 0 ,0
Exp/Cntr=0.3,0.1

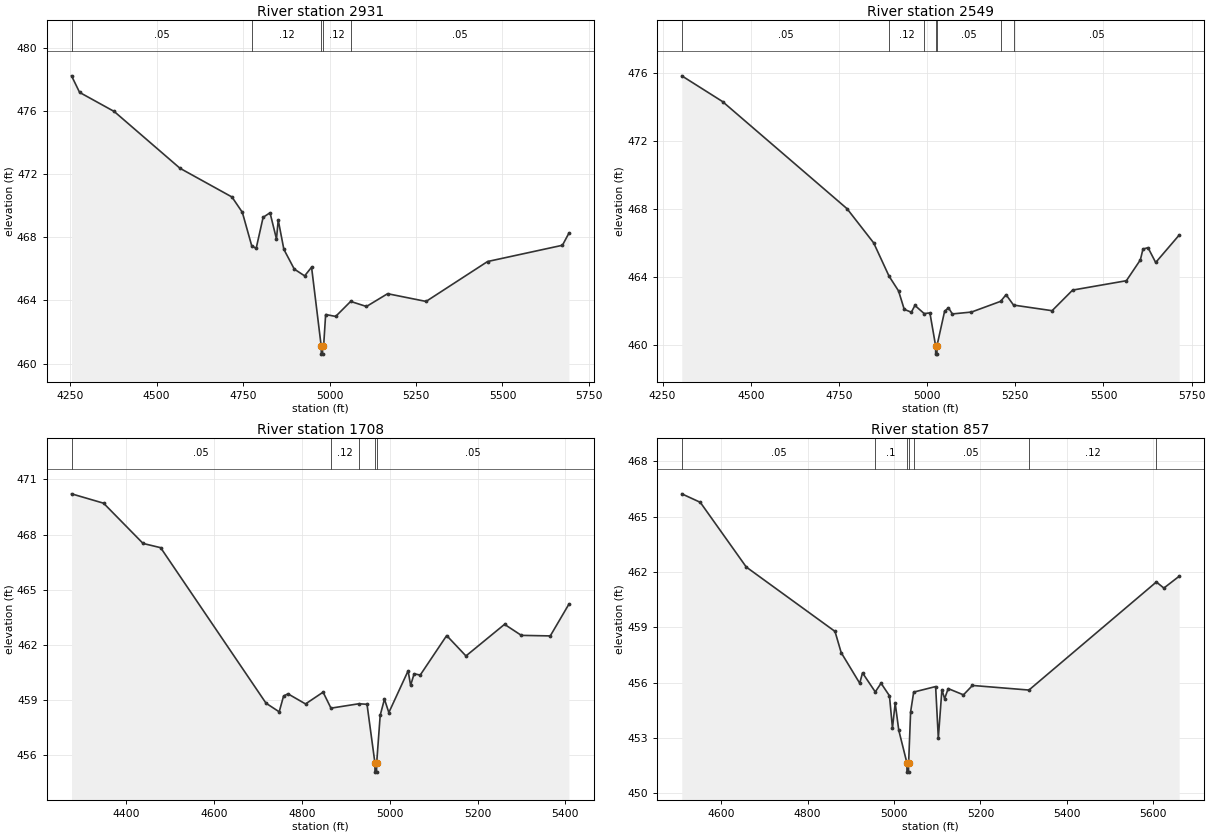
Type RM Length L Ch R = 1 ,2931    ,382,382,382
BEGIN DESCRIPTION:
Mapping XS a5299a4d
END DESCRIPTION:
XS GIS Cut Line= 3
      2728369.25      6933644.16      2727641.26      6933609.74
      2727009.22      6933931.66
#Sta/Elev= 30
    4254  478.24  4277.3  477.19  4377.4  475.98  4567.6  472.38  4717.8  470.56
  4747.8  469.59  4774.9  467.47  4787.8   467.3  4807.9  469.27  4827.9  469.56
  4846.5   467.9  4851.6   469.1  4867.9  467.24    4898  465.99    4928  465.56
    4948  466.11  4975.9   461.1  4976.2   460.6  4979.7   460.6  4979.9   461.1
  4982.8   461.1  4988.7  463.11  5017.7  462.99    5061  463.94  5106.7  463.62
  5167.8  464.43    5279  463.94  5456.9  466.47  5673.3   467.5  5692.1  468.27
#Mann= 5 ,-1 , 0
    4254     .05       0  4774.9     .12       0  4975.9     .07       0
  4979.9     .12       0    5061     .05       0
Bank Sta=4975.9,4979.9
XS Rating Curve= 0 ,0
Exp/Cntr=0.3,0.1

Type RM Length L Ch R = 1 ,2549    ,841,841,841
BEGIN DESCRIPTION:
Mapping XS aee293fe
END DESCRIPTION:
XS GIS Cut Line= 3
      2728290.28      6933383.26      2727601.85      6933284.36
      2726944.78      6933565.53
#Sta/Elev= 30
  4304.5  475.83    4420  474.32    4773  468.03  4848.6  466.02  4892.1  464.07
  4919.1   463.2  4935.2  462.12  4955.4  461.95  4965.5  462.35  4991.8  461.87
    5008  461.91  5024.1  459.99  5024.4  459.49  5027.9  459.49  5028.1  459.99
  5049.7  462.01  5060.7  462.21  5071.6  461.85  5125.9  461.96  5208.6  462.59
  5223.9  462.98  5245.1  462.37  5354.4  462.04  5412.6  463.25    5565   463.8
  5604.6  465.02  5612.1  465.66  5626.4  465.74  5648.1  464.87  5714.7  466.48
#Mann= 7 ,-1 , 0
  4304.5     .05       0  4892.1     .12       0  4991.8     .05       0
  5024.1     .05       0  5028.1     .05       0  5208.6     .12       0
  5245.1     .05       0
Bank Sta=5024.1,5028.1
XS Rating Curve= 0 ,0
Exp/Cntr=0.3,0.1

Type RM Length L Ch R = 1 ,1708    ,851,851,851
BEGIN DESCRIPTION:
Mapping XS c9cfe4df
END DESCRIPTION:
XS GIS Cut Line= 3
      2728098.98      6932678.23      2727381.55      6932661.38
      2727014.66      6932856.55
#Sta/Elev= 30
  4275.1  470.22  4348.1  469.71  4438.1  467.52  4478.1  467.29  4718.2  458.83
  4748.2  458.36  4758.2  459.22  4768.2  459.34  4808.2  458.79  4848.2  459.43
  4866.2  458.56  4929.8   458.8  4948.3  458.77  4966.3  455.58  4966.5  455.08
    4970  455.08  4970.3  455.58  4978.3  458.17    4988  459.05    4998  458.32
  5041.9  460.59  5047.6   459.8  5055.6  460.43  5069.5  460.36  5129.8  462.51
  5173.7   461.4  5261.6  463.12  5299.9  462.52  5365.8  462.49  5408.3  464.22
#Mann= 5 ,-1 , 0
  4275.1     .05       0  4866.2     .12       0  4929.8     .05       0
  4966.3     .04       0  4970.3     .05       0
Bank Sta=4966.3,4970.3
XS Rating Curve= 0 ,0
Exp/Cntr=0.3,0.1

Type RM Length L Ch R = 1 ,857     ,0,0,0
BEGIN DESCRIPTION:
Allen T3_1 1.0
END DESCRIPTION:
XS GIS Cut Line= 3
      2728050.98      6932285.98      2727688.99      6931977.52
      2727150.99      6932386.01
#Sta/Elev= 30
  4508.8  466.24  4551.6  465.78  4658.1  462.27  4863.4  458.78  4877.7  457.63
  4920.6  455.97  4927.1  456.53  4956.6   455.5    4970  455.97  4989.4  455.29
  4996.4  453.54  5002.7  454.89    5011  453.42  5029.8  451.65    5030  451.15
  5033.5  451.15  5033.8  451.65  5038.4  454.42  5045.5  455.49  5096.3  455.79
  5102.5  452.99  5110.8  455.62  5117.1  455.13  5125.3  455.68  5160.7  455.34
  5181.5  455.85  5312.2   455.6  5607.1  461.46  5624.5  461.13  5659.9  461.77
#Mann= 7 ,-1 , 0
  4508.8     .05       0  4956.6      .1       0  5029.8     .04       0
  5033.8      .1       0  5045.5     .05       0  5312.2     .12       0
  5607.1     .05       0
Bank Sta=5029.8,5033.8
XS Rating Curve= 0 ,0
Exp/Cntr=0.3,0.1

Chan Stop Cuts=-1
Use User Specified Reach Order=0
Composite Channel Slope=5