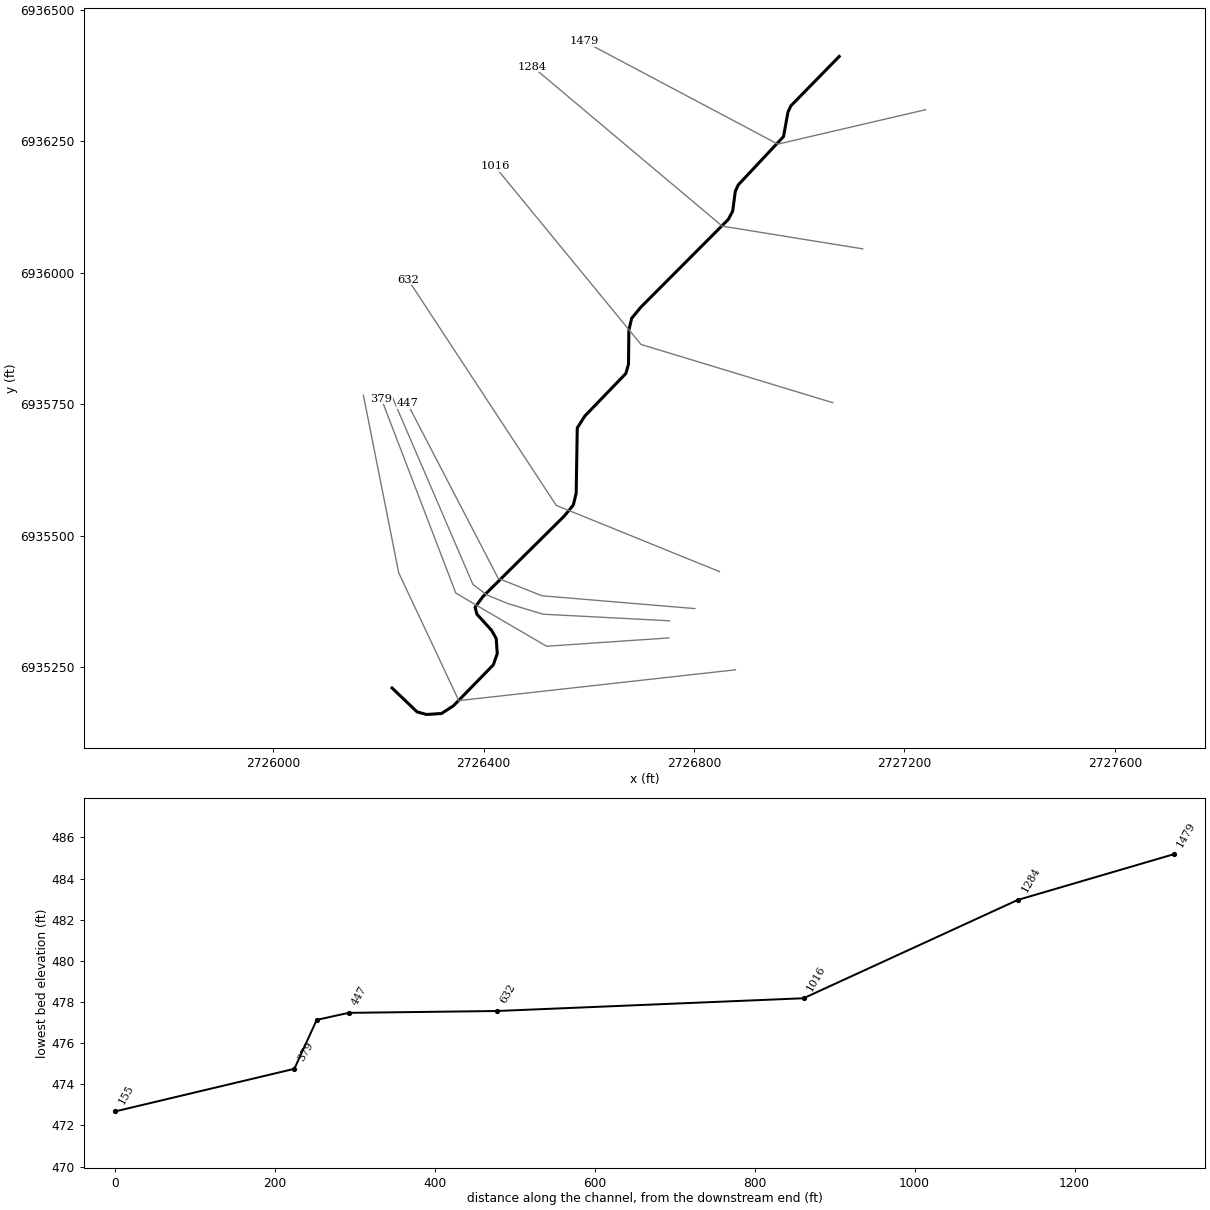
--- Allen T3_2.prj (project) ---

Proj Title=Allen T3_2 Base Level Engineering
Current Plan=p01
Default Exp/Contr=0.3,0.1
English Units
Geom File=g01
Flow File=f01
Plan File=p01
BEGIN DESCRIPTION:
Allen T3_2
END DESCRIPTION:

--- Allen T3_2.p01 (plan) ---

Plan Title=Multiple Run
Short Identifier=Multiple
Geom File=g01
Flow File=f01
Subcritical Flow
K Sum by GR= 0
Std Step Tol= 0.01
Critical Tol= 0.01
Num of Std Step Trials= 20
Max Error Tol= 0.3
Flow Tol Ratio= 0.001
Split Flow NTrial= 30
Split Flow Tol= 0.02
Split Flow Ratio= 0.02
Log Output Level= 0
Friction Slope Method= 1
Unsteady Friction Slope Method= 2
Unsteady Bridges Friction Slope Method= 1
Parabolic Critical Depth
Global Vel Dist=  1 , 1 , 1
Global Log Level= 0
CheckData=True
Encroach Param= -1, 0, 0, 0
BEGIN DESCRIPTION:
Multiple Run
END DESCRIPTION:

--- Allen T3_2.f01 (steady flow) ---

Flow Title=Multiple
Number of Profiles=7
Profile Names=10-year,25-year,50-year,1pct_min,100-year,1pct_plu,500-year
River Rch & RM= Allen T3_2,Reach-1,1479
      70      79      86      46      92     184     106
Boundary for River Rch & Prof#=Allen T3_2,Reach-1,1
Up Type=0
Dn Type=3
Dn Slope=0.005
Boundary for River Rch & Prof#=Allen T3_2,Reach-1,2
Up Type=0
Dn Type=3
Dn Slope=0.005
Boundary for River Rch & Prof#=Allen T3_2,Reach-1,3
Up Type=0
Dn Type=3
Dn Slope=0.005
Boundary for River Rch & Prof#=Allen T3_2,Reach-1,4
Up Type=0
Dn Type=3
Dn Slope=0.005
Boundary for River Rch & Prof#=Allen T3_2,Reach-1,5
Up Type=0
Dn Type=3
Dn Slope=0.005
Boundary for River Rch & Prof#=Allen T3_2,Reach-1,6
Up Type=0
Dn Type=3
Dn Slope=0.005
Boundary for River Rch & Prof#=Allen T3_2,Reach-1,7
Up Type=0
Dn Type=3
Dn Slope=0.005

--- Allen T3_2.g01 (geometry) ---

Geom Title=Existing Conditions

River Reach=Allen T3_2,Reach-1
Reach XY= 30
      2727076.00      6936411.00      2726984.11      6936317.07
      2726978.52      6936304.96      2726970.14      6936258.71
      2726884.18      6936167.04      2726878.54      6936154.95
      2726873.47      6936117.05      2726865.22      6936101.32
      2726698.88      6935934.52      2726681.52      6935913.43
      2726676.13      6935890.94      2726675.47      6935826.22
      2726670.46      6935808.58      2726592.47      6935727.75
      2726578.08      6935705.14      2726576.02      6935580.99
      2726570.53      6935558.55      2726553.14      6935537.47
      2726398.46      6935384.36      2726383.82      6935364.41
      2726387.39      6935351.13      2726415.07      6935320.68
      2726424.01      6935304.95      2726425.99      6935276.36
      2726418.51      6935254.93      2726342.73      6935177.22
      2726320.04      6935162.53      2726291.44      6935160.67
      2726273.65      6935165.57      2726226.00      6935211.00

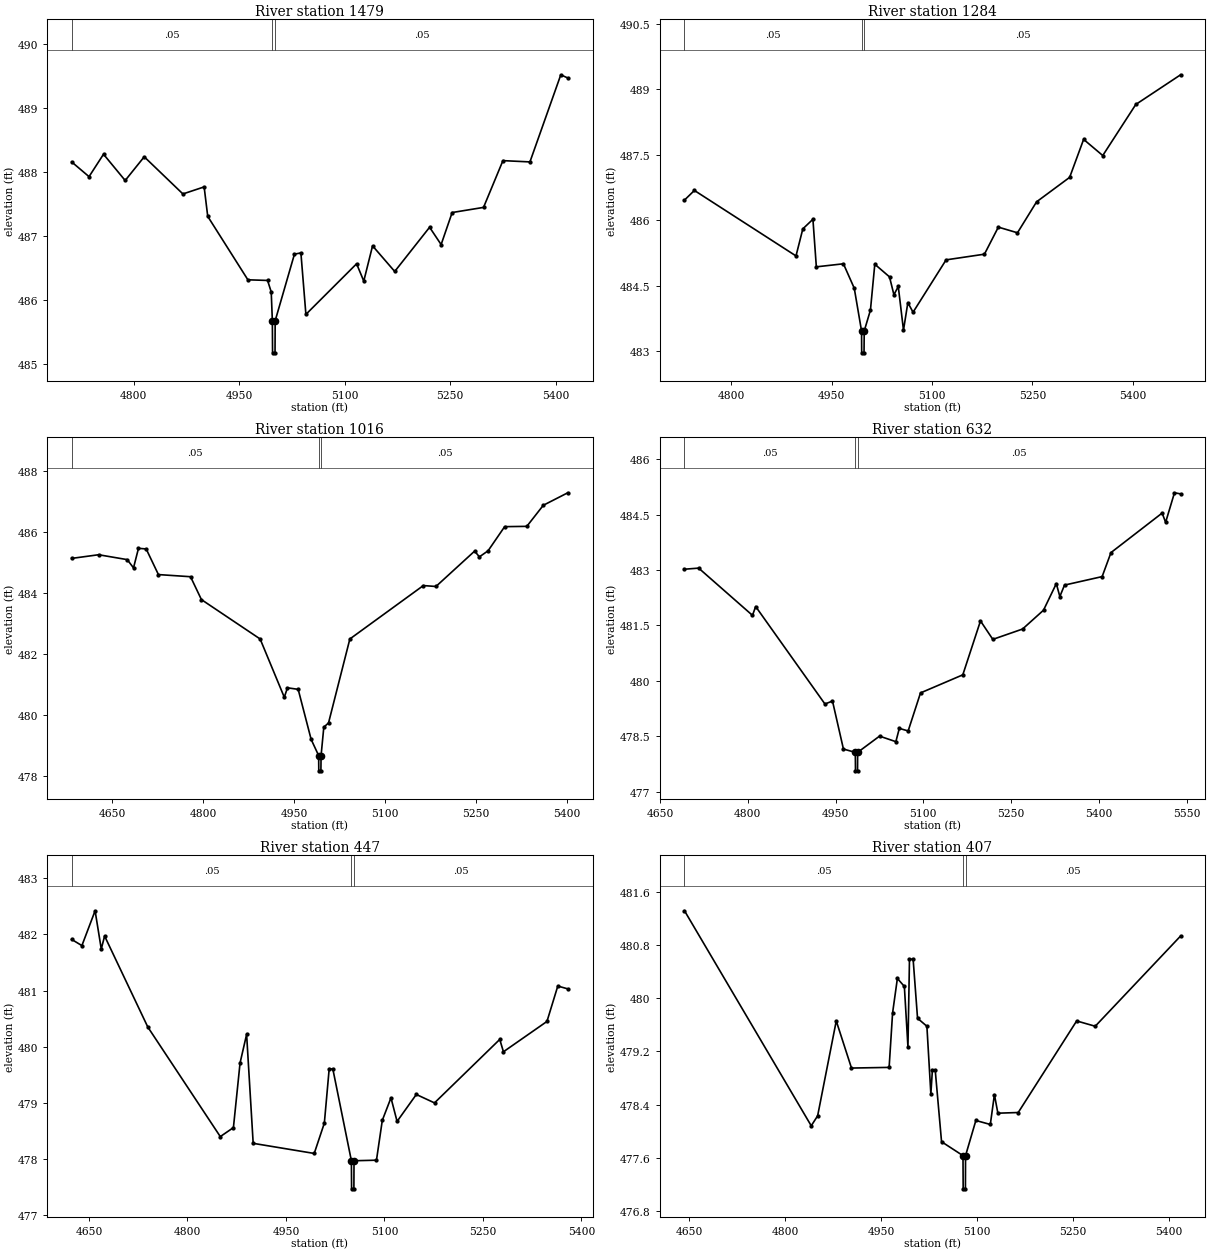
Type RM Length L Ch R = 1,1479,195,195,195
BEGIN DESCRIPTION:
Allen T3_2 1.0
END DESCRIPTION:
XS GIS Cut Line= 3
      2727240.10      6936309.76      2726959.32      6936244.34
      2726590.74      6936439.79
#Sta/Elev= 30
  4711.7  488.16  4736.4  487.93  4757.0  488.28  4787.8  487.87  4814.9  488.24
  4869.9  487.66  4900.1  487.77  4905.2  487.31  4962.3  486.32  4990.3  486.31
  4995.5  486.13  4997.1  485.68  4997.4  485.18  5000.9  485.18  5001.1  485.68
  5028.5  486.72  5037.7  486.74  5044.8  485.78  5116.9  486.57  5127.1  486.30
  5139.6  486.85  5171.1  486.45  5220.7  487.14  5237.1  486.87  5252.8  487.37
  5297.4  487.45  5325.0  488.18  5363.4  488.16  5407.3  489.52  5417.2  489.47
#Mann=3,-1,0
  4711.7    0.05       0  4997.1    0.04       0  5001.1    0.05       0
Bank Sta=4997.1,5001.1
Exp/Cntr=0.3,0.1

Type RM Length L Ch R = 1,1284,268,268,268
BEGIN DESCRIPTION:
Mapping XS 427bffb1
END DESCRIPTION:
XS GIS Cut Line= 3
      2727120.60      6936045.39      2726853.69      6936088.49
      2726492.86      6936391.73
#Sta/Elev= 30
  4729.8  486.46  4744.6  486.68  4896.5  485.18  4906.7  485.80  4921.8  486.02
  4926.9  484.93  4967.4  485.00  4983.6  484.44  4994.5  483.46  4994.7  482.96
  4998.2  482.96  4998.5  483.46  5007.8  483.94  5014.3  484.99  5036.3  484.70
  5042.9  484.29  5049.4  484.48  5057.2  483.48  5063.7  484.11  5071.5  483.89
  5120.9  485.09  5178.2  485.22  5199.0  485.84  5227.6  485.71  5256.2  486.42
  5305.6  486.98  5326.5  487.85  5355.1  487.48  5404.5  488.65  5471.5  489.33
#Mann=3,-1,0
  4729.8    0.05       0  4994.5    0.04       0  4998.5    0.05       0
Bank Sta=4994.5,4998.5
Exp/Cntr=0.3,0.1

Type RM Length L Ch R = 1,1016,384,384,384
BEGIN DESCRIPTION:
Mapping XS 1471f938
END DESCRIPTION:
XS GIS Cut Line= 3
      2727063.73      6935753.10      2726699.17      6935863.78
      2726421.39      6936202.31
#Sta/Elev= 30
  4582.8  485.14  4627.3  485.26  4674.5  485.10  4684.9  484.83  4693.1  485.47
  4705.8  485.45  4726.0  484.61  4779.0  484.54  4797.0  483.79  4893.9  482.50
  4933.8  480.59  4939.0  480.90  4956.7  480.85  4978.1  479.21  4990.5  478.68
  4990.7  478.18  4994.2  478.18  4994.5  478.68  4999.0  479.61  5006.8  479.75
  5042.0  482.50  5163.3  484.25  5184.1  484.22  5248.0  485.38  5255.8  485.19
  5270.2  485.39  5297.5  486.18  5334.1  486.19  5361.3  486.88  5401.7  487.29
#Mann=3,-1,0
  4582.8    0.05       0  4990.5    0.04       0  4994.5    0.05       0
Bank Sta=4990.5,4994.5
Exp/Cntr=0.3,0.1

Type RM Length L Ch R = 1,632,185,185,185
BEGIN DESCRIPTION:
Mapping XS bbedf3c2
END DESCRIPTION:
XS GIS Cut Line= 3
      2726848.38      6935432.18      2726538.08      6935558.03
      2726256.56      6935986.82
#Sta/Elev= 30
  4691.9  483.02  4716.1  483.05  4808.1  481.77  4813.5  482.01  4931.9  479.37
  4944.8  479.45  4963.5  478.15  4983.8  478.06  4984.1  477.56  4987.6  477.56
  4987.8  478.06  5025.2  478.50  5053.1  478.35  5059.0  478.71  5074.1  478.64
  5095.2  479.67  5167.5  480.16  5197.7  481.62  5218.8  481.12  5269.6  481.40
  5305.4  481.91  5327.3  482.63  5333.3  482.28  5341.3  482.59  5405.6  482.82
  5420.7  483.47  5508.1  484.54  5514.1  484.29  5529.2  485.09  5539.7  485.06
#Mann=3,-1,0
  4691.9    0.05       0  4983.8    0.04       0  4987.8    0.05       0
Bank Sta=4983.8,4987.8
Exp/Cntr=0.3,0.1

Type RM Length L Ch R = 1,447,40,40,40
BEGIN DESCRIPTION:
Mapping XS 367b0372
END DESCRIPTION:
XS GIS Cut Line= 4
      2726801.58      6935361.86      2726510.93      6935386.22
      2726427.76      6935419.34      2726255.17      6935751.71
#Sta/Elev= 30
  4623.6  481.91  4639.2  481.80  4659.3  482.42  4668.7  481.74  4673.8  481.97
  4739.6  480.35  4850.0  478.40  4870.0  478.56  4880.1  479.71  4890.1  480.22
  4900.1  478.28  4993.1  478.10  5008.5  478.64  5015.9  479.61  5021.5  479.60
  5049.7  477.97  5050.0  477.47  5053.5  477.47  5053.7  477.97  5087.9  477.98
  5096.8  478.69  5110.0  479.09  5119.3  478.67  5148.6  479.15  5176.3  479.00
  5275.7  480.13  5281.3  479.91  5347.6  480.45  5364.1  481.08  5379.3  481.03
#Mann=3,-1,0
  4623.6    0.05       0  5049.7    0.04       0  5053.7    0.05       0
Bank Sta=5049.7,5053.7
Exp/Cntr=0.3,0.1

Type RM Length L Ch R = 1,407,28,28,28
BEGIN DESCRIPTION:
Mapping XS 2d2a8fd5
END DESCRIPTION:
XS GIS Cut Line= 6
      2726753.70      6935338.67      2726512.85      6935351.20
      2726445.36      6935371.69      2726406.53      6935387.67
      2726379.70      6935407.82      2726226.31      6935764.04
#Sta/Elev= 30
  4642.9  481.32  4840.9  478.08  4850.9  478.23  4880.0  479.66  4903.8  478.95
  4962.6  478.96  4968.0  479.78  4975.5  480.30  4986.4  480.18  4992.0  479.27
  4994.4  480.59  5000.1  480.59  5007.0  479.70  5021.6  479.58  5027.8  478.56
  5030.2  478.92  5034.6  478.92  5044.5  477.84  5078.0  477.63  5078.3  477.13
  5081.8  477.13  5082.0  477.63  5098.1  478.16  5120.7  478.10  5127.1  478.55
  5132.5  478.27  5164.3  478.28  5255.6  479.66  5284.6  479.58  5418.0  480.94
#Mann=3,-1,0
  4642.9    0.05       0  5078.0    0.04       0  5082.0    0.05       0
Bank Sta=5078,5082
Exp/Cntr=0.3,0.1

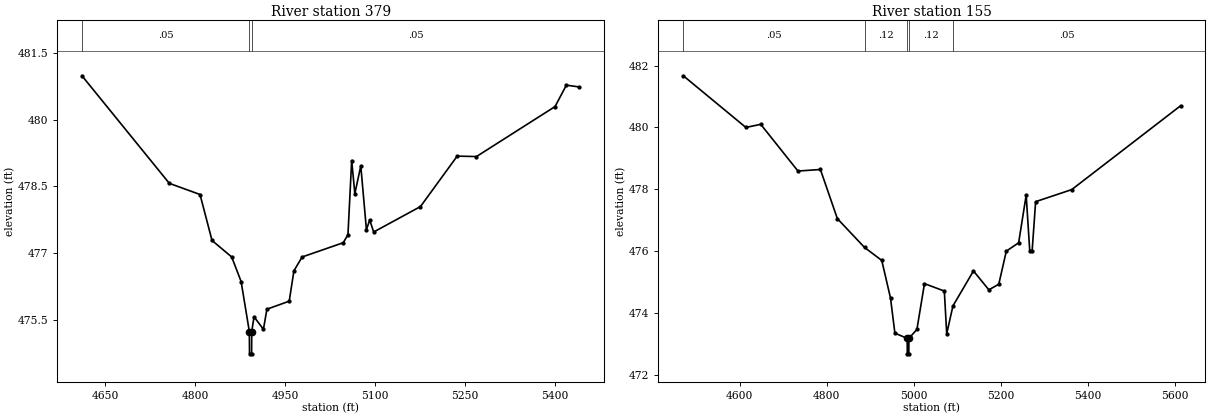
Type RM Length L Ch R = 1,379,224,224,224
BEGIN DESCRIPTION:
Mapping XS 3a5778ec
END DESCRIPTION:
XS GIS Cut Line= 5
      2726752.35      6935306.16      2726519.77      6935290.31
      2726387.23      6935367.73      2726347.12      6935391.47
      2726205.52      6935760.95
#Sta/Elev= 30
  4611.6  480.98  4757.2  478.57  4808.4  478.32  4828.4  477.29  4861.2  476.92
  4876.9  476.37  4890.6  475.25  4890.9  474.75  4894.4  474.75  4894.6  475.25
  4898.4  475.58  4914.1  475.30  4919.9  475.75  4957.1  475.93  4964.9  476.61
  4978.6  476.92  5047.2  477.24  5055.0  477.42  5061.2  479.08  5066.5  478.34
  5076.4  478.96  5085.8  477.53  5091.2  477.75  5097.9  477.48  5175.9  478.05
  5237.1  479.18  5269.2  479.17  5400.2  480.29  5419.1  480.77  5440.5  480.73
#Mann=3,-1,0
  4611.6    0.05       0  4890.6    0.04       0  4894.6    0.05       0
Bank Sta=4890.6,4894.6
Exp/Cntr=0.3,0.1

Type RM Length L Ch R = 1,155,0,0,0
BEGIN DESCRIPTION:
Allen T3_2 0.0
END DESCRIPTION:
XS GIS Cut Line= 4
      2726878.76      6935245.53      2726352.90      6935187.04
      2726238.61      6935430.00      2726171.58      6935767.30
#Sta/Elev= 30
  4470.9  481.67  4614.5  480.00  4648.7  480.10  4734.1  478.59  4785.6  478.64
  4824.6  477.05  4886.9  476.12  4926.5  475.70  4946.6  474.48  4956.6  473.35
  4984.8  473.18  4985.1  472.68  4988.6  472.68  4988.8  473.18  5007.2  473.47
  5024.5  474.95  5070.1  474.71  5075.6  473.33  5089.9  474.23  5137.0  475.36
  5172.3  474.75  5195.1  474.93  5212.4  476.00  5240.7  476.27  5258.0  477.81
  5266.3  475.99  5271.6  475.99  5279.7  477.60  5362.6  477.99  5612.4  480.70
#Mann=5,-1,0
  4470.9    0.05       0  4886.9    0.12       0  4984.8    0.07       0
  4988.8    0.12       0  5089.9    0.05       0
Bank Sta=4984.8,4988.8
Exp/Cntr=0.3,0.1

Chan Stop Cuts=-1