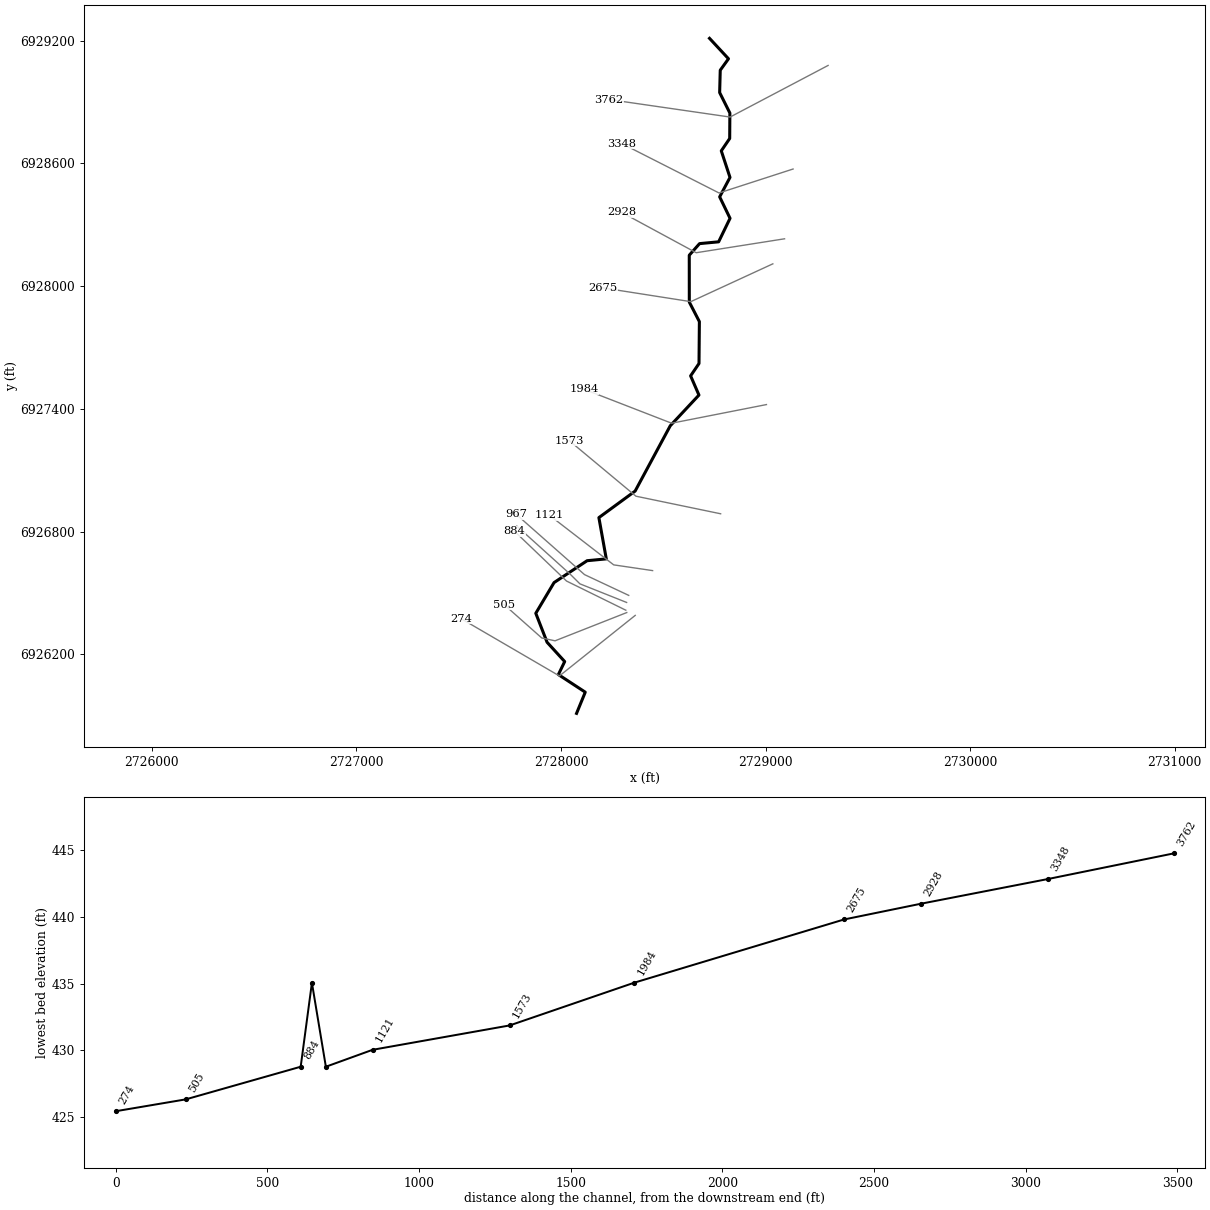
--- Allen T4.prj (project) ---

Proj Title=Allen T4 Base Level Engineering
Current Plan=p01
Default Exp/Contr=0.3,0.1
English Units
Geom File=g01
Flow File=f01
Plan File=p01
BEGIN DESCRIPTION:
Allen T4
END DESCRIPTION:

--- Allen T4.p01 (plan) ---

Plan Title=Multiple Run
Short Identifier=Multiple
Geom File=g01
Flow File=f01
Subcritical Flow
K Sum by GR= 0
Std Step Tol= 0.01
Critical Tol= 0.01
Num of Std Step Trials= 20
Max Error Tol= 0.3
Flow Tol Ratio= 0.001
Split Flow NTrial= 30
Split Flow Tol= 0.02
Split Flow Ratio= 0.02
Log Output Level= 0
Friction Slope Method= 1
Unsteady Friction Slope Method= 2
Unsteady Bridges Friction Slope Method= 1
Parabolic Critical Depth
Global Vel Dist=  1 , 1 , 1
Global Log Level= 0
CheckData=True
Encroach Param= -1, 0, 0, 0
BEGIN DESCRIPTION:
Multiple Run
END DESCRIPTION:

--- Allen T4.f01 (steady flow) ---

Flow Title=Multiple
Number of Profiles=7
Profile Names=10-year,25-year,50-year,1pct_min,100-year,1pct_plu,500-year
River Rch & RM= Allen T4,Reach-1,3762
     349     446     520     302     602    1202     805
Boundary for River Rch & Prof#=Allen T4,Reach-1,1
Up Type=0
Dn Type=3
Dn Slope=0.005
Boundary for River Rch & Prof#=Allen T4,Reach-1,2
Up Type=0
Dn Type=3
Dn Slope=0.005
Boundary for River Rch & Prof#=Allen T4,Reach-1,3
Up Type=0
Dn Type=3
Dn Slope=0.005
Boundary for River Rch & Prof#=Allen T4,Reach-1,4
Up Type=0
Dn Type=3
Dn Slope=0.005
Boundary for River Rch & Prof#=Allen T4,Reach-1,5
Up Type=0
Dn Type=3
Dn Slope=0.005
Boundary for River Rch & Prof#=Allen T4,Reach-1,6
Up Type=0
Dn Type=3
Dn Slope=0.005
Boundary for River Rch & Prof#=Allen T4,Reach-1,7
Up Type=0
Dn Type=3
Dn Slope=0.005

--- Allen T4.g01 (geometry) ---

Geom Title=Existing Conditions

River Reach=Allen T4,Reach-1
Reach XY= 30
      2728726.00      6929211.00      2728818.77      6929111.11
      2728778.45      6929055.15      2728775.53      6928945.84
      2728825.49      6928845.78      2728824.63      6928721.44
      2728783.56      6928661.00      2728826.08      6928531.10
      2728775.61      6928436.00      2728826.29      6928331.16
      2728770.56      6928216.25      2728677.32      6928207.46
      2728626.98      6928150.73      2728627.22      6927921.50
      2728676.43      6927826.18      2728674.62      6927621.44
      2728633.59      6927560.99      2728674.34      6927467.05
      2728534.14      6927317.06      2728362.38      6926997.76
      2728185.17      6926867.95      2728221.35      6926666.26
      2728127.59      6926657.35      2727966.00      6926550.35
      2727876.74      6926400.32      2727931.86      6926258.70
      2728017.98      6926164.32      2727987.12      6926100.68
      2728118.52      6926014.66      2728076.00      6925911.00

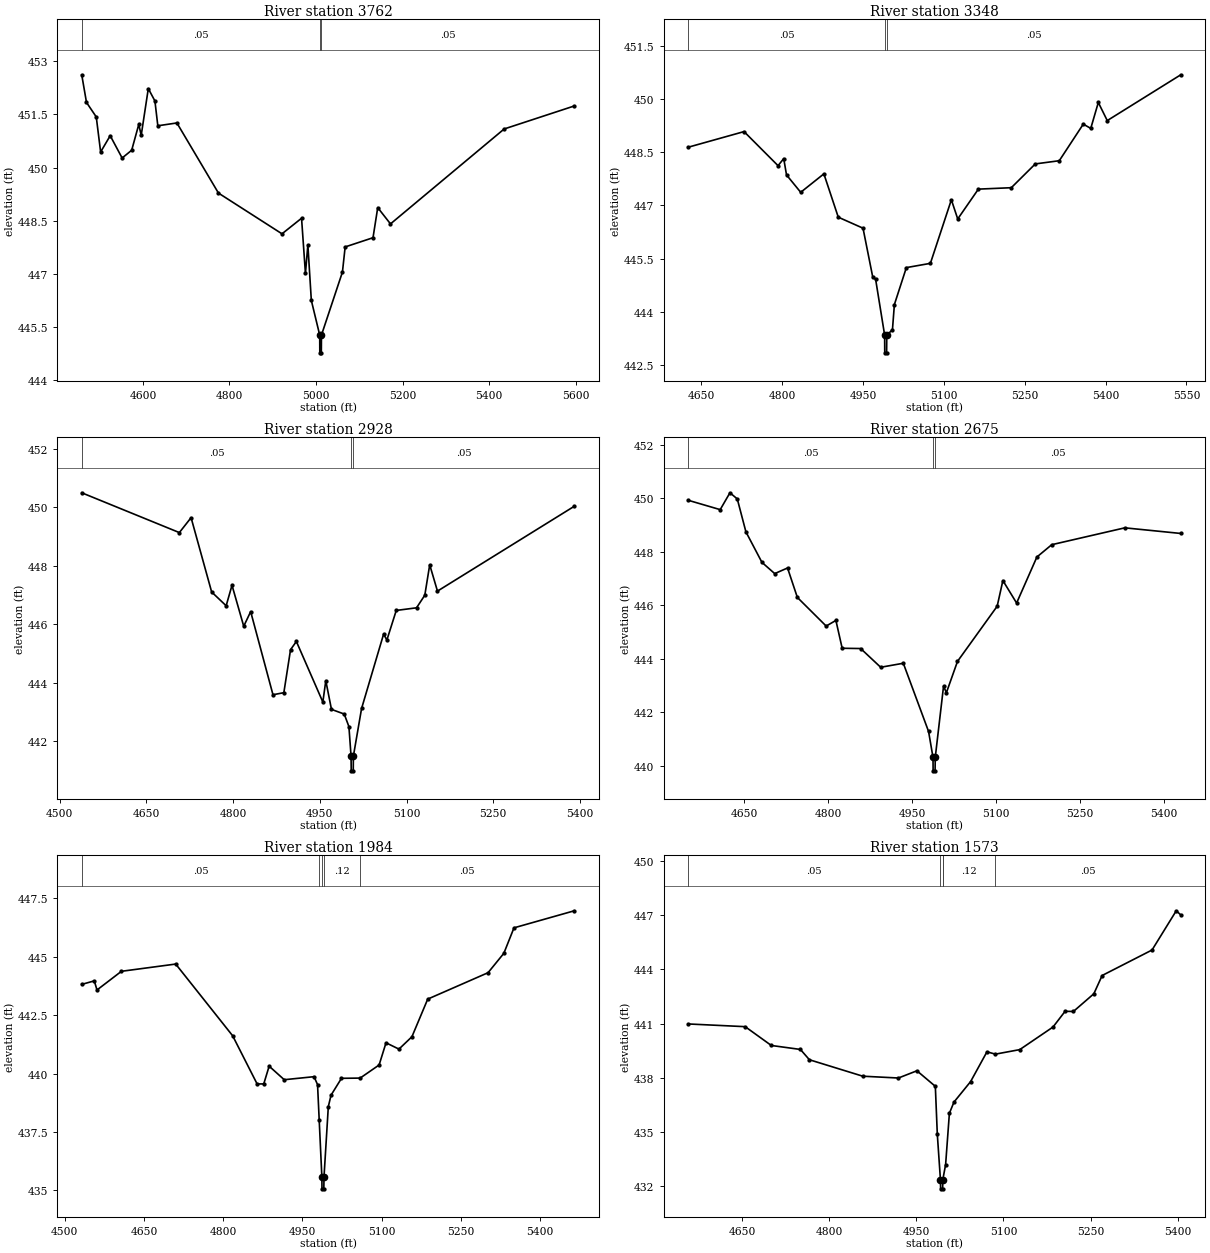
Type RM Length L Ch R = 1,3762,414,414,414
BEGIN DESCRIPTION:
Allen T4 10.0
END DESCRIPTION:
XS GIS Cut Line= 3
      2729305.71      6929078.46      2728826.47      6928826.16
      2728235.44      6928911.81
#Sta/Elev= 30
  4458.4  452.62  4469.4  451.84  4492.0  451.43  4502.1  450.44  4524.2  450.90
  4551.8  450.27  4573.9  450.49  4590.3  451.22  4595.9  450.91  4612.3  452.23
  4627.6  451.88  4634.3  451.18  4678.4  451.26  4774.5  449.28  4921.4  448.13
  4966.6  448.57  4975.6  447.01  4981.2  447.82  4989.2  446.25  5008.6  445.27
  5008.8  444.77  5012.3  444.77  5012.6  445.27  5061.1  447.05  5067.4  447.76
  5131.8  448.02  5142.7  448.87  5172.2  448.41  5435.0  451.09  5597.2  451.74
#Mann=3,-1,0
  4458.4    0.05       0  5008.6    0.04       0  5012.6    0.05       0
Bank Sta=5008.6,5012.6
Exp/Cntr=0.3,0.1

Type RM Length L Ch R = 1,3348,420,420,420
BEGIN DESCRIPTION:
Mapping XS dfdc4536
END DESCRIPTION:
XS GIS Cut Line= 3
      2729134.56      6928572.19      2728772.55      6928455.00
      2728297.13      6928696.60
#Sta/Elev= 30
  4625.8  448.64  4729.4  449.08  4792.5  448.12  4803.0  448.32  4808.2  447.86
  4834.5  447.37  4877.5  447.89  4904.2  446.67  4950.1  446.36  4968.2  444.98
  4973.5  444.92  4990.2  443.35  4990.4  442.85  4993.9  442.85  4994.2  443.35
  5004.7  443.50  5008.3  444.21  5030.5  445.25  5075.1  445.37  5114.0  447.16
  5125.8  446.62  5164.1  447.46  5225.2  447.50  5269.7  448.17  5314.2  448.26
  5358.7  449.29  5372.6  449.17  5386.6  449.90  5403.2  449.39  5539.6  450.68
#Mann=3,-1,0
  4625.8    0.05       0  4990.2    0.04       0  4994.2    0.05       0
Bank Sta=4990.2,4994.2
Exp/Cntr=0.3,0.1

Type RM Length L Ch R = 1,2928,253,253,253
BEGIN DESCRIPTION:
Mapping XS 5bd1e971
END DESCRIPTION:
XS GIS Cut Line= 3
      2729092.86      6928231.04      2728660.95      6928162.92
      2728295.90      6928360.42
#Sta/Elev= 30
  4538.0  450.49  4706.9  449.13  4727.2  449.64  4762.8  447.10  4787.9  446.63
  4798.0  447.33  4818.3  445.93  4830.3  446.43  4868.9  443.59  4887.7  443.66
  4899.3  445.13  4909.4  445.41  4955.2  443.34  4960.3  444.07  4970.1  443.09
  4992.2  442.93  5000.3  442.50  5004.0  441.49  5004.3  440.99  5007.8  440.99
  5008.0  441.49  5022.2  443.12  5060.3  445.66  5066.0  445.46  5082.2  446.47
  5117.3  446.56  5131.6  446.99  5140.1  448.03  5153.5  447.13  5390.3  450.03
#Mann=3,-1,0
  4538.0    0.05       0  5004.0    0.04       0  5008.0    0.05       0
Bank Sta=5004,5008
Exp/Cntr=0.3,0.1

Type RM Length L Ch R = 1,2675,691,691,691
BEGIN DESCRIPTION:
Mapping XS 6f49c857
END DESCRIPTION:
XS GIS Cut Line= 3
      2729035.54      6928108.63      2728634.53      6927923.75
      2728202.28      6927991.45
#Sta/Elev= 30
  4550.5  449.92  4607.6  449.57  4625.0  450.20  4638.1  449.97  4653.5  448.74
  4682.1  447.60  4704.9  447.18  4727.8  447.39  4745.3  446.29  4796.7  445.22
  4814.1  445.43  4825.3  444.39  4858.3  444.38  4894.0  443.68  4934.4  443.83
  4979.5  441.28  4987.4  440.31  4987.6  439.81  4991.1  439.81  4991.4  440.31
  5006.2  442.97  5011.3  442.73  5031.1  443.90  5101.9  445.96  5112.1  446.92
  5136.6  446.08  5172.8  447.80  5199.3  448.26  5329.7  448.89  5429.6  448.68
#Mann=3,-1,0
  4550.5    0.05       0  4987.4    0.04       0  4991.4    0.05       0
Bank Sta=4987.4,4991.4
Exp/Cntr=0.3,0.1

Type RM Length L Ch R = 1,1984,411,411,411
BEGIN DESCRIPTION:
Mapping XS 4d04c52b
END DESCRIPTION:
XS GIS Cut Line= 3
      2729004.28      6927420.61      2728540.78      6927329.47
      2728111.24      6927496.08
#Sta/Elev= 30
  4532.0  443.82  4555.8  443.97  4560.9  443.58  4607.2  444.38  4710.0  444.69
  4817.9  441.62  4864.2  439.56  4876.8  439.56  4887.0  440.32  4915.6  439.74
  4972.1  439.87  4978.7  439.53  4981.8  438.03  4986.9  435.57  4987.1  435.07
  4990.6  435.07  4990.9  435.57  4999.1  438.59  5004.3  439.08  5024.0  439.80
  5059.4  439.81  5095.3  440.37  5108.4  441.32  5132.9  441.05  5157.5  441.58
  5187.4  443.19  5301.7  444.32  5331.6  445.15  5350.8  446.24  5465.1  446.97
#Mann=5,-1,0
  4532.0    0.05       0  4981.8    0.12       0  4986.9    0.07       0
  4990.9    0.12       0  5059.4    0.05       0
Bank Sta=4986.9,4990.9
Exp/Cntr=0.3,0.1

Type RM Length L Ch R = 1,1573,452,452,452
BEGIN DESCRIPTION:
Mapping XS a270e425
END DESCRIPTION:
XS GIS Cut Line= 3
      2728780.37      6926886.76      2728366.30      6926972.70
      2728039.65      6927244.91
#Sta/Elev= 30
  4557.2  440.98  4655.3  440.83  4700.3  439.79  4750.4  439.57  4765.9  439.00
  4857.8  438.09  4919.1  437.99  4951.0  438.39  4982.7  437.53  4986.1  434.88
  4991.5  432.36  4991.8  431.86  4995.3  431.86  4995.5  432.36  4995.7  432.39
  5000.4  433.20  5006.9  436.04  5014.8  436.66  5043.4  437.79  5071.6  439.44
  5086.1  439.31  5128.0  439.56  5185.3  440.81  5206.1  441.68  5220.4  441.67
  5255.6  442.65  5269.9  443.66  5355.8  445.07  5397.5  447.24  5405.3  447.01
#Mann=5,-1,0
  4557.2    0.05       0  4991.5    0.07       0  4995.5    0.05       0
  4995.7    0.12       0  5086.1    0.05       0
Bank Sta=4991.5,4995.5
Exp/Cntr=0.3,0.1

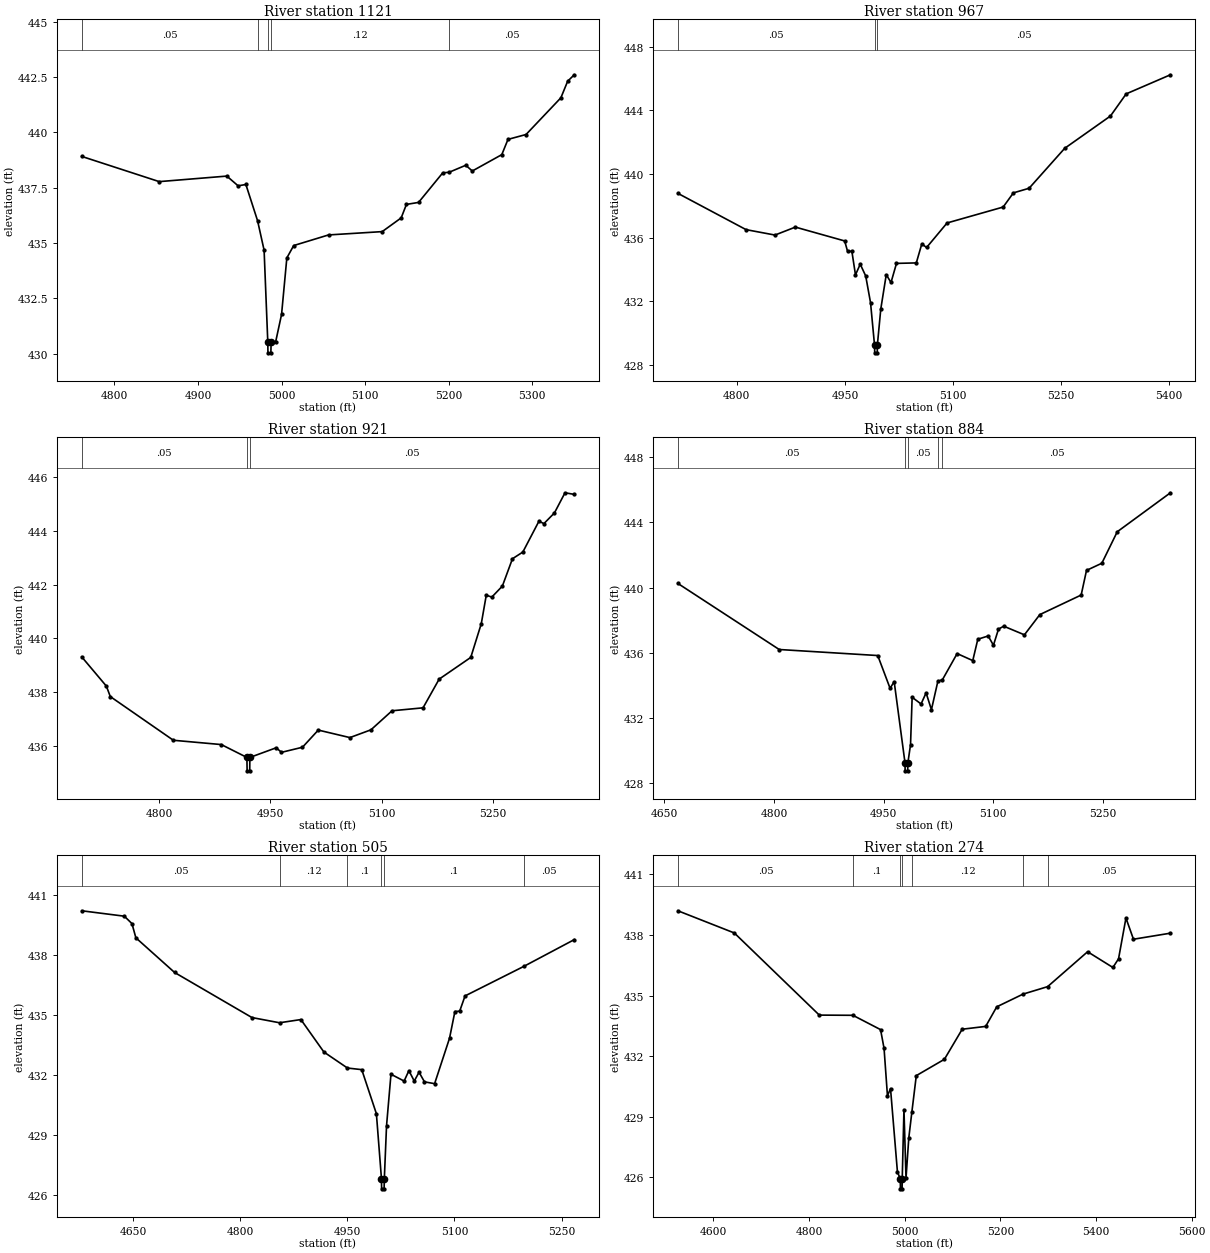
Type RM Length L Ch R = 1,1121,154,154,154
BEGIN DESCRIPTION:
Mapping XS 862bedff
END DESCRIPTION:
XS GIS Cut Line= 3
      2728447.74      6926609.00      2728257.55      6926636.99
      2727943.25      6926879.63
#Sta/Elev= 30
  4760.9  438.91  4853.6  437.77  4934.5  438.02  4948.0  437.58  4957.3  437.64
  4971.3  436.00  4979.1  434.67  4983.5  430.53  4983.7  430.03  4987.2  430.03
  4987.5  430.53  4993.0  430.54  5000.0  431.77  5006.3  434.32  5014.5  434.88
  5056.2  435.36  5120.4  435.51  5143.1  436.13  5149.4  436.74  5163.9  436.83
  5192.9  438.17  5200.3  438.19  5220.4  438.51  5228.2  438.25  5263.5  438.99
  5270.9  439.68  5292.5  439.90  5334.2  441.56  5342.3  442.31  5350.2  442.60
#Mann=5,-1,0
  4760.9    0.05       0  4971.3    0.12       0  4983.5    0.07       0
  4987.5    0.12       0  5200.3    0.05       0
Bank Sta=4983.5,4987.5
Exp/Cntr=0.3,0.1

Type RM Length L Ch R = 1,967,46,46,46
BEGIN DESCRIPTION:
Mapping XS d1fe8596
END DESCRIPTION:
XS GIS Cut Line= 3
      2728331.00      6926487.83      2728114.89      6926589.37
      2727781.57      6926883.63
#Sta/Elev= 30
  4718.2  438.78  4812.8  436.50  4852.9  436.16  4881.2  436.66  4949.6  435.79
  4953.6  435.14  4959.6  435.14  4964.6  433.66  4971.2  434.33  4978.8  433.59
  4985.5  431.91  4991.0  429.26  4991.3  428.76  4994.8  428.76  4995.0  429.26
  4999.7  431.51  5007.3  433.67  5013.9  433.18  5021.5  434.38  5049.0  434.41
  5056.6  435.60  5063.3  435.38  5091.7  436.92  5169.5  437.92  5183.7  438.81
  5205.5  439.10  5254.9  441.61  5318.4  443.64  5340.2  445.03  5401.6  446.23
#Mann=3,-1,0
  4718.2    0.05       0  4991.0    0.04       0  4995.0    0.05       0
Bank Sta=4991,4995
Exp/Cntr=0.3,0.1

Type RM Length L Ch R = 1,921,37,37,37
BEGIN DESCRIPTION:
Mapping XS c22cfca2
END DESCRIPTION:
XS GIS Cut Line= 4
      2728320.72      6926453.29      2728092.37      6926544.27
      2728045.49      6926590.79      2727784.16      6926826.53
#Sta/Elev= 30
  4695.7  439.31  4728.9  438.22  4734.2  437.83  4819.2  436.20  4883.8  436.04
  4918.3  435.56  4918.6  435.06  4922.1  435.06  4922.3  435.56  4957.8  435.92
  4964.9  435.75  4993.2  435.94  5014.5  436.58  5057.1  436.30  5085.5  436.59
  5113.9  437.30  5155.7  437.41  5177.4  438.48  5220.0  439.29  5234.2  440.55
  5240.9  441.61  5248.4  441.54  5262.6  441.95  5276.2  442.97  5290.2  443.22
  5311.9  444.37  5318.6  444.28  5332.8  444.68  5347.0  445.43  5359.5  445.37
#Mann=3,-1,0
  4695.7    0.05       0  4918.3    0.04       0  4922.3    0.05       0
Bank Sta=4918.3,4922.3
Exp/Cntr=0.3,0.1

Type RM Length L Ch R = 1,884,379,379,379
BEGIN DESCRIPTION:
Mapping XS cc43e9ed
END DESCRIPTION:
XS GIS Cut Line= 3
      2728316.78      6926415.43      2728027.04      6926557.88
      2727773.15      6926800.88
#Sta/Elev= 30
  4668.5  440.25  4807.2  436.20  4942.1  435.83  4959.0  433.82  4964.6  434.23
  4979.4  429.26  4979.6  428.76  4983.1  428.76  4983.4  429.26  4987.0  430.37
  4989.2  433.27  5001.4  432.86  5008.3  433.54  5015.6  432.51  5024.4  434.25
  5030.7  434.35  5050.8  435.95  5072.2  435.52  5079.1  436.83  5093.3  437.03
  5100.5  436.46  5107.4  437.45  5114.6  437.63  5142.9  437.10  5164.0  438.34
  5220.6  439.54  5227.9  441.05  5248.9  441.49  5270.0  443.42  5342.8  445.81
#Mann=5,-1,0
  4668.5    0.05       0  4979.4    0.04       0  4983.4    0.05       0
  5024.4    0.12       0  5030.7    0.05       0
Bank Sta=4979.4,4983.4
Exp/Cntr=0.3,0.1

Type RM Length L Ch R = 1,505,231,231,231
BEGIN DESCRIPTION:
Mapping XS 42e6b72b
END DESCRIPTION:
XS GIS Cut Line= 4
      2728321.45      6926403.84      2727970.85      6926265.72
      2727905.69      6926279.77      2727721.63      6926443.00
#Sta/Elev= 30
  4578.3  440.19  4637.9  439.92  4648.6  439.55  4654.1  438.84  4708.3  437.11
  4816.6  434.86  4855.2  434.60  4885.1  434.76  4917.3  433.14  4950.3  432.34
  4970.3  432.26  4990.8  430.06  4997.9  426.81  4998.1  426.31  5001.6  426.31
  5001.9  426.81  5005.0  429.46  5011.2  432.03  5029.6  431.69  5036.3  432.21
  5043.8  431.69  5050.5  432.13  5058.1  431.65  5072.3  431.56  5093.2  433.83
  5100.7  435.16  5107.4  435.18  5114.9  435.94  5197.5  437.42  5267.8  438.75
#Mann=6,-1,0
  4578.3    0.05       0  4855.2    0.12       0  4950.3     0.1       0
  4997.9    0.07       0  5001.9     0.1       0  5197.5    0.05       0
Bank Sta=4997.9,5001.9
Exp/Cntr=0.3,0.1

Type RM Length L Ch R = 1,274,0,0,0
BEGIN DESCRIPTION:
Allen T4 1.0
END DESCRIPTION:
XS GIS Cut Line= 3
      2728362.81      6926390.00      2727992.24      6926093.96
      2727512.22      6926373.73
#Sta/Elev= 30
  4525.7  439.20  4643.7  438.10  4821.4  434.03  4891.7  434.02  4949.5  433.31
  4956.8  432.38  4963.9  430.03  4970.3  430.39  4984.8  426.25  4990.8  425.92
  4991.0  425.42  4994.5  425.42  4994.8  425.92  4998.4  429.35  5002.7  425.95
  5008.5  427.94  5015.0  429.24  5024.2  431.03  5083.0  431.84  5120.2  433.33
  5169.3  433.47  5192.4  434.44  5247.4  435.07  5298.8  435.44  5382.4  437.17
  5435.3  436.39  5447.1  436.82  5462.6  438.84  5478.3  437.79  5555.6  438.09
#Mann=7,-1,0
  4525.7    0.05       0  4891.7     0.1       0  4990.8    0.07       0
  4994.8     0.1       0  5015.0    0.12       0  5247.4     0.1       0
  5298.8    0.05       0
Bank Sta=4990.8,4994.8
Exp/Cntr=0.3,0.1

Chan Stop Cuts=-1