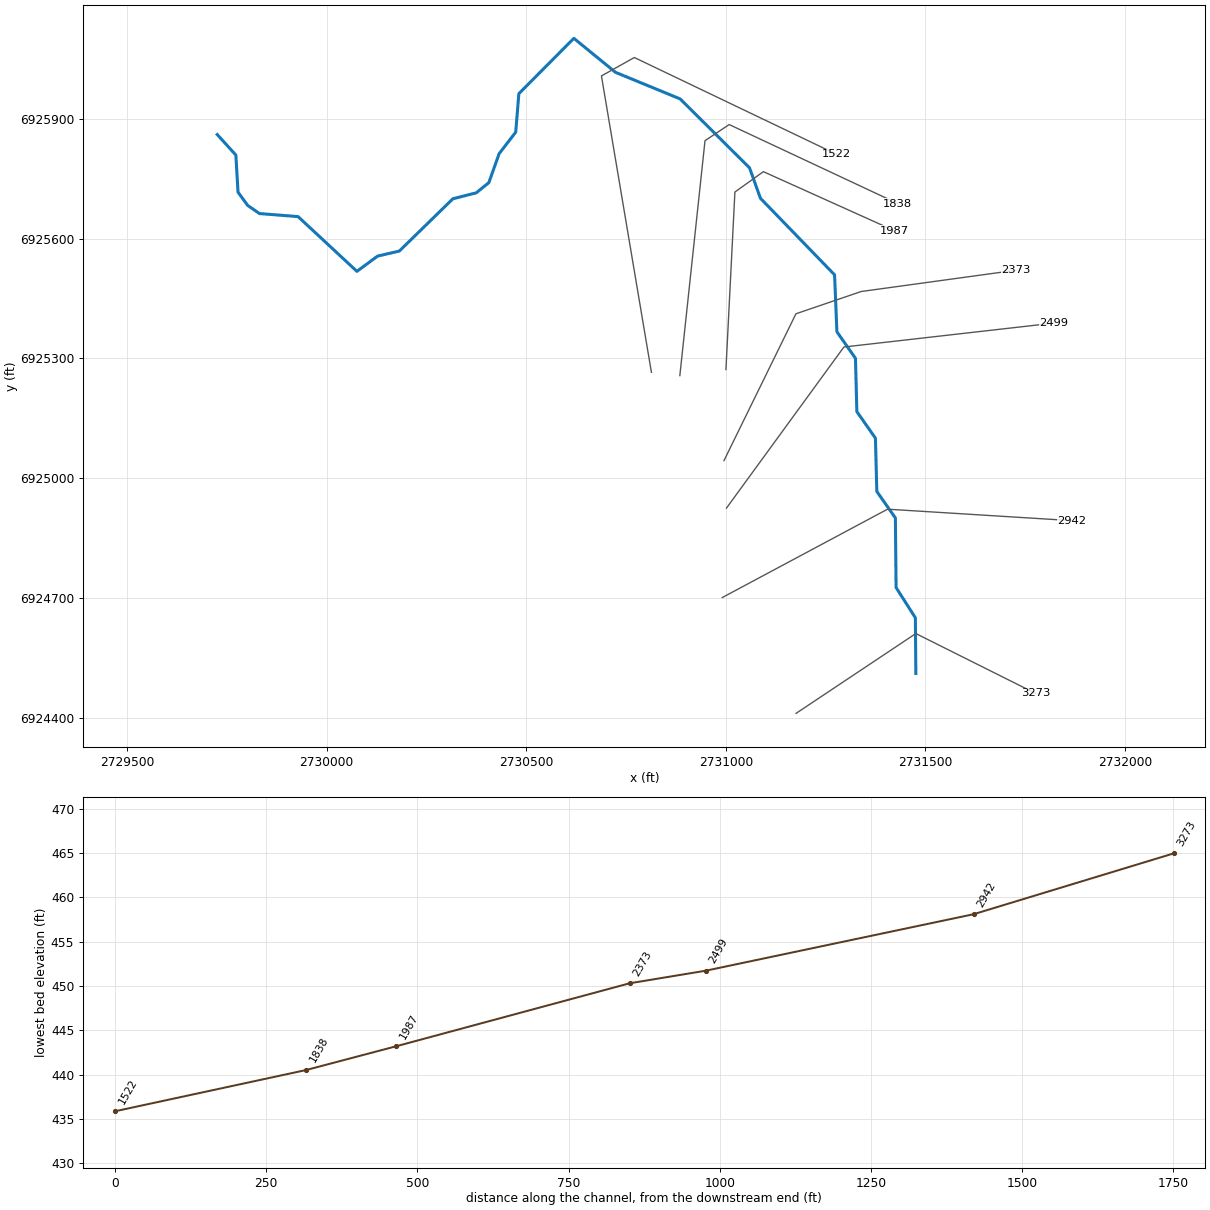
--- Allen T5.prj (project) ---

Proj Title=Allen T5 Base Level Engineering
Current Plan=p01
Default Exp/Contr=0.3,0.1
English Units
Geom File=g01
Flow File=f01
Plan File=p01
Y Axis Title=Elevation
X Axis Title(PF)=Main Channel Distance
X Axis Title(XS)=Station
BEGIN DESCRIPTION:
Allen T5
END DESCRIPTION:
DSS Export Rating Curves= 0
DSS Export Rating Curve Sorted= 0
DSS Export Volume Flow Curves= 0
DXF OffsetX= 0
DXF OffsetY= 0
DXF ScaleX= 1
DXF ScaleY= 10

--- Allen T5.p01 (plan) ---

Plan Title=Multiple Run
Short Identifier=Multiple
Geom File=g01
Flow File=f01
Subcritical Flow
K Sum by GR= 0
Std Step Tol= 0.01
Critical Tol= 0.01
Num of Std Step Trials= 20
Max Error Tol= 0.3
Flow Tol Ratio= 0.001
Split Flow NTrial= 30
Split Flow Tol= 0.02
Split Flow Ratio= 0.02
Log Output Level= 0
Friction Slope Method= 1
Unsteady Friction Slope Method= 2
Unsteady Bridges Friction Slope Method= 1
Parabolic Critical Depth
Global Vel Dist=  1 , 1 , 1
Global Log Level= 0
CheckData=True
Encroach Param= -1, 0, 0, 0
BEGIN DESCRIPTION:
Multiple Run
END DESCRIPTION:

--- Allen T5.f01 (steady flow) ---

Flow Title=Multiple
Number of Profiles=7
Profile Names=10-year,25-year,50-year,1pct_min,100-year,1pct_plu,500-year
River Rch & RM= Allen T5,Reach-1,3273
     253     320     372     215     430     858     572
Boundary for River Rch & Prof#=Allen T5,Reach-1,1
Up Type=0
Dn Type=3
Dn Slope=0.005
Boundary for River Rch & Prof#=Allen T5,Reach-1,2
Up Type=0
Dn Type=3
Dn Slope=0.005
Boundary for River Rch & Prof#=Allen T5,Reach-1,3
Up Type=0
Dn Type=3
Dn Slope=0.005
Boundary for River Rch & Prof#=Allen T5,Reach-1,4
Up Type=0
Dn Type=3
Dn Slope=0.005
Boundary for River Rch & Prof#=Allen T5,Reach-1,5
Up Type=0
Dn Type=3
Dn Slope=0.005
Boundary for River Rch & Prof#=Allen T5,Reach-1,6
Up Type=0
Dn Type=3
Dn Slope=0.005
Boundary for River Rch & Prof#=Allen T5,Reach-1,7
Up Type=0
Dn Type=3
Dn Slope=0.005

--- Allen T5.g01 (geometry) ---

Geom Title=Existing Conditions
Program Version=4.10

River Reach=Allen T5        ,Reach-1
Reach XY= 30
        2731476.        6924511.      2731474.83      6924650.52
      2731426.52      6924726.22      2731424.78      6924900.49
      2731378.27      6924966.94      2731374.77      6925100.49
      2731328.27      6925166.94      2731324.77      6925300.49
      2731278.27      6925366.94      2731272.46      6925509.53
      2731086.78      6925701.32      2731059.35      6925777.67
      2730885.68      6925950.24       2730723.7      6926016.86
      2730619.33      6926102.04      2730481.52      6925963.43
      2730473.67      6925866.97      2730432.15      6925813.15
      2730406.38      6925740.53      2730374.57      6925714.89
      2730316.34      6925700.21      2730182.05      6925569.12
      2730127.65      6925556.53      2730075.91      6925518.28
      2729928.42      6925655.47      2729831.69      6925663.07
      2729801.99      6925683.67      2729778.03      6925716.67
      2729772.61      6925809.59        2729726.        6925861.

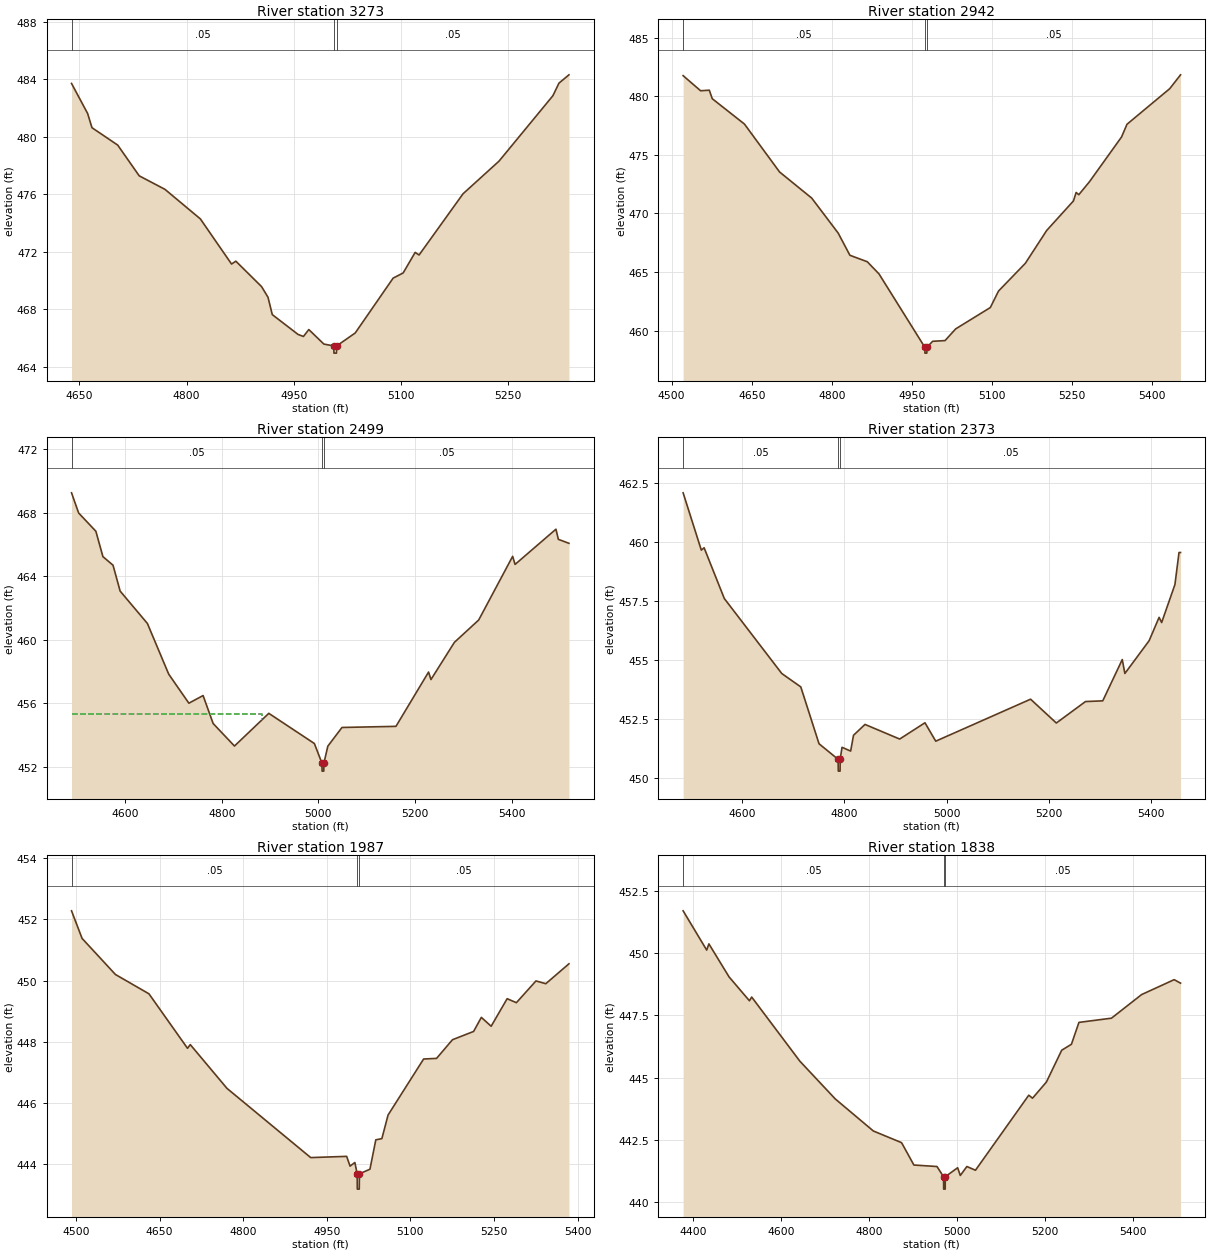
Type RM Length L Ch R = 1 ,3273    ,331,331,331
BEGIN DESCRIPTION:
Allen T5 3.0
END DESCRIPTION:
XS GIS Cut Line= 3
      2731175.99        6924411.        2731476.        6924611.
      2731776.03      6924460.99
#Sta/Elev= 30
  4638.9  483.71  4661.4  481.62  4667.5  480.63  4703.5  479.42  4733.6  477.28
  4769.6  476.34  4819.2  474.28  4862.8  471.14  4868.8  471.34  4904.8  469.57
  4913.8  468.83  4919.8  467.62  4955.9  466.24  4963.4   466.1  4970.9  466.58
    4992  465.57  5005.8  465.44  5006.1  464.94  5009.6  464.94  5009.8  465.44
  5035.8  466.34  5088.9  470.16  5102.9  470.52  5119.7  471.95  5125.2  471.77
  5186.7  476.03    5237   478.3  5312.5  482.86  5320.9  483.73  5334.9  484.31
#Mann= 3 ,-1 , 0
  4638.9     .05       0  5005.8    .035       0  5009.8     .05       0
Bank Sta=5005.8,5009.8
XS Rating Curve= 0 ,0
Exp/Cntr=0.3,0.1

Type RM Length L Ch R = 1 ,2942    ,443,443,443
BEGIN DESCRIPTION:
Mapping XS c9550a87
END DESCRIPTION:
XS GIS Cut Line= 3
       2730991.1      6924701.16      2731405.18      6924922.53
      2731866.15      6924893.88
#Sta/Elev= 30
  4521.6  481.76  4554.3  480.47  4570.6  480.52  4576.2  479.79  4636.4  477.63
  4702.2  473.54  4762.4  471.31    4812  468.32  4833.9  466.43  4866.4  465.88
  4888.4  464.84  4974.2  458.58  4974.4  458.08  4977.9  458.08  4978.2  458.58
  4988.8  459.09    5012  459.15    5032  460.15  5096.8  461.97  5112.2  463.38
  5162.3  465.74  5202.4  468.55  5252.5  471.07  5257.5  471.79  5262.5   471.6
  5282.5  472.71  5342.6  476.53  5352.7  477.61  5432.8  480.65    5453  481.83
#Mann= 3 ,-1 , 0
  4521.6     .05       0  4974.2    .035       0  4978.2     .05       0
Bank Sta=4974.2,4978.2
XS Rating Curve= 0 ,0
Exp/Cntr=0.3,0.1

Type RM Length L Ch R = 1 ,2499    ,126,126,126
BEGIN DESCRIPTION:
Mapping XS 0c0ef503
END DESCRIPTION:
XS GIS Cut Line= 3
      2731001.56      6924925.16      2731295.81      6925328.78
      2731821.42      6925388.63
#Sta/Elev= 30
  4489.5  469.24  4504.2  467.97  4539.8  466.82  4554.4  465.22  4575.3  464.68
    4590  463.05  4646.4  461.01  4690.4  457.82  4732.1  455.99  4761.5  456.47
  4782.3  454.71  4826.4  453.29  4897.4  455.35  4991.6  453.45  5007.3  452.21
  5007.6  451.71  5011.1  451.71  5011.3  452.21  5019.4  453.28  5048.7  454.46
  5160.3  454.53  5227.7  457.95  5232.7  457.48  5281.1  459.82  5331.4  461.23
  5401.6  465.24  5406.6  464.73  5491.1  466.95  5496.1  466.31    5518  466.06
#Mann= 3 ,-1 , 0
  4489.5     .05       0  5007.3    .035       0  5011.3     .05       0
#XS Ineff= 2 , 0
       0  4882.8  455.29               0
Permanent Ineff=
       F       F
Bank Sta=5007.3,5011.3
XS Rating Curve= 0 ,0
Exp/Cntr=0.3,0.1

Type RM Length L Ch R = 1 ,2373    ,386,386,386
BEGIN DESCRIPTION:
Mapping XS f4a2d5b4
END DESCRIPTION:
XS GIS Cut Line= 4
      2730995.33      6925044.08      2731175.67      6925412.02
       2731339.2      6925467.83      2731726.91      6925521.14
#Sta/Elev= 30
  4484.1  462.09  4519.7  459.66  4525.2  459.76  4564.7  457.61  4677.2  454.43
  4714.5  453.86  4750.2  451.45  4787.6  450.79  4787.9  450.29  4791.4  450.29
  4791.6  450.79  4795.2   451.3  4812.1  451.14  4817.7  451.81  4840.2  452.27
  4908.1  451.65  4957.6  452.34  4978.7  451.56  5164.4  453.34  5214.8  452.33
  5271.9  453.24  5305.7  453.27  5343.9  455.02    5349  454.43  5396.5  455.82
    5416  456.81    5421  456.59    5447   458.2    5455  459.56    5458  459.56
#Mann= 3 ,-1 , 0
  4484.1     .05       0  4787.6    .035       0  4791.6     .05       0
Bank Sta=4787.6,4791.6
XS Rating Curve= 0 ,0
Exp/Cntr=0.3,0.1

Type RM Length L Ch R = 1 ,1987    ,149,149,149
BEGIN DESCRIPTION:
Mapping XS 773d2a07
END DESCRIPTION:
XS GIS Cut Line= 4
      2731000.29      6925272.31      2731022.76      6925717.01
      2731094.09      6925768.05      2731421.98      6925620.35
#Sta/Elev= 30
    4492  452.28  4510.9  451.38  4570.8   450.2  4630.9  449.57  4700.1  447.79
  4705.1  447.91    4771  446.48  4921.2  444.22  4985.7  444.26  4991.8  443.94
  5000.4  444.06  5004.6  443.69  5004.8  443.19  5008.3  443.19  5008.6  443.69
  5027.5  443.84    5038   444.8  5048.9  444.84    5060  445.61  5123.8  447.44
    5147  447.46  5175.6  448.07  5213.5  448.34  5227.4   448.8    5245  448.51
  5273.7  449.41  5290.3  449.28  5325.4  449.99  5343.1   449.9  5384.6  450.55
#Mann= 3 ,-1 , 0
    4492     .05       0  5004.6    .035       0  5008.6     .05       0
Bank Sta=5004.6,5008.6
XS Rating Curve= 0 ,0
Exp/Cntr=0.3,0.1

Type RM Length L Ch R = 1 ,1838    ,316,316,316
BEGIN DESCRIPTION:
Mapping XS ecd92d8d
END DESCRIPTION:
XS GIS Cut Line= 4
      2730884.82      6925257.11      2730947.86      6925845.65
      2731008.44      6925886.05      2731430.66      6925688.21
#Sta/Elev= 30
  4376.7  451.71  4430.3  450.13  4435.3  450.38  4481.2  449.05  4527.5  448.09
  4532.6  448.24  4642.1  445.66  4722.6  444.14  4809.2  442.85  4873.4  442.38
  4901.4  441.48  4953.9  441.42  4968.8  441.01  4969.1  440.51  4972.6  440.51
  4972.8  441.01  5000.9  441.37  5006.9  441.06  5021.9  441.42  5041.4  441.27
  5162.6  444.29  5171.2  444.17  5202.7  444.82  5237.5   446.1  5259.6  446.34
  5276.7  447.22  5350.7  447.39  5419.2  448.34  5493.2  448.94  5507.7   448.8
#Mann= 3 ,-1 , 0
  4376.7     .05       0  4968.8    .035       0  4972.8     .05       0
Bank Sta=4968.8,4972.8
XS Rating Curve= 0 ,0
Exp/Cntr=0.3,0.1

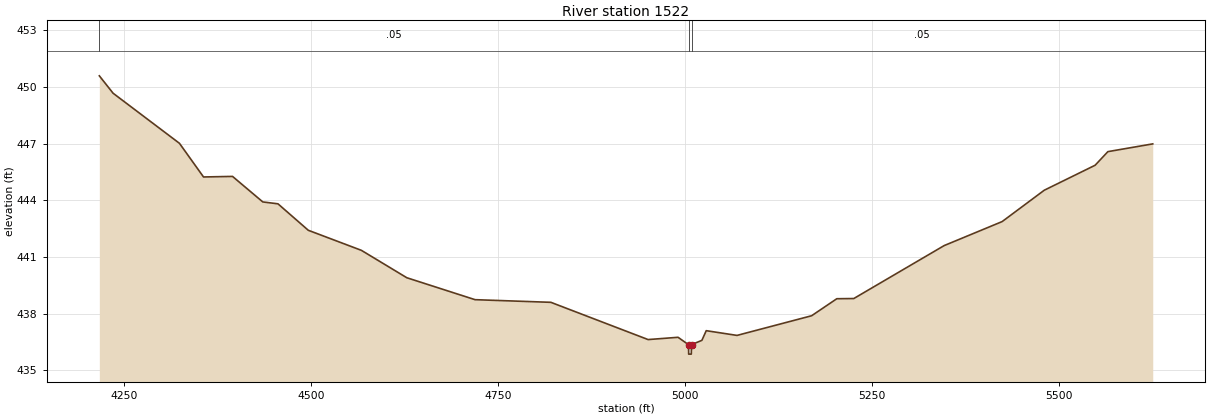
Type RM Length L Ch R = 1 ,1522    ,0,0,0
BEGIN DESCRIPTION:
Allen T5 1.0
END DESCRIPTION:
XS GIS Cut Line= 4
      2730813.63      6925265.32      2730688.43      6926007.86
      2730770.86      6926053.97      2731277.71      6925811.34
#Sta/Elev= 30
  4216.4  450.58  4234.8  449.66  4323.6  447.01  4355.8  445.23  4394.6  445.26
  4435.1  443.91  4455.4  443.81    4496  442.41    4567  441.35  4627.8   439.9
  4719.1  438.74  4820.5   438.6  4950.6  436.63  4990.7  436.75  5004.7  436.36
  5004.9  435.86  5008.4  435.86  5008.7  436.36  5022.6  436.59  5028.4   437.1
  5069.6  436.85  5169.4  437.89  5203.1  438.79  5225.8   438.8  5346.7   441.6
  5424.3  442.87  5480.7  444.53  5548.7  445.85  5565.8  446.57  5625.8  446.98
#Mann= 3 ,-1 , 0
  4216.4     .05       0  5004.7    .035       0  5008.7     .05       0
Bank Sta=5004.7,5008.7
XS Rating Curve= 0 ,0
Exp/Cntr=0.3,0.1

Chan Stop Cuts=-1
Use User Specified Reach Order=0
Composite Channel Slope=5