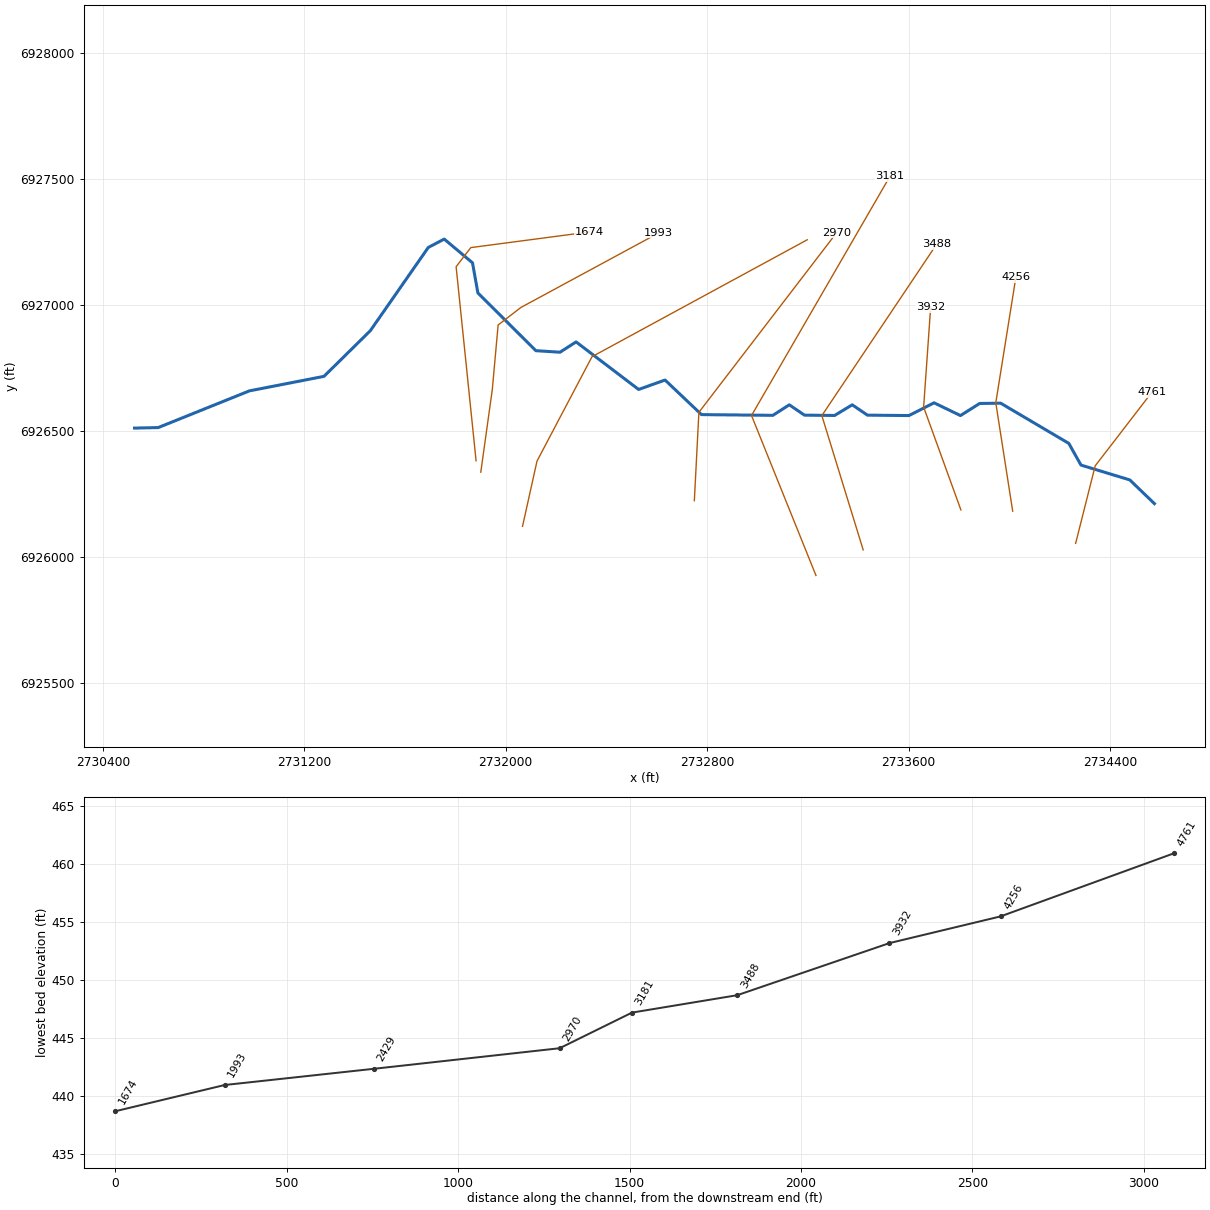
--- Allen T6.prj (project) ---

Proj Title=Allen T6 Base Level Engineering
Current Plan=p01
Default Exp/Contr=0.3,0.1
English Units
Geom File=g01
Flow File=f01
Plan File=p01
Y Axis Title=Elevation
X Axis Title(PF)=Main Channel Distance
X Axis Title(XS)=Station
BEGIN DESCRIPTION:
Allen T6
END DESCRIPTION:
DSS Export Rating Curves= 0
DSS Export Rating Curve Sorted= 0
DSS Export Volume Flow Curves= 0
DXF OffsetX= 0
DXF OffsetY= 0
DXF ScaleX= 1
DXF ScaleY= 10

--- Allen T6.p01 (plan) ---

Plan Title=Multiple Run
Short Identifier=Multiple
Geom File=g01
Flow File=f01
Subcritical Flow
K Sum by GR= 0
Std Step Tol= 0.01
Critical Tol= 0.01
Num of Std Step Trials= 20
Max Error Tol= 0.3
Flow Tol Ratio= 0.001
Split Flow NTrial= 30
Split Flow Tol= 0.02
Split Flow Ratio= 0.02
Log Output Level= 0
Friction Slope Method= 1
Unsteady Friction Slope Method= 2
Unsteady Bridges Friction Slope Method= 1
Parabolic Critical Depth
Global Vel Dist=  1 , 1 , 1
Global Log Level= 0
CheckData=True
Encroach Param= -1, 0, 0, 0
BEGIN DESCRIPTION:
Multiple Run
END DESCRIPTION:

--- Allen T6.f01 (steady flow) ---

Flow Title=Multiple
Program Version=4.10
Number of Profiles= 7
Profile Names=10-year,25-year,50-year,1pct_min,100-year,1pct_plu,500-year
River Rch & RM=Allen T6,Reach-1         ,4761
     266     337     391     226     450     899     596
River Rch & RM=Allen T6,Reach-1         ,2429
     620     832    1005     603    1203    2401    1721
Boundary for River Rch & Prof#=Allen T6,Reach-1         , 1
Up Type= 0
Dn Type= 3
Dn Slope=0.007
Boundary for River Rch & Prof#=Allen T6,Reach-1         , 2
Up Type= 0
Dn Type= 3
Dn Slope=0.007
Boundary for River Rch & Prof#=Allen T6,Reach-1         , 3
Up Type= 0
Dn Type= 3
Dn Slope=0.007
Boundary for River Rch & Prof#=Allen T6,Reach-1         , 4
Up Type= 0
Dn Type= 3
Dn Slope=0.007
Boundary for River Rch & Prof#=Allen T6,Reach-1         , 5
Up Type= 0
Dn Type= 3
Dn Slope=0.007
Boundary for River Rch & Prof#=Allen T6,Reach-1         , 6
Up Type= 0
Dn Type= 3
Dn Slope=0.007
Boundary for River Rch & Prof#=Allen T6,Reach-1         , 7
Up Type= 0
Dn Type= 3
Dn Slope=0.007
DSS Import GetInterval= 0
DSS Import GetPeak= 0
DSS Import FillOption= 0

--- Allen T6.g01 (geometry) ---

Geom Title=Existing Conditions
Program Version=4.10

River Reach=Allen T6        ,Reach-1
Reach XY= 30
        2734576.        6926211.      2734478.32      6926305.21
      2734284.35      6926364.19      2734235.97      6926450.29
      2733965.46      6926609.92      2733881.97      6926608.81
      2733805.82      6926560.73        2733701.      6926611.39
      2733601.09      6926560.81      2733436.44      6926562.38
        2733376.      6926603.44      2733306.01      6926561.16
      2733186.44      6926562.37        2733126.      6926603.44
      2733060.84      6926561.66      2732777.46      6926564.54
      2732632.73      6926701.85      2732527.74      6926664.37
      2732279.42      6926853.21      2732215.54      6926812.27
      2732119.68      6926818.36       2731889.4       6927047.7
      2731868.14      6927167.19      2731755.77      6927261.51
       2731692.5      6927228.23      2731462.37      6926897.79
      2731278.43      6926716.52      2730981.94      6926658.73
      2730620.13       6926513.1        2730526.        6926511.

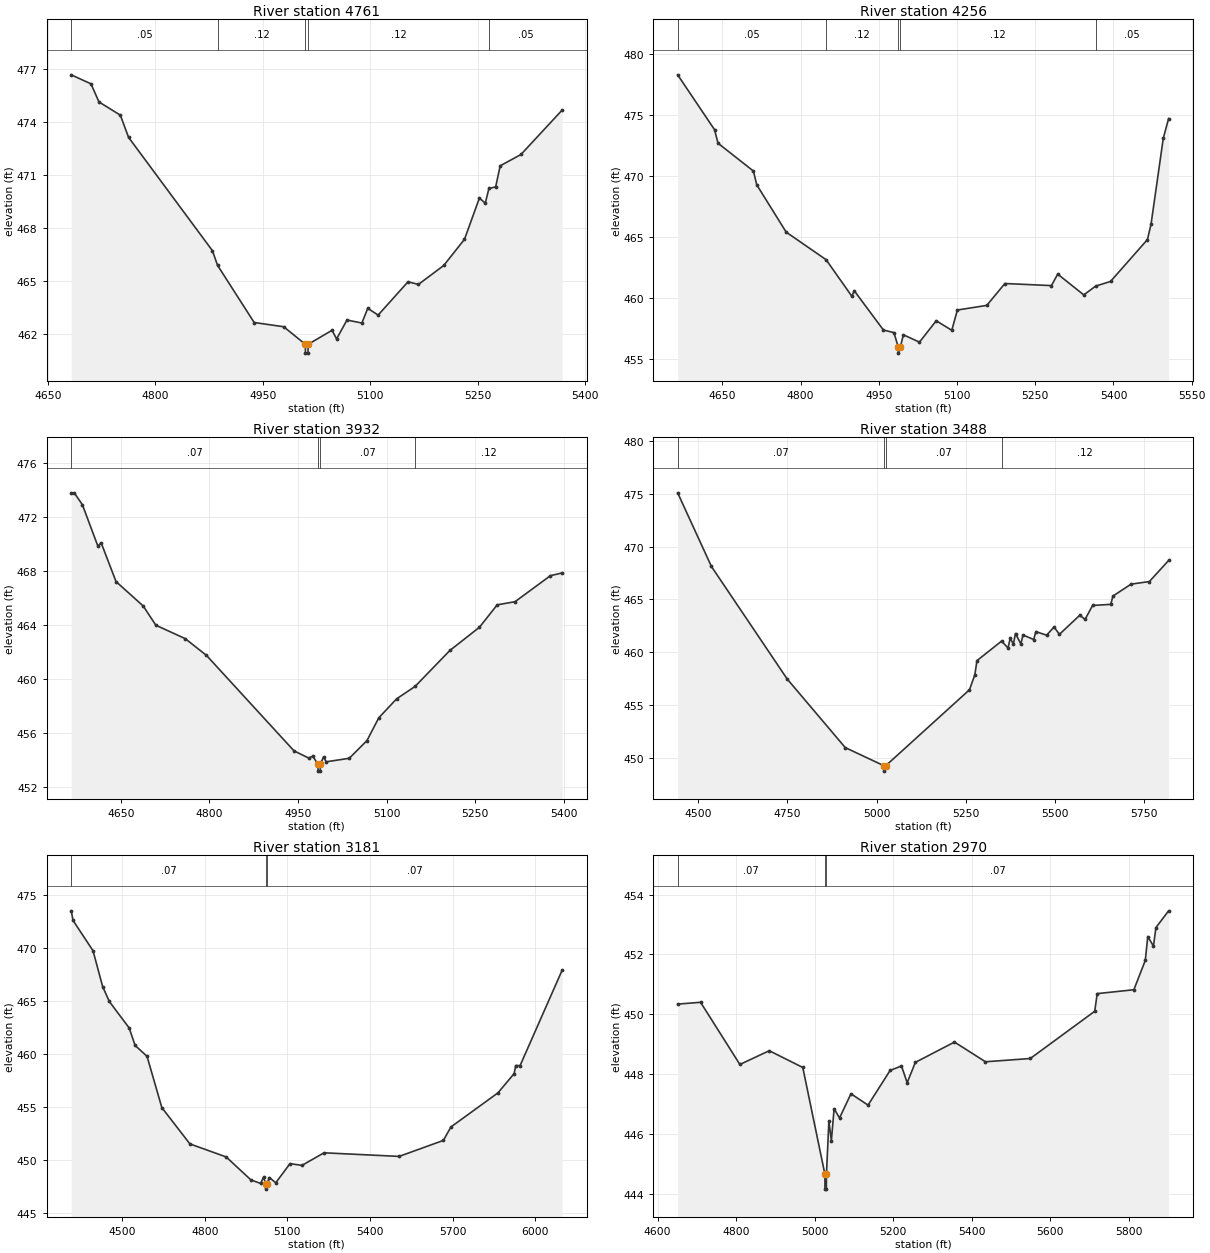
Type RM Length L Ch R = 1 ,4761    ,505,505,505
BEGIN DESCRIPTION:
Allen T6 7.0
END DESCRIPTION:
XS GIS Cut Line= 3
      2734263.18      6926053.48       2734340.8      6926361.04
       2734565.3       6926652.5
#Sta/Elev= 30
  4682.8  476.66  4710.4  476.15  4721.5  475.13  4751.4  474.38  4762.8  473.13
  4879.8  466.73    4887   465.9  4938.1  462.67  4979.3  462.43  5009.5  461.44
  5009.7  460.94  5013.2  460.94  5013.5  461.44  5046.8  462.23  5053.1  461.74
  5067.6  462.81  5088.4  462.64  5096.6  463.47  5111.1  463.09  5152.8  464.97
  5167.3  464.82  5202.6  465.89  5231.6  467.37  5252.4   469.7  5260.6  469.41
  5265.7  470.24  5275.1  470.33  5281.4  471.52  5310.4  472.16  5367.9  474.67
#Mann= 5 ,-1 , 0
  4682.8     .05       0    4887     .12       0  5009.5     .07       0
  5013.5     .12       0  5265.7     .05       0
Bank Sta=5009.5,5013.5
XS Rating Curve= 0 ,0
Exp/Cntr=0.3,0.1

Type RM Length L Ch R = 1 ,4256    ,324,324,324
BEGIN DESCRIPTION:
Allen T6 6.0
END DESCRIPTION:
XS GIS Cut Line= 3
      2734013.19       6926181.1      2733946.05       6926611.6
      2734026.01      6927111.04
#Sta/Elev= 30
  4564.3   478.3    4635  473.81  4641.7   472.7  4709.6  470.42    4716  469.29
  4772.4  465.42    4849  463.16  4898.1  460.18  4903.1  460.61  4958.9   457.4
  4979.1  457.19  4987.3  456.01  4987.5  455.51  4991.3  456.01  4997.2  457.01
    5028  456.41  5060.2  458.16    5090  457.38  5100.7  459.04  5157.1  459.42
  5191.8  461.21  5281.1  461.04  5293.1  461.98  5343.1  460.28    5366     461
  5394.4  461.38  5465.2  464.81  5472.2  466.09  5495.6  473.11  5505.8  474.72
#Mann= 5 ,-1 , 0
  4564.3     .05       0    4849     .12       0  4987.3     .07       0
  4991.3     .12       0    5366     .05       0
Bank Sta=4987.3,4991.3
XS Rating Curve= 0 ,0
Exp/Cntr=0.3,0.1

Type RM Length L Ch R = 1 ,3932    ,444,444,444
BEGIN DESCRIPTION:
Allen T6 5.0
END DESCRIPTION:
XS GIS Cut Line= 3
      2733807.46      6926186.31      2733659.52      6926594.32
      2733687.46      6926990.73
#Sta/Elev= 30
    4566  473.81  4571.2  473.81  4584.9  472.93  4611.3  469.85  4616.6  470.12
  4641.9  467.24    4688  465.43  4709.3  464.01    4759  463.02    4795  461.78
  4943.3  454.71  4968.1  454.18  4975.2  454.32  4983.8  453.71  4984.1  453.21
  4987.6  453.21  4987.8  453.71  4993.4  454.27  4997.8   453.9  5036.8  454.16
  5066.8  455.47  5086.9  457.16    5117  458.56  5148.3  459.48  5207.2  462.14
  5257.3  463.86  5287.4  465.52  5317.5  465.75  5377.6  467.68  5397.4  467.88
#Mann= 4 ,-1 , 0
    4566     .07       0  4983.8     .05       0  4987.8     .07       0
  5148.3     .12       0
Bank Sta=4983.8,4987.8
XS Rating Curve= 0 ,0
Exp/Cntr=0.3,0.1

Type RM Length L Ch R = 1 ,3488    ,307,307,307
BEGIN DESCRIPTION:
Allen T6 4.0
END DESCRIPTION:
XS GIS Cut Line= 3
      2733419.44      6926027.44      2733255.37      6926560.57
      2733711.08      6927240.96
#Sta/Elev= 30
  4442.2  475.09  4536.9  468.11  4749.3  457.45  4912.2  450.95  5021.3  449.22
  5021.6  448.72  5025.3  449.22  5260.5  456.43  5275.5  457.84  5281.5  459.19
  5350.5  461.04  5368.6  460.39  5374.6  461.29  5383.6  460.78  5389.6  461.76
  5404.6  460.77  5410.6  461.62  5440.6  461.19  5446.6  461.94  5476.6   461.6
  5497.7  462.37  5512.7  461.68  5569.7  463.49  5584.7   463.1  5605.7  464.42
  5656.7  464.52  5662.8  465.31  5713.8  466.44  5764.8  466.68  5818.9  468.68
#Mann= 4 ,-1 , 0
  4442.2     .07       0  5021.3     .05       0  5025.3     .07       0
  5350.5     .12       0
Bank Sta=5021.3,5025.3
XS Rating Curve= 0 ,0
Exp/Cntr=0.3,0.1

Type RM Length L Ch R = 1 ,3181    ,211,211,211
BEGIN DESCRIPTION:
Allen T6 3.0
END DESCRIPTION:
XS GIS Cut Line= 3
      2733231.96      6925925.85      2732976.03      6926560.93
      2733526.01      6927511.02
#Sta/Elev= 30
  4315.3   473.5    4322  472.59  4394.5  469.73  4429.5  466.34  4453.6  464.94
  4525.7  462.44  4547.3  460.79  4590.6  459.76  4644.3  454.92  4746.3  451.49
  4877.9  450.26  4967.7  448.09  5002.9  447.76  5013.7  448.36  5021.2  447.72
  5021.4  447.22  5025.2  447.72  5035.2  448.31  5057.9  447.82  5109.8  449.63
  5152.9  449.46  5233.2  450.65  5505.8  450.31  5666.5  451.82  5693.9  453.09
  5864.6  456.31  5923.4  458.13  5929.2  458.89  5944.9  458.88  6097.8   467.9
#Mann= 3 ,-1 , 0
  4315.3     .07       0  5021.2     .05       0  5025.2     .07       0
Bank Sta=5021.2,5025.2
XS Rating Curve= 0 ,0
Exp/Cntr=0.3,0.1

Type RM Length L Ch R = 1 ,2970    ,541,541,541
BEGIN DESCRIPTION:
Mapping XS 78c93f57
END DESCRIPTION:
XS GIS Cut Line= 3
      2732749.02      6926222.68       2732767.1      6926573.81
      2733314.19      6927287.06
#Sta/Elev= 30
  4651.3  450.34  4709.7   450.4  4809.8  448.32  4884.6  448.78    4970  448.22
  5026.3  444.65  5026.5  444.15    5030  444.15  5030.3  444.65  5036.5  446.43
  5042.8  445.77  5049.8  446.84  5063.6  446.53  5092.7  447.34  5136.2  446.96
  5192.4  448.12  5221.4  448.27  5235.9  447.71  5256.7  448.39  5356.4  449.07
  5435.3  448.41  5549.5  448.52  5713.6   450.1  5719.9  450.69  5813.3  450.82
  5842.4   451.8  5848.7   452.6  5863.2  452.28  5869.5   452.9  5901.8  453.46
#Mann= 3 ,-1 , 0
  4651.3     .07       0  5026.3     .05       0  5030.3     .07       0
Bank Sta=5026.3,5030.3
XS Rating Curve= 0 ,0
Exp/Cntr=0.3,0.1

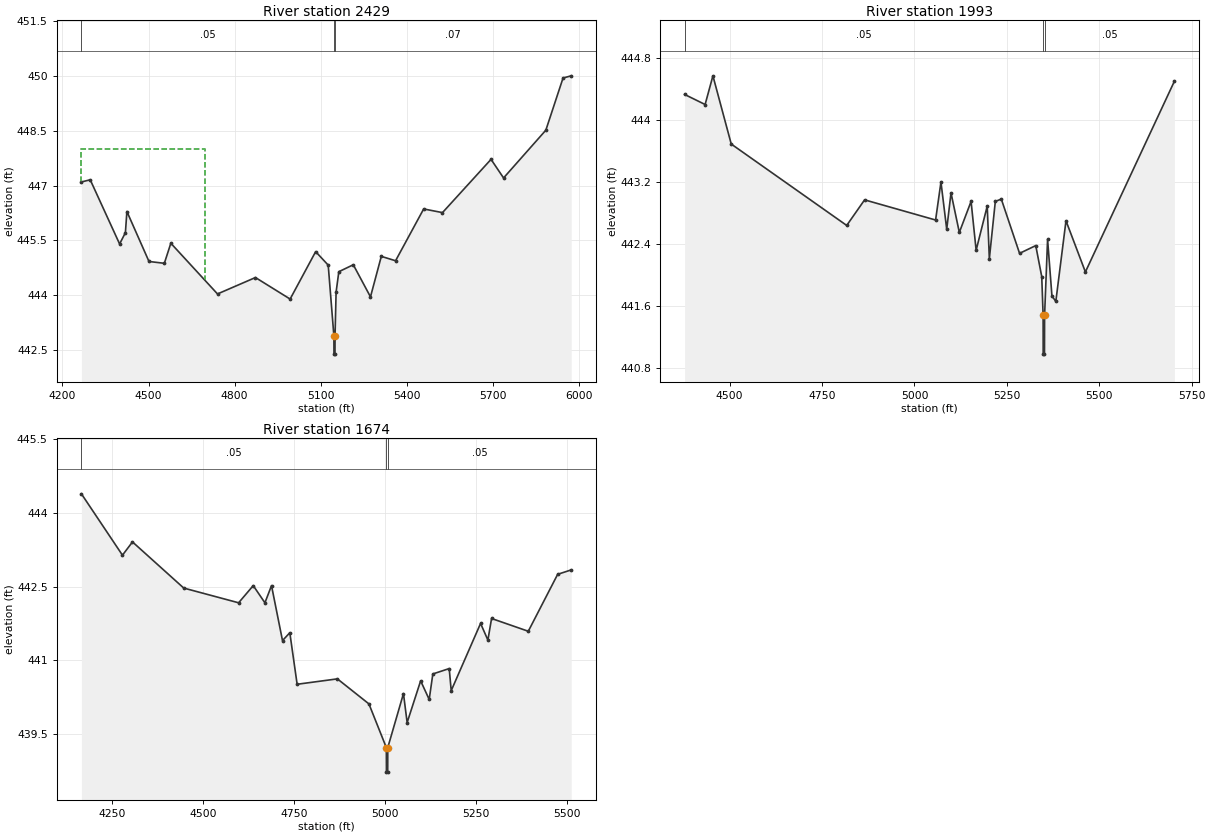
Type RM Length L Ch R = 1 ,2429    ,436,436,436
BEGIN DESCRIPTION:
Allen T6 2.0
END DESCRIPTION:
XS GIS Cut Line= 4
      2732066.75      6926121.04      2732124.18      6926379.97
      2732342.65       6926794.5       2733197.4      6927258.78
#Sta/Elev= 30
  4266.2   447.1  4296.9  447.16  4399.3   445.4  4419.5  445.71  4424.7  446.29
  4501.7  444.92  4555.2  444.87  4577.8  445.42  4740.4  444.03  4872.6  444.48
  4993.4  443.89  5082.4  445.19  5126.1  444.82  5145.9  442.88  5146.2  442.38
  5149.7  442.38  5149.9  442.88  5153.6  444.08  5163.1  444.64  5213.5  444.83
  5273.4  443.95  5311.1  445.06  5360.8  444.94  5458.7  446.36  5524.3  446.26
  5693.4  447.72  5737.1  447.21  5884.4  448.52  5944.3  449.95  5972.7  450.01
#Mann= 3 ,-1 , 0
  4266.2     .05       0  5145.9     .05       0  5149.9     .07       0
#XS Ineff= 2 , 0
       0  4696.3     448               0
Permanent Ineff=
       F       F
Bank Sta=5145.9,5149.9
XS Rating Curve= 0 ,0
Exp/Cntr=0.3,0.1

Type RM Length L Ch R = 1 ,1993    ,319,319,319
BEGIN DESCRIPTION:
Mapping XS 4ae6f312
END DESCRIPTION:
XS GIS Cut Line= 5
        2731901.      6926336.03      2731946.64      6926663.64
      2731969.86      6926920.47      2732060.52      6926990.15
      2732607.84       6927286.1
#Sta/Elev= 30
  4378.1  444.33  4433.6   444.2  4454.7  444.57  4504.3  443.69  4816.7  442.64
  4865.1  442.97  5057.2  442.71  5071.7   443.2  5087.3  442.59  5098.9  443.06
  5121.4  442.55  5153.2  442.95  5166.9  442.32  5196.9  442.89  5202.6  442.21
  5218.8  442.95    5235  442.98  5284.4  442.28  5328.2  442.38  5344.4  441.98
  5348.1  441.48  5348.3  440.98  5351.8  440.98  5352.1  441.48  5360.2  442.46
    5372  441.73  5382.5  441.66    5410   442.7  5462.5  442.04  5703.3   444.5
#Mann= 3 ,-1 , 0
  4378.1     .05       0  5348.1    .035       0  5352.1     .05       0
Bank Sta=5348.1,5352.1
XS Rating Curve= 0 ,0
Exp/Cntr=0.3,0.1

Type RM Length L Ch R = 1 ,1674    ,0,0,0
BEGIN DESCRIPTION:
Mapping XS 98713a81
END DESCRIPTION:
XS GIS Cut Line= 4
      2731882.28       6926381.3      2731803.03      6927151.82
      2731861.32      6927227.66      2732332.89      6927289.92
#Sta/Elev= 30
  4166.3  444.39  4279.1  443.14  4306.7  443.41  4447.5  442.47  4598.3  442.17
  4638.5  442.52  4670.6  442.17  4688.7  442.52  4718.9   441.4    4739  441.56
  4759.1  440.51  4869.7  440.62  4956.4  440.11  5004.2  439.22  5004.5  438.72
    5008  438.72  5008.2  439.22  5051.3  440.32  5061.4  439.73  5098.5  440.58
    5122   440.2    5132  440.72    5177  440.83  5182.5  440.38  5263.2  441.75
  5283.3  441.41  5293.4  441.85  5394.3  441.59    5475  442.75  5512.2  442.84
#Mann= 3 ,-1 , 0
  4166.3     .05       0  5004.2    .035       0  5008.2     .05       0
Bank Sta=5004.2,5008.2
XS Rating Curve= 0 ,0
Exp/Cntr=0.3,0.1

Chan Stop Cuts=-1
Use User Specified Reach Order=0
Composite Channel Slope=5