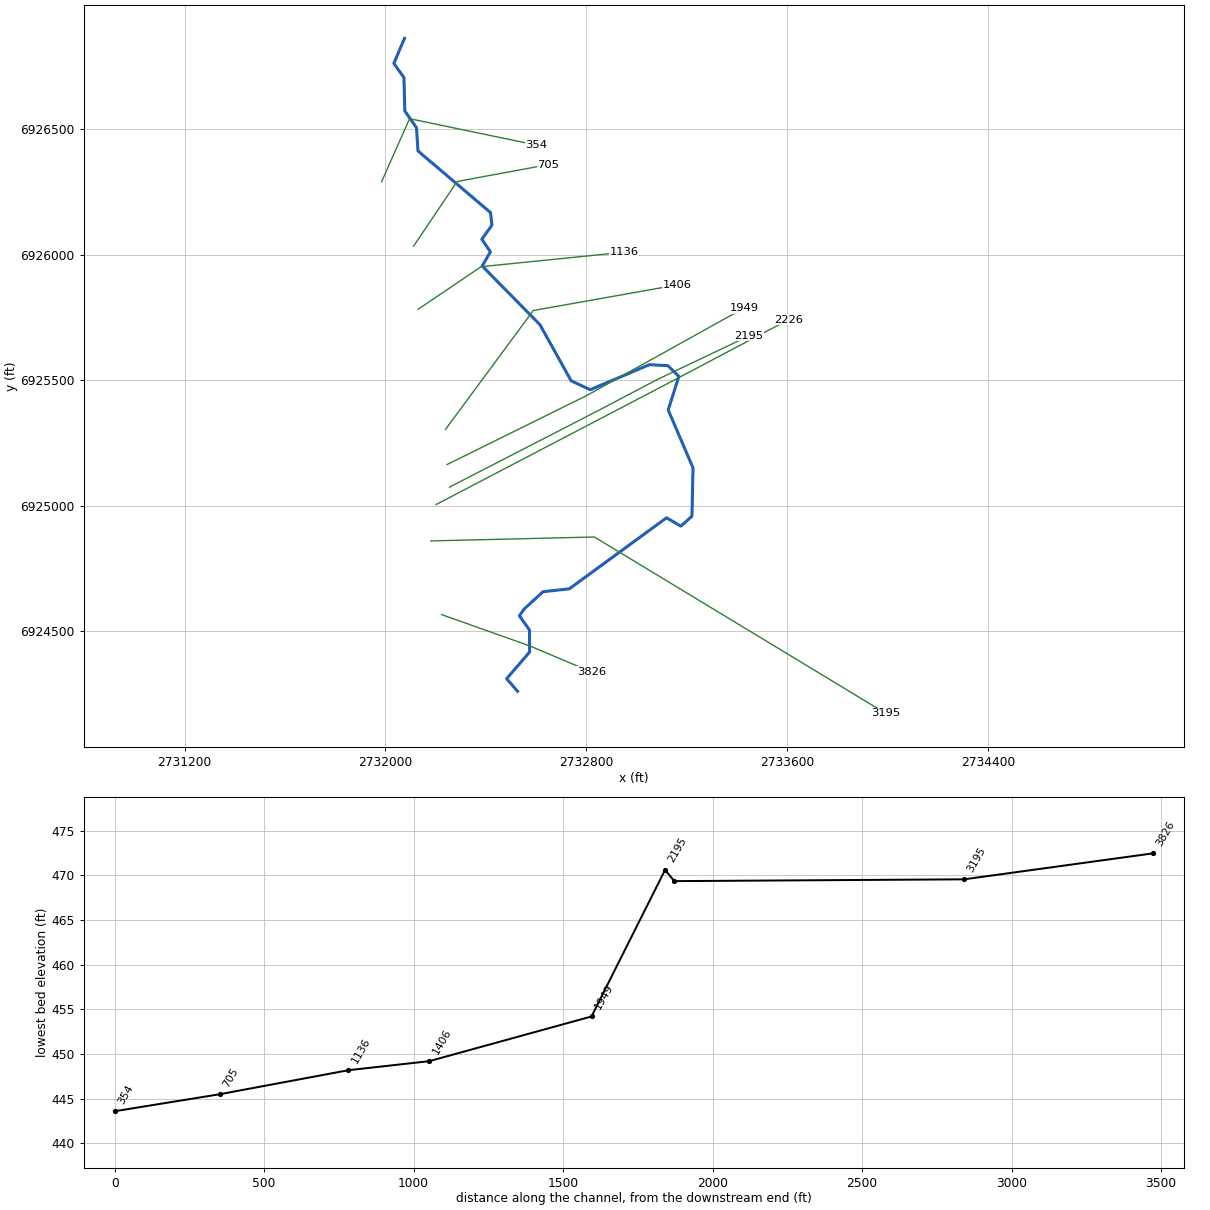
--- Allen T6_1.prj (project) ---

Proj Title=Allen T6_1 Base Level Engineering
Current Plan=p01
Default Exp/Contr=0.3,0.1
English Units
Geom File=g01
Flow File=f01
Plan File=p01
Y Axis Title=Elevation
X Axis Title(PF)=Main Channel Distance
X Axis Title(XS)=Station
BEGIN DESCRIPTION:
Allen T6_1
END DESCRIPTION:
DSS Export Rating Curves= 0
DSS Export Rating Curve Sorted= 0
DSS Export Volume Flow Curves= 0
DXF OffsetX= 0
DXF OffsetY= 0
DXF ScaleX= 1
DXF ScaleY= 10

--- Allen T6_1.p01 (plan) ---

Plan Title=Multiple Run
Short Identifier=Multiple
Geom File=g01
Flow File=f01
Subcritical Flow
K Sum by GR= 0
Std Step Tol= 0.01
Critical Tol= 0.01
Num of Std Step Trials= 20
Max Error Tol= 0.3
Flow Tol Ratio= 0.001
Split Flow NTrial= 30
Split Flow Tol= 0.02
Split Flow Ratio= 0.02
Log Output Level= 0
Friction Slope Method= 1
Unsteady Friction Slope Method= 2
Unsteady Bridges Friction Slope Method= 1
Parabolic Critical Depth
Global Vel Dist=  1 , 1 , 1
Global Log Level= 0
CheckData=True
Encroach Param= -1, 0, 0, 0
BEGIN DESCRIPTION:
Multiple Run
END DESCRIPTION:

--- Allen T6_1.f01 (steady flow) ---

Flow Title=Multiple
Program Version=4.10
Number of Profiles= 7
Profile Names=10-year,25-year,50-year,1pct_min,100-year,1pct_plu,500-year
River Rch & RM=Allen T6_1,Reach-1         ,3826
     235     295     341     196     392     781     514
River Rch & RM=Allen T6_1,Reach-1         ,1949
     280     356     415     241     480     959     641
Boundary for River Rch & Prof#=Allen T6_1,Reach-1         , 1
Up Type= 0
Dn Type= 3
Dn Slope=0.0067
Boundary for River Rch & Prof#=Allen T6_1,Reach-1         , 2
Up Type= 0
Dn Type= 3
Dn Slope=0.0067
Boundary for River Rch & Prof#=Allen T6_1,Reach-1         , 3
Up Type= 0
Dn Type= 3
Dn Slope=0.0067
Boundary for River Rch & Prof#=Allen T6_1,Reach-1         , 4
Up Type= 0
Dn Type= 3
Dn Slope=0.0067
Boundary for River Rch & Prof#=Allen T6_1,Reach-1         , 5
Up Type= 0
Dn Type= 3
Dn Slope=0.0067
Boundary for River Rch & Prof#=Allen T6_1,Reach-1         , 6
Up Type= 0
Dn Type= 3
Dn Slope=0.0067
Boundary for River Rch & Prof#=Allen T6_1,Reach-1         , 7
Up Type= 0
Dn Type= 3
Dn Slope=0.0067
DSS Import GetInterval= 0
DSS Import GetPeak= 0
DSS Import FillOption= 0

--- Allen T6_1.g01 (geometry) ---

Geom Title=Existing Conditions
Program Version=4.10

River Reach=Allen T6_1      ,Reach-1
Reach XY= 30
        2732526.        6924261.      2732482.59      6924310.99
      2732574.02      6924416.89      2732573.63      6924505.11
      2732533.31      6924561.11      2732551.69      6924587.76
      2732627.47      6924657.39      2732732.16      6924668.88
      2733119.35      6924951.68      2733176.25      6924918.46
      2733220.54        6924958.      2733224.78       6925150.5
      2733125.91       6925381.1      2733168.32      6925514.71
      2733124.98      6925557.55      2733051.02      6925561.41
      2732815.24       6925461.7      2732739.48       6925497.3
      2732615.22      6925720.68      2732385.29      6925954.33
      2732417.96        6926011.      2732383.81      6926060.91
      2732424.03      6926117.05       2732418.5      6926167.05
      2732129.61      6926412.48      2732123.64      6926505.02
      2732077.23      6926571.51      2732073.54      6926705.14
      2732033.31      6926761.04        2732076.        6926861.

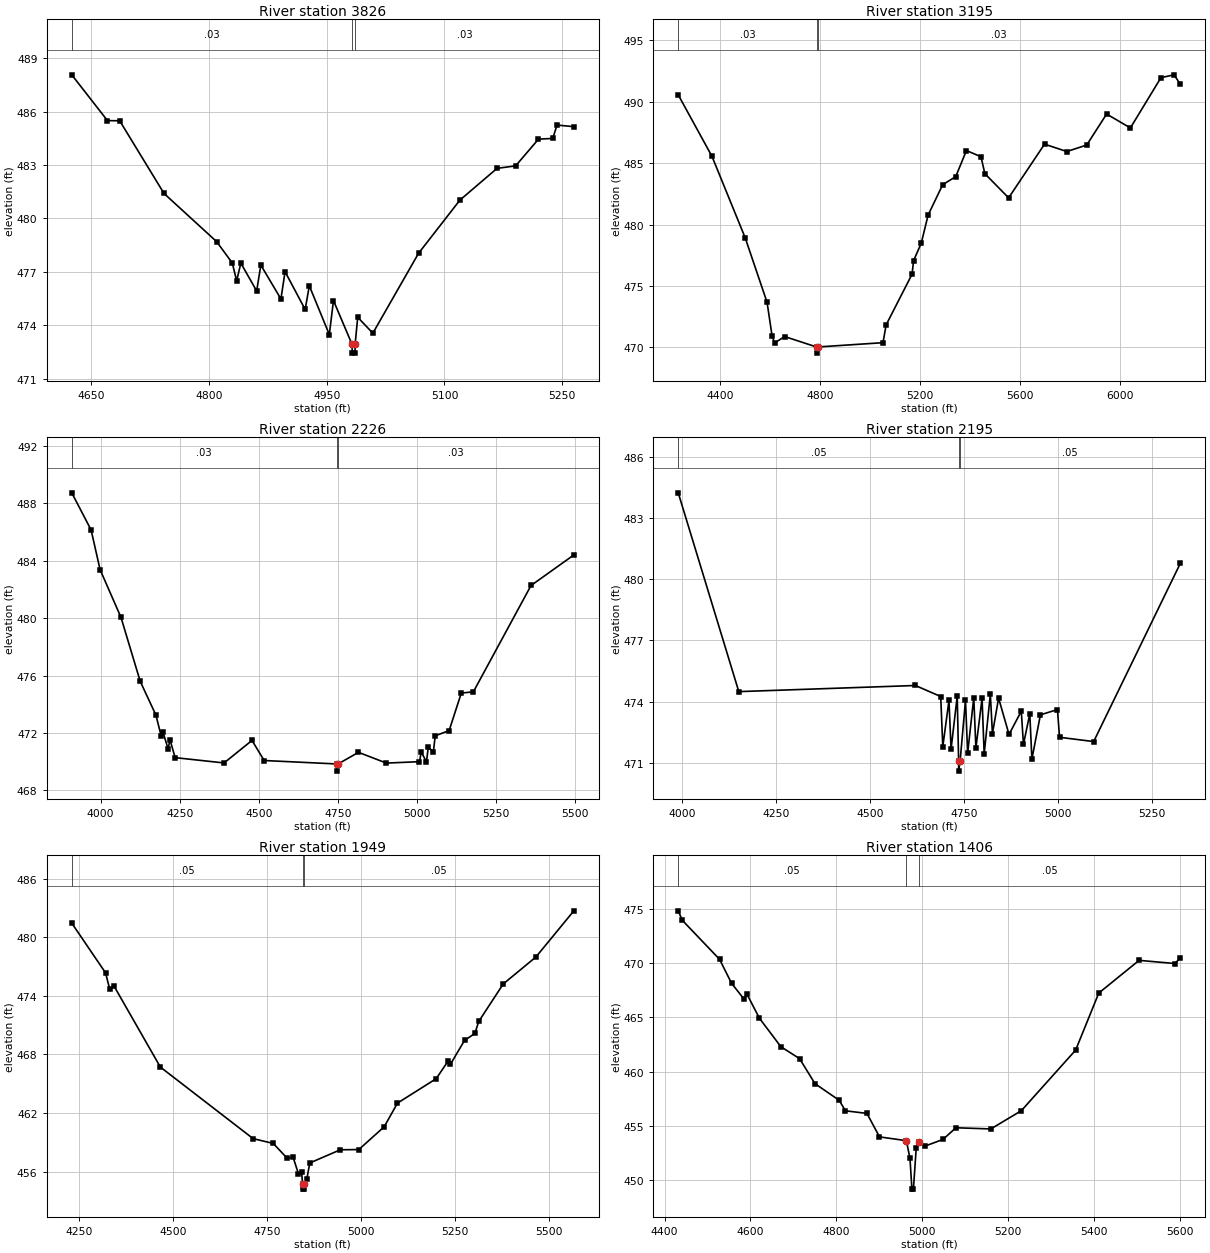
Type RM Length L Ch R = 1 ,3826    ,631,631,631
BEGIN DESCRIPTION:
Allen T6_1 5.0
END DESCRIPTION:
XS GIS Cut Line= 3
      2732223.15      6924566.36      2732576.65      6924440.92
      2732820.56      6924337.56
#Sta/Elev= 30
  4624.9  488.06  4670.4  485.49    4686  485.48  4742.5   481.4  4809.5   478.7
  4829.5   477.5  4835.1   476.5  4840.4  477.49  4860.6  475.93  4865.9  477.38
  4891.5  475.48  4896.8  477.01  4922.4  474.89  4927.7  476.22  4953.2  473.48
  4958.5  475.39  4982.1  472.94  4982.4  472.44  4985.9  472.44  4986.1  472.94
  4989.4  474.45  5008.7  473.56  5066.9  478.04  5119.7  481.03    5167  482.81
  5190.7  482.95  5219.8  484.45    5238  484.49  5243.5  485.24  5264.9  485.15
#Mann= 3 ,-1 , 0
  4624.9     .03       0  4982.1     .03       0  4986.1     .03       0
Bank Sta=4982.1,4986.1
XS Rating Curve= 0 ,0
Exp/Cntr=0.3,0.1

Type RM Length L Ch R = 1 ,3195    ,969,969,969
BEGIN DESCRIPTION:
Mapping XS b09c9dd3
END DESCRIPTION:
XS GIS Cut Line= 3
      2732180.93      6924859.63      2732832.01      6924875.25
      2733992.21      6924172.89
#Sta/Elev= 30
  4233.6  490.55  4368.7  485.54  4501.5  478.91  4588.8  473.67  4608.8  470.94
  4618.8  470.36  4658.8  470.89  4786.8  470.04  4787.1  469.54  4790.8  470.04
  5052.3  470.39  5064.9  471.84  5168.7  475.97  5174.5  477.06  5205.2  478.48
  5232.7  480.77  5290.9  483.24  5343.2   483.9  5385.9  486.02  5444.1  485.52
  5459.6  484.14  5554.6  482.17  5698.2  486.54  5787.4  485.94  5866.9  486.47
  5946.4  488.99  6041.5  487.86  6163.7  491.95    6216  492.18  6241.1  491.42
#Mann= 3 ,-1 , 0
  4233.6     .03       0  4786.8     .03       0  4790.8     .03       0
Bank Sta=4786.8,4790.8
XS Rating Curve= 0 ,0
Exp/Cntr=0.3,0.1

Type RM Length L Ch R = 1 ,2226    ,31,31,31
BEGIN DESCRIPTION:
Allen T6_1 3.0
END DESCRIPTION:
XS GIS Cut Line= 3
      2732201.87      6925004.58      2733101.37      6925474.67
      2733606.76      6925741.21
#Sta/Elev= 30
  3909.1  488.74  3970.2  486.15  3998.5  483.39  4064.7  480.05  4125.3   475.6
  4175.1  473.24  4191.5  471.79  4197.2  472.06  4213.6  470.88  4219.2  471.54
  4235.7  470.28  4390.2  469.91  4478.5  471.48    4517  470.08  4746.6  469.84
  4746.9  469.34  4750.6  469.84  4814.9  470.65  4903.2   469.9  5007.7     470
  5013.3  470.68  5029.7  469.98  5035.4  470.99  5051.7   470.7  5057.4   471.8
  5101.4  472.17  5139.8  474.78    5178  474.87  5360.1  482.28  5495.4  484.41
#Mann= 3 ,-1 , 0
  3909.1     .03       0  4746.6     .03       0  4750.6     .03       0
Bank Sta=4746.6,4750.6
XS Rating Curve= 0 ,0
Exp/Cntr=0.3,0.1

Type RM Length L Ch R = 1 ,2195    ,246,246,246
BEGIN DESCRIPTION:
Mapping XS 216730cf
END DESCRIPTION:
XS GIS Cut Line= 4
       2732254.8      6925073.75       2732855.5      6925382.78
      2733075.99       6925499.1      2733447.35       6925676.1
#Sta/Elev= 30
    3990  484.24  4151.2  474.49  4621.1  474.79  4688.5  474.25  4694.1  471.79
  4710.5  474.06  4716.1  471.67  4732.5  474.27  4736.2  471.09  4736.4  470.59
  4740.2  471.09  4754.5  474.06  4760.2  471.46  4776.5  474.19  4782.2  471.73
  4798.6  474.16  4804.2  471.43  4820.6  474.36  4826.2  472.43  4842.6  474.17
  4870.3  472.39    4903  473.53  4908.7   471.9  4925.6   473.4  4931.2  471.18
  4953.9  473.35  4999.2  473.61  5004.8  472.25  5095.6  472.04  5326.2  480.78
#Mann= 3 ,-1 , 0
    3990     .05       0  4736.2     .04       0  4740.2     .05       0
Bank Sta=4736.2,4740.2
XS Rating Curve= 0 ,0
Exp/Cntr=0.3,0.1

Type RM Length L Ch R = 1 ,1949    ,543,543,543
BEGIN DESCRIPTION:
Mapping XS 3135b4ef
END DESCRIPTION:
XS GIS Cut Line= 3
      2732245.36      6925163.76      2732799.11       6925437.3
        2733427.      6925786.33
#Sta/Elev= 30
  4230.8  481.44  4320.7  476.35  4331.9  474.66    4343  475.01  4466.5   466.7
  4713.4  459.37  4766.9  458.88  4803.1   457.4    4820  457.44  4833.8  455.79
  4842.4  455.93    4845   454.7  4845.2   454.2  4848.7   454.2    4849   454.7
  4856.3  455.25  4864.2  456.88  4945.4  458.23  4994.6  458.25  5062.2  460.59
  5097.5  463.01  5200.5  465.51  5232.5  467.33  5238.2  466.97  5275.9  469.43
  5303.4  470.14  5313.7  471.37  5378.9  475.21  5465.8  477.97  5566.8   482.7
#Mann= 3 ,-1 , 0
  4230.8     .05       0    4845     .04       0    4849     .05       0
Bank Sta=4845,4849
XS Rating Curve= 0 ,0
Exp/Cntr=0.3,0.1

Type RM Length L Ch R = 1 ,1406    ,270,270,270
BEGIN DESCRIPTION:
Mapping XS 5975b3f2
END DESCRIPTION:
XS GIS Cut Line= 3
      2732239.03      6925303.58       2732588.6      6925777.09
      2733160.56      6925878.77
#Sta/Elev= 30
  4431.7  474.82  4441.1  473.95  4527.9  470.36  4555.9  468.15  4585.2  466.68
  4591.4  467.18  4620.7  464.94  4670.8  462.31  4714.4  461.21  4750.2  458.91
  4806.5  457.38  4821.2  456.41  4871.3  456.17  4900.5  454.01  4963.1  453.66
  4971.5  452.03    4976   449.2  4979.5   449.2  4986.1  453.01  4992.3  453.57
    5007  453.17  5048.1  453.77  5078.6  454.85  5159.8  454.74  5230.9  456.42
  5357.4     462  5411.3  467.25  5505.2  470.26  5588.4  469.97  5601.2  470.47
#Mann= 3 ,-1 , 0
  4431.7     .05       0  4963.1    .035       0  4992.3     .05       0
Bank Sta=4963.1,4992.3
XS Rating Curve= 0 ,0
Exp/Cntr=0.3,0.1

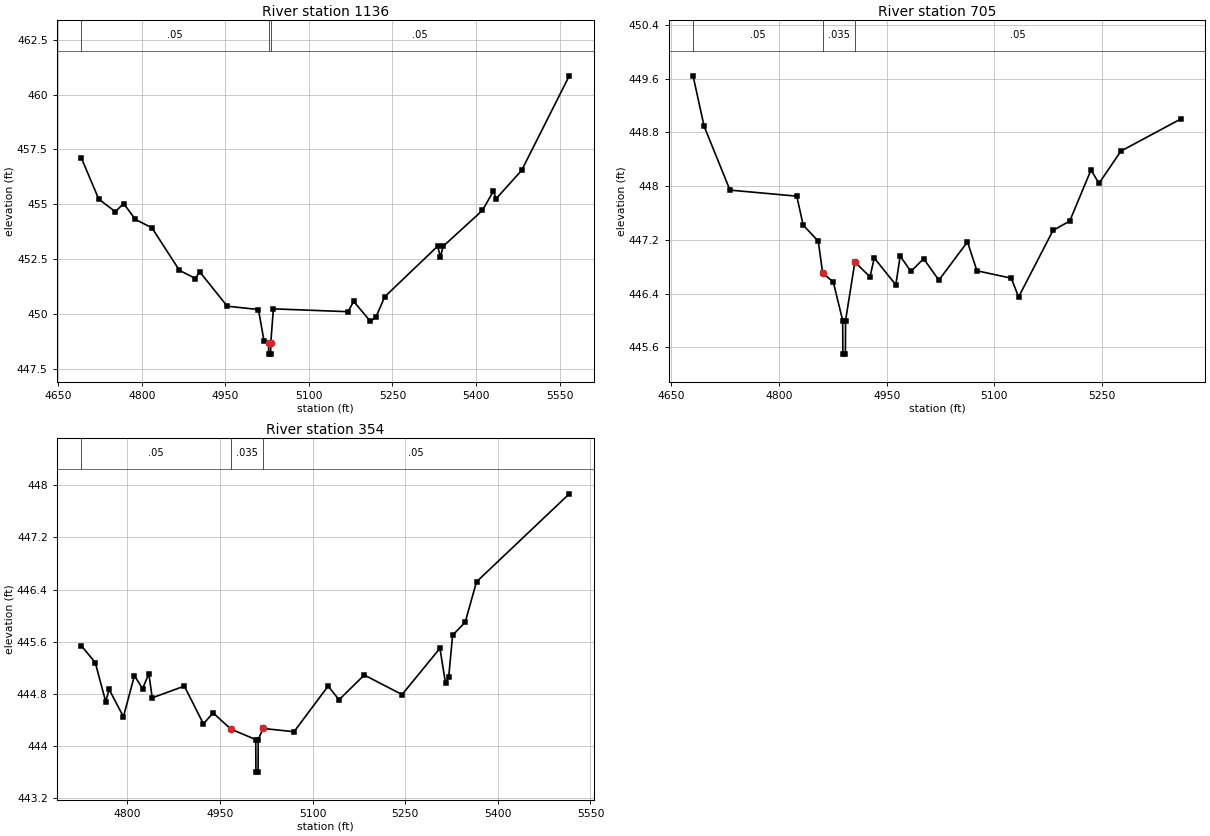
Type RM Length L Ch R = 1 ,1136    ,431,431,431
BEGIN DESCRIPTION:
Mapping XS 91d38952
END DESCRIPTION:
XS GIS Cut Line= 3
       2732130.1      6925782.03      2732381.07      6925951.64
      2732951.06      6926009.27
#Sta/Elev= 30
  4691.6  457.12  4722.9  455.24  4752.6  454.67  4767.6  455.04  4788.6  454.32
  4818.5  453.93  4867.7     452  4896.5  451.63  4903.9  451.94  4953.5  450.37
  5009.5  450.22  5019.6  448.78  5027.6  448.69  5027.9  448.19  5031.4  448.19
  5031.6  448.69  5036.3  450.25  5170.3  450.12  5180.4  450.59  5210.5  449.68
  5220.6  449.89  5236.2   450.8  5331.1   453.1  5336.1  452.62  5341.2   453.1
  5411.6  454.73  5431.1   455.6  5436.1  455.26  5481.9  456.55  5567.4  460.85
#Mann= 3 ,-1 , 0
  4691.6     .05       0  5027.6    .035       0  5031.6     .05       0
Bank Sta=5027.6,5031.6
XS Rating Curve= 0 ,0
Exp/Cntr=0.3,0.1

Type RM Length L Ch R = 1 ,705     ,351,351,351
BEGIN DESCRIPTION:
Mapping XS a7c45152
END DESCRIPTION:
XS GIS Cut Line= 3
      2732112.11      6926033.61      2732285.51      6926290.98
      2732648.35      6926357.99
#Sta/Elev= 30
  4680.5  449.64  4695.9  448.89  4731.9  447.94  4824.9  447.85  4833.8  447.42
  4854.8  447.18  4860.9  446.71  4875.8  446.57  4888.8     446  4889.1   445.5
  4892.6   445.5  4892.8     446  4905.8  446.87  4926.8  446.65  4932.8  446.93
  4962.8  446.53  4968.8  446.96  4983.8  446.73  5001.5  446.92  5022.7   446.6
  5062.5  447.17  5075.7  446.74  5123.5  446.63  5133.7  446.35  5181.6  447.34
  5204.9  447.48  5234.5  448.24  5245.6  448.04  5276.1  448.52  5359.8     449
#Mann= 3 ,-1 , 0
  4680.5     .05       0  4860.9    .035       0  4905.8     .05       0
Bank Sta=4860.9,4905.8
XS Rating Curve= 0 ,0
Exp/Cntr=0.3,0.1

Type RM Length L Ch R = 1 ,354     ,0,0,0
BEGIN DESCRIPTION:
Allen T6_1 1.0
END DESCRIPTION:
XS GIS Cut Line= 3
      2731984.78      6926290.34      2732096.09      6926541.04
      2732600.98        6926436.
#Sta/Elev= 30
  4725.7  445.54  4748.3  445.28  4765.2  444.68  4770.7  444.87  4793.9  444.45
  4811.7  445.08  4824.9  444.88    4835  445.11  4840.5  444.74  4892.5  444.92
  4923.4  444.34    4939  444.51  4967.7  444.26  5008.1   444.1  5008.4   443.6
  5011.9   443.6  5012.1   444.1    5020  444.27  5070.1  444.22  5125.3  444.92
  5142.9  444.71  5183.8  445.09    5245  444.79  5306.3   445.5  5315.4  444.96
  5320.5  445.06  5326.8   445.7  5347.2   445.9  5365.5  446.52  5515.7  447.87
#Mann= 3 ,-1 , 0
  4725.7     .05       0  4967.7    .035       0    5020     .05       0
Bank Sta=4967.7,5020
XS Rating Curve= 0 ,0
Exp/Cntr=0.3,0.1

Chan Stop Cuts=-1
Use User Specified Reach Order=0
Composite Channel Slope=5