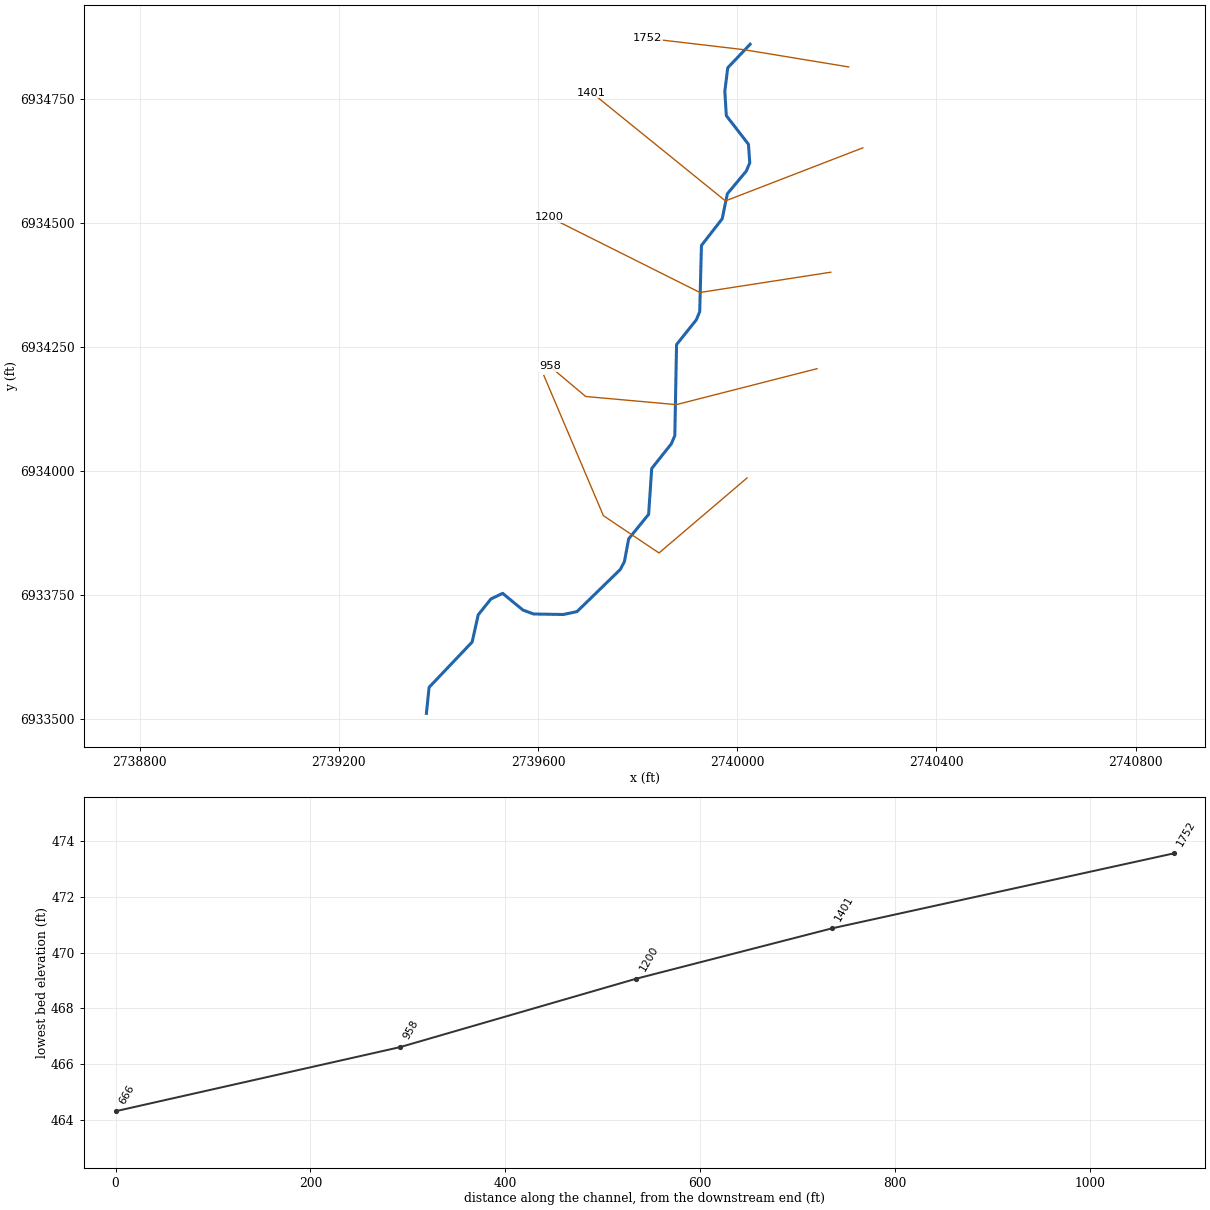
--- Allen T7.prj (project) ---

Proj Title=Allen T7 Base Level Engineering
Current Plan=p01
Default Exp/Contr=0.3,0.1
English Units
Geom File=g01
Flow File=f01
Plan File=p01
BEGIN DESCRIPTION:
Allen T7
END DESCRIPTION:

--- Allen T7.p01 (plan) ---

Plan Title=Multiple Run
Short Identifier=Multiple
Geom File=g01
Flow File=f01
Subcritical Flow
K Sum by GR= 0
Std Step Tol= 0.01
Critical Tol= 0.01
Num of Std Step Trials= 20
Max Error Tol= 0.3
Flow Tol Ratio= 0.001
Split Flow NTrial= 30
Split Flow Tol= 0.02
Split Flow Ratio= 0.02
Log Output Level= 0
Friction Slope Method= 1
Unsteady Friction Slope Method= 2
Unsteady Bridges Friction Slope Method= 1
Parabolic Critical Depth
Global Vel Dist=  1 , 1 , 1
Global Log Level= 0
CheckData=True
Encroach Param= -1, 0, 0, 0
BEGIN DESCRIPTION:
Multiple Run
END DESCRIPTION:

--- Allen T7.f01 (steady flow) ---

Flow Title=Multiple
Number of Profiles=7
Profile Names=10-year,25-year,50-year,1pct_min,100-year,1pct_plu,500-year
River Rch & RM= Allen T7,Reach-1,1752
     162     199     227     129     258     514     331
Boundary for River Rch & Prof#=Allen T7,Reach-1,1
Up Type=0
Dn Type=3
Dn Slope=0.005
Boundary for River Rch & Prof#=Allen T7,Reach-1,2
Up Type=0
Dn Type=3
Dn Slope=0.005
Boundary for River Rch & Prof#=Allen T7,Reach-1,3
Up Type=0
Dn Type=3
Dn Slope=0.005
Boundary for River Rch & Prof#=Allen T7,Reach-1,4
Up Type=0
Dn Type=3
Dn Slope=0.005
Boundary for River Rch & Prof#=Allen T7,Reach-1,5
Up Type=0
Dn Type=3
Dn Slope=0.005
Boundary for River Rch & Prof#=Allen T7,Reach-1,6
Up Type=0
Dn Type=3
Dn Slope=0.005
Boundary for River Rch & Prof#=Allen T7,Reach-1,7
Up Type=0
Dn Type=3
Dn Slope=0.005

--- Allen T7.g01 (geometry) ---

Geom Title=Existing Conditions

River Reach=Allen T7,Reach-1
Reach XY= 30
      2740026.00      6934861.00      2739981.05      6934813.55
      2739975.19      6934765.99      2739978.18      6934716.95
      2740022.63      6934659.27      2740025.25      6934621.68
      2740018.23      6934605.06      2739980.22      6934559.28
      2739969.89      6934508.82      2739928.25      6934455.07
      2739924.77      6934321.51      2739917.85      6934304.95
      2739878.26      6934255.06      2739874.78      6934071.50
      2739867.86      6934054.94      2739828.36      6934005.02
      2739822.18      6933912.58      2739782.14      6933863.17
      2739773.51      6933817.02      2739765.25      6933801.29
      2739678.44      6933716.39      2739651.04      6933710.51
      2739591.21      6933711.52      2739569.81      6933719.43
      2739529.03      6933753.20      2739505.58      6933741.87
      2739479.97      6933709.83      2739467.84      6933654.99
      2739381.33      6933563.51      2739376.00      6933511.00

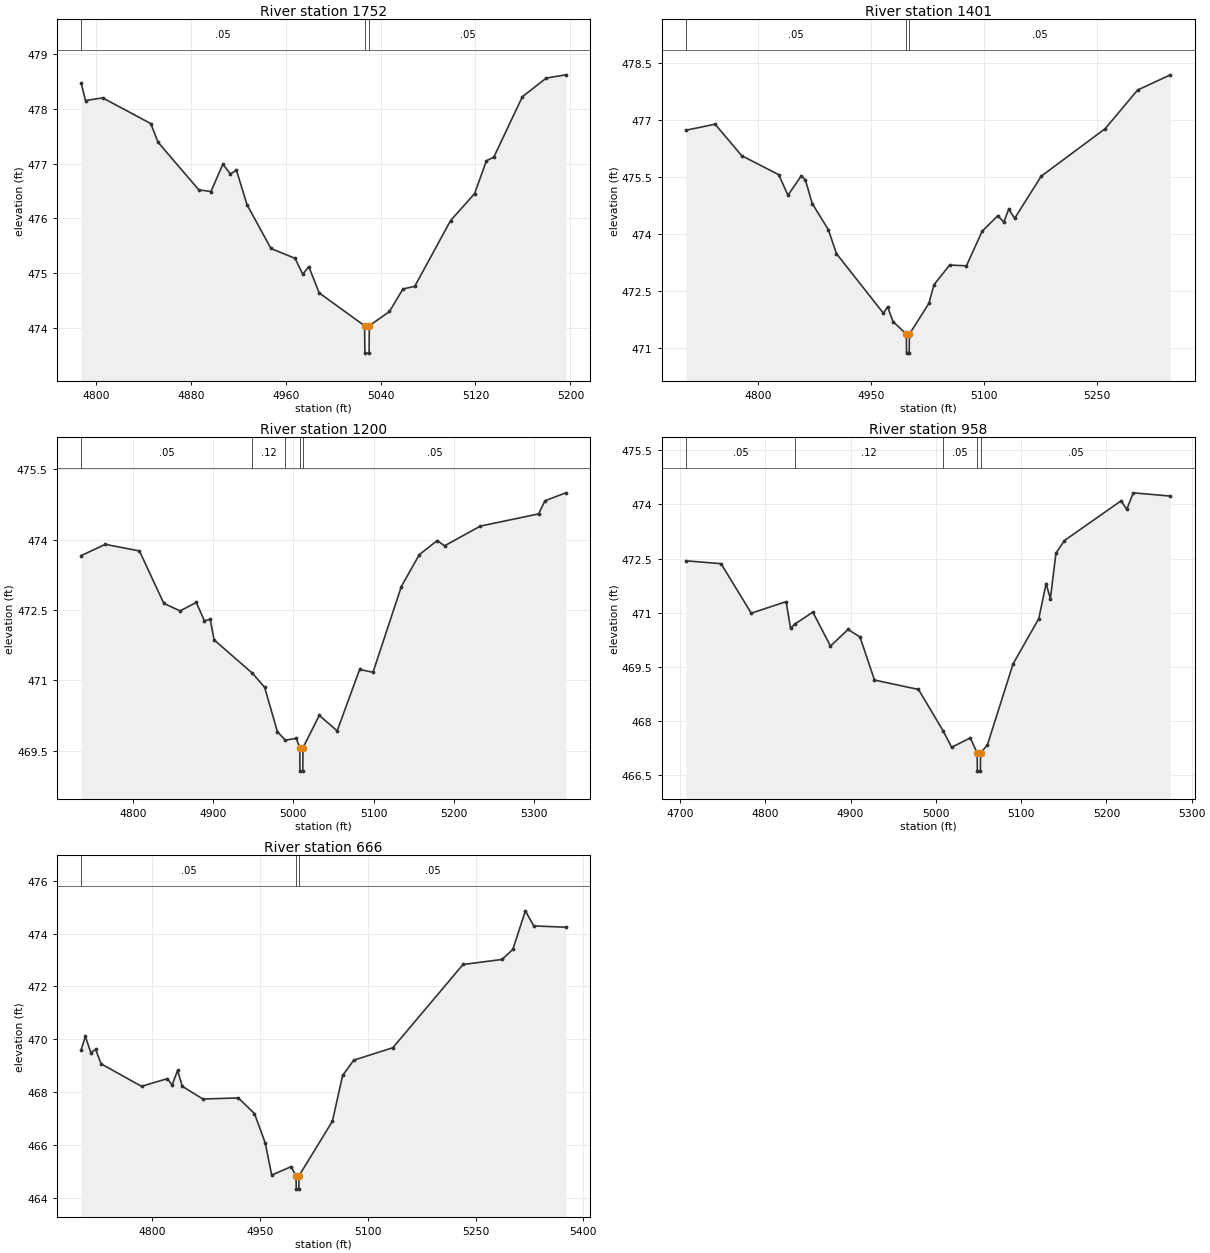
Type RM Length L Ch R = 1,1752,351,351,351
BEGIN DESCRIPTION:
Allen T7 1.0
END DESCRIPTION:
XS GIS Cut Line= 3
      2740223.90      6934815.26      2740013.59      6934850.07
      2739819.60      6934872.95
#Sta/Elev= 30
  4787.6  478.47  4791.3  478.15  4805.7  478.20  4846.3  477.73  4852.4  477.39
  4886.8  476.52  4897.0  476.49  4907.1  476.99  4913.4  476.81  4918.5  476.88
  4927.4  476.25  4947.6  475.45  4967.9  475.27  4974.4  474.98  4979.5  475.12
  4988.2  474.64  5026.5  474.04  5026.8  473.54  5030.3  473.54  5030.5  474.04
  5047.5  474.30  5058.8  474.71  5068.8  474.76  5099.0  475.96  5119.2  476.45
  5129.2  477.05  5135.5  477.12  5159.5  478.22  5179.6  478.56  5196.1  478.62
#Mann=3,-1,0
  4787.6    0.05       0  5026.5    0.04       0  5030.5    0.05       0
Bank Sta=5026.5,5030.5
Exp/Cntr=0.3,0.1

Type RM Length L Ch R = 1,1401,201,201,201
BEGIN DESCRIPTION:
Mapping XS fed08ea6
END DESCRIPTION:
XS GIS Cut Line= 3
      2740252.21      6934652.00      2739976.44      6934544.96
      2739707.57      6934763.66
#Sta/Elev= 30
  4704.7  476.73  4743.5  476.89  4778.8  476.06  4827.9  475.56  4840.1  475.02
  4857.8  475.53  4863.2  475.42  4872.3  474.80  4893.7  474.11  4904.4  473.48
  4966.7  471.91  4972.1  472.08  4979.5  471.69  4997.1  471.36  4997.3  470.86
  5000.8  470.86  5001.1  471.36  5026.9  472.17  5033.6  472.66  5054.4  473.18
  5076.7  473.16  5097.5  474.07  5118.3  474.48  5126.2  474.31  5132.7  474.65
  5140.6  474.41  5175.8  475.52  5260.5  476.77  5303.6  477.79  5347.1  478.19
#Mann=3,-1,0
  4704.7    0.05       0  4997.1    0.04       0  5001.1    0.05       0
Bank Sta=4997.1,5001.1
Exp/Cntr=0.3,0.1

Type RM Length L Ch R = 1,1200,242,242,242
BEGIN DESCRIPTION:
Mapping XS a5a972da
END DESCRIPTION:
XS GIS Cut Line= 3
      2740187.88      6934401.08      2739925.18      6934360.17
      2739622.74      6934512.27
#Sta/Elev= 30
  4735.3  473.66  4765.4  473.90  4808.0  473.76  4838.4  472.64  4858.7  472.48
  4878.9  472.66  4889.0  472.27  4896.2  472.30  4901.2  471.86  4948.9  471.15
  4964.1  470.85  4980.1  469.90  4990.0  469.72  5003.5  469.76  5008.0  469.56
  5008.2  469.06  5011.7  469.06  5012.0  469.56  5032.3  470.25  5054.6  469.92
  5082.6  471.23  5099.3  471.17  5134.6  473.00  5157.0  473.68  5179.3  473.98
  5188.6  473.87  5233.2  474.29  5305.8  474.55  5313.7  474.83  5339.7  475.00
#Mann=5,-1,0
  4735.3    0.05       0  4948.9    0.12       0  4990.0    0.05       0
  5008.0    0.04       0  5012.0    0.05       0
Bank Sta=5008,5012
Exp/Cntr=0.3,0.1

Type RM Length L Ch R = 1,958,292,292,292
BEGIN DESCRIPTION:
Mapping XS d3da0ea4
END DESCRIPTION:
XS GIS Cut Line= 4
      2740160.34      6934206.47      2739877.85      6934133.91
      2739695.82      6934150.34      2739624.04      6934210.99
#Sta/Elev= 30
  4706.7  472.44  4748.0  472.36  4783.5  470.99  4824.4  471.31  4829.5  470.58
  4834.7  470.69  4855.7  471.02  4876.4  470.08  4897.0  470.54  4911.0  470.33
  4928.0  469.14  4979.6  468.88  5008.6  467.73  5018.5  467.28  5040.4  467.54
  5048.4  467.12  5048.7  466.62  5052.2  466.62  5052.4  467.12  5060.5  467.35
  5090.6  469.59  5120.7  470.84  5129.3  471.81  5134.3  471.39  5140.8  472.65
  5150.8  473.00  5217.3  474.10  5223.8  473.86  5231.5  474.32  5275.1  474.23
#Mann=5,-1,0
  4706.7    0.05       0  4834.7    0.12       0  5008.6    0.05       0
  5048.4    0.07       0  5052.4    0.05       0
Bank Sta=5048.4,5052.4
Exp/Cntr=0.3,0.1

Type RM Length L Ch R = 1,666,0,0,0
BEGIN DESCRIPTION:
Allen T7 0.0
END DESCRIPTION:
XS GIS Cut Line= 4
      2740019.82      6933986.01      2739843.00      6933834.63
      2739731.34      6933909.90      2739611.81      6934192.75
#Sta/Elev= 30
  4701.0  469.60  4706.8  470.11  4714.5  469.49  4721.1  469.62  4728.8  469.07
  4785.0  468.22  4821.0  468.51  4827.6  468.27  4835.2  468.82  4841.8  468.22
  4870.4  467.74  4919.8  467.78  4942.2  467.19  4957.2  466.08  4966.2  464.86
  4993.2  465.18  5000.1  464.83  5000.4  464.33  5003.9  464.33  5004.1  464.83
  5050.7  466.90  5064.9  468.63  5080.5  469.21  5134.8  469.68  5232.5  472.83
  5286.8  473.02  5301.8  473.40  5319.3  474.86  5330.9  474.29  5375.5  474.24
#Mann=3,-1,0
  4701.0    0.05       0  5000.1    0.05       0  5004.1    0.05       0
Bank Sta=5000.1,5004.1
Exp/Cntr=0.3,0.1

Chan Stop Cuts=-1