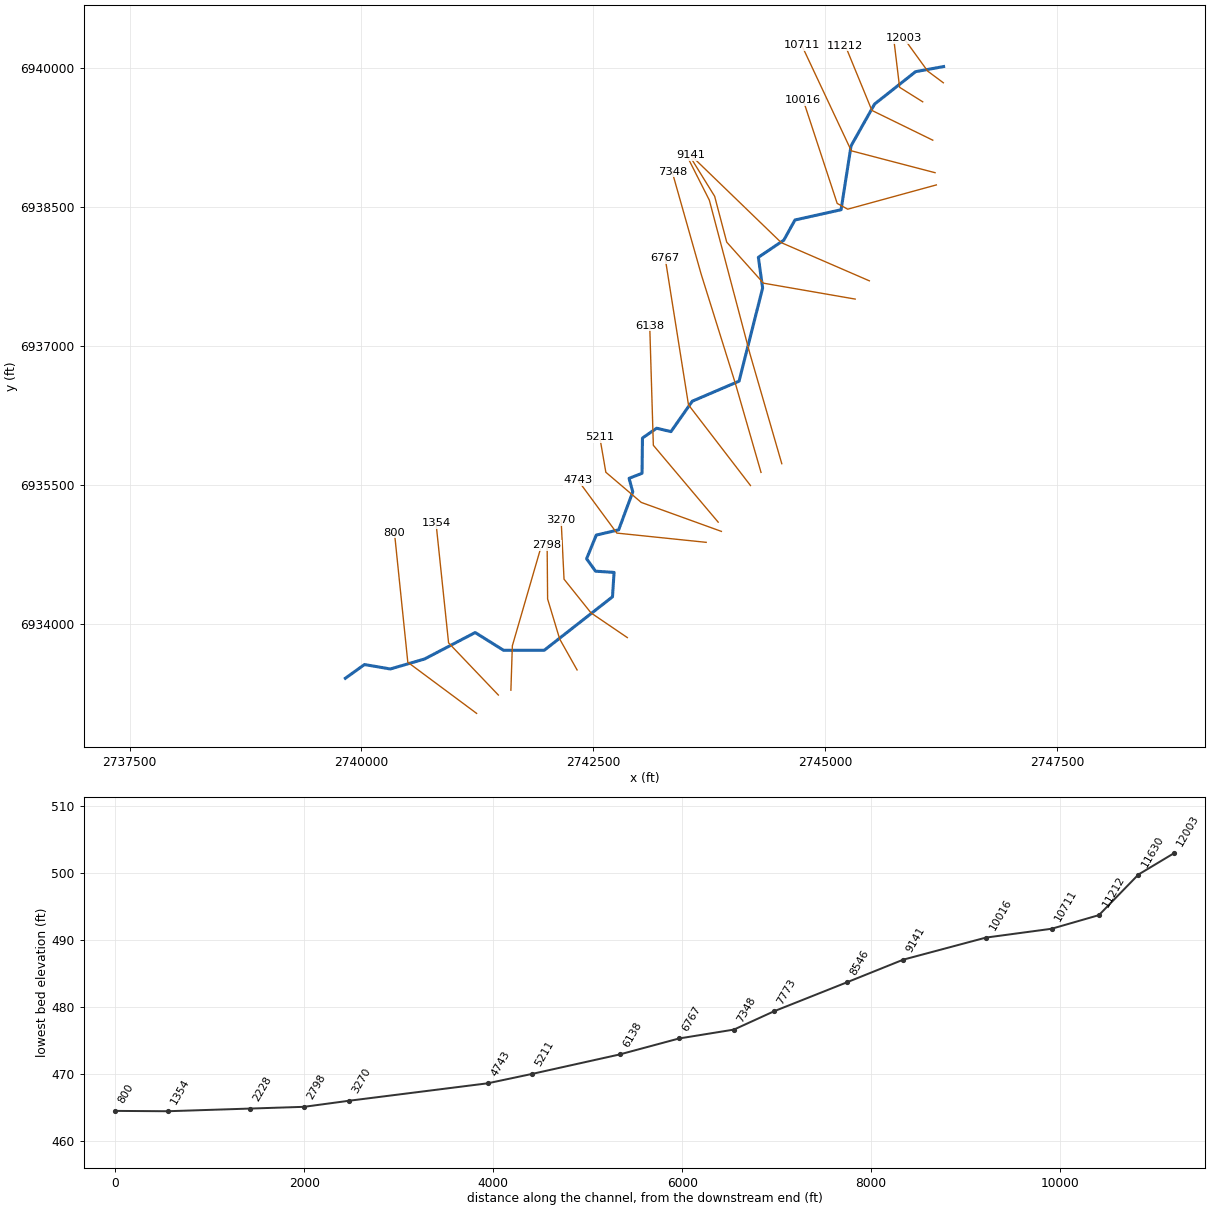
--- Allen T8.prj (project) ---

Proj Title=Allen T8 Base Level Engineering
Current Plan=p01
Default Exp/Contr=0.3,0.1
English Units
Geom File=g01
Flow File=f01
Plan File=p01
Y Axis Title=Elevation
X Axis Title(PF)=Main Channel Distance
X Axis Title(XS)=Station
BEGIN DESCRIPTION:
Allen T8
END DESCRIPTION:
DSS Export Rating Curves= 0
DSS Export Rating Curve Sorted= 0
DSS Export Volume Flow Curves= 0
DXF OffsetX= 0
DXF OffsetY= 0
DXF ScaleX= 1
DXF ScaleY= 10

--- Allen T8.p01 (plan) ---

Plan Title=Multiple Run
Short Identifier=Multiple
Geom File=g01
Flow File=f01
Subcritical Flow
K Sum by GR= 0
Std Step Tol= 0.01
Critical Tol= 0.01
Num of Std Step Trials= 20
Max Error Tol= 0.3
Flow Tol Ratio= 0.001
Split Flow NTrial= 30
Split Flow Tol= 0.02
Split Flow Ratio= 0.02
Log Output Level= 0
Friction Slope Method= 1
Unsteady Friction Slope Method= 2
Unsteady Bridges Friction Slope Method= 1
Parabolic Critical Depth
Global Vel Dist=  1 , 1 , 1
Global Log Level= 0
CheckData=True
Encroach Param= -1, 0, 0, 0
BEGIN DESCRIPTION:
Multiple Run
END DESCRIPTION:

--- Allen T8.f01 (steady flow) ---

Flow Title=Multiple
Program Version=4.10
Number of Profiles= 7
Profile Names=10-year,25-year,50-year,1pct_min,100-year,1pct_plu,500-year
River Rch & RM=Allen T8,Reach-1         ,12003
     257     326     378     219     437     872     582
River Rch & RM=Allen T8,Reach-1         ,10016
     319     410     481     281     560    1118     760
River Rch & RM=Allen T8,Reach-1         ,8546
     676     906    1093     655    1307    2607    1870
River Rch & RM=Allen T8,Reach-1         ,3270
     732     984    1190     713    1424    2840    2043
River Rch & RM=Allen T8,Reach-1         ,1354
    1027    1404    1715    1039    2072    4135    3033
Boundary for River Rch & Prof#=Allen T8,Reach-1         , 1
Up Type= 0
Dn Type= 3
Dn Slope=0.005
Boundary for River Rch & Prof#=Allen T8,Reach-1         , 2
Up Type= 0
Dn Type= 3
Dn Slope=0.005
Boundary for River Rch & Prof#=Allen T8,Reach-1         , 3
Up Type= 0
Dn Type= 3
Dn Slope=0.005
Boundary for River Rch & Prof#=Allen T8,Reach-1         , 4
Up Type= 0
Dn Type= 3
Dn Slope=0.005
Boundary for River Rch & Prof#=Allen T8,Reach-1         , 5
Up Type= 0
Dn Type= 3
Dn Slope=0.005
Boundary for River Rch & Prof#=Allen T8,Reach-1         , 6
Up Type= 0
Dn Type= 3
Dn Slope=0.005
Boundary for River Rch & Prof#=Allen T8,Reach-1         , 7
Up Type= 0
Dn Type= 3
Dn Slope=0.005
DSS Import GetInterval= 0
DSS Import GetPeak= 0
DSS Import FillOption= 0

--- Allen T8.g01 (geometry) ---

Geom Title=Existing Conditions
Program Version=4.10

River Reach=Allen T8        ,Reach-1
Reach XY= 30
        2746276.        6940011.      2745973.55      6939955.54
      2745531.47      6939605.74      2745278.15      6939155.03
      2745170.62      6938466.19      2744673.53      6938355.56
      2744552.96      6938137.54      2744278.85      6937952.82
       2744324.8       6937621.5      2744070.75      6936616.44
      2743566.27      6936400.24      2743336.36      6936072.02
      2743181.89      6936109.03      2743029.16      6936002.66
       2743024.9      6935622.74        2742885.      6935568.06
      2742924.91      6935421.55      2742772.49      6935012.25
      2742531.41      6934955.83      2742426.72      6934700.29
      2742523.53      6934566.45      2742723.09      6934553.09
      2742706.13      6934289.97      2741970.14      6933713.06
      2741532.05      6933712.67      2741226.01      6933904.41
      2740679.41      6933618.82      2740310.84      6933511.38
      2740031.89      6933559.04        2739826.        6933411.

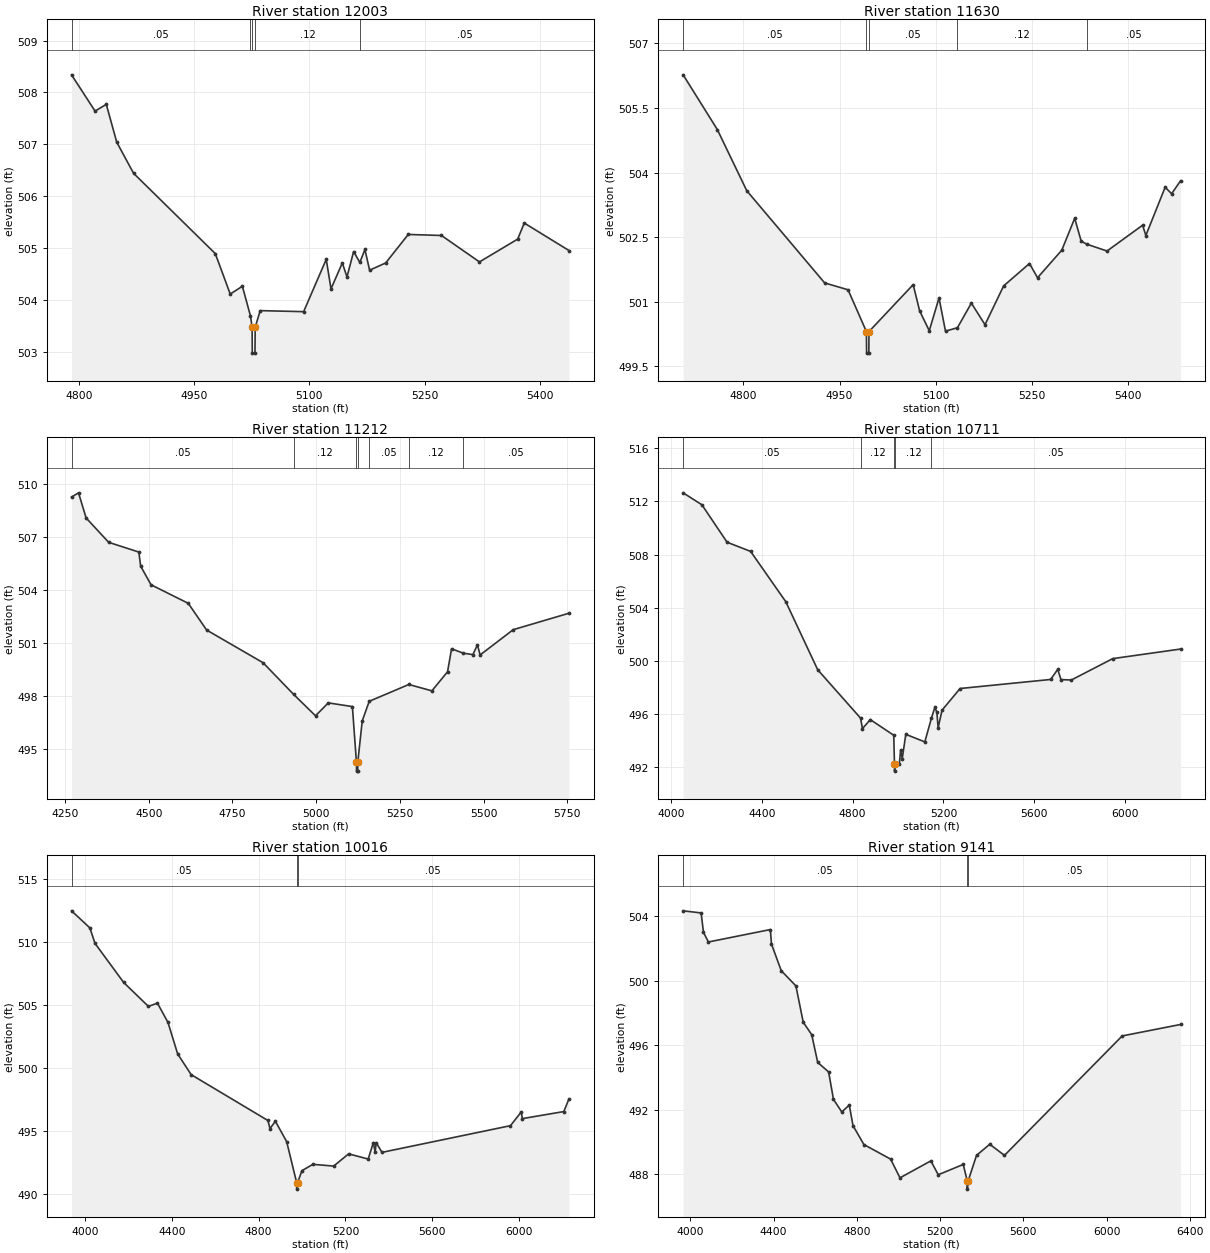
Type RM Length L Ch R = 1 ,12003   ,373,373,373
BEGIN DESCRIPTION:
Allen T8 19.0
END DESCRIPTION:
XS GIS Cut Line= 3
      2746273.13       6939835.9      2746104.24      6939961.72
      2745848.56      6940315.37
#Sta/Elev= 30
  4790.6  508.34  4821.2  507.64  4835.8  507.77  4849.4  507.04  4871.3  506.44
  4977.6  504.89    4997  504.11  5012.8  504.26  5023.3  503.69  5025.5  503.47
  5025.7  502.97  5029.2  502.97  5029.5  503.47    5036  503.79  5092.5  503.77
  5121.9  504.78  5128.1  504.21  5142.8  504.71  5148.9  504.44  5157.5  504.93
  5165.6  504.72  5172.2  504.97  5178.3  504.57  5199.2  504.71  5228.6  505.26
  5271.8  505.24  5321.2  504.73  5370.9  505.17  5379.5  505.48  5437.6  504.95
#Mann= 5 ,-1 , 0
  4790.6     .05       0  5023.3     .12       0  5025.5     .04       0
  5029.5     .12       0  5165.6     .05       0
Bank Sta=5025.5,5029.5
XS Rating Curve= 0 ,0
Exp/Cntr=0.3,0.1

Type RM Length L Ch R = 1 ,11630   ,418,418,418
BEGIN DESCRIPTION:
Allen T8 18.0
END DESCRIPTION:
XS GIS Cut Line= 3
       2746050.7      6939630.52      2745801.78      6939786.77
      2745743.91      6940264.78
#Sta/Elev= 30
  4706.1  506.27  4759.4     505  4805.3  503.58  4926.7  501.44  4963.2  501.28
  4991.8  500.31  4992.1  499.81  4995.6  499.81  4995.8  500.31  5064.7   501.4
  5074.8  500.79  5089.8  500.33    5105  501.09  5115.1  500.32  5133.7   500.4
  5155.4  500.97  5176.7  500.47  5205.7  501.37    5246  501.89  5258.6  501.56
  5296.4   502.2  5316.5  502.94  5326.6  502.41  5335.1  502.34  5366.9  502.18
  5422.4  502.78  5427.4  502.54  5457.5  503.66  5467.6  503.51  5481.5  503.81
#Mann= 5 ,-1 , 0
  4706.1     .05       0  4991.8     .04       0  4995.8     .05       0
  5133.7     .12       0  5335.1     .05       0
Bank Sta=4991.8,4995.8
XS Rating Curve= 0 ,0
Exp/Cntr=0.3,0.1

Type RM Length L Ch R = 1 ,11212   ,501,501,501
BEGIN DESCRIPTION:
Allen T8 17.0
END DESCRIPTION:
XS GIS Cut Line= 3
      2746159.32      6939216.56      2745502.87      6939537.71
      2745216.32      6940236.54
#Sta/Elev= 30
  4269.2  509.24  4290.1  509.48  4312.7  508.06  4380.2  506.68  4470.2  506.13
  4475.8  505.33  4506.7  504.28    4618  503.23  4672.8  501.72  4841.5  499.87
  4932.7  498.08  4998.1  496.87  5036.3   497.6  5108.3  497.39  5120.4  494.24
  5120.7  493.74  5124.2  493.74  5124.4  494.24  5137.7  496.58  5158.6  497.69
  5276.9  498.64  5345.8  498.28  5392.6  499.36  5404.6  500.66  5439.9  500.41
  5468.3  500.33  5481.9  500.88  5489.9  500.31  5588.7  501.74  5755.3  502.67
#Mann= 7 ,-1 , 0
  4269.2     .05       0  4932.7     .12       0  5120.4     .07       0
  5124.4     .12       0  5158.6     .05       0  5276.9     .12       0
  5439.9     .05       0
Bank Sta=5120.4,5124.4
XS Rating Curve= 0 ,0
Exp/Cntr=0.3,0.1

Type RM Length L Ch R = 1 ,10711   ,695,695,695
BEGIN DESCRIPTION:
Mapping XS 9353c63e
END DESCRIPTION:
XS GIS Cut Line= 3
      2746183.71      6938865.77      2745280.95      6939101.87
      2744746.22      6940240.77
#Sta/Elev= 30
  4053.4  512.65  4136.1  511.75  4247.1  508.93  4350.8  508.24  4505.8  504.45
  4646.3  499.33  4835.1  495.69  4843.3   494.9  4877.9  495.58  4981.3   494.4
  4984.5   492.2  4984.7   491.7  4988.5   492.2    5006  492.26  5011.6   493.3
  5018.7  492.65  5034.4  494.47  5118.1   493.9  5147.2  495.68  5162.3   496.5
  5171.2  496.13  5176.8  494.97  5194.1  496.29  5273.5  497.92  5672.4   498.6
  5703.6  499.36    5718  498.59  5763.6  498.56  5946.1  500.17  6244.7  500.89
#Mann= 5 ,-1 , 0
  4053.4     .05       0  4835.1     .12       0  4984.5     .07       0
  4988.5     .12       0  5147.2     .05       0
Bank Sta=4984.5,4988.5
XS Rating Curve= 0 ,0
Exp/Cntr=0.3,0.1

Type RM Length L Ch R = 1 ,10016   ,875,875,875
BEGIN DESCRIPTION:
Mapping XS 5f015e5e
END DESCRIPTION:
XS GIS Cut Line= 4
      2746197.64      6938733.82      2745241.86      6938472.03
      2745128.68      6938534.25      2744763.05      6939646.87
#Sta/Elev= 30
  3938.1  512.48  4022.7  511.12    4046   509.9  4178.3  506.79  4292.3  504.89
  4333.8  505.15  4382.3  503.62  4427.1  501.11  4489.3  499.47  4842.7  495.83
  4852.2  495.19  4877.2  495.77  4929.1  494.15  4975.3  490.88  4975.5  490.38
  4979.3  490.88  4999.1  491.84  5049.9  492.35  5145.6  492.21  5214.5  493.18
  5304.6  492.77  5328.5  494.08  5336.4  493.34  5341.7  494.07  5368.2   493.3
  5960.1  495.42  6009.6  496.51  6014.9  495.98  6205.7  496.54  6229.4  497.54
#Mann= 3 ,-1 , 0
  3938.1     .05       0  4975.3     .04       0  4979.3     .05       0
Bank Sta=4975.3,4979.3
XS Rating Curve= 0 ,0
Exp/Cntr=0.3,0.1

Type RM Length L Ch R = 1 ,9141    ,595,595,595
BEGIN DESCRIPTION:
Allen T8 14.0
END DESCRIPTION:
XS GIS Cut Line= 3
      2745475.39       6937699.1        2744526.        6938111.
      2743551.81      6939053.24
#Sta/Elev= 30
  3965.3  504.32  4051.8  504.19  4063.1  502.99  4086.6  502.39  4384.5  503.16
  4389.9  502.26  4436.8  500.61  4507.2  499.67  4542.4  497.42  4583.1  496.65
    4612  494.93  4664.4  494.34  4687.8  492.64  4727.7  491.86  4763.7  492.29
  4781.7  491.01  4834.1  489.84  4962.3  488.94  5007.3  487.78  5155.7  488.83
  5191.2  487.97  5311.3  488.61  5330.7  487.58  5330.9  487.08  5334.7  487.58
  5375.1  489.17  5438.7  489.86  5509.4  489.17  6075.1  496.57  6355.5  497.28
#Mann= 3 ,-1 , 0
  3965.3     .05       0  5330.7     .04       0  5334.7     .05       0
Bank Sta=5330.7,5334.7
XS Rating Curve= 0 ,0
Exp/Cntr=0.3,0.1

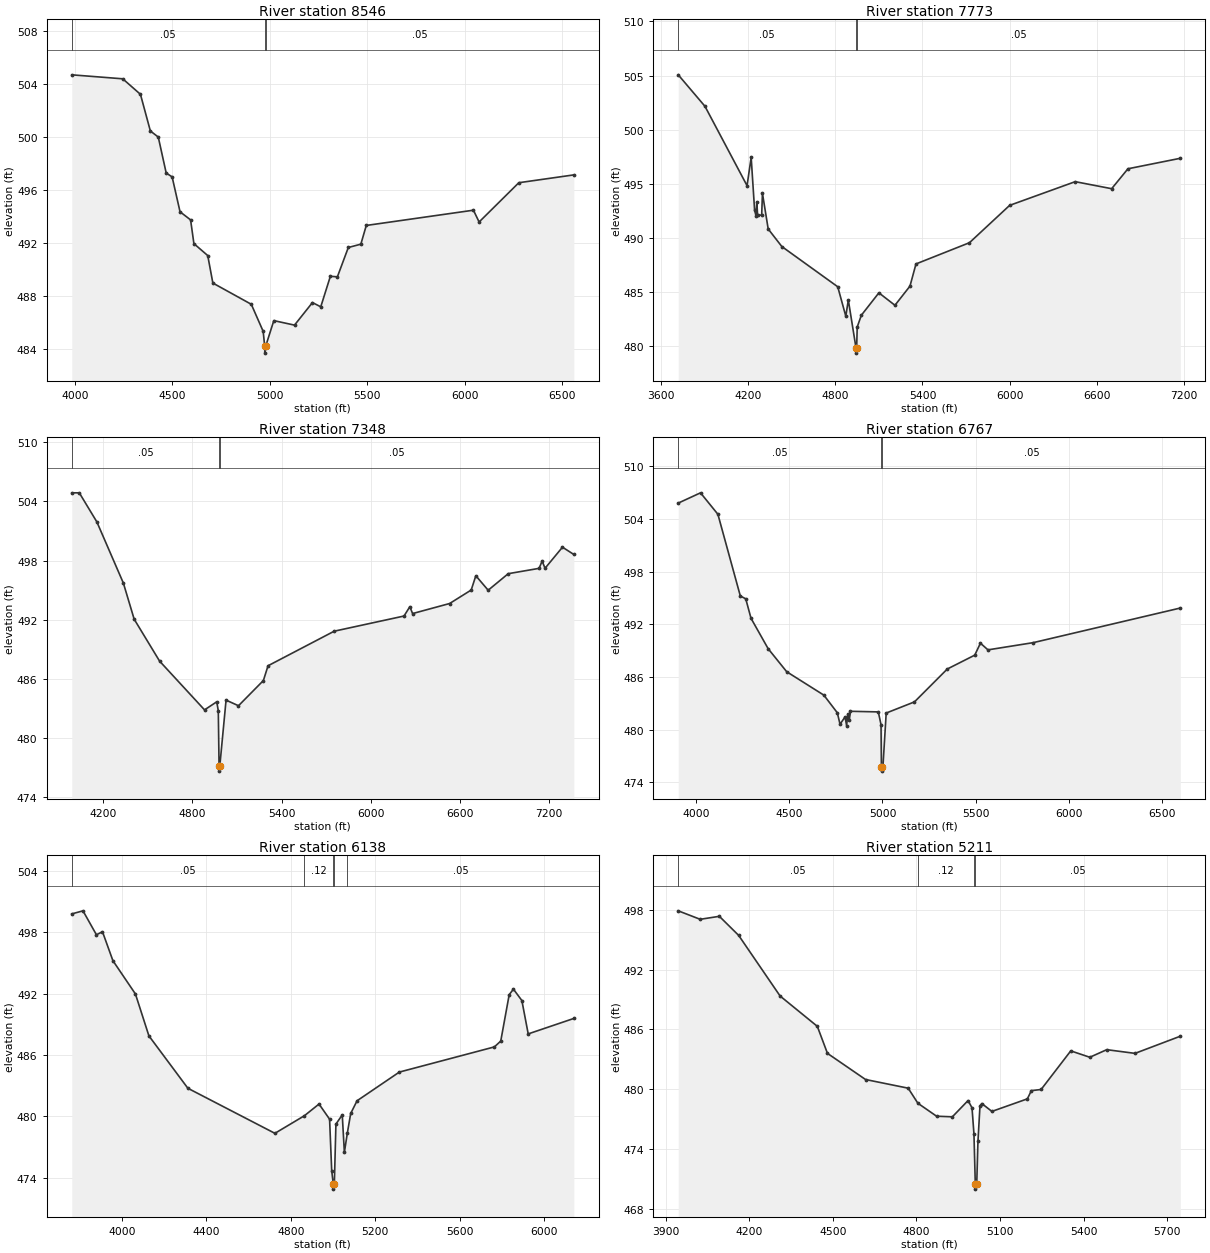
Type RM Length L Ch R = 1 ,8546    ,773,773,773
BEGIN DESCRIPTION:
Mapping XS 475030a0
END DESCRIPTION:
XS GIS Cut Line= 5
      2745323.05      6937502.05      2744333.47      6937673.92
      2743937.63      6938116.63      2743807.42      6938611.42
        2743563.      6939006.65
#Sta/Elev= 30
  3984.8  504.67  4246.2  504.37    4337   503.2  4387.8  500.44  4428.4  499.98
    4469  497.27  4499.4  496.98    4540  494.35  4594.1  493.74  4611.1  491.95
  4682.1  491.05  4708.3  488.98  4905.4  487.38  4966.3  485.34  4974.3   484.2
  4974.7   483.7  4978.7   484.2  5020.9  486.15    5127  485.81    5219  487.51
  5261.6  487.19  5310.9  489.49  5346.9  489.45  5402.9  491.66  5467.2  491.91
    5495  493.32  6044.5  494.47  6073.6  493.58  6277.2  496.54  6559.4  497.13
#Mann= 3 ,-1 , 0
  3984.8     .05       0  4974.3     .05       0  4978.7     .05       0
Bank Sta=4974.3,4978.7
XS Rating Curve= 0 ,0
Exp/Cntr=0.3,0.1

Type RM Length L Ch R = 1 ,7773    ,425,425,425
BEGIN DESCRIPTION:
Mapping XS eda8746a
END DESCRIPTION:
XS GIS Cut Line= 4
      2744531.37      6935726.05      2744187.63       6936913.5
      2743750.13      6938569.75      2743520.98      6939022.84
#Sta/Elev= 30
  3718.4  505.07  3902.6  502.16  4192.2  494.83  4220.6  497.44  4244.1  492.59
  4254.2  492.02  4259.4  493.35  4264.9  492.08    4293  492.12  4298.2  494.12
  4337.8  490.83  4431.5  489.21  4816.7  485.49  4872.2  482.77  4889.5  484.27
  4942.2  479.86  4942.8  479.36    4947  479.86  4950.7  481.77  4979.2  482.86
    5100  484.93  5210.5  483.78    5314  485.55  5355.4   487.6  5723.5  489.56
  6000.2  493.01  6451.7   495.2  6702.7  494.55  6814.7  496.39  7175.4  497.36
#Mann= 3 ,-1 , 0
  3718.4     .05       0  4942.2     .05       0    4947     .05       0
Bank Sta=4942.2,4947
XS Rating Curve= 0 ,0
Exp/Cntr=0.3,0.1

Type RM Length L Ch R = 1 ,7348    ,581,581,581
BEGIN DESCRIPTION:
Mapping XS 44d1cc85
END DESCRIPTION:
XS GIS Cut Line= 4
      2744307.42      6935632.27      2744031.38      6936590.59
      2743661.59      6937772.88      2743349.25      6938876.48
#Sta/Elev= 30
  3986.7  504.88  4037.4  504.88  4155.7  501.93  4334.5  495.71  4407.1  492.05
  4578.5  487.79  4881.3  482.84  4963.6  483.66    4974  482.75  4979.2  477.12
  4979.7  476.62    4984  477.12  5026.3  483.83  5110.1  483.26  5277.8  485.82
  5309.2  487.32  5755.1  490.83  6225.5  492.37  6264.6  493.32  6283.2  492.62
  6532.6  493.64  6678.1  495.01  6709.3  496.46  6792.4  494.99  6927.7  496.67
  7135.4  497.21  7156.1  497.95  7175.7  497.22  7293.1  499.36  7369.7  498.62
#Mann= 3 ,-1 , 0
  3986.7     .05       0  4979.2     .04       0    4984     .05       0
Bank Sta=4979.2,4984
XS Rating Curve= 0 ,0
Exp/Cntr=0.3,0.1

Type RM Length L Ch R = 1 ,6767    ,629,629,629
BEGIN DESCRIPTION:
Mapping XS 5fbb4356
END DESCRIPTION:
XS GIS Cut Line= 3
      2744193.71      6935490.75      2743525.44      6936361.21
      2743274.59      6937941.73
#Sta/Elev= 30
  3902.6  505.79  4022.3  506.96  4115.7  504.52  4236.2  495.22  4265.3   494.9
  4293.7  492.68  4385.8  489.22  4485.5   486.6  4684.9  483.94  4757.4  481.93
  4771.9  480.63  4799.1  481.46  4807.3  480.47  4813.6  481.78  4821.8  481.13
  4828.1   482.1  4977.6  482.03  4992.2  480.58  4994.3  475.79  4994.9  475.29
  4999.2  475.79  5002.4  475.79    5020   481.9  5171.9  483.17  5348.2  486.91
  5495.9  488.49  5526.3  489.85  5566.8  489.09  5809.8  489.91  6600.3  493.85
#Mann= 3 ,-1 , 0
  3902.6     .05       0  4994.3     .04       0  4999.2     .05       0
Bank Sta=4994.3,4999.2
XS Rating Curve= 0 ,0
Exp/Cntr=0.3,0.1

Type RM Length L Ch R = 1 ,6138    ,927,927,927
BEGIN DESCRIPTION:
Mapping XS f01c9ef0
END DESCRIPTION:
XS GIS Cut Line= 3
      2743845.35       6935095.6      2743146.54      6935924.62
      2743107.51      6937216.98
#Sta/Elev= 30
  3762.9  499.78    3816  500.08  3879.7  497.74  3908.3  498.04  3957.7  495.21
  4064.3  491.96  4128.1  487.87  4312.7  482.75  4724.7  478.35  4864.5  480.07
  4933.6  481.21  4983.6  479.73  4993.6   474.7  5001.1   473.4  5001.7   472.9
  5006.1   473.4  5013.6  479.25  5043.6  480.15  5053.6  476.49  5067.8  478.39
  5083.6  480.29  5113.7  481.53  5313.7  484.33  5763.9  486.79    5794  487.36
    5834  491.89    5854  492.43    5894  491.32    5924  488.06  6140.1  489.57
#Mann= 5 ,-1 , 0
  3762.9     .05       0  4864.5     .12       0  5001.1     .07       0
  5006.1     .12       0  5067.8     .05       0
Bank Sta=5001.1,5006.1
XS Rating Curve= 0 ,0
Exp/Cntr=0.3,0.1

Type RM Length L Ch R = 1 ,5211    ,468,468,468
BEGIN DESCRIPTION:
Mapping XS 6d4f3798
END DESCRIPTION:
XS GIS Cut Line= 4
      2743880.06      6934995.79      2743016.34       6935308.3
      2742634.39      6935633.82      2742569.29      6936011.38
#Sta/Elev= 30
  3944.2  497.89    4023  497.04  4091.9  497.34  4161.2  495.43  4310.1  489.35
  4443.8  486.31  4480.2   483.6    4617  480.98  4770.2  480.11    4805   478.6
  4872.2   477.3  4928.9  477.24  4985.3  478.87  4999.5  478.14  5006.4  475.55
  5011.3  470.49  5011.9  469.99  5016.4  470.49  5020.8  474.77  5028.1  478.34
  5034.7  478.57  5070.9  477.78  5198.3  479.04  5212.6  479.86  5247.7  479.98
  5354.2  483.85  5422.6  483.21  5483.5  483.97    5585   483.6  5747.7  485.32
#Mann= 4 ,-1 , 0
  3944.2     .05       0    4805     .12       0  5006.4     .05       0
  5011.3     .05       0
Bank Sta=5011.3,5016.4
XS Rating Curve= 0 ,0
Exp/Cntr=0.3,0.1

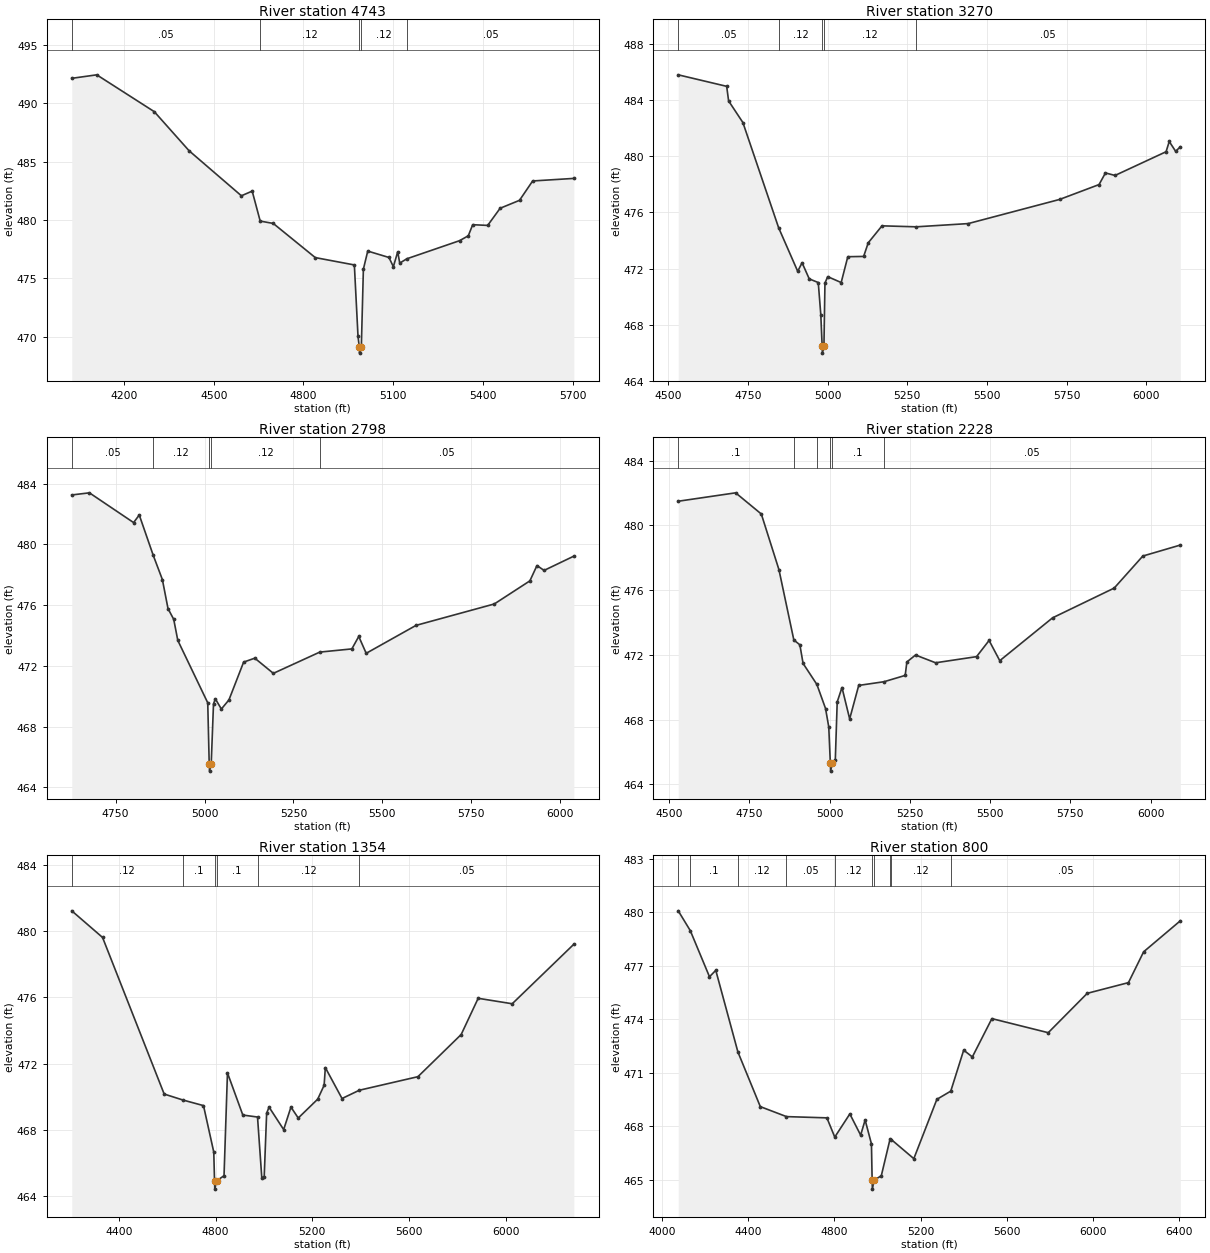
Type RM Length L Ch R = 1 ,4743    ,1473,1473,1473
BEGIN DESCRIPTION:
Mapping XS 04ede3e9
END DESCRIPTION:
XS GIS Cut Line= 3
       2743716.4      6934877.62      2742752.85      6934977.45
      2742331.83      6935550.38
#Sta/Elev= 30
  4024.8  492.15  4108.4  492.45  4300.9  489.29  4417.3  485.94  4592.3  482.08
  4628.4  482.48  4655.2  479.91  4698.8  479.71  4839.5  476.78  4970.2  476.15
  4982.4  470.04  4986.8  469.09  4987.5  468.59    4992  469.09  4993.5  469.09
  5000.4  475.79    5015  477.34    5086  476.79  5100.7     476  5115.3  477.28
    5122  476.31  5145.9  476.68  5322.1  478.23  5351.4  478.65  5366.1   479.6
  5416.2  479.54  5457.9  481.01  5522.7  481.69  5566.7  483.35  5704.5  483.57
#Mann= 5 ,-1 , 0
  4024.8     .05       0  4655.2     .12       0  4986.8     .05       0
    4992     .12       0  5145.9     .05       0
Bank Sta=4986.8,4992
XS Rating Curve= 0 ,0
Exp/Cntr=0.3,0.1

Type RM Length L Ch R = 1 ,3270    ,472,472,472
BEGIN DESCRIPTION:
Mapping XS 48d88259
END DESCRIPTION:
XS GIS Cut Line= 4
      2742865.99      6933849.99      2742475.36      6934115.62
       2742183.7       6934480.2      2742152.44      6935115.66
#Sta/Elev= 30
  4531.6   485.8  4683.6  484.98  4689.7  483.94  4734.5   482.4  4846.7   474.9
  4906.5   471.8  4920.2  472.41  4942.7  471.26    4971     471    4979   468.7
  4983.2  466.47    4984  465.97  4988.8  466.47    4992  470.96  5000.6  471.42
  5042.9     471  5063.7  472.84  5113.4  472.86  5127.8  473.83    5171  475.04
  5278.6  474.97  5441.5   475.2  5728.2  476.92  5852.1  477.98  5872.2  478.81
  5902.2  478.63  6062.4  480.32  6072.4  481.05  6092.4  480.35  6107.1  480.67
#Mann= 5 ,-1 , 0
  4531.6     .05       0  4846.7     .12       0  4983.2     .03       0
  4988.8     .12       0  5278.6     .05       0
Bank Sta=4983.2,4988.8
XS Rating Curve= 0 ,0
Exp/Cntr=0.3,0.1

Type RM Length L Ch R = 1 ,2798    ,570,570,570
BEGIN DESCRIPTION:
Mapping XS fb8bf5b1
END DESCRIPTION:
XS GIS Cut Line= 4
      2742324.31      6933501.06      2742136.82      6933834.37
      2742006.61      6934266.66      2742001.41      6934844.74
#Sta/Elev= 30
  4626.7  483.26  4676.3   483.4  4800.6  481.44  4816.5  481.94  4855.7  479.29
  4881.5  477.69  4897.4  475.77  4913.4  475.07  4924.9  473.68  5009.1  469.57
  5013.2  465.57  5014.1  465.07  5018.9  465.57  5025.3   469.5  5030.5  469.83
  5047.4  469.16  5068.7  469.76    5110  472.25  5141.4  472.51  5193.6  471.51
  5324.2  472.91  5414.4  473.12  5433.8  473.94  5454.7  472.83  5594.9  474.67
    5815  476.08    5915   477.6    5935  478.61    5955  478.29  6038.7  479.23
#Mann= 5 ,-1 , 0
  4626.7     .05       0  4855.7     .12       0  5013.2     .03       0
  5018.9     .12       0  5324.2     .05       0
Bank Sta=5013.2,5018.9
XS Rating Curve= 0 ,0
Exp/Cntr=0.3,0.1

Type RM Length L Ch R = 1 ,2228    ,874,874,874
BEGIN DESCRIPTION:
Mapping XS 263f24a3
END DESCRIPTION:
XS GIS Cut Line= 3
      2741610.78      6933282.33       2741626.4      6933761.45
       2741928.5      6934803.16
#Sta/Elev= 30
  4528.7   481.5  4707.5  482.02  4787.5  480.71  4842.4  477.27  4888.8  472.92
  4907.6  472.62  4917.6  471.47  4960.6  470.17  4987.6  468.68  4997.6  467.54
  5002.5  465.31  5003.4  464.81  5008.2  465.31    5018  465.51  5023.9  469.09
  5038.8  469.98  5062.7  468.04  5090.9  470.11    5170  470.34  5235.7  470.73
  5240.9  471.56  5267.9  471.99  5330.4  471.51    5458  471.89    5497  472.89
  5530.3  471.64  5694.8  474.29  5886.8  476.13  5975.9  478.11  6092.7  478.79
#Mann= 6 ,-1 , 0
  4528.7      .1       0  4888.8     .12       0  4960.6      .1       0
  5002.5     .03       0  5008.2      .1       0    5170     .05       0
Bank Sta=5002.5,5008.2
XS Rating Curve= 0 ,0
Exp/Cntr=0.3,0.1

Type RM Length L Ch R = 1 ,1354    ,554,554,554
BEGIN DESCRIPTION:
Mapping XS b6d91ffb
END DESCRIPTION:
XS GIS Cut Line= 3
      2741475.38      6933230.19       2740938.9       6933792.7
      2740803.48       6935084.4
#Sta/Elev= 30
  4205.4  481.24  4332.7  479.63  4587.5  470.16  4664.7   469.8  4750.1  469.46
  4792.6  466.65  4795.7  464.91  4796.9  464.41    4804  464.91    4835  465.22
  4849.2  471.44  4912.7  468.89  4973.5  468.77  4991.1  465.11  5001.1  465.15
  5011.2     469  5021.2  469.37  5081.6  468.01  5111.7  469.37  5141.9  468.71
  5222.3  469.85  5248.9  470.69  5253.9  471.76  5322.9  469.89  5394.4  470.39
  5636.8  471.21  5815.6  473.76  5885.9  475.95  6026.7  475.62  6281.5  479.22
#Mann= 6 ,-1 , 0
  4205.4     .12       0  4664.7      .1       0  4795.7     .03       0
    4804      .1       0  4973.5     .12       0  5394.4     .05       0
Bank Sta=4795.7,4804
XS Rating Curve= 0 ,0
Exp/Cntr=0.3,0.1

Type RM Length L Ch R = 1 ,800     ,0,0,0
BEGIN DESCRIPTION:
Allen T8 1.0
END DESCRIPTION:
XS GIS Cut Line= 3
      2741240.97       6933032.3      2740499.31      6933583.58
      2740355.57       6934980.2
#Sta/Elev= 30
  4075.9  480.08  4131.7  478.97  4220.8  476.38    4250  476.74  4352.5  472.16
  4456.5  469.09  4577.9  468.53  4765.3  468.46  4801.7  467.38  4871.6  468.68
  4921.7  467.49  4942.5  468.34  4971.8     467    4975  464.96  4976.2  464.46
  4983.5  464.96  5017.5  465.21  5057.9  467.26  5064.2  467.24  5168.3  466.17
  5275.2   469.5  5339.6  469.96  5399.5  472.26  5439.7  471.88  5530.2  474.03
  5791.6  473.24  5972.5  475.45  6163.5  476.05  6233.9  477.78    6404  479.52
#Mann= 10 ,-1 , 0
  4075.9     .12       0  4131.7      .1       0  4352.5     .12       0
  4577.9     .05       0  4801.7     .12       0    4975     .03       0
  4983.5     .12       0  5057.9     .05       0  5064.2     .12       0
  5339.6     .05       0
Bank Sta=4975,4983.5
XS Rating Curve= 0 ,0
Exp/Cntr=0.3,0.1

Chan Stop Cuts=-1
Use User Specified Reach Order=0
Composite Channel Slope=5