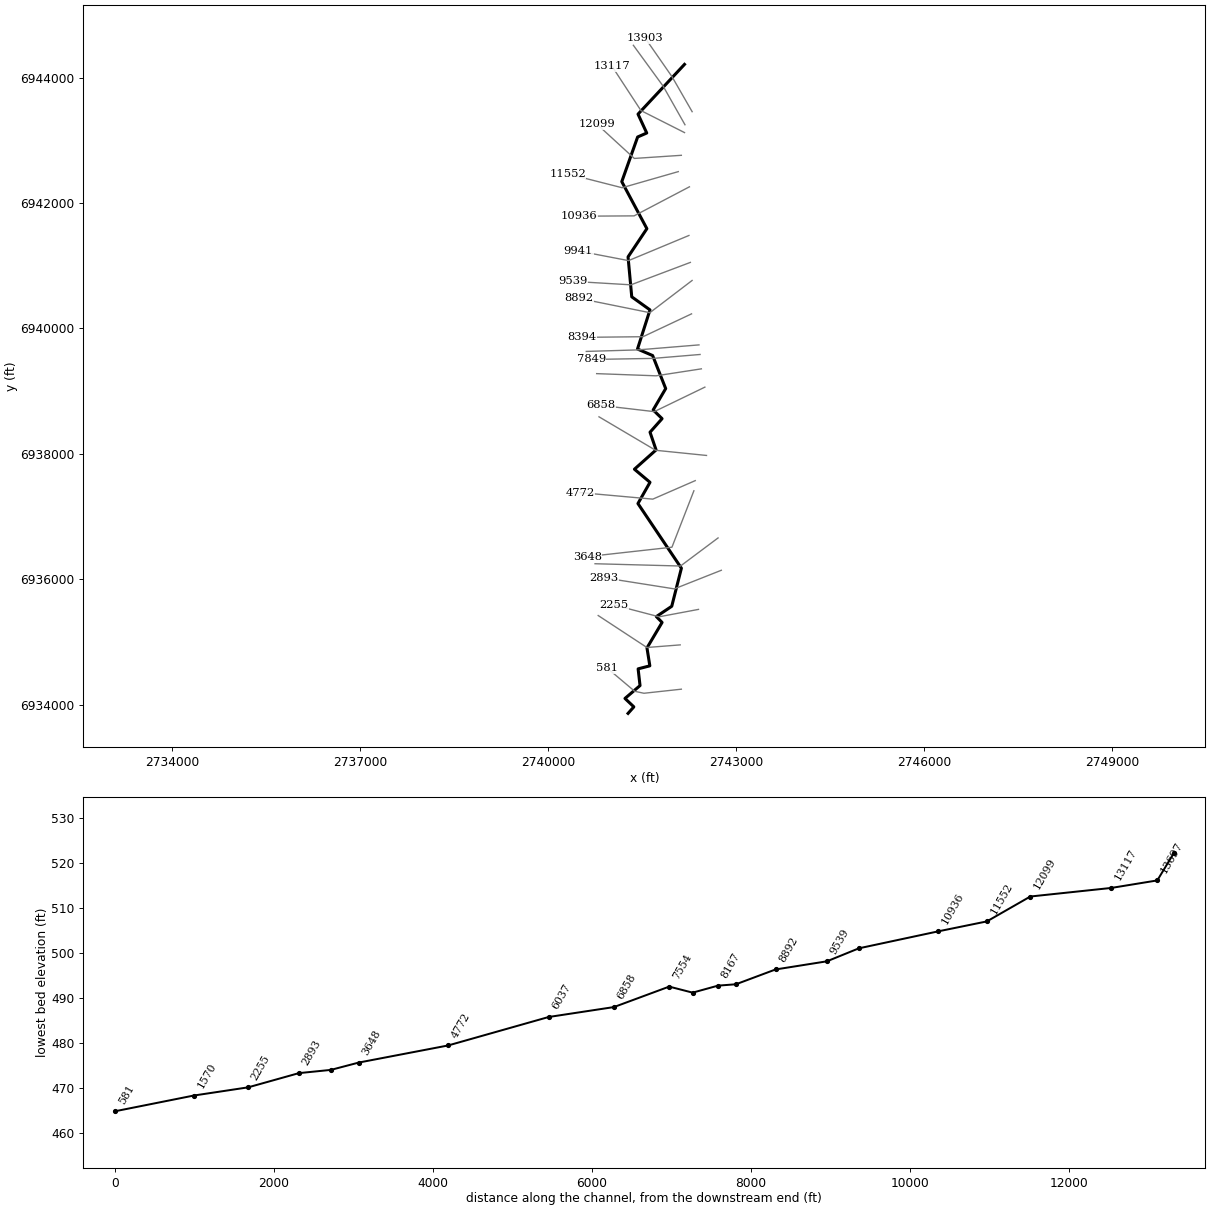
--- Allen T8_1.prj (project) ---

Proj Title=Allen T8_1 Base Level Engineering
Current Plan=p01
Default Exp/Contr=0.3,0.1
English Units
Geom File=g01
Flow File=f01
Plan File=p01
BEGIN DESCRIPTION:
Allen T8_1
END DESCRIPTION:

--- Allen T8_1.p01 (plan) ---

Plan Title=Multiple Run
Short Identifier=Multiple
Geom File=g01
Flow File=f01
Subcritical Flow
K Sum by GR= 0
Std Step Tol= 0.01
Critical Tol= 0.01
Num of Std Step Trials= 20
Max Error Tol= 0.3
Flow Tol Ratio= 0.001
Split Flow NTrial= 30
Split Flow Tol= 0.02
Split Flow Ratio= 0.02
Log Output Level= 0
Friction Slope Method= 1
Unsteady Friction Slope Method= 2
Unsteady Bridges Friction Slope Method= 1
Parabolic Critical Depth
Global Vel Dist=  1 , 1 , 1
Global Log Level= 0
CheckData=True
Encroach Param= -1, 0, 0, 0
BEGIN DESCRIPTION:
Multiple Run
END DESCRIPTION:

--- Allen T8_1.f01 (steady flow) ---

Flow Title=Multiple
Number of Profiles=7
Profile Names=10-year,25-year,50-year,1pct_min,100-year,1pct_plu,500-year
River Rch & RM= Allen T8_1,Reach-1,13903
     237     299     346     200     399     796     529
River Rch & RM= Allen T8_1,Reach-1,11552
     377     489     577     339     676    1348     928
River Rch & RM= Allen T8_1,Reach-1,6858
     476     625     743     439     876    1749    1220
Boundary for River Rch & Prof#=Allen T8_1,Reach-1,1
Up Type=0
Dn Type=3
Dn Slope=0.005
Boundary for River Rch & Prof#=Allen T8_1,Reach-1,2
Up Type=0
Dn Type=3
Dn Slope=0.005
Boundary for River Rch & Prof#=Allen T8_1,Reach-1,3
Up Type=0
Dn Type=3
Dn Slope=0.005
Boundary for River Rch & Prof#=Allen T8_1,Reach-1,4
Up Type=0
Dn Type=3
Dn Slope=0.005
Boundary for River Rch & Prof#=Allen T8_1,Reach-1,5
Up Type=0
Dn Type=3
Dn Slope=0.005
Boundary for River Rch & Prof#=Allen T8_1,Reach-1,6
Up Type=0
Dn Type=3
Dn Slope=0.005
Boundary for River Rch & Prof#=Allen T8_1,Reach-1,7
Up Type=0
Dn Type=3
Dn Slope=0.005

--- Allen T8_1.g01 (geometry) ---

Geom Title=Existing Conditions

River Reach=Allen T8_1,Reach-1
Reach XY= 30
      2742176.00      6944211.00      2741434.89      6943417.51
      2741574.03      6943116.65      2741428.85      6943052.99
      2741176.05      6942340.96      2741576.22      6941590.94
      2741276.05      6941140.96      2741335.01      6940503.94
      2741625.82      6940295.65      2741426.53      6939671.45
      2741668.28      6939567.50      2741876.30      6939040.83
      2741676.39      6938699.98      2741818.72      6938561.10
      2741626.52      6938345.11      2741722.88      6938062.62
      2741377.77      6937754.83      2741626.05      6937545.93
      2741433.65      6937207.31      2742126.78      6936176.08
      2741972.97      6935569.01      2741727.43      6935404.57
      2741818.74      6935311.30      2741577.79      6934904.91
      2741623.49      6934619.11      2741436.61      6934571.06
      2741467.02      6934304.34      2741226.99      6934099.21
      2741368.60      6933964.59      2741276.00      6933861.00

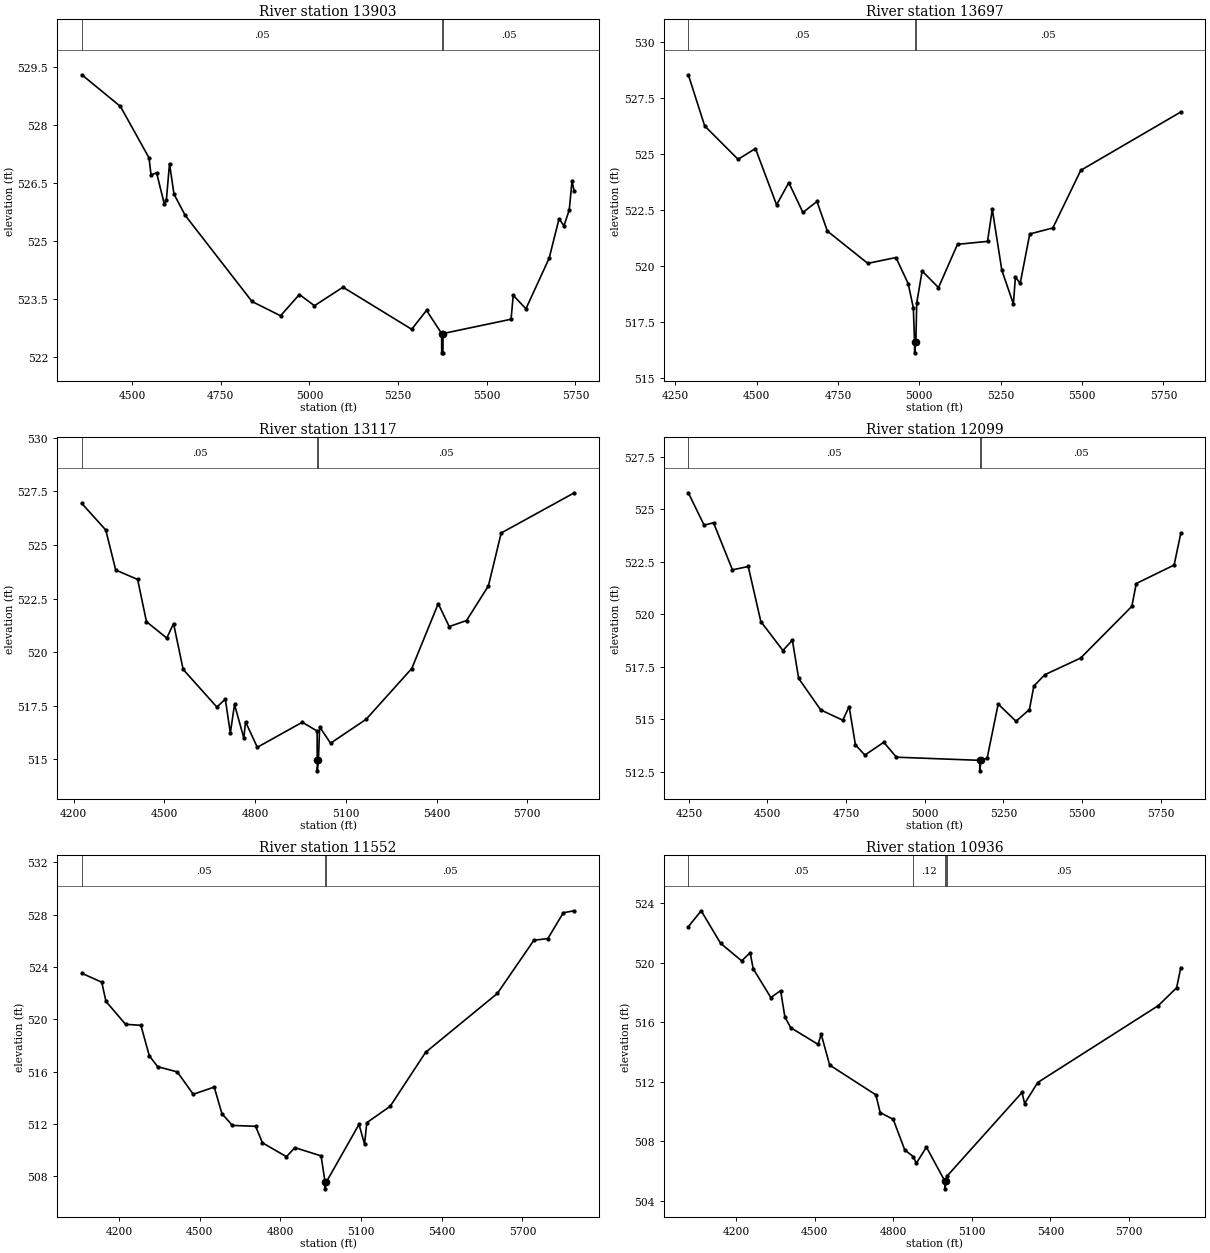
Type RM Length L Ch R = 1,13903,206,206,206
BEGIN DESCRIPTION:
Allen T8_1 23.0
END DESCRIPTION:
XS GIS Cut Line= 3
      2742298.18      6943456.67      2741978.73      6944012.24
      2741551.91      6944626.43
#Sta/Elev= 30
  4358.1  529.31  4466.9  528.49  4547.5  527.16  4553.2  526.72  4569.0  526.77
  4590.6  525.96  4596.4  526.06  4605.3  527.01  4617.9  526.22  4649.5  525.67
  4837.9  523.44  4918.4  523.07  4971.5  523.62  5014.1  523.33  5094.5  523.81
  5288.3  522.72  5330.1  523.21  5372.7  522.61  5372.9  522.11  5376.4  522.11
  5376.7  522.61  5568.5  522.98  5574.6  523.60  5610.4  523.25  5675.9  524.56
  5703.8  525.58  5717.7  525.40  5732.6  525.81  5740.3  526.55  5746.9  526.29
#Mann=3,-1,0
  4358.1    0.05       0  5372.7    0.04       0  5376.7    0.05       0
Bank Sta=5372.7,5376.7
Exp/Cntr=0.3,0.1

Type RM Length L Ch R = 1,13697,580,580,580
BEGIN DESCRIPTION:
Mapping XS 92d17390
END DESCRIPTION:
XS GIS Cut Line= 3
      2742183.58      6943248.36      2741836.36      6943862.93
      2741360.84      6944515.48
#Sta/Elev= 30
  4290.1  528.52  4340.4  526.24  4442.9  524.75  4496.4  525.23  4561.3  522.72
  4598.9  523.71  4642.2  522.38  4685.5  522.87  4717.3  521.55  4841.5  520.11
  4928.1  520.37  4965.6  519.21  4981.5  518.13  4985.3  516.62  4985.5  516.12
  4989.3  516.62  4992.0  518.35  5008.6  519.77  5058.8  519.03  5117.3  520.96
  5209.5  521.09  5224.2  522.52  5253.4  519.81  5289.0  518.30  5295.2  519.50
  5309.9  519.22  5339.3  521.42  5410.3  521.69  5496.1  524.26  5803.4  526.86
#Mann=3,-1,0
  4290.1    0.05       0  4985.3    0.05       0  4989.3    0.05       0
Bank Sta=4985.3,4989.3
Exp/Cntr=0.3,0.1

Type RM Length L Ch R = 1,13117,1018,1018,1018
BEGIN DESCRIPTION:
Mapping XS 52c1dc11
END DESCRIPTION:
XS GIS Cut Line= 3
      2742176.64      6943123.35      2741482.20      6943474.04
      2741016.90      6944185.89
#Sta/Elev= 30
  4226.9  526.94  4306.0  525.70  4338.9  523.83  4411.4  523.39  4440.5  521.42
  4507.7  520.65  4530.1  521.33  4561.8  519.19  4673.3  517.43  4701.2  517.80
  4717.9  516.22  4731.7  517.55  4762.5  515.98  4768.1  516.74  4807.1  515.55
  4955.8  516.72  5004.9  516.31  5005.1  514.95  5005.4  514.45  5009.1  514.95
  5013.2  516.50  5049.3  515.74  5167.0  516.86  5317.8  519.23  5405.3  522.26
  5441.5  521.19  5498.8  521.47  5571.2  523.09  5613.4  525.56  5855.3  527.44
#Mann=3,-1,0
  4226.9    0.05       0  5005.1    0.04       0  5009.1    0.05       0
Bank Sta=5005.1,5009.1
Exp/Cntr=0.3,0.1

Type RM Length L Ch R = 1,12099,547,547,547
BEGIN DESCRIPTION:
Allen T8_1 19.0
END DESCRIPTION:
XS GIS Cut Line= 3
      2742126.03      6942761.00      2741376.00      6942711.00
      2740776.03      6943260.97
#Sta/Elev= 30
  4248.4  525.79  4298.5  524.25  4328.6  524.36  4388.7  522.12  4438.9  522.28
  4478.9  519.66  4549.1  518.28  4579.2  518.77  4599.2  516.95  4669.4  515.45
  4739.5  514.96  4759.6  515.61  4779.6  513.79  4809.7  513.30  4869.8  513.91
  4909.9  513.20  5174.8  513.05  5175.0  512.55  5178.8  513.05  5198.3  513.15
  5233.5  515.73  5290.2  514.91  5332.8  515.47  5346.9  516.59  5382.1  517.13
  5495.6  517.92  5658.3  520.38  5672.5  521.47  5792.8  522.35  5814.0  523.86
#Mann=3,-1,0
  4248.4    0.05       0  5174.8    0.05       0  5178.8    0.05       0
Bank Sta=5174.8,5178.8
Exp/Cntr=0.3,0.1

Type RM Length L Ch R = 1,11552,616,616,616
BEGIN DESCRIPTION:
Mapping XS dcf1b8cd
END DESCRIPTION:
XS GIS Cut Line= 3
      2742076.99      6942500.78      2741181.16      6942243.84
      2740310.47      6942465.84
#Sta/Elev= 30
  4062.2  523.51  4136.1  522.83  4151.9  521.36  4224.6  519.61  4281.7  519.53
  4312.9  517.20  4344.1  516.37  4416.9  515.97  4476.3  514.26  4554.2  514.81
  4582.8  512.78  4621.7  511.88  4708.2  511.81  4733.3  510.55  4822.7  509.49
  4853.9  510.18  4951.4  509.55  4966.3  507.53  4966.6  507.03  4970.3  507.53
  5092.4  511.96  5113.0  510.44  5121.3  512.09  5208.2  513.34  5340.0  517.47
  5606.6  521.97  5742.5  526.04  5794.1  526.16  5851.9  528.14  5892.7  528.29
#Mann=3,-1,0
  4062.2    0.05       0  4966.3    0.05       0  4970.3    0.05       0
Bank Sta=4966.3,4970.3
Exp/Cntr=0.3,0.1

Type RM Length L Ch R = 1,10936,995,995,995
BEGIN DESCRIPTION:
Mapping XS 3263c466
END DESCRIPTION:
XS GIS Cut Line= 3
      2742254.90      6942258.57      2741372.13      6941795.05
      2740490.11      6941789.85
#Sta/Elev= 30
  4018.3  522.41  4067.4  523.48  4141.3  521.30  4221.7  520.12  4254.3  520.66
  4265.8  519.59  4333.3  517.65  4370.4  518.12  4386.8  516.35  4408.9  515.63
  4513.5  514.51  4525.3  515.19  4557.6  513.12  4734.0  511.12  4750.4  509.93
  4800.1  509.48  4844.2  507.42  4876.2  506.98  4888.3  506.53  4926.8  507.61
  4997.7  505.31  4998.0  504.81  5001.7  505.31  5006.2  505.68  5291.5  511.28
  5301.5  510.54  5351.5  511.95  5811.5  517.11  5881.5  518.31  5897.4  519.66
#Mann=5,-1,0
  4018.3    0.05       0  4876.2    0.12       0  4997.7    0.07       0
  5001.7    0.12       0  5006.2    0.05       0
Bank Sta=4997.7,5001.7
Exp/Cntr=0.3,0.1

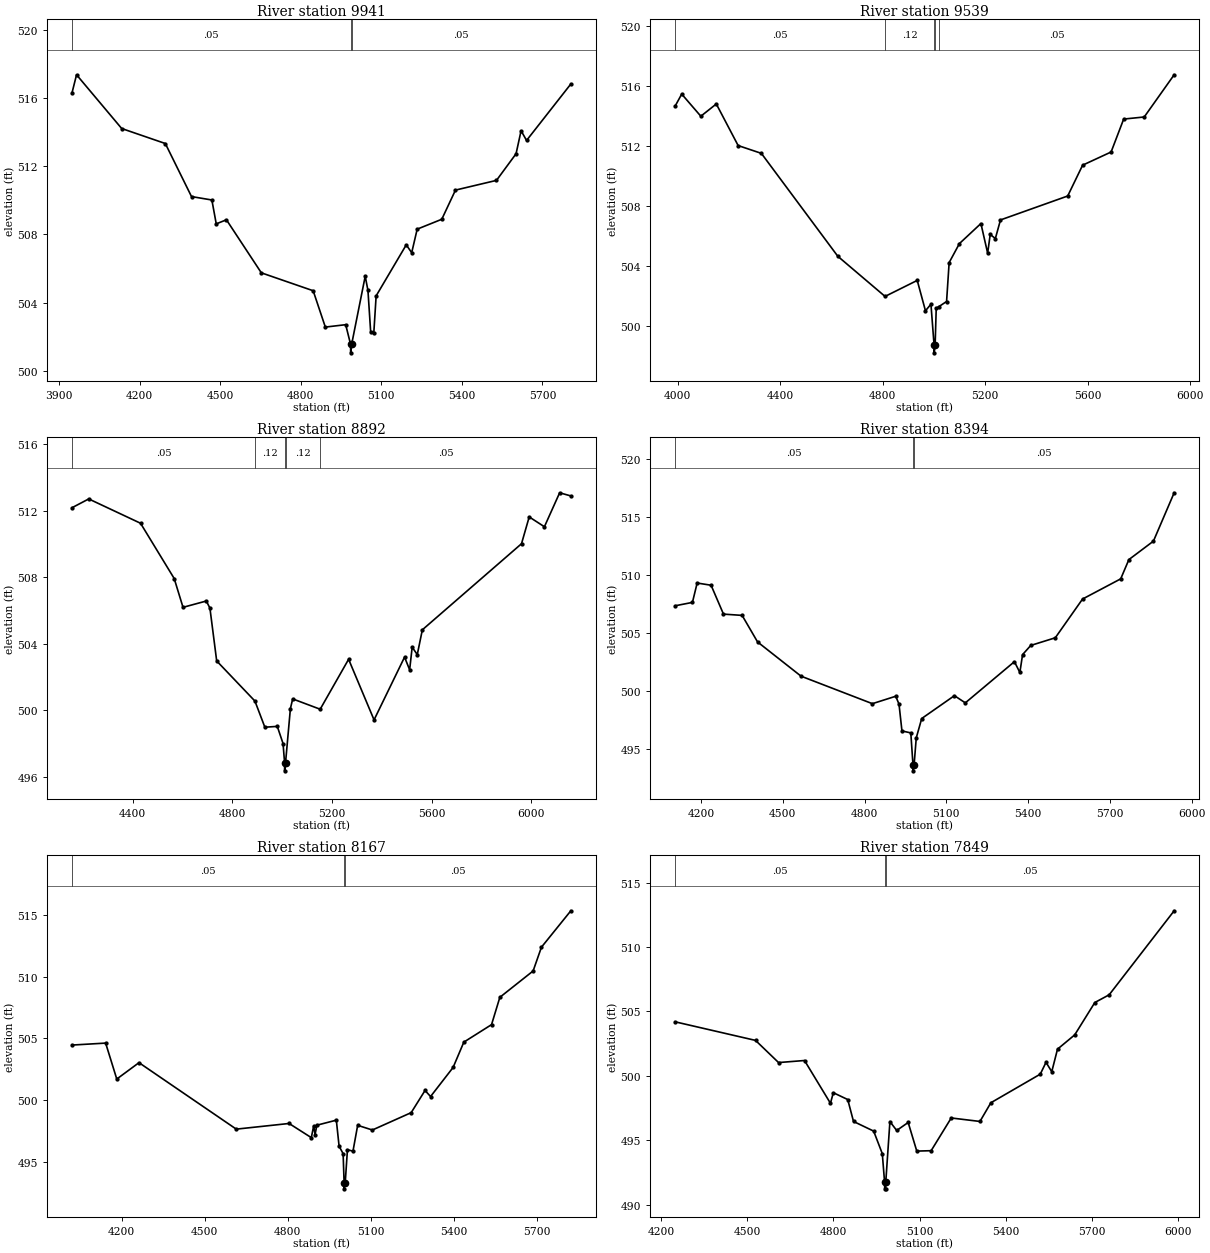
Type RM Length L Ch R = 1,9941,402,402,402
BEGIN DESCRIPTION:
Mapping XS dab29361
END DESCRIPTION:
XS GIS Cut Line= 3
      2742247.12      6941482.55      2741283.59      6941081.51
      2740484.07      6941235.16
#Sta/Elev= 30
  3948.2  516.28  3965.4  517.36  4133.5  514.21  4296.0  513.33  4393.5  510.22
  4469.3  510.02  4485.6  508.62  4523.5  508.86  4653.5  505.75  4846.5  504.70
  4891.8  502.57  4967.6  502.71  4985.8  501.56  4986.1  501.06  4989.8  501.56
  5040.3  505.55  5050.5  504.72  5060.7  502.26  5072.3  502.23  5081.0  504.40
  5193.1  507.39  5213.4  506.93  5233.8  508.31  5325.4  508.89  5376.4  510.60
  5529.1  511.17  5602.0  512.73  5620.7  514.08  5641.1  513.51  5806.0  516.82
#Mann=3,-1,0
  3948.2    0.05       0  4985.8    0.05       0  4989.8    0.05       0
Bank Sta=4985.8,4989.8
Exp/Cntr=0.3,0.1

Type RM Length L Ch R = 1,9539,647,647,647
BEGIN DESCRIPTION:
Mapping XS 7942792e
END DESCRIPTION:
XS GIS Cut Line= 3
      2742269.71      6941053.04      2741321.78      6940695.40
      2740389.38      6940750.86
#Sta/Elev= 30
  3990.9  514.68  4016.2  515.47  4090.8  513.99  4151.2  514.81  4236.4  512.03
  4327.0  511.51  4625.5  504.63  4809.8  501.95  4935.4  503.02  4967.5  500.99
  4988.9  501.43  5001.2  498.68  5001.5  498.18  5005.2  498.68  5009.5  501.16
  5020.0  501.27  5049.9  501.61  5059.9  504.21  5100.0  505.48  5183.9  506.82
  5210.2  504.84  5220.2  506.09  5240.3  505.82  5260.3  507.06  5522.6  508.66
  5580.9  510.72  5692.0  511.60  5741.1  513.80  5821.3  513.94  5938.1  516.76
#Mann=5,-1,0
  3990.9    0.05       0  4809.8    0.12       0  5001.2    0.07       0
  5005.2    0.12       0  5020.0    0.05       0
Bank Sta=5001.2,5005.2
Exp/Cntr=0.3,0.1

Type RM Length L Ch R = 1,8892,498,498,498
BEGIN DESCRIPTION:
Mapping XS 0dda9208
END DESCRIPTION:
XS GIS Cut Line= 3
      2742297.47      6940764.84      2741623.86      6940250.95
      2740491.97      6940480.11
#Sta/Elev= 30
  4156.7  512.17  4224.2  512.70  4432.0  511.24  4567.1  507.92  4602.5  506.19
  4696.0  506.57  4710.5  506.14  4737.6  502.97  4891.1  500.56  4930.9  498.99
  4980.8  499.04  5003.9  498.01  5010.0  496.87  5010.2  496.37  5014.0  496.87
  5033.4  500.11  5042.6  500.69  5152.9  500.07  5267.0  503.07  5369.1  499.43
  5491.5  503.20  5511.9  502.44  5522.1  503.80  5542.5  503.35  5562.9  504.84
  5960.8  510.01  5991.7  511.62  6052.7  511.03  6113.9  513.07  6158.8  512.88
#Mann=5,-1,0
  4156.7    0.05       0  4891.1    0.12       0  5010.0    0.07       0
  5014.0    0.12       0  5152.9    0.05       0
Bank Sta=5010,5014
Exp/Cntr=0.3,0.1

Type RM Length L Ch R = 1,8394,227,227,227
BEGIN DESCRIPTION:
Mapping XS 7b592365
END DESCRIPTION:
XS GIS Cut Line= 3
      2742288.79      6940232.55      2741514.49      6939867.97
      2740539.88      6939857.56
#Sta/Elev= 30
  4105.3  507.32  4168.4  507.61  4185.7  509.28  4236.8  509.09  4282.3  506.60
  4350.7  506.49  4407.4  504.20  4566.9  501.25  4828.6  498.88  4914.3  499.52
  4926.3  498.84  4937.1  496.53  4969.6  496.36  4977.6  493.59  4977.9  493.09
  4981.6  493.59  4989.6  495.93  5009.6  497.60  5129.6  499.57  5169.6  498.95
  5349.7  502.50  5369.7  501.57  5379.7  503.11  5409.7  503.90  5499.7  504.56
  5599.7  507.90  5739.7  509.64  5769.7  511.30  5859.7  512.89  5935.8  517.06
#Mann=3,-1,0
  4105.3    0.05       0  4977.6    0.04       0  4981.6    0.05       0
Bank Sta=4977.6,4981.6
Exp/Cntr=0.3,0.1

Type RM Length L Ch R = 1,8167,318,318,318
BEGIN DESCRIPTION:
Mapping XS ba70d80b
END DESCRIPTION:
XS GIS Cut Line= 3
      2742407.31      6939737.47      2741431.59      6939657.61
      2740609.83      6939633.34
#Sta/Elev= 30
  4020.9  504.46  4142.6  504.62  4182.8  501.70  4263.0  503.03  4614.2  497.63
  4804.8  498.09  4885.1  496.94  4893.6  497.89  4898.6  497.19  4905.2  497.95
  4975.4  498.36  4985.4  496.24  4999.9  495.64  5003.5  493.28  5003.7  492.78
  5007.5  493.28  5015.5  495.96  5035.5  495.84  5052.4  497.94  5105.5  497.56
  5245.6  498.97  5295.6  500.77  5315.6  500.28  5396.9  502.64  5435.7  504.70
  5535.7  506.12  5565.7  508.34  5685.8  510.48  5715.8  512.41  5822.0  515.37
#Mann=3,-1,0
  4020.9    0.05       0  5003.5    0.05       0  5007.5    0.05       0
Bank Sta=5003.5,5007.5
Exp/Cntr=0.3,0.1

Type RM Length L Ch R = 1,7849,295,295,295
BEGIN DESCRIPTION:
Mapping XS 08ab8de6
END DESCRIPTION:
XS GIS Cut Line= 3
      2742424.69      6939584.70      2741678.12      6939522.19
      2740689.75      6939504.85
#Sta/Elev= 30
  4248.9  504.19  4528.6  502.75  4608.8  501.03  4699.2  501.19  4789.5  497.87
  4799.5  498.69  4849.7  498.16  4869.8  496.46  4940.0  495.71  4970.1  493.96
  4978.1  491.73  4978.4  491.23  4981.9  491.23  4982.1  491.73  4996.6  496.45
  5020.2  495.76  5060.2  496.38  5090.2  494.16  5140.2  494.19  5210.2  496.73
  5310.2  496.46  5348.2  497.91  5520.3  500.13  5540.3  501.05  5560.3  500.32
  5580.3  502.07  5640.3  503.18  5710.3  505.69  5760.3  506.29  5986.6  512.81
#Mann=3,-1,0
  4248.9    0.05       0  4978.1    0.04       0  4982.1    0.05       0
Bank Sta=4978.1,4982.1
Exp/Cntr=0.3,0.1

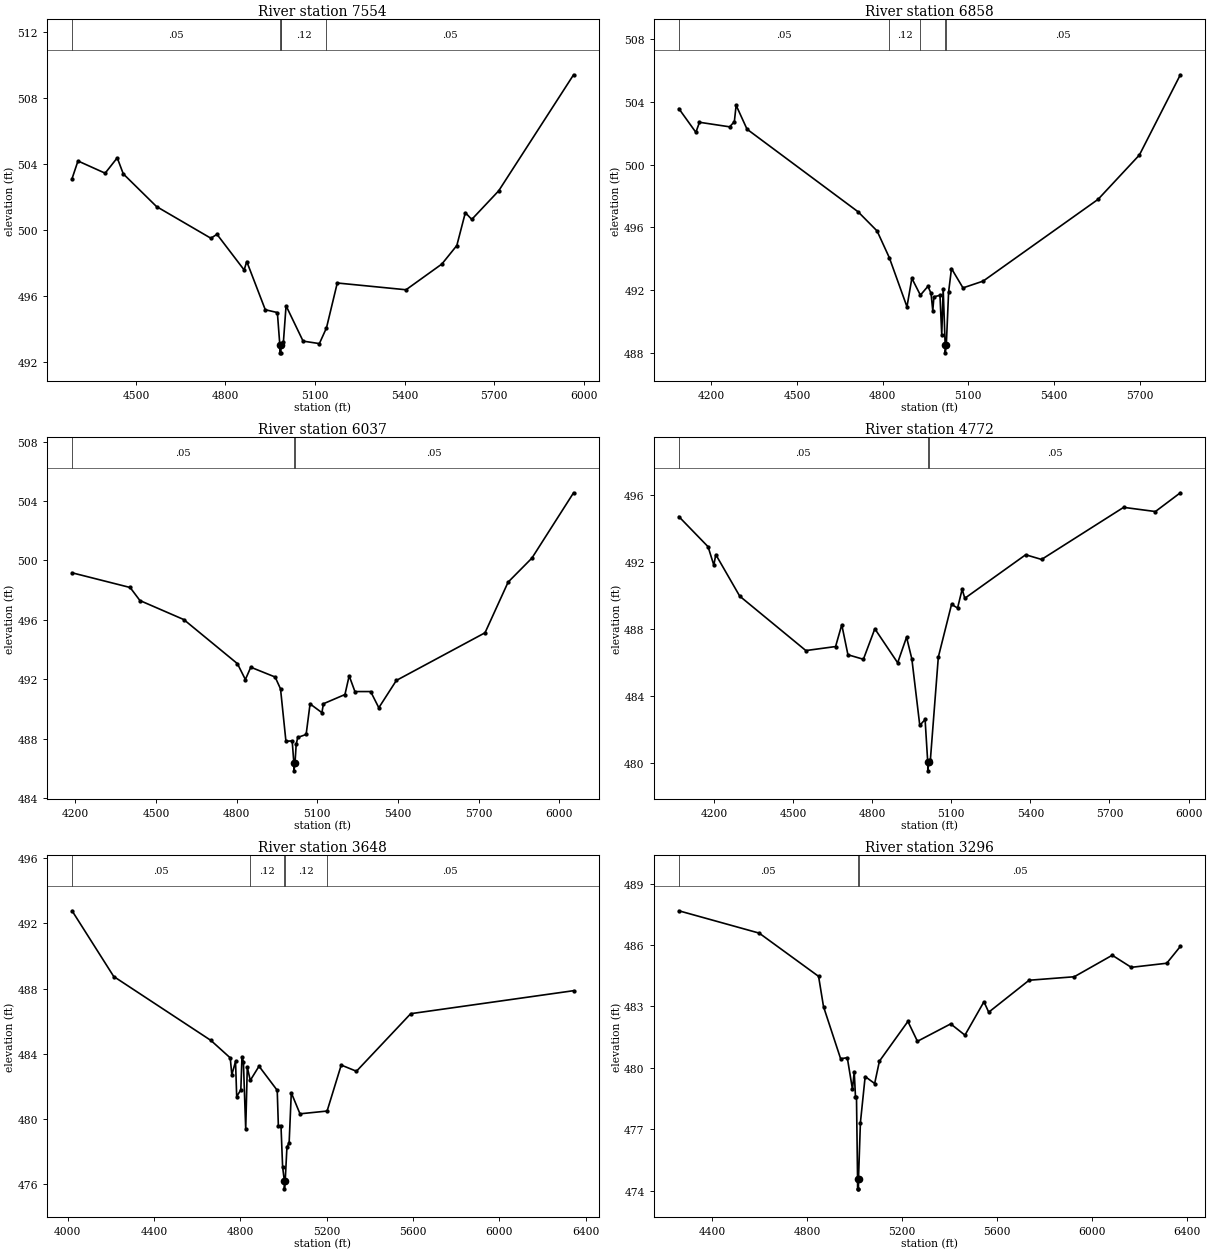
Type RM Length L Ch R = 1,7554,696,696,696
BEGIN DESCRIPTION:
Mapping XS e4c7dc08
END DESCRIPTION:
XS GIS Cut Line= 3
      2742445.52      6939355.53      2741723.26      6939244.41
      2740775.36      6939279.14
#Sta/Elev= 30
  4286.2  503.12  4306.0  504.19  4397.0  503.45  4437.5  504.38  4457.7  503.41
  4569.0  501.43  4751.1  499.51  4771.4  499.75  4862.4  497.59  4871.2  498.10
  4933.2  495.18  4973.7  495.01  4981.8  493.07  4982.1  492.57  4985.6  492.57
  4985.8  493.07  4986.4  493.08  4994.0  493.25  5002.8  495.42  5059.8  493.28
  5114.3  493.13  5138.1  494.08  5174.3  496.80  5404.5  496.39  5524.6  497.95
  5574.6  499.07  5603.1  501.06  5624.6  500.65  5714.7  502.38  5965.5  509.41
#Mann=5,-1,0
  4286.2    0.05       0  4981.8    0.07       0  4985.8    0.05       0
  4986.4    0.12       0  5138.1    0.05       0
Bank Sta=4981.8,4985.8
Exp/Cntr=0.3,0.1

Type RM Length L Ch R = 1,6858,821,821,821
BEGIN DESCRIPTION:
Mapping XS 023a2f43
END DESCRIPTION:
XS GIS Cut Line= 3
      2742501.07      6939063.73      2741693.74      6938673.09
      2740839.82      6938772.79
#Sta/Elev= 30
  4085.9  503.56  4145.6  502.05  4158.2  502.69  4264.0  502.40  4280.4  502.73
  4286.6  503.77  4324.8  502.25  4713.7  497.00  4780.3  495.78  4823.2  494.08
  4885.0  490.96  4902.1  492.77  4932.0  491.70  4958.4  492.26  4969.2  491.82
  4975.4  490.71  4979.4  491.59  5000.6  491.69  5006.8  489.17  5011.8  492.11
  5018.8  488.53  5019.0  488.03  5022.8  488.53  5030.8  491.89  5040.9  493.39
  5081.2  492.16  5151.7  492.59  5554.4  497.79  5699.1  500.61  5842.5  505.71
#Mann=5,-1,0
  4085.9    0.05       0  4823.2    0.12       0  4932.0    0.05       0
  5018.8    0.04       0  5022.8    0.05       0
Bank Sta=5018.8,5022.8
Exp/Cntr=0.3,0.1

Type RM Length L Ch R = 1,6037,1265,1265,1265
BEGIN DESCRIPTION:
Mapping XS 14c5b9d9
END DESCRIPTION:
XS GIS Cut Line= 3
      2742527.08      6937974.30      2741715.44      6938056.77
      2740812.69      6938590.61
#Sta/Elev= 30
  4188.2  499.17  4404.1  498.18  4440.6  497.30  4603.6  496.02  4803.0  493.05
  4832.6  491.98  4852.7  492.81  4943.2  492.15  4963.3  491.35  4983.4  487.82
  5006.6  487.85  5013.0  486.33  5013.2  485.83  5017.0  486.33  5021.5  487.61
  5027.3  488.08  5058.5  488.28  5073.1  490.34  5117.1  489.75  5122.9  490.35
  5202.8  490.97  5218.5  492.23  5239.9  491.17  5298.4  491.17  5328.7  490.08
  5394.0  491.92  5723.6  495.13  5809.4  498.54  5897.9  500.16  6052.8  504.56
#Mann=3,-1,0
  4188.2    0.05       0  5013.0    0.04       0  5017.0    0.05       0
Bank Sta=5013,5017
Exp/Cntr=0.3,0.1

Type RM Length L Ch R = 1,4772,1124,1124,1124
BEGIN DESCRIPTION:
Mapping XS 04fed74a
END DESCRIPTION:
XS GIS Cut Line= 3
      2742347.69      6937572.83      2741670.59      6937277.69
      2740511.79      6937381.85
#Sta/Elev= 30
  4066.7  494.70  4177.6  492.90  4199.4  491.80  4206.9  492.43  4297.6  489.95
  4548.5  486.70  4661.2  486.94  4684.7  488.24  4708.1  486.45  4766.7  486.18
  4810.1  488.00  4896.7  485.97  4930.4  487.50  4950.5  486.20  4980.6  482.23
  5000.7  482.59  5010.8  480.02  5011.1  479.52  5014.8  480.02  5020.8  480.18
  5050.9  486.31  5101.1  489.46  5123.9  489.24  5141.3  490.36  5151.3  489.82
  5382.2  492.42  5442.5  492.14  5753.7  495.25  5874.2  495.00  5968.8  496.12
#Mann=3,-1,0
  4066.7    0.05       0  5010.8    0.04       0  5014.8    0.05       0
Bank Sta=5010.8,5014.8
Exp/Cntr=0.3,0.1

Type RM Length L Ch R = 1,3648,352,352,352
BEGIN DESCRIPTION:
Allen T8_1 2.0
END DESCRIPTION:
XS GIS Cut Line= 3
      2742325.99      6937410.97      2741976.00      6936511.00
      2740626.03      6936361.00
#Sta/Elev= 30
  4020.7  492.78  4213.8  488.75  4664.1  484.83  4753.7  483.76  4761.0  482.72
  4778.2  483.54  4783.6  481.39  4802.8  481.80  4808.1  483.84  4814.7  483.50
  4825.4  479.40  4832.7  483.19  4846.6  482.38  4887.1  483.25  4971.4  481.77
  4976.7  479.59  4988.8  479.61  4996.4  477.07  5004.4  476.23  5004.7  475.73
  5008.4  476.23  5016.5  478.30  5026.6  478.55  5036.6  481.62  5076.9  480.33
  5202.5  480.50  5268.0  483.32  5338.5  482.94  5590.0  486.47  6344.6  487.88
#Mann=5,-1,0
  4020.7    0.05       0  4846.6    0.12       0  5004.4    0.07       0
  5008.4    0.12       0  5202.5    0.05       0
Bank Sta=5004.4,5008.4
Exp/Cntr=0.3,0.1

Type RM Length L Ch R = 1,3296,403,403,403
BEGIN DESCRIPTION:
Mapping XS 0ae6003b
END DESCRIPTION:
XS GIS Cut Line= 3
      2742711.50      6936658.93      2742112.51      6936210.99
      2740749.45      6936247.41
#Sta/Elev= 30
  4260.2  487.67  4598.5  486.58  4848.6  484.47  4869.4  482.99  4941.4  480.45
  4969.5  480.50  4991.3  478.96  4998.7  479.82  5004.0  478.58  5008.2  478.58
  5012.7  474.60  5012.9  474.10  5016.4  474.10  5016.7  474.60  5024.7  477.33
  5044.7  479.58  5084.7  479.24  5104.7  480.33  5224.7  482.27  5264.8  481.30
  5404.8  482.15  5464.8  481.60  5544.9  483.23  5564.9  482.72  5734.9  484.28
  5925.0  484.45  6085.0  485.50  6165.1  484.91  6314.5  485.11  6371.7  485.93
#Mann=3,-1,0
  4260.2    0.05       0  5012.7    0.04       0  5016.7    0.05       0
Bank Sta=5012.7,5016.7
Exp/Cntr=0.3,0.1

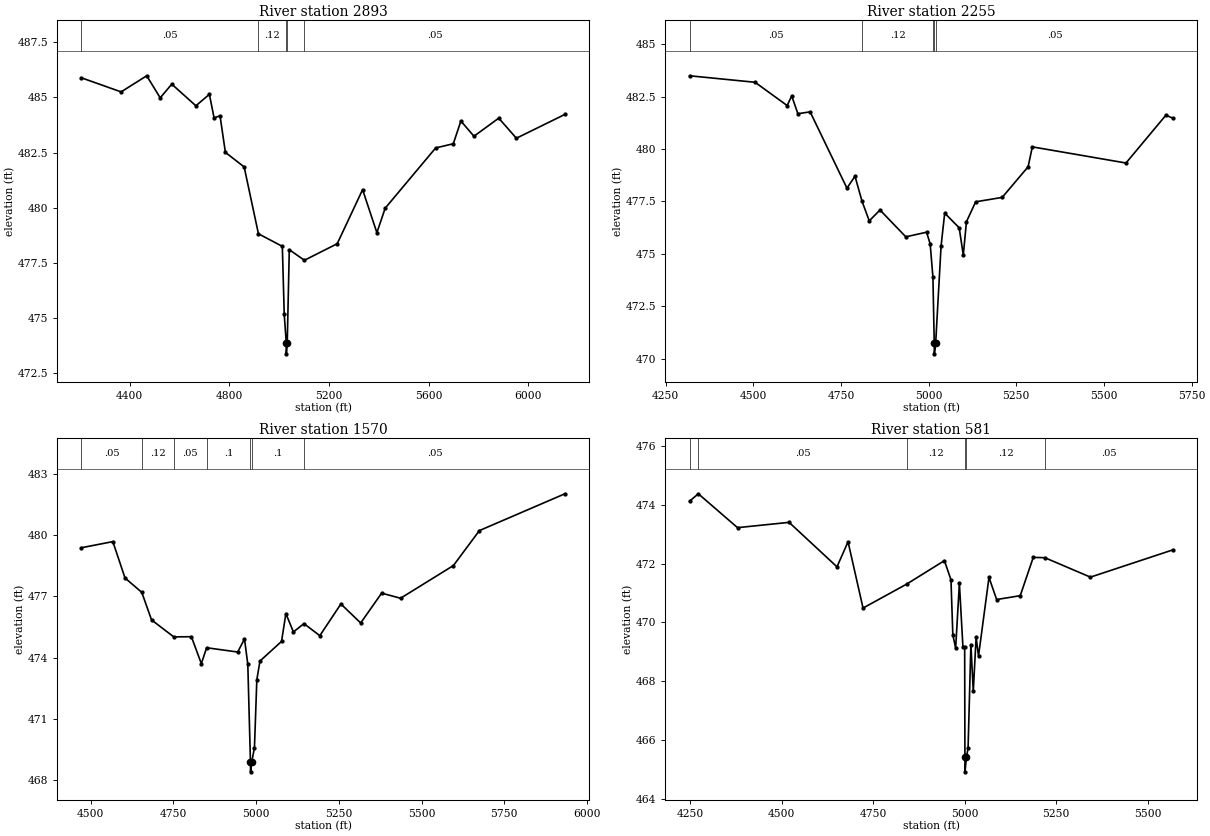
Type RM Length L Ch R = 1,2893,638,638,638
BEGIN DESCRIPTION:
Mapping XS dad0c8d2
END DESCRIPTION:
XS GIS Cut Line= 3
      2742763.50      6936143.27      2742013.55      6935846.41
      2740893.74      6936023.50
#Sta/Elev= 30
  4206.4  485.89  4366.2  485.25  4468.9  485.98  4523.0  484.98  4569.4  485.60
  4666.2  484.62  4720.3  485.14  4739.2  484.07  4763.0  484.17  4784.5  482.51
  4859.8  481.85  4917.1  478.82  5013.0  478.25  5020.6  475.17  5028.7  473.88
  5029.0  473.38  5032.7  473.88  5040.9  478.10  5101.5  477.62  5233.2  478.37
  5335.0  480.82  5392.3  478.87  5425.6  479.98  5628.1  482.71  5698.9  482.90
  5729.3  483.93  5781.8  483.24  5881.2  484.06  5952.0  483.15  6146.7  484.23
#Mann=5,-1,0
  4206.4    0.05       0  4917.1    0.12       0  5028.7    0.07       0
  5032.7    0.12       0  5101.5    0.05       0
Bank Sta=5028.7,5032.7
Exp/Cntr=0.3,0.1

Type RM Length L Ch R = 1,2255,685,685,685
BEGIN DESCRIPTION:
Mapping XS 06a36471
END DESCRIPTION:
XS GIS Cut Line= 3
      2742399.43      6935519.29      2741771.00      6935401.24
      2741055.69      6935588.75
#Sta/Elev= 30
  4318.6  483.49  4505.2  483.18  4596.8  482.07  4609.7  482.53  4627.3  481.68
  4662.2  481.77  4767.2  478.13  4790.1  478.70  4810.3  477.50  4830.8  476.57
  4861.4  477.09  4935.0  475.81  4994.2  476.03  5004.5  475.47  5012.3  473.89
  5016.1  470.73  5016.4  470.23  5020.1  470.73  5035.6  475.38  5045.9  476.94
  5087.2  476.24  5098.9  474.94  5107.9  476.53  5134.2  477.48  5209.8  477.69
  5283.7  479.15  5295.7  480.10  5562.8  479.33  5676.5  481.61  5697.5  481.46
#Mann=5,-1,0
  4318.6    0.05       0  4810.3    0.12       0  5012.3    0.05       0
  5016.1    0.07       0  5020.1    0.05       0
Bank Sta=5016.1,5020.1
Exp/Cntr=0.3,0.1

Type RM Length L Ch R = 1,1570,989,989,989
BEGIN DESCRIPTION:
Mapping XS ad28eb68
END DESCRIPTION:
XS GIS Cut Line= 3
      2742107.77      6934953.32      2741576.56      6934911.66
      2740799.91      6935421.33
#Sta/Elev= 30
  4471.3  479.37  4566.7  479.67  4603.5  477.89  4654.1  477.19  4683.7  475.84
  4750.9  475.01  4804.1  475.02  4834.2  473.70  4850.1  474.48  4944.1  474.27
  4964.6  474.91  4974.6  473.67  4982.6  468.91  4982.9  468.41  4986.7  468.91
  4994.7  469.59  5001.9  472.92  5011.4  473.83  5076.6  474.79  5089.7  476.15
  5112.5  475.25  5144.2  475.66  5192.3  475.07  5256.0  476.62  5315.8  475.69
  5379.1  477.15  5436.3  476.90  5596.1  478.50  5674.6  480.21  5933.1  482.01
#Mann=7,-1,0
  4471.3    0.05       0  4654.1    0.12       0  4750.9    0.05       0
  4850.1     0.1       0  4982.6    0.07       0  4986.7     0.1       0
  5144.2    0.05       0
Bank Sta=4982.6,4986.7
Exp/Cntr=0.3,0.1

Type RM Length L Ch R = 1,581,0,0,0
BEGIN DESCRIPTION:
Allen T8_1 1.0
END DESCRIPTION:
XS GIS Cut Line= 4
      2742126.03      6934246.87      2741529.25      6934181.77
      2741381.90      6934213.26      2740946.73      6934580.63
#Sta/Elev= 30
  4249.0  474.12  4272.8  474.37  4379.8  473.22  4520.6  473.40  4651.4  471.89
  4681.6  472.74  4722.5  470.49  4841.2  471.30  4944.7  472.10  4962.6  471.45
  4967.7  469.58  4975.4  469.13  4985.6  471.33  4995.3  469.16  5000.0  469.16
  5000.7  465.43  5001.0  464.93  5004.8  465.43  5009.3  465.73  5017.0  469.25
  5023.5  467.66  5031.3  469.50  5037.8  468.86  5066.4  471.53  5087.3  470.78
  5151.7  470.91  5187.3  472.21  5218.9  472.20  5343.4  471.54  5569.5  472.47
#Mann=6,-1,0
  4249.0    0.12       0  4272.8    0.05       0  4841.2    0.12       0
  5000.7    0.07       0  5004.8    0.12       0  5218.9    0.05       0
Bank Sta=5000.7,5004.8
Exp/Cntr=0.3,0.1

Chan Stop Cuts=-1