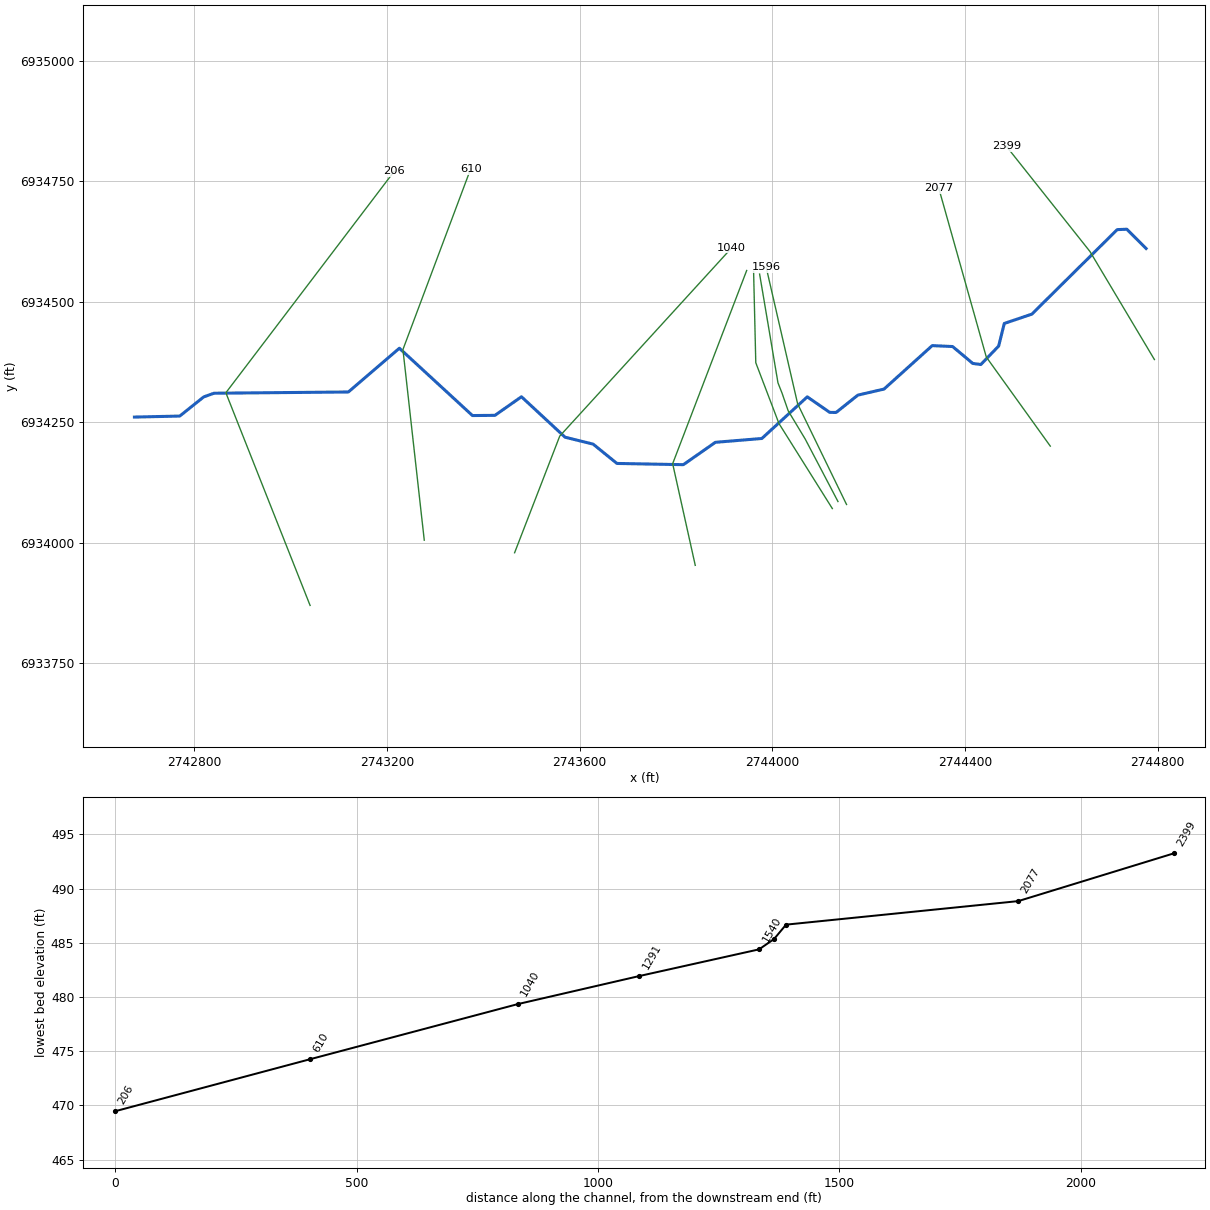
--- Allen T8_2.prj (project) ---

Proj Title=Allen T8_2 Base Level Engineering
Current Plan=p01
Default Exp/Contr=0.3,0.1
English Units
Geom File=g01
Flow File=f01
Plan File=p01
BEGIN DESCRIPTION:
Allen T8_2
END DESCRIPTION:

--- Allen T8_2.p01 (plan) ---

Plan Title=Multiple Run
Short Identifier=Multiple
Geom File=g01
Flow File=f01
Subcritical Flow
K Sum by GR= 0
Std Step Tol= 0.01
Critical Tol= 0.01
Num of Std Step Trials= 20
Max Error Tol= 0.3
Flow Tol Ratio= 0.001
Split Flow NTrial= 30
Split Flow Tol= 0.02
Split Flow Ratio= 0.02
Log Output Level= 0
Friction Slope Method= 1
Unsteady Friction Slope Method= 2
Unsteady Bridges Friction Slope Method= 1
Parabolic Critical Depth
Global Vel Dist=  1 , 1 , 1
Global Log Level= 0
CheckData=True
Encroach Param= -1, 0, 0, 0
BEGIN DESCRIPTION:
Multiple Run
END DESCRIPTION:

--- Allen T8_2.f01 (steady flow) ---

Flow Title=Multiple
Number of Profiles=7
Profile Names=10-year,25-year,50-year,1pct_min,100-year,1pct_plu,500-year
River Rch & RM= Allen T8_2,Reach-1,2399
     178     221     254     146     291     580     381
Boundary for River Rch & Prof#=Allen T8_2,Reach-1,1
Up Type=0
Dn Type=3
Dn Slope=0.005
Boundary for River Rch & Prof#=Allen T8_2,Reach-1,2
Up Type=0
Dn Type=3
Dn Slope=0.005
Boundary for River Rch & Prof#=Allen T8_2,Reach-1,3
Up Type=0
Dn Type=3
Dn Slope=0.005
Boundary for River Rch & Prof#=Allen T8_2,Reach-1,4
Up Type=0
Dn Type=3
Dn Slope=0.005
Boundary for River Rch & Prof#=Allen T8_2,Reach-1,5
Up Type=0
Dn Type=3
Dn Slope=0.005
Boundary for River Rch & Prof#=Allen T8_2,Reach-1,6
Up Type=0
Dn Type=3
Dn Slope=0.005
Boundary for River Rch & Prof#=Allen T8_2,Reach-1,7
Up Type=0
Dn Type=3
Dn Slope=0.005

--- Allen T8_2.g01 (geometry) ---

Geom Title=Existing Conditions

River Reach=Allen T8_2,Reach-1
Reach XY= 30
      2744776.00      6934611.00      2744736.00      6934650.90
      2744716.00      6934650.11      2744538.98      6934474.72
      2744481.62      6934455.32      2744470.01      6934408.49
      2744433.00      6934370.08      2744416.26      6934372.35
      2744374.36      6934407.41      2744332.05      6934409.33
      2744232.04      6934319.14      2744177.65      6934306.56
      2744132.55      6934270.59      2744119.27      6934270.77
      2744072.67      6934302.99      2743978.43      6934216.55
      2743881.98      6934208.64      2743815.49      6934162.20
      2743677.56      6934164.74      2743628.17      6934204.86
      2743569.94      6934219.18      2743479.40      6934303.17
      2743424.35      6934264.59      2743377.65      6934264.16
      2743226.00      6934403.92      2743120.15      6934313.08
      2742841.21      6934310.49      2742819.93      6934302.90
      2742770.13      6934263.10      2742676.00      6934261.00

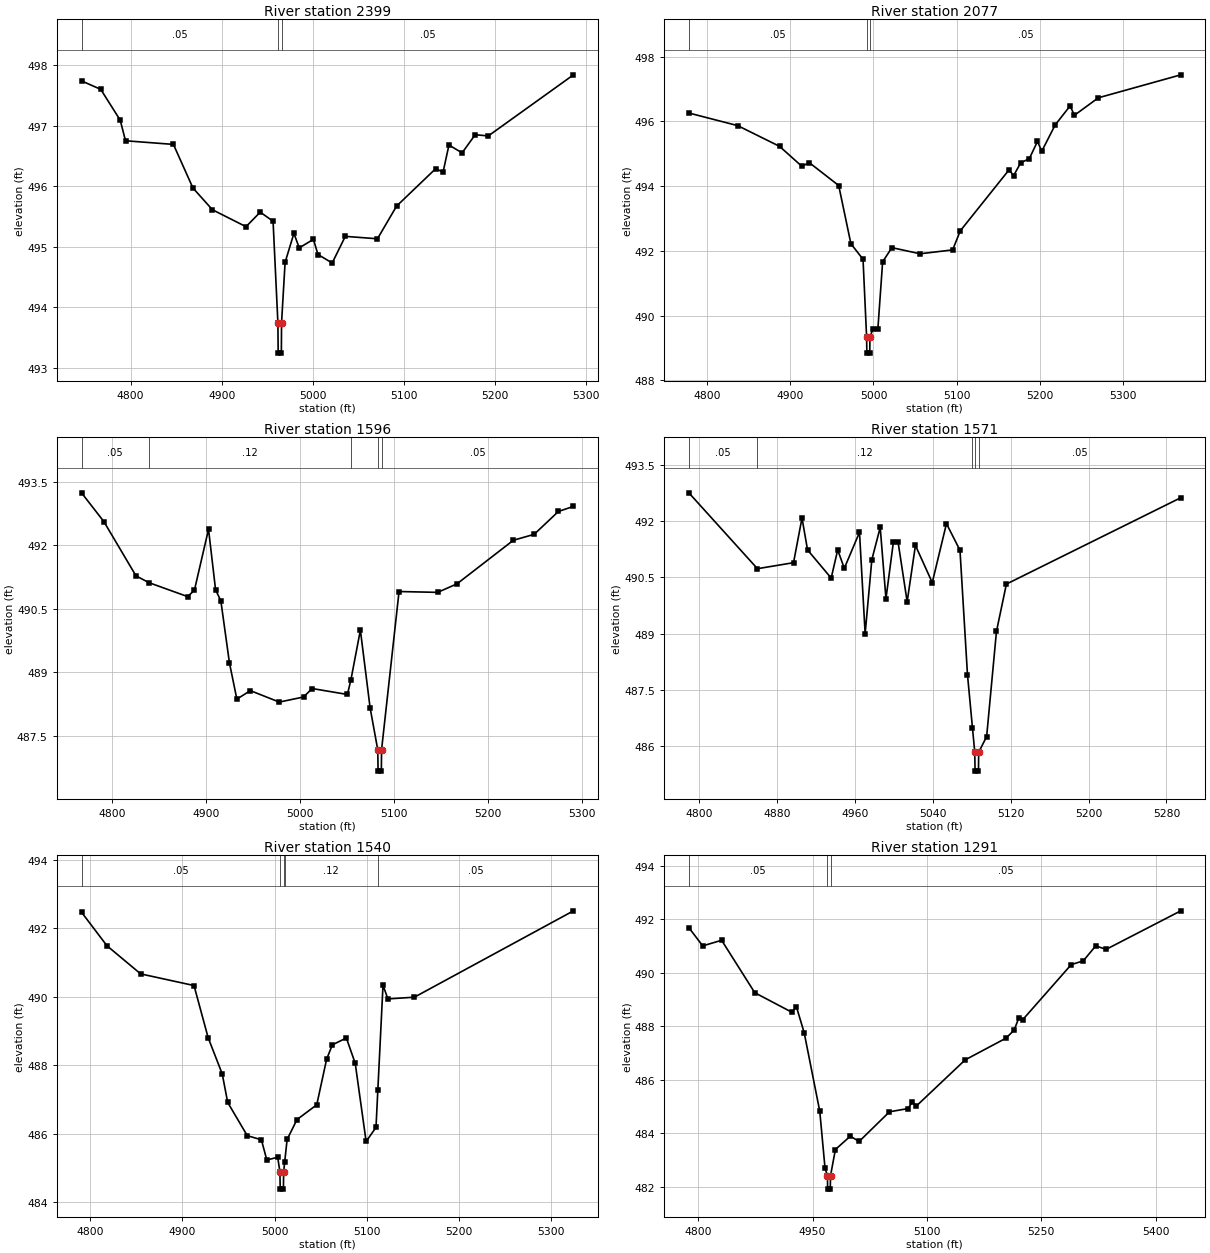
Type RM Length L Ch R = 1,2399,322,322,322
BEGIN DESCRIPTION:
Allen T8_2 2.0
END DESCRIPTION:
XS GIS Cut Line= 3
      2744793.27      6934380.40      2744659.56      6934604.56
      2744485.98      6934823.10
#Sta/Elev= 30
  4746.1  497.74  4767.2  497.60  4788.6  497.09  4794.4  496.75  4847.0  496.69
  4868.4  495.97  4889.8  495.61  4926.7  495.33  4942.3  495.57  4956.4  495.42
  4961.7  493.74  4962.0  493.24  4965.5  493.24  4965.7  493.74  4969.6  494.74
  4979.3  495.22  4985.1  494.98  5000.7  495.12  5005.7  494.87  5021.3  494.73
  5035.7  495.17  5071.0  495.13  5092.0  495.67  5135.0  496.29  5143.0  496.23
  5149.5  496.68  5163.9  496.55  5178.3  496.85  5192.7  496.83  5286.2  497.84
#Mann=3,-1,0
  4746.1    0.05       0  4961.7    0.04       0  4965.7    0.05       0
Bank Sta=4961.7,4965.7
Exp/Cntr=0.3,0.1

Type RM Length L Ch R = 1,2077,481,481,481
BEGIN DESCRIPTION:
Mapping XS 84b1e955
END DESCRIPTION:
XS GIS Cut Line= 3
      2744577.12      6934200.71      2744444.31      6934385.60
      2744345.51      6934736.61
#Sta/Elev= 30
  4777.7  496.26  4836.5  495.87  4886.9  495.23  4913.9  494.61  4922.5  494.73
  4958.1  494.02  4972.8  492.22  4987.4  491.74  4991.7  489.34  4992.0  488.84
  4995.5  488.84  4995.7  489.34  4999.6  489.60  5005.3  489.60  5011.0  491.66
  5022.1  492.10  5056.1  491.91  5095.3  492.03  5104.5  492.62  5163.4  494.51
  5168.6  494.32  5177.2  494.72  5187.6  494.85  5197.4  495.38  5202.6  495.08
  5218.7  495.89  5236.7  496.48  5241.9  496.19  5270.7  496.73  5370.0  497.44
#Mann=3,-1,0
  4777.7    0.05       0  4991.7    0.04       0  4995.7    0.05       0
Bank Sta=4991.7,4995.7
Exp/Cntr=0.3,0.1

Type RM Length L Ch R = 1,1596,25,25,25
BEGIN DESCRIPTION:
Mapping XS 8de708cb
END DESCRIPTION:
XS GIS Cut Line= 3
      2744154.16      6934079.57      2744052.69      6934288.43
      2743987.44      6934571.71
#Sta/Elev= 30
  4767.8  493.24  4791.6  492.56  4825.7  491.28  4839.4  491.12  4880.6  490.79
  4887.8  490.94  4902.8  492.38  4910.3  490.95  4915.9  490.69  4925.0  489.23
  4932.9  488.37  4947.3  488.57  4978.0  488.30  5003.8  488.42  5012.9  488.62
  5050.4  488.48  5054.1  488.82  5064.2  490.00  5074.5  488.17  5082.7  487.17
  5083.0  486.67  5086.5  486.67  5086.7  487.17  5105.3  490.91  5146.3  490.89
  5166.8  491.09  5226.8  492.12  5248.9  492.26  5274.7  492.80  5290.7  492.92
#Mann=5,-1,0
  4767.8    0.05       0  4839.4    0.12       0  5054.1    0.05       0
  5082.7    0.07       0  5086.7    0.05       0
Bank Sta=5082.7,5086.7
Exp/Cntr=0.3,0.1

Type RM Length L Ch R = 1,1571,31,31,31
BEGIN DESCRIPTION:
Mapping XS c0a21688
END DESCRIPTION:
XS GIS Cut Line= 6
      2744136.42      6934085.66      2744068.49      6934215.22
      2744033.02      6934274.11      2744020.04      6934311.47
      2744011.86      6934332.05      2743973.76      6934557.83
#Sta/Elev= 30
  4789.1  492.75  4859.6  490.73  4896.7  490.89  4905.4  492.08  4911.1  491.23
  4935.4  490.48  4942.1  491.23  4948.9  490.74  4964.5  491.70  4970.3  489.00
  4977.2  490.97  4985.8  491.83  4991.7  489.93  4999.4  491.45  5004.1  491.45
  5013.5  489.85  5022.0  491.35  5039.3  490.36  5053.9  491.93  5067.8  491.22
  5075.5  487.91  5080.6  486.50  5083.0  485.84  5083.3  485.34  5086.8  485.34
  5087.0  485.84  5095.2  486.26  5105.3  489.06  5115.5  490.32  5294.8  492.62
#Mann=5,-1,0
  4789.1    0.05       0  4859.6    0.12       0  5080.6    0.05       0
  5083.0    0.07       0  5087.0    0.05       0
Bank Sta=5083,5087
Exp/Cntr=0.3,0.1

Type RM Length L Ch R = 1,1540,249,249,249
BEGIN DESCRIPTION:
Mapping XS 1b66543f
END DESCRIPTION:
XS GIS Cut Line= 4
      2744124.71      6934071.06      2744013.88      6934247.68
      2743965.81      6934373.81      2743961.26      6934563.37
#Sta/Elev= 30
  4790.8  492.47  4818.4  491.49  4854.9  490.67  4912.7  490.33  4928.0  488.81
  4943.3  487.75  4949.2  486.92  4970.4  485.95  4985.7  485.83  4991.6  485.24
  5003.4  485.32  5005.8  484.89  5006.1  484.39  5009.6  484.39  5009.8  484.89
  5011.0  485.19  5013.6  485.84  5024.3  486.42  5045.7  486.85  5056.4  488.18
  5062.6  488.60  5077.8  488.80  5087.4  488.06  5099.2  485.78  5109.9  486.19
  5111.9  487.28  5117.5  490.34  5122.8  489.94  5151.5  489.99  5323.9  492.51
#Mann=5,-1,0
  4790.8    0.05       0  5005.8    0.04       0  5009.8    0.05       0
  5011.0    0.12       0  5111.9    0.05       0
Bank Sta=5005.8,5009.8
Exp/Cntr=0.3,0.1

Type RM Length L Ch R = 1,1291,251,251,251
BEGIN DESCRIPTION:
Mapping XS bd232228
END DESCRIPTION:
XS GIS Cut Line= 3
      2743840.16      6933953.26      2743793.27      6934164.24
      2743946.92      6934565.29
#Sta/Elev= 30
  4787.6  491.69  4805.8  491.01  4830.6  491.22  4874.1  489.26  4922.8  488.53
  4928.7  488.74  4938.9  487.77  4959.4  484.83  4966.3  482.70  4969.5  482.42
  4969.7  481.92  4973.2  481.92  4973.5  482.42  4979.9  483.40  4999.5  483.90
  5011.0  483.70  5050.9  484.81  5075.2  484.93  5080.9  485.18  5086.3  485.03
  5150.2  486.75  5203.7  487.56  5214.4  487.86  5220.4  488.30  5225.7  488.25
  5289.4  490.31  5305.2  490.45  5321.5  491.01  5335.2  490.88  5433.2  492.32
#Mann=3,-1,0
  4787.6    0.05       0  4969.5    0.04       0  4973.5    0.05       0
Bank Sta=4969.5,4973.5
Exp/Cntr=0.3,0.1

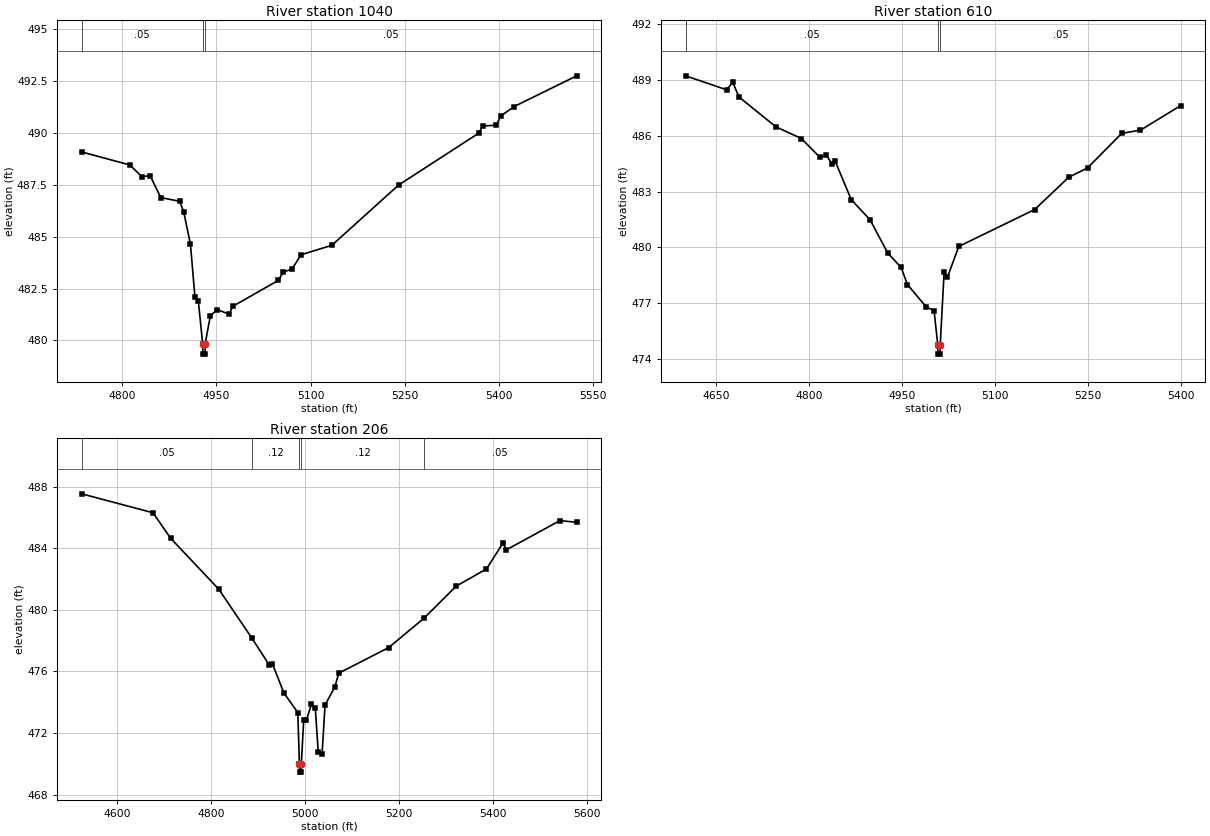
Type RM Length L Ch R = 1,1040,430,430,430
BEGIN DESCRIPTION:
Mapping XS fe36bb59
END DESCRIPTION:
XS GIS Cut Line= 3
      2743465.16      6933979.37      2743558.90      6934221.53
      2743915.67      6934612.16
#Sta/Elev= 30
  4735.4  489.09  4812.3  488.46  4831.5  487.89  4844.4  487.95  4861.4  486.89
  4891.4  486.71  4898.0  486.20  4908.7  484.64  4915.9  482.09  4921.3  481.89
  4928.2  479.84  4928.4  479.34  4931.9  479.34  4932.2  479.84  4940.5  481.20
  4951.6  481.48  4970.4  481.27  4975.8  481.64  5049.0  482.90  5056.4  483.30
  5070.6  483.44  5084.8  484.13  5134.1  484.59  5240.2  487.49  5367.8  489.99
  5374.6  490.34  5396.2  490.38  5403.0  490.82  5424.6  491.28  5524.1  492.76
#Mann=3,-1,0
  4735.4    0.05       0  4928.2    0.04       0  4932.2    0.05       0
Bank Sta=4928.2,4932.2
Exp/Cntr=0.3,0.1

Type RM Length L Ch R = 1,610,404,404,404
BEGIN DESCRIPTION:
Mapping XS b9a1f430
END DESCRIPTION:
XS GIS Cut Line= 3
      2743277.64      6934005.43      2743233.38      6934401.22
      2743373.95      6934776.07
#Sta/Elev= 30
  4601.4  489.22  4667.4  488.47  4677.4  488.87  4687.5  488.08  4747.0  486.48
  4788.1  485.85  4818.3  484.83  4828.4  484.95  4837.3  484.50  4842.3  484.66
  4868.6  482.56  4898.8  481.49  4927.5  479.69  4949.1  478.92  4959.2  478.00
  4989.4  476.80  5002.2  476.60  5008.1  474.76  5008.4  474.26  5011.9  474.26
  5012.1  474.76  5018.4  478.67  5023.7  478.39  5042.1  480.05  5164.4  482.03
  5219.5  483.77  5249.8  484.27  5305.0  486.13  5335.2  486.30  5400.0  487.62
#Mann=3,-1,0
  4601.4    0.05       0  5008.1    0.04       0  5012.1    0.05       0
Bank Sta=5008.1,5012.1
Exp/Cntr=0.3,0.1

Type RM Length L Ch R = 1,206,0,0,0
BEGIN DESCRIPTION:
Allen T8_2 1.0
END DESCRIPTION:
XS GIS Cut Line= 3
      2743040.65      6933870.02      2742865.81      6934311.45
      2743215.17      6934771.04
#Sta/Elev= 30
  4525.2  487.54  4676.8  486.31  4714.4  484.65  4816.7  481.34  4887.3  478.15
  4924.2  476.41  4930.6  476.50  4954.9  474.61  4984.6  473.33  4988.0  469.96
  4988.3  469.46  4991.8  469.46  4992.0  469.96  4997.1  472.84  5002.9  472.84
  5013.4  473.86  5021.7  473.65  5028.0  470.75  5036.2  470.66  5042.5  473.83
  5063.3  474.99  5071.6  475.89  5177.7  477.55  5252.4  479.45  5321.1  481.54
  5385.6  482.66  5421.0  484.36  5427.2  483.89  5541.6  485.80  5577.3  485.69
#Mann=5,-1,0
  4525.2    0.05       0  4887.3    0.12       0  4988.0    0.07       0
  4992.0    0.12       0  5252.4    0.05       0
Bank Sta=4988,4992
Exp/Cntr=0.3,0.1

Chan Stop Cuts=-1