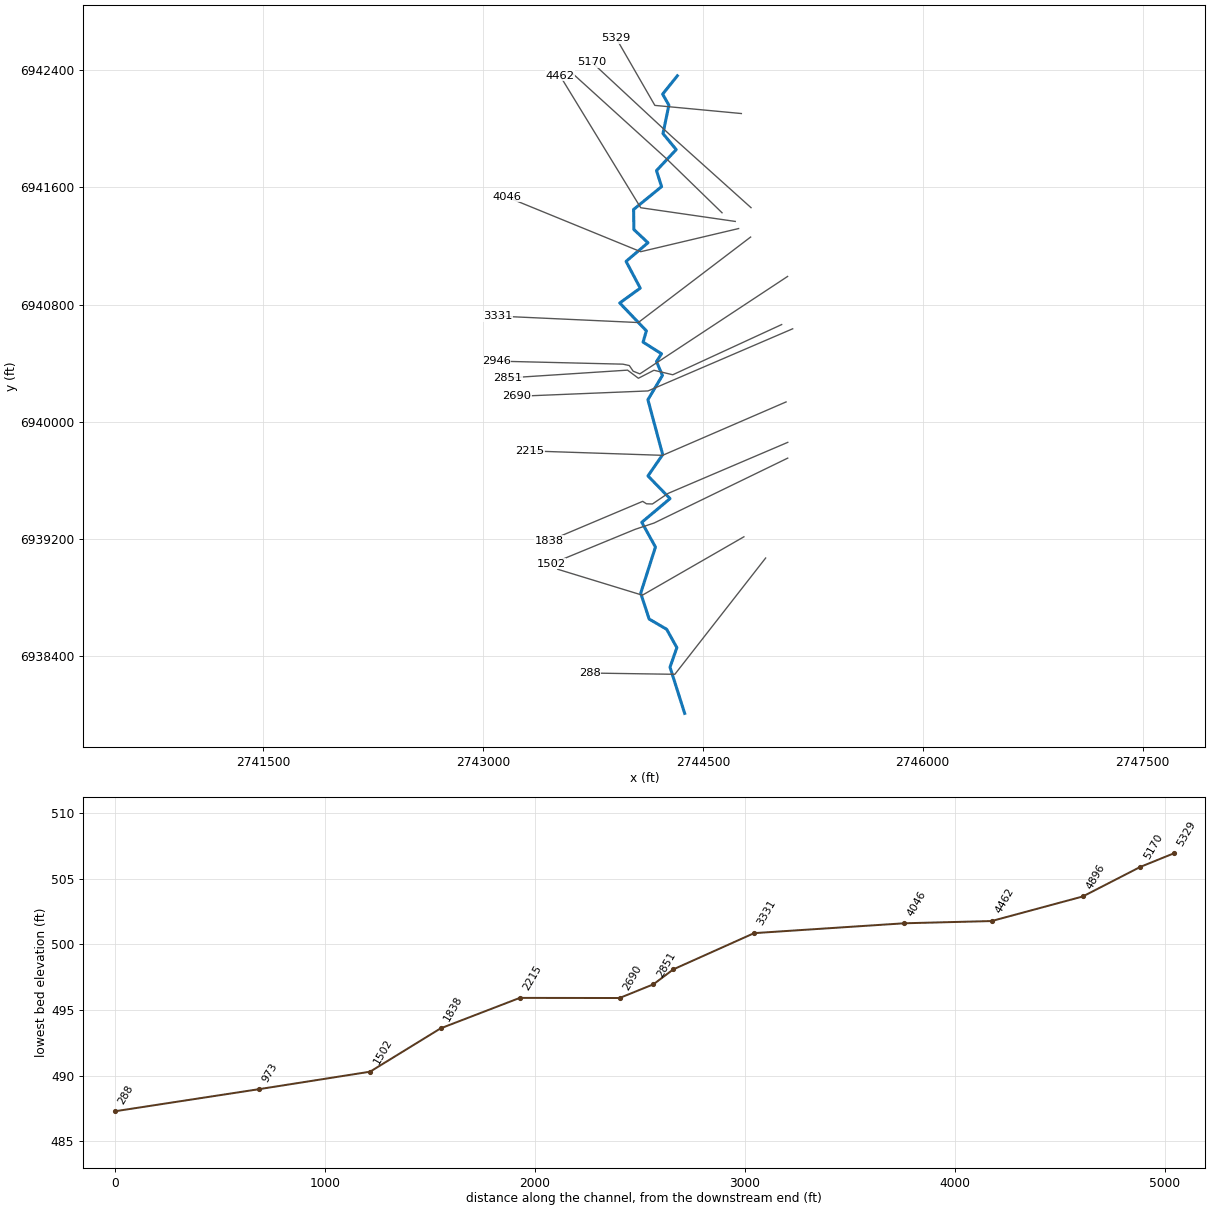
--- Allen T8_3.prj (project) ---

Proj Title=Allen T8_3 Base Level Engineering
Current Plan=p01
Default Exp/Contr=0.3,0.1
English Units
Geom File=g01
Flow File=f01
Plan File=p01
Y Axis Title=Elevation
X Axis Title(PF)=Main Channel Distance
X Axis Title(XS)=Station
BEGIN DESCRIPTION:
Allen T8_3
END DESCRIPTION:
DSS Export Rating Curves= 0
DSS Export Rating Curve Sorted= 0
DSS Export Volume Flow Curves= 0
DXF OffsetX= 0
DXF OffsetY= 0
DXF ScaleX= 1
DXF ScaleY= 10

--- Allen T8_3.p01 (plan) ---

Plan Title=Multiple Run
Short Identifier=Multiple
Geom File=g01
Flow File=f01
Subcritical Flow
K Sum by GR= 0
Std Step Tol= 0.01
Critical Tol= 0.01
Num of Std Step Trials= 20
Max Error Tol= 0.3
Flow Tol Ratio= 0.001
Split Flow NTrial= 30
Split Flow Tol= 0.02
Split Flow Ratio= 0.02
Log Output Level= 0
Friction Slope Method= 1
Unsteady Friction Slope Method= 2
Unsteady Bridges Friction Slope Method= 1
Parabolic Critical Depth
Global Vel Dist=  1 , 1 , 1
Global Log Level= 0
CheckData=True
Encroach Param= -1, 0, 0, 0
BEGIN DESCRIPTION:
Multiple Run
END DESCRIPTION:

--- Allen T8_3.f01 (steady flow) ---

Flow Title=Multiple
Program Version=4.10
Number of Profiles= 7
Profile Names=10-year,25-year,50-year,1pct_min,100-year,1pct_plu,500-year
River Rch & RM=Allen T8_3,Reach-1         ,5329
     289     368     429     249     497     991     666
Boundary for River Rch & Prof#=Allen T8_3,Reach-1         , 1
Up Type= 0
Dn Type= 3
Dn Slope=0.00254
Boundary for River Rch & Prof#=Allen T8_3,Reach-1         , 2
Up Type= 0
Dn Type= 3
Dn Slope=0.00254
Boundary for River Rch & Prof#=Allen T8_3,Reach-1         , 3
Up Type= 0
Dn Type= 3
Dn Slope=0.00254
Boundary for River Rch & Prof#=Allen T8_3,Reach-1         , 4
Up Type= 0
Dn Type= 3
Dn Slope=0.00254
Boundary for River Rch & Prof#=Allen T8_3,Reach-1         , 5
Up Type= 0
Dn Type= 3
Dn Slope=0.00254
Boundary for River Rch & Prof#=Allen T8_3,Reach-1         , 6
Up Type= 0
Dn Type= 3
Dn Slope=0.00254
Boundary for River Rch & Prof#=Allen T8_3,Reach-1         , 7
Up Type= 0
Dn Type= 3
Dn Slope=0.00254
DSS Import GetInterval= 0
DSS Import GetPeak= 0
DSS Import FillOption= 0

--- Allen T8_3.g01 (geometry) ---

Geom Title=Existing Conditions
Program Version=4.10

River Reach=Allen T8_3      ,Reach-1
Reach XY= 30
        2744326.        6942361.      2744225.57      6942235.99
      2744268.41      6942161.01      2744228.07      6941966.86
       2744318.4      6941857.66      2744183.82      6941714.41
       2744218.5      6941604.95      2744027.61      6941449.17
      2744029.47      6941312.27      2744125.61      6941222.01
      2743976.17      6941094.96      2744072.99      6940912.43
      2743932.98      6940811.21      2744114.75      6940620.99
      2744092.24      6940543.96      2744218.11      6940464.58
      2744183.84       6940411.1      2744224.34      6940317.05
      2744125.21      6940150.96      2744226.04      6939776.34
      2744125.49      6939631.06      2744276.14      6939476.41
      2744083.49      6939314.58      2744176.73      6939145.94
      2744076.05      6938831.04      2744133.75      6938654.55
      2744253.14      6938584.84      2744322.66      6938459.28
       2744276.1       6938326.4        2744376.        6938011.

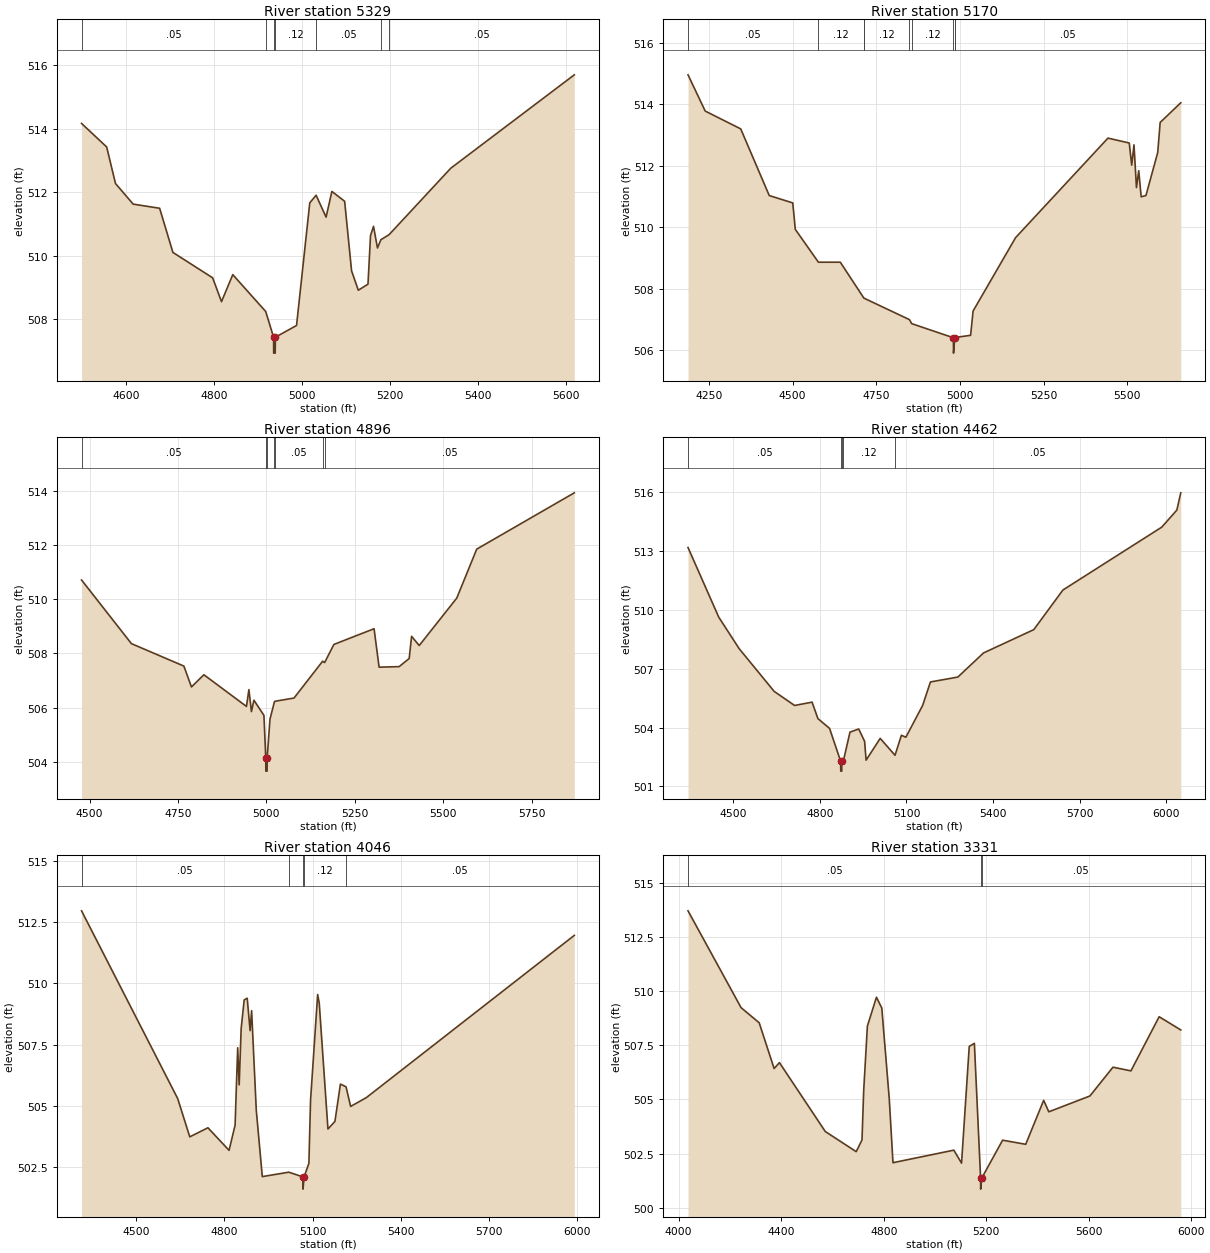
Type RM Length L Ch R = 1 ,5329    ,159,159,159
BEGIN DESCRIPTION:
Allen T8_3 6.0
END DESCRIPTION:
XS GIS Cut Line= 3
      2744762.85       6942103.7      2744172.62      6942159.25
      2743909.19      6942616.79
#Sta/Elev= 30
  4499.1  514.16  4556.2  513.42  4576.3  512.27  4616.5  511.62  4676.7  511.49
  4706.9   510.1  4797.3   509.3  4817.4  508.55  4843.1   509.4    4918  508.24
  4935.9  507.43  4936.1  506.93  4939.6  506.93  4939.9  507.43  4988.1   507.8
  5018.2  511.66  5032.6   511.9  5055.3  511.21  5068.5  512.02  5097.5  511.71
  5113.3  509.52  5128.6  508.91  5150.6   509.1  5156.4  510.63  5163.2  510.92
  5172.2  510.24    5180   510.5  5198.7  510.66  5338.9  512.75  5619.9  515.69
#Mann= 7 ,-1 , 0
  4499.1     .05       0    4918     .12       0  4935.9     .07       0
  4939.9     .12       0  5032.6     .05       0    5180     .12       0
  5198.7     .05       0
Bank Sta=4935.9,4939.9
XS Rating Curve= 0 ,0
Exp/Cntr=0.3,0.1

Type RM Length L Ch R = 1 ,5170    ,274,274,274
BEGIN DESCRIPTION:
Mapping XS ef0b20b9
END DESCRIPTION:
XS GIS Cut Line= 3
      2744828.86      6941461.34      2744283.73      6941950.92
      2743742.08      6942454.38
#Sta/Elev= 30
  4187.8  514.96  4239.2  513.78  4345.3   513.2  4430.5  511.03  4500.8  510.79
  4508.3  509.93  4577.4  508.86  4642.8  508.86  4713.3  507.69  4713.4  507.69
  4849.4  506.99    4856  506.86  4980.8   506.4    4981   505.9  4984.8   506.4
  4986.5  506.41  5032.1  506.48  5039.5  507.27  5166.5  509.66  5442.5   512.9
  5506.1  512.74  5513.4  512.02  5520.2  512.68  5527.6  511.29  5534.4  511.84
  5541.7  510.99  5555.9  511.03  5591.1  512.43  5598.4  513.41    5660  514.05
#Mann= 9 ,-1 , 0
  4187.8     .05       0  4577.4     .12       0  4713.3     .05       0
  4713.4     .12       0  4849.4     .05       0    4856     .12       0
  4980.8     .04       0  4984.8     .12       0  4986.5     .05       0
Bank Sta=4980.8,4984.8
XS Rating Curve= 0 ,0
Exp/Cntr=0.3,0.1

Type RM Length L Ch R = 1 ,4896    ,434,434,434
BEGIN DESCRIPTION:
Mapping XS 8490d34d
END DESCRIPTION:
XS GIS Cut Line= 3
      2744630.97       6941426.6      2744249.01      6941798.14
      2743611.64      6942376.62
#Sta/Elev= 30
  4477.2  510.71  4618.2  508.36  4766.6  507.53    4788  506.76  4823.2  507.21
  4943.6  506.04  4950.5  506.66  4957.7  505.85  4964.7  506.27    4993  505.71
  4998.2  504.15  4998.4  503.65  5001.9  503.65  5002.2  504.15  5010.1  505.57
  5022.6  506.21  5024.3  506.23  5078.1  506.35    5159  507.71  5164.7  507.66
  5190.9  508.33  5304.5  508.91  5318.7  507.49  5375.4  507.51  5403.8  507.81
  5410.6  508.63  5432.2  508.29  5538.3  510.04  5594.8  511.85  5870.8  513.93
#Mann= 7 ,-1 , 0
  4477.2     .05       0  4998.2     .04       0  5002.2     .05       0
  5022.6     .12       0  5024.3     .05       0    5159     .12       0
  5164.7     .05       0
Bank Sta=4998.2,5002.2
XS Rating Curve= 0 ,0
Exp/Cntr=0.3,0.1

Type RM Length L Ch R = 1 ,4462    ,416,416,416
BEGIN DESCRIPTION:
Allen T8_3 5.0
END DESCRIPTION:
XS GIS Cut Line= 3
      2744721.24      6941367.58        2744076.        6941461.
      2743526.01      6942360.98
#Sta/Elev= 30
  4343.3  513.19  4449.6  509.64  4520.4  508.03  4641.6  505.85  4712.4  505.13
    4773   505.3  4793.2  504.46  4833.6  503.96    4872  502.28  4872.3  501.78
  4875.8  501.78    4876  502.28  4881.7  502.32  4904.3  503.77  4934.6  503.93
  4954.9   503.3  4960.1  502.34  5008.9  503.45  5060.3  502.59  5082.4  503.61
  5097.8  503.51  5155.9  505.13    5183  506.33  5277.9  506.58  5366.8  507.81
    5541     509  5641.7  511.02  5984.2  514.23  6036.4   515.1    6050  515.98
#Mann= 5 ,-1 , 0
  4343.3     .05       0    4872     .07       0    4876     .05       0
  4881.7     .12       0  5060.3     .05       0
Bank Sta=4872,4876
XS Rating Curve= 0 ,0
Exp/Cntr=0.3,0.1

Type RM Length L Ch R = 1 ,4046    ,715,715,715
BEGIN DESCRIPTION:
Allen T8_3 4.0
END DESCRIPTION:
XS GIS Cut Line= 3
      2744744.14      6941318.97        2744076.        6941161.
      2743160.55      6941535.09
#Sta/Elev= 30
  4314.3  512.95  4641.2   505.3  4682.3  503.74    4744  504.11  4815.9  503.19
  4836.4  504.22  4845.2  507.37  4850.3  505.86    4857  508.15  4867.3  509.32
  4877.6  509.39  4887.4  508.07  4892.6  508.88  4908.4  504.83  4928.9  502.12
  5018.9   502.3    5067  502.11  5067.3  501.61    5071  502.11  5087.3  502.66
    5093  505.24  5117.1  509.54  5122.5  509.19  5152.1  504.06  5175.9  504.37
  5194.5  505.89  5213.6  505.78  5229.3  504.98  5282.8  505.34  5989.8  511.95
#Mann= 5 ,-1 , 0
  4314.3     .05       0  5018.9     .12       0    5067     .03       0
    5071     .12       0  5213.6     .05       0
Bank Sta=5067,5071
XS Rating Curve= 0 ,0
Exp/Cntr=0.3,0.1

Type RM Length L Ch R = 1 ,3331    ,385,385,385
BEGIN DESCRIPTION:
Allen T8_3 3.0
END DESCRIPTION:
XS GIS Cut Line= 3
        2744826.        6941261.      2744059.52      6940677.67
      2743101.84      6940721.75
#Sta/Elev= 30
  4036.8  513.71  4243.7  509.24  4314.4  508.54  4372.6  506.43  4393.4   506.7
  4572.2  503.52  4692.8  502.59  4715.4  503.13  4721.9  505.39  4736.4  508.39
  4771.8  509.72  4792.6  509.22  4821.7  505.03  4836.2  502.08  5073.6  502.66
  5103.6  502.06  5133.7  507.45  5153.7  507.59    5178  501.36  5178.2  500.86
    5182  501.36  5263.8  503.12  5353.9  502.93    5424  504.96    5444  504.43
  5604.2  505.16  5694.3  506.49  5764.3  506.32  5874.4  508.82  5958.7  508.21
#Mann= 3 ,-1 , 0
  4036.8     .05       0    5178     .03       0    5182     .05       0
Bank Sta=5178,5182
XS Rating Curve= 0 ,0
Exp/Cntr=0.3,0.1

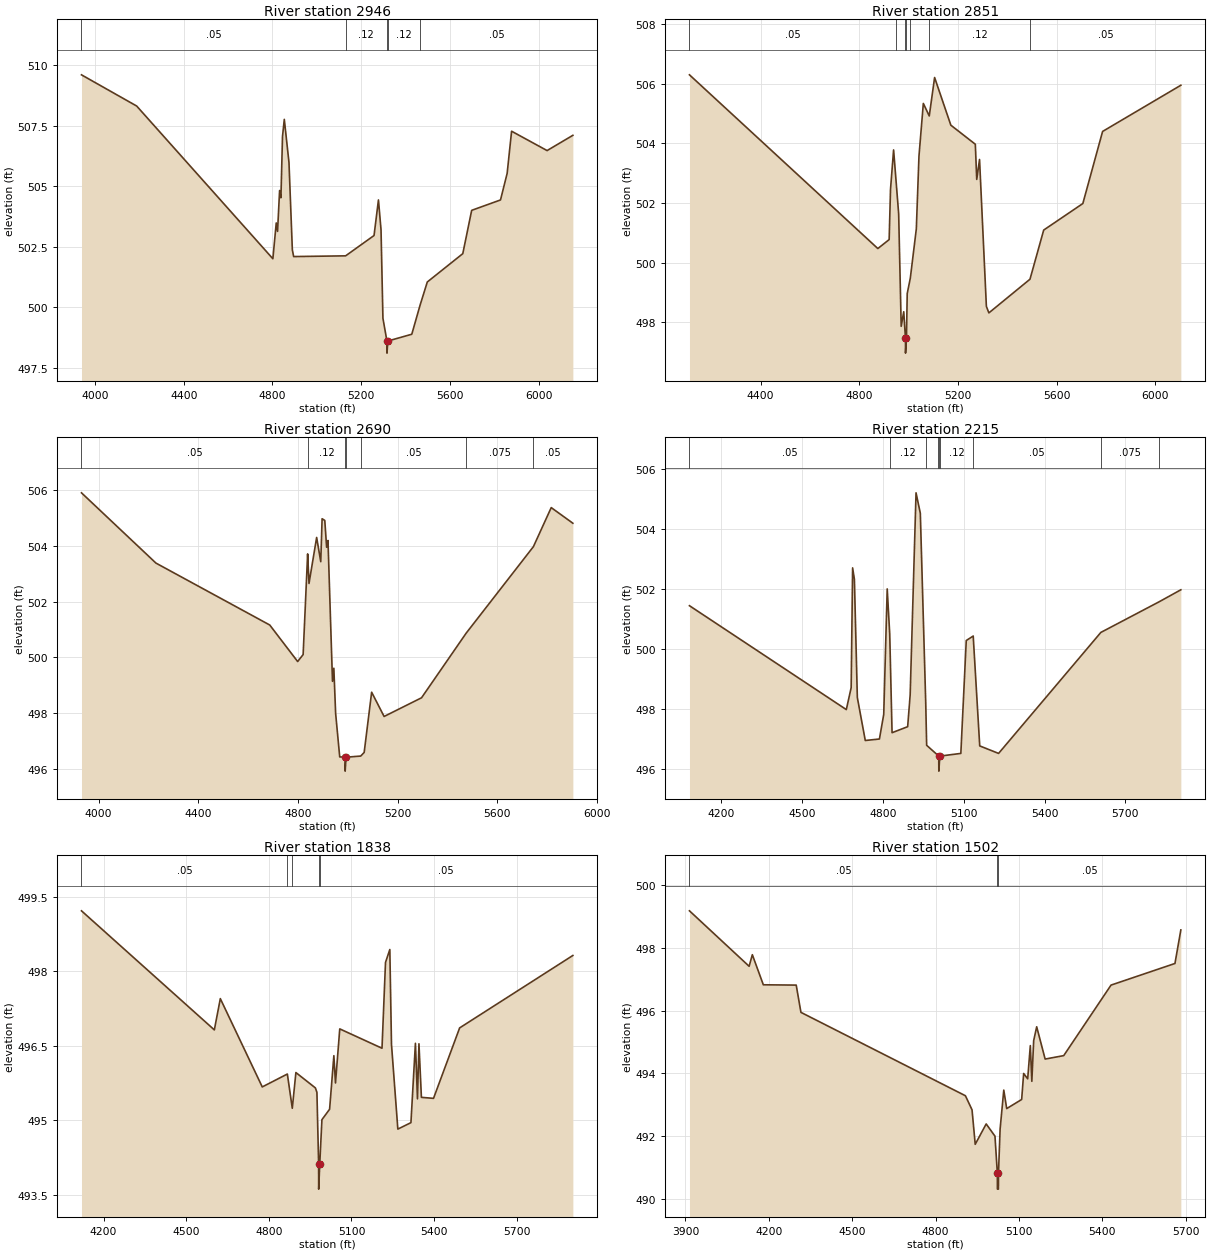
Type RM Length L Ch R = 1 ,2946    ,95,95,95
BEGIN DESCRIPTION:
Mapping XS 49873d89
END DESCRIPTION:
XS GIS Cut Line= 6
      2745078.24      6940992.16      2744070.17      6940327.38
       2744024.7      6940345.77      2743998.51      6940384.11
      2743954.67       6940393.7      2743089.79      6940414.47
#Sta/Elev= 30
  3938.7   509.6  4187.7  508.31  4801.8     502    4817  503.48  4822.9  503.13
  4832.1  504.82  4838.1  504.52  4845.2  507.05  4853.3  507.76  4874.4  505.98
  4889.6  502.37  4895.5  502.09  5129.9  502.12    5258  502.96  5277.9  504.43
  5289.5   503.2  5298.1  499.54  5316.1   498.6  5316.4   498.1  5320.1   498.6
  5428.2  498.88  5465.9  500.09  5498.2  501.04  5658.2  502.21  5698.3     504
  5828.3  504.43  5858.3  505.53  5878.3  507.27  6038.4  506.47  6154.6   507.1
#Mann= 5 ,-1 , 0
  3938.7     .05       0  5129.9     .12       0  5316.1     .03       0
  5320.1     .12       0  5465.9     .05       0
Bank Sta=5316.1,5320.1
XS Rating Curve= 0 ,0
Exp/Cntr=0.3,0.1

Type RM Length L Ch R = 1 ,2851    ,161,161,161
BEGIN DESCRIPTION:
Mapping XS c16c979e
END DESCRIPTION:
XS GIS Cut Line= 6
      2745037.86      6940663.91      2744294.73      6940321.34
      2744166.57      6940352.03      2744060.24      6940297.52
      2743986.41       6940352.9      2743169.62       6940299.6
#Sta/Elev= 30
  4111.4   506.3  4874.8  500.47  4920.7  500.77  4926.2  502.46  4938.7  503.78
  4949.8  502.62  4959.2  501.64  4969.5  497.86  4979.8  498.35  4986.8  497.46
    4987  496.96  4990.8  497.46  4993.9  498.96  5006.5  499.48  5030.8  501.13
  5041.5  503.57  5059.2  505.34  5083.2  504.92  5104.9  506.21  5170.7  504.61
  5269.9  503.97  5275.6  502.79    5287  503.46  5314.7  498.53  5324.8  498.31
  5491.4  499.44    5547  501.09  5705.6  501.98  5785.7   504.4  6102.8  505.95
#Mann= 7 ,-1 , 0
  4111.4     .05       0  4949.8     .12       0  4986.8     .07       0
  4990.8     .12       0  5006.5     .05       0  5083.2     .12       0
  5491.4     .05       0
Bank Sta=4986.8,4990.8
XS Rating Curve= 0 ,0
Exp/Cntr=0.3,0.1

Type RM Length L Ch R = 1 ,2690    ,475,475,475
BEGIN DESCRIPTION:
Allen T8_3 2.0
END DESCRIPTION:
XS GIS Cut Line= 3
      2745112.99      6940635.05        2744126.        6940211.
      2743229.28      6940174.18
#Sta/Elev= 30
  3931.6   505.9  4230.4  503.38    4687  501.16    4799  499.85    4821   500.1
  4839.1  503.71  4842.2  503.11  4844.6  502.65  4875.2   504.3  4891.7  503.43
  4897.1  504.97  4907.9  504.91  4915.2  503.95  4920.7  504.19  4938.8  499.14
  4944.2  499.61  4951.4  497.99  4967.8  496.43  4989.3  496.42  4989.6  495.92
  4993.3  496.42    5052  496.46  5065.9  496.59  5095.9  498.75  5145.9  497.88
  5296.1  498.55  5475.4  500.87    5745  503.97  5816.5  505.37  5903.3  504.81
#Mann= 7 ,-1 , 0
  3931.6     .05       0  4842.2     .12       0  4989.3     .07       0
  4993.3     .12       0    5052     .05       0  5475.4    .075       0
    5745     .05       0
Bank Sta=4989.3,4993.3
XS Rating Curve= 0 ,0
Exp/Cntr=0.3,0.1

Type RM Length L Ch R = 1 ,2215    ,377,377,377
BEGIN DESCRIPTION:
Mapping XS 218d61bc
END DESCRIPTION:
XS GIS Cut Line= 3
      2745067.89      6940135.97      2744225.39      6939771.62
      2743319.89      6939801.72
#Sta/Elev= 30
  4082.1  501.44  4664.3  497.98  4682.3  498.71  4687.7   502.7  4694.3  502.32
  4705.2  498.38  4734.7  496.95  4787.2     497  4803.2  497.82  4816.1     502
  4825.4   500.5  4834.1  497.21    4892  497.41  4901.3  498.47  4923.1   505.2
    4939  504.52  4959.1  498.19  4962.5  496.79  5005.1  496.45  5007.4  496.43
  5007.7  495.93  5011.4  496.43  5089.4  496.52  5109.5  500.28  5135.3  500.43
  5159.5  496.77  5229.5  496.52  5609.1  500.55  5825.3  501.57    5906  501.97
#Mann= 9 ,-1 , 0
  4082.1     .05       0  4825.4     .12       0  4959.1     .05       0
  5005.1     .12       0  5007.4     .03       0  5011.4     .12       0
  5135.3     .05       0  5609.1    .075       0  5825.3     .05       0
Bank Sta=5007.4,5011.4
XS Rating Curve= 0 ,0
Exp/Cntr=0.3,0.1

Type RM Length L Ch R = 1 ,1838    ,336,336,336
BEGIN DESCRIPTION:
Mapping XS 19acab09
END DESCRIPTION:
XS GIS Cut Line= 6
      2745079.49       6939860.2      2744262.23      6939511.55
      2744155.94      6939439.72      2744115.64      6939440.92
       2744089.6      6939457.61      2743449.55      6939187.43
#Sta/Elev= 30
  4120.1  499.22  4602.3  496.82    4624  497.45  4776.2  495.67  4867.3  495.93
  4885.2  495.24  4898.3  495.96  4969.1  495.65  4974.6  495.56  4980.8  494.11
    4981  493.61  4984.8  494.11  4992.7  495.01  5020.6  495.22  5036.1   496.3
    5042  495.75  5057.5  496.84  5210.8  496.45  5223.5  498.18  5239.2  498.44
  5245.2  496.53  5268.3  494.82  5315.8  494.95  5332.1  496.55  5339.5  495.43
  5344.9  496.54  5353.8  495.46  5397.8  495.44  5492.6  496.86  5903.5  498.32
#Mann= 5 ,-1 , 0
  4120.1     .05       0  4867.3     .12       0  4885.2     .05       0
  4980.8     .04       0  4984.8     .05       0
Bank Sta=4980.8,4984.8
XS Rating Curve= 0 ,0
Exp/Cntr=0.3,0.1

Type RM Length L Ch R = 1 ,1502    ,529,529,529
BEGIN DESCRIPTION:
Mapping XS 16b92e05
END DESCRIPTION:
XS GIS Cut Line= 4
       2745079.1      6939752.58      2744167.62      6939309.86
      2744037.41      6939266.45      2743466.37      6939031.36
#Sta/Elev= 30
  3914.5  499.19  4129.2  497.42  4140.7  497.79  4180.3  496.83  4298.6  496.82
  4315.6  495.95  4907.4  493.29  4931.3  492.84  4942.7  491.74  4982.2  492.39
  5013.8     492  5022.4  490.81  5022.6  490.31  5026.1  490.31  5026.4  490.81
  5032.3  492.23  5045.5  493.47    5056  492.88  5109.8  493.17    5117     494
  5131.5  493.83    5141  494.89  5146.4  493.75  5153.1  495.05  5163.9  495.49
  5194.3  494.46  5261.2  494.57  5431.4  496.82  5661.4  497.51  5682.6  498.58
#Mann= 3 ,-1 , 0
  3914.5     .05       0  5022.4     .04       0  5026.4     .05       0
Bank Sta=5022.4,5026.4
XS Rating Curve= 0 ,0
Exp/Cntr=0.3,0.1

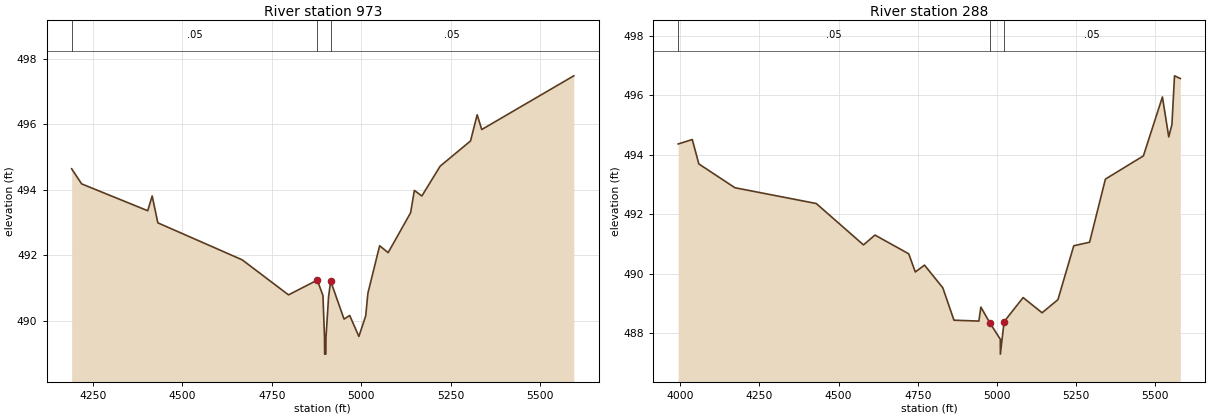
Type RM Length L Ch R = 1 ,973     ,685,685,685
BEGIN DESCRIPTION:
Mapping XS 72bc06c7
END DESCRIPTION:
XS GIS Cut Line= 3
      2744780.18      6939215.78      2744087.48      6938817.34
      2743510.17      6938994.18
#Sta/Elev= 30
  4190.4  494.64  4218.3  494.18  4402.9  493.36  4415.4  493.81  4431.2  492.99
  4666.9  491.86  4796.3  490.79  4876.7  491.24  4892.5  490.77  4896.9  489.48
  4897.2  488.98  4900.7  488.98  4900.9  489.48  4908.3  490.74  4914.1  491.21
  4951.5  490.05  4967.3  490.16  4992.9  489.52    5012  490.15  5018.1  490.84
  5050.9  492.29  5074.7  492.08  5137.5   493.3  5147.9  493.98  5168.9  493.81
  5219.9  494.72  5304.8  495.49  5323.4  496.29  5336.2  495.84  5593.3  497.48
#Mann= 3 ,-1 , 0
  4190.4     .05       0  4876.7     .04       0  4914.1     .05       0
Bank Sta=4876.7,4914.1
XS Rating Curve= 0 ,0
Exp/Cntr=0.3,0.1

Type RM Length L Ch R = 1 ,288     ,0,0,0
BEGIN DESCRIPTION:
Allen T8_3 1.0
END DESCRIPTION:
XS GIS Cut Line= 3
      2744928.48        6939071.      2744308.99       6938277.6
      2743729.46      6938286.23
#Sta/Elev= 30
  3993.4  494.36  4037.9  494.51  4058.7  493.69  4172.7  492.89  4429.6  492.36
  4578.8  490.97  4615.1   491.3  4721.7  490.67  4742.5  490.06  4771.5  490.29
  4829.3  489.53  4864.6  488.44  4943.3  488.41  4949.6  488.88  4978.6  488.34
    5011   487.8  5011.2   487.3    5023  488.39    5083   489.2    5143  488.69
    5193  489.13    5243  490.94    5293  491.06    5343  493.18    5463  493.96
  5523.1  495.94  5543.1   494.6  5553.1  495.01  5561.3  496.65  5579.6  496.56
#Mann= 3 ,-1 , 0
  3993.4     .05       0  4978.6     .04       0    5023     .05       0
Bank Sta=4978.6,5023
XS Rating Curve= 0 ,0
Exp/Cntr=0.3,0.1

Chan Stop Cuts=-1
Use User Specified Reach Order=0
Composite Channel Slope=5