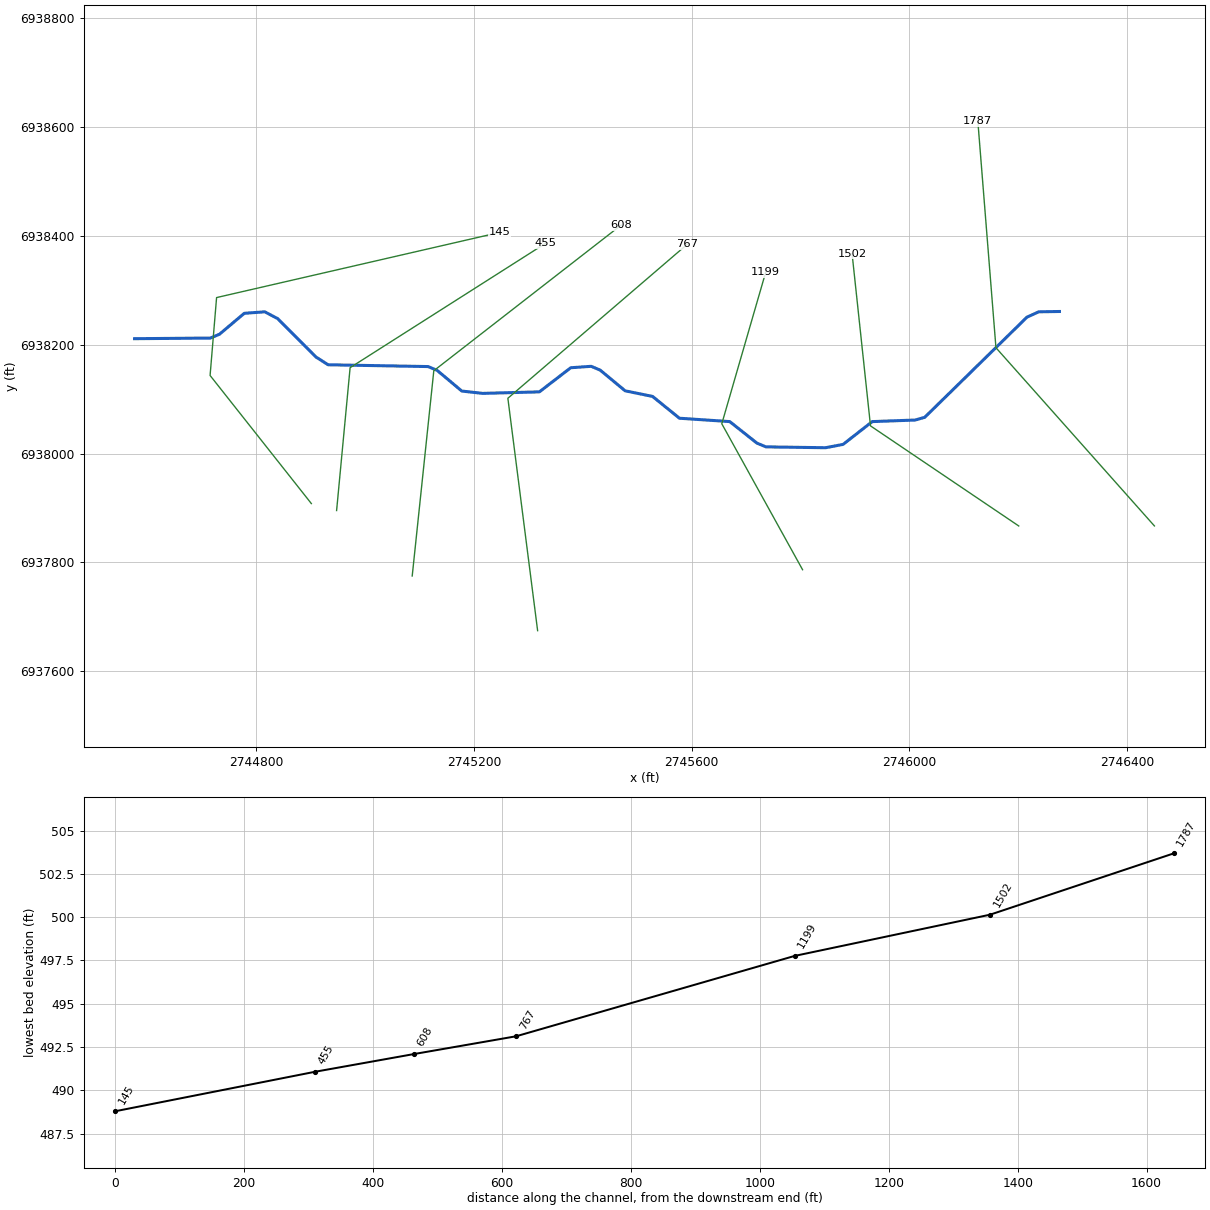
--- Allen T8_4.prj (project) ---

Proj Title=Allen T8_4 Base Level Engineering
Current Plan=p01
Default Exp/Contr=0.3,0.1
English Units
Geom File=g01
Flow File=f01
Plan File=p01
Y Axis Title=Elevation
X Axis Title(PF)=Main Channel Distance
X Axis Title(XS)=Station
BEGIN DESCRIPTION:
Allen T8_4
END DESCRIPTION:
DSS Export Rating Curves= 0
DSS Export Rating Curve Sorted= 0
DSS Export Volume Flow Curves= 0
DXF OffsetX= 0
DXF OffsetY= 0
DXF ScaleX= 1
DXF ScaleY= 10

--- Allen T8_4.p01 (plan) ---

Plan Title=Multiple Run
Short Identifier=Multiple
Geom File=g01
Flow File=f01
Subcritical Flow
K Sum by GR= 0
Std Step Tol= 0.01
Critical Tol= 0.01
Num of Std Step Trials= 20
Max Error Tol= 0.3
Flow Tol Ratio= 0.001
Split Flow NTrial= 30
Split Flow Tol= 0.02
Split Flow Ratio= 0.02
Log Output Level= 0
Friction Slope Method= 1
Unsteady Friction Slope Method= 2
Unsteady Bridges Friction Slope Method= 1
Parabolic Critical Depth
Global Vel Dist=  1 , 1 , 1
Global Log Level= 0
CheckData=True
Encroach Param= -1, 0, 0, 0
BEGIN DESCRIPTION:
Multiple Run
END DESCRIPTION:

--- Allen T8_4.f01 (steady flow) ---

Flow Title=Multiple
Program Version=4.10
Number of Profiles= 7
Profile Names=10-year,25-year,50-year,1pct_min,100-year,1pct_plu,500-year
River Rch & RM=Allen T8_4,Reach-1         ,1787
     127     154     174      98     196     391     248
Boundary for River Rch & Prof#=Allen T8_4,Reach-1         , 1
Up Type= 0
Dn Type= 3
Dn Slope=0.00732
Boundary for River Rch & Prof#=Allen T8_4,Reach-1         , 2
Up Type= 0
Dn Type= 3
Dn Slope=0.00732
Boundary for River Rch & Prof#=Allen T8_4,Reach-1         , 3
Up Type= 0
Dn Type= 3
Dn Slope=0.00732
Boundary for River Rch & Prof#=Allen T8_4,Reach-1         , 4
Up Type= 0
Dn Type= 3
Dn Slope=0.00732
Boundary for River Rch & Prof#=Allen T8_4,Reach-1         , 5
Up Type= 0
Dn Type= 3
Dn Slope=0.00732
Boundary for River Rch & Prof#=Allen T8_4,Reach-1         , 6
Up Type= 0
Dn Type= 3
Dn Slope=0.00732
Boundary for River Rch & Prof#=Allen T8_4,Reach-1         , 7
Up Type= 0
Dn Type= 3
Dn Slope=0.00732
DSS Import GetInterval= 0
DSS Import GetPeak= 0
DSS Import FillOption= 0

--- Allen T8_4.g01 (geometry) ---

Geom Title=Existing Conditions

River Reach=Allen T8_4,Reach-1
Reach XY= 30
      2746276.00      6938261.00      2746237.84      6938260.41
      2746216.21      6938250.48      2746028.43      6938066.52
      2746010.78      6938061.52      2745931.98      6938058.64
      2745878.33      6938016.74      2745846.13      6938010.61
      2745736.51      6938012.20      2745719.94      6938019.13
      2745670.02      6938058.64      2745577.58      6938064.83
      2745528.18      6938104.89      2745477.72      6938115.22
      2745431.94      6938153.23      2745415.32      6938160.25
      2745377.74      6938157.63      2745320.07      6938113.28
      2745215.83      6938110.50      2745177.57      6938114.77
      2745132.06      6938152.86      2745115.49      6938159.78
      2744931.86      6938163.07      2744909.25      6938177.47
      2744839.20      6938247.85      2744815.38      6938260.40
      2744777.75      6938257.66      2744732.08      6938219.18
      2744715.52      6938212.19      2744576.00      6938211.00

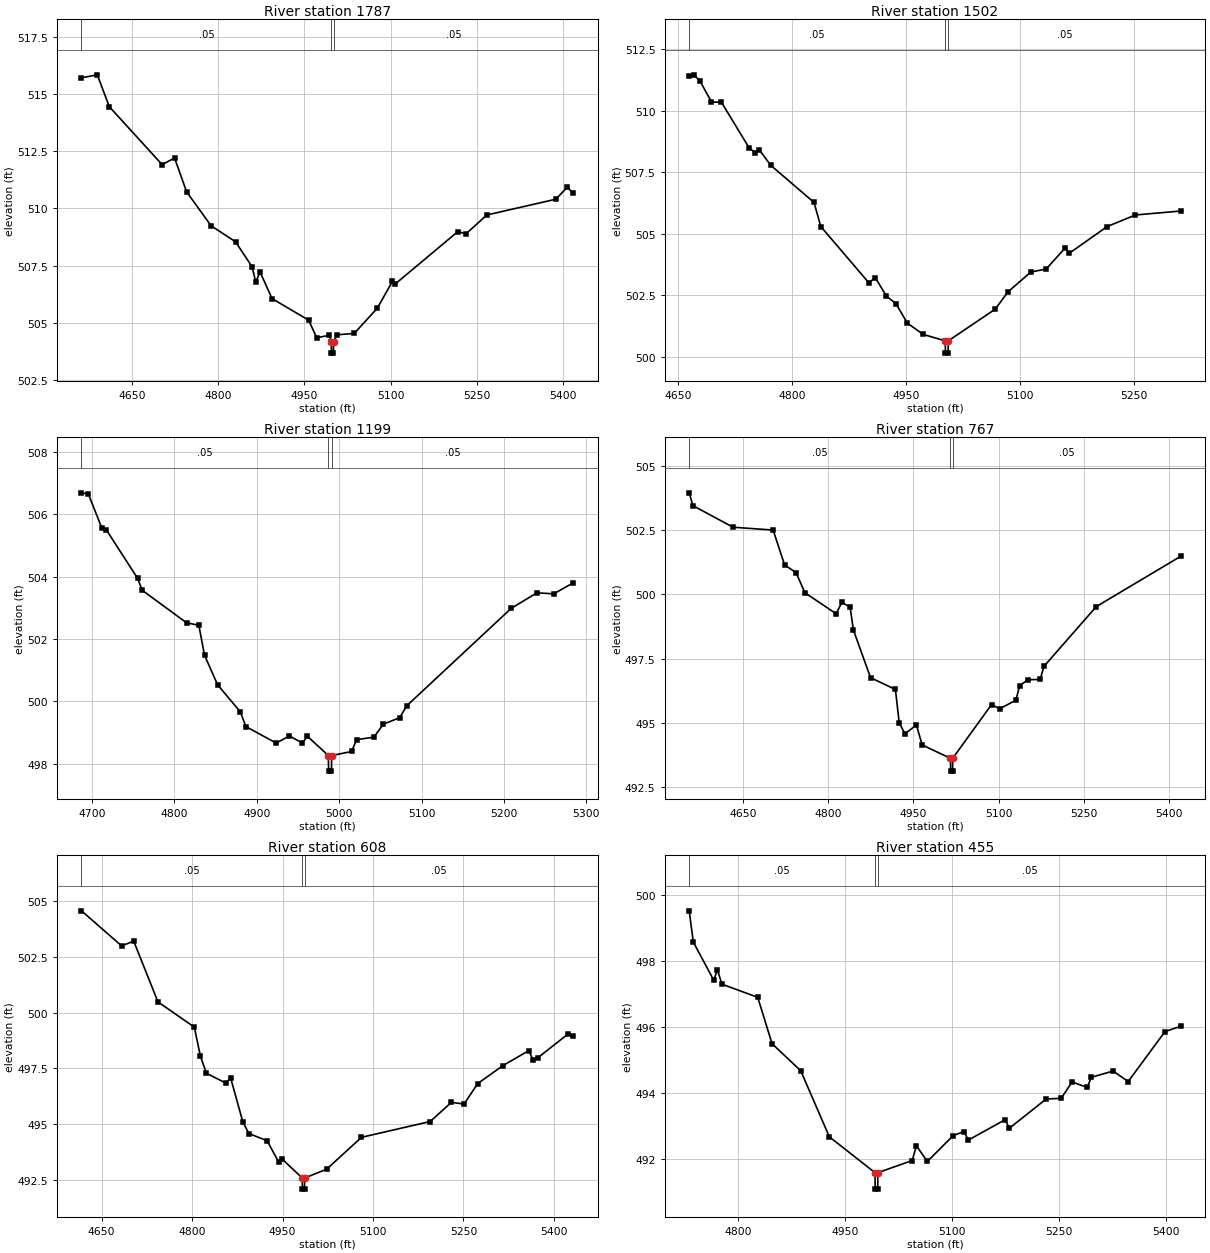
Type RM Length L Ch R = 1,1787,285,285,285
BEGIN DESCRIPTION:
Allen T8_4 2.0
END DESCRIPTION:
XS GIS Cut Line= 3
      2746450.58      6937866.88      2746159.31      6938194.40
      2746126.00      6938610.97
#Sta/Elev= 30
  4561.7  515.70  4589.2  515.83  4610.1  514.44  4702.1  511.91  4723.8  512.20
  4744.8  510.72  4787.4  509.24  4830.0  508.54  4858.5  507.46  4865.2  506.79
  4872.7  507.22  4893.6  506.06  4957.2  505.12  4971.4  504.35  4993.1  504.46
  4996.7  504.18  4997.0  503.68  5000.5  503.68  5000.7  504.18  5006.6  504.48
  5036.7  504.54  5076.8  505.64  5103.1  506.81  5108.1  506.70  5217.3  508.99
  5231.0  508.88  5267.5  509.71  5387.8  510.40  5407.9  510.93  5417.9  510.65
#Mann=3,-1,0
  4561.7    0.05       0  4996.7    0.04       0  5000.7    0.05       0
Bank Sta=4996.7,5000.7
Exp/Cntr=0.3,0.1

Type RM Length L Ch R = 1,1502,303,303,303
BEGIN DESCRIPTION:
Mapping XS 74d83169
END DESCRIPTION:
XS GIS Cut Line= 3
      2746201.20      6937866.83      2745928.74      6938050.77
      2745894.86      6938367.32
#Sta/Elev= 30
  4664.7  511.43  4671.0  511.46  4679.0  511.20  4694.0  510.36  4707.2  510.34
  4743.4  508.50  4751.0  508.30  4757.0  508.41  4772.0  507.78  4829.0  506.27
  4837.9  505.29  4900.9  503.01  4909.8  503.20  4924.3  502.46  4936.9  502.15
  4951.8  501.36  4972.8  500.90  5001.7  500.64  5002.0  500.14  5005.5  500.14
  5005.7  500.64  5067.6  501.93  5084.2  502.63  5114.4  503.44  5134.5  503.56
  5159.9  504.43  5164.9  504.20  5214.9  505.29  5252.1  505.76  5311.8  505.92
#Mann=3,-1,0
  4664.7    0.05       0  5001.7    0.04       0  5005.7    0.05       0
Bank Sta=5001.7,5005.7
Exp/Cntr=0.3,0.1

Type RM Length L Ch R = 1,1199,432,432,432
BEGIN DESCRIPTION:
Mapping XS c210058f
END DESCRIPTION:
XS GIS Cut Line= 3
      2745803.86      6937786.43      2745655.42      6938054.66
      2745736.16      6938333.33
#Sta/Elev= 30
  4687.2  506.69  4695.6  506.65  4711.7  505.57  4717.4  505.50  4755.2  503.95
  4761.0  503.56  4814.7  502.52  4829.6  502.44  4836.5  501.48  4852.4  500.53
  4880.0  499.66  4886.7  499.19  4923.5  498.66  4939.5  498.89  4955.3  498.66
  4961.3  498.88  4986.8  498.26  4987.1  497.76  4990.6  497.76  4990.8  498.26
  5014.9  498.39  5021.2  498.77  5042.0  498.85  5053.7  499.27  5073.2  499.47
  5082.1  499.86  5208.6  502.98  5239.8  503.48  5260.4  503.45  5283.9  503.80
#Mann=3,-1,0
  4687.2    0.05       0  4986.8    0.04       0  4990.8    0.05       0
Bank Sta=4986.8,4990.8
Exp/Cntr=0.3,0.1

Type RM Length L Ch R = 1,767,159,159,159
BEGIN DESCRIPTION:
Mapping XS cd4de4fd
END DESCRIPTION:
XS GIS Cut Line= 3
      2745316.88      6937674.45      2745262.19      6938101.54
      2745591.93      6938384.54
#Sta/Elev= 30
  4555.6  503.96  4562.2  503.46  4632.8  502.62  4703.3  502.51  4723.5  501.15
  4743.7  500.85  4759.1  500.07  4814.2  499.25  4824.3  499.70  4838.8  499.50
  4844.5  498.62  4874.7  496.76  4918.5  496.30  4925.1  495.01  4935.2  494.57
  4955.4  494.92  4965.5  494.14  5015.3  493.62  5015.6  493.12  5019.1  493.12
  5019.3  493.62  5087.6  495.71  5101.9  495.55  5130.4  495.88  5137.0  496.44
  5151.2  496.68  5173.2  496.69  5179.8  497.20  5272.0  499.53  5420.7  501.49
#Mann=3,-1,0
  4555.6    0.05       0  5015.3    0.04       0  5019.3    0.05       0
Bank Sta=5015.3,5019.3
Exp/Cntr=0.3,0.1

Type RM Length L Ch R = 1,608,153,153,153
BEGIN DESCRIPTION:
Mapping XS e18a4bcd
END DESCRIPTION:
XS GIS Cut Line= 3
      2745086.37      6937774.90      2745126.06      6938152.11
      2745470.36      6938419.78
#Sta/Elev= 30
  4616.6  504.56  4683.1  502.99  4703.2  503.20  4743.4  500.48  4803.7  499.35
  4813.8  498.05  4823.8  497.28  4855.5  496.85  4864.1  497.06  4884.2  495.10
  4894.2  494.58  4924.4  494.26  4943.5  493.31  4948.5  493.46  4982.7  492.59
  4983.0  492.09  4986.5  492.09  4986.7  492.59  5023.0  492.98  5080.9  494.41
  5194.9  495.12  5230.2  495.98  5251.1  495.90  5273.7  496.82  5315.3  497.62
  5358.7  498.30  5365.1  497.88  5373.2  497.97  5423.0  499.03  5432.0  498.94
#Mann=3,-1,0
  4616.6    0.05       0  4982.7    0.04       0  4986.7    0.05       0
Bank Sta=4982.7,4986.7
Exp/Cntr=0.3,0.1

Type RM Length L Ch R = 1,455,310,310,310
BEGIN DESCRIPTION:
Mapping XS f9401f3a
END DESCRIPTION:
XS GIS Cut Line= 3
      2744947.41      6937895.21      2744972.22      6938157.72
      2745331.91      6938386.58
#Sta/Elev= 30
  4731.0  499.53  4736.8  498.58  4765.5  497.42  4770.6  497.74  4777.0  497.30
  4827.2  496.90  4847.3  495.49  4887.5  494.67  4927.7  492.66  4991.8  491.57
  4992.1  491.07  4995.6  491.07  4995.8  491.57  5044.0  491.94  5049.9  492.39
  5065.2  491.91  5101.6  492.70  5116.8  492.82  5122.7  492.56  5174.4  493.18
  5180.3  492.92  5232.0  493.81  5253.1  493.83  5268.4  494.33  5289.5  494.16
  5295.5  494.47  5325.9  494.66  5347.1  494.34  5398.8  495.86  5421.0  496.02
#Mann=3,-1,0
  4731.0    0.05       0  4991.8    0.04       0  4995.8    0.05       0
Bank Sta=4991.8,4995.8
Exp/Cntr=0.3,0.1

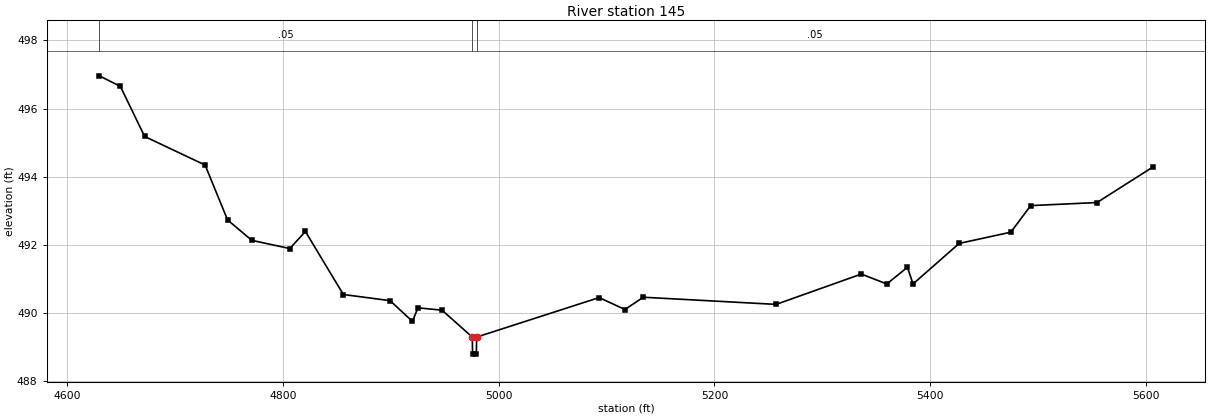
Type RM Length L Ch R = 1,145,0,0,0
BEGIN DESCRIPTION:
Allen T8_4 1.0
END DESCRIPTION:
XS GIS Cut Line= 4
      2744901.00      6937908.00      2744714.87      6938143.42
      2744726.81      6938286.58      2745246.36      6938406.19
#Sta/Elev= 30
  4629.6  496.96  4649.1  496.65  4671.6  495.18  4727.7  494.34  4748.5  492.73
  4771.0  492.13  4806.2  491.89  4820.7  492.39  4855.9  490.54  4899.2  490.36
  4920.0  489.75  4925.0  490.15  4947.4  490.08  4975.5  489.29  4975.7  488.79
  4979.2  488.79  4979.5  489.29  5093.1  490.45  5117.0  490.10  5134.1  490.46
  5257.2  490.25  5336.2  491.14  5359.9  490.85  5379.0  491.34  5384.2  490.85
  5427.0  492.04  5474.9  492.37  5493.3  493.15  5554.8  493.24  5606.5  494.28
#Mann=3,-1,0
  4629.6    0.05       0  4975.5    0.04       0  4979.5    0.05       0
Bank Sta=4975.5,4979.5
Exp/Cntr=0.3,0.1

Chan Stop Cuts=-1