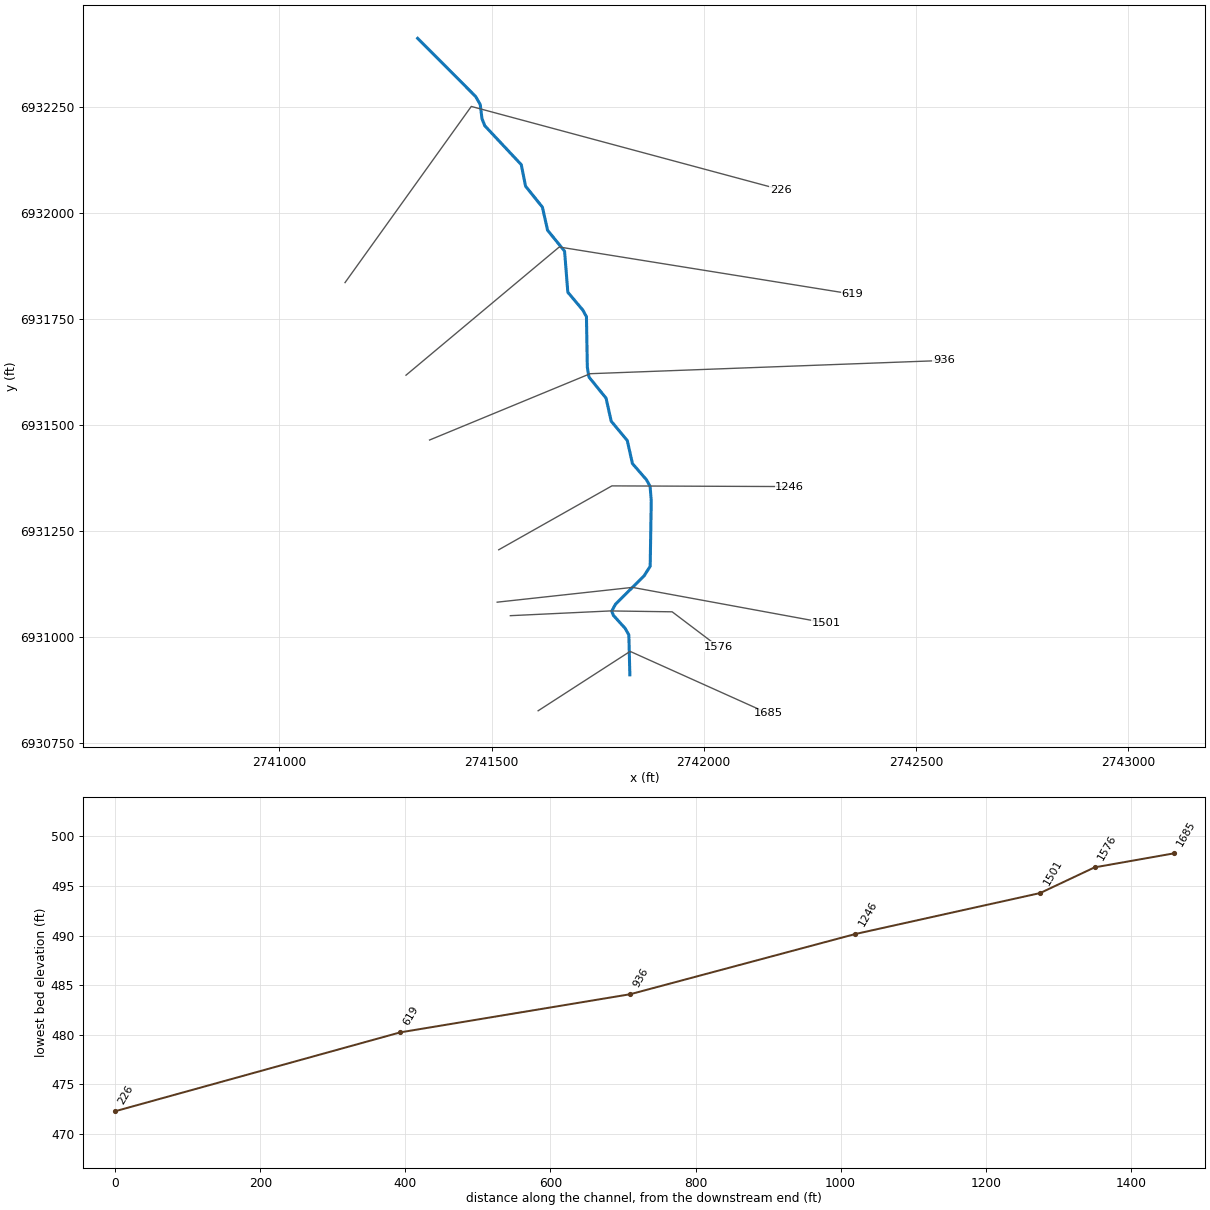
--- Allen T9.prj (project) ---

Proj Title=Allen T9 Base Level Engineering
Current Plan=p01
Default Exp/Contr=0.3,0.1
English Units
Geom File=g01
Flow File=f01
Plan File=p01
BEGIN DESCRIPTION:
Allen T9
END DESCRIPTION:

--- Allen T9.p01 (plan) ---

Plan Title=Multiple Run
Short Identifier=Multiple
Geom File=g01
Flow File=f01
Subcritical Flow
K Sum by GR= 0
Std Step Tol= 0.01
Critical Tol= 0.01
Num of Std Step Trials= 20
Max Error Tol= 0.3
Flow Tol Ratio= 0.001
Split Flow NTrial= 30
Split Flow Tol= 0.02
Split Flow Ratio= 0.02
Log Output Level= 0
Friction Slope Method= 1
Unsteady Friction Slope Method= 2
Unsteady Bridges Friction Slope Method= 1
Parabolic Critical Depth
Global Vel Dist=  1 , 1 , 1
Global Log Level= 0
CheckData=True
Encroach Param= -1, 0, 0, 0
BEGIN DESCRIPTION:
Multiple Run
END DESCRIPTION:

--- Allen T9.f01 (steady flow) ---

Flow Title=Multiple
Number of Profiles=7
Profile Names=10-year,25-year,50-year,1pct_min,100-year,1pct_plu,500-year
River Rch & RM= Allen T9,Reach-1,1685
      83      97     108      60     119     238     145
Boundary for River Rch & Prof#=Allen T9,Reach-1,1
Up Type=0
Dn Type=3
Dn Slope=0.005
Boundary for River Rch & Prof#=Allen T9,Reach-1,2
Up Type=0
Dn Type=3
Dn Slope=0.005
Boundary for River Rch & Prof#=Allen T9,Reach-1,3
Up Type=0
Dn Type=3
Dn Slope=0.005
Boundary for River Rch & Prof#=Allen T9,Reach-1,4
Up Type=0
Dn Type=3
Dn Slope=0.005
Boundary for River Rch & Prof#=Allen T9,Reach-1,5
Up Type=0
Dn Type=3
Dn Slope=0.005
Boundary for River Rch & Prof#=Allen T9,Reach-1,6
Up Type=0
Dn Type=3
Dn Slope=0.005
Boundary for River Rch & Prof#=Allen T9,Reach-1,7
Up Type=0
Dn Type=3
Dn Slope=0.005

--- Allen T9.g01 (geometry) ---

Geom Title=Existing Conditions

River Reach=Allen T9,Reach-1
Reach XY= 30
      2741826.00      6930911.00      2741823.65      6931005.23
      2741814.72      6931020.82      2741787.25      6931051.15
      2741783.28      6931061.09      2741792.32      6931077.69
      2741859.50      6931144.24      2741873.93      6931166.85
      2741876.46      6931321.19      2741873.76      6931355.07
      2741865.20      6931370.67      2741832.12      6931408.82
      2741819.92      6931463.20      2741782.08      6931508.80
      2741769.88      6931563.18      2741729.76      6931612.56
      2741725.81      6931635.92      2741723.73      6931755.06
      2741715.15      6931770.65      2741679.86      6931812.60
      2741672.17      6931909.42      2741632.12      6931958.82
      2741619.92      6932013.20      2741580.19      6932062.74
      2741570.15      6932113.29      2741484.18      6932204.96
      2741477.55      6932221.64      2741473.47      6932254.95
      2741462.38      6932274.21      2741326.00      6932411.00

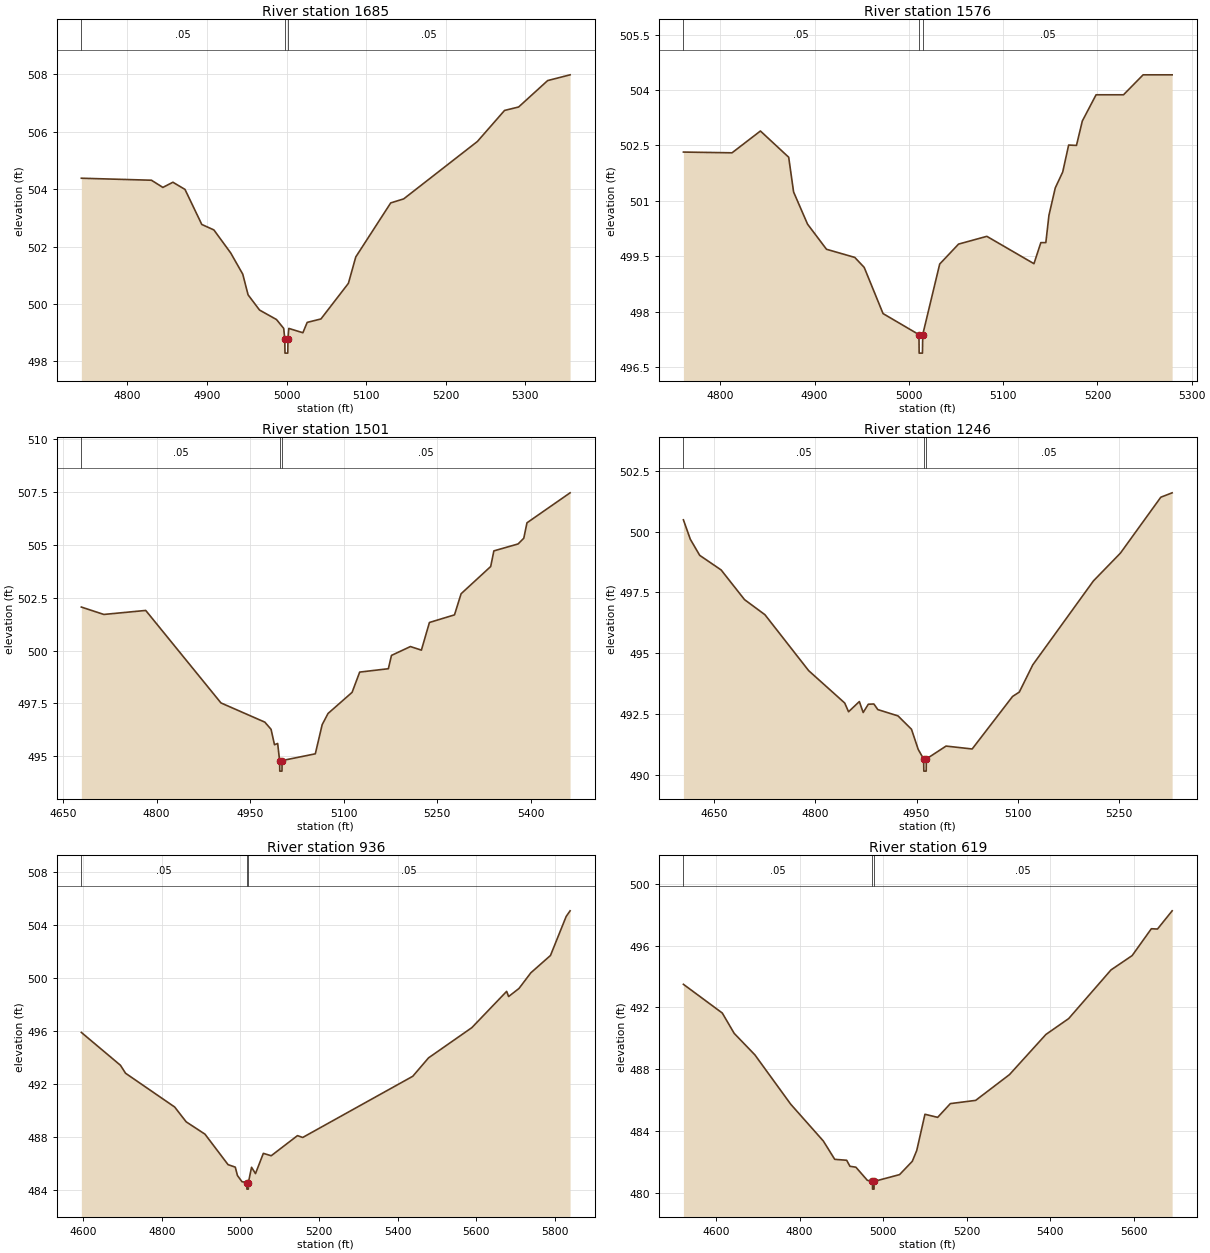
Type RM Length L Ch R = 1,1685,109,109,109
BEGIN DESCRIPTION:
Allen T9 3.0
END DESCRIPTION:
XS GIS Cut Line= 3
      2741609.89      6930826.37      2741826.64      6930966.31
      2742151.72      6930820.22
#Sta/Elev= 30
  4742.0  504.38  4830.1  504.31  4844.5  504.06  4857.1  504.24  4872.3  503.99
  4893.4  502.77  4908.6  502.58  4929.7  501.78  4944.9  501.04  4951.6  500.32
  4966.0  499.79  4987.3  499.46  4996.4  499.15  4997.7  498.79  4998.0  498.29
  5001.5  498.29  5001.7  498.79  5002.8  499.15  5020.5  499.00  5025.9  499.36
  5043.2  499.48  5077.7  500.72  5087.0  501.64  5130.9  503.52  5147.2  503.66
  5239.9  505.66  5274.0  506.74  5291.7  506.86  5328.2  507.78  5356.4  507.98
#Mann=3,-1,0
  4742.0    0.05       0  4997.7   0.035       0  5001.7    0.05       0
Bank Sta=4997.7,5001.7
Exp/Cntr=0.3,0.1

Type RM Length L Ch R = 1,1576,75,75,75
BEGIN DESCRIPTION:
Mapping XS 210d59ca
END DESCRIPTION:
XS GIS Cut Line= 4
      2741544.41      6931050.45      2741779.73      6931061.62
      2741925.70      6931059.57      2742034.92      6930976.97
#Sta/Elev= 30
  4760.8  502.32  4812.4  502.30  4842.5  502.89  4872.5  502.18  4877.7  501.24
  4892.5  500.37  4912.6  499.69  4942.6  499.47  4952.6  499.20  4972.6  497.95
  5010.7  497.38  5010.9  496.88  5014.4  496.88  5014.7  497.38  5032.7  499.29
  5052.7  499.83  5082.7  500.04  5132.7  499.30  5140.0  499.87  5145.3  499.87
  5148.6  500.61  5155.3  501.35  5163.2  501.78  5169.5  502.51  5177.8  502.50
  5184.0  503.16  5198.6  503.87  5227.7  503.87  5248.5  504.41  5279.3  504.41
#Mann=3,-1,0
  4760.8    0.05       0  5010.7   0.035       0  5014.7    0.05       0
Bank Sta=5010.7,5014.7
Exp/Cntr=0.3,0.1

Type RM Length L Ch R = 1,1501,255,255,255
BEGIN DESCRIPTION:
Mapping XS b7fb50e3
END DESCRIPTION:
XS GIS Cut Line= 3
      2741513.36      6931082.28      2741832.16      6931117.12
      2742288.01      6931033.28
#Sta/Elev= 30
  4679.3  502.06  4715.4  501.71  4782.6  501.90  4903.3  497.52  4973.7  496.61
  4983.7  496.27  4989.2  495.54  4994.3  495.60  4997.4  494.79  4997.7  494.29
  5001.2  494.29  5001.4  494.79  5054.7  495.11  5065.7  496.49  5075.1  497.02
  5113.7  498.02  5125.9  498.98  5171.9  499.14  5176.9  499.77  5207.3  500.19
  5224.9  500.02  5237.8  501.33  5278.0  501.69  5288.6  502.69  5336.1  503.98
  5341.2  504.72  5380.1  505.05  5389.2  505.32  5394.3  506.05  5463.5  507.47
#Mann=3,-1,0
  4679.3    0.05       0  4997.4   0.035       0  5001.4    0.05       0
Bank Sta=4997.4,5001.4
Exp/Cntr=0.3,0.1

Type RM Length L Ch R = 1,1246,310,310,310
BEGIN DESCRIPTION:
Mapping XS f85371ff
END DESCRIPTION:
XS GIS Cut Line= 3
      2741517.01      6931205.77      2741783.67      6931356.31
      2742202.75      6931354.70
#Sta/Elev= 30
  4604.0  500.48  4614.3  499.68  4628.2  499.02  4660.0  498.42  4694.7  497.20
  4725.0  496.58  4789.9  494.28  4843.4  492.95  4849.1  492.59  4865.1  493.01
  4870.8  492.56  4878.4  492.90  4886.7  492.91  4892.5  492.68  4922.5  492.42
  4942.5  491.87  4952.5  491.04  4960.5  490.65  4960.8  490.15  4964.3  490.15
  4964.5  490.65  4993.8  491.18  5032.5  491.06  5092.5  493.22  5102.5  493.40
  5122.5  494.52  5212.5  497.97  5252.5  499.11  5312.5  501.41  5329.3  501.59
#Mann=3,-1,0
  4604.0    0.05       0  4960.5   0.035       0  4964.5    0.05       0
Bank Sta=4960.5,4964.5
Exp/Cntr=0.3,0.1

Type RM Length L Ch R = 1,936,317,317,317
BEGIN DESCRIPTION:
Mapping XS fb7dcbfe
END DESCRIPTION:
XS GIS Cut Line= 3
      2741354.04      6931464.41      2741732.54      6931620.67
      2742565.87      6931651.92
#Sta/Elev= 30
  4595.6  495.91  4695.1  493.43  4708.0  492.83  4833.0  490.28  4862.3  489.16
  4910.1  488.23  4968.8  485.93  4987.2  485.74  4992.7  485.11  5004.2  484.64
  5016.6  484.58  5016.8  484.08  5020.3  484.08  5020.6  484.58  5028.6  485.73
  5038.6  485.25  5058.6  486.78  5078.6  486.60  5145.5  488.12  5158.7  487.98
  5438.8  492.60  5478.9  493.99  5589.0  496.27  5677.6  499.01  5682.6  498.62
  5709.0  499.23  5739.1  500.41  5789.1  501.72  5829.1  504.67  5839.0  505.09
#Mann=3,-1,0
  4595.6    0.05       0  5016.6    0.04       0  5020.6    0.05       0
Bank Sta=5016.6,5020.6
Exp/Cntr=0.3,0.1

Type RM Length L Ch R = 1,619,393,393,393
BEGIN DESCRIPTION:
Mapping XS f6197eda
END DESCRIPTION:
XS GIS Cut Line= 3
      2741298.49      6931617.17      2741659.62      6931919.28
      2742350.61      6931808.16
#Sta/Elev= 30
  4521.6  493.50  4614.7  491.64  4643.3  490.32  4692.8  488.93  4778.7  485.73
  4856.7  483.35  4884.1  482.16  4912.7  482.10  4920.5  481.71  4934.8  481.65
  4962.2  480.80  4974.5  480.73  4974.7  480.23  4978.2  480.23  4978.5  480.73
  5039.4  481.17  5069.8  482.03  5080.5  482.73  5100.2  485.08  5130.6  484.88
  5161.0  485.77  5221.7  485.98  5302.7  487.65  5389.9  490.25  5444.5  491.28
  5545.8  494.43  5596.5  495.36  5642.5  497.10  5657.2  497.08  5692.3  498.26
#Mann=3,-1,0
  4521.6    0.05       0  4974.5    0.04       0  4978.5    0.05       0
Bank Sta=4974.5,4978.5
Exp/Cntr=0.3,0.1

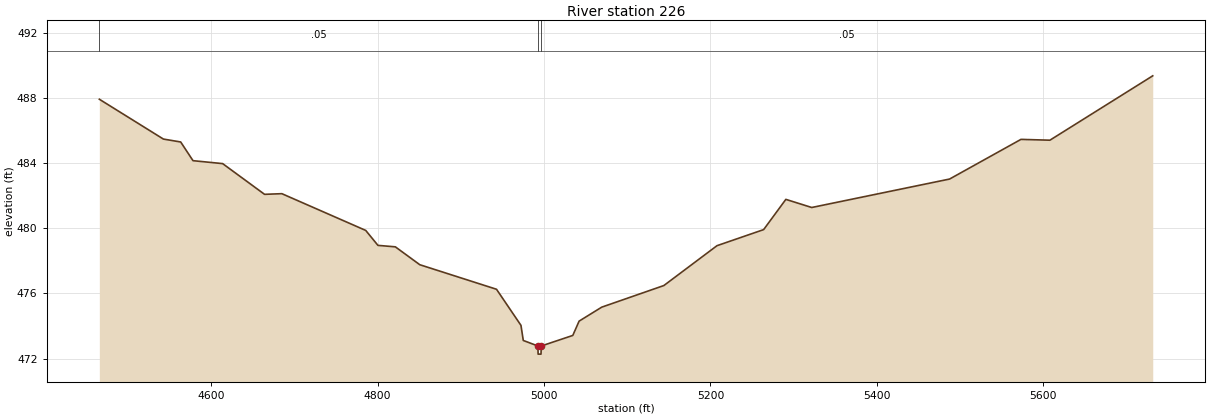
Type RM Length L Ch R = 1,226,0,0,0
BEGIN DESCRIPTION:
Allen T9 1.0
END DESCRIPTION:
XS GIS Cut Line= 3
      2741154.80      6931835.35      2741452.35      6932250.53
      2742181.82      6932054.27
#Sta/Elev= 30
  4465.5  487.95  4542.5  485.50  4563.3  485.32  4578.1  484.17  4613.7  483.99
  4664.1  482.10  4684.9  482.14  4785.7  479.88  4800.4  478.96  4821.3  478.87
  4850.7  477.77  4942.9  476.26  4972.3  474.04  4975.1  473.11  4992.7  472.77
  4992.9  472.27  4996.4  472.27  4996.7  472.77  5034.6  473.42  5042.2  474.30
  5069.4  475.16  5144.1  476.49  5207.9  478.94  5264.0  479.93  5290.7  481.79
  5321.8  481.29  5487.5  483.04  5573.3  485.48  5608.1  485.43  5731.7  489.39
#Mann=3,-1,0
  4465.5    0.05       0  4992.7   0.035       0  4996.7    0.05       0
Bank Sta=4992.7,4996.7
Exp/Cntr=0.3,0.1

Chan Stop Cuts=-1