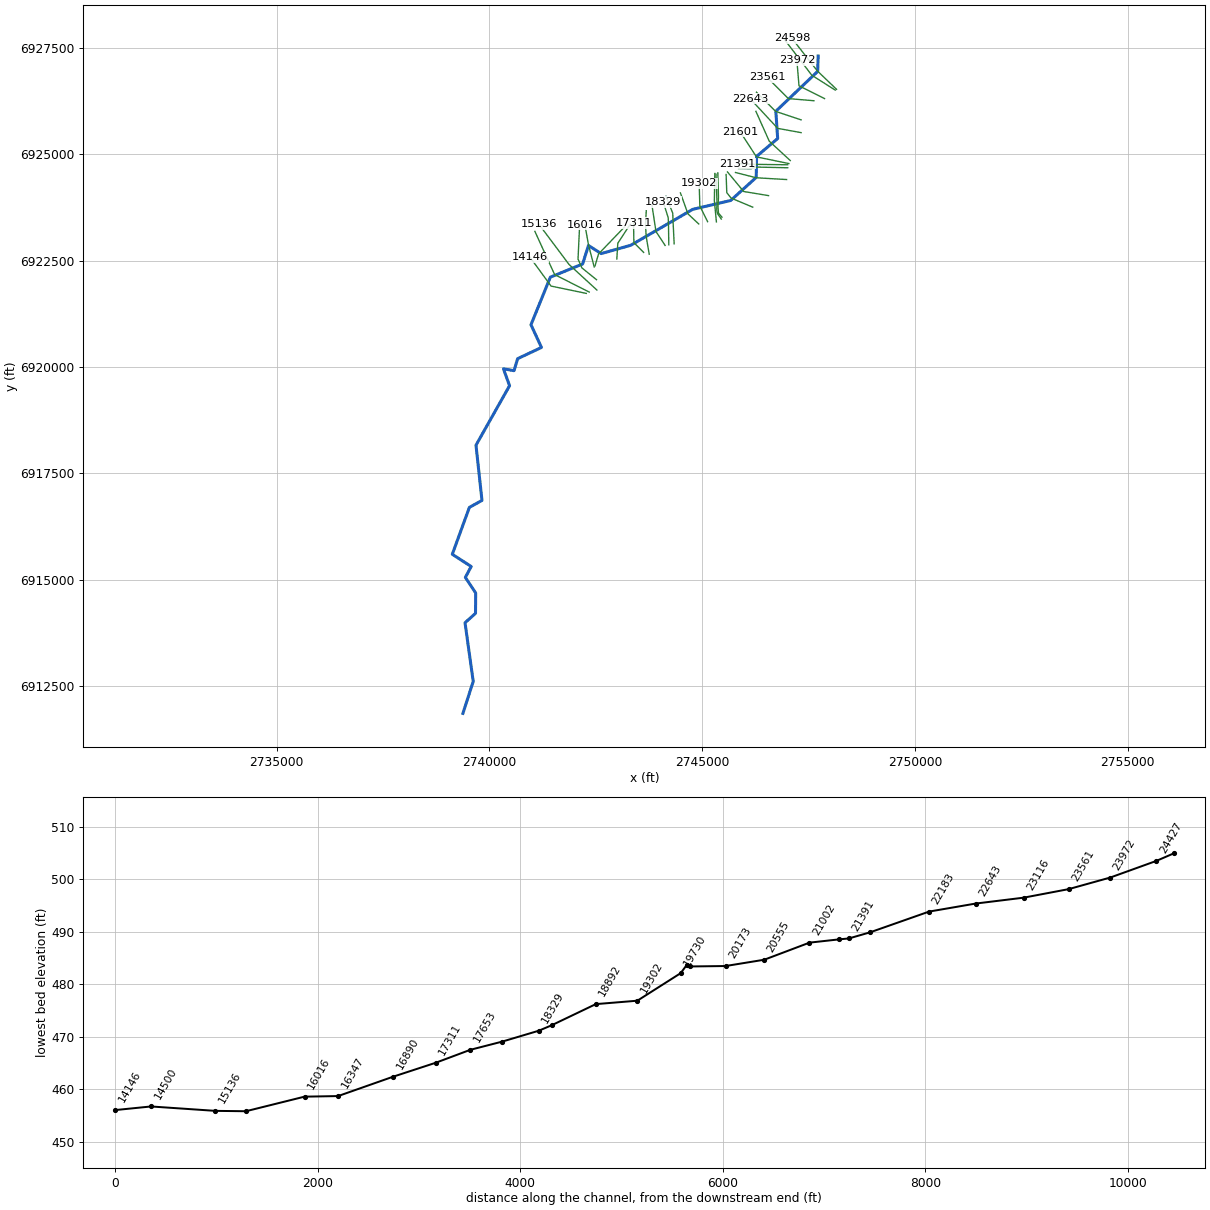
--- Andy Branch.prj (project) ---

Proj Title=Andy Branch Base Level Engineering
Current Plan=p01
Default Exp/Contr=0.3,0.1
English Units
Geom File=g01
Flow File=f01
Plan File=p01
Y Axis Title=Elevation
X Axis Title(PF)=Main Channel Distance
X Axis Title(XS)=Station
BEGIN DESCRIPTION:
Andy Branch
END DESCRIPTION:
DSS Export Rating Curves= 0
DSS Export Rating Curve Sorted= 0
DSS Export Volume Flow Curves= 0
DXF OffsetX= 0
DXF OffsetY= 0
DXF ScaleX= 1
DXF ScaleY= 10

--- Andy Branch.p01 (plan) ---

Plan Title=Multiple Run
Short Identifier=Multiple
Geom File=g01
Flow File=f01
Subcritical Flow
K Sum by GR= 0
Std Step Tol= 0.01
Critical Tol= 0.01
Num of Std Step Trials= 20
Max Error Tol= 0.3
Flow Tol Ratio= 0.001
Split Flow NTrial= 30
Split Flow Tol= 0.02
Split Flow Ratio= 0.02
Log Output Level= 0
Friction Slope Method= 1
Unsteady Friction Slope Method= 2
Unsteady Bridges Friction Slope Method= 1
Parabolic Critical Depth
Global Vel Dist=  1 , 1 , 1
Global Log Level= 0
CheckData=True
Encroach Param= -1, 0, 0, 0
BEGIN DESCRIPTION:
Multiple Run
END DESCRIPTION:

--- Andy Branch.f01 (steady flow) ---

Flow Title=Multiple
Program Version=4.10
Number of Profiles= 7
Profile Names=10-year,25-year,50-year,1pct_min,100-year,1pct_plu,500-year
River Rch & RM=Andy Branch,Reach-1         ,24598
     456     601     717     425     849    1694    1191
River Rch & RM=Andy Branch,Reach-1         ,16016
     785    1067    1299     785    1566    3125    2282
River Rch & RM=Andy Branch,Reach-1         ,15136
     872    1191    1455     882    1759    3510    2578
River Rch & RM=Andy Branch,Reach-1         ,13626
    1008    1383    1693    1028    2051    4092    3017
River Rch & RM=Andy Branch,Reach-1         ,7449
    1090    1497    1833    1113    2221    4431    3268
Boundary for River Rch & Prof#=Andy Branch,Reach-1         , 1
Up Type= 0
Dn Type= 3
Dn Slope=0.005
Boundary for River Rch & Prof#=Andy Branch,Reach-1         , 2
Up Type= 0
Dn Type= 3
Dn Slope=0.005
Boundary for River Rch & Prof#=Andy Branch,Reach-1         , 3
Up Type= 0
Dn Type= 3
Dn Slope=0.005
Boundary for River Rch & Prof#=Andy Branch,Reach-1         , 4
Up Type= 0
Dn Type= 3
Dn Slope=0.005
Boundary for River Rch & Prof#=Andy Branch,Reach-1         , 5
Up Type= 0
Dn Type= 3
Dn Slope=0.005
Boundary for River Rch & Prof#=Andy Branch,Reach-1         , 6
Up Type= 0
Dn Type= 3
Dn Slope=0.005
Boundary for River Rch & Prof#=Andy Branch,Reach-1         , 7
Up Type= 0
Dn Type= 3
Dn Slope=0.005
DSS Import GetInterval= 0
DSS Import GetPeak= 0
DSS Import FillOption= 0

--- Andy Branch.g01 (geometry) ---

Geom Title=Existing Conditions
Program Version=4.10

River Reach=Andy Branch     ,Reach-1
Reach XY= 30
        2747726.        6927311.      2747715.53      6926951.18
      2746731.45      6926013.46      2746774.52      6925372.49
      2746279.16      6924952.68       2746270.2      6924458.71
      2745670.59      6923916.17      2744777.64      6923707.86
      2743320.14      6922863.06      2742625.91      6922668.19
      2742327.63      6922857.91      2742189.81      6922424.22
      2741431.35       6922113.7      2740976.12      6920995.24
      2741222.57      6920462.22      2740662.19      6920197.77
      2740578.21      6919915.82      2740329.33      6919959.31
      2740472.69      6919562.73      2739683.73      6918164.65
      2739824.51      6916866.91      2739528.84      6916702.99
      2739126.53      6915600.31      2739570.91       6915313.3
      2739433.53      6915057.43      2739676.58      6914690.58
      2739672.47      6914212.47      2739426.04      6913990.81
      2739618.72       6912610.9        2739376.        6911861.

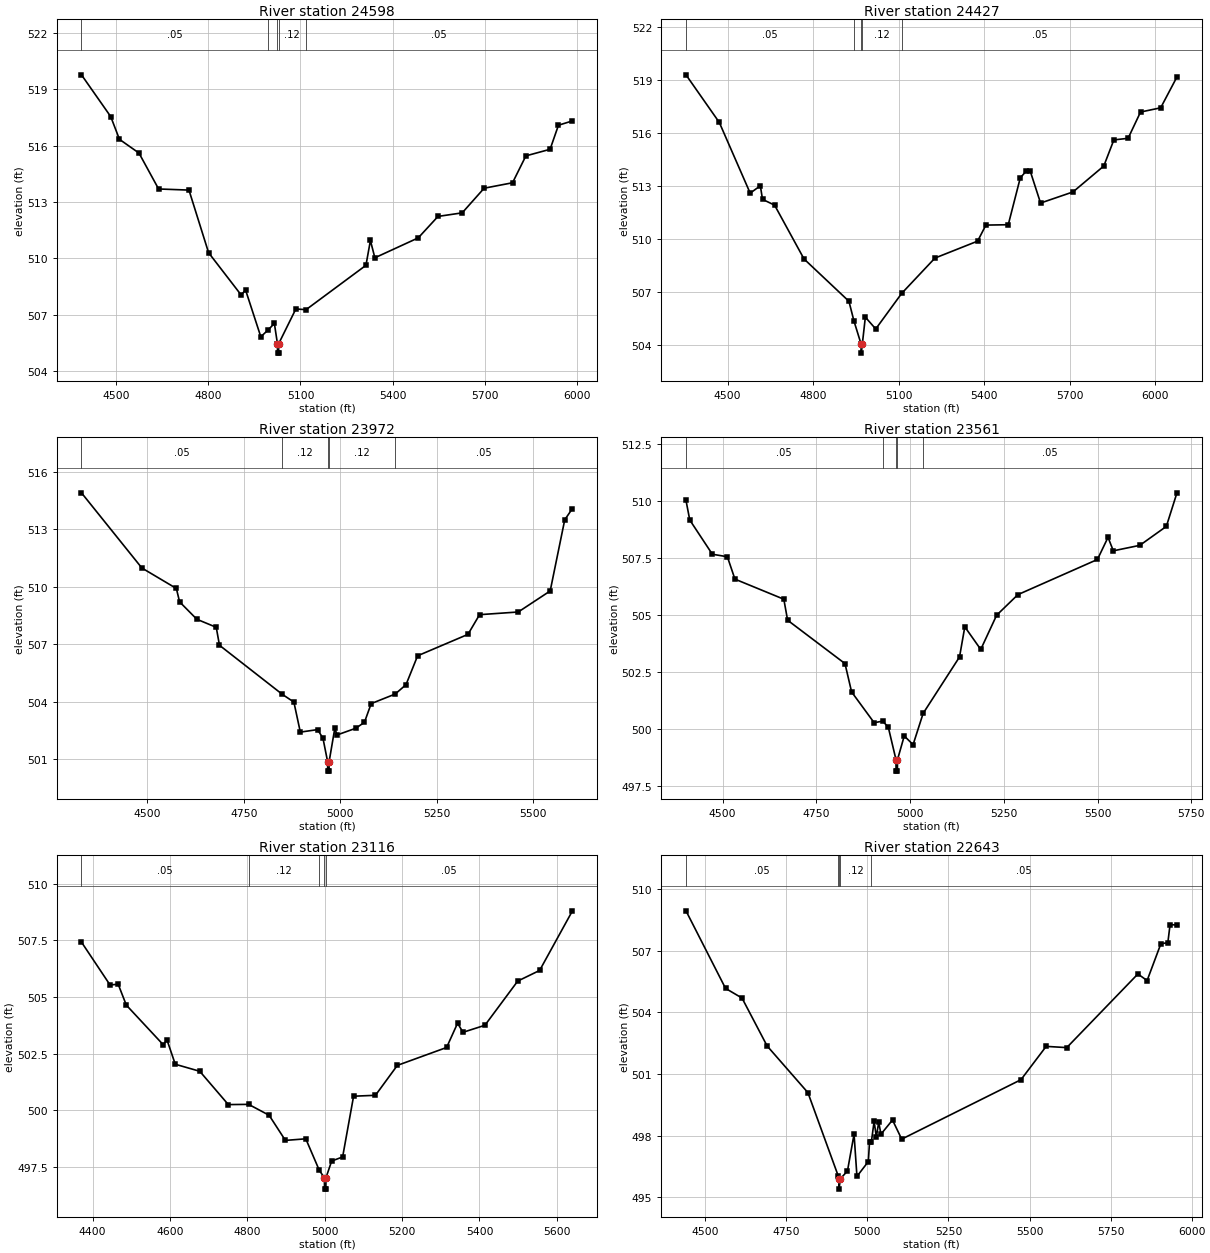
Type RM Length L Ch R = 1 ,24598   ,171,171,171
BEGIN DESCRIPTION:
Andy Branch 44.0
END DESCRIPTION:
XS GIS Cut Line= 3
      2748158.39      6926528.91      2747708.01      6926960.49
      2747109.54      6927727.44
#Sta/Elev= 30
  4387.9  519.76    4483  517.54  4511.4  516.33  4574.9   515.6  4638.7  513.69
  4737.5  513.63  4801.3   510.3  4907.3  508.05  4921.5  508.32  4971.1  505.83
  4995.3   506.2  5015.2  506.54  5025.2  505.46  5025.5  504.96    5029  504.96
  5029.2  505.46  5085.1  507.31  5118.2  507.27    5313  509.63  5327.5  510.95
    5342  510.03  5483.1  511.09  5547.3  512.23    5626  512.42  5697.3  513.73
  5789.7  514.02  5833.1  515.45  5911.8   515.8    5939  517.08  5984.5  517.31
#Mann= 5 ,-1 , 0
  4387.9     .05       0  4995.3     .12       0  5025.2     .07       0
  5029.2     .12       0  5118.2     .05       0
Bank Sta=5025.2,5029.2
XS Rating Curve= 0 ,0
Exp/Cntr=0.3,0.1

Type RM Length L Ch R = 1 ,24427   ,455,455,455
BEGIN DESCRIPTION:
Andy Branch 43.0
END DESCRIPTION:
XS GIS Cut Line= 3
      2748126.03      6926510.98        2747576.        6926861.
        2746926.        6927711.
#Sta/Elev= 30
  4354.1  519.31    4471  516.61  4579.3   512.6  4614.9  513.02  4622.5  512.25
  4664.9  511.92  4768.1  508.87  4925.6  506.47  4943.1  505.36  4968.5  504.03
  4968.7  503.53  4972.5  504.03  4983.2  505.57  5019.6   504.9  5110.8  506.92
  5227.3  508.92  5376.9  509.88    5406  510.79  5484.4  510.81  5526.6  513.47
  5547.4  513.85  5561.9  513.83  5597.7  512.04  5711.5  512.67  5819.5  514.14
  5854.8  515.62  5904.7  515.71  5948.3   517.2    6019  517.44  6076.1  519.19
#Mann= 5 ,-1 , 0
  4354.1     .05       0  4943.1     .12       0  4968.5     .07       0
  4972.5     .12       0  5110.8     .05       0
Bank Sta=4968.5,4972.5
XS Rating Curve= 0 ,0
Exp/Cntr=0.3,0.1

Type RM Length L Ch R = 1 ,23972   ,411,411,411
BEGIN DESCRIPTION:
Andy Branch 42.0
END DESCRIPTION:
XS GIS Cut Line= 3
      2747876.03      6926310.99        2747276.        6926611.
        2747226.      6927210.97
#Sta/Elev= 30
  4328.9  514.91  4485.5  510.98  4574.9  509.91  4583.3  509.21    4628   508.3
  4678.3  507.88  4686.7  506.94  4849.9  504.37  4879.6  503.97  4896.3   502.4
  4941.1  502.53    4955  502.08    4967  500.86  4967.3  500.36  4970.8  500.36
    4971  500.86  4985.8  502.61  4991.4  502.25  5039.9   502.6  5062.5  502.91
    5080  503.89  5142.3  504.39  5170.3  504.88  5200.4  506.39  5330.9  507.51
    5361  508.54  5461.3  508.68  5544.1  509.78  5581.8   513.5  5601.8  514.09
#Mann= 5 ,-1 , 0
  4328.9     .05       0  4849.9     .12       0    4967     .07       0
    4971     .12       0  5142.3     .05       0
Bank Sta=4967,4971
XS Rating Curve= 0 ,0
Exp/Cntr=0.3,0.1

Type RM Length L Ch R = 1 ,23561   ,445,445,445
BEGIN DESCRIPTION:
Andy Branch 41.0
END DESCRIPTION:
XS GIS Cut Line= 3
      2747626.03        6926261.        2747026.        6926311.
      2746526.01      6926810.99
#Sta/Elev= 30
  4402.5  510.01  4412.6  509.15  4472.8  507.65  4512.9  507.54    4533  506.56
  4663.4  505.68  4673.5  504.76  4826.5  502.86  4844.1  501.62  4904.3  500.27
  4926.7  500.34  4941.9  500.08  4962.5  498.65  4962.7  498.15  4966.2  498.15
  4966.5  498.65  4984.5  499.69  5008.1  499.31  5034.9  500.68  5131.9  503.15
    5146  504.47  5188.5  503.48  5230.9  504.98  5287.5  505.88  5499.6  507.42
  5527.9  508.39    5542   507.8  5612.7  508.04  5683.4  508.87  5711.7  510.34
#Mann= 5 ,-1 , 0
  4402.5     .05       0  4926.7     .12       0  4962.5     .07       0
  4966.5     .12       0  5034.9     .05       0
Bank Sta=4962.5,4966.5
XS Rating Curve= 0 ,0
Exp/Cntr=0.3,0.1

Type RM Length L Ch R = 1 ,23116   ,473,473,473
BEGIN DESCRIPTION:
Andy Branch 40.0
END DESCRIPTION:
XS GIS Cut Line= 3
      2747325.98      6925811.01        2746726.        6926011.
      2746276.03      6926460.97
#Sta/Elev= 30
  4371.4  507.42  4445.2  505.53  4466.3  505.56  4487.3  504.64  4582.2   502.9
  4592.7  503.09  4613.8  502.03  4677.1  501.72  4750.9  500.25  4803.4  500.26
  4856.3  499.78  4898.4  498.67  4951.1  498.74    4986  497.35  4999.2  497.02
  4999.5  496.52    5003  496.52  5003.2  497.02    5018  497.76  5046.3  497.94
  5074.6  500.62  5131.1  500.66  5187.7  501.98    5315  502.77  5343.3  503.84
  5357.4  503.44    5414  503.75  5498.8   505.7  5555.4  506.17  5640.2   508.8
#Mann= 5 ,-1 , 0
  4371.4     .05       0  4803.4     .12       0    4986     .05       0
  4999.2     .04       0  5003.2     .05       0
Bank Sta=4999.2,5003.2
XS Rating Curve= 0 ,0
Exp/Cntr=0.3,0.1

Type RM Length L Ch R = 1 ,22643   ,460,460,460
BEGIN DESCRIPTION:
Andy Branch 39.0
END DESCRIPTION:
XS GIS Cut Line= 3
      2747326.01        6925511.        2746776.        6925611.
      2746125.98      6926311.02
#Sta/Elev= 30
  4440.4  508.93  4562.4  505.16  4613.2  504.69  4690.7  502.36  4816.5  500.09
  4909.8  496.05  4912.3   495.9  4912.6   495.4  4916.3   495.9  4938.4  496.28
  4958.8  498.07  4967.7  496.02  5002.8  496.74  5006.5  497.69  5012.1  497.69
  5020.7   498.7  5027.5  497.93  5034.9  498.66  5041.7  498.07  5077.4  498.76
  5105.7  497.83  5473.6  500.72  5551.3  502.34  5614.8  502.28  5834.2  505.86
  5862.6  505.54  5905.1  507.33  5926.6  507.38  5933.4  508.26  5954.7  508.24
#Mann= 5 ,-1 , 0
  4440.4     .05       0  4909.8     .12       0  4912.3     .07       0
  4916.3     .12       0  5012.1     .05       0
Bank Sta=4912.3,4916.3
XS Rating Curve= 0 ,0
Exp/Cntr=0.3,0.1

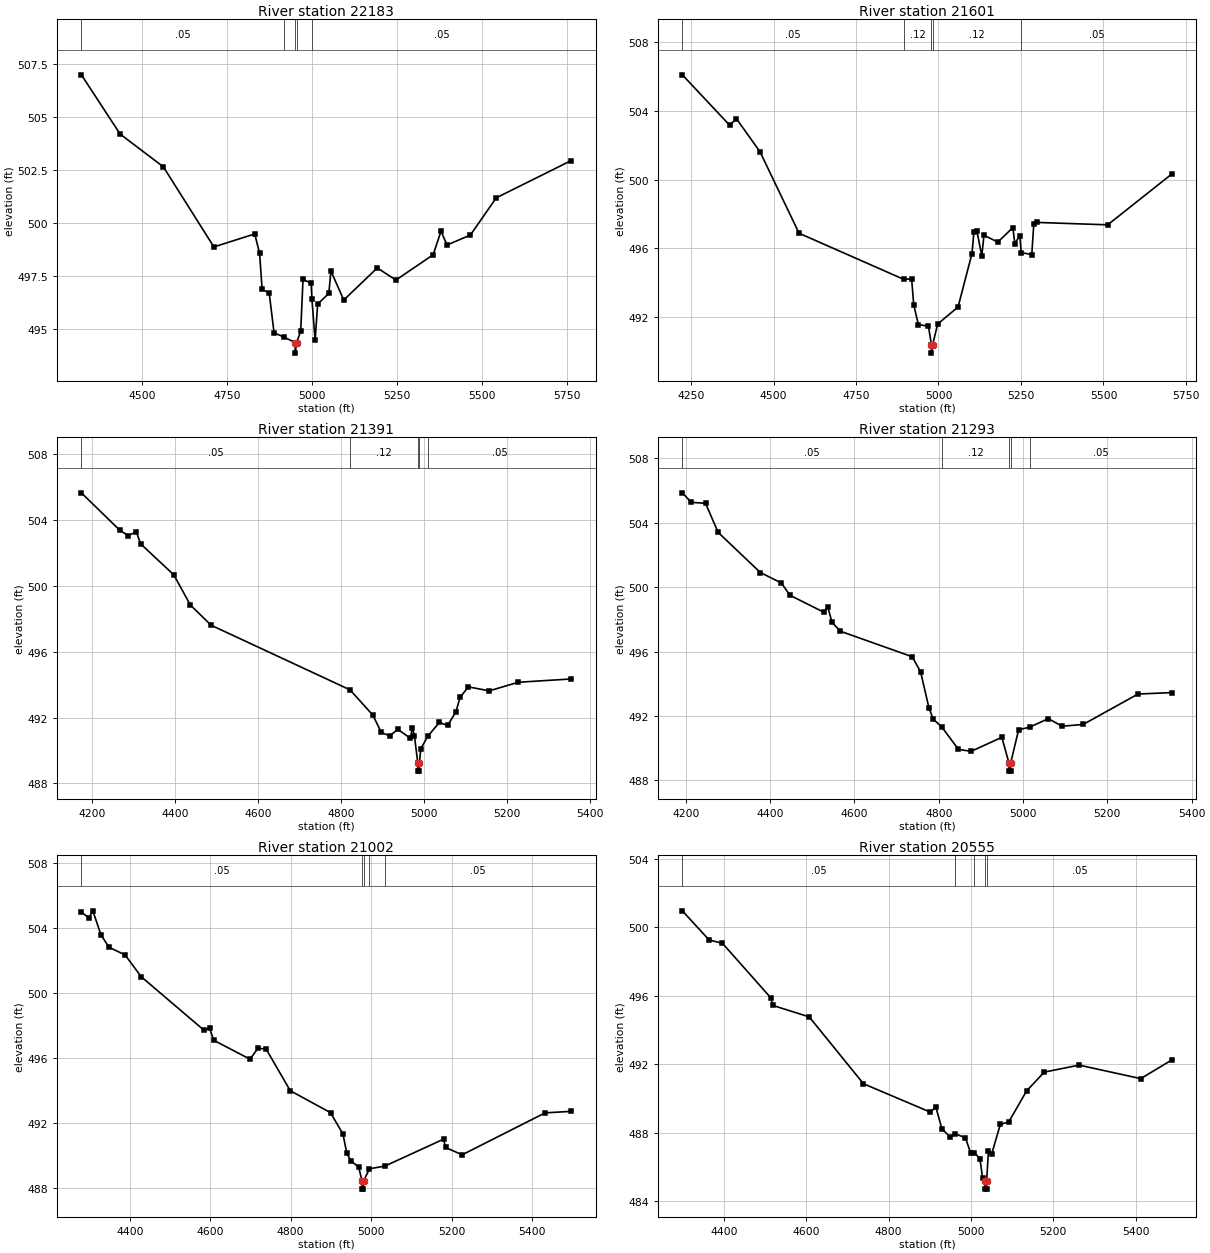
Type RM Length L Ch R = 1 ,22183   ,582,582,582
BEGIN DESCRIPTION:
Andy Branch 38.0
END DESCRIPTION:
XS GIS Cut Line= 3
      2747070.53       6924854.9        2746576.        6925311.
      2746263.23      6926011.17
#Sta/Elev= 30
  4322.4  506.97  4436.3  504.18  4563.3  502.64  4711.9  498.87  4832.1  499.48
  4846.3  498.56  4853.7  496.88  4874.6  496.69  4888.8  494.83    4918  494.62
  4950.9  494.37  4951.1  493.87  4954.9  494.37  4967.1  494.89  4973.9  497.34
  4997.9  497.16  5000.1  496.42  5009.5  494.47    5017  496.18  5049.9  496.68
  5055.9  497.74  5093.7  496.37  5192.3  497.88    5247  497.31  5356.6   498.5
  5379.6  499.61  5397.3  498.96  5466.1  499.43    5542  501.18    5762  502.93
#Mann= 5 ,-1 , 0
  4322.4     .05       0    4918     .12       0  4950.9     .07       0
  4954.9     .12       0  5000.1     .05       0
Bank Sta=4950.9,4954.9
XS Rating Curve= 0 ,0
Exp/Cntr=0.3,0.1

Type RM Length L Ch R = 1 ,21601   ,210,210,210
BEGIN DESCRIPTION:
Mapping XS a1f1e4e3
END DESCRIPTION:
XS GIS Cut Line= 3
      2747036.63       6924784.6      2746276.26      6924940.84
      2745890.91      6925534.48
#Sta/Elev= 30
  4223.7  506.08  4367.3  503.15  4387.7  503.53  4459.1  501.61  4577.5  496.88
  4895.2   494.2  4918.5  494.24  4924.9  492.73    4939  491.58  4969.6  491.48
  4978.4  490.42  4978.7  489.92  4982.4  490.42  4997.5  491.61  5059.3   492.6
  5101.5   495.7  5107.4  496.98  5116.6     497  5131.3  495.56  5137.7  496.76
  5179.9  496.37  5225.4  497.21  5231.3  496.28  5246.5  496.75  5250.6  495.76
  5282.7  495.64  5288.7  497.39  5297.9  497.51  5512.8  497.37  5707.7  500.33
#Mann= 5 ,-1 , 0
  4223.7     .05       0  4895.2     .12       0  4978.4     .07       0
  4982.4     .12       0  5250.6     .05       0
Bank Sta=4978.4,4982.4
XS Rating Curve= 0 ,0
Exp/Cntr=0.3,0.1

Type RM Length L Ch R = 1 ,21391   ,98,98,98
BEGIN DESCRIPTION:
Mapping XS 1b6aba87
END DESCRIPTION:
XS GIS Cut Line= 3
      2747008.45      6924755.84      2746190.72      6924766.25
       2745829.1      6924785.02
#Sta/Elev= 30
  4174.7  505.63  4267.2  503.36  4287.2  503.04  4307.2  503.26  4317.2  502.54
  4397.2  500.66  4437.2  498.83  4487.2   497.6    4822  493.68  4877.2  492.14
  4897.2   491.1  4917.2  490.89  4937.2  491.28  4967.2  490.75  4972.3  491.38
  4977.3  490.86  4985.2  489.25  4985.5  488.75    4989  488.75  4989.2  489.25
  4992.4   490.1  5009.6  490.88  5037.3   491.7  5057.3  491.52  5077.3  492.36
  5087.3  493.24  5107.4  493.86  5157.4  493.62  5227.5  494.14  5354.6  494.34
#Mann= 5 ,-1 , 0
  4174.7     .05       0    4822     .12       0  4985.2     .07       0
  4989.2     .12       0  5009.6     .05       0
Bank Sta=4985.2,4989.2
XS Rating Curve= 0 ,0
Exp/Cntr=0.3,0.1

Type RM Length L Ch R = 1 ,21293   ,291,291,291
BEGIN DESCRIPTION:
Mapping XS 62f7a404
END DESCRIPTION:
XS GIS Cut Line= 4
      2747010.99      6924685.53      2746274.05      6924701.15
      2746146.45      6924662.09      2745855.35      6924667.63
#Sta/Elev= 30
  4191.7  505.86  4212.9  505.27  4246.7  505.21  4276.7   503.4  4376.7  500.91
  4426.7  500.26  4446.7   499.5  4526.8  498.45  4536.8  498.77  4546.8  497.81
  4566.8  497.26  4736.8  495.68  4756.8  494.75  4776.8   492.5  4786.8   491.8
  4807.3  491.31  4846.8  489.92  4876.8   489.8  4949.7  490.67  4966.6  489.07
  4966.8  488.57  4970.3  488.57  4970.6  489.07  4989.5  491.14  5015.6   491.3
  5059.9  491.83  5092.7  491.36  5142.7  491.47  5272.7  493.36  5353.4  493.45
#Mann= 5 ,-1 , 0
  4191.7     .05       0  4807.3     .12       0  4966.6     .07       0
  4970.6     .12       0  5015.6     .05       0
Bank Sta=4966.6,4970.6
XS Rating Curve= 0 ,0
Exp/Cntr=0.3,0.1

Type RM Length L Ch R = 1 ,21002   ,447,447,447
BEGIN DESCRIPTION:
Mapping XS e9385076
END DESCRIPTION:
XS GIS Cut Line= 3
      2746984.46      6924408.18      2746273.53      6924449.85
      2745783.51      6924573.76
#Sta/Elev= 30
  4279.7  504.98  4298.2  504.63  4308.2  505.06  4328.2  503.59  4348.3  502.82
  4388.3  502.35  4428.4  501.01    4584  497.73  4598.7  497.83  4608.7   497.1
  4698.9  495.94  4718.9  496.61    4739  496.56  4799.1     494  4899.2  492.65
  4930.2  491.33  4939.3  490.19  4949.3   489.7  4969.3   489.3  4977.4  488.45
  4977.6  487.95  4981.1  487.95  4981.4  488.45    4996   489.2  5034.6  489.37
  5180.1  491.02  5185.3  490.51  5226.5  490.06  5432.8  492.64  5497.3  492.73
#Mann= 5 ,-1 , 0
  4279.7     .05       0  4977.4     .07       0  4981.4     .05       0
    4996     .12       0  5034.6     .05       0
Bank Sta=4977.4,4981.4
XS Rating Curve= 0 ,0
Exp/Cntr=0.3,0.1

Type RM Length L Ch R = 1 ,20555   ,382,382,382
BEGIN DESCRIPTION:
Mapping XS a680da03
END DESCRIPTION:
XS GIS Cut Line= 3
      2746560.02      6924030.57      2745976.65      6924126.93
      2745594.63      6924586.92
#Sta/Elev= 30
    4299  500.96  4363.9  499.26  4396.5  499.06  4513.6  495.88  4518.7  495.43
  4607.1  494.76  4738.9  490.85  4900.6   489.2  4914.9  489.47  4929.2  488.23
  4950.1  487.71  4960.2  487.94  4986.5  487.69  4999.5  486.78  5008.3  486.82
  5021.7  486.47  5028.2  485.34    5034  485.19  5034.3  484.69  5037.8  484.69
    5038  485.19  5042.5  486.94  5050.3  486.75  5071.2  488.47    5092  488.63
    5135  490.43  5177.9  491.53  5262.6  491.94  5412.3  491.15  5488.2  492.25
#Mann= 5 ,-1 , 0
    4299     .05       0  4960.2     .12       0  5008.3     .05       0
    5034     .07       0    5038     .05       0
Bank Sta=5034,5038
XS Rating Curve= 0 ,0
Exp/Cntr=0.3,0.1

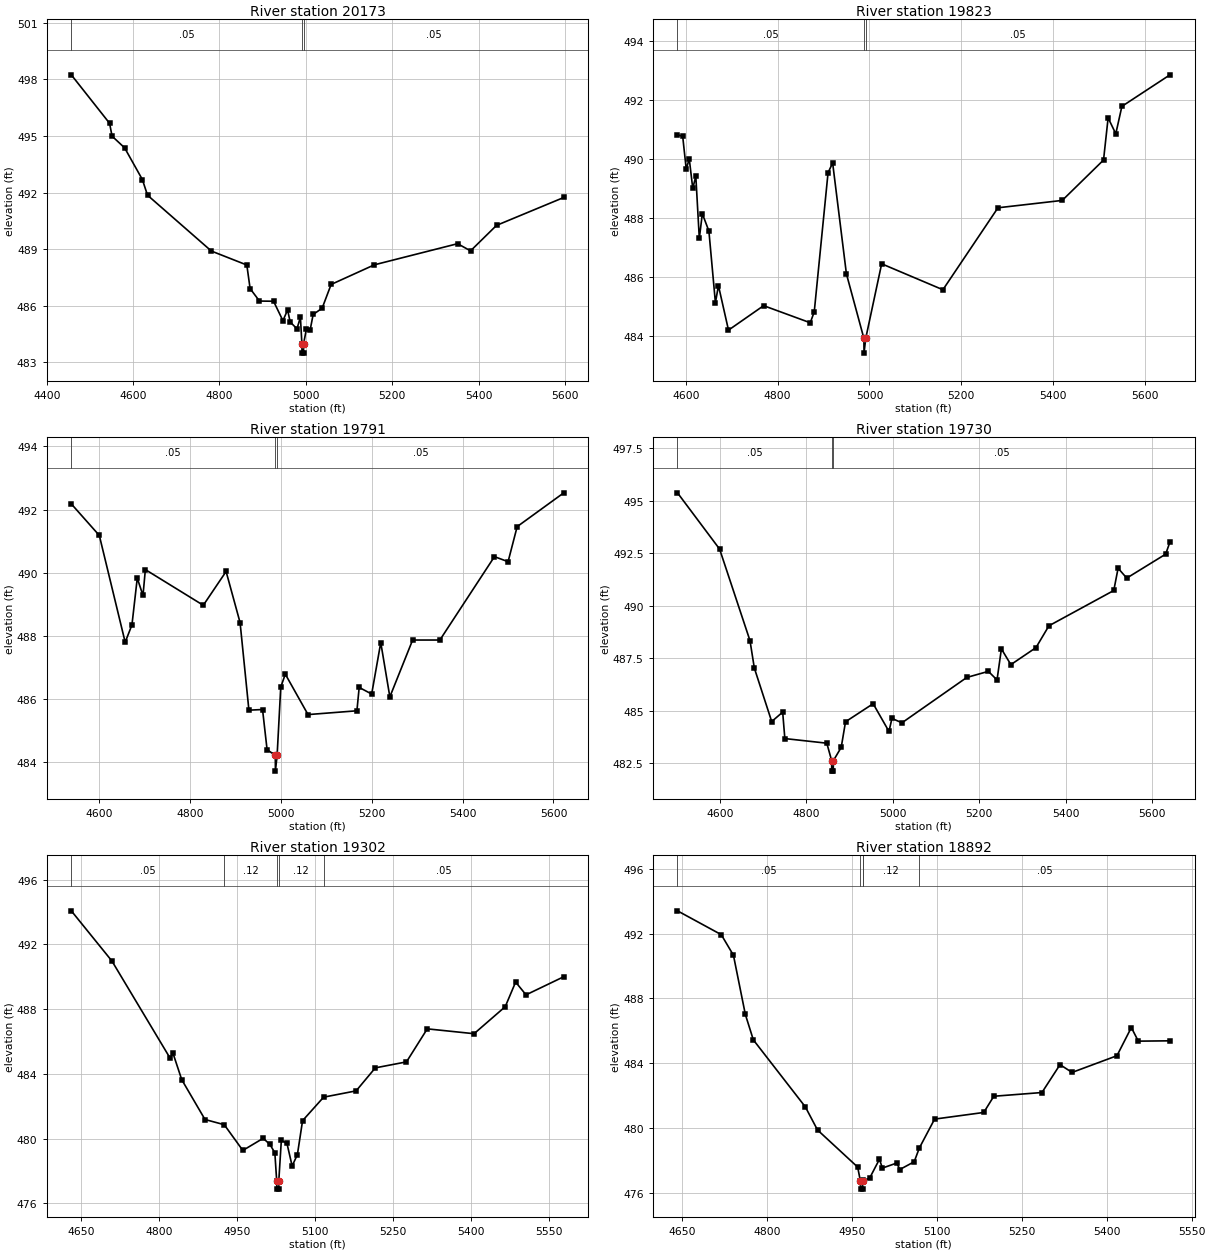
Type RM Length L Ch R = 1 ,20173   ,350,350,350
BEGIN DESCRIPTION:
Mapping XS 726aa76a
END DESCRIPTION:
XS GIS Cut Line= 4
      2746187.77      6923759.33        2745680.      6923972.85
      2745578.43      6924100.46      2745562.84      6924526.74
#Sta/Elev= 30
  4456.8  498.24  4545.5  495.67  4551.2  494.99  4580.3  494.37  4621.4  492.69
  4633.3  491.86  4781.2   488.9  4863.3  488.16  4870.9  486.91  4892.6  486.25
  4925.2  486.24  4946.9  485.21  4957.7  485.78  4963.7  485.14  4979.4  484.78
  4987.4  485.39  4990.8  483.99  4991.1  483.49  4994.6  483.49  4994.8  483.99
  5001.1  484.75  5009.7  484.69  5016.9  485.54  5037.7  485.87  5058.5  487.13
  5158.6  488.17  5351.4  489.29  5381.4  488.91  5441.5  490.26  5597.3  491.74
#Mann= 3 ,-1 , 0
  4456.8     .05       0  4990.8     .04       0  4994.8     .05       0
Bank Sta=4990.8,4994.8
XS Rating Curve= 0 ,0
Exp/Cntr=0.3,0.1

Type RM Length L Ch R = 1 ,19823   ,32,32,32
BEGIN DESCRIPTION:
Mapping XS cf1b0a78
END DESCRIPTION:
XS GIS Cut Line= 5
      2745465.36      6923523.73      2745383.94      6923617.92
      2745371.29      6923778.67      2745383.87      6923986.79
      2745367.76      6924565.71
#Sta/Elev= 30
  4581.6  490.82    4593  490.76  4600.7  489.65  4607.3     490  4614.9     489
  4621.6  489.41  4629.2   487.3  4635.8  488.14  4650.1  487.55  4664.3  485.12
  4670.9   485.7  4692.8  484.19  4769.4  485.02    4871  484.44  4879.7  484.81
  4909.8  489.53  4919.8  489.86  4949.8   486.1  4987.9  483.91  4988.2  483.41
  4991.9  483.91  5026.6  486.44  5160.1  485.56  5280.1  488.34  5420.2  488.59
  5510.2  489.96  5520.2  491.39  5536.9  490.85  5550.2  491.78    5655  492.85
#Mann= 3 ,-1 , 0
  4581.6     .05       0  4987.9     .04       0  4991.9     .05       0
#XS Ineff= 2 , 0
       0  4919.8  489.86               0
Permanent Ineff=
       F       F
Bank Sta=4987.9,4991.9
XS Rating Curve= 0 ,0
Exp/Cntr=0.3,0.1

Type RM Length L Ch R = 1 ,19791   ,61,61,61
BEGIN DESCRIPTION:
Mapping XS 98f3a551
END DESCRIPTION:
XS GIS Cut Line= 6
       2745448.8      6923479.23      2745364.55      6923601.86
      2745345.23      6923674.13      2745343.29      6923754.62
      2745350.58      6923817.14      2745324.58      6924533.53
#Sta/Elev= 30
  4538.8  492.18  4600.5  491.18  4657.4   487.8  4672.3  488.35    4684  489.83
  4696.6  489.28  4701.8   490.1  4829.3  488.97  4879.5  490.04  4910.3  488.42
  4929.7  485.65  4959.7  485.67  4969.7   484.4  4987.8  484.22    4988  483.72
  4991.8  484.22  4999.8  486.38  5009.8  486.79  5059.8  485.51  5167.4  485.63
  5172.4  486.37  5199.9  486.16  5219.9  487.79  5239.9  486.07    5290  487.87
    5350  487.87  5470.1  490.51  5500.1  490.35  5520.1  491.46  5622.7  492.53
#Mann= 3 ,-1 , 0
  4538.8     .05       0  4987.8     .04       0  4991.8     .05       0
Bank Sta=4987.8,4991.8
XS Rating Curve= 0 ,0
Exp/Cntr=0.3,0.1

Type RM Length L Ch R = 1 ,19730   ,428,428,428
BEGIN DESCRIPTION:
Mapping XS 3ebdd660
END DESCRIPTION:
XS GIS Cut Line= 3
      2745334.44        6923414.       2745286.5      6923909.78
      2745297.18      6924550.99
#Sta/Elev= 30
  4501.9  495.38  4599.4   492.7  4669.7  488.34  4679.7  487.04  4719.9  484.49
  4745.3  484.94  4750.3  483.68  4847.4  483.46  4858.6  482.63  4858.8  482.13
  4862.3  482.13  4862.6  482.63  4880.7  483.26  4890.7  484.48  4954.6  485.34
  4991.2  484.02  4998.1  484.64  5021.2  484.43  5171.2  486.59  5221.2  486.88
  5241.2  486.47  5251.3  487.95  5273.2   487.2  5331.3  488.01  5361.3  489.05
  5511.3  490.73  5521.3  491.79  5541.3  491.32  5631.3  492.46  5641.3  493.04
#Mann= 3 ,-1 , 0
  4501.9     .05       0  4858.6     .04       0  4862.6     .05       0
Bank Sta=4858.6,4862.6
XS Rating Curve= 0 ,0
Exp/Cntr=0.3,0.1

Type RM Length L Ch R = 1 ,19302   ,410,410,410
BEGIN DESCRIPTION:
Mapping XS 363387ba
END DESCRIPTION:
XS GIS Cut Line= 3
      2745127.17      6923418.67      2744944.86      6923785.46
      2744929.67      6924323.65
#Sta/Elev= 30
  4631.4  494.07  4709.6  490.97  4821.6  484.97  4827.2  485.27    4844  483.64
  4888.8  481.18  4925.8  480.86  4961.6  479.27  5000.8  480.02  5013.7  479.64
  5023.2  479.13  5026.8  477.38  5027.1  476.88  5030.6  476.88  5030.8  477.38
  5035.7  479.89  5046.5  479.71  5056.5  478.31  5066.6  479.01  5076.6  481.11
  5117.1  482.56  5179.7  482.95  5216.6  484.37  5276.6  484.74  5316.6  486.78
  5406.7  486.48  5466.7  488.15  5486.7  489.67  5506.7  488.88  5579.4     490
#Mann= 5 ,-1 , 0
  4631.4     .05       0  4925.8     .12       0  5026.8     .07       0
  5030.8     .12       0  5117.1     .05       0
Bank Sta=5026.8,5030.8
XS Rating Curve= 0 ,0
Exp/Cntr=0.3,0.1

Type RM Length L Ch R = 1 ,18892   ,437,437,437
BEGIN DESCRIPTION:
Mapping XS 3ba17f94
END DESCRIPTION:
XS GIS Cut Line= 3
       2744918.8      6923364.47      2744666.22      6923601.43
      2744489.13      6924093.61
#Sta/Elev= 30
  4642.3   493.4  4719.6  491.93  4741.1  490.66  4762.1  487.01  4776.2  485.44
  4868.1   481.3  4889.5  479.88  4960.4  477.59  4965.2  476.73  4965.5  476.23
    4969  476.23  4969.2  476.73  4970.4  476.77  4981.4   476.9  4998.8  478.07
  5004.1  477.53  5029.5  477.84  5034.8  477.44  5060.2  477.92  5069.3  478.77
  5096.2  480.55    5183  480.96  5200.7  481.96  5285.7  482.19  5317.6  483.91
  5338.9  483.43  5418.1  484.46  5443.5   486.2  5455.8  485.36  5511.7  485.38
#Mann= 5 ,-1 , 0
  4642.3     .05       0  4965.2     .07       0  4969.2     .05       0
  4970.4     .12       0  5069.3     .05       0
Bank Sta=4965.2,4969.2
XS Rating Curve= 0 ,0
Exp/Cntr=0.3,0.1

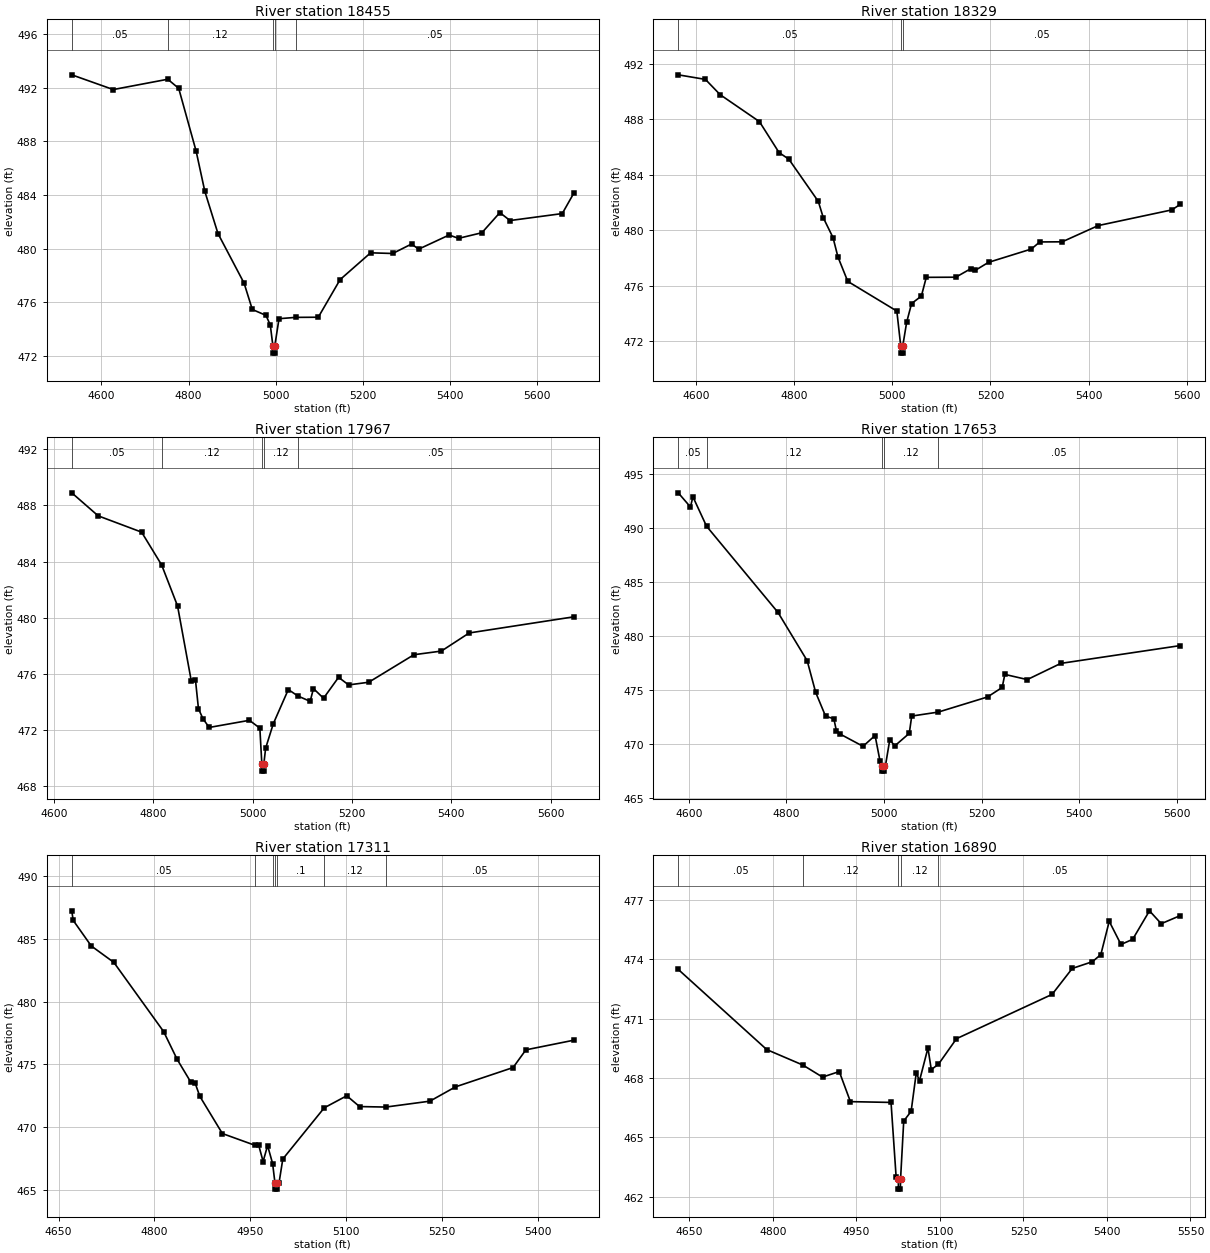
Type RM Length L Ch R = 1 ,18455   ,126,126,126
BEGIN DESCRIPTION:
Mapping XS 1c06445f
END DESCRIPTION:
XS GIS Cut Line= 4
      2744341.99      6922895.96      2744318.56      6923362.07
      2744308.14      6923617.27      2744149.76      6924017.13
#Sta/Elev= 30
    4532  492.97  4627.2  491.87  4752.3  492.64  4777.4  491.96  4817.4  487.27
  4837.4  484.26  4867.5  481.12  4927.5  477.41  4946.3  475.45  4977.6  475.01
  4987.6  474.29  4993.7  472.69  4993.9  472.19  4997.4  472.19  4997.7  472.69
  5007.6  474.76    5046  474.86  5097.7  474.87  5147.8  477.68  5217.8  479.68
  5268.5  479.63  5311.9  480.34  5327.9  479.95    5398  481.01  5419.5  480.76
  5473.2  481.18  5514.4  482.68  5537.8  482.09  5657.6  482.61  5684.2  484.14
#Mann= 5 ,-1 , 0
    4532     .05       0  4752.3     .12       0  4993.7     .07       0
  4997.7     .12       0    5046     .05       0
Bank Sta=4993.7,4997.7
XS Rating Curve= 0 ,0
Exp/Cntr=0.3,0.1

Type RM Length L Ch R = 1 ,18329   ,362,362,362
BEGIN DESCRIPTION:
Mapping XS d5c092c0
END DESCRIPTION:
XS GIS Cut Line= 4
      2744215.41      6922875.65      2744208.89      6923305.35
      2744202.38      6923509.35       2744085.2      6923880.43
#Sta/Elev= 30
  4563.8  491.21  4619.2  490.88  4649.2  489.78  4729.2  487.84  4769.2  485.61
  4789.2  485.13  4849.2  482.09  4859.4  480.91  4879.2  479.48  4889.2  478.09
  4909.2  476.33  5009.2  474.19  5017.2  471.66  5017.5  471.16    5021  471.16
  5021.2  471.66  5029.2  473.38  5039.2  474.73  5059.2  475.27  5069.2  476.62
  5129.3  476.63  5159.3  477.23  5169.3  477.13    5196   477.7  5283.3  478.66
  5300.4  479.17  5346.2  479.18  5419.6  480.35  5569.6  481.48  5586.8  481.88
#Mann= 3 ,-1 , 0
  4563.8     .05       0  5017.2     .05       0  5021.2     .05       0
Bank Sta=5017.2,5021.2
XS Rating Curve= 0 ,0
Exp/Cntr=0.3,0.1

Type RM Length L Ch R = 1 ,17967   ,314,314,314
BEGIN DESCRIPTION:
Mapping XS 2746e97d
END DESCRIPTION:
XS GIS Cut Line= 3
      2744128.89      6922859.61      2743914.04       6923187.3
      2743820.73      6923799.28
#Sta/Elev= 30
  4635.7   488.9  4688.9  487.26  4776.3   486.1  4816.7  483.76  4848.7  480.84
  4876.5  475.47  4884.8  475.56  4890.8  473.52  4899.9  472.81  4912.4  472.19
  4993.4   472.7  5014.4  472.14  5018.4  469.58  5018.7  469.08  5022.2  469.08
  5022.4  469.58    5026  470.71  5041.4  472.45  5071.7  474.89    5091  474.43
  5115.7  474.05  5122.3  474.96  5142.6  474.27  5172.9  475.76  5193.1  475.22
  5233.6  475.41  5324.6  477.37  5379.9  477.63  5435.9  478.92  5646.6  480.07
#Mann= 5 ,-1 , 0
  4635.7     .05       0  4816.7     .12       0  5018.4     .07       0
  5022.4     .12       0    5091     .05       0
Bank Sta=5018.4,5022.4
XS Rating Curve= 0 ,0
Exp/Cntr=0.3,0.1

Type RM Length L Ch R = 1 ,17653   ,342,342,342
BEGIN DESCRIPTION:
Mapping XS 94517900
END DESCRIPTION:
XS GIS Cut Line= 4
      2743755.63      6922653.43      2743684.01      6923067.94
      2743668.82      6923358.74      2743686.18      6923675.62
#Sta/Elev= 30
  4578.3   493.3  4603.3  491.99  4608.4  492.93  4636.3  490.21  4782.8  482.22
  4842.6  477.75    4860  474.82  4880.3  472.61  4897.3  472.37  4902.4  471.28
  4910.7  470.94  4957.1  469.82  4981.8  470.82  4991.9  468.46    4996  468.02
  4996.2  467.52  4999.7  467.52    5000  468.02    5003  468.02    5012  470.44
    5022  469.85  5051.9  471.02  5056.9  472.62  5111.4  472.99  5212.3  474.39
  5242.3  475.27  5247.8  476.48  5293.8     476  5362.5   477.5  5607.5  479.15
#Mann= 5 ,-1 , 0
  4578.3     .05       0  4636.3     .12       0    4996     .07       0
    5000     .12       0  5111.4     .05       0
Bank Sta=4996,5000
XS Rating Curve= 0 ,0
Exp/Cntr=0.3,0.1

Type RM Length L Ch R = 1 ,17311   ,421,421,421
BEGIN DESCRIPTION:
Mapping XS 2f9e82d9
END DESCRIPTION:
XS GIS Cut Line= 3
      2743624.01      6922695.93      2743394.84       6922925.1
      2743387.03      6923386.03
#Sta/Elev= 30
  4670.7  487.23  4672.9  486.47  4701.2  484.43  4736.5  483.12  4814.3  477.61
  4835.5  475.39  4856.7  473.59  4863.8  473.47  4870.9  472.45  4906.2  469.48
  4957.3  468.54  4962.8  468.59  4969.9  467.25  4976.9  468.52  4984.8  467.08
  4988.4  465.55  4988.7  465.05  4992.2  465.05  4992.4  465.55  4994.8  465.55
  5000.7  467.45  5065.5  471.53  5100.7  472.49  5120.7  471.63  5161.7  471.59
  5230.7  472.06  5270.7   473.2  5360.8  474.74  5380.8  476.15  5455.8  476.92
#Mann= 7 ,-1 , 0
  4670.7     .05       0  4957.3     .12       0  4984.8      .1       0
  4988.4     .07       0  4992.4      .1       0  5065.5     .12       0
  5161.7     .05       0
Bank Sta=4988.4,4992.4
XS Rating Curve= 0 ,0
Exp/Cntr=0.3,0.1

Type RM Length L Ch R = 1 ,16890   ,543,543,543
BEGIN DESCRIPTION:
Mapping XS 10cd0145
END DESCRIPTION:
XS GIS Cut Line= 3
       2742993.8      6922542.32      2743017.24      6922912.08
      2743308.45       6923356.7
#Sta/Elev= 30
  4629.8  473.49  4788.8  469.44  4853.6  468.66    4889  468.05  4919.1  468.33
  4939.1  466.81  5012.1  466.77  5021.2  463.02  5025.2  462.89  5025.4  462.39
  5028.9  462.39  5029.2  462.89  5034.9  465.83  5048.2  466.32  5057.4  468.26
  5063.3  467.87  5078.4  469.52  5084.4  468.43  5097.3   468.7  5129.7  469.99
  5301.5  472.23  5337.7  473.54  5373.9  473.88    5389  474.24  5404.1  475.92
  5425.2  474.75  5446.2  475.01  5476.4  476.45  5497.5   475.8  5531.8  476.21
#Mann= 5 ,-1 , 0
  4629.8     .05       0  4853.6     .12       0  5025.2     .07       0
  5029.2     .12       0  5097.3     .05       0
Bank Sta=5025.2,5029.2
XS Rating Curve= 0 ,0
Exp/Cntr=0.3,0.1

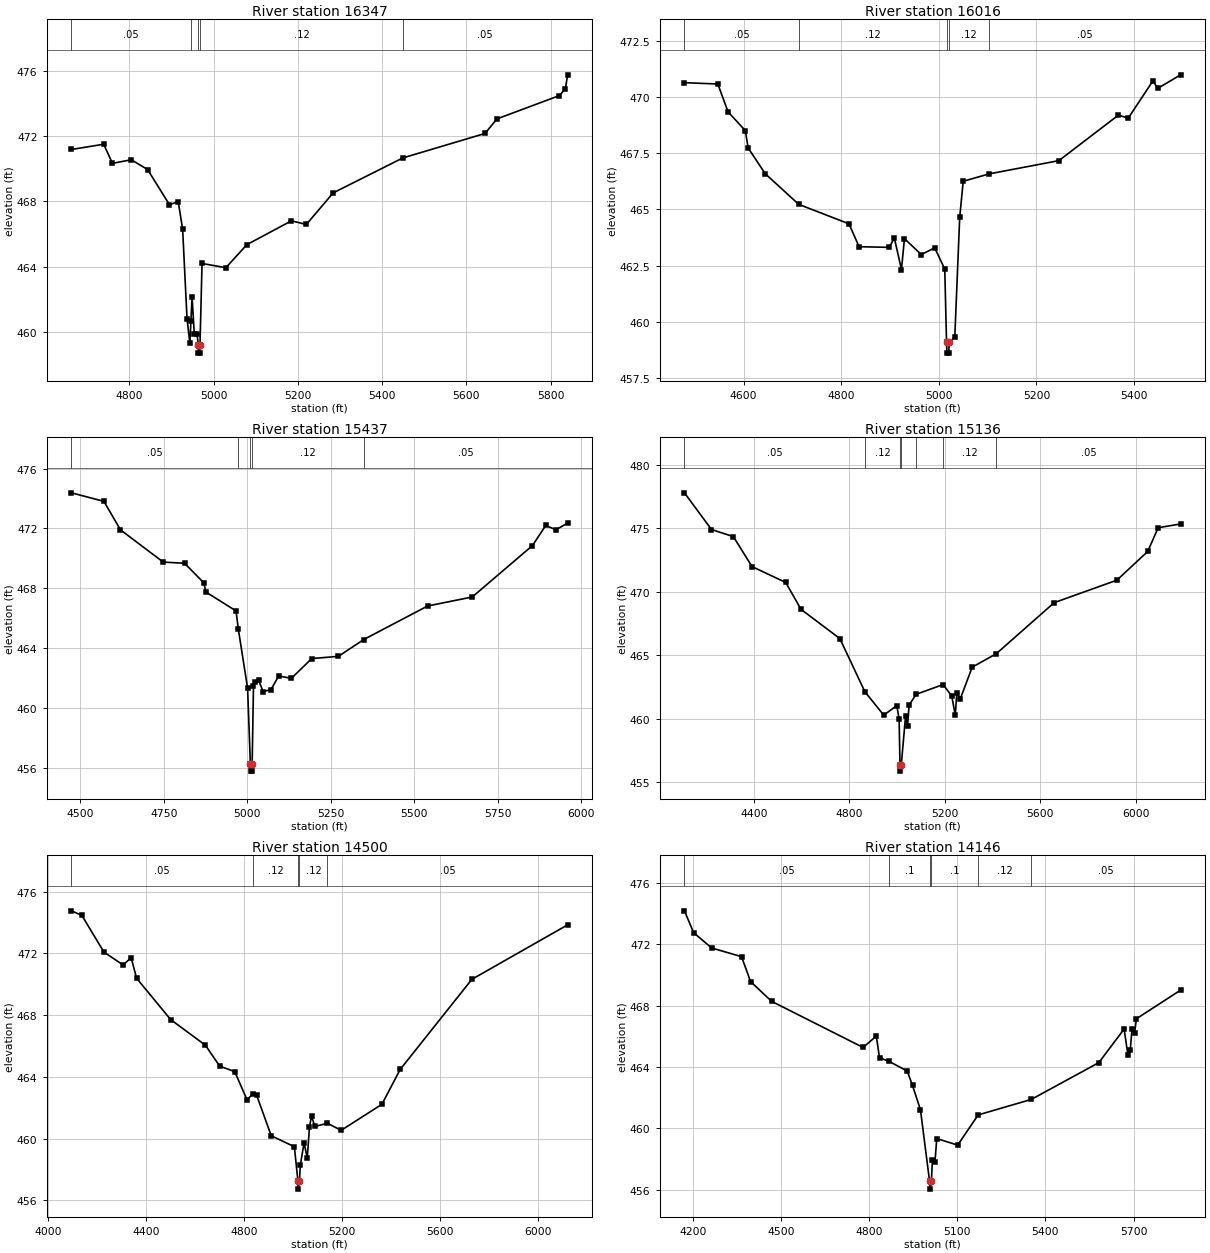
Type RM Length L Ch R = 1 ,16347   ,331,331,331
BEGIN DESCRIPTION:
Andy Branch 25.0
END DESCRIPTION:
XS GIS Cut Line= 3
      2742481.82      6922377.59      2742563.96      6922659.26
      2743177.37      6923297.04
#Sta/Elev= 30
  4662.3  471.17  4738.8  471.49  4759.6  470.32  4804.4  470.54  4843.1  469.94
    4895  467.79  4915.9  467.97  4926.3  466.28  4936.7  460.82  4943.5  459.29
    4946  460.66  4948.7  462.14    4954  459.89  4960.4  459.89  4963.5   459.2
  4963.7   458.7  4967.2   458.7  4967.5   459.2  4972.4  464.19    5029  463.93
  5078.7  465.34  5184.6   466.8  5220.2  466.58  5283.7  468.51  5449.1  470.65
  5644.4  472.15  5672.7  473.04  5821.1  474.47  5835.3  474.89  5840.6  475.74
#Mann= 5 ,-1 , 0
  4662.3     .05       0    4946     .12       0  4963.5     .07       0
  4967.5     .12       0  5449.1     .05       0
Bank Sta=4963.5,4967.5
XS Rating Curve= 0 ,0
Exp/Cntr=0.3,0.1

Type RM Length L Ch R = 1 ,16016   ,579,579,579
BEGIN DESCRIPTION:
Mapping XS edaaef21
END DESCRIPTION:
XS GIS Cut Line= 3
       2742462.1      6922354.78       2742326.7      6922878.18
      2742243.44      6923346.51
#Sta/Elev= 30
  4478.9  470.66  4547.3   470.6  4568.1  469.36  4603.6  468.52  4609.3  467.75
  4644.2   466.6  4712.9  465.23  4815.9  464.36  4836.5  463.34  4898.5  463.31
  4908.8  463.73  4923.4  462.32  4929.5   463.7    4964  462.99  4991.5  463.29
  5012.1  462.34  5015.7  459.09  5016.5  458.59  5020.3  458.59  5021.1  459.09
  5032.6  459.29  5042.7  464.65  5049.9  466.26  5103.2  466.59  5245.8  467.18
  5367.7  469.21    5388  469.08  5438.8  470.75    5448   470.4  5495.2  471.01
#Mann= 5 ,-1 , 0
  4478.9     .05       0  4712.9     .12       0  5015.7     .07       0
  5021.1     .12       0  5103.2     .05       0
Bank Sta=5015.7,5021.1
XS Rating Curve= 0 ,0
Exp/Cntr=0.3,0.1

Type RM Length L Ch R = 1 ,15437   ,301,301,301
BEGIN DESCRIPTION:
Mapping XS b7f9caad
END DESCRIPTION:
XS GIS Cut Line= 4
      2742515.92      6922054.41      2742173.05      6922332.18
      2742081.91      6922540.51      2742120.96      6923356.22
#Sta/Elev= 30
  4473.3  474.38  4570.4  473.81    4620  471.91  4747.9  469.76  4811.8  469.68
  4869.3  468.38  4875.8  467.76    4966   466.5  4972.7   465.3  5000.6  461.34
  5008.8  456.31  5009.6  455.81  5013.5  455.81  5014.2  456.31  5018.2  461.52
  5023.7  461.79  5033.3  461.88  5047.1  461.12  5070.5  461.25  5093.8  462.16
  5131.6     462  5192.5  463.32  5272.6  463.47  5348.2  464.59  5539.6  466.83
  5673.1  467.43  5853.3  470.86  5893.3  472.21  5923.3  471.91  5958.6  472.36
#Mann= 5 ,-1 , 0
  4473.3     .05       0  4972.7     .12       0  5008.8     .07       0
  5014.2     .12       0  5348.2     .05       0
Bank Sta=5008.8,5014.2
XS Rating Curve= 0 ,0
Exp/Cntr=0.3,0.1

Type RM Length L Ch R = 1 ,15136   ,636,636,636
BEGIN DESCRIPTION:
Andy Branch 22.0
END DESCRIPTION:
XS GIS Cut Line= 3
        2742526.        6921811.      2741869.93      6922413.42
      2741157.42      6923365.16
#Sta/Elev= 30
  4109.3   477.8  4222.5  474.91  4314.3  474.35  4392.6  471.99  4533.8  470.74
  4597.9  468.62  4760.7  466.32  4865.3  462.14  4944.5  460.29  4999.3  461.04
  5009.1  459.97  5012.6  456.38  5013.4  455.88  5018.1  456.38  5036.1  460.22
  5044.5  459.42  5050.7  461.08  5080.3  461.93  5193.7   462.7  5229.9  461.78
  5244.5  460.27  5250.8  462.04  5265.4  461.57  5315.4  464.07  5415.8  465.12
    5659  469.15  5921.8  470.92    6051  473.18  6094.8  475.05  6188.9  475.35
#Mann= 7 ,-1 , 0
  4109.3     .05       0  4865.3     .12       0  5012.6     .07       0
  5018.1     .12       0  5080.3     .05       0  5193.7     .12       0
  5415.8     .05       0
Bank Sta=5012.6,5018.1
XS Rating Curve= 0 ,0
Exp/Cntr=0.3,0.1

Type RM Length L Ch R = 1 ,14500   ,354,354,354
BEGIN DESCRIPTION:
Andy Branch 21.0
END DESCRIPTION:
XS GIS Cut Line= 3
      2742344.04      6921763.61      2741531.56      6922175.06
      2741068.03      6923190.65
#Sta/Elev= 30
  4094.5  474.76  4137.1  474.46  4226.8  472.09  4305.3  471.25  4338.3  471.72
  4360.6  470.39  4499.8  467.71  4641.6  466.05  4700.3  464.69  4761.5  464.34
  4811.7  462.51  4836.1  462.91  4850.6  462.83  4910.6  460.18  5005.2  459.47
  5019.8  457.22  5020.8  456.72  5025.8  457.22  5029.5  458.27  5044.7  459.72
    5058  458.73  5066.7  460.73  5075.5  461.47  5088.7  460.78  5140.2  460.99
  5196.2  460.53  5362.9  462.22  5437.5  464.48  5730.4  470.32  6121.6  473.85
#Mann= 5 ,-1 , 0
  4094.5     .05       0  4836.1     .12       0  5019.8     .07       0
  5025.8     .12       0  5140.2     .05       0
Bank Sta=5019.8,5025.8
XS Rating Curve= 0 ,0
Exp/Cntr=0.3,0.1

Type RM Length L Ch R = 1 ,14146   ,520,520,520
BEGIN DESCRIPTION:
Andy Branch 20.0
END DESCRIPTION:
XS GIS Cut Line= 3
      2742276.35      6921732.35      2741448.22      6921904.22
        2740951.        6922586.
#Sta/Elev= 30
  4170.8  474.18  4201.8  472.76  4263.1  471.76  4365.2  471.19  4395.8  469.57
  4467.3  468.28  4779.1  465.27  4824.1  466.01    4835   464.6  4867.8  464.36
  4929.5  463.73  4947.4  462.79  4974.5   461.2  5005.6  456.53  5006.6  456.03
  5011.7  456.53  5015.2  457.93  5023.8  457.78    5030  459.33  5101.1   458.9
  5171.1  460.87  5351.9  461.88  5581.9  464.28    5668  466.47  5680.9  464.79
  5688.9  465.09  5695.1   466.5  5703.6  466.19  5709.8  467.14  5860.4  469.01
#Mann= 6 ,-1 , 0
  4170.8     .05       0  4867.8      .1       0  5005.6     .07       0
  5011.7      .1       0  5171.1     .12       0  5351.9     .05       0
Bank Sta=5005.6,5011.7
XS Rating Curve= 0 ,0
Exp/Cntr=0.3,0.1