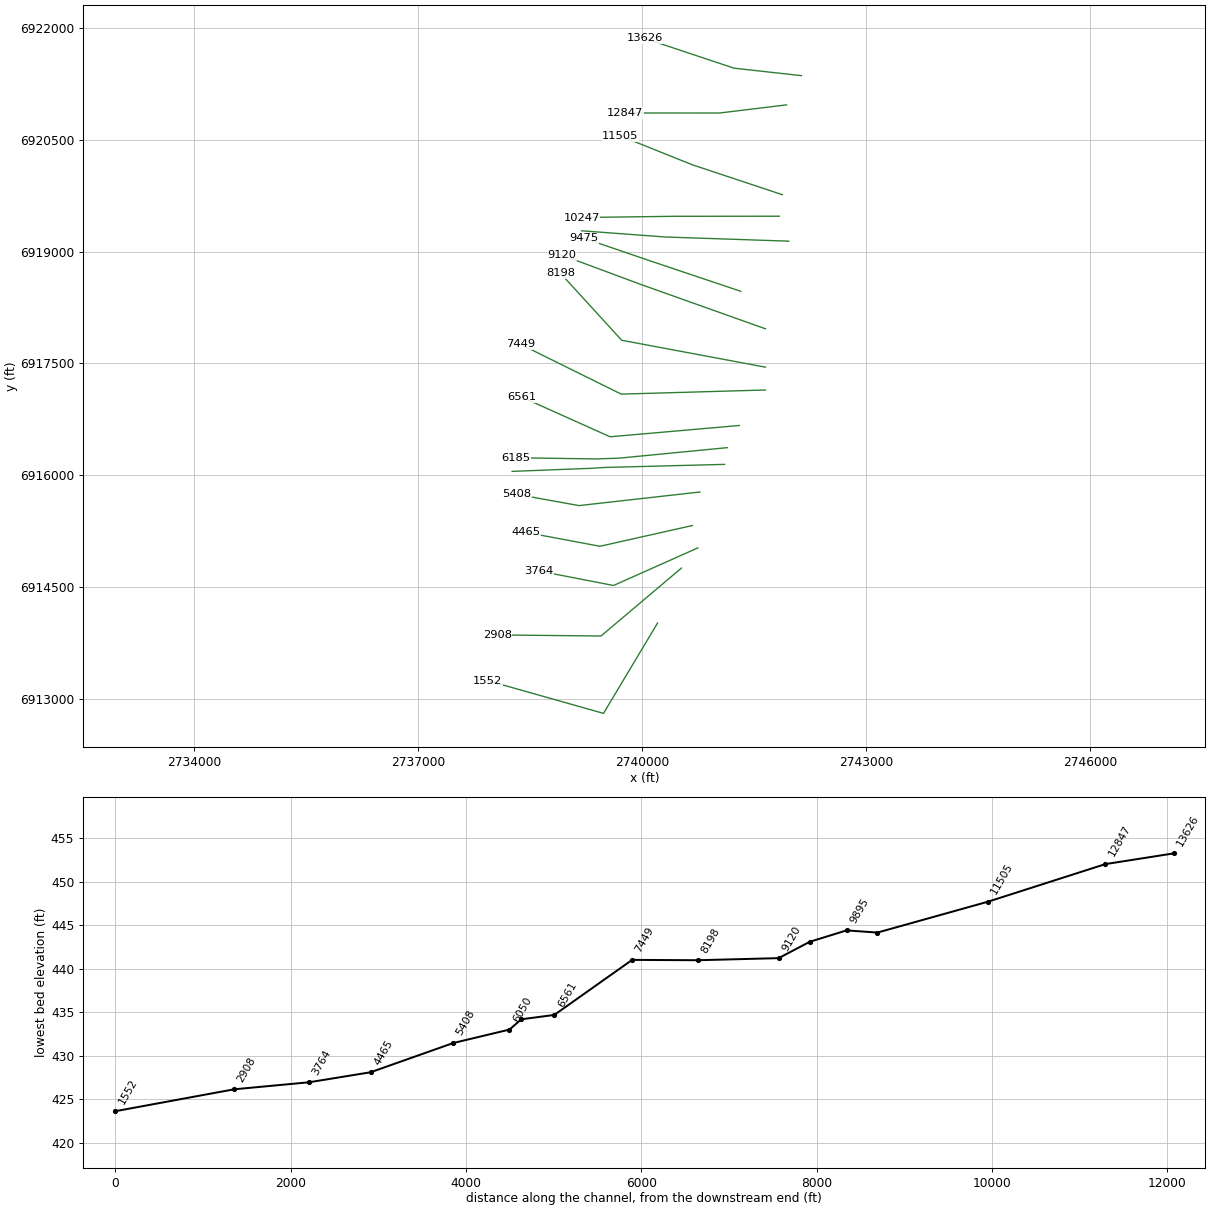
HEC-RAS study Andy Branch.prj: Andy Branch Base Level Engineering

--- Andy Branch.g01 (geometry) --- (continued)

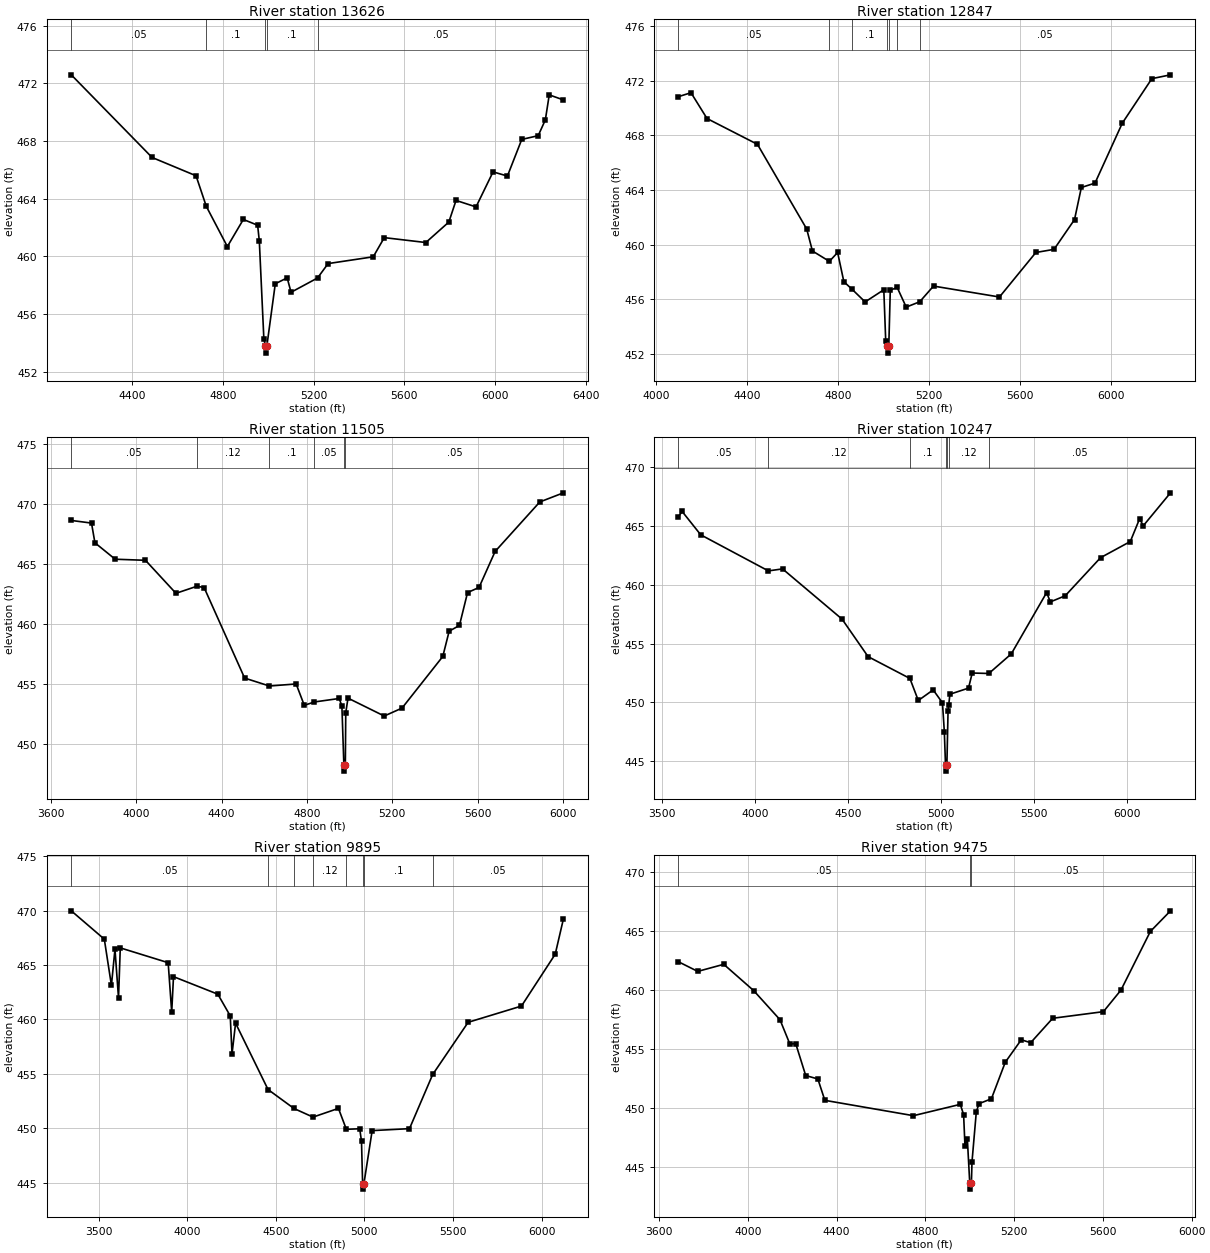
Type RM Length L Ch R = 1 ,13626   ,779,779,779
BEGIN DESCRIPTION:
Andy Branch 18.0
END DESCRIPTION:
XS GIS Cut Line= 3
      2742129.98      6921355.51      2741229.97      6921455.51
       2740030.5      6921855.33
#Sta/Elev= 30
  4131.4  472.58  4487.6  466.85  4681.5  465.58  4726.7  463.46  4819.6  460.67
    4890  462.55  4953.1  462.15  4960.5  461.05  4980.6  454.25  4987.4  453.78
  4988.5  453.28  4993.8  453.78  5030.9  458.09  5083.3   458.5  5100.4   457.5
  5217.1  458.49  5263.8  459.49  5462.8  459.96  5511.5  461.29  5694.7  460.95
  5796.1  462.37  5827.8  463.87    5916  463.42  5991.1  465.85  6054.4  465.56
  6117.6   468.1  6190.1  468.36  6221.7  469.46  6238.8  471.19  6301.3  470.84
#Mann= 5 ,-1 , 0
  4131.4     .05       0  4726.7      .1       0  4987.4     .07       0
  4993.8      .1       0  5217.1     .05       0
Bank Sta=4987.4,4993.8
XS Rating Curve= 0 ,0
Exp/Cntr=0.3,0.1

Type RM Length L Ch R = 1 ,12847   ,1342,1342,1342
BEGIN DESCRIPTION:
Andy Branch 17.0
END DESCRIPTION:
XS GIS Cut Line= 3
      2741931.21      6920964.12      2741034.51      6920855.06
      2739774.11      6920855.61
#Sta/Elev= 30
  4096.7  470.83  4152.3  471.12  4222.8  469.23  4444.5  467.34    4661  461.14
  4686.2  459.53  4760.7  458.77    4797  459.42  4824.4  457.28  4860.2  456.73
  4917.9   455.8    5000  456.69  5008.5  452.91  5015.2  452.55  5016.3  452.05
  5021.9  452.55  5028.5  456.66  5058.8  456.86  5098.5  455.42  5157.8  455.81
  5218.5  456.96  5508.5  456.16  5668.5  459.42  5748.5  459.65  5838.5  461.83
  5868.5  464.18  5928.5   464.5  6048.5  468.89  6178.5  472.15  6260.4  472.43
#Mann= 7 ,-1 , 0
  4096.7     .05       0  4760.7     .12       0  4860.2      .1       0
  5015.2     .07       0  5021.9      .1       0  5058.8     .12       0
  5157.8     .05       0
Bank Sta=5015.2,5021.9
XS Rating Curve= 0 ,0
Exp/Cntr=0.3,0.1

Type RM Length L Ch R = 1 ,11505   ,1258,1258,1258
BEGIN DESCRIPTION:
Andy Branch 15.0
END DESCRIPTION:
XS GIS Cut Line= 3
      2741875.97      6919761.01      2740672.53      6920161.17
      2739709.01      6920547.45
#Sta/Elev= 30
  3695.6   468.6  3790.4  468.38  3806.4  466.74  3901.3  465.37  4043.3  465.28
  4186.2  462.53  4284.5  463.12  4318.1  463.01    4508  455.47  4624.2  454.81
  4749.4  454.98  4787.6   453.2  4834.6  453.48  4951.2  453.77  4963.8  453.14
  4973.1  448.22  4974.2  447.72  4979.9  448.22  4981.9  452.58  4992.4   453.8
  5162.2  452.31  5245.6  452.97  5436.6  457.27  5466.5  459.38  5514.6  459.85
  5552.6  462.59  5606.5  463.02  5681.9  466.02  5891.3  470.14  6001.9   470.9
#Mann= 6 ,-1 , 0
  3695.6     .05       0  4284.5     .12       0  4624.2      .1       0
  4834.6     .05       0  4973.1     .04       0  4979.9     .05       0
Bank Sta=4973.1,4979.9
XS Rating Curve= 0 ,0
Exp/Cntr=0.3,0.1

Type RM Length L Ch R = 1 ,10247   ,352,352,352
BEGIN DESCRIPTION:
Andy Branch 14.0
END DESCRIPTION:
XS GIS Cut Line= 3
      2741836.41      6919472.87      2740424.51      6919471.62
      2739189.91      6919455.53
#Sta/Elev= 30
  3588.1  465.75  3608.5   466.2  3708.5  464.22  4072.3  461.16  4148.5  461.33
  4468.5  457.07  4608.5  453.89  4833.3  452.04  4878.5  450.17  4958.5  451.07
  5008.5  449.97  5018.5  447.52  5024.9  444.68    5026  444.18  5032.2  444.68
  5038.5  449.27  5042.4  449.83  5048.5   450.7  5148.5  451.22  5168.5   452.5
  5257.8  452.46  5378.5  454.12  5568.6  459.32  5588.6  458.53  5668.6  459.05
  5858.6  462.28  6018.6  463.65  6068.6  465.58  6088.6  464.99  6234.7  467.78
#Mann= 7 ,-1 , 0
  3588.1     .05       0  4072.3     .12       0  4833.3      .1       0
  5024.9     .07       0  5032.2      .1       0  5042.4     .12       0
  5257.8     .05       0
Bank Sta=5024.9,5032.2
XS Rating Curve= 0 ,0
Exp/Cntr=0.3,0.1

Type RM Length L Ch R = 1 ,9895    ,420,420,420
BEGIN DESCRIPTION:
Andy Branch 13.0
END DESCRIPTION:
XS GIS Cut Line= 3
      2741962.33      6919138.67      2740309.66      6919194.31
      2739189.95      6919277.48
#Sta/Elev= 30
  3346.4  469.97  3532.8  467.37  3572.9  463.13  3592.9  466.45  3612.9  461.97
  3622.9  466.57    3893  465.21    3913  460.67  3923.1  463.93  4173.2  462.32
  4243.2  460.33  4253.2  456.83  4273.3  459.66  4456.5  453.57  4602.8  451.83
  4710.2  451.04  4853.6  451.84  4898.2  449.92  4973.7  449.97  4983.7  448.81
    4990  444.93  4991.1  444.43  4997.3  444.93  5043.8   449.8  5254.4  449.98
  5385.3  454.95  5585.3  459.74  5886.1  461.23  6076.6  465.99  6122.8  469.23
#Mann= 8 ,-1 , 0
  3346.4     .05       0  4456.5     .12       0  4602.8     .05       0
  4710.2     .12       0  4898.2      .1       0    4990     .07       0
  4997.3      .1       0  5385.3     .05       0
Bank Sta=4990,4997.3
XS Rating Curve= 0 ,0
Exp/Cntr=0.3,0.1

Type RM Length L Ch R = 1 ,9475    ,355,355,355
BEGIN DESCRIPTION:
Andy Branch 12.0
END DESCRIPTION:
XS GIS Cut Line= 3
      2741319.92      6918466.81      2740090.79      6918879.99
       2739220.1      6919178.31
#Sta/Elev= 30
  3687.5  462.38  3774.9  461.56  3892.1  462.16  4027.1  459.93  4145.3  457.47
  4189.9  455.41  4216.2  455.45  4261.3  452.74    4316  452.45  4347.5  450.64
  4746.6  449.34  4957.6   450.3  4972.6  449.44  4978.7   446.8  4989.4   447.4
  5000.3  443.62  5001.4  443.12  5007.7  443.62  5010.4  445.43  5029.9  449.68
  5042.1  450.36  5097.8  450.77  5160.4  453.87  5232.4  455.77  5274.7  455.52
    5374  457.59  5602.4  458.15  5681.6  459.98  5813.8  464.94  5904.6  466.69
#Mann= 3 ,-1 , 0
  3687.5     .05       0  5000.3     .05       0  5007.7     .05       0
Bank Sta=5000.3,5007.7
XS Rating Curve= 0 ,0
Exp/Cntr=0.3,0.1

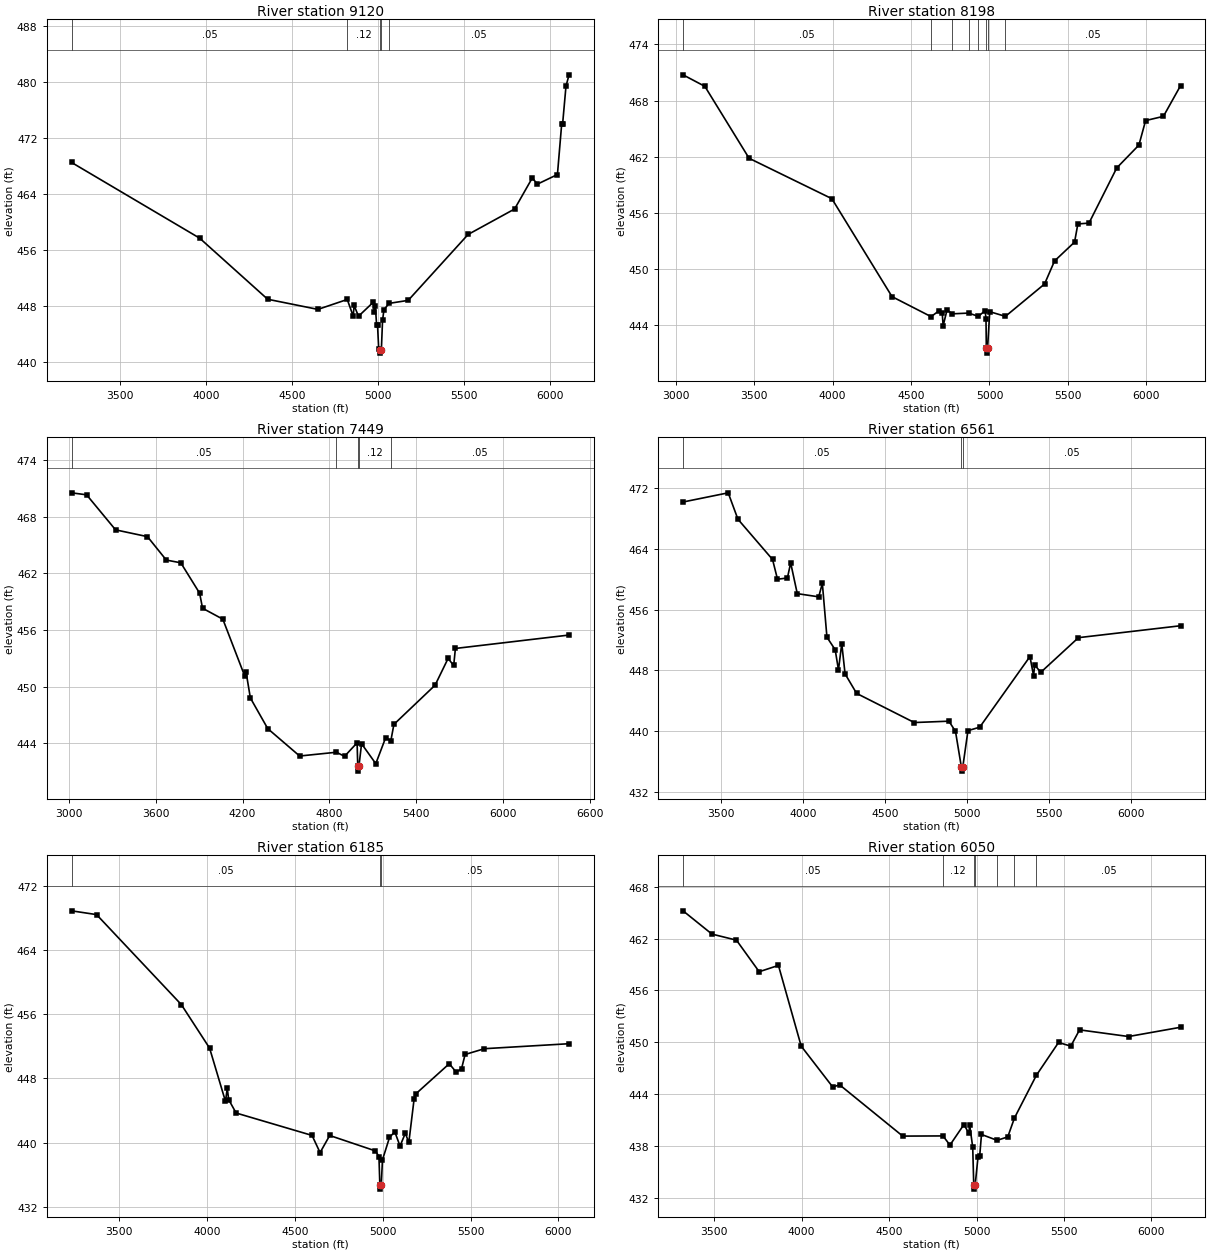
Type RM Length L Ch R = 1 ,9120    ,922,922,922
BEGIN DESCRIPTION:
Andy Branch 11.0
END DESCRIPTION:
XS GIS Cut Line= 3
      2741649.83      6917964.71        2739976.        6918561.
      2738929.28       6918950.2
#Sta/Elev= 30
  3219.2  468.53  3964.5  457.69  4359.9  448.95  4652.2   447.5  4822.8  448.92
  4857.4  446.53  4862.7  448.06  4888.2  446.52  4974.8  448.54  4980.7  447.14
    4986  448.04  4993.4  445.32  4998.7  445.32  5005.9  441.77  5013.7  441.74
  5014.8  441.24  5021.2  441.74  5028.1  445.93  5036.3  447.46  5065.9  448.36
  5177.3  448.79  5525.5  458.22  5796.2  461.87  5898.7   466.3  5929.1  465.43
  6045.2   466.8  6070.2   474.1  6075.5  474.08    6095  479.46  6112.8  481.07
#Mann= 5 ,-1 , 0
  3219.2     .05       0  4822.8     .12       0  5013.7     .07       0
  5021.2     .12       0  5065.9     .05       0
Bank Sta=5013.7,5021.2
XS Rating Curve= 0 ,0
Exp/Cntr=0.3,0.1

Type RM Length L Ch R = 1 ,8198    ,749,749,749
BEGIN DESCRIPTION:
Andy Branch 10.0
END DESCRIPTION:
XS GIS Cut Line= 3
       2741649.8      6917450.83        2739726.        6917811.
      2738907.55      6918706.91
#Sta/Elev= 30
  3047.2  470.75  3186.2  469.52  3468.2  461.83  3995.6  457.51  4379.1  447.04
  4628.1   444.9  4678.9  445.53  4699.2  445.26  4704.9  443.92  4729.7  445.62
  4762.1   445.2  4867.5  445.28  4929.4  444.93    4973  445.55  4978.1   444.6
  4980.2   441.5  4981.4     441  4987.9   441.5  5001.9  445.43  5101.9  444.93
  5351.3  448.39  5414.8  450.85  5542.5  452.87  5563.5  454.81  5634.4   454.9
  5811.4   460.8  5952.6  463.24  5995.2  465.86  6108.7  466.31  6217.9  469.59
#Mann= 8 ,-1 , 0
  3047.2     .05       0  4628.1     .12       0  4762.1      .1       0
  4867.5     .12       0  4929.4      .1       0  4980.2     .07       0
  4987.9      .1       0  5101.9     .05       0
Bank Sta=4980.2,4987.9
XS Rating Curve= 0 ,0
Exp/Cntr=0.3,0.1

Type RM Length L Ch R = 1 ,7449    ,888,888,888
BEGIN DESCRIPTION:
Mapping XS 5c5d1c1e
END DESCRIPTION:
XS GIS Cut Line= 3
      2741649.82      6917145.27      2739719.26      6917089.71
       2738372.4       6917756.2
#Sta/Elev= 30
  3019.8  470.51  3123.7   470.3  3323.7  466.59  3543.8  465.87  3673.9  463.39
  3773.9   463.1    3904  459.88    3924  458.29  4064.1  457.13  4214.1  451.15
  4224.1  451.57  4254.1  448.79  4374.2  445.54  4594.3  442.64  4847.9  443.04
  4904.4  442.61  4990.9  444.04  4995.5  441.54  4996.7  441.04  5003.3  441.54
  5021.7  443.94  5119.9  441.83  5187.2  444.55  5224.1  444.28  5244.9  445.99
  5529.2  450.14  5618.9  452.97  5657.7  452.23  5669.4  454.03  6453.9  455.45
#Mann= 5 ,-1 , 0
  3019.8     .05       0  4847.9     .12       0  4995.5     .07       0
  5003.3     .12       0  5224.1     .05       0
Bank Sta=4995.5,5003.3
XS Rating Curve= 0 ,0
Exp/Cntr=0.3,0.1

Type RM Length L Ch R = 1 ,6561    ,376,376,376
BEGIN DESCRIPTION:
Mapping XS 803c9ef6
END DESCRIPTION:
XS GIS Cut Line= 3
      2741299.15      6916669.58      2739569.95      6916518.53
      2738389.34      6917049.03
#Sta/Elev= 30
  3271.1  470.16  3546.2  471.37  3605.5  467.89  3816.3  462.59  3846.4  459.99
  3906.7  460.15  3926.7  462.14  3966.9  458.09  4097.4  457.67  4119.6  459.44
  4147.6  452.35  4197.8   450.7  4217.8  448.04  4237.9  451.51    4258  447.52
  4328.3  444.95  4679.6  441.11  4890.4  441.29  4930.5  439.95  4966.6  435.21
  4967.8  434.71  4974.7  435.21  5006.4  440.04  5078.2   440.5    5384   449.8
  5405.9   447.3  5413.4  448.69  5449.7  447.72  5679.2  452.29  6301.2  453.86
#Mann= 3 ,-1 , 0
  3271.1     .05       0  4966.6     .04       0  4974.7     .05       0
Bank Sta=4966.6,4974.7
XS Rating Curve= 0 ,0
Exp/Cntr=0.3,0.1

Type RM Length L Ch R = 1 ,6185    ,135,135,135
BEGIN DESCRIPTION:
Mapping XS 7ed8b21d
END DESCRIPTION:
XS GIS Cut Line= 4
      2741137.63       6916372.7      2739689.75      6916232.07
      2739382.45      6916221.66      2738314.73      6916237.28
#Sta/Elev= 30
  3230.6  468.87  3372.9   468.4  3855.2  457.19  4015.9  451.77  4106.3  445.13
  4116.4  446.78  4124.4  445.36  4166.6  443.69  4598.6   440.9  4644.3  438.76
  4699.1  440.89  4959.2  438.97  4979.2  438.27  4984.4  434.71  4985.6  434.21
  4992.5  434.71  4999.2  437.85  5039.2  440.64  5069.2  441.36  5099.2  439.57
  5129.2  441.17  5149.2  440.02  5179.2  445.43  5189.2  446.08  5379.3  449.83
  5419.3  448.76  5449.3  449.23  5469.3  450.98  5579.3   451.7  6060.6  452.32
#Mann= 3 ,-1 , 0
  3230.6     .05       0  4984.4     .05       0  4992.5     .05       0
Bank Sta=4984.4,4992.5
XS Rating Curve= 0 ,0
Exp/Cntr=0.3,0.1

Type RM Length L Ch R = 1 ,6050    ,642,642,642
BEGIN DESCRIPTION:
Mapping XS 49e7a7aa
END DESCRIPTION:
XS GIS Cut Line= 4
       2741101.2      6916148.74      2739481.41      6916107.07
      2739330.37      6916096.66       2738259.2      6916055.06
#Sta/Elev= 30
  3322.4   465.2  3487.7  462.51  3627.7  461.81  3757.7  458.16  3867.8  458.89
  3997.8  449.56  4177.9  444.84  4217.9  445.08    4578  439.16  4808.3  439.18
  4848.1  438.12  4928.1   440.5  4955.8  439.49  4960.8  440.43  4978.2  437.89
  4984.1  433.53  4985.3  433.03  4992.3  433.53  5008.3  436.71  5018.3   436.9
  5028.3  439.35  5117.7  438.67  5178.6  439.07  5216.7  441.25  5342.1  446.19
  5468.8  449.98  5538.8  449.56  5588.9  451.44  5869.1  450.67  6166.1  451.74
#Mann= 7 ,-1 , 0
  3322.4     .05       0  4808.3     .12       0  4984.1     .07       0
  4992.3     .12       0  5117.7     .05       0  5216.7     .12       0
  5342.1     .05       0
Bank Sta=4984.1,4992.3
XS Rating Curve= 0 ,0
Exp/Cntr=0.3,0.1

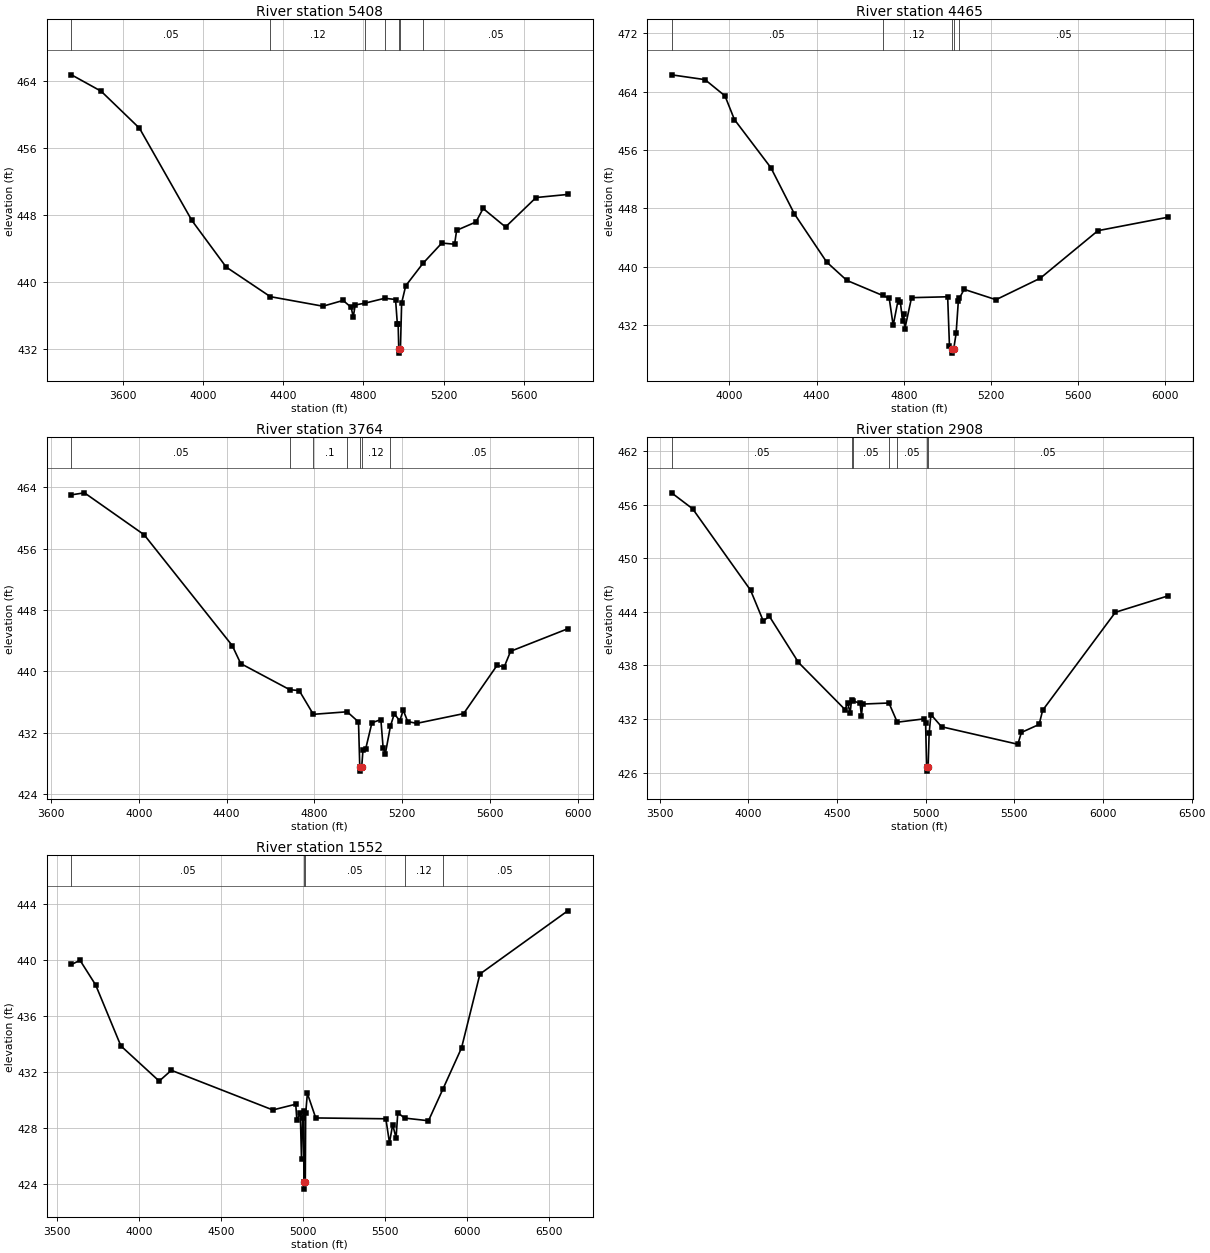
Type RM Length L Ch R = 1 ,5408    ,943,943,943
BEGIN DESCRIPTION:
Mapping XS a4c02601
END DESCRIPTION:
XS GIS Cut Line= 3
      2740773.04      6915778.95      2739153.29      6915596.66
      2738320.43      6915747.61
#Sta/Elev= 30
  3343.1  464.75  3491.1  462.79  3682.3  458.37  3943.9  447.34    4115  441.77
  4335.4  438.23    4598  437.09  4698.6  437.78  4738.9  436.95    4749  435.77
    4759  437.24  4807.1  437.45  4906.5  438.04  4960.3  437.89  4969.2  434.96
  4973.1  434.96  4976.3  431.98  4977.6  431.48  4984.6  431.98  4990.6  437.48
    5011  439.53  5096.6   442.2  5191.2  444.64  5254.9   444.5    5265  446.16
  5361.7  447.16  5397.2  448.77    5509  446.56  5661.4  450.08  5819.5  450.45
#Mann= 7 ,-1 , 0
  3343.1     .05       0  4335.4     .12       0  4807.1     .05       0
  4906.5     .12       0  4976.3     .07       0  4984.6     .12       0
  5096.6     .05       0
Bank Sta=4976.3,4984.6
XS Rating Curve= 0 ,0
Exp/Cntr=0.3,0.1

Type RM Length L Ch R = 1 ,4465    ,701,701,701
BEGIN DESCRIPTION:
Mapping XS 30629899
END DESCRIPTION:
XS GIS Cut Line= 3
      2740671.12      6915329.59       2739434.1      6915051.81
      2738440.59      6915238.36
#Sta/Elev= 30
  3734.1   466.3  3887.7  465.64  3979.4  463.41  4022.8  460.16  4190.3  453.55
    4298  447.23  4446.5  440.61  4538.8   438.1  4702.7  436.04  4733.5  435.65
  4751.7  431.92  4774.5  435.41  4784.7   435.1    4795  432.54  4800.2  433.44
  4805.3  431.46    4836  435.73  5001.9  435.85  5010.2  429.08  5020.8  428.62
    5022  428.12  5029.3  428.62  5040.7  430.83  5050.9  435.27    5055  435.62
  5077.6  436.87  5223.8  435.45  5427.3   438.4  5691.9  444.92  6012.8  446.76
#Mann= 5 ,-1 , 0
  3734.1     .05       0  4702.7     .12       0  5020.8     .07       0
  5029.3     .12       0    5055     .05       0
Bank Sta=5020.8,5029.3
XS Rating Curve= 0 ,0
Exp/Cntr=0.3,0.1

Type RM Length L Ch R = 1 ,3764    ,856,856,856
BEGIN DESCRIPTION:
Mapping XS 277d162b
END DESCRIPTION:
XS GIS Cut Line= 3
      2740744.89      6915030.12       2739616.4      6914526.64
      2738610.27      6914721.79
#Sta/Elev= 30
  3693.1  463.01  3752.2  463.27  4024.1   457.8  4425.5  443.34    4464     441
  4687.4  437.59  4730.4  437.48  4794.7  434.38  4948.8  434.71  5000.5  433.39
  5006.4  427.47  5007.7  426.97    5015  427.47  5020.9  429.71  5033.3  429.88
  5061.6  433.27  5102.4   433.7  5112.6  430.05  5122.8  429.23  5145.9  432.81
  5163.5  434.45  5188.5  433.53  5204.3  434.92  5224.6  433.44  5265.4   433.2
  5479.3  434.47  5632.1  440.78  5664.2  440.55  5693.2   442.6  5953.7  445.54
#Mann= 7 ,-1 , 0
  3693.1     .05       0  4687.4     .12       0  4794.7      .1       0
  4948.8     .12       0  5006.4     .07       0    5015     .12       0
  5145.9     .05       0
Bank Sta=5006.4,5015
XS Rating Curve= 0 ,0
Exp/Cntr=0.3,0.1

Type RM Length L Ch R = 1 ,2908    ,1356,1356,1356
BEGIN DESCRIPTION:
Mapping XS 19b18c2d
END DESCRIPTION:
XS GIS Cut Line= 3
      2740525.24      6914759.85      2739448.86      6913850.13
      2738060.45      6913864.01
#Sta/Elev= 30
  3567.8  457.33  3686.7  455.54    4013  446.43  4084.5  442.99  4119.6  443.49
  4283.4  438.33    4546  433.05  4560.3  433.84  4574.6  432.66  4582.6  434.15
  4590.3  434.05  4630.6  433.74  4638.3  432.36  4644.8  433.67  4793.3  433.79
  4840.3  431.64    4990  432.01    5000   431.6  5005.7  426.66  5006.9  426.16
  5014.3  426.66    5020   430.4    5030   432.5    5090  431.13    5520  429.17
    5540  430.49    5640  431.39    5660  432.98    6070  443.95  6365.6  445.78
#Mann= 7 ,-1 , 0
  3567.8     .05       0  4582.6     .12       0  4590.3     .05       0
  4793.3     .12       0  4840.3     .05       0  5005.7     .04       0
  5014.3     .05       0
Bank Sta=5005.7,5014.3
XS Rating Curve= 0 ,0
Exp/Cntr=0.3,0.1

Type RM Length L Ch R = 1 ,1552    ,0,0,0
BEGIN DESCRIPTION:
Andy Branch 1.0
END DESCRIPTION:
XS GIS Cut Line= 3
      2740205.82      6914023.77       2739482.2      6912813.62
      2737929.54      6913252.48
#Sta/Elev= 30
    3590  439.67    3642  439.97  3737.3  438.21    3891  433.86  4124.4  431.35
  4198.4  432.12  4816.6  429.29  4956.4   429.7  4962.8   428.6  4984.2  429.04
  4991.4  425.79  4998.6  428.69    5005  429.22  5005.8  424.14  5007.1  423.64
  5014.5  424.14  5016.8  429.05  5027.2  430.47  5078.1  428.72  5505.3  428.66
  5527.4  426.95  5546.8  428.24  5567.6  427.29    5578  429.09  5619.7  428.71
    5765  428.52  5852.2  430.76  5966.2  433.71  6078.5  438.99  6613.5   443.5
#Mann= 5 ,-1 , 0
    3590     .05       0  5005.8     .05       0  5014.5     .05       0
  5619.7     .12       0  5852.2     .05       0
Bank Sta=5005.8,5014.5
XS Rating Curve= 0 ,0
Exp/Cntr=0.3,0.1

Chan Stop Cuts=-1
Use User Specified Reach Order=0
Composite Channel Slope=5