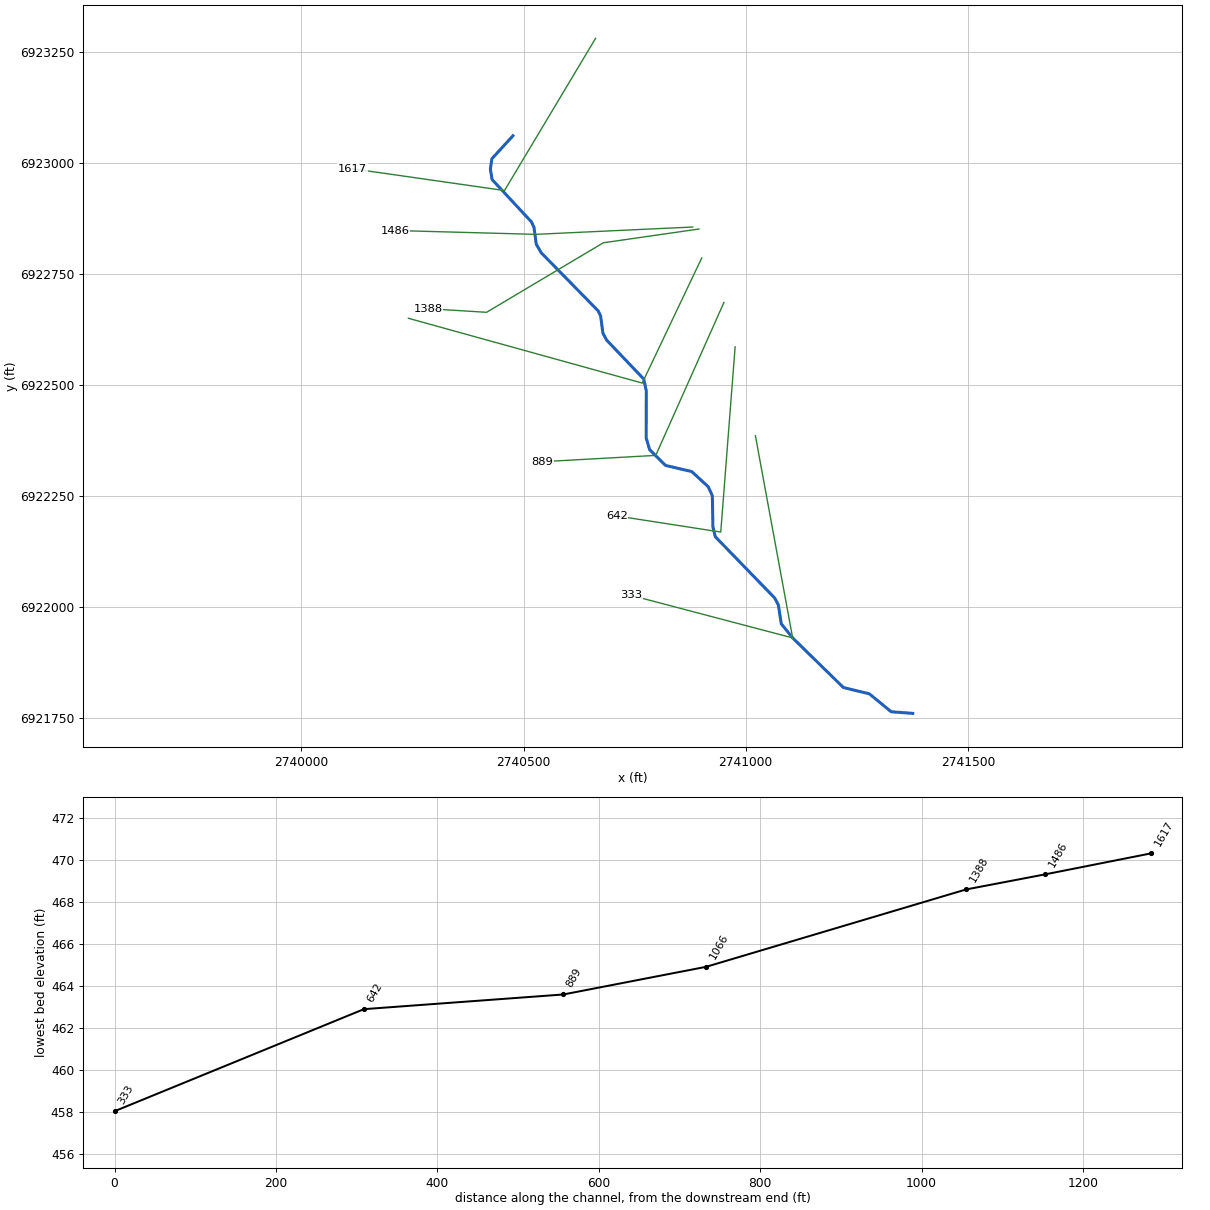
--- Andy T1.prj (project) ---

Proj Title=Andy T1 Base Level Engineering
Current Plan=p01
Default Exp/Contr=0.3,0.1
English Units
Geom File=g01
Flow File=f01
Plan File=p01
BEGIN DESCRIPTION:
Andy T1
END DESCRIPTION:

--- Andy T1.p01 (plan) ---

Plan Title=Multiple Run
Short Identifier=Multiple
Geom File=g01
Flow File=f01
Subcritical Flow
K Sum by GR= 0
Std Step Tol= 0.01
Critical Tol= 0.01
Num of Std Step Trials= 20
Max Error Tol= 0.3
Flow Tol Ratio= 0.001
Split Flow NTrial= 30
Split Flow Tol= 0.02
Split Flow Ratio= 0.02
Log Output Level= 0
Friction Slope Method= 1
Unsteady Friction Slope Method= 2
Unsteady Bridges Friction Slope Method= 1
Parabolic Critical Depth
Global Vel Dist=  1 , 1 , 1
Global Log Level= 0
CheckData=True
Encroach Param= -1, 0, 0, 0
BEGIN DESCRIPTION:
Multiple Run
END DESCRIPTION:

--- Andy T1.f01 (steady flow) ---

Flow Title=Multiple
Number of Profiles=7
Profile Names=10-year,25-year,50-year,1pct_min,100-year,1pct_plu,500-year
River Rch & RM= Andy T1,Reach-1,1617
      92     108     120      66     132     264     161
Boundary for River Rch & Prof#=Andy T1,Reach-1,1
Up Type=0
Dn Type=3
Dn Slope=0.005
Boundary for River Rch & Prof#=Andy T1,Reach-1,2
Up Type=0
Dn Type=3
Dn Slope=0.005
Boundary for River Rch & Prof#=Andy T1,Reach-1,3
Up Type=0
Dn Type=3
Dn Slope=0.005
Boundary for River Rch & Prof#=Andy T1,Reach-1,4
Up Type=0
Dn Type=3
Dn Slope=0.005
Boundary for River Rch & Prof#=Andy T1,Reach-1,5
Up Type=0
Dn Type=3
Dn Slope=0.005
Boundary for River Rch & Prof#=Andy T1,Reach-1,6
Up Type=0
Dn Type=3
Dn Slope=0.005
Boundary for River Rch & Prof#=Andy T1,Reach-1,7
Up Type=0
Dn Type=3
Dn Slope=0.005

--- Andy T1.g01 (geometry) ---

Geom Title=Existing Conditions

River Reach=Andy T1,Reach-1
Reach XY= 30
      2740476.00      6923061.00      2740428.67      6923009.38
      2740425.28      6922985.90      2740429.09      6922962.58
      2740517.82      6922867.04      2740523.46      6922854.95
      2740528.53      6922817.05      2740539.63      6922797.79
      2740667.84      6922667.05      2740673.47      6922654.95
      2740678.54      6922617.05      2740686.80      6922601.33
      2740770.52      6922513.44      2740776.27      6922486.11
      2740775.94      6922380.89      2740783.70      6922354.53
      2740819.64      6922319.03      2740878.55      6922305.25
      2740915.61      6922271.10      2740924.90      6922250.67
      2740926.14      6922181.06      2740931.53      6922158.58
      2741065.22      6922020.68      2741073.46      6922004.95
      2741079.98      6921962.65      2741105.61      6921930.84
      2741219.94      6921819.13      2741278.24      6921805.03
      2741327.49      6921764.60      2741376.00      6921761.00

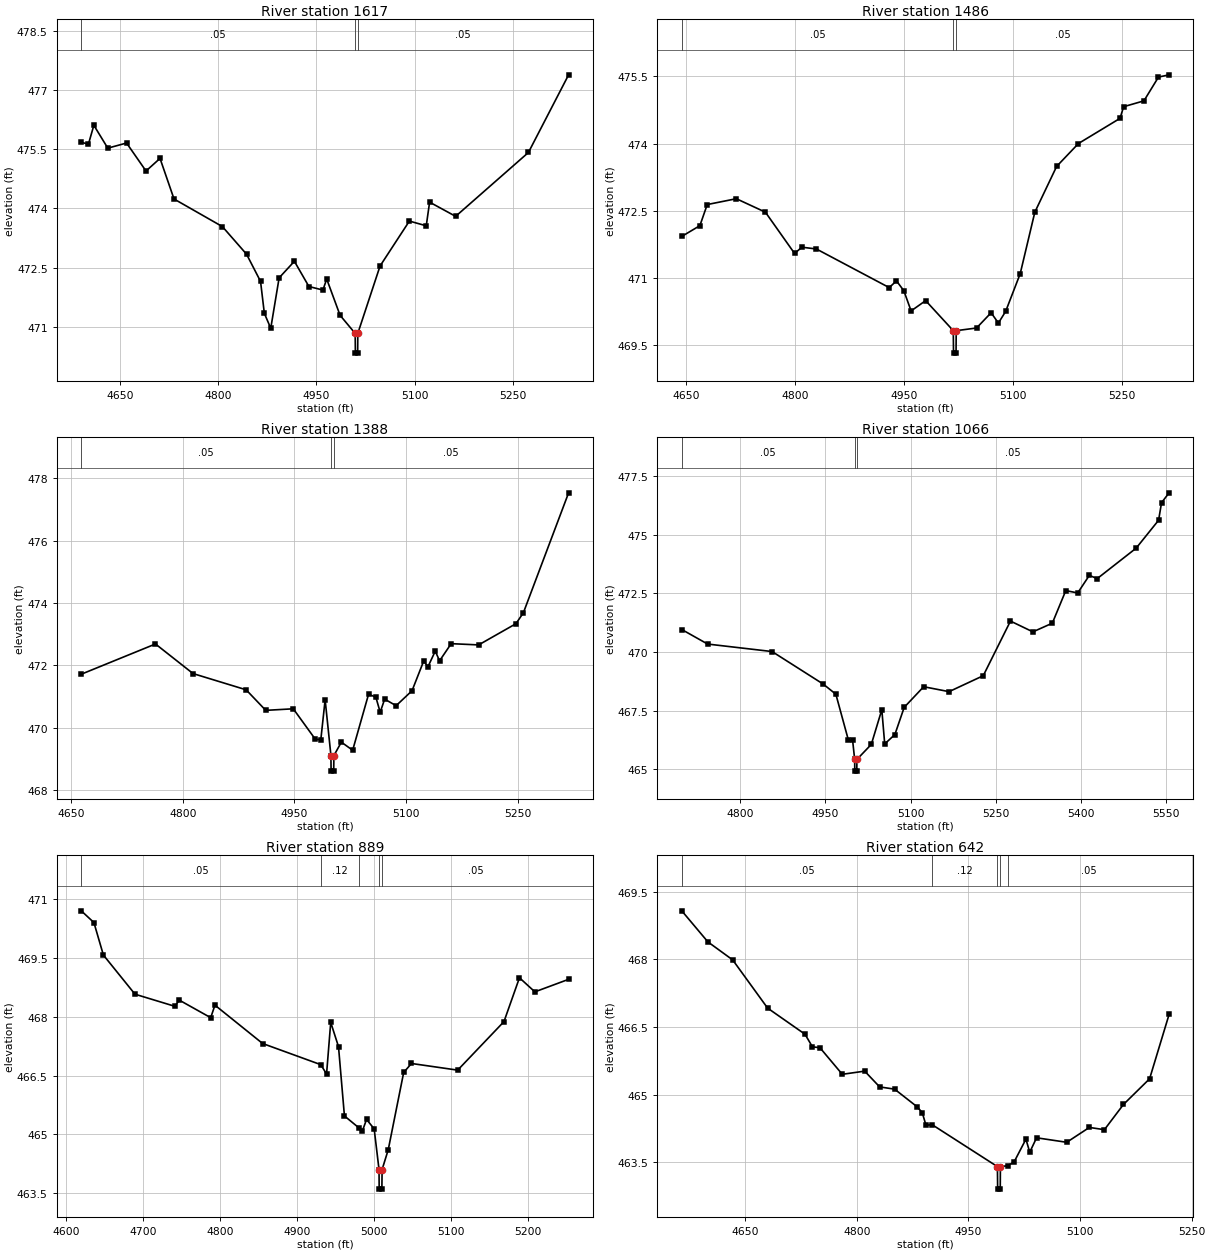
Type RM Length L Ch R = 1,1617,131,131,131
BEGIN DESCRIPTION:
Andy T1 0.0
END DESCRIPTION:
XS GIS Cut Line= 3
      2740662.07      6923280.36      2740457.06      6922937.79
      2740115.18      6922986.78
#Sta/Elev= 30
  4590.8  475.68  4601.7  475.63  4610.0  476.11  4631.3  475.53  4660.0  475.66
  4689.7  474.95  4711.1  475.27  4732.5  474.24  4806.4  473.54  4843.3  472.84
  4864.7  472.15  4870.5  471.34  4880.3  470.96  4893.1  472.24  4916.4  472.66
  4938.6  472.02  4960.0  471.93  4965.8  472.21  4986.2  471.29  5009.3  470.83
  5009.6  470.33  5013.1  470.33  5013.3  470.83  5047.3  472.54  5092.1  473.68
  5117.9  473.56  5123.0  474.16  5162.8  473.80  5274.0  475.42  5335.4  477.39
#Mann=3,-1,0
  4590.8    0.05       0  5009.3    0.04       0  5013.3    0.05       0
Bank Sta=5009.3,5013.3
Exp/Cntr=0.3,0.1

Type RM Length L Ch R = 1,1486,98,98,98
BEGIN DESCRIPTION:
Mapping XS 34d1408d
END DESCRIPTION:
XS GIS Cut Line= 3
      2740880.92      6922855.70      2740527.31      6922839.17
      2740211.42      6922847.78
#Sta/Elev= 30
  4644.4  471.93  4669.3  472.17  4679.4  472.64  4719.4  472.77  4759.4  472.47
  4799.5  471.55  4809.5  471.69  4829.5  471.65  4929.6  470.79  4939.6  470.94
  4949.7  470.72  4959.7  470.27  4979.7  470.50  5017.7  469.83  5018.0  469.33
  5021.5  469.33  5021.7  469.83  5049.7  469.89  5069.7  470.23  5079.7  470.00
  5089.7  470.26  5109.7  471.10  5129.8  472.47  5159.8  473.49  5189.8  474.00
  5246.9  474.56  5251.9  474.82  5279.8  474.95  5299.8  475.48  5314.4  475.53
#Mann=3,-1,0
  4644.4    0.05       0  5017.7    0.04       0  5021.7    0.05       0
Bank Sta=5017.7,5021.7
Exp/Cntr=0.3,0.1

Type RM Length L Ch R = 1,1388,322,322,322
BEGIN DESCRIPTION:
Mapping XS 30c9d47c
END DESCRIPTION:
XS GIS Cut Line= 4
      2740894.69      6922851.18      2740679.48      6922820.19
      2740416.70      6922663.70      2740285.34      6922671.87
#Sta/Elev= 30
  4663.7  471.72  4763.4  472.69  4813.9  471.74  4885.2  471.22  4911.6  470.56
  4948.6  470.61  4978.3  469.63  4985.6  469.62  4991.4  470.90  4999.2  469.11
  4999.4  468.61  5002.9  468.61  5003.2  469.11  5013.2  469.54  5028.4  469.28
  5049.8  471.08  5059.6  470.98  5065.4  470.50  5071.4  470.92  5086.8  470.71
  5108.2  471.19  5123.8  472.14  5129.6  471.96  5139.4  472.46  5145.2  472.15
  5160.8  472.70  5197.7  472.66  5247.8  473.34  5257.8  473.69  5318.6  477.54
#Mann=3,-1,0
  4663.7    0.05       0  4999.2    0.04       0  5003.2    0.05       0
Bank Sta=4999.2,5003.2
Exp/Cntr=0.3,0.1

Type RM Length L Ch R = 1,1066,177,177,177
BEGIN DESCRIPTION:
Mapping XS 8d3c36c7
END DESCRIPTION:
XS GIS Cut Line= 3
      2740901.01      6922786.02      2740767.08      6922504.45
      2740240.70      6922650.27
#Sta/Elev= 30
  4697.2  470.96  4742.7  470.34  4856.2  470.02  4946.4  468.63  4968.5  468.20
  4990.7  466.23  4998.0  466.23  5001.6  465.42  5001.8  464.92  5005.3  464.92
  5005.6  465.42  5030.9  466.06  5049.4  467.54  5054.5  466.08  5072.4  466.48
  5088.8  467.64  5123.1  468.52  5167.8  468.31  5228.0  468.99  5275.9  471.32
  5315.4  470.86  5349.6  471.23  5373.3  472.62  5394.3  472.52  5414.8  473.27
  5428.6  473.13  5497.2  474.43  5536.7  475.62  5541.9  476.37  5555.2  476.79
#Mann=3,-1,0
  4697.2    0.05       0  5001.6    0.04       0  5005.6    0.05       0
Bank Sta=5001.6,5005.6
Exp/Cntr=0.3,0.1

Type RM Length L Ch R = 1,889,247,247,247
BEGIN DESCRIPTION:
Mapping XS fa12d417
END DESCRIPTION:
XS GIS Cut Line= 3
      2740950.99      6922685.97      2740797.52      6922341.67
      2740542.27      6922327.49
#Sta/Elev= 30
  4620.0  470.71  4636.4  470.41  4648.7  469.58  4689.7  468.58  4741.6  468.27
  4747.1  468.43  4788.0  467.98  4793.5  468.30  4855.4  467.32  4930.9  466.78
  4938.4  466.54  4943.8  467.86  4953.9  467.24  4961.6  465.47  4980.1  465.17
  4984.8  465.08  4990.3  465.38  5000.2  465.14  5006.5  464.10  5006.7  463.60
  5010.2  463.60  5010.5  464.10  5018.5  464.61  5038.5  466.58  5048.6  466.81
  5108.6  466.64  5168.7  467.88  5188.8  469.00  5208.8  468.64  5252.6  468.96
#Mann=5,-1,0
  4620.0    0.05       0  4930.9    0.12       0  4980.1    0.05       0
  5006.5    0.04       0  5010.5    0.05       0
Bank Sta=5006.5,5010.5
Exp/Cntr=0.3,0.1

Type RM Length L Ch R = 1,642,309,309,309
BEGIN DESCRIPTION:
Mapping XS 5d58cbef
END DESCRIPTION:
XS GIS Cut Line= 3
      2740976.16      6922586.00      2740943.79      6922169.10
      2740710.14      6922205.34
#Sta/Elev= 30
  4565.0  469.08  4600.1  468.39  4633.4  467.99  4680.3  466.92  4730.5  466.34
  4740.5  466.06  4750.6  466.04  4780.6  465.45  4810.7  465.52  4830.8  465.17
  4850.9  465.12  4881.0  464.73  4888.0  464.60  4893.0  464.32  4901.4  464.33
  4989.0  463.40  4989.3  462.90  4992.8  462.90  4993.0  463.40  5002.6  463.42
  5011.3  463.50  5027.3  464.01  5032.4  463.72  5041.6  464.04  5082.1  463.94
  5112.5  464.27  5132.7  464.22  5158.3  464.78  5193.4  465.35  5219.6  466.78
#Mann=5,-1,0
  4565.0    0.05       0  4901.4    0.12       0  4989.0    0.07       0
  4993.0    0.12       0  5002.6    0.05       0
Bank Sta=4989,4993
Exp/Cntr=0.3,0.1

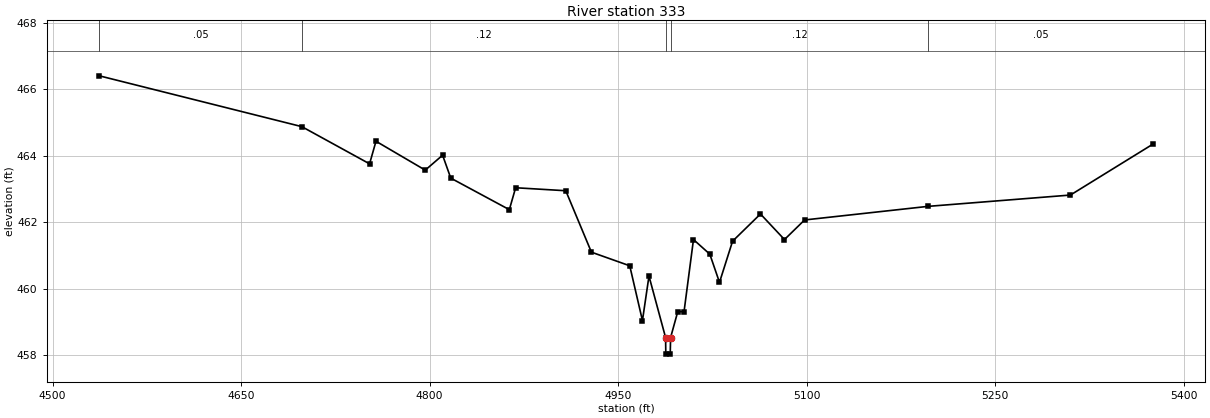
Type RM Length L Ch R = 1,333,0,0,0
BEGIN DESCRIPTION:
Andy T1 1.0
END DESCRIPTION:
XS GIS Cut Line= 3
      2741021.76      6922385.98      2741105.61      6921930.84
      2740742.70      6922026.45
#Sta/Elev= 30
  4537.2  466.41  4698.3  464.88  4752.2  463.76  4757.3  464.44  4796.5  463.57
  4810.3  464.02  4816.8  463.33  4863.4  462.38  4868.4  463.04  4908.3  462.95
  4928.7  461.10  4959.2  460.69  4969.3  459.04  4974.5  460.38  4987.7  458.53
  4987.9  458.03  4991.4  458.03  4991.7  458.53  4997.4  459.31  5002.4  459.31
  5009.9  461.48  5022.9  461.04  5030.6  460.19  5041.0  461.43  5063.2  462.25
  5082.3  461.48  5098.3  462.07  5196.7  462.48  5309.8  462.82  5375.3  464.35
#Mann=5,-1,0
  4537.2    0.05       0  4698.3    0.12       0  4987.7    0.07       0
  4991.7    0.12       0  5196.7    0.05       0
Bank Sta=4987.7,4991.7
Exp/Cntr=0.3,0.1

Chan Stop Cuts=-1