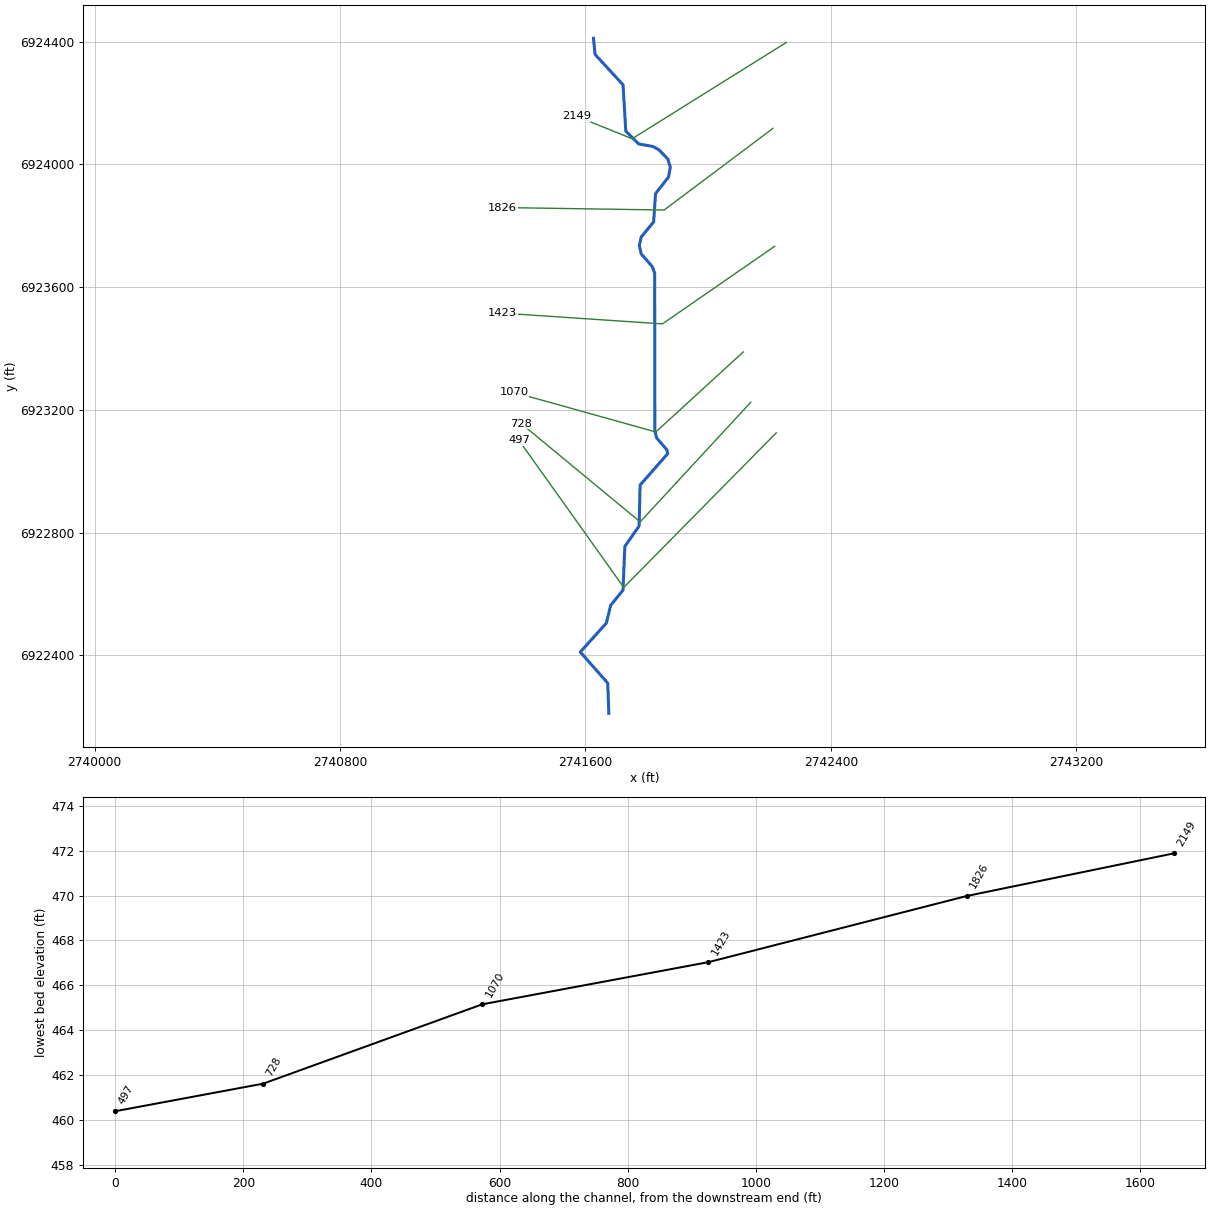
--- Andy T2.prj (project) ---

Proj Title=Andy T2 Base Level Engineering
Current Plan=p01
Default Exp/Contr=0.3,0.1
English Units
Geom File=g01
Flow File=f01
Plan File=p01
BEGIN DESCRIPTION:
Andy T2
END DESCRIPTION:

--- Andy T2.p01 (plan) ---

Plan Title=Multiple Run
Short Identifier=Multiple
Geom File=g01
Flow File=f01
Subcritical Flow
K Sum by GR= 0
Std Step Tol= 0.01
Critical Tol= 0.01
Num of Std Step Trials= 20
Max Error Tol= 0.3
Flow Tol Ratio= 0.001
Split Flow NTrial= 30
Split Flow Tol= 0.02
Split Flow Ratio= 0.02
Log Output Level= 0
Friction Slope Method= 1
Unsteady Friction Slope Method= 2
Unsteady Bridges Friction Slope Method= 1
Parabolic Critical Depth
Global Vel Dist=  1 , 1 , 1
Global Log Level= 0
CheckData=True
Encroach Param= -1, 0, 0, 0
BEGIN DESCRIPTION:
Multiple Run
END DESCRIPTION:

--- Andy T2.f01 (steady flow) ---

Flow Title=Multiple
Number of Profiles=7
Profile Names=10-year,25-year,50-year,1pct_min,100-year,1pct_plu,500-year
River Rch & RM= Andy T2,Reach-1,2149
     210     264     305     176     352     702     466
Boundary for River Rch & Prof#=Andy T2,Reach-1,1
Up Type=0
Dn Type=3
Dn Slope=0.005
Boundary for River Rch & Prof#=Andy T2,Reach-1,2
Up Type=0
Dn Type=3
Dn Slope=0.005
Boundary for River Rch & Prof#=Andy T2,Reach-1,3
Up Type=0
Dn Type=3
Dn Slope=0.005
Boundary for River Rch & Prof#=Andy T2,Reach-1,4
Up Type=0
Dn Type=3
Dn Slope=0.005
Boundary for River Rch & Prof#=Andy T2,Reach-1,5
Up Type=0
Dn Type=3
Dn Slope=0.005
Boundary for River Rch & Prof#=Andy T2,Reach-1,6
Up Type=0
Dn Type=3
Dn Slope=0.005
Boundary for River Rch & Prof#=Andy T2,Reach-1,7
Up Type=0
Dn Type=3
Dn Slope=0.005

--- Andy T2.g01 (geometry) ---

Geom Title=Existing Conditions

River Reach=Andy T2,Reach-1
Reach XY= 30
      2741626.00      6924411.00      2741631.33      6924358.49
      2741722.46      6924259.53      2741731.37      6924108.30
      2741773.45      6924066.75      2741820.14      6924058.52
      2741839.69      6924047.51      2741868.63      6924017.34
      2741876.44      6923990.97      2741870.66      6923958.85
      2741828.38      6923905.04      2741822.11      6923812.58
      2741781.37      6923763.18      2741775.60      6923736.00
      2741781.38      6923708.82      2741817.81      6923667.08
      2741825.46      6923645.79      2741826.19      6923130.98
      2741832.03      6923108.55      2741864.66      6923070.85
      2741868.19      6923057.59      2741778.08      6922955.14
      2741774.77      6922821.51      2741728.27      6922755.06
      2741722.24      6922612.56      2741682.14      6922563.17
      2741667.82      6922504.94      2741583.09      6922411.00
      2741672.59      6922309.60      2741676.00      6922211.00

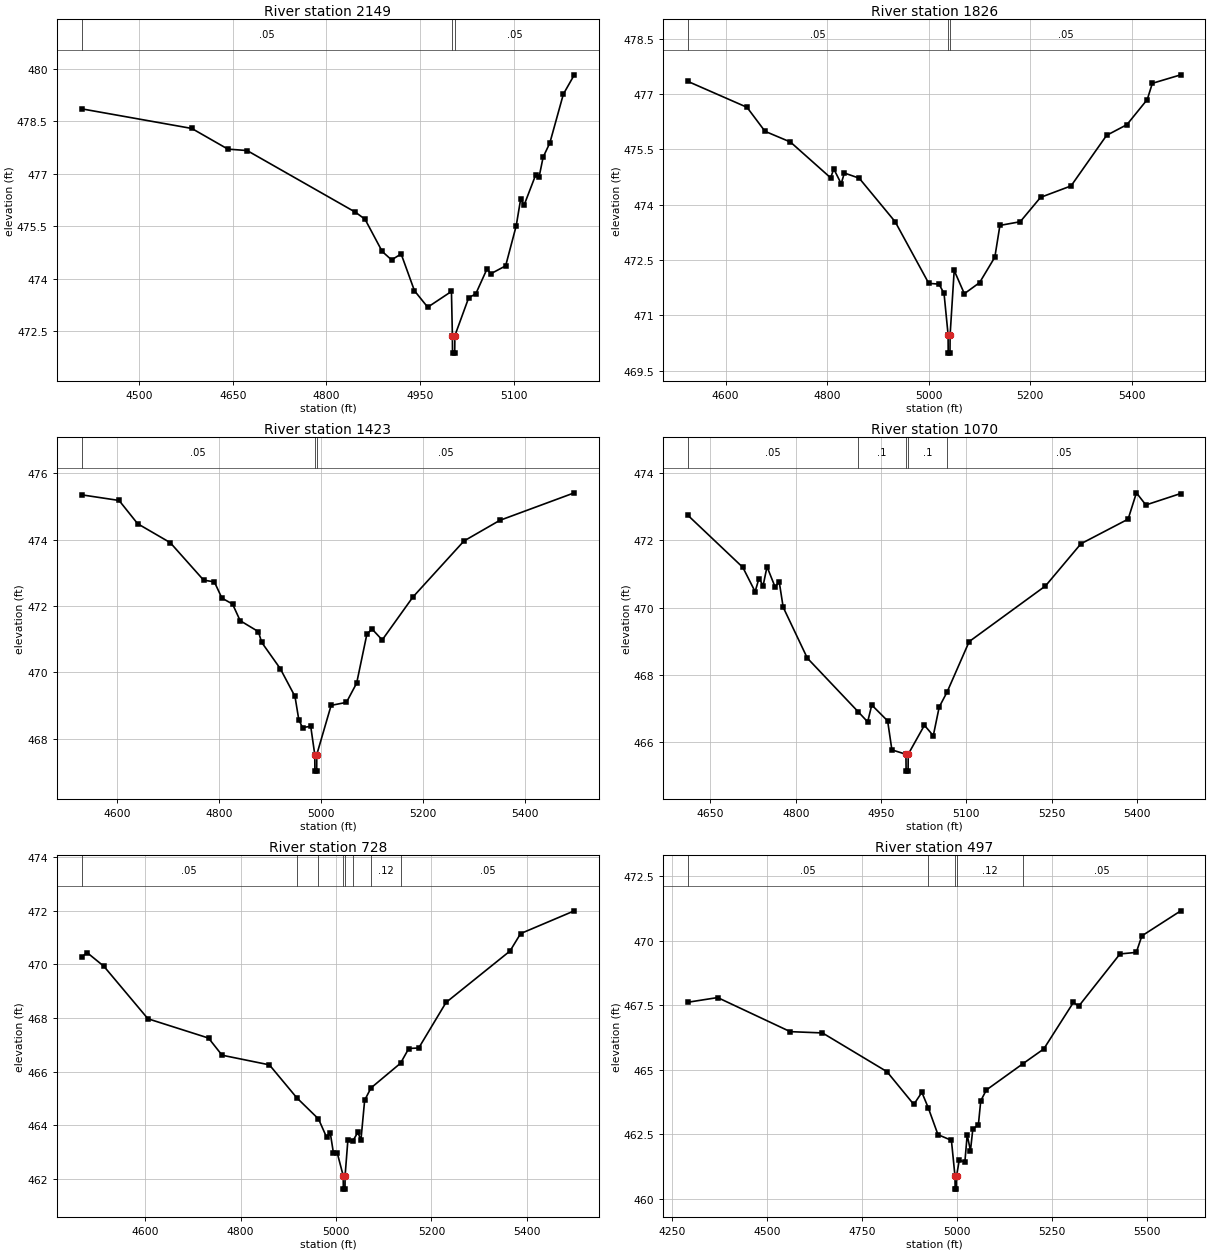
Type RM Length L Ch R = 1,2149,323,323,323
BEGIN DESCRIPTION:
Andy T2 1.0
END DESCRIPTION:
XS GIS Cut Line= 3
      2742254.11      6924397.29      2741752.04      6924083.81
      2741569.77      6924157.48
#Sta/Elev= 30
  4408.1  478.85  4584.5  478.29  4642.3  477.70  4673.0  477.66  4846.4  475.90
  4861.7  475.70  4889.2  474.78  4904.2  474.54  4919.5  474.71  4940.8  473.66
  4962.0  473.19  5000.0  473.64  5001.5  472.38  5001.7  471.88  5005.2  471.88
  5005.5  472.38  5027.6  473.46  5038.9  473.57  5057.1  474.29  5062.5  474.14
  5086.7  474.37  5103.6  475.51  5110.8  476.28  5116.2  476.10  5134.9  476.97
  5140.3  476.91  5146.7  477.47  5157.5  477.88  5179.1  479.27  5196.6  479.82
#Mann=3,-1,0
  4408.1    0.05       0  5001.5    0.04       0  5005.5    0.05       0
Bank Sta=5001.5,5005.5
Exp/Cntr=0.3,0.1

Type RM Length L Ch R = 1,1826,403,403,403
BEGIN DESCRIPTION:
Mapping XS 00a67a7c
END DESCRIPTION:
XS GIS Cut Line= 3
      2742211.15      6924117.68      2741856.19      6923851.47
      2741330.05      6923859.52
#Sta/Elev= 30
  4526.2  477.34  4642.3  476.64  4677.7  475.99  4727.7  475.70  4806.9  474.73
  4813.1  474.97  4827.7  474.57  4833.9  474.86  4863.1  474.72  4933.9  473.54
  5000.1  471.87  5020.1  471.85  5030.1  471.60  5038.1  470.48  5038.3  469.98
  5041.8  469.98  5042.1  470.48  5050.1  472.22  5070.1  471.59  5100.1  471.89
  5130.1  472.58  5140.1  473.44  5180.1  473.54  5220.1  474.20  5280.1  474.51
  5350.1  475.88  5390.1  476.17  5430.1  476.85  5440.1  477.29  5496.1  477.52
#Mann=3,-1,0
  4526.2    0.05       0  5038.1    0.04       0  5042.1    0.05       0
Bank Sta=5038.1,5042.1
Exp/Cntr=0.3,0.1

Type RM Length L Ch R = 1,1423,353,353,353
BEGIN DESCRIPTION:
Mapping XS 17775a37
END DESCRIPTION:
XS GIS Cut Line= 3
      2742216.52      6923733.17      2741850.81      6923480.40
      2741330.04      6923515.30
#Sta/Elev= 30
  4530.6  475.35  4604.2  475.18  4640.6  474.48  4704.5  473.91  4770.1  472.78
  4791.0  472.73  4805.9  472.24  4826.8  472.06  4841.7  471.56  4877.5  471.23
  4883.8  470.91  4920.2  470.12  4949.2  469.28  4956.7  468.58  4964.0  468.34
  4980.1  468.38  4988.0  467.53  4988.3  467.03  4991.8  467.03  4992.0  467.53
  5020.1  469.01  5050.1  469.10  5070.2  469.68  5090.2  471.15  5100.3  471.31
  5120.3  470.98  5180.4  472.27  5280.7  473.96  5350.8  474.58  5497.1  475.41
#Mann=3,-1,0
  4530.6    0.05       0  4988.0    0.04       0  4992.0    0.05       0
Bank Sta=4988,4992
Exp/Cntr=0.3,0.1

Type RM Length L Ch R = 1,1070,342,342,342
BEGIN DESCRIPTION:
Mapping XS 46d4fc42
END DESCRIPTION:
XS GIS Cut Line= 3
      2742114.34      6923388.99      2741829.30      6923128.16
      2741366.85      6923257.21
#Sta/Elev= 30
  4610.6  472.73  4707.0  471.19  4728.6  470.47  4735.3  470.86  4742.7  470.65
  4749.5  471.21  4763.7  470.61  4771.0  470.76  4777.9  470.01  4820.4  468.50
  4909.8  466.91  4926.5  466.61  4933.7  467.11  4961.6  466.64  4969.1  465.78
  4993.8  465.65  4994.1  465.15  4997.6  465.15  4997.8  465.65  5026.3  466.51
  5041.9  466.20  5052.3  467.05  5066.3  467.50  5105.0  468.99  5239.2  470.64
  5301.5  471.89  5384.5  472.62  5399.1  473.40  5415.7  473.04  5477.1  473.38
#Mann=5,-1,0
  4610.6    0.05       0  4909.8     0.1       0  4993.8    0.07       0
  4997.8     0.1       0  5066.3    0.05       0
Bank Sta=4993.8,4997.8
Exp/Cntr=0.3,0.1

Type RM Length L Ch R = 1,728,231,231,231
BEGIN DESCRIPTION:
Mapping XS 9bd6eac7
END DESCRIPTION:
XS GIS Cut Line= 3
      2742138.52      6923224.95      2741778.21      6922835.07
      2741391.00      6923155.05
#Sta/Elev= 30
  4466.5  470.27  4478.1  470.44  4513.3  469.93  4605.7  467.97  4732.7  467.25
  4761.1  466.61  4860.3  466.25  4917.8  465.02  4963.3  464.23  4980.5  463.54
  4987.9  463.72  4994.7  462.95  5002.8  462.95  5015.1  462.11  5015.4  461.61
  5018.9  461.61  5019.1  462.11  5025.0  463.46  5034.7  463.39  5045.8  463.73
  5052.3  463.44  5060.1  464.93  5073.5  465.39  5135.3  466.31  5152.6  466.86
  5173.5  466.88  5230.8  468.58  5364.9  470.50  5387.1  471.15  5499.7  472.00
#Mann=8,-1,0
  4466.5    0.05       0  4917.8     0.1       0  4963.3    0.12       0
  5015.1    0.07       0  5019.1    0.12       0  5034.7     0.1       0
  5073.5    0.12       0  5135.3    0.05       0
Bank Sta=5015.1,5019.1
Exp/Cntr=0.3,0.1

Type RM Length L Ch R = 1,497,0,0,0
BEGIN DESCRIPTION:
Andy T2 0.0
END DESCRIPTION:
XS GIS Cut Line= 3
      2742221.90      6923125.49      2741724.79      6922621.50
      2741382.94      6923101.27
#Sta/Elev= 30
  4292.1  467.62  4370.1  467.80  4561.1  466.48  4646.0  466.43  4815.7  464.93
  4886.4  463.66  4907.6  464.13  4924.7  463.52  4950.0  462.49  4985.4  462.27
  4994.8  460.88  4995.1  460.38  4998.6  460.38  4998.8  460.88  5006.0  461.50
  5020.8  461.43  5026.9  462.48  5035.5  461.87  5041.7  462.70  5056.4  462.88
  5062.6  463.80  5077.3  464.22  5172.8  465.23  5228.5  465.81  5306.4  467.61
  5320.7  467.47  5429.1  469.49  5472.0  469.55  5486.7  470.19  5589.1  471.16
#Mann=5,-1,0
  4292.1    0.05       0  4924.7    0.12       0  4994.8    0.07       0
  4998.8    0.12       0  5172.8    0.05       0
Bank Sta=4994.8,4998.8
Exp/Cntr=0.3,0.1

Chan Stop Cuts=-1