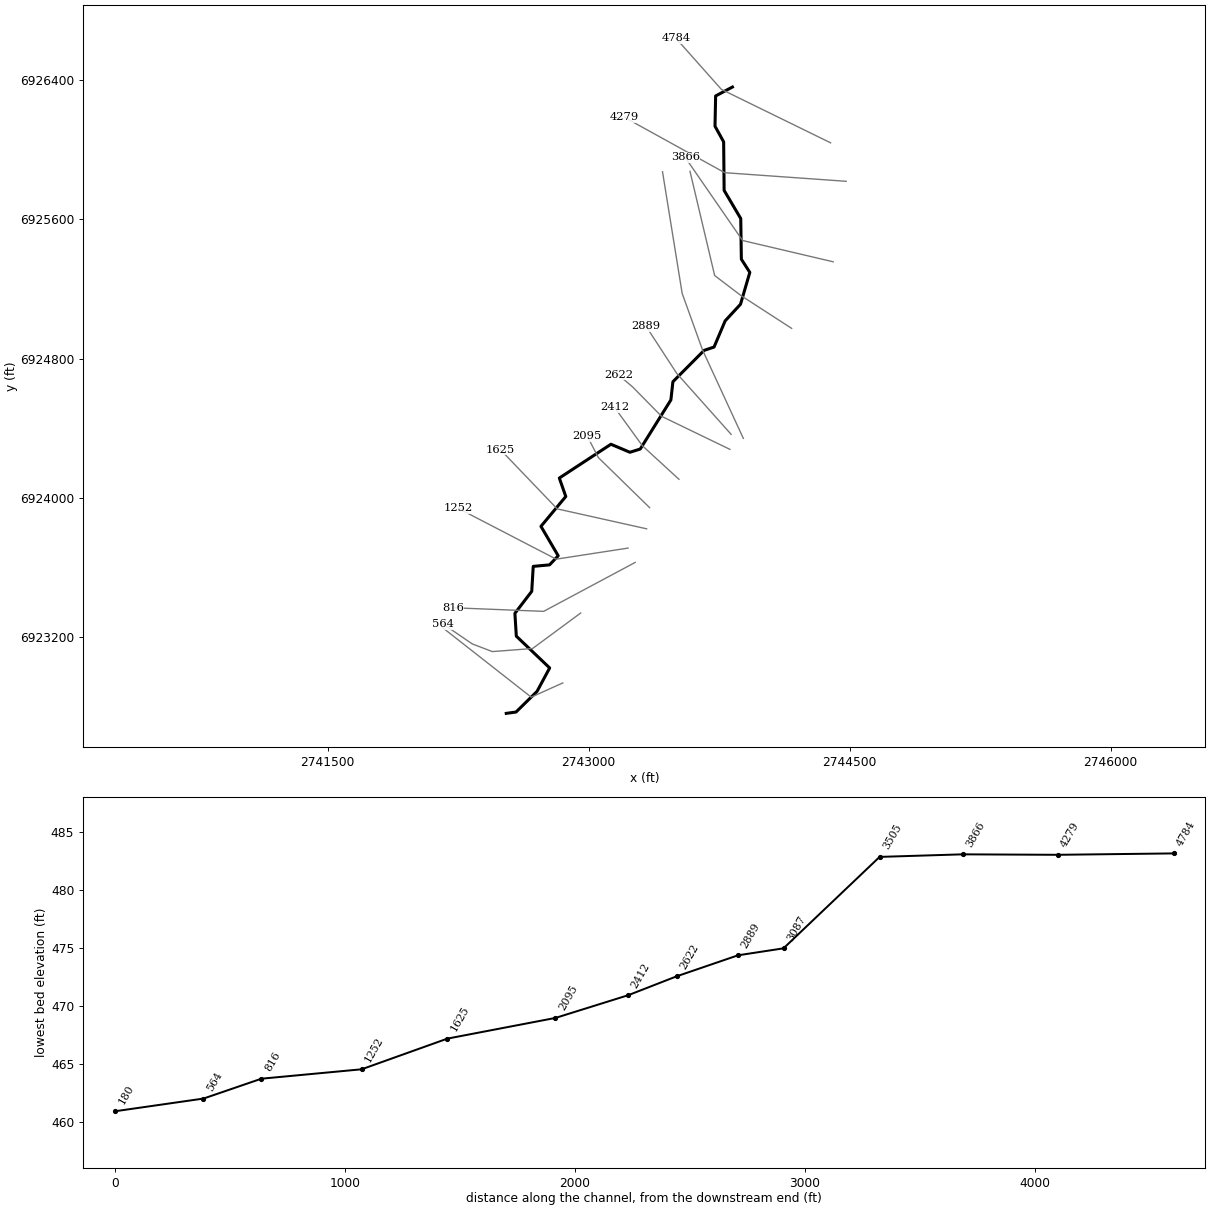
--- Andy T3.prj (project) ---

Proj Title=Andy T3 Base Level Engineering
Current Plan=p01
Default Exp/Contr=0.3,0.1
English Units
Geom File=g01
Flow File=f01
Plan File=p01
Y Axis Title=Elevation
X Axis Title(PF)=Main Channel Distance
X Axis Title(XS)=Station
BEGIN DESCRIPTION:
Andy T3
END DESCRIPTION:
DSS Export Rating Curves= 0
DSS Export Rating Curve Sorted= 0
DSS Export Volume Flow Curves= 0
DXF OffsetX= 0
DXF OffsetY= 0
DXF ScaleX= 1
DXF ScaleY= 10

--- Andy T3.p01 (plan) ---

Plan Title=Multiple Run
Short Identifier=Multiple
Geom File=g01
Flow File=f01
Subcritical Flow
K Sum by GR= 0
Std Step Tol= 0.01
Critical Tol= 0.01
Num of Std Step Trials= 20
Max Error Tol= 0.3
Flow Tol Ratio= 0.001
Split Flow NTrial= 30
Split Flow Tol= 0.02
Split Flow Ratio= 0.02
Log Output Level= 0
Friction Slope Method= 1
Unsteady Friction Slope Method= 2
Unsteady Bridges Friction Slope Method= 1
Parabolic Critical Depth
Global Vel Dist=  1 , 1 , 1
Global Log Level= 0
CheckData=True
Encroach Param= -1, 0, 0, 0
BEGIN DESCRIPTION:
Multiple Run
END DESCRIPTION:

--- Andy T3.f01 (steady flow) ---

Flow Title=Multiple
Number of Profiles=7
Profile Names=10-year,25-year,50-year,1pct_min,100-year,1pct_plu,500-year
River Rch & RM= Andy T3,Reach-1,4784
     472     624     745     443     884    1764    1245
Boundary for River Rch & Prof#=Andy T3,Reach-1,1
Up Type=0
Dn Type=3
Dn Slope=0.005
Boundary for River Rch & Prof#=Andy T3,Reach-1,2
Up Type=0
Dn Type=3
Dn Slope=0.005
Boundary for River Rch & Prof#=Andy T3,Reach-1,3
Up Type=0
Dn Type=3
Dn Slope=0.005
Boundary for River Rch & Prof#=Andy T3,Reach-1,4
Up Type=0
Dn Type=3
Dn Slope=0.005
Boundary for River Rch & Prof#=Andy T3,Reach-1,5
Up Type=0
Dn Type=3
Dn Slope=0.005
Boundary for River Rch & Prof#=Andy T3,Reach-1,6
Up Type=0
Dn Type=3
Dn Slope=0.005
Boundary for River Rch & Prof#=Andy T3,Reach-1,7
Up Type=0
Dn Type=3
Dn Slope=0.005

--- Andy T3.g01 (geometry) ---

Geom Title=Existing Conditions
Program Version=4.10

River Reach=Andy T3         ,Reach-1
Reach XY= 30
        2743826.        6926361.      2743729.37      6926309.74
       2743725.8      6926135.92      2743775.48      6926045.78
      2743778.24      6925766.93      2743873.76      6925605.07
      2743877.24       6925371.5      2743925.91      6925295.61
      2743872.38       6925112.5      2743784.16      6925017.05
      2743720.41      6924866.61      2743663.02      6924847.27
      2743483.86      6924667.17      2743472.17      6924562.59
      2743296.13      6924280.41      2743236.71      6924261.74
      2743127.64      6924307.86      2742831.01      6924113.54
      2742868.18      6924007.59      2742725.41        6923836.
       2742824.5      6923666.85       2742774.7      6923614.56
      2742681.04      6923605.92      2742672.44      6923462.48
      2742575.68      6923336.11      2742583.81      6923204.81
      2742775.46      6923022.09      2742702.99      6922887.53
      2742582.21      6922768.76        2742526.        6922761.

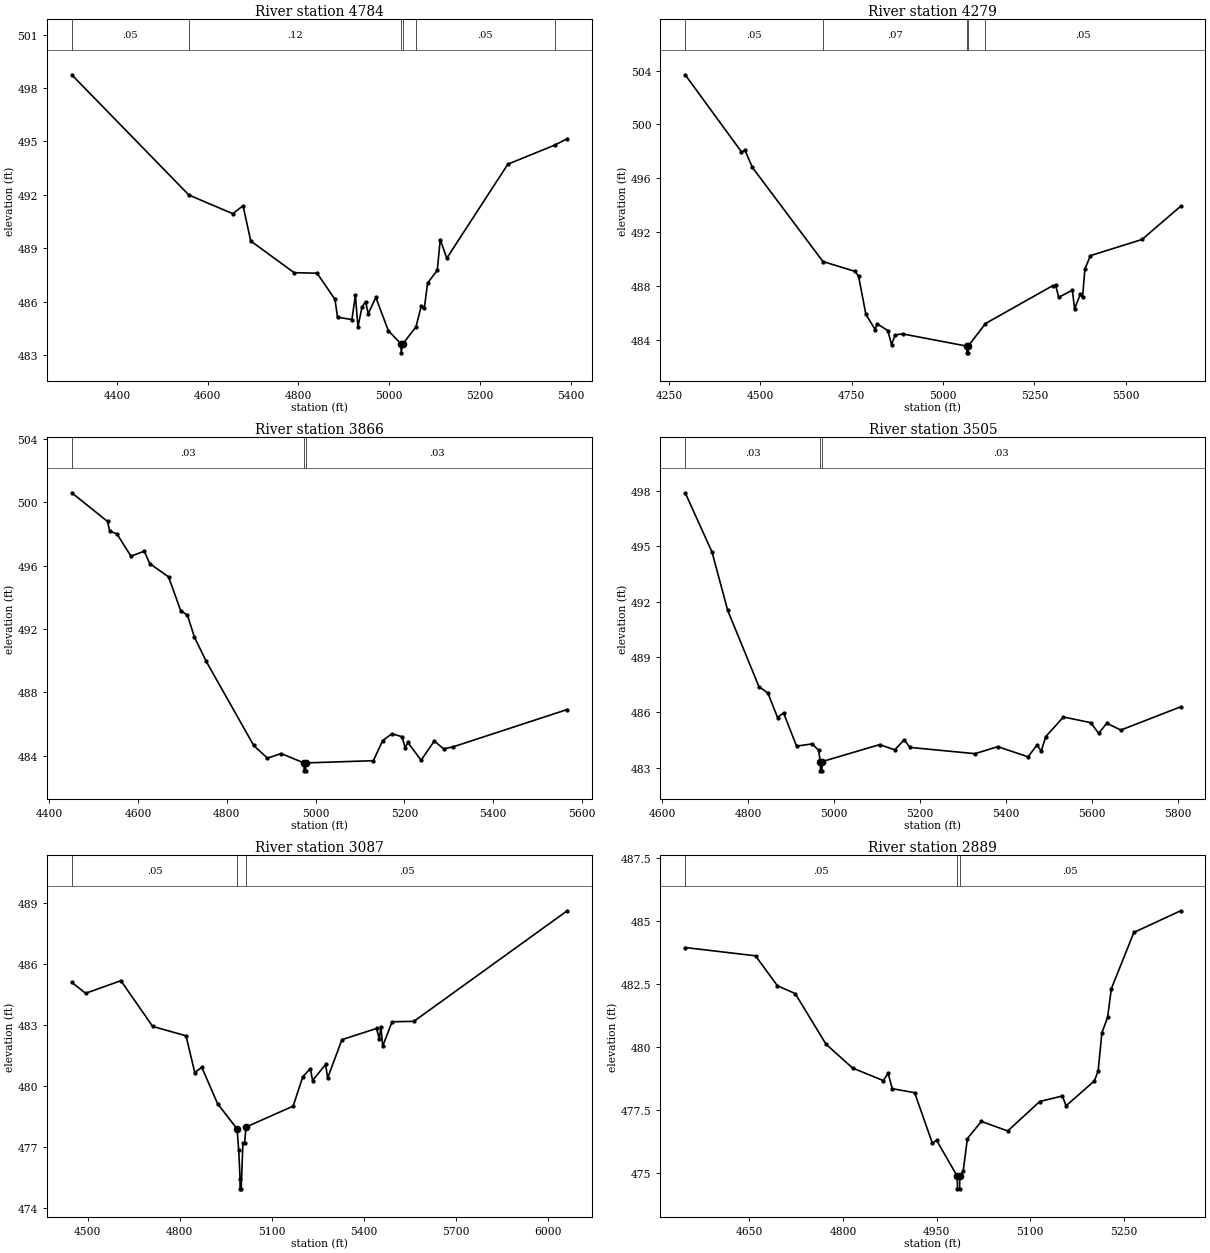
Type RM Length L Ch R = 1 ,4784    ,505,505,505
BEGIN DESCRIPTION:
Andy T3 6.0
END DESCRIPTION:
XS GIS Cut Line= 3
       2744390.4      6926040.26      2743762.12      6926347.77
      2743501.57      6926640.91
#Sta/Elev= 30
  4300.5  498.74  4558.6  491.99  4655.4  490.94  4677.9  491.39  4694.9  489.41
  4790.5  487.63  4841.1   487.6  4880.5  486.13  4886.1  485.13  4917.8     485
  4925.5  486.35  4931.1  484.58    4940   485.7    4948  486.01  4953.6  485.32
  4970.5  486.24    4998  484.38  5026.1  483.63  5026.3  483.13  5030.1  483.63
    5059  484.59  5070.7  485.76  5077.4  485.65  5084.6  487.05  5105.9  487.76
  5112.5  489.49  5126.8  488.44  5261.4  493.72  5364.6  494.79  5392.2  495.15
#Mann= 6 ,-1 , 0
  4300.5     .05       0  4558.6     .12       0  5026.1     .07       0
  5030.1     .12       0    5059     .05       0  5364.6    .075       0
Bank Sta=5026.1,5030.1
XS Rating Curve= 0 ,0
Exp/Cntr=0.3,0.1

Type RM Length L Ch R = 1 ,4279    ,413,413,413
BEGIN DESCRIPTION:
Mapping XS ceaf050a
END DESCRIPTION:
XS GIS Cut Line= 3
      2744479.58      6925819.18      2743781.63      6925868.67
      2743206.45      6926186.18
#Sta/Elev= 30
  4293.8  503.69  4447.8  497.96  4457.8  498.06  4477.8   496.8    4671   489.8
  4758.5  489.07  4768.6   488.7  4788.6  485.87    4814  484.74    4819  485.17
  4848.8  484.66  4858.8  483.62  4868.8  484.34  4888.9  484.42  5064.8  483.51
    5065  483.01  5068.5  483.01  5068.8  483.51    5116  485.19  5300.5  488.01
  5308.3  488.02  5316.6  487.14    5354  487.67  5360.1  486.29  5376.1  487.39
  5381.9  487.15  5388.3  489.25  5403.6  490.24  5544.6  491.44  5650.5  493.91
#Mann= 5 ,-1 , 0
  4293.8     .05       0    4671     .07       0  5064.8     .05       0
  5068.8     .07       0    5116     .05       0
Bank Sta=5064.8,5068.8
XS Rating Curve= 0 ,0
Exp/Cntr=0.3,0.1

Type RM Length L Ch R = 1 ,3866    ,361,361,361
BEGIN DESCRIPTION:
Mapping XS b6603b1e
END DESCRIPTION:
XS GIS Cut Line= 3
      2744405.01      6925356.52       2743884.2      6925478.91
      2743554.17      6925957.07
#Sta/Elev= 30
  4450.6   500.6  4531.2  498.79  4536.3  498.17  4552.3  498.01  4583.9   496.6
  4613.9  496.91  4626.3  496.13  4668.7  495.29  4696.1  493.15  4711.1  492.88
  4726.9  491.49  4753.5  489.96  4860.5  484.65  4891.3  483.85  4922.1  484.14
  4973.7  483.55    4974  483.05  4977.5  483.05  4977.7  483.55    5130  483.69
  5150.9  484.96  5171.9  485.39  5194.7   485.2  5201.6   484.5  5207.7  484.84
  5237.5  483.72  5267.2  484.93  5288.2  484.44  5309.1  484.56  5566.6  486.92
#Mann= 3 ,-1 , 0
  4450.6     .03       0  4973.7     .03       0  4977.7     .03       0
Bank Sta=4973.7,4977.7
XS Rating Curve= 0 ,0
Exp/Cntr=0.3,0.1

Type RM Length L Ch R = 1 ,3505    ,418,418,418
BEGIN DESCRIPTION:
Mapping XS fad58e22
END DESCRIPTION:
XS GIS Cut Line= 4
      2744166.32      6924973.84      2743876.09      6925161.71
      2743723.85      6925277.55      2743582.11      6925876.38
#Sta/Elev= 30
  4654.2   497.9  4716.7  494.68    4753  491.53  4825.6   487.4  4846.7  487.04
    4869  485.72  4882.9  485.97  4913.3  484.17  4949.5  484.29  4964.3  483.95
  4968.6  483.33  4968.9  482.83  4972.4  482.83  4972.6  483.33  5106.5  484.25
  5141.8  483.97  5163.4  484.51  5177.2   484.1  5328.4  483.76  5381.1  484.14
  5451.7  483.59  5472.2  484.22  5482.5  483.91  5492.8  484.68  5533.9  485.75
  5597.5  485.44  5616.1  484.86  5634.6  485.41  5667.5  485.04  5806.6   486.3
#Mann= 3 ,-1 , 0
  4654.2     .03       0  4968.6     .03       0  4972.6     .03       0
Bank Sta=4968.6,4972.6
XS Rating Curve= 0 ,0
Exp/Cntr=0.3,0.1

Type RM Length L Ch R = 1 ,3087    ,198,198,198
BEGIN DESCRIPTION:
Mapping XS ff1b568d
END DESCRIPTION:
XS GIS Cut Line= 4
      2743888.54      6924341.76      2743654.17      6924849.57
      2743536.98      6925175.09      2743424.13      6925873.88
#Sta/Elev= 30
  4448.6  485.12  4493.9  484.58  4608.6   485.2  4712.1  482.95  4820.6  482.49
  4849.1  480.68    4872  480.94  4923.4  479.15  4986.8  477.91  4992.3  476.85
  4996.5  475.46  4996.7  474.96  5000.2  474.96  5005.9  477.21  5011.3  477.21
    5016     478  5169.5  479.03  5200.7  480.47  5225.6  480.88  5232.6  480.29
  5275.1  481.08  5281.7  480.41  5328.3   482.3  5440.9  482.85    5450  482.33
  5455.1  482.94  5461.1  481.98  5491.5  483.18  5562.4   483.2  6061.7  488.64
#Mann= 3 ,-1 , 0
  4448.6     .05       0  4986.8     .04       0    5016     .05       0
Bank Sta=4986.8,5016
XS Rating Curve= 0 ,0
Exp/Cntr=0.3,0.1

Type RM Length L Ch R = 1 ,2889    ,267,267,267
BEGIN DESCRIPTION:
Mapping XS 4ac2f2ab
END DESCRIPTION:
XS GIS Cut Line= 3
      2743818.59      6924364.74      2743505.38      6924715.72
      2743328.92      6924986.84
#Sta/Elev= 30
  4547.2  483.95  4659.9  483.62    4695  482.43  4723.5  482.12  4772.8  480.11
  4815.4  479.16  4864.8  478.66  4872.3  478.96    4879  478.34  4914.9  478.18
  4943.3  476.17    4950  476.29  4983.2  474.86  4983.4  474.36  4986.9  474.36
  4987.2  474.86  4992.7  475.07  4999.4  476.36  5021.8  477.04    5064  476.66
  5115.3  477.83  5151.6  478.05  5157.5  477.66  5202.9  478.65  5208.9  479.04
  5214.9  480.56    5224  481.17    5230  482.31  5266.2  484.55  5341.1  485.41
#Mann= 3 ,-1 , 0
  4547.2     .05       0  4983.2     .04       0  4987.2     .05       0
Bank Sta=4983.2,4987.2
XS Rating Curve= 0 ,0
Exp/Cntr=0.3,0.1

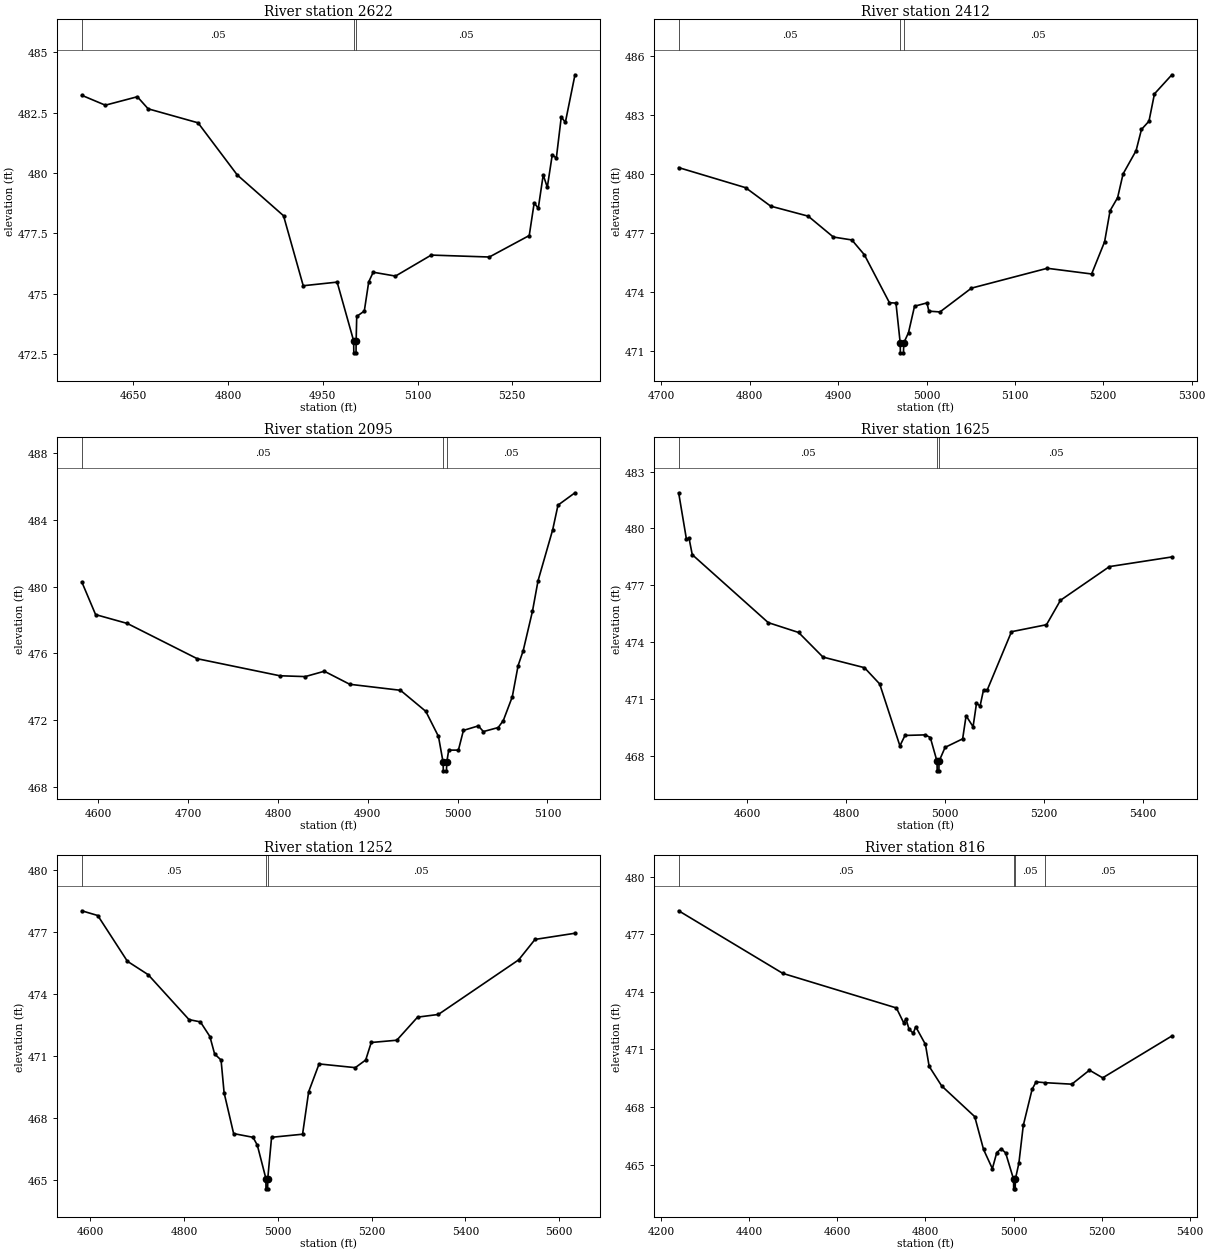
Type RM Length L Ch R = 1 ,2622    ,210,210,210
BEGIN DESCRIPTION:
Mapping XS 8bd4bfe8
END DESCRIPTION:
XS GIS Cut Line= 4
      2743811.71      6924278.39      2743418.49      6924468.49
      2743251.82      6924637.76      2743170.31      6924706.59
#Sta/Elev= 30
  4568.3  483.22  4605.6  482.81  4656.3  483.16  4673.4  482.66  4752.4  482.08
  4814.5  479.92  4887.8  478.23    4919  475.33  4972.7  475.48  4998.8  473.05
  4999.1  472.55  5002.6  472.55  5002.8  473.05  5003.7  474.06  5015.7  474.28
  5022.7  475.49  5029.8  475.89  5065.1  475.73  5121.7   476.6  5213.7  476.52
  5276.9  477.41  5284.7  478.76  5291.2  478.54    5299  479.92  5305.5  479.41
  5313.3  480.75  5319.8  480.62  5327.6  482.32  5334.1   482.1  5349.3  484.07
#Mann= 3 ,-1 , 0
  4568.3     .05       0  4998.8     .04       0  5002.8     .05       0
Bank Sta=4998.8,5002.8
XS Rating Curve= 0 ,0
Exp/Cntr=0.3,0.1

Type RM Length L Ch R = 1 ,2412    ,317,317,317
BEGIN DESCRIPTION:
Mapping XS 39a53dbb
END DESCRIPTION:
XS GIS Cut Line= 3
      2743518.55      6924106.42      2743308.77      6924298.84
      2743148.14      6924520.13
#Sta/Elev= 30
  4719.5  480.35  4795.2  479.33  4823.6  478.39  4866.1  477.88  4894.5  476.82
  4915.5  476.67  4929.6  475.92    4958  473.48  4965.4  473.46  4970.2  471.43
  4970.4  470.93  4973.9  470.93  4974.2  471.43  4979.6  471.96  4986.4   473.3
  5000.5  473.47  5002.6  473.05  5015.2  473.01  5050.8  474.22  5136.6  475.23
  5186.8  474.94  5201.5  476.58  5207.7  478.16  5216.2  478.82  5222.4  480.03
  5237.1  481.21  5243.2  482.29  5251.7  482.71  5257.9   484.1  5277.6  485.07
#Mann= 3 ,-1 , 0
  4719.5     .05       0  4970.2     .04       0  4974.2     .05       0
Bank Sta=4970.2,4974.2
XS Rating Curve= 0 ,0
Exp/Cntr=0.3,0.1

Type RM Length L Ch R = 1 ,2095    ,470,470,470
BEGIN DESCRIPTION:
Mapping XS c902f081
END DESCRIPTION:
XS GIS Cut Line= 3
      2743350.13      6923943.32      2743054.99      6924231.51
      2742992.47      6924353.08
#Sta/Elev= 30
  4581.5  480.28  4596.9  478.32  4632.2  477.79  4710.1  475.68    4802  474.66
  4830.3  474.61  4851.6  474.93  4879.9  474.15  4936.4  473.79  4964.6  472.53
  4978.7  471.03  4983.9  469.47  4984.1  468.97  4987.6  468.97  4987.9  469.47
  4990.1  470.21  5000.9  470.21  5006.5  471.39  5023.1  471.66  5028.7  471.32
  5045.2  471.56  5050.9  471.98  5060.9   473.4  5067.4  475.27    5073  476.15
  5083.4  478.53  5089.6  480.35  5105.9   483.4  5111.8  484.87  5130.7  485.61
#Mann= 3 ,-1 , 0
  4581.5     .05       0  4983.9     .04       0  4987.9     .05       0
Bank Sta=4983.9,4987.9
XS Rating Curve= 0 ,0
Exp/Cntr=0.3,0.1

Type RM Length L Ch R = 1 ,1625    ,373,373,373
BEGIN DESCRIPTION:
Mapping XS 8184851d
END DESCRIPTION:
XS GIS Cut Line= 3
      2743332.81      6923821.78      2742818.88      6923936.38
      2742492.81      6924276.32
#Sta/Elev= 30
  4461.2  481.88  4476.9  479.43  4482.1  479.49  4488.7  478.61  4642.4  475.02
  4703.8   474.5  4753.1   473.2    4837  472.64  4867.8  471.78  4908.7  468.51
    4919  469.06    4960  469.09  4970.2  468.95  4983.8  467.69  4984.1  467.19
  4987.6  467.19  4987.8  467.69  5000.1  468.43  5035.6  468.88  5042.6   470.1
  5056.7  469.52  5063.6  470.75  5070.9  470.62  5077.8  471.46    5085  471.44
  5134.4  474.54  5205.2  474.91  5233.5   476.2  5332.5  477.98  5458.8  478.49
#Mann= 3 ,-1 , 0
  4461.2     .05       0  4983.8     .04       0  4987.8     .05       0
Bank Sta=4983.8,4987.8
XS Rating Curve= 0 ,0
Exp/Cntr=0.3,0.1

Type RM Length L Ch R = 1 ,1252    ,436,436,436
BEGIN DESCRIPTION:
Andy T3 2.0
END DESCRIPTION:
XS GIS Cut Line= 3
      2743225.98        6923711.      2742813.06      6923647.38
      2742250.36      6923939.06
#Sta/Elev= 30
  4582.2  478.04  4616.3  477.81  4679.5  475.59  4723.8  474.94  4810.9  472.76
  4835.1  472.65  4855.4  471.94  4865.5  471.09  4879.2   470.8  4885.7  469.21
    4906  467.23  4947.4  467.05  4956.5  466.67  4974.8  465.05    4975  464.55
  4978.5  464.55  4978.8  465.05  4986.9  467.05    5053   467.2    5066  469.26
  5088.2  470.61  5165.4  470.43  5187.6   470.8  5199.4  471.65  5253.9  471.76
  5298.2  472.88  5342.5  473.01  5513.8  475.66  5548.6  476.65  5633.8  476.95
#Mann= 3 ,-1 , 0
  4582.2     .05       0  4974.8     .04       0  4978.8     .05       0
Bank Sta=4974.8,4978.8
XS Rating Curve= 0 ,0
Exp/Cntr=0.3,0.1

Type RM Length L Ch R = 1 ,816     ,252,252,252
BEGIN DESCRIPTION:
Mapping XS 32de846f
END DESCRIPTION:
XS GIS Cut Line= 3
      2743266.97      6923628.59      2742740.91      6923347.33
      2742219.25      6923368.09
#Sta/Elev= 30
  4240.2  478.22  4476.4  474.96    4734  473.16  4750.3   472.4    4756  472.57
  4762.9  472.04  4772.3  471.85  4777.9  472.18  4799.9  471.26  4808.3  470.12
  4836.7   469.1  4911.7   467.5  4931.7  465.79  4951.7  464.79  4961.7  465.63
  4971.7  465.83  4981.8  465.61  4999.8  464.24    5000  463.74  5003.5  463.74
  5003.8  464.24  5011.8  465.07  5021.8  467.04  5041.8  468.92  5050.8  469.31
  5070.1  469.27  5131.9  469.19  5171.9  469.92  5201.9  469.52  5358.8   471.7
#Mann= 4 ,-1 , 0
  4240.2     .05       0  4999.8     .04       0  5003.8     .05       0
  5070.1     .05       0
Bank Sta=4999.8,5003.8
XS Rating Curve= 0 ,0
Exp/Cntr=0.3,0.1

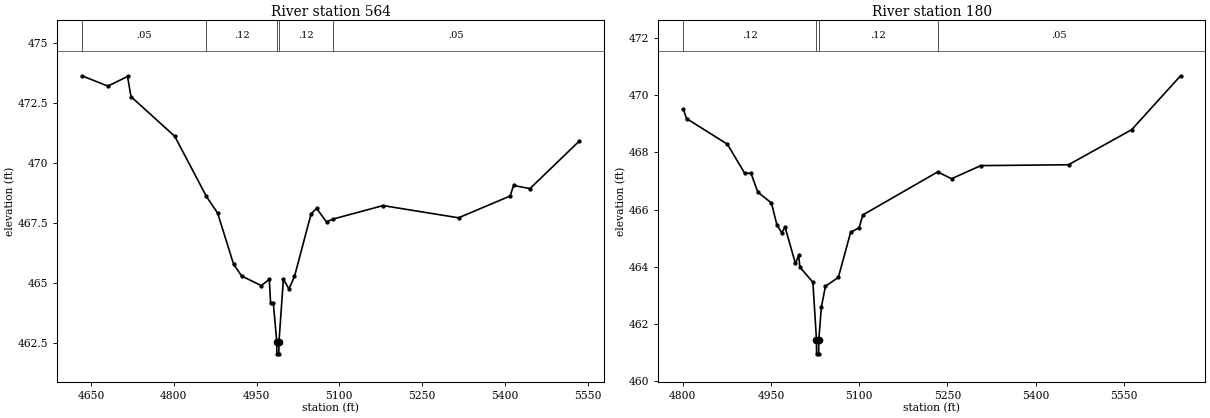
Type RM Length L Ch R = 1 ,564     ,384,384,384
BEGIN DESCRIPTION:
Mapping XS dd989812
END DESCRIPTION:
XS GIS Cut Line= 5
      2742953.72      6923337.82      2742677.28       6923133.8
      2742446.18      6923116.14      2742330.82      6923160.14
      2742163.94      6923273.93
#Sta/Elev= 30
  4633.8  473.64  4680.7  473.21  4716.4  473.61  4722.6  472.77    4802  471.11
  4859.3   468.6  4879.5  467.91  4908.5  465.77  4923.1  465.28  4958.6  464.88
  4973.2  465.14  4975.5  464.14  4980.5  464.14  4986.7  462.53  4986.9  462.03
  4990.4  462.03  4990.7  462.53  4998.7  465.15  5008.7  464.74  5018.8  465.26
  5048.9  467.88  5058.9   468.1  5076.8  467.54    5089  467.66  5179.2  468.22
    5316  467.71  5409.5  468.62  5415.6  469.06  5445.4  468.93  5534.6  470.91
#Mann= 5 ,-1 , 0
  4633.8     .05       0  4859.3     .12       0  4986.7     .07       0
  4990.7     .12       0    5089     .05       0
Bank Sta=4986.7,4990.7
XS Rating Curve= 0 ,0
Exp/Cntr=0.3,0.1

Type RM Length L Ch R = 1 ,180     ,0,0,0
BEGIN DESCRIPTION:
Andy T3 1.0
END DESCRIPTION:
XS GIS Cut Line= 3
      2742851.03      6922936.02       2742669.5      6922854.26
      2742160.57      6923253.27
#Sta/Elev= 30
  4800.9  469.52  4806.4  469.19  4875.9  468.29  4905.1  467.28  4916.1  467.27
  4927.6  466.61  4950.8  466.23    4960  465.47  4968.4  465.18  4973.9  465.39
  4991.6  464.11  4997.1  464.39  4999.2  463.98  5021.3  463.45  5027.4  461.44
  5027.6  460.94  5031.1  460.94  5031.4  461.44  5035.7  462.57  5042.6  463.31
  5064.6  463.62  5085.5   465.2  5099.9  465.36  5106.3  465.81  5233.6  467.32
  5257.2  467.08  5306.9  467.54  5456.1  467.57  5563.6   468.8  5646.7  470.69
#Mann= 4 ,-1 , 0
  4800.9     .12       0  5027.4     .07       0  5031.4     .12       0
  5233.6     .05       0
Bank Sta=5027.4,5031.4
XS Rating Curve= 0 ,0
Exp/Cntr=0.3,0.1

Chan Stop Cuts=-1
Use User Specified Reach Order=0
Composite Channel Slope=5