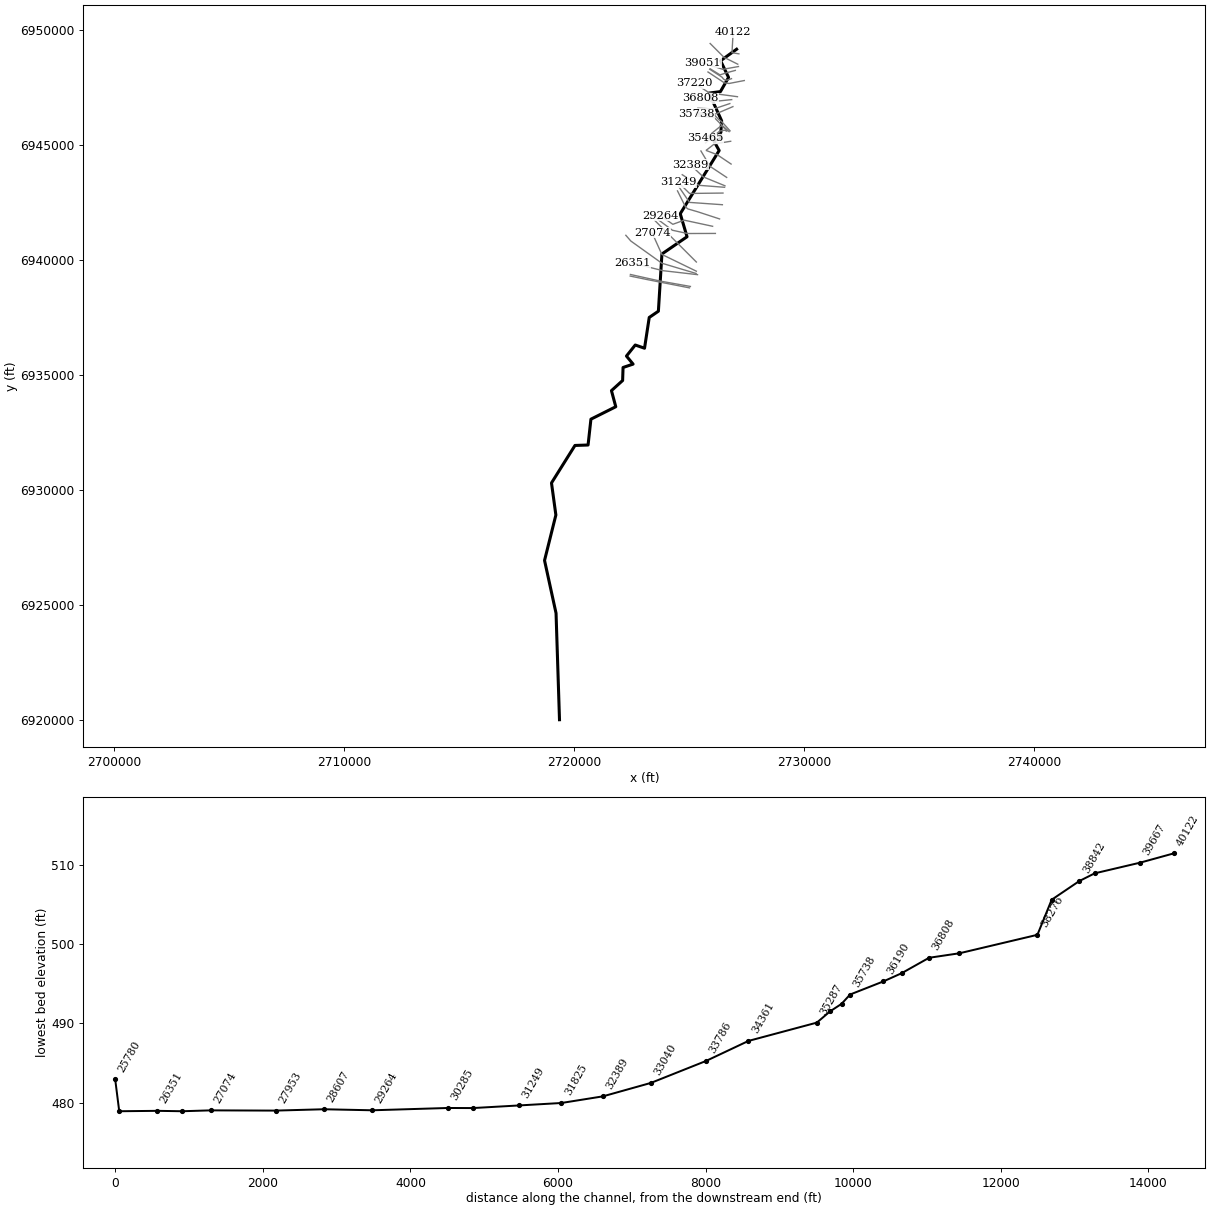
--- Blackberry Creek.prj (project) ---

Proj Title=Blackberry Creek Base Level Engineering
Current Plan=p01
Default Exp/Contr=0.3,0.1
English Units
Geom File=g01
Flow File=f01
Plan File=p01
Y Axis Title=Elevation
X Axis Title(PF)=Main Channel Distance
X Axis Title(XS)=Station
BEGIN DESCRIPTION:
Blackberry Creek
END DESCRIPTION:
DSS Export Rating Curves= 0
DSS Export Rating Curve Sorted= 0
DSS Export Volume Flow Curves= 0
DXF OffsetX= 0
DXF OffsetY= 0
DXF ScaleX= 1
DXF ScaleY= 10

--- Blackberry Creek.p01 (plan) ---

Plan Title=Multiple Run
Short Identifier=Multiple
Geom File=g01
Flow File=f01
Subcritical Flow
K Sum by GR= 0
Std Step Tol= 0.01
Critical Tol= 0.01
Num of Std Step Trials= 20
Max Error Tol= 0.3
Flow Tol Ratio= 0.001
Split Flow NTrial= 30
Split Flow Tol= 0.02
Split Flow Ratio= 0.02
Log Output Level= 0
Friction Slope Method= 1
Unsteady Friction Slope Method= 2
Unsteady Bridges Friction Slope Method= 1
Parabolic Critical Depth
Global Vel Dist=  1 , 1 , 1
Global Log Level= 0
CheckData=True
Encroach Param= -1, 0, 0, 0
BEGIN DESCRIPTION:
Multiple Run
END DESCRIPTION:

--- Blackberry Creek.f01 (steady flow) ---

Flow Title=Multiple
Program Version=4.10
Number of Profiles= 7
Profile Names=10-year,25-year,50-year,1pct_min,100-year,1pct_plu,500-year
River Rch & RM=Blackberry Creek,Reach-1         ,40122
     165     201     227     128     255     510     321
River Rch & RM=Blackberry Creek,Reach-1         ,39667
     420     546     644     378     753    1503    1028
River Rch & RM=Blackberry Creek,Reach-1         ,36808
     695     925    1109     659    1316    2625    1849
River Rch & RM=Blackberry Creek,Reach-1         ,29264
     889    1195    1443     862    1720    3431    2441
River Rch & RM=Blackberry Creek,Reach-1         ,25663
     992    1343    1629     978    1951    3893    2797
River Rch & RM=Blackberry Creek,Reach-1         ,22051
    1265    1730    2112    1274    2543    5074    3685
River Rch & RM=Blackberry Creek,Reach-1         ,10976
    1467    2024    2484    1506    3005    5996    4399
River Rch & RM=Blackberry Creek,Reach-1         ,2176
    1786    2487    3073    1874    3740    7462    5541
Boundary for River Rch & Prof#=Blackberry Creek,Reach-1         , 1
Up Type= 0
Dn Type= 3
Dn Slope=0.0023
Boundary for River Rch & Prof#=Blackberry Creek,Reach-1         , 2
Up Type= 0
Dn Type= 3
Dn Slope=0.0023
Boundary for River Rch & Prof#=Blackberry Creek,Reach-1         , 3
Up Type= 0
Dn Type= 3
Dn Slope=0.0023
Boundary for River Rch & Prof#=Blackberry Creek,Reach-1         , 4
Up Type= 0
Dn Type= 3
Dn Slope=0.0023
Boundary for River Rch & Prof#=Blackberry Creek,Reach-1         , 5
Up Type= 0
Dn Type= 3
Dn Slope=0.0023
Boundary for River Rch & Prof#=Blackberry Creek,Reach-1         , 6
Up Type= 0
Dn Type= 3
Dn Slope=0.0023
Boundary for River Rch & Prof#=Blackberry Creek,Reach-1         , 7
Up Type= 0
Dn Type= 3
Dn Slope=0.0023
DSS Import GetInterval= 0
DSS Import GetPeak= 0
DSS Import FillOption= 0

--- Blackberry Creek.g01 (geometry) ---

Geom Title=Existing Conditions
Program Version=4.10

River Reach=Blackberry Creek,Reach-1
Reach XY= 30
        2727076.        6949161.      2726379.46       6948659.5
      2726726.51      6947936.03      2726372.63      6947319.03
      2725878.04      6947255.15      2726425.11      6946050.66
      2726372.46      6945262.44      2726075.76      6945191.08
      2726318.16      6944757.77        2724626.        6942011.
      2724920.54      6941008.55      2723829.53      6940259.55
      2723675.32      6937771.75       2723277.5      6937499.79
      2723072.93      6936162.43      2722669.29      6936301.71
      2722286.95      6935821.36      2722575.47      6935471.69
      2722139.36      6935325.14      2722120.55      6934758.53
      2721634.82        6934318.      2721823.03      6933618.58
      2720742.37       6933077.7      2720618.31      6931954.43
      2720048.81      6931934.98      2719028.07      6930305.14
       2719218.7      6928911.08       2718725.8      6926935.92
      2719226.09       6924640.9        2719376.        6920011.

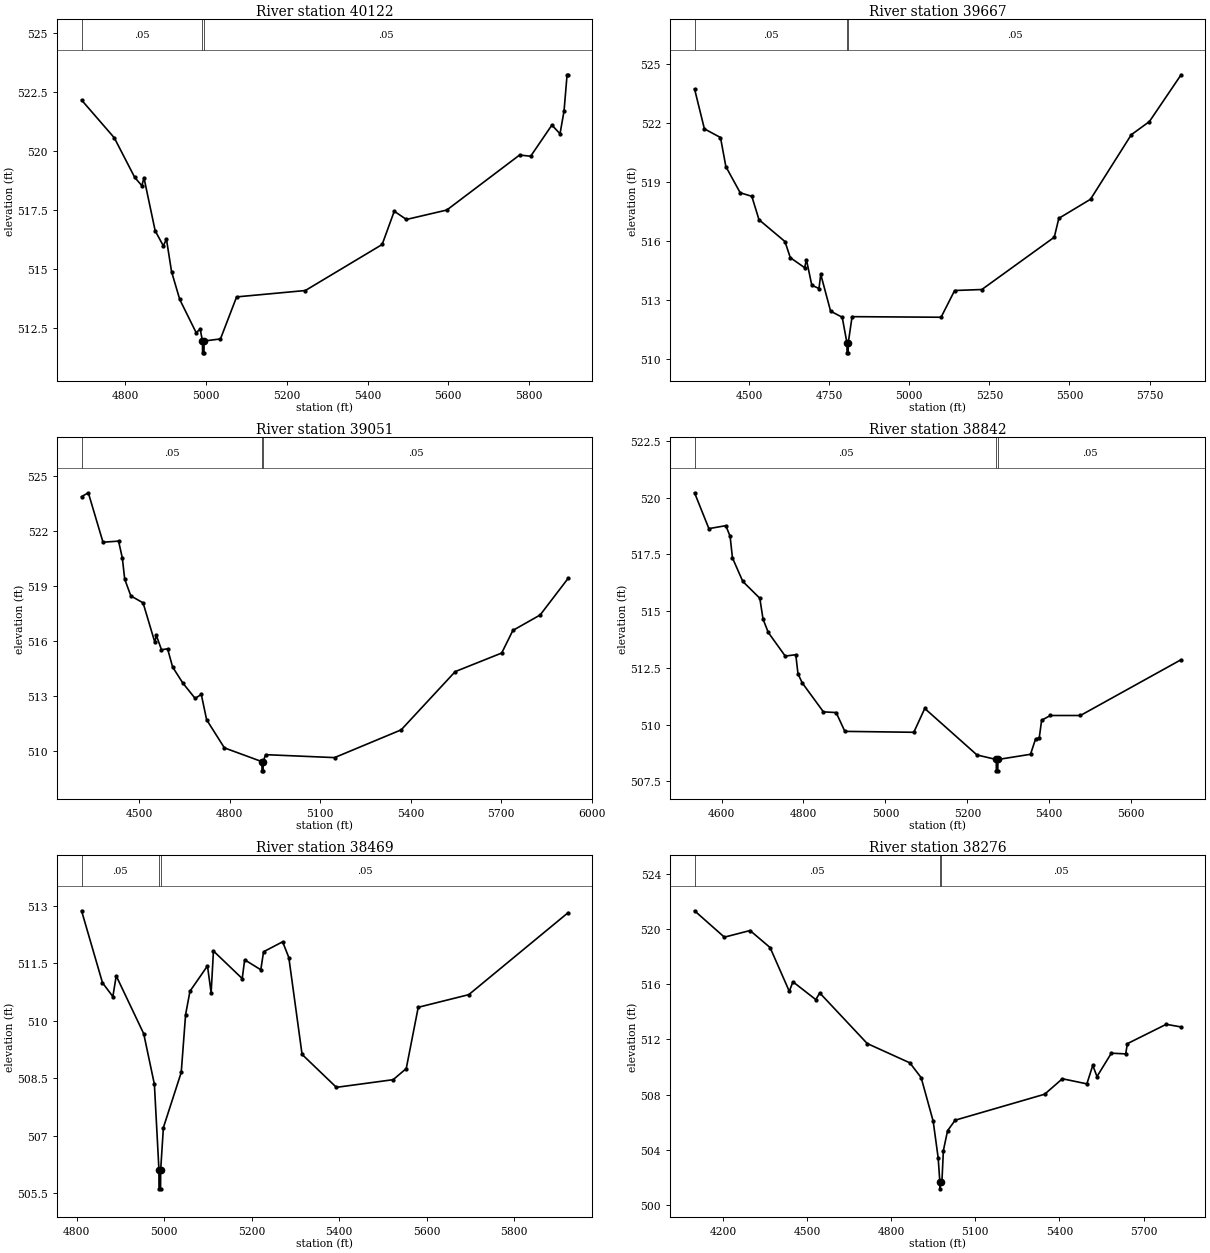
Type RM Length L Ch R = 1 ,40122   ,455,455,455
BEGIN DESCRIPTION:
Blackberry Creek 69.0
END DESCRIPTION:
XS GIS Cut Line= 3
      2727175.96      6948961.01        2726876.        6949011.
        2726926.      6949911.02
#Sta/Elev= 30
  4691.5  522.17  4772.6  520.57  4823.3  518.89    4841  518.54  4846.1  518.88
  4873.9  516.63  4894.2  515.99  4901.8  516.28  4914.5   514.9  4934.8  513.72
  4975.3  512.32  4985.5  512.46  4991.1  511.96  4991.3  511.46  4994.8  511.46
  4995.1  511.96  5035.7  512.05  5075.7  513.83    5246   514.1  5436.3  516.05
  5466.3  517.46  5496.4  517.11  5596.5  517.51  5776.8  519.84  5804.3  519.79
  5856.9  521.11    5877  520.74    5887  521.71  5894.5  523.24    5897  523.24
#Mann= 3 ,-1 , 0
  4691.5     .05       0  4991.1     .04       0  4995.1     .05       0
Bank Sta=4991.1,4995.1
XS Rating Curve= 0 ,0
Exp/Cntr=0.3,0.1

Type RM Length L Ch R = 1 ,39667   ,616,616,616
BEGIN DESCRIPTION:
Blackberry Creek 68.0
END DESCRIPTION:
XS GIS Cut Line= 3
      2727125.96      6948511.02        2726526.        6948811.
      2725926.01      6949410.99
#Sta/Elev= 30
  4329.2  523.71  4359.9  521.68  4410.2  521.24    4427  519.76  4471.7  518.43
    4508  518.25  4530.4  517.06  4611.5  515.95  4628.2  515.13    4673  514.62
  4678.5  515.03  4695.3  513.73  4717.7  513.56  4723.3  514.28    4754  512.41
  4790.3   512.1  4805.1  510.79  4805.4  510.29  4808.9  510.29  4809.1  510.79
  4821.1  512.13    5099   512.1  5141.4  513.46  5226.3  513.51  5452.5  516.17
  5466.7  517.13  5565.7   518.1  5692.9  521.38  5749.5  522.05  5848.5  524.43
#Mann= 3 ,-1 , 0
  4329.2     .05       0  4805.1     .03       0  4809.1     .05       0
Bank Sta=4805.1,4809.1
XS Rating Curve= 0 ,0
Exp/Cntr=0.3,0.1

Type RM Length L Ch R = 1 ,39051   ,209,209,209
BEGIN DESCRIPTION:
Mapping XS 8a967893
END DESCRIPTION:
XS GIS Cut Line= 3
      2727156.86      6948409.24      2726475.45      6948287.71
      2725599.86       6948573.8
#Sta/Elev= 30
  4308.3  523.86  4330.7  524.07  4379.4  521.38  4431.1  521.44  4443.5  520.52
  4451.4  519.37  4471.7  518.46  4512.3  518.08  4551.2  515.94  4556.3  516.31
  4573.3  515.53  4593.6  515.58  4610.2  514.59  4644.4  513.71    4685  512.88
  4705.3   513.1    4723  511.72  4781.9  510.19  4906.5  509.44  4906.7  508.94
  4910.2  508.94  4910.5  509.44  4918.6  509.82  5147.2  509.66  5368.1  511.17
  5547.3  514.34  5701.4  515.35  5738.5  516.58  5828.9  517.42  5921.6  519.41
#Mann= 3 ,-1 , 0
  4308.3     .05       0  4906.5     .04       0  4910.5     .05       0
Bank Sta=4906.5,4910.5
XS Rating Curve= 0 ,0
Exp/Cntr=0.3,0.1

Type RM Length L Ch R = 1 ,38842   ,373,373,373
BEGIN DESCRIPTION:
Mapping XS 32441fd3
END DESCRIPTION:
XS GIS Cut Line= 4
      2727019.77      6948240.21      2726625.43      6948133.97
      2726355.15      6948046.23      2725933.65      6948306.22
#Sta/Elev= 30
  4534.1  520.22  4569.1  518.64  4610.5  518.77  4620.9   518.3  4626.6  517.35
  4651.9  516.31  4693.4  515.57  4701.3  514.65  4714.1  514.06  4755.5  513.02
  4781.2  513.08  4786.6  512.24  4796.9  511.84  4848.7  510.56  4879.8  510.53
    4901   509.7  5069.4  509.66  5096.1  510.71  5223.6  508.66  5270.7  508.46
  5270.9  507.96  5274.4  507.96  5274.7  508.46  5354.3  508.69  5366.7  509.37
  5375.6  509.41  5381.4  510.19  5402.7   510.4  5476.1   510.4  5721.9  512.86
#Mann= 3 ,-1 , 0
  4534.1     .05       0  5270.7     .05       0  5274.7     .05       0
Bank Sta=5270.7,5274.7
XS Rating Curve= 0 ,0
Exp/Cntr=0.3,0.1

Type RM Length L Ch R = 1 ,38469   ,193,193,193
BEGIN DESCRIPTION:
Mapping XS cf15da91
END DESCRIPTION:
XS GIS Cut Line= 6
      2726853.85      6947882.14      2726671.95      6947820.74
      2726569.76      6947823.54      2726501.68        6947870.
      2726445.03        6947944.      2725905.36       6948293.7
#Sta/Elev= 30
  4810.8  512.87  4858.7  510.99  4882.4  510.63  4890.1  511.17    4953  509.66
  4977.4  508.34  4987.8  506.11    4988  505.61  4991.5  505.61  4991.8  506.11
    4998  507.21  5038.8  508.65  5048.8  510.16  5058.8  510.77  5098.8  511.43
  5107.2  510.73  5112.5  511.82  5178.3   511.1  5183.9  511.59  5220.8  511.33
  5227.1   511.8  5270.7  512.06  5284.9  511.65  5315.2  509.12  5393.7  508.26
  5523.6  508.46  5553.5  508.75  5580.9  510.35  5696.5  510.68  5923.7  512.82
#Mann= 3 ,-1 , 0
  4810.8     .05       0  4987.8     .04       0  4991.8     .05       0
Bank Sta=4987.8,4991.8
XS Rating Curve= 0 ,0
Exp/Cntr=0.3,0.1

Type RM Length L Ch R = 1 ,38276   ,1056,1056,1056
BEGIN DESCRIPTION:
Mapping XS b2c5b674
END DESCRIPTION:
XS GIS Cut Line= 4
      2727410.33      6947800.73      2726746.96      6947672.16
      2726545.19      6947700.33      2725831.84      6948171.95
#Sta/Elev= 30
    4099  521.31  4205.3   519.4  4296.9  519.88  4368.2  518.65  4436.8  515.48
  4449.7  516.17  4531.2  514.88  4545.4  515.36  4714.6   511.7  4866.6   510.3
  4906.9  509.23  4949.7  506.08  4967.5  503.43  4973.5  501.68  4973.8  501.18
  4977.5  501.68  4980.9  501.68  4986.1  503.95  5001.1  505.39  5028.2  506.15
  5347.2  508.03  5410.4  509.15  5497.7  508.78  5518.7  510.12  5533.8  509.31
    5585     511  5636.1  510.95  5642.1  511.69  5780.6  513.09  5833.6   512.9
#Mann= 3 ,-1 , 0
    4099     .05       0  4973.5     .04       0  4977.5     .05       0
Bank Sta=4973.5,4977.5
XS Rating Curve= 0 ,0
Exp/Cntr=0.3,0.1

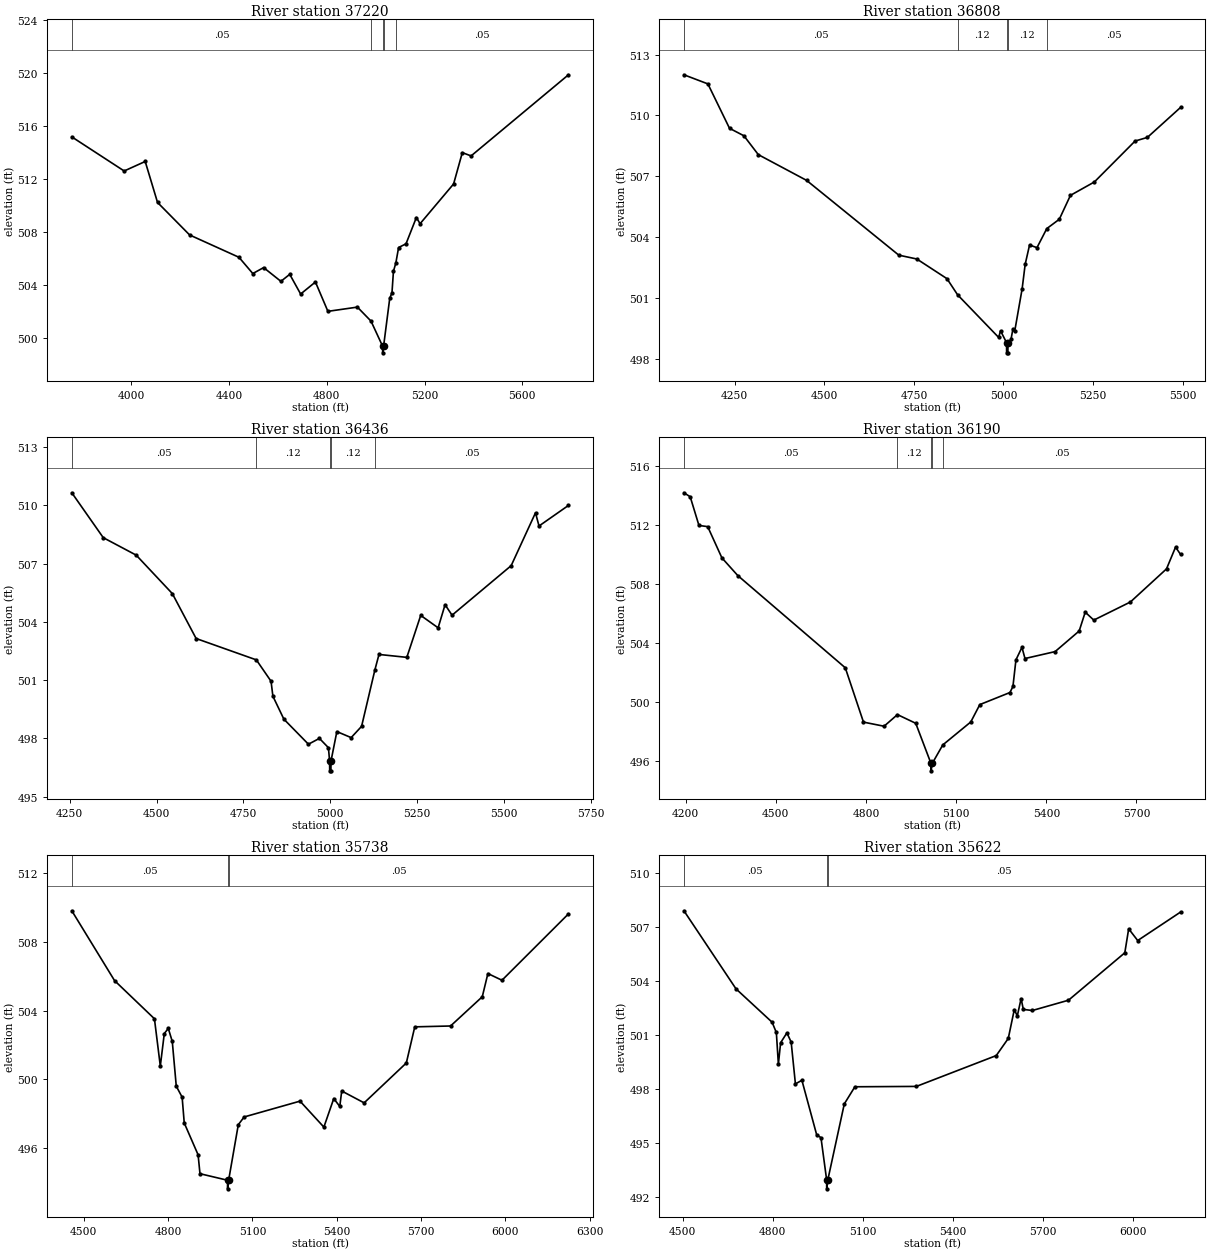
Type RM Length L Ch R = 1 ,37220   ,412,412,412
BEGIN DESCRIPTION:
Mapping XS a2a2d00b
END DESCRIPTION:
XS GIS Cut Line= 3
      2727113.43      6947097.62      2725894.72       6947260.8
      2725221.12      6947694.83
#Sta/Elev= 30
  3757.8  515.19  3971.9  512.61  4057.9  513.33  4108.3  510.23  4239.5  507.77
  4441.3  506.08  4497.9  504.85  4542.2   505.3  4612.8  504.26  4648.9  504.79
  4693.5   503.3    4754  504.21    4805  501.99  4925.6  502.31  4981.3  501.25
  5028.7  499.35  5028.9  498.85  5032.7  499.35  5057.8  502.97    5067   503.4
    5073  505.02  5082.8  505.65  5094.1  506.82  5124.4   507.1  5166.7  509.09
  5181.9  508.62    5319  511.63  5354.6     514  5390.5  513.75  5788.7  519.89
#Mann= 5 ,-1 , 0
  3757.8     .05       0  4981.3     .12       0  5028.7     .07       0
  5032.7     .12       0  5082.8     .05       0
Bank Sta=5028.7,5032.7
XS Rating Curve= 0 ,0
Exp/Cntr=0.3,0.1

Type RM Length L Ch R = 1 ,36808   ,372,372,372
BEGIN DESCRIPTION:
Mapping XS 4d7e22bf
END DESCRIPTION:
XS GIS Cut Line= 3
      2726862.56      6946970.87      2726000.63      6946882.33
      2725499.55      6947019.93
#Sta/Elev= 30
  4108.2     512  4175.1  511.55  4235.4  509.36  4275.6  508.99  4315.8  508.06
  4450.5  506.79  4707.9   503.1  4758.2  502.91  4842.3  501.94  4872.1  501.14
  4986.6  499.04  4991.8  499.37  5008.6  498.78  5008.8  498.28  5012.3  498.28
  5012.6  498.78    5021  498.94  5026.2  499.44  5031.4  499.35  5052.1  501.44
  5060.6  502.65  5072.8   503.6  5093.5  503.47  5120.9  504.41  5155.8  504.87
  5186.9  506.05  5253.6  506.71  5367.3  508.73  5401.7  508.91  5494.3  510.39
#Mann= 5 ,-1 , 0
  4108.2     .05       0  4872.1     .12       0  5008.6     .07       0
  5012.6     .12       0  5120.9     .05       0
Bank Sta=5008.6,5012.6
XS Rating Curve= 0 ,0
Exp/Cntr=0.3,0.1

Type RM Length L Ch R = 1 ,36436   ,246,246,246
BEGIN DESCRIPTION:
Mapping XS 8a4c2dbb
END DESCRIPTION:
XS GIS Cut Line= 3
      2726781.86      6946798.99      2726081.36      6946564.62
      2725391.26      6946598.48
#Sta/Elev= 30
    4256  510.64  4346.5  508.33  4441.4  507.43  4545.4  505.45  4613.8  503.14
  4787.2  502.04  4829.5  500.94  4834.8  500.17  4866.4  498.99  4937.1   497.7
  4968.7     498  4994.7  497.52    4998  496.83  4998.3  496.33  5001.8  496.33
    5002  496.83  5018.9  498.35  5060.1  498.04  5090.1  498.62  5128.6  501.54
  5140.2  502.32  5220.3  502.17  5260.3  504.33  5310.4  503.69  5330.4  504.88
  5350.5  504.34  5520.7  506.89  5590.7  509.61  5600.8  508.93  5685.6  509.99
#Mann= 5 ,-1 , 0
    4256     .05       0  4787.2     .12       0    4998     .07       0
    5002     .12       0  5128.6     .05       0
Bank Sta=4998,5002
XS Rating Curve= 0 ,0
Exp/Cntr=0.3,0.1

Type RM Length L Ch R = 1 ,36190   ,452,452,452
BEGIN DESCRIPTION:
Mapping XS e8c3c633
END DESCRIPTION:
XS GIS Cut Line= 3
      2726915.59       6946666.2       2726174.3       6946350.3
      2725329.31      6946404.15
#Sta/Elev= 30
  4194.2  514.19  4215.1  513.92  4244.2  511.97  4273.3  511.89  4320.5  509.77
  4373.2  508.57  4731.1   502.3  4791.6  498.61  4860.1  498.33  4904.7  499.12
  4965.5  498.53  5016.3   495.8  5016.6   495.3  5020.3   495.8  5055.5  497.06
  5148.6  498.62  5178.7   499.8  5278.9  500.62  5288.9  501.03  5298.9  502.84
  5318.9  503.69    5329  502.93  5429.2   503.4  5509.3   504.8  5529.4  506.08
  5557.9  505.54  5679.7  506.77  5799.9  509.02    5830   510.5  5846.7     510
#Mann= 5 ,-1 , 0
  4194.2     .05       0  4904.7     .12       0  5016.3     .07       0
  5020.3     .12       0  5055.5     .05       0
Bank Sta=5016.3,5020.3
XS Rating Curve= 0 ,0
Exp/Cntr=0.3,0.1

Type RM Length L Ch R = 1 ,35738   ,116,116,116
BEGIN DESCRIPTION:
Mapping XS 18fe6b14
END DESCRIPTION:
XS GIS Cut Line= 5
      2726792.42      6945612.57      2726438.24      6946004.94
      2726303.46      6946103.74      2726109.54      6946307.32
      2725319.58      6946346.89
#Sta/Elev= 30
  4457.3  509.81  4609.4  505.75  4751.4  503.53  4772.3  500.78  4786.5  502.67
  4800.7  502.97  4814.9  502.21  4829.1  499.61    4850  498.97  4857.5  497.47
  4906.8  495.62  4913.5  494.52  5011.5  494.14  5011.7  493.64  5015.5  494.14
  5049.9  497.37  5070.7  497.82  5269.6  498.74  5354.5  497.23  5389.7  498.89
  5411.1  498.43    5418  499.33  5497.8  498.64    5648  500.96    5678  503.06
  5805.4  503.11  5918.3  504.81  5938.3  506.16  5988.4  505.77  6225.1  509.63
#Mann= 3 ,-1 , 0
  4457.3     .05       0  5011.5     .04       0  5015.5     .05       0
Bank Sta=5011.5,5015.5
XS Rating Curve= 0 ,0
Exp/Cntr=0.3,0.1

Type RM Length L Ch R = 1 ,35622   ,157,157,157
BEGIN DESCRIPTION:
Mapping XS e0e6275b
END DESCRIPTION:
XS GIS Cut Line= 4
      2726749.79      6945579.46      2726377.42      6945915.37
      2726101.38      6946196.62      2725343.54      6946261.73
#Sta/Elev= 30
  4503.9  507.88  4677.6  503.55  4797.9   501.7  4812.1  501.13  4818.9  499.37
  4826.3  500.56  4847.3  501.11  4861.5   500.6  4875.7  498.28  4897.3  498.48
  4946.7  495.45  4960.9   495.3  4979.8  492.96    4980  492.46  4983.8  492.96
  5038.7  497.17    5074  498.12  5279.1  498.14  5545.4  499.85  5585.5   500.8
  5605.6   502.4  5615.6  502.05  5628.3  503.01  5635.7  502.41  5665.8  502.35
  5786.3  502.92  5974.1  505.55    5987  506.88  6017.1  506.23  6160.1  507.81
#Mann= 3 ,-1 , 0
  4503.9     .05       0  4979.8     .05       0  4983.8     .05       0
Bank Sta=4979.8,4983.8
XS Rating Curve= 0 ,0
Exp/Cntr=0.3,0.1

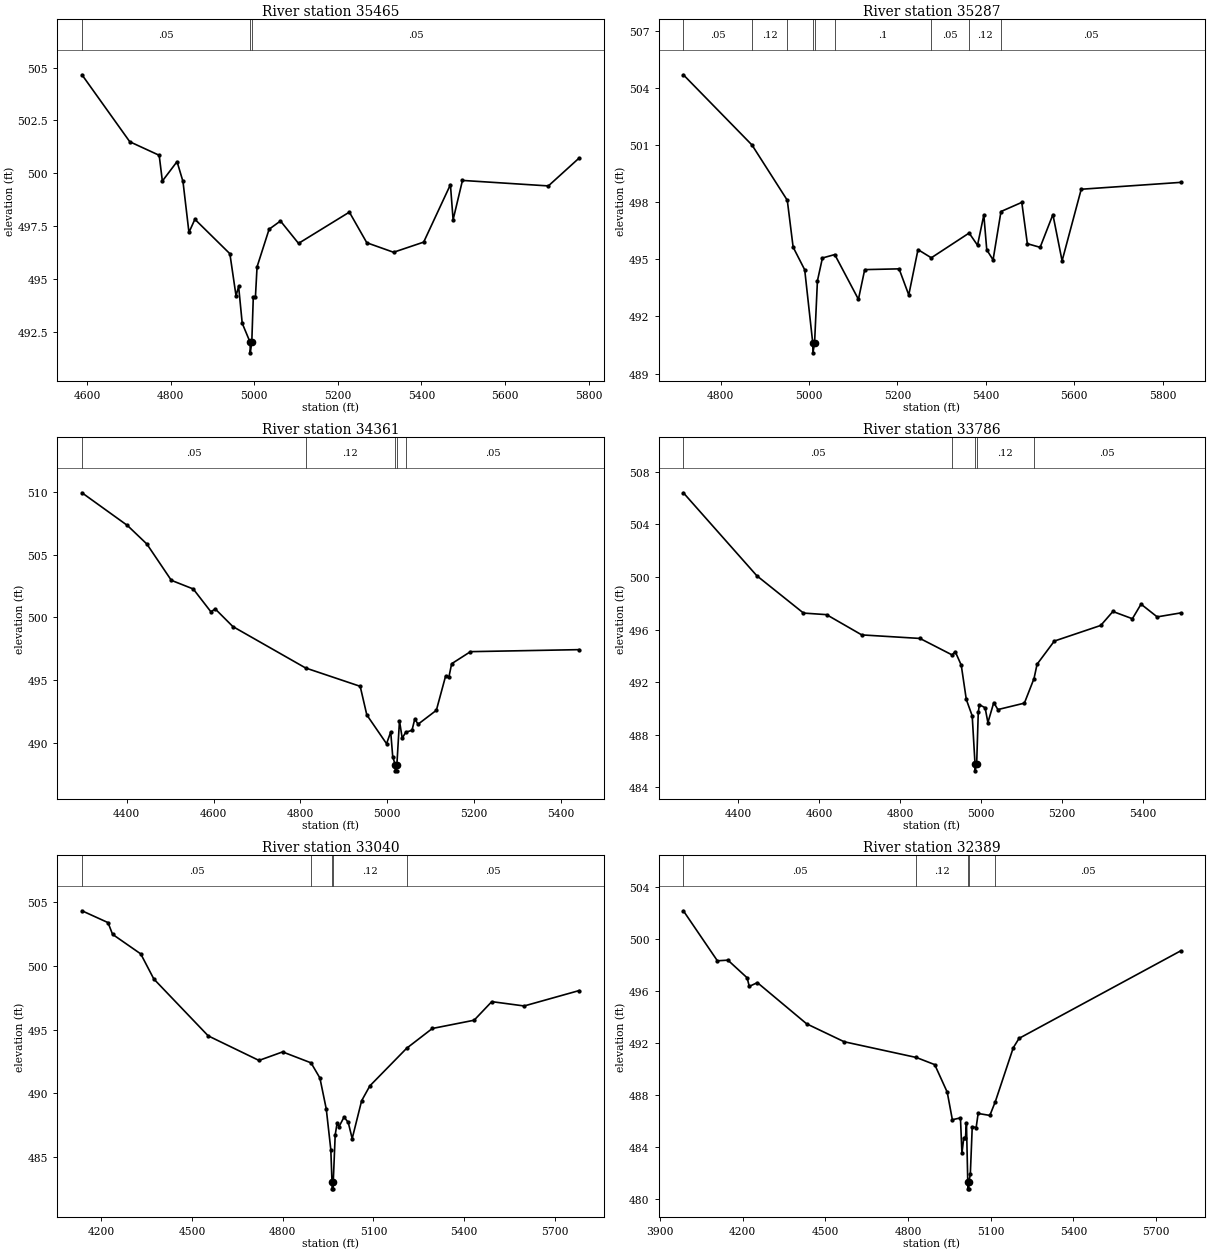
Type RM Length L Ch R = 1 ,35465   ,178,178,178
BEGIN DESCRIPTION:
Mapping XS ecd7c49e
END DESCRIPTION:
XS GIS Cut Line= 4
      2726643.03      6945647.16      2726421.69      6945839.85
      2726322.73      6945769.54      2725718.58      6945285.18
#Sta/Elev= 30
  4588.2  504.66  4702.6  501.49  4772.9  500.85  4780.5  499.63  4815.6  500.55
  4829.8  499.61  4844.1   497.2  4858.3  497.82    4942  496.19  4956.7   494.2
  4962.9  494.64  4971.5   492.9  4990.4     492  4990.7   491.5  4994.4     492
    4998  494.14  5003.1  494.14    5007  495.57  5035.8  497.35    5063  497.74
  5106.2  496.68  5227.8  498.16  5269.5  496.71  5333.5  496.26  5405.5  496.74
  5469.5  499.46  5475.9   497.8  5498.3  499.66  5703.8   499.4  5777.4  500.72
#Mann= 3 ,-1 , 0
  4588.2     .05       0  4990.4     .05       0  4994.4     .05       0
Bank Sta=4990.4,4994.4
XS Rating Curve= 0 ,0
Exp/Cntr=0.3,0.1

Type RM Length L Ch R = 1 ,35287   ,926,926,926
BEGIN DESCRIPTION:
Mapping XS 54f5dfa8
END DESCRIPTION:
XS GIS Cut Line= 5
      2726649.33      6945598.69      2726555.55      6945640.37
      2726342.01      6945603.91      2726010.23      6945313.81
      2725723.78      6945087.25
#Sta/Elev= 30
  4715.6  504.69    4871     501  4950.8   498.1    4964  495.64  4990.2  494.45
  5008.5  490.59  5008.8  490.09  5012.5  490.59    5019  493.87  5030.3  495.07
  5058.2  495.25  5111.8   492.9    5126  494.46  5203.8   494.5  5225.7  493.13
  5246.6  495.51  5276.7  495.08  5362.3  496.38  5381.3  495.74  5395.6  497.33
  5402.2   495.5  5416.5  494.97  5434.4  497.51  5481.5  497.99  5494.1  495.82
    5523  495.63  5551.9  497.35  5572.7  494.92    5616  498.68  5840.8  499.04
#Mann= 9 ,-1 , 0
  4715.6     .05       0    4871     .12       0  4950.8     .05       0
  5008.5     .04       0  5012.5     .05       0  5058.2      .1       0
  5276.7     .05       0  5362.3     .12       0  5434.4     .05       0
Bank Sta=5008.5,5012.5
XS Rating Curve= 0 ,0
Exp/Cntr=0.3,0.1

Type RM Length L Ch R = 1 ,34361   ,575,575,575
BEGIN DESCRIPTION:
Mapping XS 849c474e
END DESCRIPTION:
XS GIS Cut Line= 3
      2726819.43      6945159.47      2726111.97      6945046.62
      2725773.41      6944781.85
#Sta/Elev= 30
  4296.7  509.92  4401.4  507.32  4446.3  505.84  4502.7  502.95  4553.3  502.26
  4593.8  500.45    4604  500.67  4644.5  499.27  4812.3  495.97  4938.1  494.51
  4953.4  492.23  4998.9  489.94  5008.5  490.88  5013.1  488.91  5018.7  488.28
  5018.9  487.78  5022.4  487.78  5022.7  488.28  5028.7  491.76    5035  490.38
  5043.1  490.85  5057.6  491.01    5064  491.92  5071.5  491.49  5113.7   492.6
  5134.9  495.31  5142.6  495.25    5149  496.31  5192.4  497.27  5442.9  497.43
#Mann= 5 ,-1 , 0
  4296.7     .05       0  4812.3     .12       0  5018.7     .07       0
  5022.7     .12       0  5043.1     .05       0
Bank Sta=5018.7,5022.7
XS Rating Curve= 0 ,0
Exp/Cntr=0.3,0.1

Type RM Length L Ch R = 1 ,33786   ,746,746,746
BEGIN DESCRIPTION:
Mapping XS ce5c2383
END DESCRIPTION:
XS GIS Cut Line= 3
      2726836.77      6944169.91      2726229.16      6944577.87
      2725764.75      6944755.82
#Sta/Elev= 30
  4264.2   506.4  4445.8  500.09  4561.2  497.25  4618.2  497.13  4705.2  495.59
  4849.2  495.32  4928.4  494.07  4936.3  494.32  4951.2  493.29  4963.7  490.68
  4978.3  489.43  4985.3  485.75  4985.5  485.25  4989.3  485.75  4993.3   489.7
  4996.1  490.28  5010.2  490.05  5017.1  488.92  5031.6  490.44  5041.8  489.91
  5107.3   490.4  5131.1  492.27  5138.7  493.36  5181.3  495.12  5296.1  496.31
  5326.1  497.37  5374.3  496.82  5395.7  497.93  5435.6  496.96  5493.4  497.26
#Mann= 5 ,-1 , 0
  4264.2     .05       0  4928.4     .12       0  4985.3     .07       0
  4989.3     .12       0  5131.1     .05       0
Bank Sta=4985.3,4989.3
XS Rating Curve= 0 ,0
Exp/Cntr=0.3,0.1

Type RM Length L Ch R = 1 ,33040   ,651,651,651
BEGIN DESCRIPTION:
Mapping XS e0e4c518
END DESCRIPTION:
XS GIS Cut Line= 3
      2726644.07      6943589.17      2725924.01      6944066.68
      2725525.29      6944737.65
#Sta/Elev= 30
    4136  504.33  4222.2   503.4  4237.2  502.48  4330.5  500.94  4373.7  498.97
  4553.6   494.5  4721.5  492.57  4799.7  493.24  4893.7  492.38    4923  491.19
  4944.1  488.75  4959.1  485.56  4963.1  482.98  4963.4  482.48  4966.9  482.48
  4967.1  482.98  4973.6  486.72  4980.1  487.67  4986.1  487.36  5002.9  488.12
  5016.7   487.7  5029.8  486.43    5061   489.4  5088.2  490.57  5210.1  493.53
  5294.8  495.08  5433.1  495.73  5491.5  497.19  5598.6  496.85  5780.5  498.06
#Mann= 5 ,-1 , 0
    4136     .05       0  4893.7     .12       0  4963.1     .07       0
  4967.1     .12       0  5210.1     .05       0
Bank Sta=4963.1,4967.1
XS Rating Curve= 0 ,0
Exp/Cntr=0.3,0.1

Type RM Length L Ch R = 1 ,32389   ,564,564,564
BEGIN DESCRIPTION:
Blackberry Creek 55.0
END DESCRIPTION:
XS GIS Cut Line= 3
      2726570.27      6943224.59        2725626.        6943611.
      2725055.58      6944149.02
#Sta/Elev= 30
  3984.5  502.18    4108  498.33  4146.2  498.38    4216  497.02  4223.6  496.36
  4253.1  496.65  4431.9  493.48  4568.1   492.1  4829.9  490.89  4896.7  490.34
  4942.1  488.22  4960.7   486.1  4990.1  486.24  4995.5  483.51  5002.1   484.7
  5008.2   484.7  5011.9  485.81  5016.7  481.28    5017  480.78  5020.5  480.78
  5020.7  481.28    5026  481.94  5032.9  485.56  5047.1   485.5  5054.3  486.58
  5096.8  486.43  5116.8   487.5  5181.8  491.64  5202.8  492.36  5788.9  499.09
#Mann= 5 ,-1 , 0
  3984.5     .05       0  4829.9     .12       0  5016.7     .07       0
  5020.7     .12       0  5116.8     .05       0
Bank Sta=5016.7,5020.7
XS Rating Curve= 0 ,0
Exp/Cntr=0.3,0.1

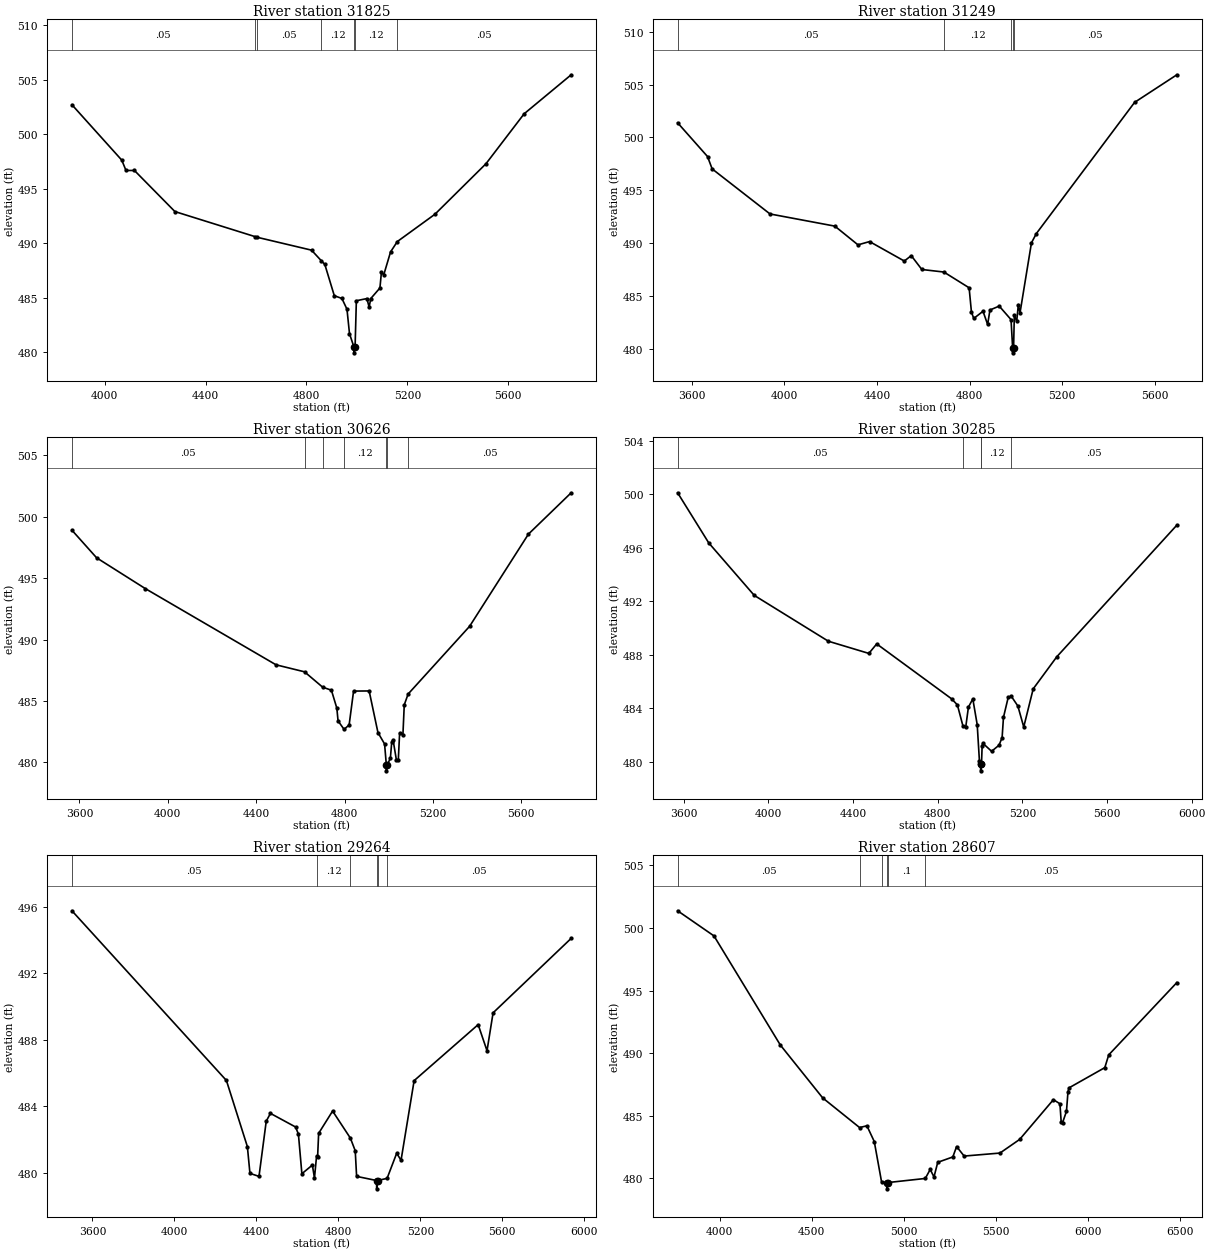
Type RM Length L Ch R = 1 ,31825   ,576,576,576
BEGIN DESCRIPTION:
Blackberry Creek 54.0
END DESCRIPTION:
XS GIS Cut Line= 3
      2726552.96      6943159.47      2725426.77      6943245.91
      2724712.89       6943706.2
#Sta/Elev= 30
  3870.5   502.7    4068  497.62  4084.8  496.67  4118.2  496.67  4278.7   492.9
  4595.2  490.61  4605.1  490.54  4820.2  489.36  4858.1  488.41  4872.9  488.05
  4910.5  485.18  4940.6  484.93  4960.7  483.94  4970.7   481.7  4988.7  480.44
    4989  479.94  4992.8  480.44  4997.9  484.72  5039.8  484.92  5048.5  484.13
    5055  484.92  5091.3  485.89  5097.2  487.32  5106.5   487.1  5133.5   489.2
  5160.3  490.15  5309.1  492.65  5511.7  497.29  5662.9  501.87  5849.4  505.45
#Mann= 7 ,-1 , 0
  3870.5     .05       0  4595.2     .12       0  4605.1     .05       0
  4858.1     .12       0  4988.7     .07       0  4992.8     .12       0
  5160.3     .05       0
Bank Sta=4988.7,4992.8
XS Rating Curve= 0 ,0
Exp/Cntr=0.3,0.1

Type RM Length L Ch R = 1 ,31249   ,623,623,623
BEGIN DESCRIPTION:
Mapping XS 40beeee1
END DESCRIPTION:
XS GIS Cut Line= 3
      2726485.19       6942908.6      2725030.37      6942891.24
      2724530.69      6943383.99
#Sta/Elev= 30
  3538.7  501.38  3667.9  498.19  3687.9  497.02  3937.9  492.76  4217.9  491.61
  4317.9  489.84    4368  490.15    4518  488.31    4548  488.82  4593.8  487.51
  4688.9  487.27    4798  485.78    4808  483.49    4818  482.88    4858  483.56
    4878  482.31    4888  483.68    4928  484.05  4979.1  482.77  4985.9  480.13
  4986.2  479.63  4990.1  480.13  4993.3  483.19  5003.6  482.61  5010.7   484.2
  5017.7  483.39  5067.3  490.03  5088.5  490.91  5512.8  503.31  5695.4  505.92
#Mann= 5 ,-1 , 0
  3538.7     .05       0  4688.9     .12       0  4979.1     .05       0
  4985.9     .04       0  4990.1     .05       0
Bank Sta=4985.9,4990.1
XS Rating Curve= 0 ,0
Exp/Cntr=0.3,0.1

Type RM Length L Ch R = 1 ,30626   ,341,341,341
BEGIN DESCRIPTION:
Mapping XS 132f3885
END DESCRIPTION:
XS GIS Cut Line= 3
      2726457.42      6942401.66      2725030.37      6942502.35
      2724561.86      6943186.03
#Sta/Elev= 30
    3566  498.91  3677.7  496.66  3898.2  494.15  4489.7  487.94  4618.6  487.37
  4700.5  486.12  4740.3  485.87  4764.8  484.41  4770.4  483.37  4797.6  482.68
  4820.5  483.04  4840.6   485.8  4911.1  485.81  4950.9  482.42  4980.9  481.49
  4988.8   479.8  4989.2   479.3  4993.1   479.8  5007.1  480.32  5013.2  481.62
  5019.2  481.84  5034.1  480.22    5043  480.17    5049  482.39  5063.9  482.24
    5070  484.68  5087.5  485.56  5365.8  491.08  5631.9  498.59  5825.4  501.96
#Mann= 7 ,-1 , 0
    3566     .05       0  4618.6     .12       0  4700.5     .05       0
  4797.6     .12       0  4988.8     .07       0  4993.1     .12       0
  5087.5     .05       0
Bank Sta=4988.8,4993.1
XS Rating Curve= 0 ,0
Exp/Cntr=0.3,0.1

Type RM Length L Ch R = 1 ,30285   ,1021,1021,1021
BEGIN DESCRIPTION:
Mapping XS 99bdc81f
END DESCRIPTION:
XS GIS Cut Line= 5
       2726335.9      6941783.61      2725391.48      6942092.63
      2724960.93      6942217.63      2724860.23      6942297.49
      2724506.06      6943002.37
#Sta/Elev= 30
  3570.8   500.1    3718  496.35  3932.9  492.43  4283.4     489  4474.6  488.09
  4511.7   488.8  4865.2   484.7    4893  484.24  4919.5  482.65  4932.3  482.56
  4945.1  484.07  4965.9  484.69  4986.7  482.76  4997.1  480.06  5002.5  479.81
  5002.9  479.31  5006.9  479.81  5009.9  481.14  5012.8  481.38  5054.7  480.77
    5090  481.23  5104.4   481.8  5110.8  483.31  5133.3  484.81  5148.5  484.87
  5178.7  484.16  5206.6  482.59  5251.3  485.44  5362.9  487.84  5930.2  497.68
#Mann= 5 ,-1 , 0
  3570.8     .05       0  4919.5     .12       0  5002.5     .07       0
  5006.9     .12       0  5148.5     .05       0
Bank Sta=5002.5,5006.9
XS Rating Curve= 0 ,0
Exp/Cntr=0.3,0.1

Type RM Length L Ch R = 1 ,29264   ,657,657,657
BEGIN DESCRIPTION:
Blackberry Creek 48.0
END DESCRIPTION:
XS GIS Cut Line= 4
      2726032.71       6941463.9      2724798.37      6941729.52
      2724303.58      6941549.83      2723774.97      6941922.21
#Sta/Elev= 30
  3500.1  495.75  4253.7  485.54    4356  481.56  4368.5  479.95  4412.7  479.77
    4448  483.09  4468.5  483.56  4591.2  482.74    4605  482.31  4621.9  479.93
  4673.1  480.45  4683.3  479.67  4693.6     481  4698.5  480.91  4703.7  482.36
  4771.8   483.7  4858.6  482.07  4882.2  481.31  4888.9  479.77  4986.3  479.52
  4986.8  479.02  4990.9  479.52  5037.6  479.65  5084.4  481.16  5105.7  480.74
  5169.5  485.53  5481.9   488.9  5525.1  487.33  5554.7  489.61  5935.7  494.09
#Mann= 6 ,-1 , 0
  3500.1     .05       0  4693.6     .12       0  4858.6      .1       0
  4986.3     .07       0  4990.9      .1       0  5037.6     .05       0
Bank Sta=4986.3,4990.9
XS Rating Curve= 0 ,0
Exp/Cntr=0.3,0.1

Type RM Length L Ch R = 1 ,28607   ,654,654,654
BEGIN DESCRIPTION:
Mapping XS df173ae2
END DESCRIPTION:
XS GIS Cut Line= 4
      2726153.36      6941152.96       2724941.6      6941149.49
      2724285.35      6941291.85      2723622.14      6941784.92
#Sta/Elev= 30
  3772.3  501.38  3969.7  499.37  4329.7  490.65  4559.7  486.42  4759.9  484.05
  4799.7  484.19  4839.7  482.93  4879.6  479.68  4907.3  479.65  4907.8  479.15
  4912.1  479.65  5116.6  479.98  5143.3   480.7  5163.8   480.1  5184.2  481.27
  5266.1   481.7  5286.5  482.53  5327.5  481.77  5521.9  482.01  5628.7   483.1
    5812  486.28  5847.4  485.95  5854.1  484.52    5862  484.45  5882.9  485.35
  5891.2  486.93  5897.5  487.23  6090.9  488.84  6112.3  489.86    6482  495.64
#Mann= 6 ,-1 , 0
  3772.3     .05       0  4759.9     .12       0  4879.6      .1       0
  4907.3     .07       0  4912.1      .1       0  5116.6     .05       0
Bank Sta=4907.3,4912.1
XS Rating Curve= 0 ,0
Exp/Cntr=0.3,0.1

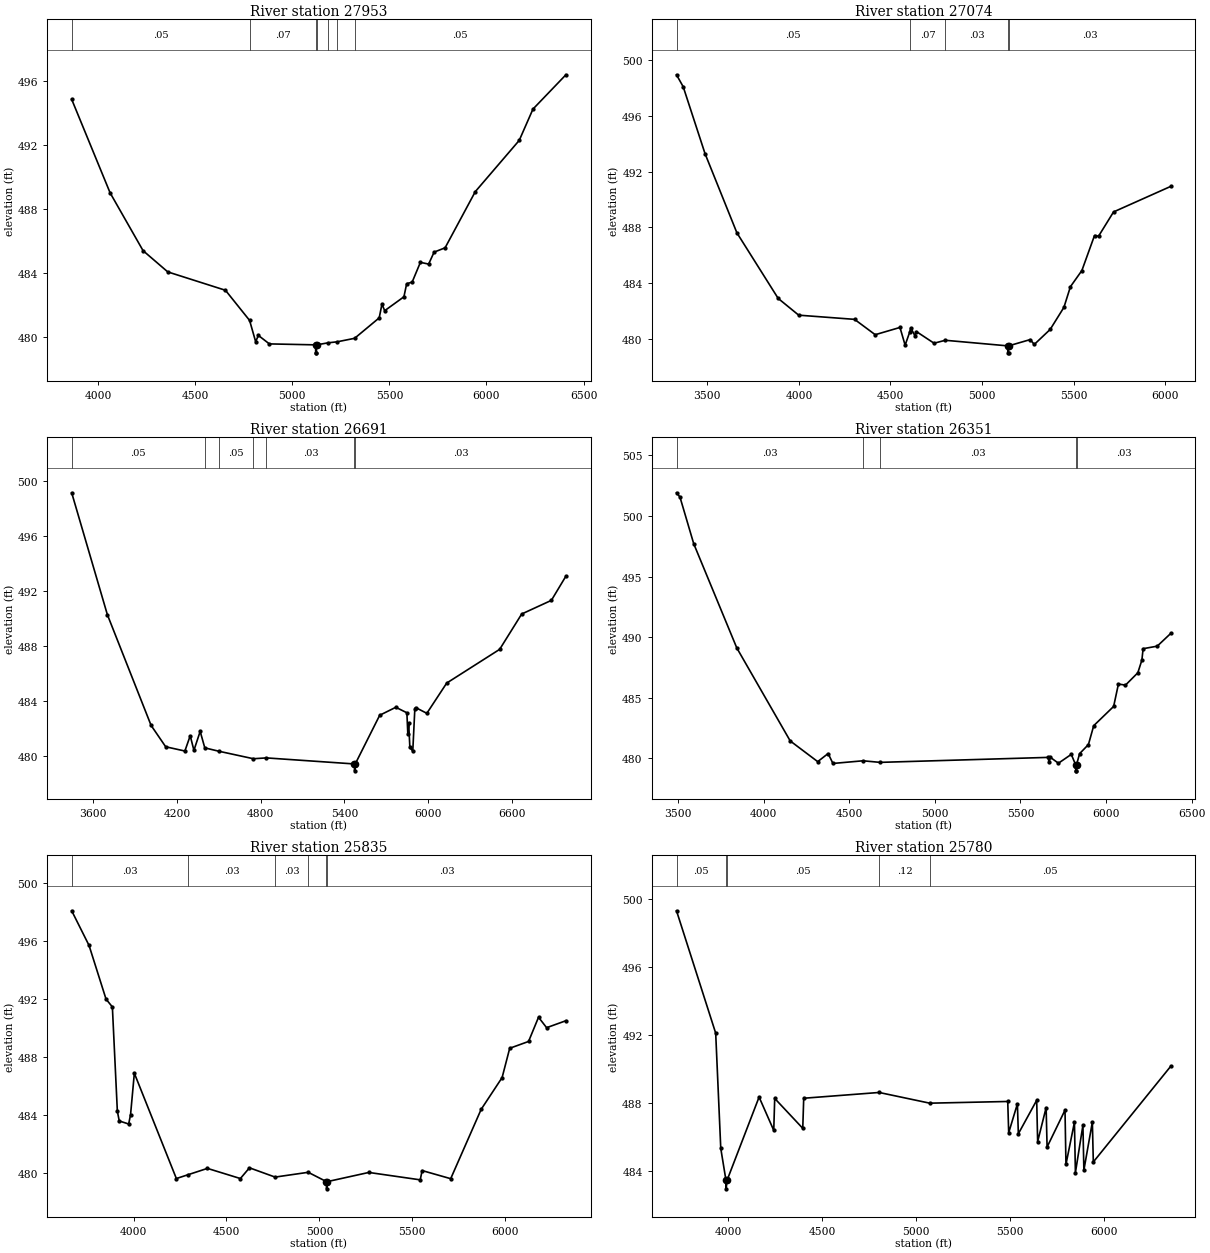
Type RM Length L Ch R = 1 ,27953   ,879,879,879
BEGIN DESCRIPTION:
Blackberry Creek 46.0
END DESCRIPTION:
XS GIS Cut Line= 3
      2725326.01      6939910.99        2724526.        6940711.
        2723526.        6941711.
#Sta/Elev= 30
  3863.6  494.86  4061.6     489  4231.3  485.38  4358.6  484.05  4655.6   482.9
    4780  481.01  4811.1  479.68  4825.3  480.07  4881.8  479.54  5119.8  479.48
  5120.4  478.98  5124.1  478.98  5124.8  479.48  5185.6  479.61  5230.5  479.67
  5320.8  479.89  5447.5  481.17  5461.7  482.03  5475.8  481.62  5574.8  482.49
    5589  483.31  5617.2  483.41  5659.7  484.65  5702.1  484.54  5730.4  485.29
  5786.9  485.56  5942.5  489.08  6168.8  492.29  6239.5  494.25  6409.2   496.4
#Mann= 7 ,-1 , 0
  3863.6     .05       0    4780     .07       0  5119.8     .05       0
  5124.8     .07       0  5185.6      .1       0  5230.5     .12       0
  5320.8     .05       0
Bank Sta=5119.8,5124.8
XS Rating Curve= 0 ,0
Exp/Cntr=0.3,0.1

Type RM Length L Ch R = 1 ,27074   ,383,383,383
BEGIN DESCRIPTION:
Blackberry Creek 45.0
END DESCRIPTION:
XS GIS Cut Line= 3
      2725326.04      6939510.98      2723825.96      6940241.02
      2723402.53      6941180.29
#Sta/Elev= 30
  3331.7  498.94  3368.3  498.08  3487.4  493.29  3661.5  487.61  3886.9  482.91
    3999  481.71  4303.9  481.41  4416.7  480.31  4551.9  480.83    4580  479.56
  4605.4  480.51  4610.7   480.8  4632.9  480.25  4642.1  480.53  4737.9   479.7
  4799.4  479.91    5140  479.51  5140.7  479.01  5144.5  479.01  5145.1  479.51
  5263.2  479.96  5285.2  479.61  5372.2  480.69  5447.1  482.27  5482.6  483.75
  5545.2  484.91  5614.2  487.42  5636.2  487.37  5718.1  489.11  6030.3  490.94
#Mann= 5 ,-1 , 0
  3331.7     .05       0  4605.4     .07       0  4799.4     .03       0
    5140     .03       0  5145.1     .03       0
Bank Sta=5140,5145.1
XS Rating Curve= 0 ,0
Exp/Cntr=0.3,0.1

Type RM Length L Ch R = 1 ,26691   ,340,340,340
BEGIN DESCRIPTION:
Mapping XS 69e13e17
END DESCRIPTION:
XS GIS Cut Line= 4
      2725315.58      6939412.52      2723825.89      6939858.25
      2722477.96      6940822.54       2722260.4      6941072.15
#Sta/Elev= 30
  3444.7  499.11  3700.5  490.25  4014.1   482.2  4118.6  480.65  4256.2  480.34
  4294.5  481.45  4321.1  480.39  4365.9  481.77    4399  480.57  4497.5  480.33
  4747.4  479.78  4840.5  479.84  5472.3   479.4    5473   478.9  5477.7   479.4
  5653.1  482.94  5768.6  483.52  5847.9  483.12  5854.6  481.61  5860.7   482.4
  5869.3   480.6  5890.2  480.33    5905  483.41  5911.1   483.5    5991  483.08
  6133.5  485.28  6513.1  487.73  6671.2   490.3  6883.9  491.29  6988.1  493.05
#Mann= 7 ,-1 , 0
  3444.7     .05       0    4399     .12       0  4497.5     .05       0
  4747.4     .03       0  4840.5     .03       0  5472.3     .03       0
  5477.7     .03       0
Bank Sta=5472.3,5477.7
XS Rating Curve= 0 ,0
Exp/Cntr=0.3,0.1

Type RM Length L Ch R = 1 ,26351   ,516,516,516
BEGIN DESCRIPTION:
Blackberry Creek 44.0
END DESCRIPTION:
XS GIS Cut Line= 3
      2725375.96        6939361.      2723871.29      6939534.44
      2722539.51      6939867.39
#Sta/Elev= 30
  3490.3  501.92  3510.4  501.57  3590.9  497.71  3842.6   489.1  4154.6  481.42
  4315.3  479.71  4376.1  480.38  4404.2  479.56  4579.8  479.78  4679.7  479.65
  5659.8  480.06    5668  479.65  5673.1  480.08  5721.6  479.58  5796.8  480.31
    5822  479.45  5822.7  478.95  5826.6  478.95  5827.4  479.45  5845.3  480.37
  5896.9  481.12  5927.8  482.68  6044.2  484.27  6072.1  486.12  6113.3  486.03
  6185.5  487.05  6209.2   488.1  6216.4  489.04  6298.9  489.25  6377.7   490.3
#Mann= 5 ,-1 , 0
  3490.3     .03       0  4579.8     .03       0  4679.7     .03       0
    5822     .03       0  5827.4     .03       0
Bank Sta=5822,5827.4
XS Rating Curve= 0 ,0
Exp/Cntr=0.3,0.1

Type RM Length L Ch R = 1 ,25835   ,55,55,55
BEGIN DESCRIPTION:
Blackberry Creek 42.0
END DESCRIPTION:
XS GIS Cut Line= 3
      2725067.91      6938847.98      2723755.72      6939080.89
      2722460.84      6939368.76
#Sta/Elev= 30
  3667.3  498.07  3760.7  495.68  3852.1  491.98  3886.2  491.44    3913  484.25
  3923.2  483.58  3973.9  483.37  3984.1  484.02  4004.4  486.87  4230.5  479.61
    4295  479.88  4397.6  480.31  4574.9  479.61  4623.8  480.35  4761.8  479.71
  4939.9  480.04  5037.8   479.4  5038.7   478.9  5043.5   479.4  5266.1  480.03
  5542.7  479.52  5552.9  480.16  5706.6   479.6  5870.5  484.38  5983.2  486.57
  6024.1  488.59  6125.5  489.06  6179.2  490.73  6222.7  490.01  6326.5  490.49
#Mann= 6 ,-1 , 0
  3667.3     .03       0    4295     .03       0  4761.8     .03       0
  4939.9     .03       0  5037.8     .03       0  5043.5     .03       0
Bank Sta=5037.8,5043.5
XS Rating Curve= 0 ,0
Exp/Cntr=0.3,0.1

Type RM Length L Ch R = 1 ,25780   ,117,117,117
BEGIN DESCRIPTION:
Mapping XS 0f974ccc
END DESCRIPTION:
XS GIS Cut Line= 4
      2725027.03      6938786.17      2723770.07       6939032.7
      2723152.02      6939154.23      2722449.09      6939299.66
#Sta/Elev= 30
  3725.6  499.31    3934  492.11    3961  485.33  3988.7  483.45  3989.6  482.95
  3994.4  483.45  4164.8  488.35  4242.8  486.39  4247.9  488.27  4397.1  486.51
  4402.2  488.28  4803.3  488.62  5072.6  487.99  5487.3  488.09  5492.4  486.25
  5538.7  487.95  5543.8  486.19  5641.3  488.16  5646.4  485.73  5691.5  487.73
  5696.6  485.41  5791.9  487.58    5797  484.39  5842.1  486.87  5847.2   483.9
  5887.2  486.69  5892.3  484.05  5937.4  486.88  5942.5  484.53  6354.2  490.16
#Mann= 5 ,-1 , 0
  3725.6     .05       0  3988.7     .07       0  3994.4     .05       0
  4803.3     .12       0  5072.6     .05       0
Bank Sta=3988.7,3994.4
XS Rating Curve= 0 ,0
Exp/Cntr=0.3,0.1