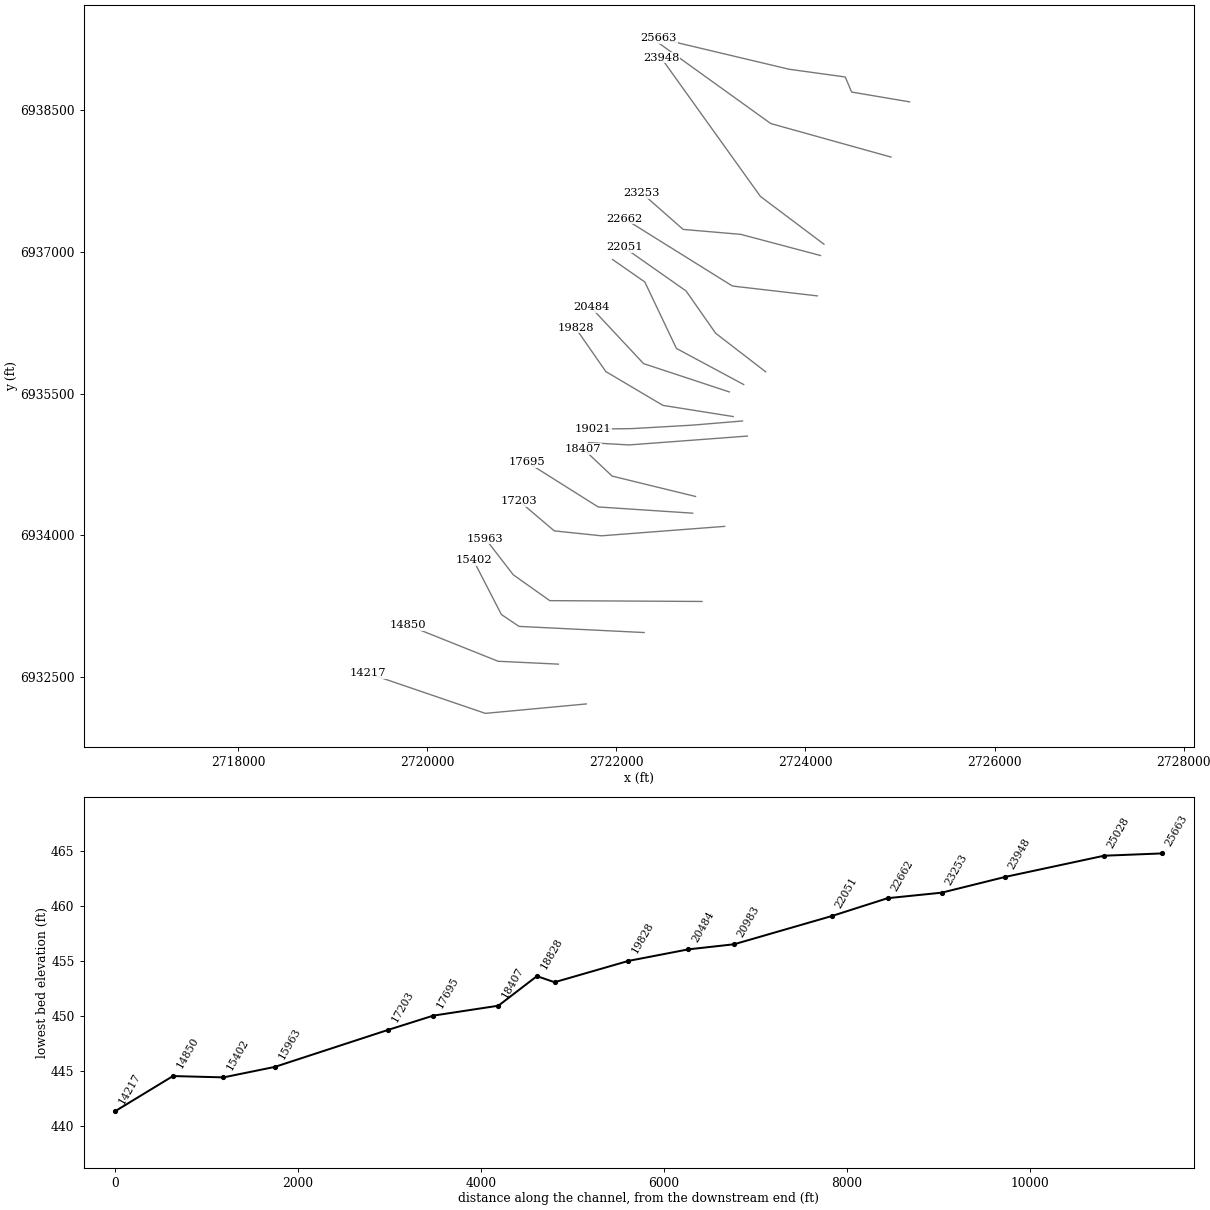
HEC-RAS study Blackberry Creek.prj: Blackberry Creek Base Level Engineering

--- Blackberry Creek.g01 (geometry) --- (continued)

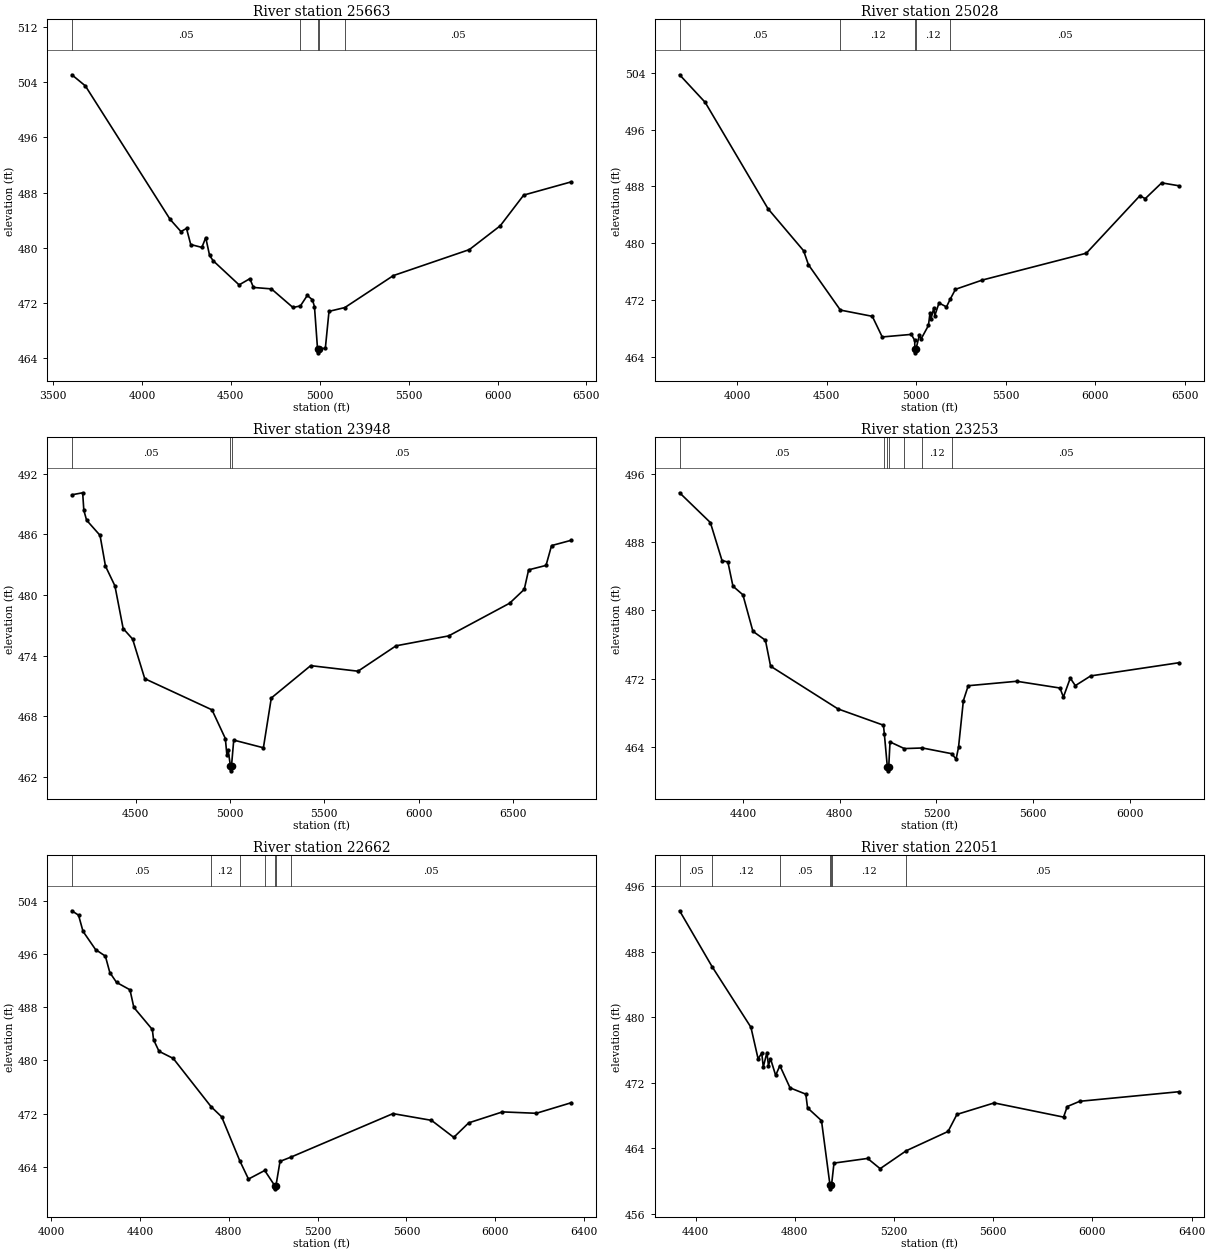
Type RM Length L Ch R = 1 ,25663   ,635,635,635
BEGIN DESCRIPTION:
Mapping XS 119ec998
END DESCRIPTION:
XS GIS Cut Line= 5
      2725100.96      6938586.01      2724488.18      6938689.78
      2724420.74      6938849.25       2723826.6      6938931.05
      2722449.06      6939257.95
#Sta/Elev= 30
  3605.6   505.1  3681.6  503.49  4158.3  484.12  4219.2  482.35  4250.6   482.8
  4274.3  480.47    4337  480.05  4358.7  481.47  4380.4  478.88  4400.3  478.12
  4546.4  474.61  4606.9  475.51  4627.1  474.24  4728.1  474.03  4849.2  471.33
  4891.2  471.56  4929.9  473.08  4959.1  472.44  4970.3  471.44  4987.7  465.25
  4988.6  464.75  4993.4  465.25  5031.5  465.44    5052  470.77    5141  471.32
    5414  475.96  5841.3  479.73  6015.3  483.19    6147  487.64  6415.8  489.57
#Mann= 5 ,-1 , 0
  3605.6     .05       0  4891.2     .12       0  4987.7     .07       0
  4993.4     .12       0    5141     .05       0
Bank Sta=4987.7,4993.4
XS Rating Curve= 0 ,0
Exp/Cntr=0.3,0.1

Type RM Length L Ch R = 1 ,25028   ,1080,1080,1080
BEGIN DESCRIPTION:
Mapping XS 813e3113
END DESCRIPTION:
XS GIS Cut Line= 3
      2724903.72      6938002.33      2723632.92      6938356.49
      2722436.08      6939216.82
#Sta/Elev= 30
  3677.1  503.75  3820.1  499.86  4171.4  484.86  4370.3  478.94  4397.4  476.96
  4575.9  470.57  4754.4  469.69  4809.9  466.78  4972.4  467.14  4991.2  466.31
  4992.6  465.04  4993.5  464.54  4998.3  465.04    5018   467.1  5026.5  466.47
  5068.3   468.4  5076.9  470.18    5083  469.37  5097.8  470.84  5103.9  469.79
  5127.2  471.57    5169  471.02  5189.6  472.09  5219.3   473.5  5370.3  474.81
    5951  478.59  6250.5   486.7    6280  486.28  6372.1  488.51  6470.3  488.09
#Mann= 5 ,-1 , 0
  3677.1     .05       0  4575.9     .12       0  4992.6     .07       0
  4998.3     .12       0  5189.6     .05       0
Bank Sta=4992.6,4998.3
XS Rating Curve= 0 ,0
Exp/Cntr=0.3,0.1

Type RM Length L Ch R = 1 ,23948   ,695,695,695
BEGIN DESCRIPTION:
Mapping XS f626b4b2
END DESCRIPTION:
XS GIS Cut Line= 3
      2724195.43      6937080.44      2723523.54      6937585.66
      2722471.48      6939054.38
#Sta/Elev= 30
  4162.2  489.91  4219.6  490.11  4225.8  488.37  4240.4   487.4  4311.6   485.9
  4340.4  482.86  4390.4  480.91  4434.1  476.69  4484.1  475.65  4548.6  471.73
  4904.8  468.65  4975.6  465.81  4983.9  464.14  4990.1  464.71  5002.3  463.12
  5003.2  462.62  5008.2  463.12    5020  465.66  5177.2   464.9    5219  469.82
  5427.6  473.02  5678.4  472.47  5879.8  474.98  6158.7  475.96  6481.7  479.19
  6559.3  480.56  6582.4  482.49  6674.6  482.93    6704  484.89  6809.5  485.42
#Mann= 3 ,-1 , 0
  4162.2     .05       0  5002.3     .04       0  5008.2     .05       0
Bank Sta=5002.3,5008.2
XS Rating Curve= 0 ,0
Exp/Cntr=0.3,0.1

Type RM Length L Ch R = 1 ,23253   ,591,591,591
BEGIN DESCRIPTION:
Mapping XS 7cf8c1db
END DESCRIPTION:
XS GIS Cut Line= 4
      2724158.97      6936960.65      2723315.21      6937184.61
      2722705.84       6937236.7      2722269.64      6937620.97
#Sta/Elev= 30
  4138.2  493.79  4265.4   490.3  4313.5  485.85  4337.9  485.67  4358.8  482.84
  4399.9  481.83  4441.3  477.55  4493.1   476.5  4514.4  473.46  4793.1  468.45
  4981.1  466.54  4984.7  465.54    4997  461.69    4998  461.19    5003  461.69
  5008.2  464.58  5067.4   463.8  5142.4  463.87  5263.3   463.2  5281.4  462.57
  5291.4  463.93  5311.5  469.42  5331.6  471.17  5532.3  471.69  5710.8   470.9
  5725.1  469.84  5753.5  472.06  5774.4  471.18    5838  472.32  6204.1  473.87
#Mann= 7 ,-1 , 0
  4138.2     .05       0  4984.7     .12       0    4997     .07       0
    5003     .12       0  5067.4      .1       0  5142.4     .12       0
  5263.3     .05       0
Bank Sta=4997,5003
XS Rating Curve= 0 ,0
Exp/Cntr=0.3,0.1

Type RM Length L Ch R = 1 ,22662   ,611,611,611
BEGIN DESCRIPTION:
Mapping XS d877b1d3
END DESCRIPTION:
XS GIS Cut Line= 3
        2724126.      6936533.57      2723227.54      6936637.74
      2722086.07      6937349.53
#Sta/Elev= 30
  4093.7   502.5  4123.9  501.84    4144  499.41  4200.5  496.67  4244.7  495.68
  4264.8  493.21    4295  491.73  4355.4  490.62  4372.9  487.97  4456.1  484.65
  4461.6  483.12  4486.3  481.37  4550.3   480.3  4720.5  473.05  4768.2  471.52
  4849.9  464.91    4889  462.16  4962.2  463.45  5006.8  461.19  5007.8  460.69
  5012.9  461.19  5031.1  464.82  5079.5  465.45  5539.6     472    5713  470.99
  5813.3  468.43  5880.6  470.61  6032.8  472.26    6185  472.05  6343.4  473.65
#Mann= 7 ,-1 , 0
  4093.7     .05       0  4720.5     .12       0  4849.9      .1       0
  4962.2     .12       0  5006.8     .07       0  5012.9     .12       0
  5079.5     .05       0
Bank Sta=5006.8,5012.9
XS Rating Curve= 0 ,0
Exp/Cntr=0.3,0.1

Type RM Length L Ch R = 1 ,22051   ,1068,1068,1068
BEGIN DESCRIPTION:
Mapping XS 1b381048
END DESCRIPTION:
XS GIS Cut Line= 4
      2723579.09      6935730.63      2723049.59      6936138.61
      2722737.09      6936585.66      2722081.73      6937045.71
#Sta/Elev= 30
  4335.3  492.99    4466  486.19  4622.9  478.78  4651.9  474.92  4666.4  475.64
  4672.8  473.93  4687.3   475.7  4693.6  474.11  4701.8  474.95  4722.6  472.91
  4739.6   474.1  4780.6  471.39  4844.2  470.62  4851.2  468.95  4907.4  467.39
  4941.5  459.57  4942.5  459.07  4947.7  459.57  4948.3  459.64  4957.8  462.21
  5093.4  462.78  5143.9  461.53  5249.4  463.72  5417.8  466.07  5453.5  468.15
  5603.7  469.55  5883.5  467.82  5898.3  469.11  5948.8  469.75  6349.9  470.92
#Mann= 7 ,-1 , 0
  4335.3     .05       0    4466     .12       0  4739.6     .05       0
  4941.5     .07       0  4947.7     .05       0  4948.3     .12       0
  5249.4     .05       0
Bank Sta=4941.5,4947.7
XS Rating Curve= 0 ,0
Exp/Cntr=0.3,0.1

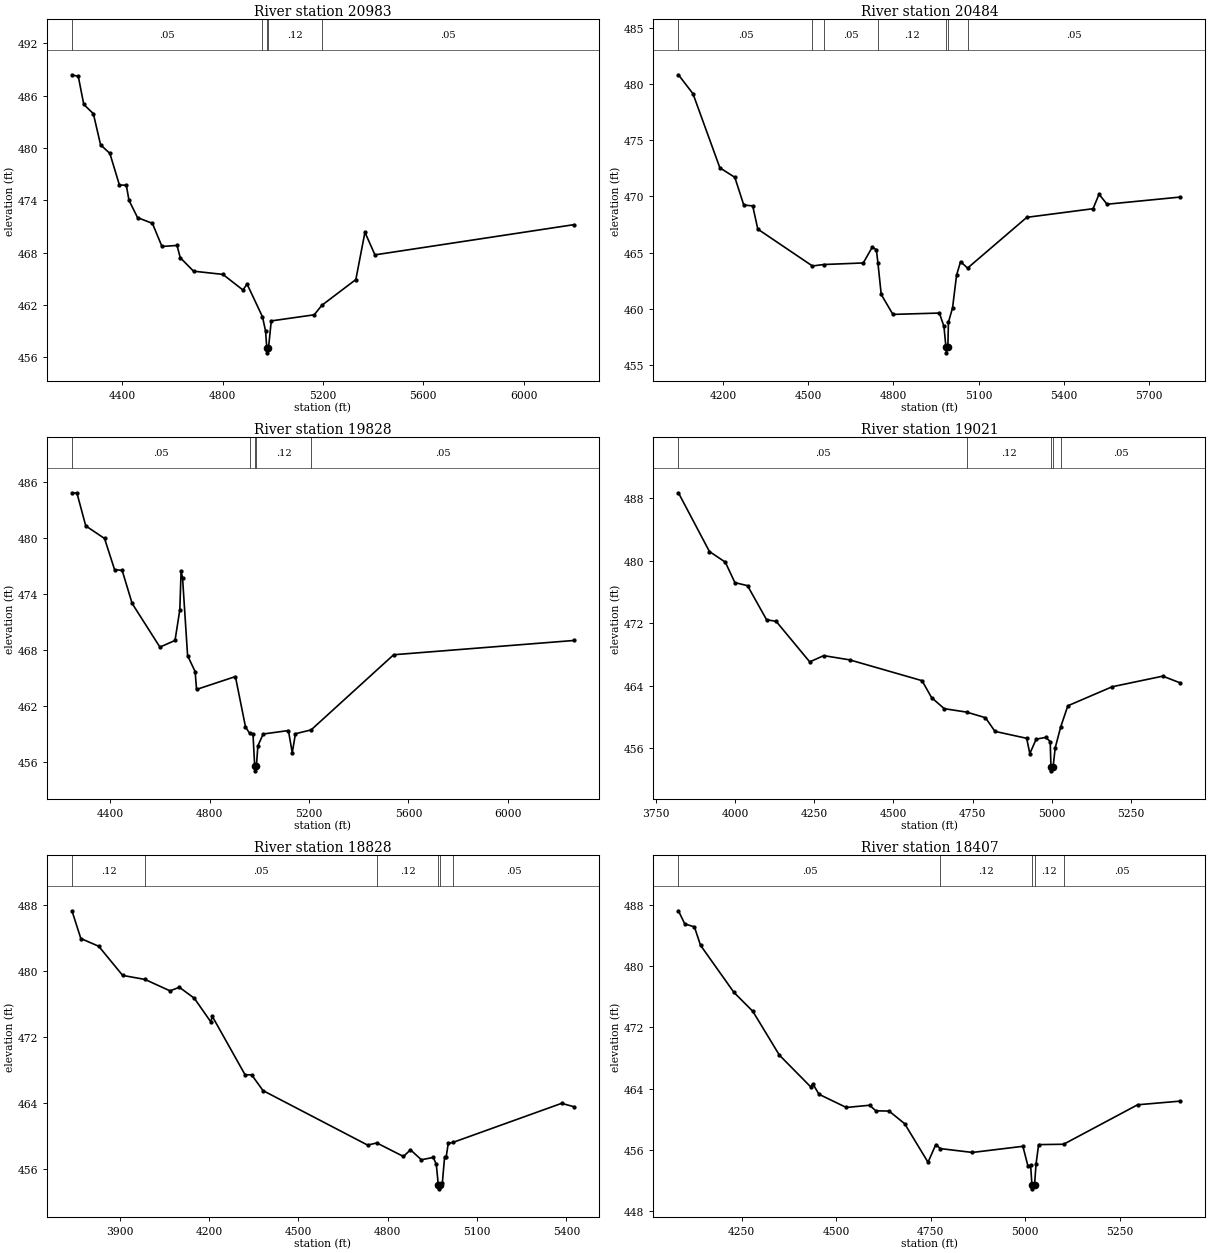
Type RM Length L Ch R = 1 ,20983   ,499,499,499
BEGIN DESCRIPTION:
Mapping XS 54fea6a1
END DESCRIPTION:
XS GIS Cut Line= 4
      2723346.59       6935595.8      2722634.82      6935977.73
      2722300.62      6936680.85      2721959.35      6936918.44
#Sta/Elev= 30
  4198.7  488.38    4224  488.19  4245.9  484.98  4284.1  483.92  4312.9  480.35
  4349.9  479.37    4388  475.75  4415.6  475.72  4426.2  473.99  4460.4  472.01
  4519.6  471.35  4557.8   468.7  4617.9  468.82  4630.6  467.42  4683.6  465.87
  4800.9   465.5  4880.9  463.71  4897.2   464.4  4958.7  460.64  4971.1     459
    4976  457.01    4977  456.51  4982.5  457.01  4993.8  460.17  5165.1  460.87
  5195.6  461.96  5331.2  464.91  5367.4  470.33  5407.3  467.74  6200.8   471.2
#Mann= 5 ,-1 , 0
  4198.7     .05       0  4958.7     .12       0    4976     .07       0
  4982.5     .12       0  5195.6     .05       0
Bank Sta=4976,4982.5
XS Rating Curve= 0 ,0
Exp/Cntr=0.3,0.1

Type RM Length L Ch R = 1 ,20484   ,656,656,656
BEGIN DESCRIPTION:
Mapping XS 18bbecb2
END DESCRIPTION:
XS GIS Cut Line= 3
      2723194.73      6935517.65       2722287.6      6935817.14
      2721732.01      6936411.78
#Sta/Elev= 30
  4041.9  480.86  4093.2  479.17    4188  472.56  4240.7  471.71  4272.2  469.24
  4303.8  469.16  4321.7  467.09  4514.2   463.8  4553.8  463.93  4693.5  464.07
  4725.1  465.48  4739.6  465.25  4745.3  464.04  4756.7  461.26  4797.9  459.48
  4961.8   459.6  4977.8  458.41  4984.9  456.55    4986  456.05  4991.7  456.55
  4993.6  458.78  5008.1  460.05  5022.3  462.98  5036.4  464.19  5061.1  463.61
  5269.9  468.14  5503.4  468.91  5524.5   470.2  5552.8  469.31    5811  469.95
#Mann= 7 ,-1 , 0
  4041.9     .05       0  4514.2     .12       0  4553.8     .05       0
  4745.3     .12       0  4984.9     .07       0  4991.7     .12       0
  5061.1     .05       0
Bank Sta=4984.9,4991.7
XS Rating Curve= 0 ,0
Exp/Cntr=0.3,0.1

Type RM Length L Ch R = 1 ,19828   ,807,807,807
BEGIN DESCRIPTION:
Mapping XS c8384a5b
END DESCRIPTION:
XS GIS Cut Line= 4
      2723235.52      6935257.24      2722492.46       6935375.3
      2721888.29      6935732.94      2721566.13      6936197.13
#Sta/Elev= 30
    4246  484.77  4265.8  484.82  4301.5  481.27  4377.1  479.92  4417.6  476.57
    4448   476.5  4488.2  472.95  4599.9  468.27  4660.7  468.98    4680  472.26
  4685.1  476.39    4691   475.7  4711.3  467.36  4741.7  465.64  4747.3  463.73
  4903.7  465.11  4944.2  459.73  4960.8  459.02  4974.5   458.9  4981.3   455.5
  4982.4     455  4988.1   455.5  4994.1  457.68  5015.5  458.95  5116.9  459.32
  5132.5  456.94  5145.3  458.98  5208.3  459.39  5540.4  467.45  6265.5  468.98
#Mann= 5 ,-1 , 0
    4246     .05       0  4960.8     .12       0  4981.3     .07       0
  4988.1     .12       0  5208.3     .05       0
Bank Sta=4981.3,4988.1
XS Rating Curve= 0 ,0
Exp/Cntr=0.3,0.1

Type RM Length L Ch R = 1 ,19021   ,193,193,193
BEGIN DESCRIPTION:
Mapping XS 1fa5f61a
END DESCRIPTION:
XS GIS Cut Line= 4
      2723333.62      6935210.37      2722799.75       6935166.1
      2722161.73      6935129.64      2721750.62      6935124.43
#Sta/Elev= 30
  3820.7  488.72  3918.7  481.19  3968.8  479.83  3999.2   477.2  4039.1  476.81
  4099.3  472.44  4129.4  472.24  4235.6  467.04  4279.9  467.84  4361.6   467.3
  4590.5  464.63  4620.6  462.46  4660.6  461.04  4731.4   460.6  4790.9  459.88
  4820.9  458.13  4921.1  457.24  4931.1  455.28  4951.1  457.13  4981.2  457.36
  4995.5  456.83  4997.8  453.57  4998.9  453.07  5004.6  453.57  5011.2     456
  5028.6   458.7  5051.2  461.41  5191.2  463.85  5351.2  465.21  5406.6  464.34
#Mann= 5 ,-1 , 0
  3820.7     .05       0  4731.4     .12       0  4997.8     .07       0
  5004.6     .12       0  5028.6     .05       0
Bank Sta=4997.8,5004.6
XS Rating Curve= 0 ,0
Exp/Cntr=0.3,0.1

Type RM Length L Ch R = 1 ,18828   ,421,421,421
BEGIN DESCRIPTION:
Mapping XS 254f3998
END DESCRIPTION:
XS GIS Cut Line= 3
      2723385.68      6935050.86      2722135.69      6934957.11
      2721705.08      6934981.42
#Sta/Elev= 30
  3739.9  487.31  3769.7  483.95  3829.8  483.01  3910.1  479.48  3985.1  478.99
  4068.9  477.61  4100.6  478.04  4150.7  476.71    4206  473.85    4211  474.52
  4321.2  467.43    4343  467.44  4381.4  465.52  4732.4  458.92  4763.3  459.18
  4852.7  457.54  4876.2  458.35  4912.9  457.14    4953  457.43    4963  456.57
  4969.6  454.12  4970.7  453.62  4976.5  454.12  4983.1  454.28  4990.7  457.43
  4995.8  457.43  5003.1  459.12  5019.2  459.25  5383.7  463.98  5424.7  463.57
#Mann= 6 ,-1 , 0
  3739.9     .12       0  3985.1     .05       0  4763.3     .12       0
  4969.6     .07       0  4976.5     .12       0  5019.2     .05       0
Bank Sta=4969.6,4976.5
XS Rating Curve= 0 ,0
Exp/Cntr=0.3,0.1

Type RM Length L Ch R = 1 ,18407   ,712,712,712
BEGIN DESCRIPTION:
Mapping XS fb00f80c
END DESCRIPTION:
XS GIS Cut Line= 3
      2722837.07      6934411.97      2721955.13      6934627.25
      2721650.27      6934914.79
#Sta/Elev= 30
  4083.1  487.23  4099.9  485.52  4125.4  485.13  4141.5  482.73    4230  476.57
  4279.8  474.11  4349.9   468.4  4433.2  464.23  4438.4  464.65  4454.8  463.28
  4526.9  461.56  4588.6  461.85  4605.1  461.12  4640.1  461.09  4681.2  459.44
    4743  454.41  4763.6  456.72  4775.9  456.19  4860.3  455.69  4993.8  456.49
    5007  453.95  5014.3  453.99  5017.7  451.44  5018.8  450.94  5024.6  451.44
  5028.5  454.13  5035.3  456.71  5101.5  456.76  5297.1  461.91    5410  462.39
#Mann= 5 ,-1 , 0
  4083.1     .05       0  4775.9     .12       0  5017.7     .07       0
  5024.6     .12       0  5101.5     .05       0
Bank Sta=5017.7,5024.6
XS Rating Curve= 0 ,0
Exp/Cntr=0.3,0.1

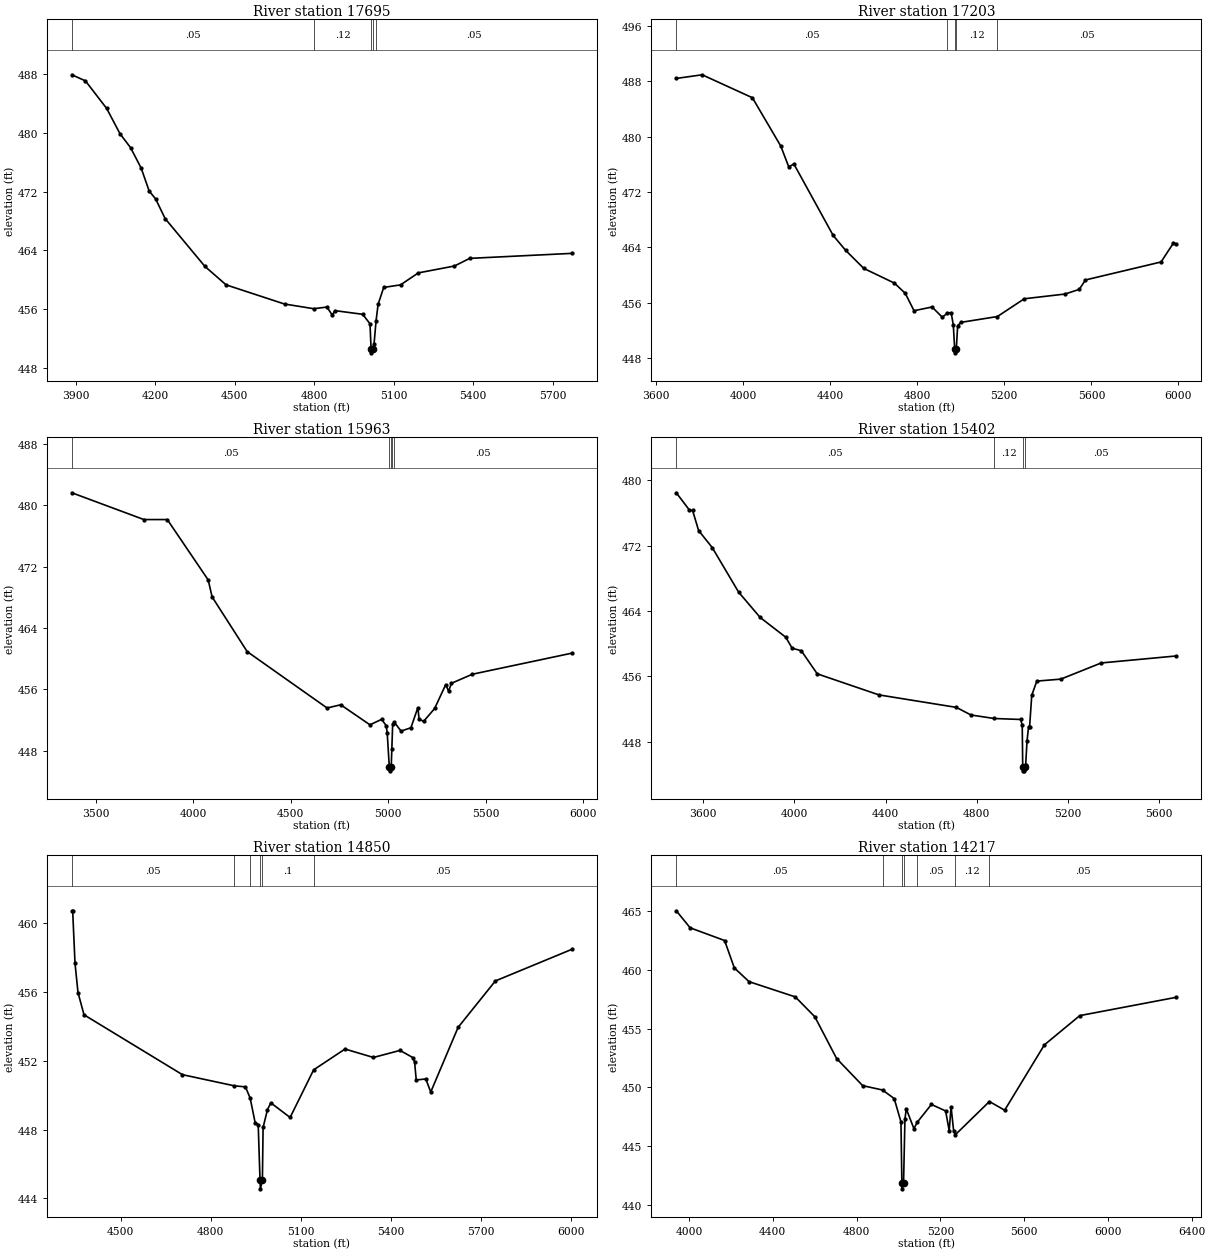
Type RM Length L Ch R = 1 ,17695   ,492,492,492
BEGIN DESCRIPTION:
Mapping XS b5650aad
END DESCRIPTION:
XS GIS Cut Line= 3
      2722807.23      6934235.18      2721807.27      6934301.15
      2721057.29      6934773.36
#Sta/Elev= 30
  3884.7  487.92    3936  487.09  4016.2  483.33  4066.3   479.9  4106.4  477.99
  4146.5   475.2  4176.6  472.09  4201.3  470.99  4236.7  468.34    4387  461.82
  4467.2   459.3  4687.7  456.69  4798.4  456.05    4848  456.28  4868.1  455.17
  4878.1  455.79  4982.9  455.29  5010.5     454  5014.7  450.54  5015.8  450.04
    5022  450.54  5025.8  451.22  5033.3  454.35  5041.1  456.64  5062.3  458.95
  5125.9   459.3    5193  460.93  5329.5  461.87  5387.2  462.91  5773.1  463.59
#Mann= 5 ,-1 , 0
  3884.7     .05       0  4798.4     .12       0  5014.7     .07       0
    5022     .12       0  5033.3     .05       0
Bank Sta=5014.7,5022
XS Rating Curve= 0 ,0
Exp/Cntr=0.3,0.1

Type RM Length L Ch R = 1 ,17203   ,1240,1240,1240
BEGIN DESCRIPTION:
Mapping XS aafd1d46
END DESCRIPTION:
XS GIS Cut Line= 4
      2723144.36      6934095.59      2721842.28      6933995.77
      2721343.15      6934047.85      2720970.46      6934364.21
#Sta/Elev= 30
  3693.8  488.43  3812.5  488.96  4043.2  485.64  4173.6  478.65  4210.2  475.64
  4233.7  476.06  4414.3  465.72  4471.4  463.57  4554.7  460.96  4695.1  458.84
  4745.2  457.36  4785.4  454.84  4868.2  455.38  4915.7  453.89  4938.8  454.51
  4955.9  454.55  4965.9   452.8  4972.3  449.25  4973.4  448.75  4979.6  449.25
  4985.9  452.69  5001.5  453.16  5168.5     454  5291.8  456.57  5478.6  457.25
  5544.4  457.93  5572.9  459.29    5920  461.89  5977.1  464.64  5990.4  464.44
#Mann= 5 ,-1 , 0
  3693.8     .05       0  4938.8     .12       0  4972.3     .07       0
  4979.6     .12       0  5168.5     .05       0
Bank Sta=4972.3,4979.6
XS Rating Curve= 0 ,0
Exp/Cntr=0.3,0.1

Type RM Length L Ch R = 1 ,15963   ,561,561,561
BEGIN DESCRIPTION:
Mapping XS 050579c3
END DESCRIPTION:
XS GIS Cut Line= 4
      2722905.69      6933301.32      2721295.41        6933310.
      2720909.12      6933583.44      2720613.96      6933965.42
#Sta/Elev= 30
  3376.5  481.63  3746.2  478.14  3866.2  478.14  4076.2  470.27  4096.2  468.06
  4276.2  460.93  4686.2  453.58  4756.2     454  4906.2  451.39  4966.2   452.1
  4989.5  451.28  4994.7  450.38  5005.6  445.89  5006.8  445.39  5013.3  445.89
  5015.6     446  5018.5   448.2  5022.8  451.45    5031  451.73  5066.1  450.57
  5116.5  451.01  5152.2  453.63  5158.3  452.14  5181.8  451.84  5238.4  453.52
    5295  456.63  5309.7  455.77  5324.5   456.8  5431.6  457.98  5942.8  460.73
#Mann= 5 ,-1 , 0
  3376.5     .05       0  5005.6     .04       0  5013.3     .05       0
  5018.5     .12       0    5031     .05       0
Bank Sta=5005.6,5013.3
XS Rating Curve= 0 ,0
Exp/Cntr=0.3,0.1

Type RM Length L Ch R = 1 ,15402   ,552,552,552
BEGIN DESCRIPTION:
Mapping XS 696cab6f
END DESCRIPTION:
XS GIS Cut Line= 4
       2722293.7      6932972.55      2720969.89      6933037.65
      2720783.26      6933163.52      2720488.25      6933736.18
#Sta/Elev= 30
  3481.9  478.49  3539.7  476.36  3553.4  476.32  3579.7  473.87  3639.8  471.77
  3755.4  466.32    3850  463.22  3962.3   460.8  3990.2  459.46  4030.3  459.15
  4100.3  456.32  4371.1  453.74  4711.1  452.21  4774.9  451.28  4876.9  450.85
  4992.9  450.73    5000  450.04  5002.2  444.94  5003.4  444.44  5008.8  444.44
    5010  444.94    5015  445.13    5021  448.06  5027.8  449.86  5032.4  449.86
  5041.9   453.7  5064.1  455.43  5169.3  455.67  5346.6  457.65  5676.6  458.51
#Mann= 4 ,-1 , 0
  3481.9     .05       0  4876.9     .12       0  5002.2     .07       0
    5010     .05       0
Bank Sta=5002.2,5010
XS Rating Curve= 0 ,0
Exp/Cntr=0.3,0.1

Type RM Length L Ch R = 1 ,14850   ,633,633,633
BEGIN DESCRIPTION:
Mapping XS 50aaf8e5
END DESCRIPTION:
XS GIS Cut Line= 3
      2721386.51      6932638.35      2720748.53      6932668.73
      2719793.69      6933050.67
#Sta/Elev= 30
    4337  460.73  4339.7  460.73  4347.5  457.68  4357.5  455.97  4377.6  454.68
  4705.5   451.2  4878.8  450.55  4915.7  450.49  4931.5  449.83  4948.2  448.39
  4958.2   448.3  4964.3  445.06  4965.5  444.56  4972.2  445.06  4974.5  448.13
  4989.2  449.17  5000.3  449.56  5064.6  448.71    5143  451.48  5247.7  452.69
  5342.3   452.2  5431.1  452.61  5473.9  452.19  5479.6  451.94    5485  450.89
  5516.9  450.95  5533.4  450.19  5624.6  453.95  5748.9  456.65  6004.1  458.49
#Mann= 6 ,-1 , 0
    4337     .05       0  4878.8     .12       0  4931.5      .1       0
  4964.3     .07       0  4972.2      .1       0    5143     .05       0
Bank Sta=4964.3,4972.2
XS Rating Curve= 0 ,0
Exp/Cntr=0.3,0.1

Type RM Length L Ch R = 1 ,14217   ,957,957,957
BEGIN DESCRIPTION:
Mapping XS 82bdc39d
END DESCRIPTION:
XS GIS Cut Line= 3
      2721681.72      6932217.34      2720613.98      6932117.51
      2719369.62      6932542.42
#Sta/Elev= 30
  3939.7  465.03  4005.7  463.58  4170.2   462.5  4216.6  460.17  4286.9     459
  4507.9   457.7    4601  456.01  4704.9  452.46  4829.3  450.15  4924.2  449.78
  4979.9  449.05  5012.1  447.07  5016.5  441.87  5017.7  441.37  5024.5  441.87
  5031.1  447.29  5037.4  448.18    5074  446.49  5090.1  447.04  5157.4  448.55
  5225.3     448  5242.4  446.32  5251.3  448.35  5263.6  446.31  5272.1  445.98
  5434.4   448.8  5507.2  448.06  5696.8  453.62  5865.9  456.11    6327  457.67
#Mann= 7 ,-1 , 0
  3939.7     .05       0  4924.2     .12       0  5016.5     .07       0
  5024.5     .12       0  5090.1     .05       0  5272.1     .12       0
  5434.4     .05       0
Bank Sta=5016.5,5024.5
XS Rating Curve= 0 ,0
Exp/Cntr=0.3,0.1