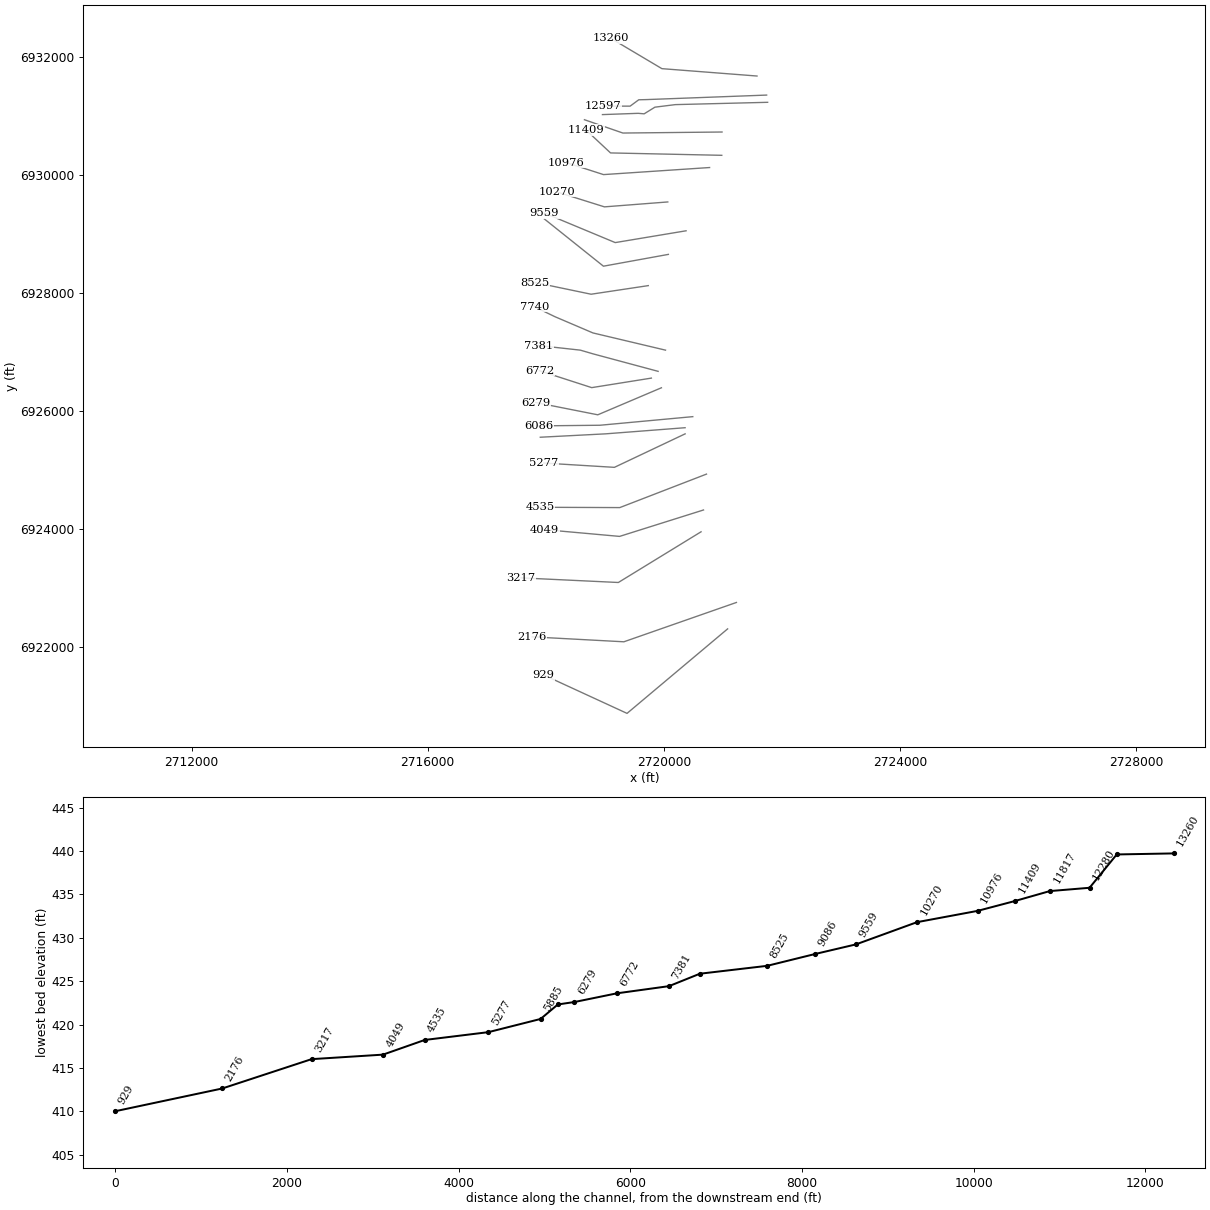
HEC-RAS study Blackberry Creek.prj: Blackberry Creek Base Level Engineering

--- Blackberry Creek.g01 (geometry) --- (continued)

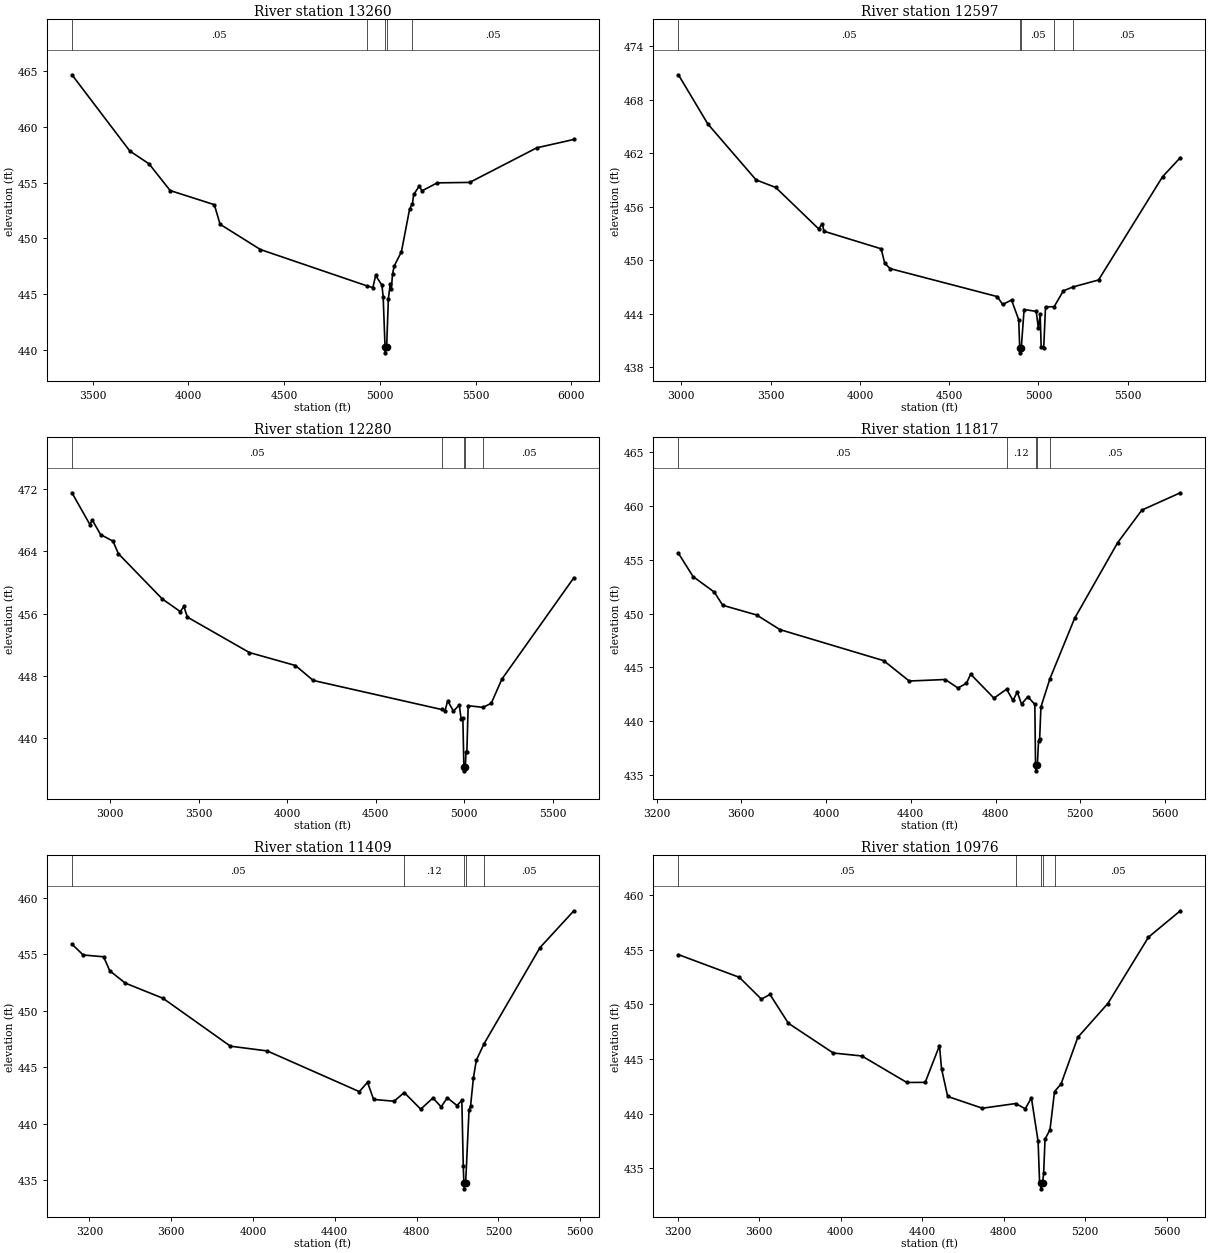
Type RM Length L Ch R = 1 ,13260   ,663,663,663
BEGIN DESCRIPTION:
Mapping XS a63b98b3
END DESCRIPTION:
XS GIS Cut Line= 3
      2721577.51      6931684.35      2719966.42      6931809.35
      2719101.84      6932323.24
#Sta/Elev= 30
  3391.7   464.7  3694.1  457.85  3794.4   456.7  3904.7   454.3  4135.4  453.03
  4165.5  451.27  4376.2     449  4930.3  445.75  4963.6  445.58    4978  446.67
  5010.8   445.8  5017.3  444.78  5027.2  440.22  5028.4  439.72  5035.5  440.22
  5044.5  444.56  5054.3  445.93  5060.1  445.45  5066.3  446.83  5075.7  447.54
  5112.8  448.81  5155.6  452.65  5170.2  453.12    5177  453.95  5205.9   454.7
  5219.8  454.27  5299.7  454.99  5469.2  455.03  5819.9  458.14  6013.4  458.89
#Mann= 5 ,-1 , 0
  3391.7     .05       0  4930.3     .12       0  5027.2     .07       0
  5035.5     .12       0  5170.2     .05       0
Bank Sta=5027.2,5035.5
XS Rating Curve= 0 ,0
Exp/Cntr=0.3,0.1

Type RM Length L Ch R = 1 ,12597   ,317,317,317
BEGIN DESCRIPTION:
Mapping XS f9dce575
END DESCRIPTION:
XS GIS Cut Line= 5
       2721740.7      6931361.44      2719709.47      6931285.05
      2719574.05      6931281.58      2719428.22      6931173.94
       2718966.4      6931173.94
#Sta/Elev= 30
  2983.6  470.79  3148.4  465.27  3418.6     459  3528.7  458.15  3768.9  453.51
  3788.9  454.07  3798.9  453.24  4119.1  451.27  4139.1  449.66  4169.1  449.05
  4769.6  445.91  4799.6  445.03  4849.6  445.52  4889.6  443.31  4895.4   440.1
  4896.7   439.6  4903.9   440.1  4919.7  444.46  4987.8  444.25  4999.7  442.37
  5009.7  443.92  5015.5  440.26  5029.7  440.18  5039.7  444.75  5088.2  444.78
  5139.8  446.56    5195     447  5336.6  447.77  5695.2  459.35  5794.8   461.5
#Mann= 5 ,-1 , 0
  2983.6     .05       0  4895.4     .05       0  4903.9     .05       0
  5088.2     .12       0    5195     .05       0
Bank Sta=4895.4,4903.9
XS Rating Curve= 0 ,0
Exp/Cntr=0.3,0.1

Type RM Length L Ch R = 1 ,12280   ,463,463,463
BEGIN DESCRIPTION:
Mapping XS 8f19b879
END DESCRIPTION:
XS GIS Cut Line= 6
       2721757.7      6931238.81      2720195.23      6931199.75
      2719848.01      6931156.34      2719665.72       6931043.5
      2719565.89      6931052.18      2718959.65      6931030.53
#Sta/Elev= 30
  2784.3  471.56    2886  467.46  2898.9  468.06    2946  466.18  3016.1  465.33
  3046.1  463.73    3294   457.9  3396.2  456.26  3416.2  456.92  3436.2  455.55
  3786.3  450.99  4046.4  449.32  4146.4   447.4  4871.2  443.66  4890.7  443.47
  4906.1  444.78  4938.4  443.44  4971.5  444.25  4981.6  442.46  4991.6  442.57
  4997.4  436.26  4998.6  435.76  5005.9  436.26  5009.2   438.2  5014.2   438.2
  5021.7  444.15  5104.9  443.93  5151.8  444.45  5211.8  447.56  5618.4  460.62
#Mann= 5 ,-1 , 0
  2784.3     .05       0  4871.2     .12       0  4997.4     .07       0
  5005.9     .12       0  5104.9     .05       0
Bank Sta=4997.4,5005.9
XS Rating Curve= 0 ,0
Exp/Cntr=0.3,0.1

Type RM Length L Ch R = 1 ,11817   ,408,408,408
BEGIN DESCRIPTION:
Mapping XS 511e2d49
END DESCRIPTION:
XS GIS Cut Line= 3
      2720985.19      6930735.34      2719305.48      6930717.98
      2718654.39      6930943.69
#Sta/Elev= 30
  3303.3  455.61  3372.5  453.44  3472.5     452  3512.5  450.77  3672.5  449.87
  3782.5  448.51  4272.5  445.62  4392.5  443.73  4562.6  443.87  4622.6  443.08
  4662.6  443.52  4682.6  444.36  4792.6  442.14  4852.2  442.97  4882.6  441.92
  4902.6  442.71  4922.6  441.59  4952.6  442.27  4985.5  441.56  4988.9  435.88
  4990.1  435.38  4997.4  435.88    5003  438.17  5008.3  438.38  5014.3  441.31
  5056.3  443.92  5173.1  449.55  5376.7   456.6  5490.6  459.62  5672.2  461.23
#Mann= 5 ,-1 , 0
  3303.3     .05       0  4852.2     .12       0  4988.9     .07       0
  4997.4     .12       0  5056.3     .05       0
Bank Sta=4988.9,4997.4
XS Rating Curve= 0 ,0
Exp/Cntr=0.3,0.1

Type RM Length L Ch R = 1 ,11409   ,433,433,433
BEGIN DESCRIPTION:
Blackberry Creek 18.0
END DESCRIPTION:
XS GIS Cut Line= 3
      2720980.87      6930340.37       2719096.3      6930380.87
      2718680.73      6930769.83
#Sta/Elev= 30
    3115  455.88  3169.9  454.92  3269.9  454.76  3299.9  453.52  3375.9  452.43
    3560  451.09    3890  446.85  4070.1  446.43  4520.2  442.83  4560.2  443.65
  4590.2  442.14  4690.2  441.98  4739.8  442.75  4820.3  441.28  4880.3  442.27
  4920.3  441.48  4950.3  442.29  4997.7   441.6  5021.5  442.06  5028.4  436.29
  5031.4  434.73  5032.7  434.23    5040  434.73  5056.7  441.23    5064  441.54
  5078.2  444.06  5092.4  445.61  5130.5  447.08  5403.5  455.57  5569.2  458.83
#Mann= 5 ,-1 , 0
    3115     .05       0  4739.8     .12       0  5031.4     .07       0
    5040     .12       0  5130.5     .05       0
Bank Sta=5031.4,5040
XS Rating Curve= 0 ,0
Exp/Cntr=0.3,0.1

Type RM Length L Ch R = 1 ,10976   ,706,706,706
BEGIN DESCRIPTION:
Mapping XS 830fc7a8
END DESCRIPTION:
XS GIS Cut Line= 3
      2720774.33      6930133.27       2718977.5      6930013.48
      2718347.24      6930216.62
#Sta/Elev= 30
    3204  454.57    3503  452.49  3611.1  450.49  3653.3  450.92  3743.5  448.28
    3964  445.55  4104.3  445.28  4324.8  442.85    4415  442.86  4485.2  446.23
  4495.2  444.11  4525.3  441.57  4695.6  440.49  4859.2  440.92  4906.1  440.44
  4936.2  441.44  4969.1  437.46  4976.3   433.7  4981.8   433.6  4983.1   433.1
  4990.7   433.6  4996.3  434.54  5003.1  437.65  5027.4  438.52  5049.8  442.02
  5081.7  442.71    5164  446.99  5311.4  450.09  5510.7  456.17    5667  458.59
#Mann= 5 ,-1 , 0
    3204     .05       0  4859.2     .12       0  4981.8     .07       0
  4990.7     .12       0  5049.8     .05       0
Bank Sta=4981.8,4990.7
XS Rating Curve= 0 ,0
Exp/Cntr=0.3,0.1

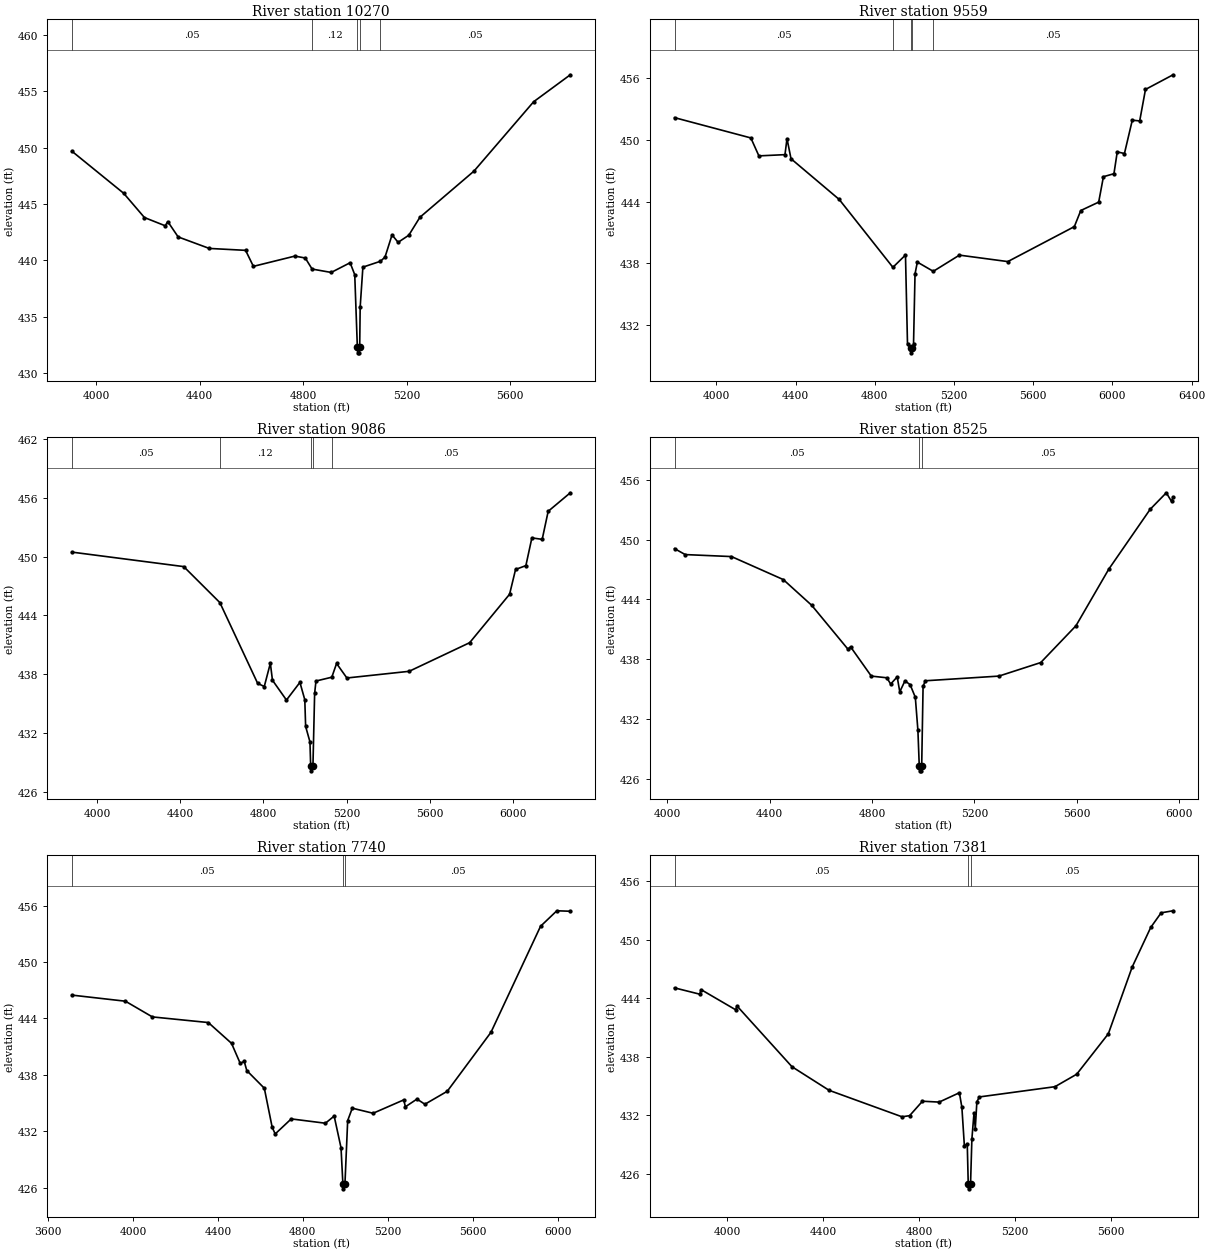
Type RM Length L Ch R = 1 ,10270   ,711,711,711
BEGIN DESCRIPTION:
Mapping XS 7eeaa8de
END DESCRIPTION:
XS GIS Cut Line= 3
      2720066.05      6929549.94      2718993.12       6929466.6
      2718180.81      6929721.75
#Sta/Elev= 30
  3905.7  449.69  4106.4  445.95  4186.6   443.8  4266.8  443.07  4276.9  443.44
    4317  442.08  4437.3  441.06  4577.8  440.89  4607.9  439.47  4768.3  440.38
  4808.5  440.21  4834.9  439.23  4908.8  438.93  4981.9  439.79  4999.8  438.73
  5009.9   432.3  5011.2   431.8  5017.6   431.8  5018.9   432.3  5020.8  435.87
  5031.3   439.4  5099.1  439.92  5116.8  440.29    5144  442.26  5167.5   441.6
  5208.8  442.23  5251.7  443.82    5461  447.92  5691.6  454.07  5833.3  456.46
#Mann= 5 ,-1 , 0
  3905.7     .05       0  4834.9     .12       0  5009.9     .07       0
  5018.9     .12       0  5099.1     .05       0
Bank Sta=5009.9,5018.9
XS Rating Curve= 0 ,0
Exp/Cntr=0.3,0.1

Type RM Length L Ch R = 1 ,9559    ,473,473,473
BEGIN DESCRIPTION:
Blackberry Creek 14.0
END DESCRIPTION:
XS GIS Cut Line= 3
      2720375.96      6929060.99        2719176.        6928861.
      2717976.01        6929361.
#Sta/Elev= 30
  3789.3  452.18  4174.5   450.2  4215.1  448.45  4346.8  448.57    4357  450.13
  4377.3  448.17  4620.6   444.2  4891.6  437.58  4955.1  438.78  4965.3  430.08
  4980.9  429.74  4982.2  429.24  4990.1  429.74  4995.7  430.06  5003.3  436.94
    5015  438.09  5095.5  437.19  5227.4  438.77  5471.6  438.14  5807.5  441.55
    5840  443.12  5930.4  443.94  5954.3  446.42  6007.4  446.71  6024.1  448.84
  6060.4  448.68    6100  451.93  6137.4  451.86  6166.6  454.93  6305.8  456.36
#Mann= 5 ,-1 , 0
  3789.3     .05       0  4891.6     .12       0  4980.9     .07       0
  4990.1     .12       0  5095.5     .05       0
Bank Sta=4980.9,4990.1
XS Rating Curve= 0 ,0
Exp/Cntr=0.3,0.1

Type RM Length L Ch R = 1 ,9086    ,561,561,561
BEGIN DESCRIPTION:
Blackberry Creek 13.0
END DESCRIPTION:
XS GIS Cut Line= 3
      2720075.99        6928661.        2718976.        6928461.
      2717975.96      6929261.03
#Sta/Elev= 30
  3877.8  450.45  4416.5  448.97  4590.3   445.3  4772.2  437.06    4804  436.74
  4833.2  439.11  4843.4  437.38  4910.7  435.36  4975.5  437.16    4999  435.39
    5003  432.67  5023.8  431.09  5027.2  428.64  5028.5  428.14  5036.4  428.64
  5038.2  428.66  5046.3  436.03  5052.7   437.3  5128.9  437.69  5151.9  439.09
  5201.5  437.61  5500.9  438.29  5792.2  441.21  5984.3  446.15  6013.1  448.68
  6062.7  449.07  6091.6   451.9  6141.2  451.75    6170  454.61  6276.5   456.5
#Mann= 5 ,-1 , 0
  3877.8     .05       0  4590.3     .12       0  5027.2     .07       0
  5036.4     .12       0  5128.9     .05       0
Bank Sta=5027.2,5036.4
XS Rating Curve= 0 ,0
Exp/Cntr=0.3,0.1

Type RM Length L Ch R = 1 ,8525    ,785,785,785
BEGIN DESCRIPTION:
Mapping XS 16f9020b
END DESCRIPTION:
XS GIS Cut Line= 3
      2719735.97      6928131.64      2718767.21      6927985.81
      2717820.11      6928183.55
#Sta/Elev= 30
  4028.7   449.1  4070.4   448.5  4251.2   448.3  4453.4  445.99  4564.6   443.4
  4706.2  438.99  4716.3  439.23  4797.2  436.29  4857.9  436.12  4872.9  435.49
  4898.4  436.21  4908.5  434.71  4928.7  435.81  4948.9  435.43  4969.2  434.16
  4979.3  430.84  4984.6  427.27    4986  426.77  4992.8  426.77  4994.1  427.27
  4999.5  435.26  5008.4  435.82  5295.7  436.29  5459.1  437.65  5596.7  441.35
  5724.7  447.03  5886.5  453.05  5949.5  454.71  5969.9  453.84  5975.9  454.28
#Mann= 3 ,-1 , 0
  4028.7     .05       0  4984.6     .04       0  4994.1     .05       0
Bank Sta=4984.6,4994.1
XS Rating Curve= 0 ,0
Exp/Cntr=0.3,0.1

Type RM Length L Ch R = 1 ,7740    ,359,359,359
BEGIN DESCRIPTION:
Mapping XS b51628cd
END DESCRIPTION:
XS GIS Cut Line= 4
      2720027.59       6927037.9      2718798.46      6927329.56
      2718152.63       6927605.6       2717809.9      6927771.77
#Sta/Elev= 30
  3712.3  446.47  3964.8  445.82  4091.5  444.15    4355  443.55  4464.2  441.34
  4505.3   439.2  4523.9  439.42  4536.1  438.44  4618.6  436.56  4655.6   432.4
  4669.8   431.7  4745.2   433.3  4906.1  432.84  4947.3   433.6  4979.6  430.23
  4988.4  426.36  4989.8  425.86    4998  426.36  5010.9  433.12  5032.6  434.44
  5130.5   433.9  5274.6  435.32  5282.7  434.59  5337.1  435.41  5374.4  434.86
  5479.7  436.24  5685.3  442.51  5918.7  453.79  5995.3  455.44  6058.8  455.39
#Mann= 3 ,-1 , 0
  3712.3     .05       0  4988.4     .05       0    4998     .05       0
Bank Sta=4988.4,4998
XS Rating Curve= 0 ,0
Exp/Cntr=0.3,0.1

Type RM Length L Ch R = 1 ,7381    ,609,609,609
BEGIN DESCRIPTION:
Mapping XS e982a9c3
END DESCRIPTION:
XS GIS Cut Line= 4
      2719902.58      6926678.53      2718798.46      6926975.39
      2718584.92      6927037.89      2717876.65      6927116.01
#Sta/Elev= 30
    3781  445.05  3886.5   444.4  3891.7  444.87    4036   442.8  4041.2   443.2
  4270.6  436.96  4425.3  434.54  4729.5  431.82  4761.2  431.94  4814.6  433.42
  4884.2  433.33  4968.6  434.29    4979  432.79  4989.4  428.83  5001.4  429.03
  5005.5  424.93  5006.8  424.43  5015.1  424.93  5020.7  429.55  5029.6  432.22
  5034.8  430.62  5041.5  433.36  5051.9  433.86  5367.1  434.91  5457.6  436.19
  5589.6  440.34    5689  447.19  5766.3  451.25  5809.7  452.75  5859.4  452.96
#Mann= 3 ,-1 , 0
    3781     .05       0  5005.5     .05       0  5015.1     .05       0
Bank Sta=5005.5,5015.1
XS Rating Curve= 0 ,0
Exp/Cntr=0.3,0.1

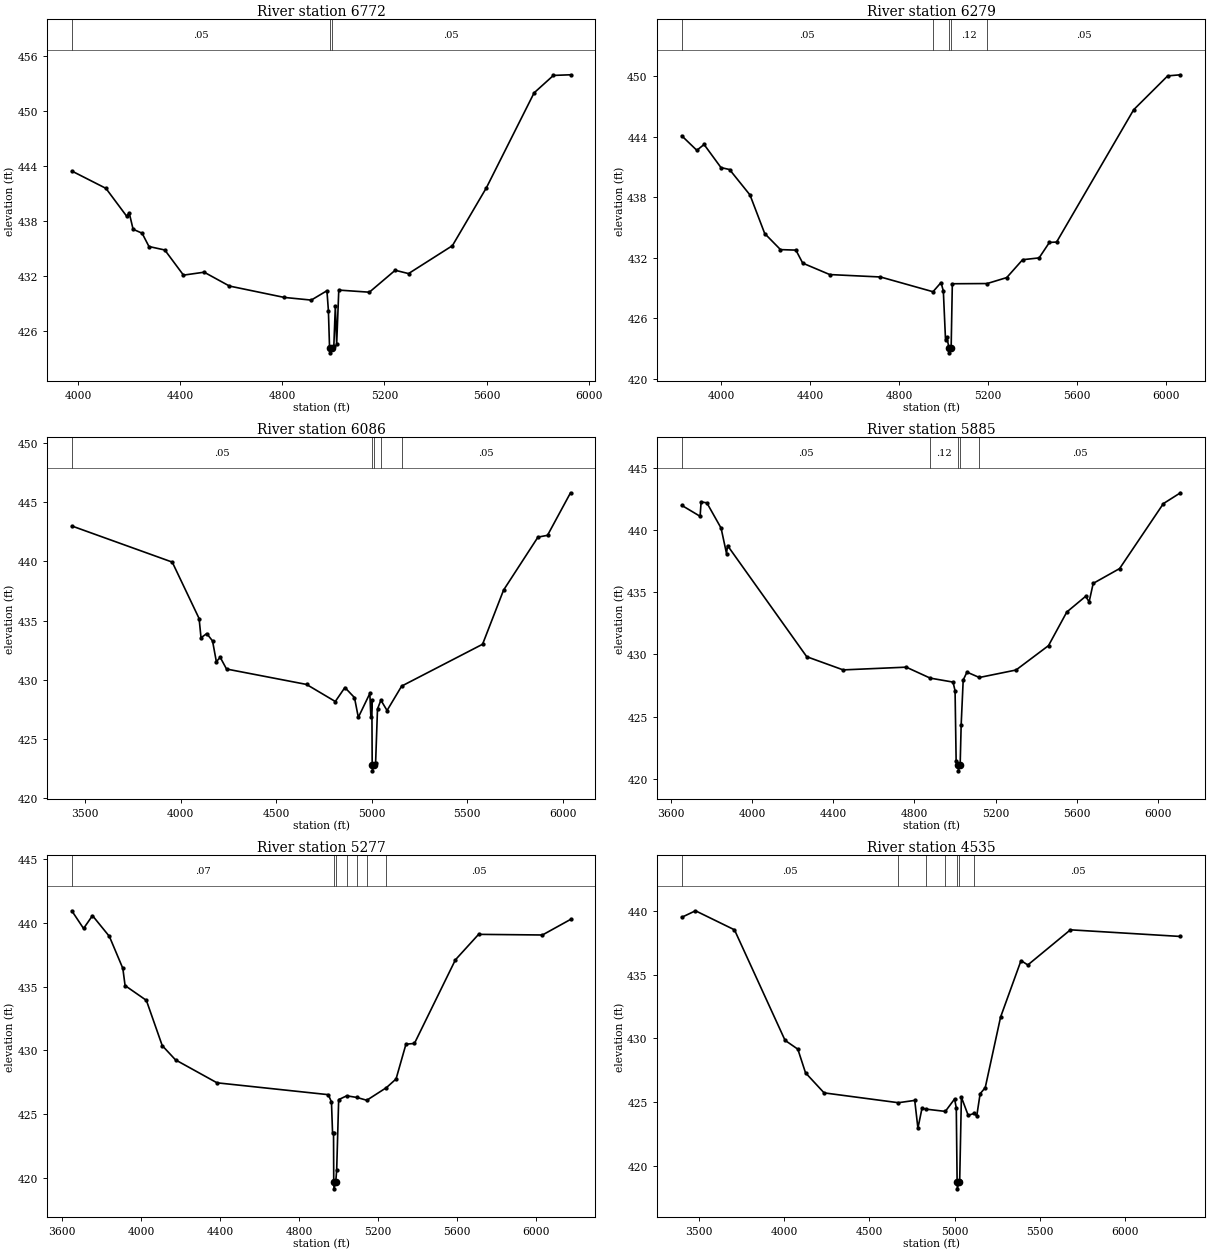
Type RM Length L Ch R = 1 ,6772    ,493,493,493
BEGIN DESCRIPTION:
Mapping XS dcdabbe2
END DESCRIPTION:
XS GIS Cut Line= 3
      2719788.06      6926563.94      2718777.63      6926402.47
      2717892.17      6926688.95
#Sta/Elev= 30
    3975  443.42  4108.7  441.53  4189.8   438.5  4199.9  438.86  4215.2  437.07
  4250.5  436.64  4277.3  435.19  4339.4  434.81  4412.5  432.07  4493.6  432.39
  4592.7  430.88  4807.5  429.64  4913.2  429.35  4974.6  430.37  4980.3  428.21
  4984.9   424.1  4986.3   423.6  4994.6   424.1  5001.7   424.4  5007.5   428.7
  5012.7  424.55    5021  430.44  5140.8  430.21    5242   432.6  5294.3  432.24
  5466.1  435.28  5599.4   441.6  5786.2  451.94  5861.8  453.84  5928.9  453.91
#Mann= 3 ,-1 , 0
    3975     .05       0  4984.9     .04       0  4994.6     .05       0
Bank Sta=4984.9,4994.6
XS Rating Curve= 0 ,0
Exp/Cntr=0.3,0.1

Type RM Length L Ch R = 1 ,6279    ,193,193,193
BEGIN DESCRIPTION:
Mapping XS 0c8cc50e
END DESCRIPTION:
XS GIS Cut Line= 3
      2719958.44      6926400.21      2718880.28      6925941.86
      2717829.63      6926149.91
#Sta/Elev= 30
  3823.4  444.09  3891.3  442.65  3923.8  443.23  3999.9  440.94  4038.3  440.75
  4130.3  438.23  4196.5  434.41  4267.4  432.82  4336.8  432.77  4367.4  431.48
  4488.9  430.35  4717.1  430.11  4953.2  428.65  4989.3  429.56  4999.7  428.72
  5009.5  423.88  5015.4  424.14    5025   423.1  5026.3   422.6  5034.8   423.1
  5040.1  429.44  5196.5  429.46  5284.7  430.05  5356.1  431.82  5430.3     432
  5476.5  433.53    5509  433.57  5855.6  446.67  6008.5  450.02    6066  450.13
#Mann= 5 ,-1 , 0
  3823.4     .05       0  4953.2     .12       0    5025     .07       0
  5034.8     .12       0  5196.5     .05       0
Bank Sta=5025,5034.8
XS Rating Curve= 0 ,0
Exp/Cntr=0.3,0.1

Type RM Length L Ch R = 1 ,6086    ,201,201,201
BEGIN DESCRIPTION:
Mapping XS a2c0d792
END DESCRIPTION:
XS GIS Cut Line= 3
      2720489.61      6925910.61      2718916.73      6925764.78
      2717885.51      6925754.36
#Sta/Elev= 30
  3429.7  442.98  3955.6  439.93  4096.2  435.17  4106.2  433.55  4136.3   433.9
  4166.5  433.28  4186.5  431.53  4206.6   431.9  4239.8  430.91  4658.6  429.61
  4809.2  428.17  4859.4  429.35  4909.6   428.5  4929.7  426.83    4990  428.85
  4995.5  426.83  5000.6   428.3  5002.3  422.82  5003.6  422.32  5012.1  422.82
  5020.1  422.95  5030.1  427.54  5047.9  428.28  5080.1  427.41  5156.6  429.47
  5580.1     433  5690.1  437.57  5870.1  442.04  5920.1  442.19  6040.6  445.78
#Mann= 5 ,-1 , 0
  3429.7     .05       0  5002.3     .05       0  5012.1     .05       0
  5047.9     .12       0  5156.6     .05       0
Bank Sta=5002.3,5012.1
XS Rating Curve= 0 ,0
Exp/Cntr=0.3,0.1

Type RM Length L Ch R = 1 ,5885    ,608,608,608
BEGIN DESCRIPTION:
Mapping XS 2d84bfdc
END DESCRIPTION:
XS GIS Cut Line= 3
      2720359.42      6925723.11      2719010.48      6925618.95
      2717906.32      6925561.65
#Sta/Elev= 30
    3653  441.98  3743.5   441.1  3748.5  442.26  3776.8  442.18    3847  440.15
  3873.7  438.11  3878.7  438.75  4269.1  429.82  4448.8  428.76  4759.7  428.98
  4877.7   428.1  4990.4  427.78  5000.4  427.08  5005.7  421.41  5015.5  421.15
  5016.9  420.65  5025.5  421.15  5030.5  424.37  5040.5  427.95  5059.1  428.58
  5120.1  428.15  5300.8  428.75    5461  430.71  5551.2  433.41    5644  434.67
  5661.3  434.23  5681.3  435.71  5811.5   436.9  6027.3  442.12  6111.6  442.99
#Mann= 5 ,-1 , 0
    3653     .05       0  4877.7     .12       0  5015.5     .07       0
  5025.5     .12       0  5120.1     .05       0
Bank Sta=5015.5,5025.5
XS Rating Curve= 0 ,0
Exp/Cntr=0.3,0.1

Type RM Length L Ch R = 1 ,5277    ,742,742,742
BEGIN DESCRIPTION:
Mapping XS 78f7e547
END DESCRIPTION:
XS GIS Cut Line= 3
      2720359.87      6925618.94      2719161.96      6925051.24
        2717964.      6925124.16
#Sta/Elev= 30
  3648.1  440.95  3707.7  439.56  3752.9  440.57  3838.4  438.94  3906.6  436.43
    3918  435.08  4025.8  433.92  4106.1  430.37  4173.4  429.25  4383.6  427.45
  4947.1  426.52  4963.2  425.95  4968.7  423.52  4973.7  423.52  4974.7  419.63
  4976.1  419.13  4984.7  419.63  4989.7  420.64  4999.7  426.13  5040.4  426.43
  5092.5   426.3    5142  426.08  5241.4  427.07  5290.3  427.75  5340.4  430.48
  5383.4  430.54  5590.8   437.1  5708.3   439.1  6031.6  439.05  6173.9  440.27
#Mann= 7 ,-1 , 0
  3648.1     .07       0  4974.7     .04       0  4984.7     .07       0
  5040.4     .12       0  5092.5      .1       0    5142     .12       0
  5241.4     .05       0
Bank Sta=4974.7,4984.7
XS Rating Curve= 0 ,0
Exp/Cntr=0.3,0.1

Type RM Length L Ch R = 1 ,4535    ,486,486,486
BEGIN DESCRIPTION:
Mapping XS 2fa217ce
END DESCRIPTION:
XS GIS Cut Line= 3
      2720721.71      6924936.79      2719252.94      6924369.08
      2717899.92      6924374.28
#Sta/Elev= 30
  3398.5  439.48  3479.1  439.99    3708   438.5    4005  429.85    4080  429.16
  4125.1  427.31  4234.1  425.74  4670.1  424.97  4766.2  425.15  4784.9  422.98
  4809.1  424.55  4830.9  424.47  4945.8  424.29  5000.1  425.26  5010.1  424.57
  5015.1  418.73  5016.5  418.23  5025.2  418.73  5030.1  418.86  5040.1   425.4
  5080.1  423.98  5116.6  424.14  5130.1  423.92  5150.1  425.67  5180.1  426.15
  5270.1  431.67  5390.1  436.09  5430.1  435.75  5680.1   438.5  6326.2  437.98
#Mann= 7 ,-1 , 0
  3398.5     .05       0  4670.1     .12       0  4830.9      .1       0
  4945.8     .07       0  5015.1     .04       0  5025.2     .07       0
  5116.6     .05       0
Bank Sta=5015.1,5025.2
XS Rating Curve= 0 ,0
Exp/Cntr=0.3,0.1

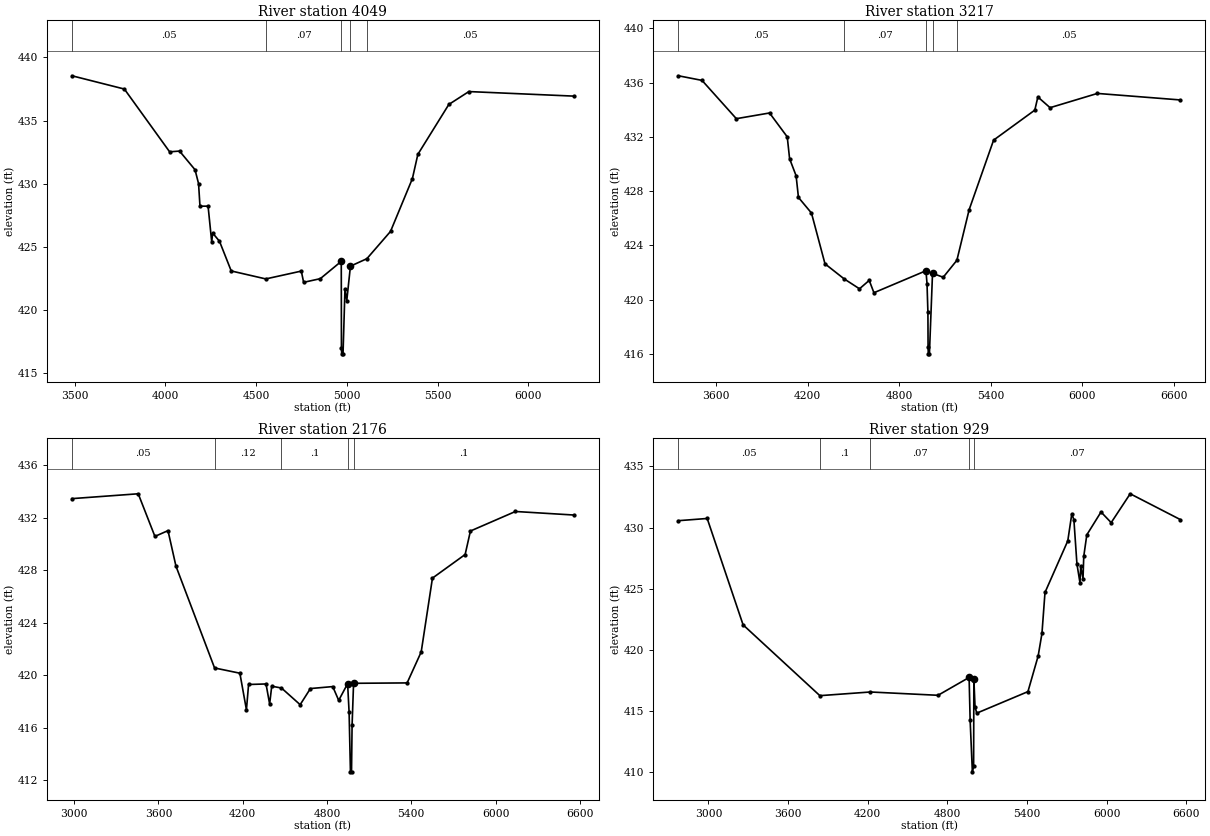
Type RM Length L Ch R = 1 ,4049    ,832,832,832
BEGIN DESCRIPTION:
Mapping XS 943a00b2
END DESCRIPTION:
XS GIS Cut Line= 3
      2720671.43       6924328.7      2719249.52      6923880.77
      2717979.87      6923995.25
#Sta/Elev= 30
  3485.3  438.55  3774.1   437.5  4023.6  432.53  4078.1  432.59  4163.6  431.11
    4183  430.01  4190.7  428.23  4235.4  428.23  4255.4   425.4  4260.7   426.1
  4298.3  425.45    4363   423.1  4553.4  422.47  4749.1  423.09  4761.9   422.2
  4853.8  422.49  4969.3  423.86  4970.2  417.04  4971.7  416.54    4979  416.54
  4989.7  421.67  4999.7  420.76  5019.8  423.48  5110.3  424.07  5240.7  426.23
  5361.2  430.41  5391.3  432.33    5562  436.28  5672.4   437.3  6250.9  436.94
#Mann= 5 ,-1 , 0
  3485.3     .05       0  4553.4     .07       0  4969.3     .04       0
  5019.8     .07       0  5110.3     .05       0
Bank Sta=4969.3,5019.8
XS Rating Curve= 0 ,0
Exp/Cntr=0.3,0.1

Type RM Length L Ch R = 1 ,3217    ,1041,1041,1041
BEGIN DESCRIPTION:
Mapping XS 03bc8d0e
END DESCRIPTION:
XS GIS Cut Line= 3
      2720629.74       6923958.9      2719228.69      6923099.52
      2717582.86      6923177.65
#Sta/Elev= 30
  3353.2   436.5    3508  436.16    3733  433.34  3950.8  433.76  4066.9     432
  4082.3  430.39  4124.9  429.14  4140.3  427.54  4225.7  426.39  4314.4  422.65
  4438.9  421.55  4540.6  420.81  4604.4  421.43  4635.3  420.52  4976.5  422.14
  4983.4   421.2  4989.3  419.08  4990.4  416.52  4991.8  416.02  4999.2  416.02
  5019.5  421.95  5089.6  421.66  5179.3  422.91  5259.8  426.64    5420  431.76
  5690.3  433.97  5710.3  434.94  5790.4  434.15  6100.7   435.2  6644.5  434.72
#Mann= 5 ,-1 , 0
  3353.2     .05       0  4438.9     .07       0  4976.5     .04       0
  5019.5     .07       0  5179.3     .05       0
Bank Sta=4976.5,5019.5
XS Rating Curve= 0 ,0
Exp/Cntr=0.3,0.1

Type RM Length L Ch R = 1 ,2176    ,1247,1247,1247
BEGIN DESCRIPTION:
Mapping XS 939507b5
END DESCRIPTION:
XS GIS Cut Line= 3
      2721228.69      6922760.98      2719322.44      6922094.31
      2717770.64      6922177.63
#Sta/Elev= 30
  2984.1  433.47    3456  433.84  3574.8  430.59  3667.9  431.03  3724.7  428.32
  3999.5  420.56  4179.7  420.16  4226.4  417.37  4241.7   419.3  4365.9  419.34
  4391.6  417.81  4406.5  419.17    4476  419.03  4608.9  417.76    4682  418.99
  4840.9  419.14  4883.3  418.09  4946.8  419.36  4957.4  417.17  4966.9  412.64
  4974.6  412.64  4978.6  416.19  4989.2  419.39  5370.5  419.42  5470.7  421.78
  5550.8  427.41  5783.6  429.21  5821.2     431  6141.6  432.49  6557.6  432.22
#Mann= 5 ,-1 , 0
  2984.1     .05       0  3999.5     .12       0    4476      .1       0
  4946.8     .04       0  4989.2      .1       0
Bank Sta=4946.8,4989.2
XS Rating Curve= 0 ,0
Exp/Cntr=0.3,0.1

Type RM Length L Ch R = 1 ,929     ,0,0,0
BEGIN DESCRIPTION:
Blackberry Creek 1.0
END DESCRIPTION:
XS GIS Cut Line= 3
      2721079.71      6922313.21        2719376.      6920880.89
       2717963.4      6921531.91
#Sta/Elev= 30
  2774.2  430.56    2991  430.74  3261.5  422.04  3839.8  416.25  4220.2  416.55
    4730  416.28  4964.2  417.74  4971.9  414.25  4988.8  410.02  4998.2  410.52
    5000  417.62  5008.9  415.31    5022  414.82  5407.4  416.58  5484.5   419.5
    5513  421.34  5535.9  424.69  5707.6  428.91  5737.7  431.11  5753.5  430.65
  5776.5  427.02  5799.5  425.48    5805  426.82  5822.4  425.83  5827.9  427.64
  5850.9   429.4  5957.9  431.27  6034.5   430.4  6177.8  432.76  6555.4  430.65
#Mann= 5 ,-1 , 0
  2774.2     .05       0  3839.8      .1       0  4220.2     .07       0
  4964.2     .04       0    5000     .07       0
Bank Sta=4964.2,5000
XS Rating Curve= 0 ,0
Exp/Cntr=0.3,0.1

Chan Stop Cuts=-1
Use User Specified Reach Order=0
Composite Channel Slope=5