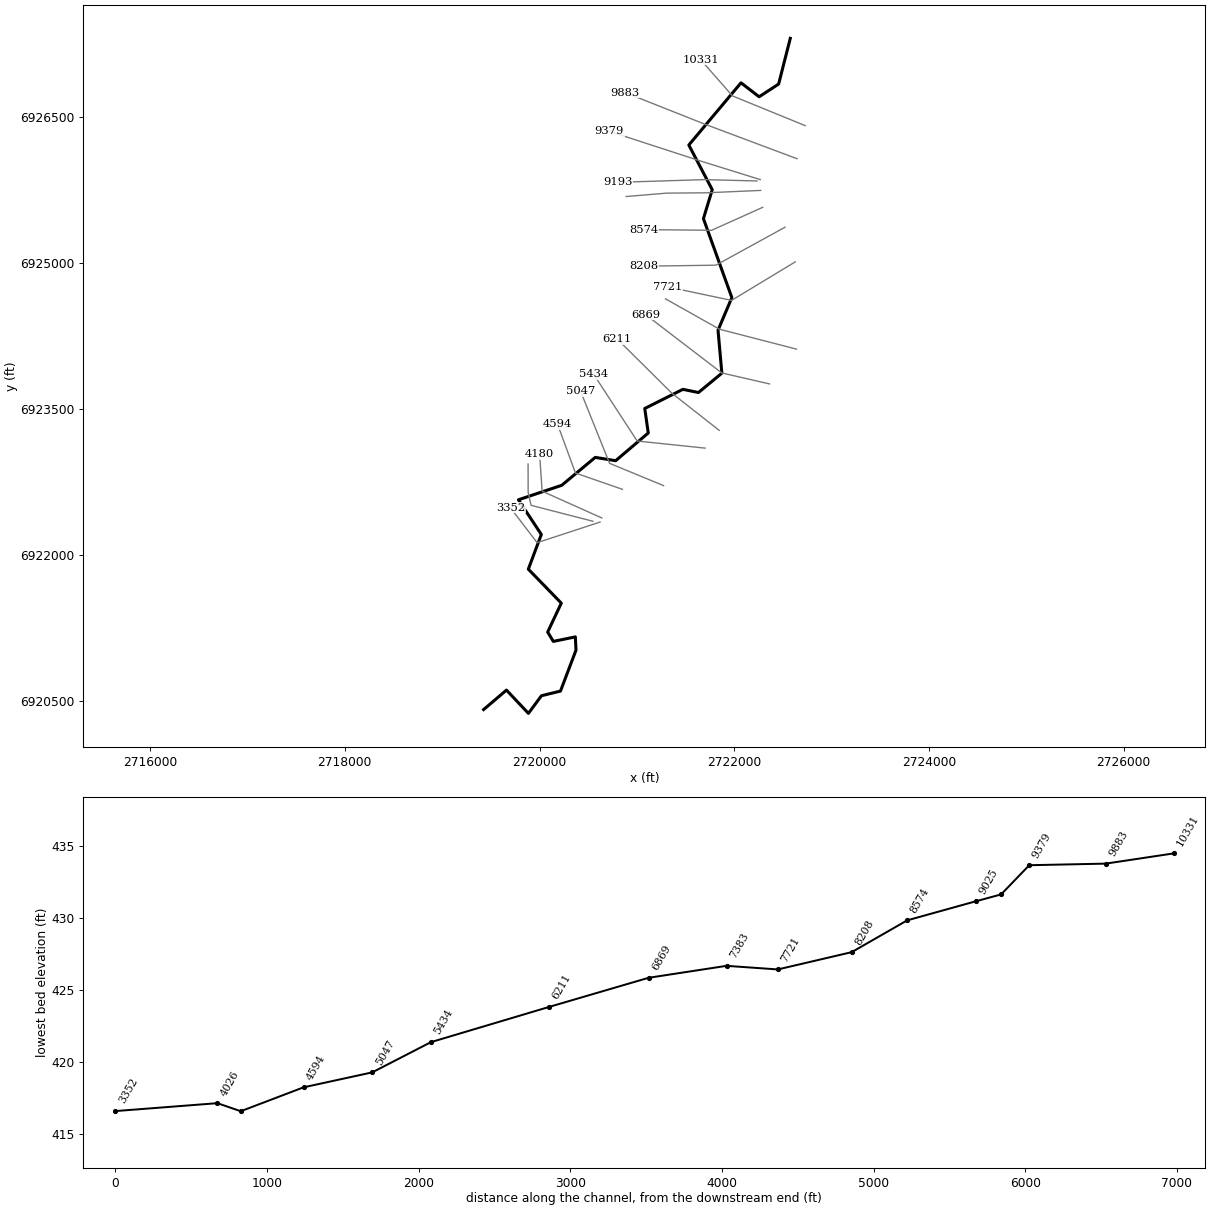
--- Blackberry T1.prj (project) ---

Proj Title=Blackberry T1 Base Level Engineering
Current Plan=p01
Default Exp/Contr=0.3,0.1
English Units
Geom File=g01
Flow File=f01
Plan File=p01
Y Axis Title=Elevation
X Axis Title(PF)=Main Channel Distance
X Axis Title(XS)=Station
BEGIN DESCRIPTION:
Blackberry T1
END DESCRIPTION:
DSS Export Rating Curves= 0
DSS Export Rating Curve Sorted= 0
DSS Export Volume Flow Curves= 0
DXF OffsetX= 0
DXF OffsetY= 0
DXF ScaleX= 1
DXF ScaleY= 10

--- Blackberry T1.p01 (plan) ---

Plan Title=Multiple Run
Short Identifier=Multiple
Geom File=g01
Flow File=f01
Subcritical Flow
K Sum by GR= 0
Std Step Tol= 0.01
Critical Tol= 0.01
Num of Std Step Trials= 20
Max Error Tol= 0.3
Flow Tol Ratio= 0.001
Split Flow NTrial= 30
Split Flow Tol= 0.02
Split Flow Ratio= 0.02
Log Output Level= 0
Friction Slope Method= 1
Unsteady Friction Slope Method= 2
Unsteady Bridges Friction Slope Method= 1
Parabolic Critical Depth
Global Vel Dist=  1 , 1 , 1
Global Log Level= 0
CheckData=True
Encroach Param= -1, 0, 0, 0
BEGIN DESCRIPTION:
Multiple Run
END DESCRIPTION:

--- Blackberry T1.f01 (steady flow) ---

Flow Title=Multiple
Number of Profiles=7
Profile Names=10-year,25-year,50-year,1pct_min,100-year,1pct_plu,500-year
River Rch & RM= Blackberry T1,Reach-1,10331
     556     733     873     516    1029    2054    1429
River Rch & RM= Blackberry T1,Reach-1,6869
     640     850    1017     603    1203    2401    1685
Boundary for River Rch & Prof#=Blackberry T1,Reach-1,1
Up Type=0
Dn Type=3
Dn Slope=0.005
Boundary for River Rch & Prof#=Blackberry T1,Reach-1,2
Up Type=0
Dn Type=3
Dn Slope=0.005
Boundary for River Rch & Prof#=Blackberry T1,Reach-1,3
Up Type=0
Dn Type=3
Dn Slope=0.005
Boundary for River Rch & Prof#=Blackberry T1,Reach-1,4
Up Type=0
Dn Type=3
Dn Slope=0.005
Boundary for River Rch & Prof#=Blackberry T1,Reach-1,5
Up Type=0
Dn Type=3
Dn Slope=0.005
Boundary for River Rch & Prof#=Blackberry T1,Reach-1,6
Up Type=0
Dn Type=3
Dn Slope=0.005
Boundary for River Rch & Prof#=Blackberry T1,Reach-1,7
Up Type=0
Dn Type=3
Dn Slope=0.005

--- Blackberry T1.g01 (geometry) ---

Geom Title=Existing Conditions
Program Version=4.10

River Reach=Blackberry T1   ,Reach-1
Reach XY= 30
        2722576.        6927311.      2722456.22      6926840.91
      2722255.86      6926710.29      2722069.69      6926853.66
       2721533.6      6926214.33      2721774.37      6925754.96
      2721683.81      6925457.59      2721975.75      6924645.78
      2721833.76      6924310.92      2721873.07      6923868.97
      2721632.95      6923670.17      2721472.77      6923702.77
       2721081.1      6923505.89      2721116.99      6923253.98
      2720782.05      6922969.12      2720572.67      6923003.39
      2720228.45      6922716.47      2719783.32      6922567.38
      2720018.67       6922211.1      2719885.13      6921854.28
      2720223.95      6921505.14      2720083.82      6921207.73
      2720141.86      6921111.52      2720368.06      6921158.18
       2720374.8      6921021.52      2720215.38      6920600.95
      2720019.79      6920553.19      2719886.31      6920371.82
      2719660.64      6920611.11        2719426.        6920411.

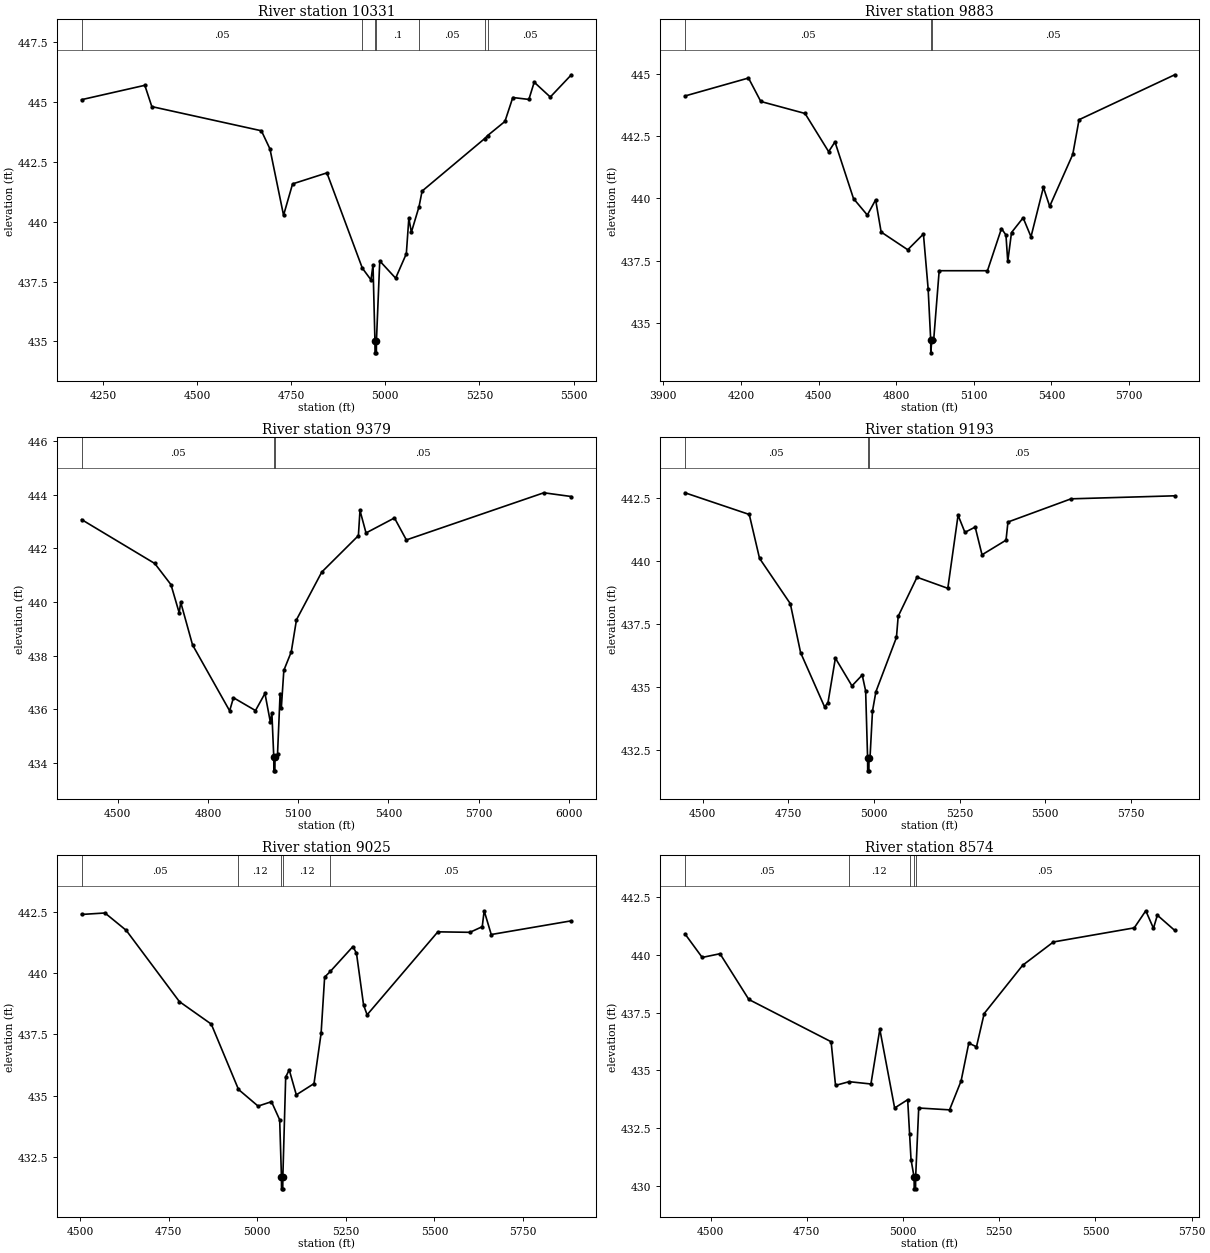
Type RM Length L Ch R = 1 ,10331   ,448,448,448
BEGIN DESCRIPTION:
Blackberry T1 10.0
END DESCRIPTION:
XS GIS Cut Line= 3
      2722729.23      6926413.51      2721982.31      6926719.05
      2721656.17      6927090.49
#Sta/Elev= 30
    4193   445.1    4361   445.7  4379.6  444.81  4670.7   443.8  4693.5  443.04
  4729.6  440.27  4753.6  441.58  4844.8  442.04  4938.9  438.06  4961.9  437.57
  4967.3   438.2  4972.4  435.02  4972.7  434.52  4976.2  434.52  4976.4  435.02
  4985.2  438.36  5027.4  437.64  5055.8  438.66  5062.5  440.15  5069.2  439.56
  5089.6  440.63  5097.7  441.28  5263.7  443.47  5271.8   443.6  5317.8  444.19
  5338.7  445.19  5381.4  445.11  5395.6  445.83  5438.3  445.21  5494.3  446.14
#Mann= 7 ,-1 , 0
    4193     .05       0  4938.9      .1       0  4972.4     .07       0
  4976.4      .1       0  5089.6     .05       0  5263.7     .12       0
  5271.8     .05       0
Bank Sta=4972.4,4976.4
XS Rating Curve= 0 ,0
Exp/Cntr=0.3,0.1

Type RM Length L Ch R = 1 ,9883    ,504,504,504
BEGIN DESCRIPTION:
Mapping XS 906d4540
END DESCRIPTION:
XS GIS Cut Line= 3
      2722645.88      6926073.24      2721701.48      6926427.39
      2720879.77       6926753.3
#Sta/Elev= 30
  3983.9   444.1  4229.4  444.82    4277  443.88  4447.9   443.4  4539.1  441.87
  4563.6  442.26  4635.2  439.99  4688.6  439.33  4720.7  439.94    4742  438.65
  4844.8  437.94  4905.4  438.57  4923.6  436.38  4933.6  434.31  4933.9  433.81
  4937.6  434.31    4945  434.32  4966.3   437.1  5152.9   437.1    5207  438.79
  5224.3  438.53  5231.3  437.47  5245.8  438.63  5290.7  439.22  5321.1  438.46
    5369  440.44  5393.3  439.68  5482.5  441.76  5506.8  443.15  5876.5  444.95
#Mann= 3 ,-1 , 0
  3983.9     .05       0  4933.6     .05       0  4937.6     .05       0
Bank Sta=4933.6,4937.6
XS Rating Curve= 0 ,0
Exp/Cntr=0.3,0.1

Type RM Length L Ch R = 1 ,9379    ,186,186,186
BEGIN DESCRIPTION:
Mapping XS dbf93542
END DESCRIPTION:
XS GIS Cut Line= 3
      2722268.46      6925858.65      2721633.08      6926056.56
      2720716.39      6926355.17
#Sta/Elev= 30
  4379.3  443.08  4622.8  441.44  4676.7  440.65    4704   439.6  4709.2  439.99
  4748.5   438.4  4871.9  435.94  4884.6  436.43  4957.9  435.95  4989.4  436.59
  5007.2  435.53  5012.4  435.87  5018.8   434.2    5019   433.7  5022.5   433.7
  5022.8   434.2  5031.3  434.34  5039.7  436.56  5043.9  436.05  5052.2  437.45
  5076.9  438.14  5094.3  439.34  5178.4  441.12  5300.3  442.48  5305.6  443.42
  5325.7  442.58  5420.3  443.14  5459.9  442.32  5917.3  444.08  6008.9  443.94
#Mann= 3 ,-1 , 0
  4379.3     .05       0  5018.8     .03       0  5022.8     .05       0
Bank Sta=5018.8,5022.8
XS Rating Curve= 0 ,0
Exp/Cntr=0.3,0.1

Type RM Length L Ch R = 1 ,9193    ,168,168,168
BEGIN DESCRIPTION:
Mapping XS 0ce0f8c5
END DESCRIPTION:
XS GIS Cut Line= 3
      2722233.81      6925844.75      2721695.58      6925858.64
      2720803.22      6925830.86
#Sta/Elev= 30
  4447.7   442.7  4635.6  441.84  4665.6   440.1  4755.6   438.3  4785.6  436.36
  4855.6  434.21  4865.6  434.37  4887.3  436.14  4935.7  435.04  4965.7  435.47
  4975.7  434.84  4981.4  432.17  4981.7  431.67  4985.2  431.67  4985.4  432.17
  4988.4  432.17  4995.7  434.04  5005.7  434.81  5065.7  436.96  5070.8   437.8
  5125.8  439.35  5215.8  438.91  5245.8  441.81  5265.8  441.13  5295.8  441.34
  5315.8  440.24  5385.9  440.82  5391.6  441.54    5576  442.46  5878.9  442.58
#Mann= 3 ,-1 , 0
  4447.7     .05       0  4981.4     .05       0  4985.4     .05       0
Bank Sta=4981.4,4985.4
XS Rating Curve= 0 ,0
Exp/Cntr=0.3,0.1

Type RM Length L Ch R = 1 ,9025    ,451,451,451
BEGIN DESCRIPTION:
Mapping XS 2495dba5
END DESCRIPTION:
XS GIS Cut Line= 4
      2722271.93      6925747.53      2721712.94      6925723.22
      2721306.69      6925719.75      2720890.52      6925685.07
#Sta/Elev= 30
  4503.5   442.4  4569.5  442.46  4629.6  441.75  4779.7  438.84  4869.8  437.92
  4946.7  435.25    5002  434.57  5039.9  434.75    5063  434.01    5068  431.69
  5068.2  431.19  5071.7  431.19    5072  431.69    5080  435.76    5090  436.05
    5110  435.03    5160  435.49    5180  437.54    5190  439.84  5205.9  440.07
    5270  441.09    5280  440.81    5300   438.7    5310   438.3  5509.8  441.69
  5600.4  441.67  5635.2   441.9  5640.6  442.55  5660.6  441.58  5886.9  442.14
#Mann= 5 ,-1 , 0
  4503.5     .05       0  4946.7     .12       0    5068     .07       0
    5072     .12       0  5205.9     .05       0
Bank Sta=5068,5072
XS Rating Curve= 0 ,0
Exp/Cntr=0.3,0.1

Type RM Length L Ch R = 1 ,8574    ,366,366,366
BEGIN DESCRIPTION:
Mapping XS b21cb519
END DESCRIPTION:
XS GIS Cut Line= 3
      2722292.83      6925573.93      2721768.49      6925337.81
      2721070.78      6925344.75
#Sta/Elev= 30
  4433.2  440.91    4478  439.89  4524.3  440.05  4599.2  438.07    4813  436.24
  4824.5  434.35  4859.9  434.51  4916.5  434.41  4939.6  436.78  4978.1  433.37
    5012  433.73    5017  432.24  5020.7  431.14  5028.7  430.37    5029  429.87
  5032.5  429.87  5032.7  430.37  5040.7  433.37  5120.8  433.29  5150.8  434.54
  5170.8  436.18  5190.8  436.02  5210.8  437.46  5310.8  439.55  5390.8  440.56
  5600.8  441.17  5630.8  441.91  5650.8  441.15  5660.8  441.72    5706  441.06
#Mann= 5 ,-1 , 0
  4433.2     .05       0  4859.9     .12       0    5017     .05       0
  5028.7     .07       0  5032.7     .05       0
Bank Sta=5028.7,5032.7
XS Rating Curve= 0 ,0
Exp/Cntr=0.3,0.1

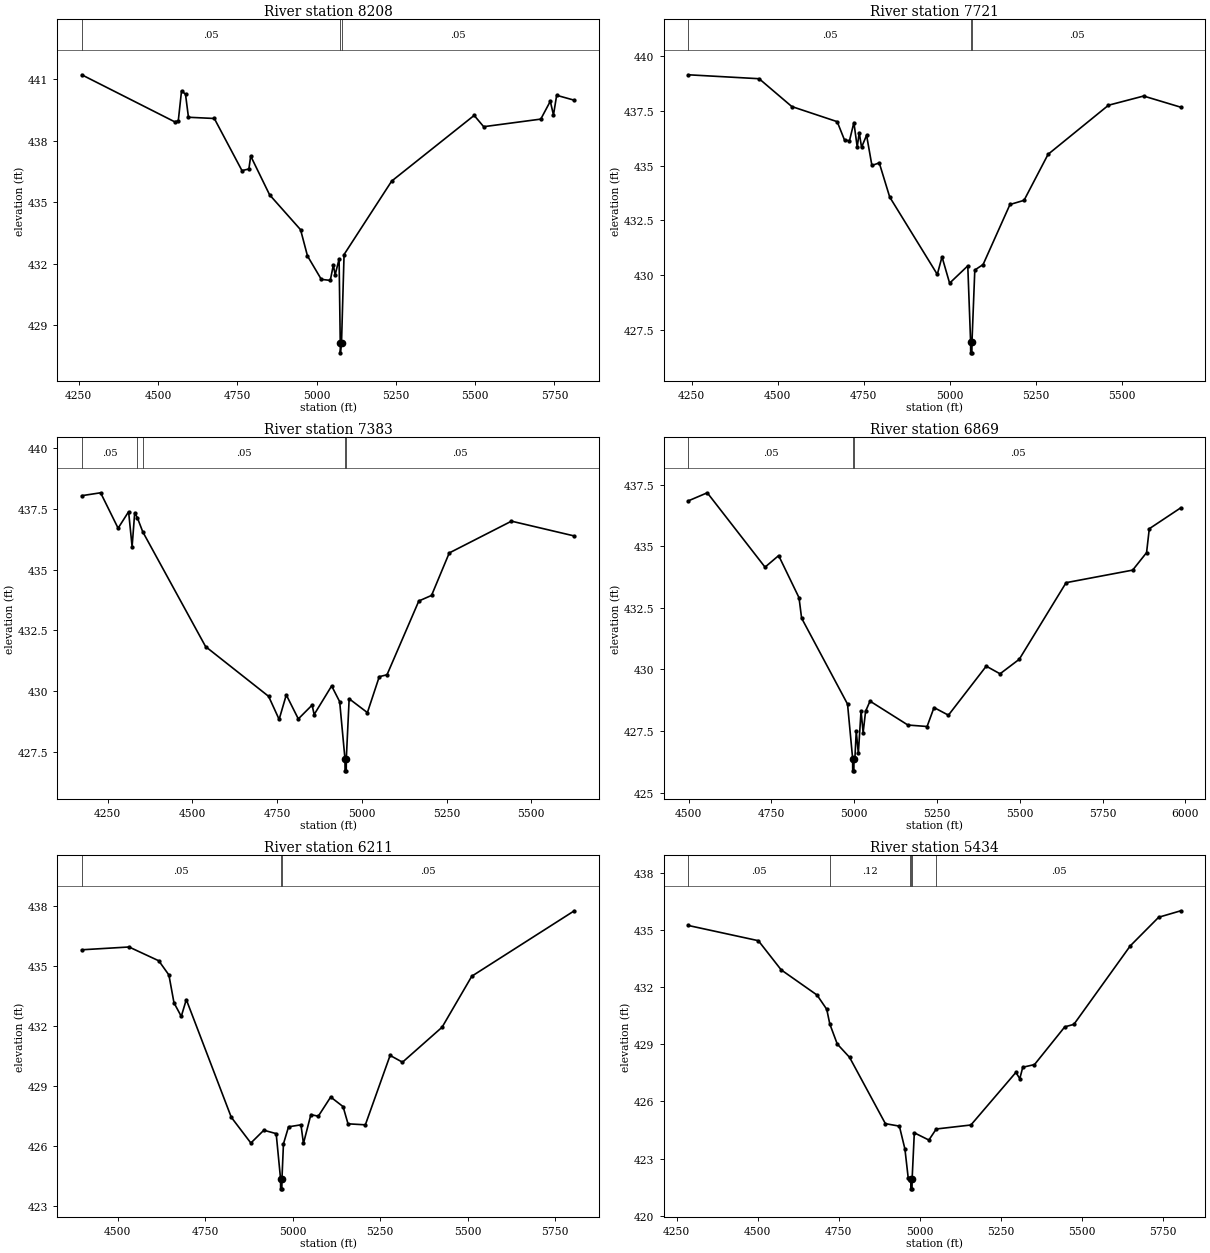
Type RM Length L Ch R = 1 ,8208    ,487,487,487
BEGIN DESCRIPTION:
Mapping XS 1a705959
END DESCRIPTION:
XS GIS Cut Line= 3
       2722522.7      6925369.75      2721811.76      6924979.12
      2721070.32      6924968.72
#Sta/Elev= 30
  4259.9  441.21  4552.7  438.92  4564.2  438.96  4574.5  440.43    4587  440.26
  4596.3  439.14  4677.8  439.08    4765  436.54  4786.8  436.62  4792.5  437.25
  4852.1  435.36  4949.7  433.66  4971.5  432.38  5015.1  431.24  5043.4  431.19
    5053  431.94  5058.7  431.46  5071.1  432.23  5074.8  428.16  5075.1  427.66
  5078.8  428.16  5086.8  432.45  5236.9  436.03  5496.9  439.23  5526.9  438.68
  5706.9  439.05  5736.9  439.92  5746.9  439.25  5756.9  440.21  5812.6  439.97
#Mann= 3 ,-1 , 0
  4259.9     .05       0  5074.8     .04       0  5078.8     .05       0
Bank Sta=5074.8,5078.8
XS Rating Curve= 0 ,0
Exp/Cntr=0.3,0.1

Type RM Length L Ch R = 1 ,7721    ,338,338,338
BEGIN DESCRIPTION:
Mapping XS 7c576da7
END DESCRIPTION:
XS GIS Cut Line= 3
      2722626.91        6925013.      2721973.22      6924617.15
      2721320.33      6924755.01
#Sta/Elev= 30
    4240  439.15  4446.1  438.97  4541.1   437.7    4673  437.01  4694.3  436.17
  4708.7  436.14  4721.5  436.97  4731.2  435.85    4737  436.51  4743.8  435.84
  4758.4  436.39  4773.9  435.01  4795.2  435.13  4825.6  433.57  4963.9  430.04
  4977.6  430.84  4999.7  429.64  5052.5  430.43  5060.7  426.96  5060.9  426.46
  5064.4  426.46  5064.7  426.96  5072.9  430.24    5097  430.49  5175.1  433.23
    5216  433.42  5285.8  435.52  5461.3  437.76  5563.5  438.18  5671.5  437.67
#Mann= 3 ,-1 , 0
    4240     .05       0  5060.7     .04       0  5064.7     .05       0
Bank Sta=5060.7,5064.7
XS Rating Curve= 0 ,0
Exp/Cntr=0.3,0.1

Type RM Length L Ch R = 1 ,7383    ,514,514,514
BEGIN DESCRIPTION:
Mapping XS 0f74e679
END DESCRIPTION:
XS GIS Cut Line= 3
      2722639.91      6924116.27      2721849.96      6924320.27
      2721294.39      6924632.78
#Sta/Elev= 30
  4173.8  438.05  4229.5  438.17  4281.1  436.71  4312.1  437.39  4322.4  435.95
  4330.1  437.35  4337.9  437.14  4353.9  436.56  4539.3  431.83  4725.2  429.78
  4756.2  428.83  4777.3  429.84  4812.8  428.85  4853.5  429.42  4859.5  429.03
  4911.1  430.21  4934.8  429.56  4950.4  427.21  4950.7  426.71  4954.2  426.71
  4954.4  427.21  4962.8  429.68  5016.6  429.11  5051.6  430.59  5074.5  430.67
  5168.3  433.71  5205.9  433.94  5258.1  435.69  5441.7     437  5627.1  436.39
#Mann= 5 ,-1 , 0
  4173.8     .05       0  4337.9     .12       0  4353.9     .05       0
  4950.4     .04       0  4954.4     .05       0
Bank Sta=4950.4,4954.4
XS Rating Curve= 0 ,0
Exp/Cntr=0.3,0.1

Type RM Length L Ch R = 1 ,6869    ,658,658,658
BEGIN DESCRIPTION:
Mapping XS c70ade85
END DESCRIPTION:
XS GIS Cut Line= 3
      2722362.12      6923758.64      2721871.66      6923871.49
      2721090.73       6924470.2
#Sta/Elev= 30
    4499  436.84  4556.6  437.17    4731  434.15  4772.1  434.62  4833.6  432.91
  4841.4  432.08  4980.1  428.59  4995.5  426.38  4995.7  425.88  4999.2  425.88
  4999.5  426.38  5002.3  426.38  5006.4  427.49  5012.7  426.59  5020.9  428.31
  5027.2  427.43  5034.6   428.3    5048  428.71  5162.3  427.74  5220.3  427.68
  5241.2  428.45  5284.7  428.14  5398.9  430.13  5440.6  429.82  5498.6  430.41
    5640  433.52    5841  434.03    5883  434.74  5891.2  435.71  5986.3  436.56
#Mann= 3 ,-1 , 0
    4499     .05       0  4995.5     .04       0  4999.5     .05       0
Bank Sta=4995.5,4999.5
XS Rating Curve= 0 ,0
Exp/Cntr=0.3,0.1

Type RM Length L Ch R = 1 ,6211    ,777,777,777
BEGIN DESCRIPTION:
Mapping XS 5282168f
END DESCRIPTION:
XS GIS Cut Line= 3
      2721845.62      6923281.21      2721359.51      6923663.15
      2720799.58      6924218.74
#Sta/Elev= 30
  4397.3   435.8  4532.4  435.94  4617.4  435.25  4646.3  434.54  4660.8  433.15
  4681.6  432.47    4696  433.31  4824.4  427.43  4880.4  426.14  4917.4  426.78
  4952.7  426.61  4965.2  424.35  4965.4  423.85  4968.9  423.85  4969.2  424.35
  4973.5   426.1    4988  426.95  5023.5  427.05  5030.6  426.12  5051.8  427.56
    5073  427.48  5108.4  428.44  5143.8  427.96  5157.9   427.1  5207.4  427.05
  5278.1  430.52  5313.5  430.18  5426.6  431.93  5511.5  434.48  5804.3  437.75
#Mann= 3 ,-1 , 0
  4397.3     .05       0  4965.2     .05       0  4969.2     .05       0
Bank Sta=4965.2,4969.2
XS Rating Curve= 0 ,0
Exp/Cntr=0.3,0.1

Type RM Length L Ch R = 1 ,5434    ,387,387,387
BEGIN DESCRIPTION:
Mapping XS e6b1b37b
END DESCRIPTION:
XS GIS Cut Line= 3
      2721701.43      6923098.48      2721003.46       6923171.4
      2720556.47      6923857.47
#Sta/Elev= 30
  4285.6  435.23  4502.2  434.43  4572.6   432.9  4683.2  431.58  4713.3  430.83
  4722.7  430.06  4745.7  429.01  4783.7  428.31  4894.3  424.83  4937.5   424.7
  4954.6   423.5  4964.7  421.99  4971.4  421.92  4972.8  421.91    4973  421.41
  4976.5  421.41  4976.8  421.91  4983.6  424.35  5028.6  423.97  5051.3  424.55
  5158.3  424.76  5297.2  427.52  5309.2  427.19  5318.4  427.79  5354.6  427.93
  5448.1  429.91  5476.2  430.04  5650.3  434.16  5737.9  435.66  5806.2     436
#Mann= 6 ,-1 , 0
  4285.6     .05       0  4722.7     .12       0  4971.4      .1       0
  4972.8     .07       0  4976.8      .1       0  5051.3     .05       0
Bank Sta=4972.8,4976.8
XS Rating Curve= 0 ,0
Exp/Cntr=0.3,0.1

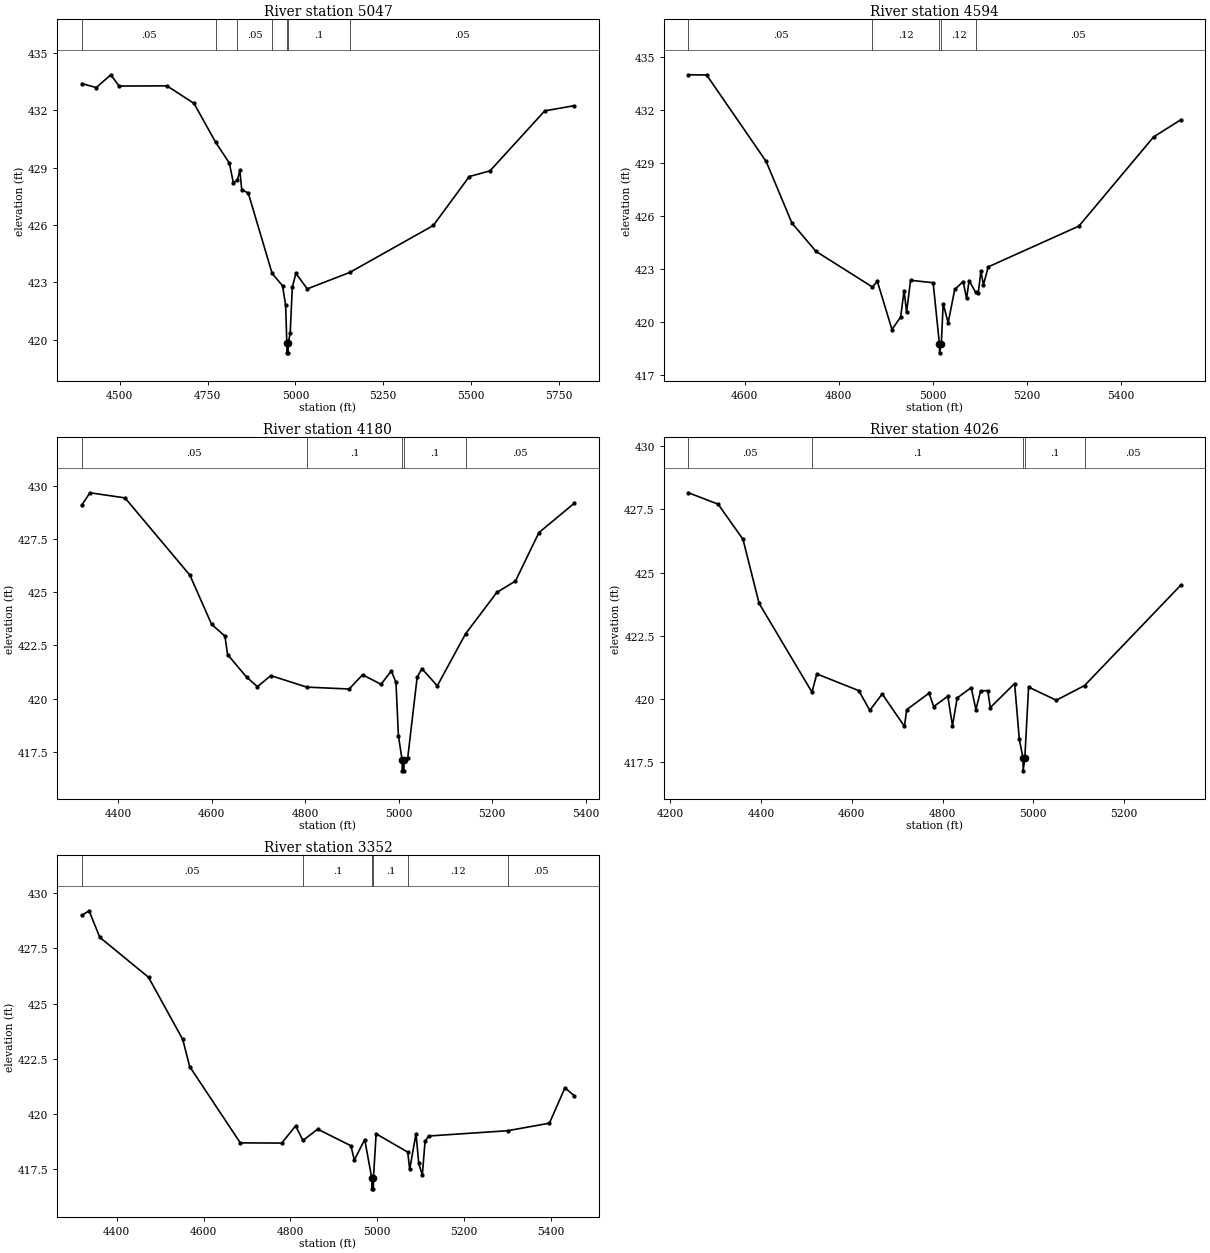
Type RM Length L Ch R = 1 ,5047    ,453,453,453
BEGIN DESCRIPTION:
Mapping XS a2ed61de
END DESCRIPTION:
XS GIS Cut Line= 3
       2721274.3      6922713.06      2720719.61      6922942.23
      2720420.77      6923685.43
#Sta/Elev= 30
  4391.8  433.41  4433.2   433.2  4474.6  433.87  4498.2  433.28  4634.3  433.29
  4711.5  432.37  4773.1  430.33  4811.9  429.25  4823.3  428.22  4834.6  428.34
  4841.8  428.86  4847.3  427.85  4865.8  427.68  4933.7  423.47  4963.4  422.82
  4972.2  421.79  4975.6  419.81  4975.9  419.31  4979.4  419.31  4979.6  419.81
  4985.1  420.34  4991.2  422.75  5001.4  423.47  5033.8  422.66  5154.6  423.52
  5392.6  425.98  5494.7  428.54  5553.8  428.84  5709.7  431.98    5793  432.25
#Mann= 7 ,-1 , 0
  4391.8     .05       0  4773.1     .12       0  4834.6     .05       0
  4933.7      .1       0  4975.6     .07       0  4979.6      .1       0
  5154.6     .05       0
Bank Sta=4975.6,4979.6
XS Rating Curve= 0 ,0
Exp/Cntr=0.3,0.1

Type RM Length L Ch R = 1 ,4594    ,414,414,414
BEGIN DESCRIPTION:
Mapping XS a4f04670
END DESCRIPTION:
XS GIS Cut Line= 3
      2720851.94      6922674.97      2720369.18      6922842.57
      2720185.12      6923345.32
#Sta/Elev= 30
  4480.8  434.02  4519.3  434.01  4645.9  429.11  4700.7  425.62  4751.7  424.02
  4871.7     422  4882.2  422.32  4913.3  419.59  4931.7   420.3  4939.1   421.8
  4944.4  420.57  4952.8  422.38  5000.8  422.24  5014.2  418.77  5014.4  418.27
  5018.2  418.77  5022.1  421.06  5032.7  419.97  5046.7  421.86  5064.7  422.31
  5071.9  421.35  5077.2  422.36  5091.3  421.69  5096.6  421.66  5102.4   422.9
  5107.7  422.12  5117.9  423.14  5310.7  425.45  5469.4   430.5  5527.2  431.47
#Mann= 5 ,-1 , 0
  4480.8     .05       0  4871.7     .12       0  5014.2     .07       0
  5018.2     .12       0  5091.3     .05       0
Bank Sta=5014.2,5018.2
XS Rating Curve= 0 ,0
Exp/Cntr=0.3,0.1

Type RM Length L Ch R = 1 ,4180    ,154,154,154
BEGIN DESCRIPTION:
Mapping XS 8c67ad94
END DESCRIPTION:
XS GIS Cut Line= 3
      2720640.44      6922380.32      2720026.86       6922655.8
        2720001.      6923036.03
#Sta/Elev= 30
  4321.7  429.08  4339.3  429.66  4414.3  429.42  4553.3  425.79  4599.6  423.49
  4628.3  422.93  4633.8  422.07  4674.6  421.01  4697.8  420.56  4726.4  421.08
  4803.2  420.54  4894.1  420.45  4922.8  421.12  4962.3  420.67  4984.3   421.3
  4994.3  420.76  4999.5  418.26  5007.5  417.11  5007.8  416.61  5011.3  416.61
  5011.5  417.11  5019.5  417.23  5039.6     421  5049.6  421.41  5082.7   420.6
  5143.2  423.04    5210  424.98  5250.1  425.52  5300.2  427.79  5375.4  429.16
#Mann= 5 ,-1 , 0
  4321.7     .05       0  4803.2      .1       0  5007.5     .05       0
  5011.5      .1       0  5143.2     .05       0
Bank Sta=5007.5,5011.5
XS Rating Curve= 0 ,0
Exp/Cntr=0.3,0.1

Type RM Length L Ch R = 1 ,4026    ,674,674,674
BEGIN DESCRIPTION:
Mapping XS 74d8f8f1
END DESCRIPTION:
XS GIS Cut Line= 4
      2720549.28      6922346.52      2719913.41      6922510.56
       2719883.5      6922643.41      2719882.46      6922935.34
#Sta/Elev= 30
  4240.2  428.16  4305.5  427.71  4360.3  426.32  4395.8  423.79  4512.3  420.28
    4523     421  4615.4  420.34  4639.8  419.56    4667  420.21    4716  418.93
  4721.2  419.59  4770.3  420.24  4780.6  419.71  4811.6  420.12  4821.9  418.95
  4832.2  420.05  4863.2  420.46  4873.5  419.59  4883.9  420.33  4899.7  420.34
  4905.2  419.67  4958.8  420.62  4969.1  418.43  4977.3  417.67  4977.6  417.17
  4981.3  417.67  4989.6  420.48  5050.7  419.96  5112.9  420.54    5325  424.51
#Mann= 5 ,-1 , 0
  4240.2     .05       0  4512.3      .1       0  4977.3     .05       0
  4981.3      .1       0  5112.9     .05       0
Bank Sta=4977.3,4981.3
XS Rating Curve= 0 ,0
Exp/Cntr=0.3,0.1

Type RM Length L Ch R = 1 ,3352    ,0,0,0
BEGIN DESCRIPTION:
Blackberry T1 1.0
END DESCRIPTION:
XS GIS Cut Line= 3
       2720622.1      6922338.49      2719975.67      6922126.19
      2719700.98      6922486.02
#Sta/Elev= 30
  4319.6  428.99  4336.5   429.2  4361.2     428  4473.4  426.19  4552.1  423.38
  4568.1  422.15  4684.6   418.7  4780.1  418.69  4811.9  419.47  4828.8  418.81
  4862.8  419.32  4939.1  418.57    4947  417.92  4970.9  418.85  4987.1  417.12
  4987.4  416.62  4990.9  416.62  4991.1  417.12  4997.2  419.11    5070  418.28
  5074.4   417.5    5089  419.11  5095.3  417.78  5103.5  417.23  5109.8  418.77
    5118  419.01    5300  419.25  5396.1  419.59  5431.8  421.19  5452.7  420.84
#Mann= 6 ,-1 , 0
  4319.6     .05       0  4828.8      .1       0  4987.1     .05       0
  4991.1      .1       0    5070     .12       0    5300     .05       0
Bank Sta=4987.1,4991.1
XS Rating Curve= 0 ,0
Exp/Cntr=0.3,0.1

Chan Stop Cuts=-1
Use User Specified Reach Order=0
Composite Channel Slope=5