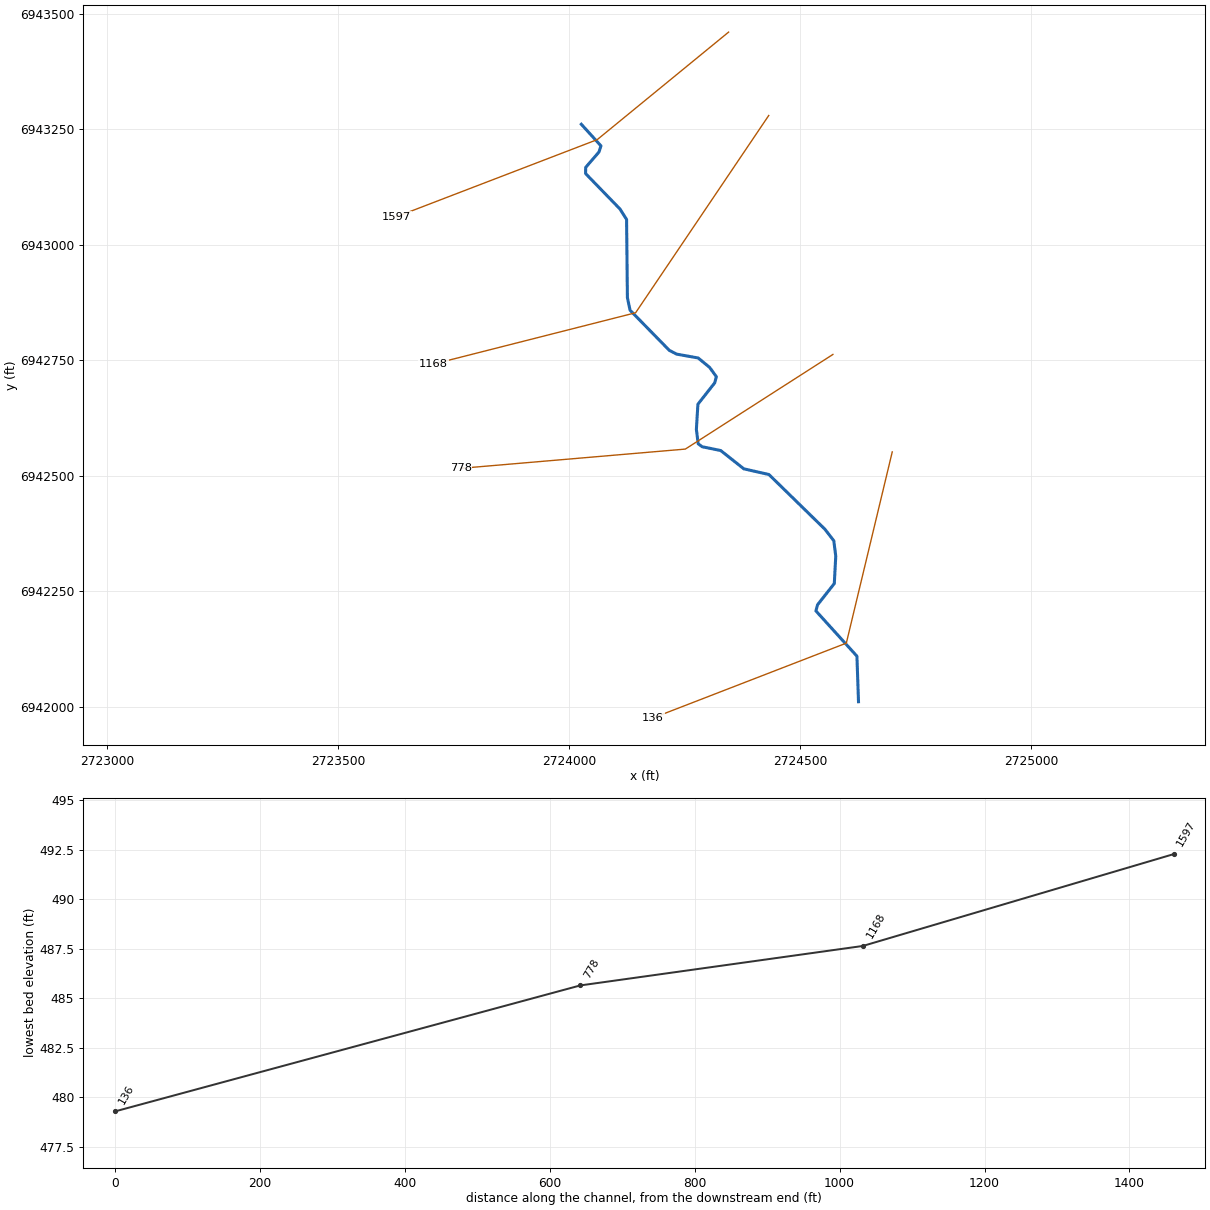
--- Blackberry T2.prj (project) ---

Proj Title=Blackberry T2 Base Level Engineering
Current Plan=p01
Default Exp/Contr=0.3,0.1
English Units
Geom File=g01
Flow File=f01
Plan File=p01
BEGIN DESCRIPTION:
Blackberry T2
END DESCRIPTION:

--- Blackberry T2.p01 (plan) ---

Plan Title=Multiple Run
Short Identifier=Multiple
Geom File=g01
Flow File=f01
Subcritical Flow
K Sum by GR= 0
Std Step Tol= 0.01
Critical Tol= 0.01
Num of Std Step Trials= 20
Max Error Tol= 0.3
Flow Tol Ratio= 0.001
Split Flow NTrial= 30
Split Flow Tol= 0.02
Split Flow Ratio= 0.02
Log Output Level= 0
Friction Slope Method= 1
Unsteady Friction Slope Method= 2
Unsteady Bridges Friction Slope Method= 1
Parabolic Critical Depth
Global Vel Dist=  1 , 1 , 1
Global Log Level= 0
CheckData=True
Encroach Param= -1, 0, 0, 0
BEGIN DESCRIPTION:
Multiple Run
END DESCRIPTION:

--- Blackberry T2.f01 (steady flow) ---

Flow Title=Multiple
Number of Profiles=7
Profile Names=10-year,25-year,50-year,1pct_min,100-year,1pct_plu,500-year
River Rch & RM= Blackberry T2,Reach-1,1597
     140     168     189     106     211     421     262
Boundary for River Rch & Prof#=Blackberry T2,Reach-1,1
Up Type=0
Dn Type=3
Dn Slope=0.005
Boundary for River Rch & Prof#=Blackberry T2,Reach-1,2
Up Type=0
Dn Type=3
Dn Slope=0.005
Boundary for River Rch & Prof#=Blackberry T2,Reach-1,3
Up Type=0
Dn Type=3
Dn Slope=0.005
Boundary for River Rch & Prof#=Blackberry T2,Reach-1,4
Up Type=0
Dn Type=3
Dn Slope=0.005
Boundary for River Rch & Prof#=Blackberry T2,Reach-1,5
Up Type=0
Dn Type=3
Dn Slope=0.005
Boundary for River Rch & Prof#=Blackberry T2,Reach-1,6
Up Type=0
Dn Type=3
Dn Slope=0.005
Boundary for River Rch & Prof#=Blackberry T2,Reach-1,7
Up Type=0
Dn Type=3
Dn Slope=0.005

--- Blackberry T2.g01 (geometry) ---

Geom Title=Existing Conditions

River Reach=Blackberry T2,Reach-1
Reach XY= 30
      2724026.00      6943261.00      2724068.48      6943214.33
      2724064.15      6943201.00      2724035.36      6943167.67
      2724035.21      6943154.34      2724109.50      6943077.77
      2724123.92      6943055.15      2724125.71      6942885.88
      2724131.45      6942858.53      2724216.33      6942771.77
      2724232.12      6942763.53      2724278.85      6942755.15
      2724303.70      6942734.73      2724318.30      6942714.66
      2724314.72      6942701.28      2724278.34      6942655.03
      2724275.04      6942600.55      2724278.97      6942569.32
      2724287.62      6942562.96      2724327.78      6942554.74
      2724377.70      6942515.18      2724432.05      6942502.86
      2724553.16      6942384.52      2724572.54      6942359.50
      2724576.76      6942326.08      2724573.63      6942266.89
      2724537.34      6942220.85      2724533.81      6942207.59
      2724622.59      6942109.60      2724626.00      6942011.00

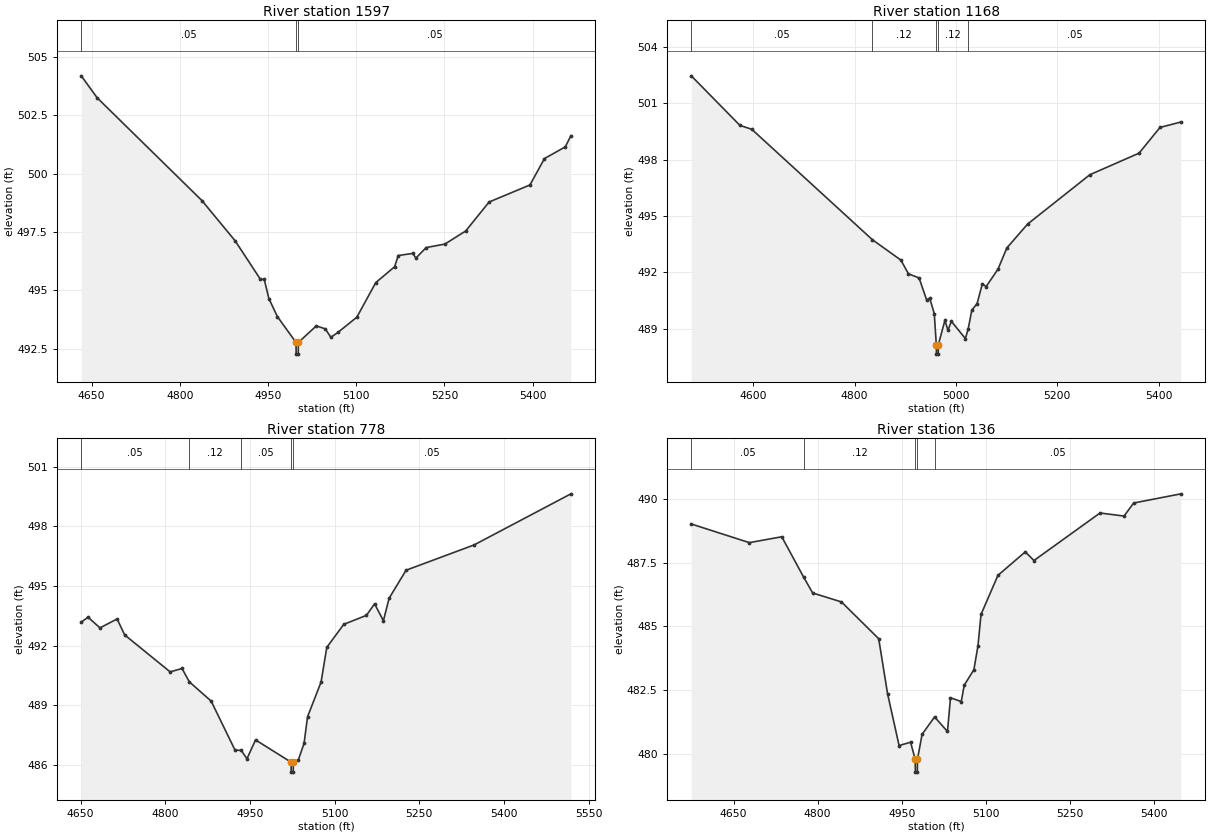
Type RM Length L Ch R = 1,1597,429,429,429
BEGIN DESCRIPTION:
Blackberry T2 2.0
END DESCRIPTION:
XS GIS Cut Line= 3
      2724344.86      6943460.65      2724060.31      6943227.78
      2723626.03      6943061.01
#Sta/Elev= 30
  4632.3  504.18  4659.3  503.24  4837.6  498.84  4894.0  497.12  4937.1  495.47
  4943.5  495.47  4951.4  494.65  4965.8  493.88  4997.6  492.77  4997.8  492.27
  5001.3  492.27  5001.6  492.77  5032.1  493.48  5047.5  493.35  5056.8  492.99
  5068.9  493.20  5101.0  493.85  5133.2  495.33  5165.3  496.01  5171.5  496.49
  5196.1  496.58  5201.5  496.38  5218.9  496.83  5250.8  496.98  5286.2  497.54
  5326.0  498.78  5395.5  499.51  5420.2  500.64  5455.6  501.14  5465.2  501.62
#Mann=3,-1,0
  4632.3    0.05       0  4997.6    0.04       0  5001.6    0.05       0
Bank Sta=4997.6,5001.6
Exp/Cntr=0.3,0.1

Type RM Length L Ch R = 1,1168,390,390,390
BEGIN DESCRIPTION:
Mapping XS da0a1770
END DESCRIPTION:
XS GIS Cut Line= 3
      2724431.68      6943280.09      2724143.51      6942853.05
      2723705.98      6942741.93
#Sta/Elev= 30
  4477.5  502.47  4573.5  499.83  4597.0  499.62  4834.9  493.74  4891.3  492.65
  4906.2  491.92  4927.2  491.70  4942.2  490.52  4948.2  490.62  4957.2  489.80
  4961.2  488.14  4961.5  487.64  4965.0  487.64  4965.2  488.14  4978.2  489.44
  4984.2  488.91  4990.9  489.39  5018.6  488.47  5024.1  488.98  5031.4  489.99
  5041.7  490.33  5052.0  491.38  5059.6  491.24  5083.0  492.17  5100.5  493.30
  5141.4  494.57  5264.3  497.20  5361.5  498.35  5402.8  499.72  5444.1  500.01
#Mann=5,-1,0
  4477.5    0.05       0  4834.9    0.12       0  4961.2    0.07       0
  4965.2    0.12       0  5024.1    0.05       0
Bank Sta=4961.2,4965.2
Exp/Cntr=0.3,0.1

Type RM Length L Ch R = 1,778,642,642,642
BEGIN DESCRIPTION:
Mapping XS 553bb709
END DESCRIPTION:
XS GIS Cut Line= 3
      2724570.62      6942762.79      2724251.15      6942557.91
      2723765.05      6942516.24
#Sta/Elev= 30
  4651.3  493.19  4663.3  493.44  4684.4  492.90  4714.8  493.35  4728.1  492.55
  4808.7  490.69  4829.8  490.86  4842.7  490.19  4881.4  489.22  4923.6  486.76
  4934.7  486.74  4944.8  486.32  4960.0  487.27  5023.0  486.15  5023.2  485.65
  5026.7  485.65  5027.0  486.15  5036.0  486.28  5046.0  487.10  5052.1  488.43
  5076.1  490.18  5086.2  491.92  5116.3  493.08  5156.4  493.53  5170.9  494.11
  5186.5  493.26  5196.6  494.39  5226.7  495.80  5347.1  497.07  5518.7  499.64
#Mann=5,-1,0
  4651.3    0.05       0  4842.7    0.12       0  4934.7    0.05       0
  5023.0    0.04       0  5027.0    0.05       0
Bank Sta=5023,5027
Exp/Cntr=0.3,0.1

Type RM Length L Ch R = 1,136,0,0,0
BEGIN DESCRIPTION:
Blackberry T2 1.0
END DESCRIPTION:
XS GIS Cut Line= 3
      2724699.06      6942551.80      2724599.67      6942137.86
      2724181.21      6941975.92
#Sta/Elev= 30
  4574.3  489.01  4678.0  488.28  4735.9  488.51  4775.2  486.92  4791.1  486.31
  4842.5  485.96  4909.0  484.52  4924.8  482.37  4945.4  480.34  4965.9  480.47
  4974.2  479.80  4974.5  479.30  4978.0  479.30  4978.2  479.80  4986.5  480.78
  5008.8  481.46  5031.8  480.89  5037.2  482.21  5056.4  482.06  5061.7  482.70
  5079.0  483.31  5086.3  484.25  5091.7  485.47  5121.9  487.00  5170.8  487.92
  5186.2  487.58  5304.2  489.44  5347.1  489.32  5364.3  489.83  5448.7  490.19
#Mann=5,-1,0
  4574.3    0.05       0  4775.2    0.12       0  4974.2    0.07       0
  4978.2    0.12       0  5008.8    0.05       0
Bank Sta=4974.2,4978.2
Exp/Cntr=0.3,0.1

Chan Stop Cuts=-1