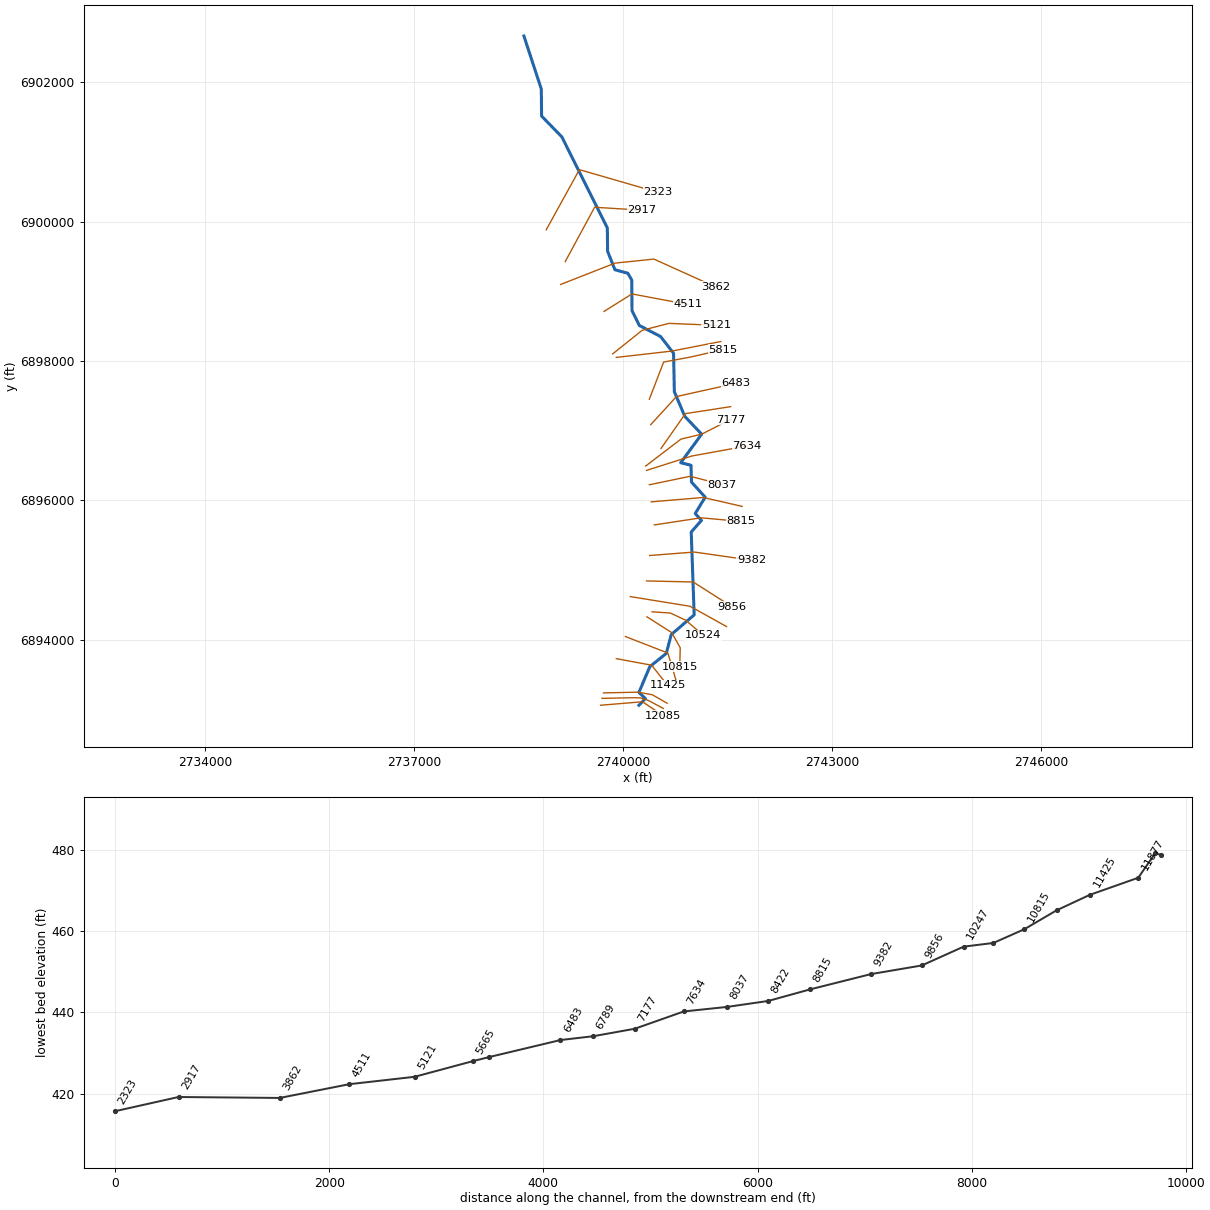
--- Britton Creek.prj (project) ---

Proj Title=Britton Creek Base Level Engineering
Current Plan=p01
Default Exp/Contr=0.3,0.1
English Units
Geom File=g01
Flow File=f01
Plan File=p01
Y Axis Title=Elevation
X Axis Title(PF)=Main Channel Distance
X Axis Title(XS)=Station
BEGIN DESCRIPTION:
Britton Creek
END DESCRIPTION:
DSS Export Rating Curves= 0
DSS Export Rating Curve Sorted= 0
DSS Export Volume Flow Curves= 0
DXF OffsetX= 0
DXF OffsetY= 0
DXF ScaleX= 1
DXF ScaleY= 10

--- Britton Creek.p01 (plan) ---

Plan Title=Multiple Run
Short Identifier=Multiple
Geom File=g01
Flow File=f01
Subcritical Flow
K Sum by GR= 0
Std Step Tol= 0.01
Critical Tol= 0.01
Num of Std Step Trials= 20
Max Error Tol= 0.3
Flow Tol Ratio= 0.001
Split Flow NTrial= 30
Split Flow Tol= 0.02
Split Flow Ratio= 0.02
Log Output Level= 0
Friction Slope Method= 1
Unsteady Friction Slope Method= 2
Unsteady Bridges Friction Slope Method= 1
Parabolic Critical Depth
Global Vel Dist=  1 , 1 , 1
Global Log Level= 0
CheckData=True
Encroach Param= -1, 0, 0, 0
BEGIN DESCRIPTION:
Multiple Run
END DESCRIPTION:

--- Britton Creek.f01 (steady flow) ---

Flow Title=Multiple
Program Version=4.10
Number of Profiles= 7
Profile Names=10-year,25-year,50-year,1pct_min,100-year,1pct_plu,500-year
River Rch & RM=Britton Creek,Reach-1         ,12085
     398     524     625     371     741    1478    1042
River Rch & RM=Britton Creek,Reach-1         ,7634
     593     798     966     581    1159    2313    1674
River Rch & RM=Britton Creek,Reach-1         ,5665
     891    1223    1498     912    1819    3629    2686
Boundary for River Rch & Prof#=Britton Creek,Reach-1         , 1
Up Type= 0
Dn Type= 3
Dn Slope=0.005
Boundary for River Rch & Prof#=Britton Creek,Reach-1         , 2
Up Type= 0
Dn Type= 3
Dn Slope=0.005
Boundary for River Rch & Prof#=Britton Creek,Reach-1         , 3
Up Type= 0
Dn Type= 3
Dn Slope=0.005
Boundary for River Rch & Prof#=Britton Creek,Reach-1         , 4
Up Type= 0
Dn Type= 3
Dn Slope=0.005
Boundary for River Rch & Prof#=Britton Creek,Reach-1         , 5
Up Type= 0
Dn Type= 3
Dn Slope=0.005
Boundary for River Rch & Prof#=Britton Creek,Reach-1         , 6
Up Type= 0
Dn Type= 3
Dn Slope=0.005
Boundary for River Rch & Prof#=Britton Creek,Reach-1         , 7
Up Type= 0
Dn Type= 3
Dn Slope=0.005
DSS Import GetInterval= 0
DSS Import GetPeak= 0
DSS Import FillOption= 0

--- Britton Creek.g01 (geometry) ---

Geom Title=Existing Conditions
Program Version=4.10

River Reach=Britton Creek   ,Reach-1
Reach XY= 30
        2740226.        6893061.      2740318.59      6893157.85
      2740225.76      6893245.29      2740381.42      6893613.67
      2740618.21      6893804.56      2740689.26      6894074.65
      2741018.28      6894357.34      2740975.95      6895545.66
      2741123.05      6895713.01      2741033.23      6895810.71
      2741176.11      6896045.64      2740979.54      6896262.46
      2740973.08      6896503.08      2740825.45      6896540.37
      2741125.41      6896949.17      2740883.83      6897204.81
      2740734.08      6897557.72      2740722.71      6898109.64
      2740535.81      6898350.49      2740231.52      6898508.56
      2740126.61      6898721.63      2740122.67      6899159.31
      2740067.72      6899257.93      2739881.35      6899308.26
      2739776.61      6899571.62      2739772.18      6899909.44
      2739120.46      6901213.42      2738829.53      6901512.45
      2738825.23      6901900.31        2738576.        6902661.

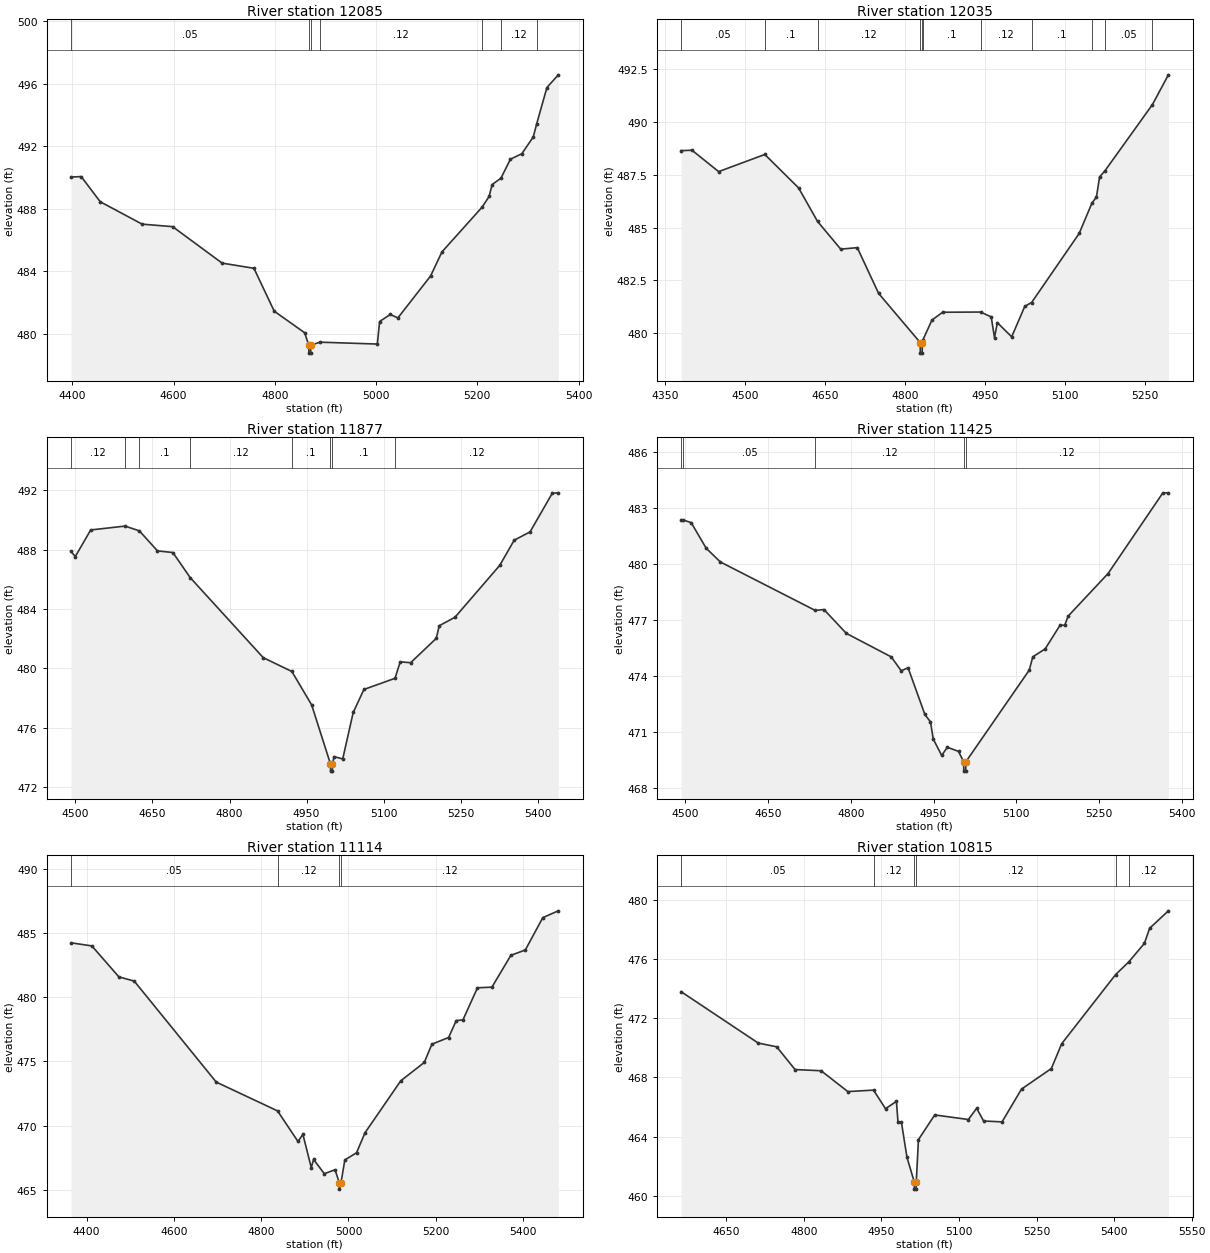
Type RM Length L Ch R = 1 ,12085   ,50,50,50
BEGIN DESCRIPTION:
Britton Creek 20.0
END DESCRIPTION:
XS GIS Cut Line= 3
      2739675.99        6893061.        2740276.        6893111.
      2740575.96      6892911.03
#Sta/Elev= 30
  4397.4  490.03  4417.5  490.06  4455.1  488.45  4537.9  487.02  4598.1  486.86
  4695.9  484.53  4758.7   484.2  4798.8  481.46    4859  480.08    4867  479.28
  4867.3  478.78  4870.8  478.78    4871  479.28  4889.1  479.48  5002.5  479.36
    5007   480.8    5028  481.25  5043.1  481.03  5107.7  483.71  5130.2  485.25
  5209.3   488.1  5223.3  488.79  5229.3  489.55  5246.7  489.96  5265.4  491.17
  5287.9  491.52  5310.5  492.59  5317.3  493.43  5337.5  495.75    5360  496.56
#Mann= 7 ,-1 , 0
  4397.4     .05       0    4867     .07       0    4871     .05       0
  4889.1     .12       0  5209.3     .05       0  5246.7     .12       0
  5317.3     .05       0
Bank Sta=4867,4871
XS Rating Curve= 0 ,0
Exp/Cntr=0.3,0.1

Type RM Length L Ch R = 1 ,12035   ,158,158,158
BEGIN DESCRIPTION:
Mapping XS 8eda542b
END DESCRIPTION:
XS GIS Cut Line= 5
       2739695.6        6893160.      2740156.52      6893169.12
      2740254.18      6893165.21      2740351.84      6893133.96
       2740575.3      6893015.73
#Sta/Elev= 30
  4380.6  488.63    4401  488.65    4451  487.64  4537.6  488.45    4601  486.87
  4636.5  485.29    4680  483.98  4711.1  484.05  4751.1  481.89  4829.1  479.57
  4829.3  479.07  4832.8  479.07  4833.1  479.57  4834.5  479.71  4851.1  480.63
  4871.1     481  4942.3  481.01  4962.3  480.78  4968.5   479.8  4973.8  480.51
  5000.7  479.84  5025.3  481.28  5038.1  481.46  5127.3  484.72  5151.2  486.15
  5159.7  486.44  5165.6  487.39  5175.4  487.67  5264.6   490.8  5294.7  492.21
#Mann= 11 ,-1 , 0
  4380.6     .05       0  4537.6      .1       0  4636.5     .12       0
  4829.1     .07       0  4833.1     .12       0  4834.5      .1       0
  4942.3     .12       0  5038.1      .1       0  5151.2     .12       0
  5175.4     .05       0  5264.6     .12       0
Bank Sta=4829.1,4833.1
XS Rating Curve= 0 ,0
Exp/Cntr=0.3,0.1

Type RM Length L Ch R = 1 ,11877   ,452,452,452
BEGIN DESCRIPTION:
Mapping XS 8880878a
END DESCRIPTION:
XS GIS Cut Line= 4
      2739717.72      6893238.13      2740213.82      6893248.54
      2740419.55      6893210.78      2740630.48      6893089.69
#Sta/Elev= 30
  4491.5  487.87  4499.8  487.53  4529.8  489.32  4596.7  489.58  4624.5  489.26
  4659.8  487.91  4689.8   487.8  4723.5  486.11  4865.7  480.72  4921.4  479.79
  4959.9  477.54  4996.4  473.58  4996.7  473.08  5000.2  473.08  5000.4  473.58
  5003.5  474.06  5020.4   473.9  5040.8  477.03  5061.7  478.58  5122.2  479.33
  5132.3  480.44  5152.6  480.38  5202.5  482.02  5208.3  482.87  5238.9  483.44
  5326.2  486.94  5354.2  488.63  5385.1  489.19  5428.3  491.79  5440.1  491.82
#Mann= 8 ,-1 , 0
  4491.5     .12       0  4596.7     .05       0  4624.5      .1       0
  4723.5     .12       0  4921.4      .1       0  4996.4     .07       0
  5000.4      .1       0  5122.2     .12       0
Bank Sta=4996.4,5000.4
XS Rating Curve= 0 ,0
Exp/Cntr=0.3,0.1

Type RM Length L Ch R = 1 ,11425   ,311,311,311
BEGIN DESCRIPTION:
Mapping XS eb3261c7
END DESCRIPTION:
XS GIS Cut Line= 3
      2739901.34      6893729.01      2740409.13      6893635.26
      2740635.67      6893346.23
#Sta/Elev= 30
  4492.2  482.35  4496.3  482.35  4510.5  482.21  4537.6  480.84  4563.4   480.1
  4735.5   477.5  4751.2  477.55  4791.8  476.27  4873.2  475.01  4891.4  474.26
  4903.7  474.43  4934.2  471.92  4944.4  471.52  4949.4   470.6  4964.7  469.72
  4974.9  470.16  4995.2  469.94  5004.5  469.38  5004.8  468.88  5008.3  468.88
  5008.5  469.38  5123.5   474.3  5129.9  475.01  5152.4  475.44  5179.6  476.72
  5187.7   476.7  5194.1   477.2  5266.4  479.48  5365.8  483.81  5375.8  483.81
#Mann= 5 ,-1 , 0
  4492.2     .12       0  4496.3     .05       0  4735.5     .12       0
  5004.5     .07       0  5008.5     .12       0
Bank Sta=5004.5,5008.5
XS Rating Curve= 0 ,0
Exp/Cntr=0.3,0.1

Type RM Length L Ch R = 1 ,11114   ,299,299,299
BEGIN DESCRIPTION:
Mapping XS 7dbfb955
END DESCRIPTION:
XS GIS Cut Line= 3
      2740031.51      6894046.73       2740640.9      6893809.74
      2740773.73      6893366.99
#Sta/Elev= 30
  4364.5  484.23  4412.2  483.99  4474.1  481.58  4509.3  481.25  4697.1  473.39
  4837.5  471.15  4884.3  468.77  4895.6  469.32  4914.7  466.74  4920.1  467.37
  4944.6  466.26  4969.2  466.57  4978.9  465.56  4979.2  465.06  4982.9  465.56
  4991.6  467.33  5018.4  467.89  5037.9  469.45  5119.7  473.49  5173.6  474.92
    5191  476.34  5229.3  476.86  5246.7  478.17  5262.3  478.24  5295.4  480.73
  5328.5  480.78    5372  483.26    5405  483.67  5445.1  486.19  5480.6  486.72
#Mann= 4 ,-1 , 0
  4364.5     .05       0  4837.5     .12       0  4978.9     .07       0
  4982.9     .12       0
Bank Sta=4978.9,4982.9
XS Rating Curve= 0 ,0
Exp/Cntr=0.3,0.1

Type RM Length L Ch R = 1 ,10815   ,291,291,291
BEGIN DESCRIPTION:
Mapping XS 817fe59d
END DESCRIPTION:
XS GIS Cut Line= 4
       2740339.9      6894329.56      2740696.02       6894103.6
      2740818.13      6893885.22      2740811.66      6893614.66
#Sta/Elev= 30
  4562.4   473.8  4711.7  470.32  4747.3  470.07  4782.8  468.53  4833.2  468.45
  4884.9  467.04  4934.6  467.14  4957.8  465.88  4978.9  466.38  4981.9  464.98
  4988.5  464.98  4999.3  462.59  5013.3  460.94  5013.6  460.44  5017.1  460.44
  5017.3  460.94  5021.5  463.79    5053  465.46  5118.1  465.15  5134.1  465.91
  5147.5  465.05  5183.2  464.99  5220.9  467.21  5278.6   468.6  5298.6  470.28
    5403  474.96  5428.5  475.82  5458.6  477.07  5468.7  478.09    5505  479.27
#Mann= 6 ,-1 , 0
  4562.4     .05       0  4934.6     .12       0  5013.3     .07       0
  5017.3     .12       0    5403      .1       0  5428.5     .12       0
Bank Sta=5013.3,5017.3
XS Rating Curve= 0 ,0
Exp/Cntr=0.3,0.1

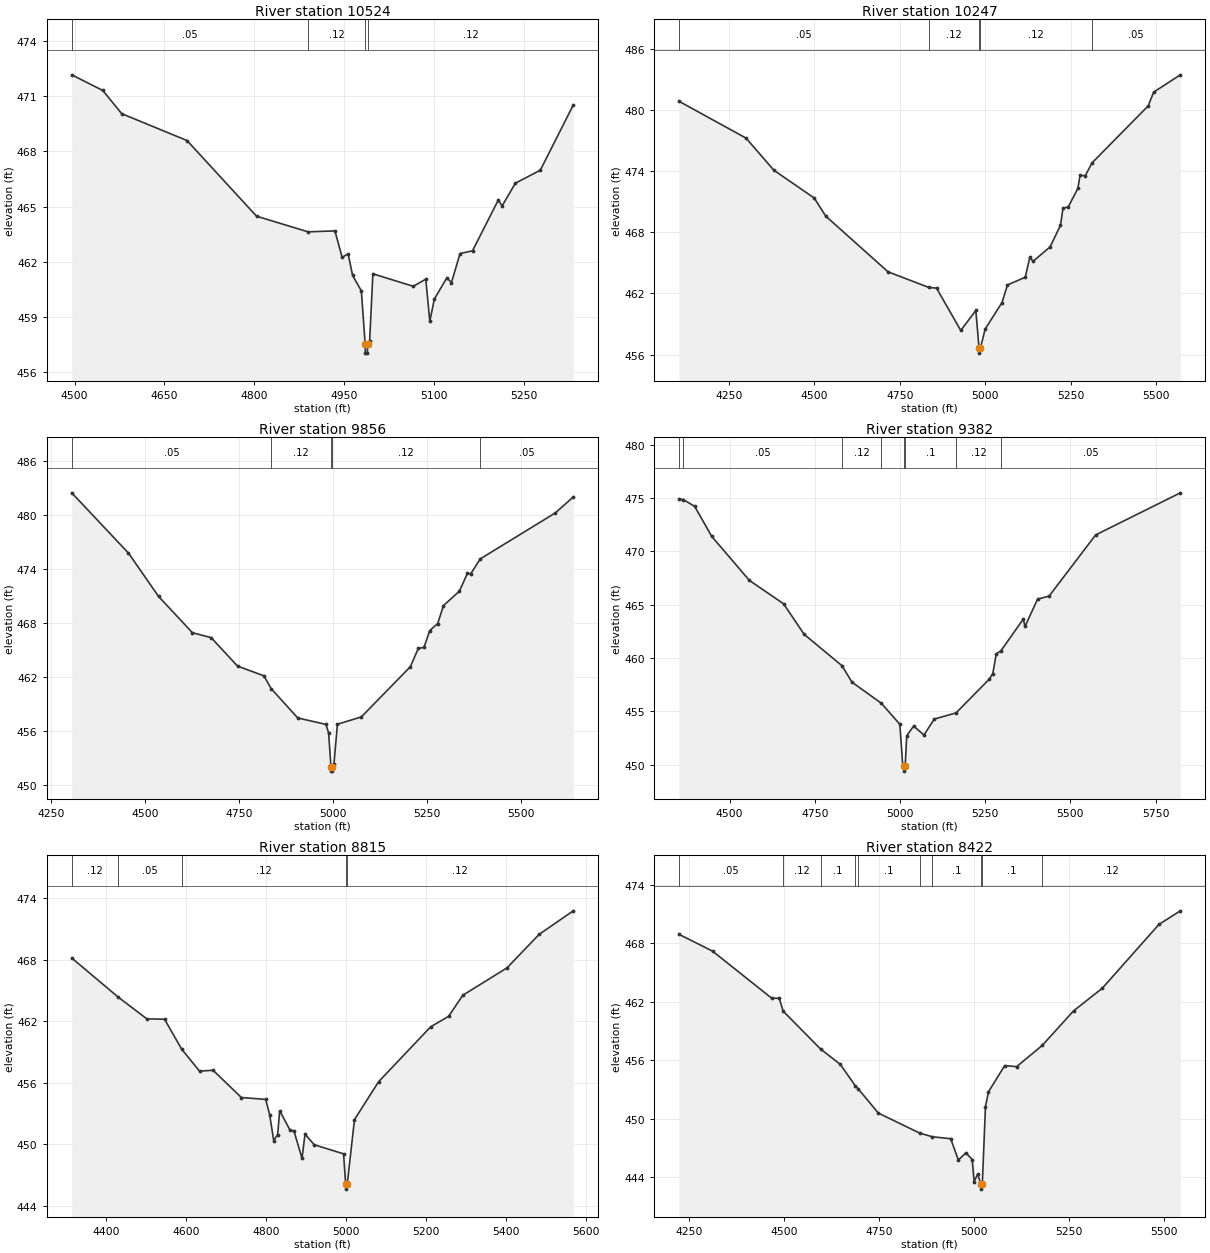
Type RM Length L Ch R = 1 ,10524   ,277,277,277
BEGIN DESCRIPTION:
Mapping XS 7e4f7cb1
END DESCRIPTION:
XS GIS Cut Line= 4
      2740414.28      6894401.42      2740676.35      6894383.57
      2740895.89      6894281.45      2741147.83      6894066.17
#Sta/Elev= 30
  4495.4  472.16  4547.2  471.31  4578.7  470.05  4687.6  468.59  4803.5  464.48
  4889.4  463.63  4934.2  463.68  4946.3  462.24  4956.2  462.44  4963.7  461.26
  4978.3  460.42  4984.6  457.54  4984.9  457.04  4988.4  457.04  4988.6  457.54
  4992.1  457.71  4997.5  461.35  5064.9  460.67  5085.7  461.06  5092.4  458.77
    5100  459.98  5120.8  461.13  5128.5  460.87  5142.8  462.45  5163.6   462.6
  5206.5  465.35    5213  465.04    5235  466.27  5276.7  466.98  5331.6  470.52
#Mann= 4 ,-1 , 0
  4495.4     .05       0  4889.4     .12       0  4984.6     .07       0
  4988.6     .12       0
Bank Sta=4984.6,4988.6
XS Rating Curve= 0 ,0
Exp/Cntr=0.3,0.1

Type RM Length L Ch R = 1 ,10247   ,391,391,391
BEGIN DESCRIPTION:
Mapping XS 2e752948
END DESCRIPTION:
XS GIS Cut Line= 3
       2740101.8      6894619.64      2740959.48      6894480.75
      2741482.36      6894189.87
#Sta/Elev= 30
  4103.1   480.9  4299.8  477.27    4381  474.12  4499.3  471.38  4532.8  469.61
  4715.2  464.13  4834.8  462.59    4857  462.53  4927.9  458.37    4972  460.33
  4981.4  456.64  4981.7  456.14  4985.4  456.64  4999.4  458.51  5048.6  461.11
  5064.6  462.84  5116.7   463.6  5129.8  465.54  5139.6  465.17  5189.3  466.58
  5219.7  468.71    5227  470.38  5242.6  470.52  5270.5  472.33  5276.9   473.6
  5292.2  473.58  5312.1  474.84  5476.3  480.44  5492.3  481.79  5570.3  483.49
#Mann= 5 ,-1 , 0
  4103.1     .05       0  4834.8     .12       0  4981.4     .07       0
  4985.4     .12       0  5312.1     .05       0
Bank Sta=4981.4,4985.4
XS Rating Curve= 0 ,0
Exp/Cntr=0.3,0.1

Type RM Length L Ch R = 1 ,9856    ,474,474,474
BEGIN DESCRIPTION:
Mapping XS 0de3c606
END DESCRIPTION:
XS GIS Cut Line= 3
      2740335.37      6894844.46      2741004.61      6894828.84
      2741564.48      6894472.08
#Sta/Elev= 30
  4304.8  482.43  4455.5  475.74  4535.5  470.93  4625.5  466.89  4675.5  466.34
  4745.5  463.18  4815.6   462.1  4834.9  460.68  4905.6  457.42  4980.7   456.7
  4987.7  455.75  4993.9  452.01  4994.1  451.51  4997.6  451.51  4997.9  452.01
  5001.8  452.27  5011.1  456.72  5074.6  457.53    5205  463.11  5226.1  465.14
  5241.3  465.26  5256.6  467.13  5277.7   467.9    5293   469.9  5335.3   471.5
  5356.5  473.47  5365.8  473.45  5390.8  475.09  5590.1  480.19  5638.1  481.97
#Mann= 5 ,-1 , 0
  4304.8     .05       0  4834.9     .12       0  4993.9     .07       0
  4997.9     .12       0  5390.8     .05       0
Bank Sta=4993.9,4997.9
XS Rating Curve= 0 ,0
Exp/Cntr=0.3,0.1

Type RM Length L Ch R = 1 ,9382    ,567,567,567
BEGIN DESCRIPTION:
Mapping XS 415321d3
END DESCRIPTION:
XS GIS Cut Line= 3
       2740379.6      6895209.05      2741020.24      6895258.53
      2741840.56      6895141.34
#Sta/Elev= 30
  4351.2  474.88  4364.2  474.85  4397.7  474.21  4447.9  471.39  4558.2  467.27
  4658.5  465.08  4718.7  462.22  4829.9  459.27  4859.1  457.73  4945.1  455.76
  4999.6  453.78  5008.1   449.9  5011.2  449.89  5011.4  449.39  5015.2  449.89
  5019.8  452.71    5040  453.61  5070.3  452.78  5100.6  454.27  5164.5  454.85
  5262.2  458.02  5272.3  458.54  5282.4  460.38  5296.6  460.69  5361.7  463.65
  5366.7  462.95  5403.6  465.51  5437.4   465.8  5573.8  471.53  5822.4  475.48
#Mann= 8 ,-1 , 0
  4351.2     .12       0  4364.2     .05       0  4829.9     .12       0
  4945.1      .1       0  5011.2     .07       0  5015.2      .1       0
  5164.5     .12       0  5296.6     .05       0
Bank Sta=5011.2,5015.2
XS Rating Curve= 0 ,0
Exp/Cntr=0.3,0.1

Type RM Length L Ch R = 1 ,8815    ,393,393,393
BEGIN DESCRIPTION:
Mapping XS dad3d563
END DESCRIPTION:
XS GIS Cut Line= 3
       2740446.5      6895647.42      2741116.59      6895749.85
      2741691.16      6895697.77
#Sta/Elev= 30
  4313.9  468.17  4430.1  464.36  4501.8  462.24  4546.1   462.2  4588.9  459.29
  4633.7  457.14  4667.5  457.23  4738.3  454.57    4799  454.39  4809.1   452.9
  4819.2  450.38  4829.1  450.96  4834.2  453.29  4859.7  451.41  4869.8  451.33
    4890  448.64  4897.6  451.01  4920.4  449.97    4994  449.08  4999.2  446.14
  4999.5  445.64  5003.2  446.14  5021.3  452.42  5081.6  456.11  5212.1  461.47
  5256.6  462.48  5292.4  464.54  5402.9  467.21  5483.2  470.47  5568.7  472.77
#Mann= 5 ,-1 , 0
  4313.9     .12       0  4430.1     .05       0  4588.9     .12       0
  4999.2     .07       0  5003.2     .12       0
Bank Sta=4999.2,5003.2
XS Rating Curve= 0 ,0
Exp/Cntr=0.3,0.1

Type RM Length L Ch R = 1 ,8422    ,385,385,385
BEGIN DESCRIPTION:
Mapping XS 2bdafb76
END DESCRIPTION:
XS GIS Cut Line= 3
      2740402.14      6895978.57      2741148.71      6896041.51
      2741706.48      6895913.46
#Sta/Elev= 30
  4222.2  468.92    4311  467.19  4466.9  462.36    4487  462.35    4497  461.04
  4596.2  457.13  4647.6  455.58    4687  453.39  4695.3  453.05  4747.9  450.58
  4856.7  448.53  4890.1  448.15  4938.6  447.95  4958.7  445.77  4978.9  446.51
  4995.2  445.81  5000.3  443.56  5009.7  444.32  5017.9  443.28  5018.2  442.78
  5021.9  443.28  5030.2  451.23    5038  452.75  5080.9  455.45  5112.3  455.34
  5179.6  457.51  5262.6  461.07    5338  463.38  5487.2  469.92  5543.7  471.32
#Mann= 10 ,-1 , 0
  4222.2     .05       0    4497     .12       0  4596.2      .1       0
    4687     .12       0  4695.3      .1       0  4856.7     .12       0
  4890.1      .1       0  5017.9     .07       0  5021.9      .1       0
  5179.6     .12       0
Bank Sta=5017.9,5021.9
XS Rating Curve= 0 ,0
Exp/Cntr=0.3,0.1

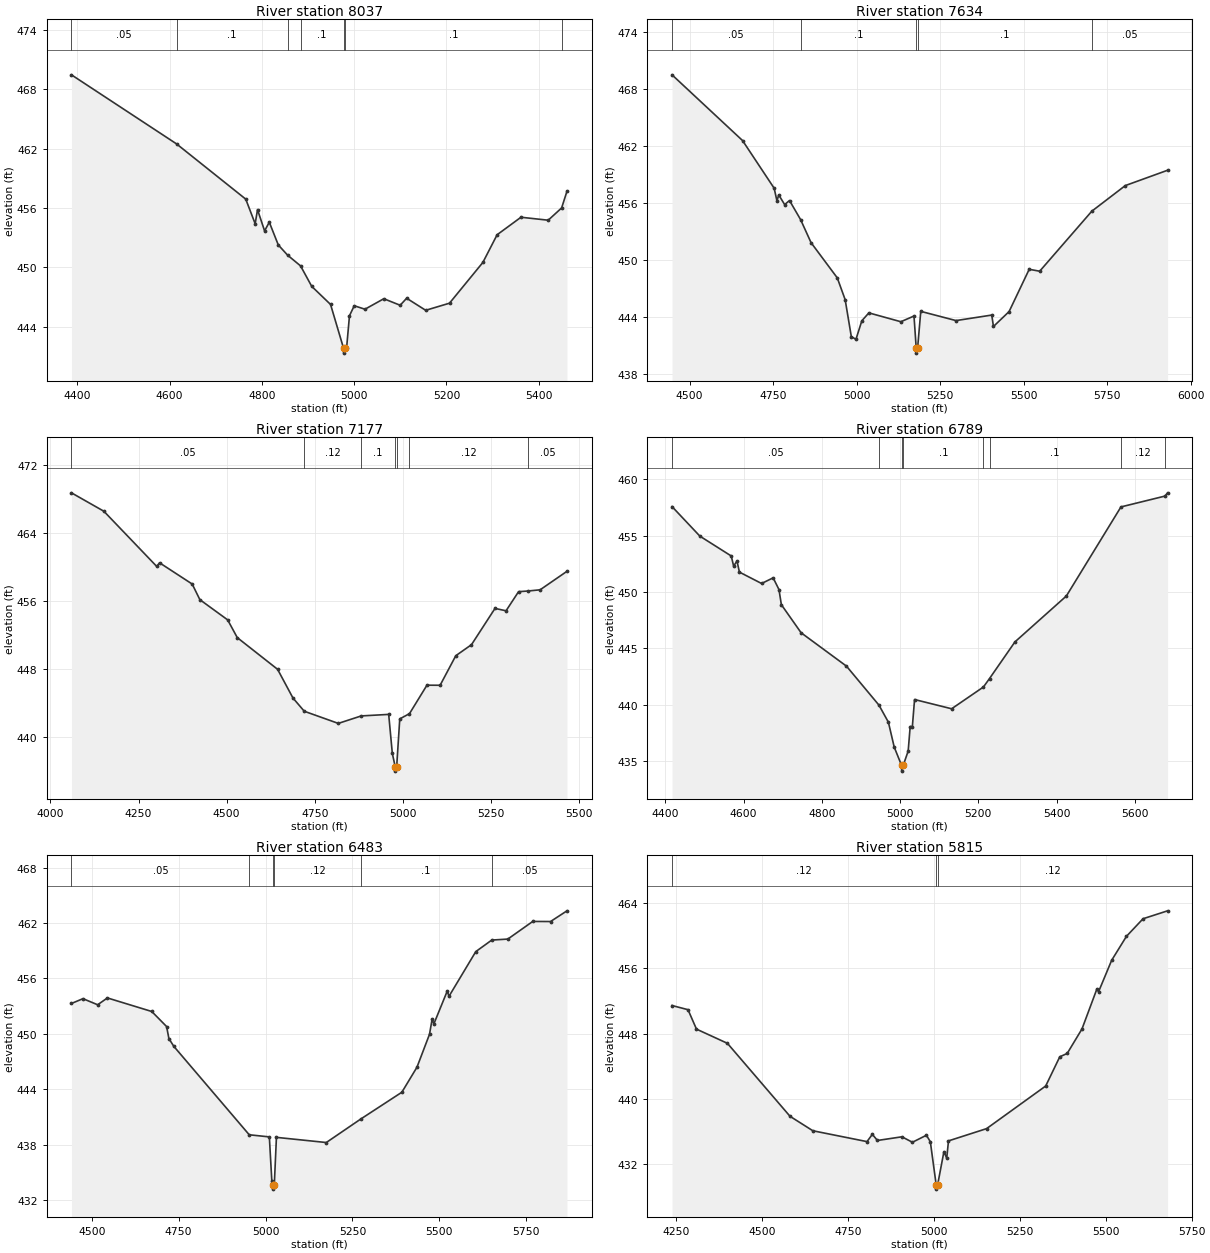
Type RM Length L Ch R = 1 ,8037    ,403,403,403
BEGIN DESCRIPTION:
Mapping XS 4d57b15a
END DESCRIPTION:
XS GIS Cut Line= 3
      2740376.15      6896223.81      2740959.91      6896345.33
       2741422.6      6896226.42
#Sta/Elev= 30
  4387.3  469.45    4615  462.47  4765.1  456.88  4785.5  454.39  4790.6  455.82
  4805.9  453.67  4816.1  454.55  4835.6  452.25  4855.9  451.21  4883.9  450.13
  4908.1  448.06  4948.9  446.23    4977  441.81  4977.3  441.31    4981  441.81
  4983.6  441.81  4989.9  445.09  5000.2   446.1  5023.5  445.75  5064.3  446.81
  5099.8  446.15  5113.8  446.86  5155.1  445.64  5206.7  446.36    5279  450.48
  5309.9  453.28  5361.6  455.05  5420.6  454.75  5449.7  455.99  5461.3  457.68
#Mann= 7 ,-1 , 0
  4387.3     .05       0    4615      .1       0  4855.9     .12       0
  4883.9      .1       0    4977     .07       0    4981      .1       0
  5449.7     .12       0
Bank Sta=4977,4981
XS Rating Curve= 0 ,0
Exp/Cntr=0.3,0.1

Type RM Length L Ch R = 1 ,7634    ,457,457,457
BEGIN DESCRIPTION:
Britton Creek 9.0
END DESCRIPTION:
XS GIS Cut Line= 3
      2740334.88      6896429.96      2740983.78      6896636.13
      2741772.36      6896779.11
#Sta/Elev= 30
  4447.7  469.45  4658.7  462.54  4753.2  457.53  4761.6   456.2  4766.9  456.83
  4784.6  455.81  4799.1  456.24  4832.2  454.24  4863.6  451.81    4942  448.11
  4965.6  445.82    4984  441.94  4997.9  441.65  5015.5   443.6  5036.5  444.43
  5132.2   443.5  5171.5   444.1  5178.2   440.7  5178.5   440.2  5182.2   440.7
  5191.8  444.59  5297.2  443.62  5404.1   444.2  5409.2     443    5456  444.57
  5516.1  449.01  5547.5  448.81  5703.5  455.12  5803.6  457.81    5930  459.42
#Mann= 5 ,-1 , 0
  4447.7     .05       0  4832.2      .1       0  5178.2     .07       0
  5182.2      .1       0  5703.5     .05       0
Bank Sta=5178.2,5182.2
XS Rating Curve= 0 ,0
Exp/Cntr=0.3,0.1

Type RM Length L Ch R = 1 ,7177    ,388,388,388
BEGIN DESCRIPTION:
Britton Creek 7.0
END DESCRIPTION:
XS GIS Cut Line= 4
      2740323.82      6896493.24      2740829.68      6896879.25
      2741125.41      6896949.17      2741540.01      6897159.94
#Sta/Elev= 30
  4059.8  468.72  4151.8  466.55  4301.5  460.06  4309.7  460.48  4402.2  457.98
    4424  456.14  4502.8  453.76  4530.1  451.67  4644.4  447.94    4688  444.56
  4720.1     443  4816.6  441.57  4881.6  442.45  4959.5  442.63  4969.8  438.03
  4978.1  436.45  4978.3  435.95  4982.1  436.45  4990.9   442.1  5018.5  442.72
    5068  446.07  5105.3  446.06  5149.8  449.54  5194.3  450.84    5261  455.11
  5292.3  454.83  5327.8  457.08  5354.7  457.16  5388.9   457.3  5465.1  459.48
#Mann= 7 ,-1 , 0
  4059.8     .05       0  4720.1     .12       0  4881.6      .1       0
  4978.1     .07       0  4982.1      .1       0  5018.5     .12       0
  5354.7     .05       0
Bank Sta=4978.1,4982.1
XS Rating Curve= 0 ,0
Exp/Cntr=0.3,0.1

Type RM Length L Ch R = 1 ,6789    ,306,306,306
BEGIN DESCRIPTION:
Britton Creek 6.0
END DESCRIPTION:
XS GIS Cut Line= 3
      2740542.53      6896744.33      2740892.51      6897244.29
      2741541.78      6897344.18
#Sta/Elev= 30
  4416.8  457.57    4488  454.95  4568.2  453.19  4574.3   452.3    4583  452.74
  4589.1  451.76  4645.8  450.75  4675.4  451.25  4690.3  450.21  4696.4  448.87
  4746.9  446.38  4862.9  443.42    4946  439.96  4970.1  438.45    4985  436.24
  5003.9  434.61  5004.1  434.11  5007.9  434.61  5020.7  435.89  5025.8  438.06
  5031.4  438.06    5037  440.46  5131.8  439.64  5213.1  441.57  5228.7  442.32
  5293.7  445.57  5425.2  449.64  5564.8  457.54  5677.2   458.5    5684  458.79
#Mann= 8 ,-1 , 0
  4416.8     .05       0    4946      .1       0  5003.9     .07       0
  5007.9      .1       0  5213.1     .12       0  5228.7      .1       0
  5564.8     .12       0  5677.2     .05       0
Bank Sta=5003.9,5007.9
XS Rating Curve= 0 ,0
Exp/Cntr=0.3,0.1

Type RM Length L Ch R = 1 ,6483    ,668,668,668
BEGIN DESCRIPTION:
Britton Creek 5.0
END DESCRIPTION:
XS GIS Cut Line= 3
      2740395.05      6897085.31      2740764.12       6897489.1
      2741622.18      6897679.64
#Sta/Elev= 30
  4441.5  453.29  4474.7  453.81  4516.9  453.15    4545  453.89  4672.7  452.42
  4715.3  450.79    4722  449.48  4736.2  448.64  4953.1  439.06    5011  438.83
  5018.2  434.02  5021.3  433.67  5021.6  433.17  5025.3  433.67  5031.4  438.78
  5174.9  438.22  5273.8  440.76  5392.3  443.67  5435.8  446.38  5471.9  449.95
  5479.4  451.58  5484.5  451.08  5522.9  454.63    5528  454.07  5605.1  458.91
    5651  460.16  5697.3  460.27    5769  462.18  5820.2  462.17  5867.5  463.33
#Mann= 6 ,-1 , 0
  4441.5     .05       0  4953.1     .12       0  5021.3     .07       0
  5025.3     .12       0  5273.8      .1       0    5651     .05       0
Bank Sta=5021.3,5025.3
XS Rating Curve= 0 ,0
Exp/Cntr=0.3,0.1

Type RM Length L Ch R = 1 ,5815    ,150,150,150
BEGIN DESCRIPTION:
Mapping XS 2f94a979
END DESCRIPTION:
XS GIS Cut Line= 4
      2740375.04      6897450.69      2740580.26       6897983.9
      2740958.04      6898053.96      2741431.72      6898161.52
#Sta/Elev= 30
  4238.6  451.46  4285.1  450.95  4309.7  448.57  4399.7  446.83  4581.8  437.89
  4648.2  436.12  4805.7  434.79  4821.2  435.68  4836.1  434.93  4907.3  435.38
  4937.8  434.71  4978.5  435.57  4989.9  434.78    5007  429.47  5007.3  428.97
    5011  429.47  5029.4  433.56  5037.6  432.76  5042.7  434.88  5153.5  436.38
  5325.4   441.6  5366.4  445.18    5388  445.59  5431.1   448.6  5474.2  453.47
  5479.3  453.16  5517.3     457  5560.4  459.94  5608.6  462.09  5679.9  463.06
#Mann= 3 ,-1 , 0
  4238.6     .12       0    5007     .07       0    5011     .12       0
Bank Sta=5007,5011
XS Rating Curve= 0 ,0
Exp/Cntr=0.3,0.1

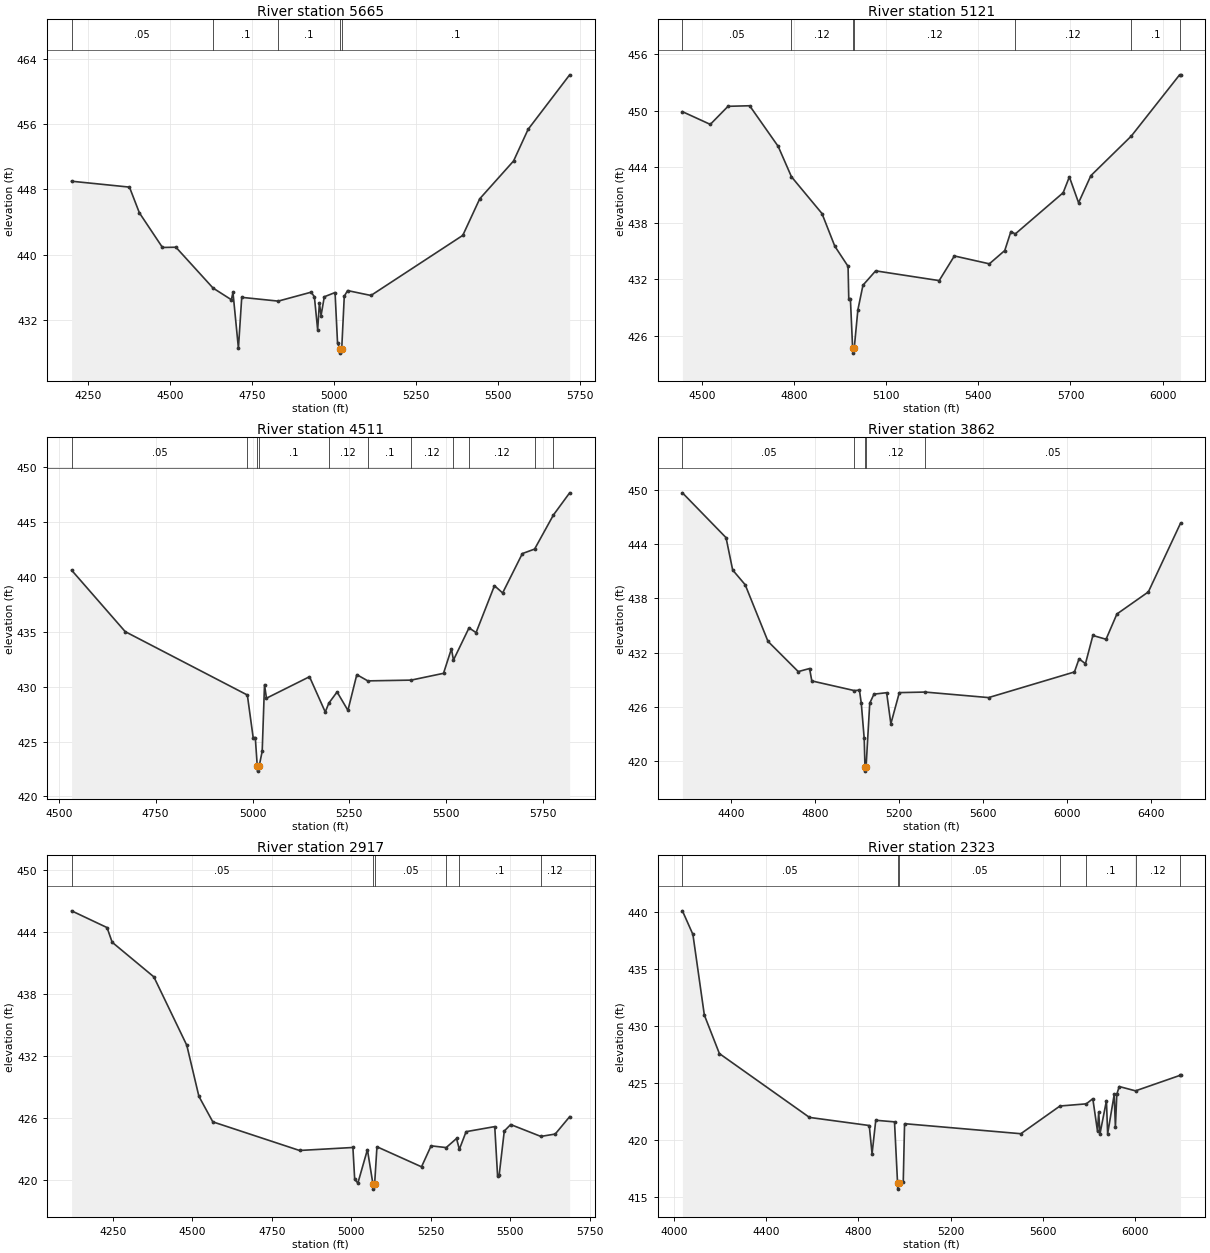
Type RM Length L Ch R = 1 ,5665    ,544,544,544
BEGIN DESCRIPTION:
Britton Creek 4.0
END DESCRIPTION:
XS GIS Cut Line= 3
      2739900.77      6898050.52      2740696.23      6898141.09
      2741400.37      6898278.39
#Sta/Elev= 30
  4199.4     449  4375.8  448.28    4406  445.14  4476.4   440.9  4517.4  440.93
  4630.5  435.94  4686.3  434.51  4691.3   435.4  4707.9  428.58    4718   434.8
  4829.2  434.34  4929.3  435.43  4939.4  434.88  4949.4  430.83  4954.7  434.11
  4959.8  432.58  4969.6  434.87  5002.4  435.39    5010   429.2  5017.6  428.48
  5018.2  427.98  5022.7  428.48  5030.5  434.93  5040.5  435.63  5111.8  435.03
  5391.7  442.38  5443.3  446.85  5546.5  451.48  5590.7  455.34  5717.4  462.01
#Mann= 5 ,-1 , 0
  4199.4     .05       0  4630.5      .1       0  4829.2      .1       0
  5017.6     .07       0  5022.7      .1       0
Bank Sta=5017.6,5022.7
XS Rating Curve= 0 ,0
Exp/Cntr=0.3,0.1

Type RM Length L Ch R = 1 ,5121    ,610,610,610
BEGIN DESCRIPTION:
Mapping XS e08d488a
END DESCRIPTION:
XS GIS Cut Line= 4
      2739848.73      6898100.44       2740271.9      6898438.98
      2740656.02      6898538.81      2741337.43      6898510.59
#Sta/Elev= 30
  4437.2   449.9  4527.9  448.54  4585.6  450.47    4656  450.53  4748.9  446.19
    4792  442.95  4891.3  439.03  4933.1  435.54  4976.2  433.39  4978.5  429.93
  4983.8  429.93  4991.1  424.63  4991.8  424.13  4996.2  424.63  5008.1  428.74
  5024.7  431.38    5066  432.91  5272.7  431.87  5322.1   434.5    5436  433.66
  5486.1  435.08  5506.1  437.11  5520.3  436.85  5676.2  441.25  5696.3  442.94
  5726.3  440.18  5766.3  443.07    5898   447.3    6055  453.83    6058  453.83
#Mann= 7 ,-1 , 0
  4437.2     .05       0    4792     .12       0  4991.1     .07       0
  4996.2     .12       0  5520.3     .12       0    5898      .1       0
    6055     .12       0
Bank Sta=4991.1,4996.2
XS Rating Curve= 0 ,0
Exp/Cntr=0.3,0.1

Type RM Length L Ch R = 1 ,4511    ,649,649,649
BEGIN DESCRIPTION:
Britton Creek 3.0
END DESCRIPTION:
XS GIS Cut Line= 3
      2739726.02      6898711.02        2740126.        6898961.
      2740925.99        6898811.
#Sta/Elev= 30
    4533  440.64  4671.5  435.03  4986.7  429.25  5001.7  425.37  5007.2  425.37
  5012.2  422.81  5012.9  422.31  5017.4  422.81    5025  424.12    5031   430.2
    5036  428.96  5147.1  430.92  5187.8   427.7    5197  428.51  5218.3  429.53
  5246.3  427.85  5269.2  431.11  5297.6  430.54  5409.5  430.61    5493  431.23
  5513.4  433.46  5518.7  432.44  5558.9  435.38    5577  434.94  5624.5  439.22
  5645.6  438.56  5696.5  442.15  5728.1  442.56  5776.7  445.67  5818.6  447.69
#Mann= 11 ,-1 , 0
    4533     .05       0  4986.7      .1       0  5012.2     .07       0
  5017.4      .1       0    5197     .12       0  5297.6      .1       0
  5409.5     .12       0  5518.7      .1       0  5558.9     .12       0
  5728.1     .05       0  5776.7     .12       0
Bank Sta=5012.2,5017.4
XS Rating Curve= 0 ,0
Exp/Cntr=0.3,0.1

Type RM Length L Ch R = 1 ,3862    ,945,945,945
BEGIN DESCRIPTION:
Britton Creek 2.0
END DESCRIPTION:
XS GIS Cut Line= 4
      2739102.81      6899096.85       2739883.3      6899403.39
       2740440.3      6899461.24      2741326.04      6899060.98
#Sta/Elev= 30
  4169.1  449.66  4376.7  444.71  4408.2  441.14  4467.8  439.51  4576.3  433.26
  4720.4  429.92  4774.2  430.26  4784.9  428.89  4987.9  427.82  5011.5  427.88
  5020.4  426.41  5034.2  422.54  5037.9  419.43  5038.6  418.93  5043.2  419.43
  5060.6  426.43  5080.7  427.43    5141  427.59  5161.1  424.16  5201.4   427.6
  5324.3  427.66  5626.1  427.05  6034.8  429.88  6056.7  431.33  6087.2  430.79
  6122.6  433.91  6185.2  433.49  6236.9  436.28  6386.6  438.72  6539.6   446.3
#Mann= 5 ,-1 , 0
  4169.1     .05       0  4987.9     .12       0  5037.9     .07       0
  5043.2     .12       0  5324.3     .05       0
Bank Sta=5037.9,5043.2
XS Rating Curve= 0 ,0
Exp/Cntr=0.3,0.1

Type RM Length L Ch R = 1 ,2917    ,594,594,594
BEGIN DESCRIPTION:
Mapping XS c70156d4
END DESCRIPTION:
XS GIS Cut Line= 3
      2739169.04      6899425.77      2739590.39      6900204.69
      2740271.38      6900162.08
#Sta/Elev= 30
  4119.4  446.09    4231  444.47  4247.2  443.05  4378.4   439.7  4482.1  433.08
  4520.2  428.14    4564  425.67    4837   422.9    5005  423.19  5010.6  420.11
  5020.6  419.74  5050.7  422.98    5068  419.66  5068.8  419.16  5073.4  419.66
  5080.7  423.26    5221  421.32  5251.1  423.35  5298.6  423.18  5331.2  424.06
  5340.1  423.01  5361.3  424.72  5451.5  425.21  5460.4  420.44  5465.5  420.55
  5481.5  424.78  5501.6  425.41  5596.6  424.26  5641.8  424.49  5687.3  426.17
#Mann= 6 ,-1 , 0
  4119.4     .05       0    5068     .04       0  5073.4     .05       0
  5298.6     .12       0  5340.1      .1       0  5596.6     .12       0
Bank Sta=5068,5073.4
XS Rating Curve= 0 ,0
Exp/Cntr=0.3,0.1

Type RM Length L Ch R = 1 ,2323    ,0,0,0
BEGIN DESCRIPTION:
Britton Creek 1.0
END DESCRIPTION:
XS GIS Cut Line= 3
      2738895.94      6899881.14       2739371.8      6900743.92
      2740501.51      6900417.25
#Sta/Elev= 30
  4036.2  440.07  4081.7     438  4131.3  430.93  4196.6  427.55  4587.5  421.95
  4846.9  421.24  4859.1  418.76  4875.2   421.7  4956.5  421.56  4969.8  416.16
  4970.5  415.66  4975.2  416.16  4994.4  416.26  5000.1   421.4  5504.7  420.52
  5674.4  422.95  5788.6  423.14    5817  423.59  5837.3  420.74  5842.5  422.43
  5848.2  420.52  5876.1  423.42  5881.3  420.51  5909.8  423.96    5915  421.09
  5921.1  423.98  5931.5  424.66  6002.3  424.28    6197  425.65  6197.5  425.66
#Mann= 7 ,-1 , 0
  4036.2     .05       0  4969.8     .04       0  4975.2     .05       0
  5674.4     .12       0  5788.6      .1       0  6002.3     .12       0
    6197     .05       0
Bank Sta=4969.8,4975.2
XS Rating Curve= 0 ,0
Exp/Cntr=0.3,0.1

Chan Stop Cuts=-1
Use User Specified Reach Order=0
Composite Channel Slope=5