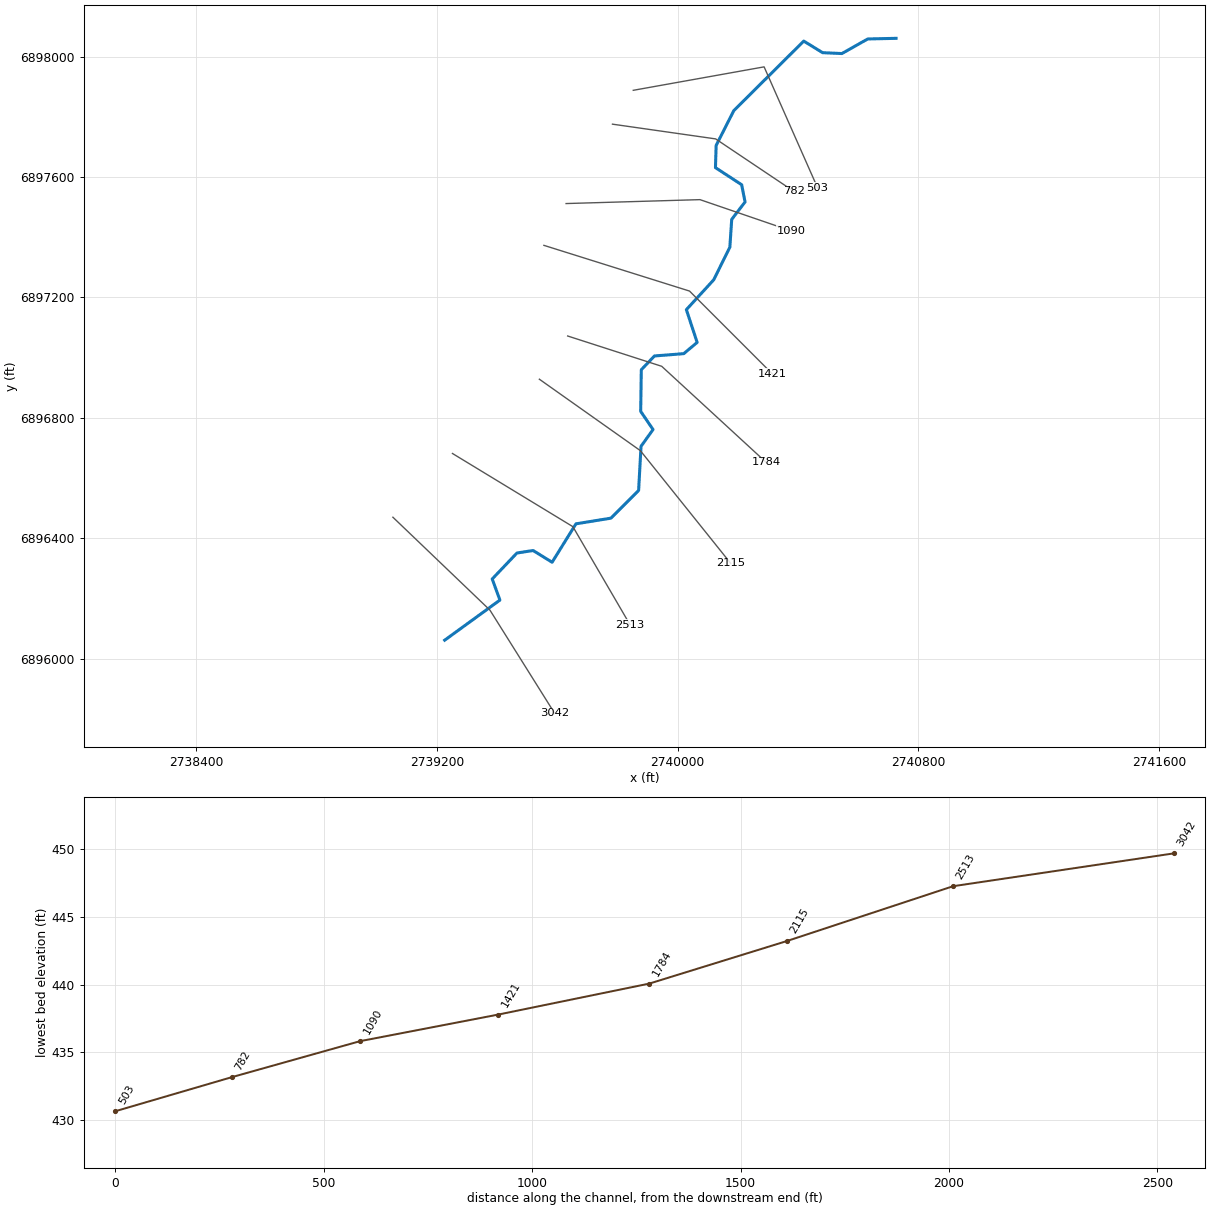
--- Britton T1.prj (project) ---

Proj Title=Britton T1 Base Level Engineering
Current Plan=p01
Default Exp/Contr=0.3,0.1
English Units
Geom File=g01
Flow File=f01
Plan File=p01
Y Axis Title=Elevation
X Axis Title(PF)=Main Channel Distance
X Axis Title(XS)=Station
BEGIN DESCRIPTION:
Britton T1
END DESCRIPTION:
DSS Export Rating Curves= 0
DSS Export Rating Curve Sorted= 0
DSS Export Volume Flow Curves= 0
DXF OffsetX= 0
DXF OffsetY= 0
DXF ScaleX= 1
DXF ScaleY= 10

--- Britton T1.p01 (plan) ---

Plan Title=Multiple Run
Short Identifier=Multiple
Geom File=g01
Flow File=f01
Subcritical Flow
K Sum by GR= 0
Std Step Tol= 0.01
Critical Tol= 0.01
Num of Std Step Trials= 20
Max Error Tol= 0.3
Flow Tol Ratio= 0.001
Split Flow NTrial= 30
Split Flow Tol= 0.02
Split Flow Ratio= 0.02
Log Output Level= 0
Friction Slope Method= 1
Unsteady Friction Slope Method= 2
Unsteady Bridges Friction Slope Method= 1
Parabolic Critical Depth
Global Vel Dist=  1 , 1 , 1
Global Log Level= 0
CheckData=True
Encroach Param= -1, 0, 0, 0
BEGIN DESCRIPTION:
Multiple Run
END DESCRIPTION:

--- Britton T1.f01 (steady flow) ---

Flow Title=Multiple
Program Version=4.10
Number of Profiles= 7
Profile Names=10-year,25-year,50-year,1pct_min,100-year,1pct_plu,500-year
River Rch & RM=Britton T1,Reach-1         ,3042
     489     646     771     458     913    1823    1278
Boundary for River Rch & Prof#=Britton T1,Reach-1         , 1
Up Type= 0
Dn Type= 3
Dn Slope=0.009
Boundary for River Rch & Prof#=Britton T1,Reach-1         , 2
Up Type= 0
Dn Type= 3
Dn Slope=0.009
Boundary for River Rch & Prof#=Britton T1,Reach-1         , 3
Up Type= 0
Dn Type= 3
Dn Slope=0.009
Boundary for River Rch & Prof#=Britton T1,Reach-1         , 4
Up Type= 0
Dn Type= 3
Dn Slope=0.009
Boundary for River Rch & Prof#=Britton T1,Reach-1         , 5
Up Type= 0
Dn Type= 3
Dn Slope=0.009
Boundary for River Rch & Prof#=Britton T1,Reach-1         , 6
Up Type= 0
Dn Type= 3
Dn Slope=0.009
Boundary for River Rch & Prof#=Britton T1,Reach-1         , 7
Up Type= 0
Dn Type= 3
Dn Slope=0.009
DSS Import GetInterval= 0
DSS Import GetPeak= 0
DSS Import FillOption= 0

--- Britton T1.g01 (geometry) ---

Geom Title=Existing Conditions
Program Version=4.10

River Reach=Britton T1      ,Reach-1
Reach XY= 30
        2739226.        6896061.      2739409.62       6896194.3
        2739384.      6896264.35      2739466.28      6896350.79
      2739519.96      6896359.01      2739583.01      6896320.03
      2739662.35      6896447.73      2739778.44      6896466.52
      2739870.54      6896558.54      2739878.47      6896705.14
      2739918.44        6896761.      2739877.37      6896821.44
      2739879.43      6896959.77      2739923.29      6897005.59
      2740020.51      6897013.15      2740065.04      6897050.57
      2740029.17      6897159.35      2740120.15      6897258.71
      2740173.67      6897366.97      2740179.89      6897459.42
      2740224.23      6897517.17      2740212.95      6897574.54
      2740125.89      6897631.27       2740128.1      6897704.95
      2740186.76      6897820.68      2740419.26      6898051.87
      2740481.89      6898013.37      2740546.04      6898010.41
      2740631.87      6898058.89        2740726.        6898061.

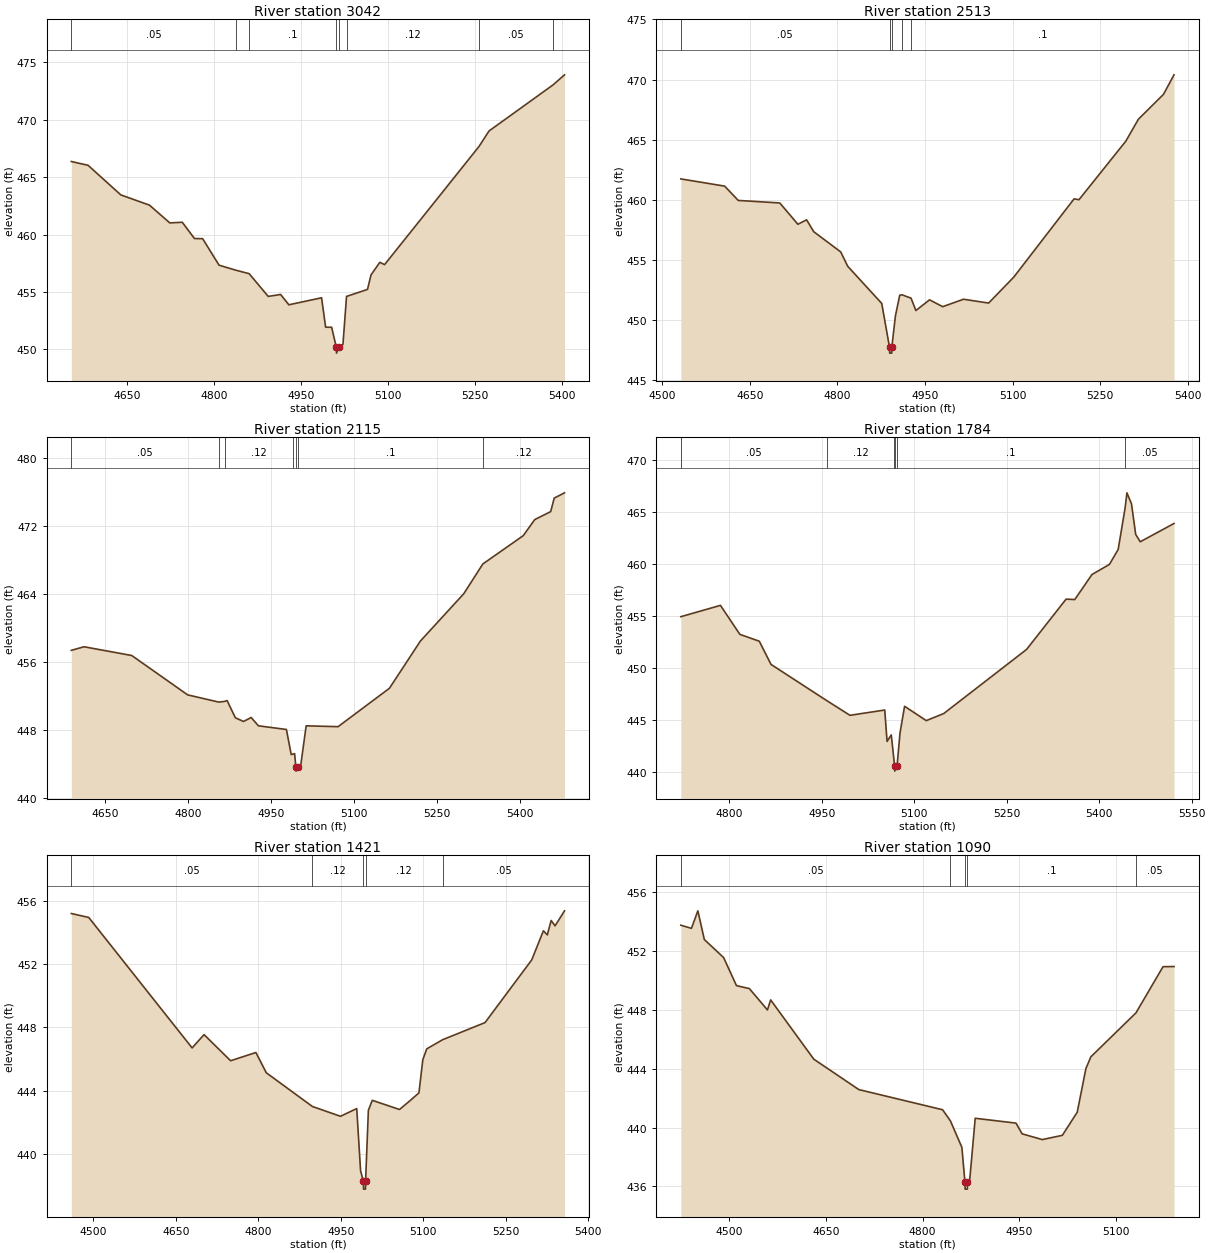
Type RM Length L Ch R = 1 ,3042    ,529,529,529
BEGIN DESCRIPTION:
Britton T1 4.0
END DESCRIPTION:
XS GIS Cut Line= 3
        2739054.      6896469.67      2739376.56      6896160.79
      2739591.61      6895817.84
#Sta/Elev= 30
  4553.4  466.37  4582.3  466.04  4638.9  463.46  4688.3  462.57  4723.5  461.02
  4744.9  461.08    4766  459.66  4780.1  459.65  4808.4  457.34  4837.7   456.9
  4860.4   456.6  4893.3  454.62  4914.7  454.79  4928.9  453.89  4985.4   454.5
  4992.4  451.94  5002.8  451.93  5010.9  450.18  5011.2  449.68  5014.9  450.18
  5022.3  450.44  5028.5  454.62  5064.7  455.23  5070.7  456.49    5086  457.59
  5094.2  457.39  5257.2  467.68  5274.5  469.03  5384.9  473.04  5404.8  473.92
#Mann= 8 ,-1 , 0
  4553.4     .05       0  4837.7     .12       0  4860.4      .1       0
  5010.9     .07       0  5014.9      .1       0  5028.5     .12       0
  5257.2     .05       0  5384.9     .12       0
Bank Sta=5010.9,5014.9
XS Rating Curve= 0 ,0
Exp/Cntr=0.3,0.1

Type RM Length L Ch R = 1 ,2513    ,398,398,398
BEGIN DESCRIPTION:
Britton T1 3.0
END DESCRIPTION:
XS GIS Cut Line= 3
      2739251.91      6896681.47      2739652.11      6896438.27
      2739841.61      6896113.05
#Sta/Elev= 30
  4531.7  461.74  4606.7  461.14  4630.1  459.95  4701.2  459.74  4732.2  457.97
  4747.1  458.34  4759.4  457.35  4805.6  455.67  4817.5  454.48  4875.8  451.39
  4889.1  447.76  4889.4  447.26  4892.9  447.26  4893.1  447.76  4899.2  450.34
  4906.6  452.07  4910.3  452.11    4926  451.83  4934.3   450.8  4957.7  451.69
  4980.2  451.12  5015.9  451.74  5058.9  451.42    5102  453.58  5205.2  460.08
  5213.6  460.01  5293.9  464.88  5315.4   466.7  5358.4  468.77  5376.4  470.39
#Mann= 5 ,-1 , 0
  4531.7     .05       0  4889.1     .07       0  4893.1     .05       0
  4910.3     .12       0    4926      .1       0
Bank Sta=4889.1,4893.1
XS Rating Curve= 0 ,0
Exp/Cntr=0.3,0.1

Type RM Length L Ch R = 1 ,2115    ,331,331,331
BEGIN DESCRIPTION:
Britton T1 2.0
END DESCRIPTION:
XS GIS Cut Line= 3
      2739540.72      6896928.26      2739876.21      6896691.01
      2740176.54      6896316.32
#Sta/Elev= 30
  4589.1  457.43  4612.1  457.85  4698.3  456.82  4799.3  452.19  4855.6  451.34
  4865.9  451.42  4870.6  451.52  4885.4   449.5  4900.2  449.06    4914  449.53
  4927.2  448.55  4977.7  448.12  4986.4  445.17  4989.2  445.22  4992.5  445.28
  4994.8  443.72  4995.1  443.22  4998.8  443.72  5003.2  443.72  5013.4  448.55
  5071.1  448.45  5163.9  452.97  5219.9  458.53  5298.3   464.1  5332.6  467.59
  5405.6  470.92  5426.4  472.81  5455.2  473.75  5461.6  475.34  5480.2  475.96
#Mann= 7 ,-1 , 0
  4589.1     .05       0  4855.6      .1       0  4865.9     .12       0
  4989.2      .1       0  4994.8     .07       0  4998.8      .1       0
  5332.6     .12       0
Bank Sta=4994.8,4998.8
XS Rating Curve= 0 ,0
Exp/Cntr=0.3,0.1

Type RM Length L Ch R = 1 ,1784    ,363,363,363
BEGIN DESCRIPTION:
Mapping XS b63bd96a
END DESCRIPTION:
XS GIS Cut Line= 3
      2739634.79      6897071.86      2739947.25      6896971.18
      2740294.48      6896651.73
#Sta/Elev= 30
  4721.3  454.93  4785.6  456.02  4817.1  453.23  4848.6  452.57  4867.6  450.34
  4958.2  446.85  4995.7  445.44  5052.1  445.95  5055.9  442.93  5062.7  443.56
  5067.2  441.07  5068.1  440.57  5068.4  440.07  5072.1  440.57  5076.9  443.75
  5084.3  446.31  5119.5  444.93  5147.8  445.61  5282.2  451.78  5346.3  456.62
  5360.4  456.58  5388.3  458.99  5416.6  459.96  5430.8   461.4    5442  465.37
    5445  466.85  5452.4  465.79  5459.2  462.85  5466.6  462.14  5521.4   463.9
#Mann= 6 ,-1 , 0
  4721.3     .05       0  4958.2     .12       0  5067.2      .1       0
  5068.1     .07       0  5072.1      .1       0    5442     .05       0
Bank Sta=5068.1,5072.1
XS Rating Curve= 0 ,0
Exp/Cntr=0.3,0.1

Type RM Length L Ch R = 1 ,1421    ,331,331,331
BEGIN DESCRIPTION:
Mapping XS 5e2e34dd
END DESCRIPTION:
XS GIS Cut Line= 3
      2739555.76      6897373.09       2740039.7      6897221.18
       2740315.1      6896945.78
#Sta/Elev= 30
  4460.2  455.19  4491.9  454.94  4679.8   446.7  4701.5  447.54  4749.8  445.89
  4795.8  446.41  4814.7  445.13  4898.5     443  4949.6  442.38  4979.1  442.87
  4986.1  438.94  4991.2  438.28  4991.5  437.78    4995  437.78  4995.2  438.28
  5000.3  442.76  5007.4  443.39  5056.9  442.81  5078.1  443.43  5092.2  443.86
  5099.3  445.96  5106.4  446.64  5135.4  447.22  5212.4   448.3  5297.3  452.26
  5318.5   454.1  5325.6  453.84  5332.6  454.75  5339.7  454.41  5356.9  455.36
#Mann= 5 ,-1 , 0
  4460.2     .05       0  4898.5     .12       0  4991.2     .07       0
  4995.2     .12       0  5135.4     .05       0
Bank Sta=4991.2,4995.2
XS Rating Curve= 0 ,0
Exp/Cntr=0.3,0.1

Type RM Length L Ch R = 1 ,1090    ,308,308,308
BEGIN DESCRIPTION:
Mapping XS 3e77c605
END DESCRIPTION:
XS GIS Cut Line= 3
       2739629.5      6897511.97      2740074.42        6897525.
      2740378.25      6897420.83
#Sta/Elev= 30
  4424.4  453.77  4440.9  453.56  4450.9  454.75  4460.9   452.8  4490.9  451.57
  4510.9  449.66  4530.9  449.46    4559  448.01    4564  448.69    4631  444.66
    4701  442.59  4831.1  441.22  4843.3  440.46  4861.1  438.66  4865.8  436.32
  4866.1  435.82  4869.6  435.82  4869.8  436.32    4873  436.32  4881.8  440.64
  4945.2  440.31  4954.7  439.58    4986  439.19  5017.2  439.48  5040.3  441.05
  5053.8  444.02  5061.5  444.82  5131.6  447.81  5173.6  450.95  5190.7  450.96
#Mann= 5 ,-1 , 0
  4424.4     .05       0  4843.3      .1       0  4865.8     .05       0
  4869.8      .1       0  5131.6     .05       0
Bank Sta=4865.8,4869.8
XS Rating Curve= 0 ,0
Exp/Cntr=0.3,0.1

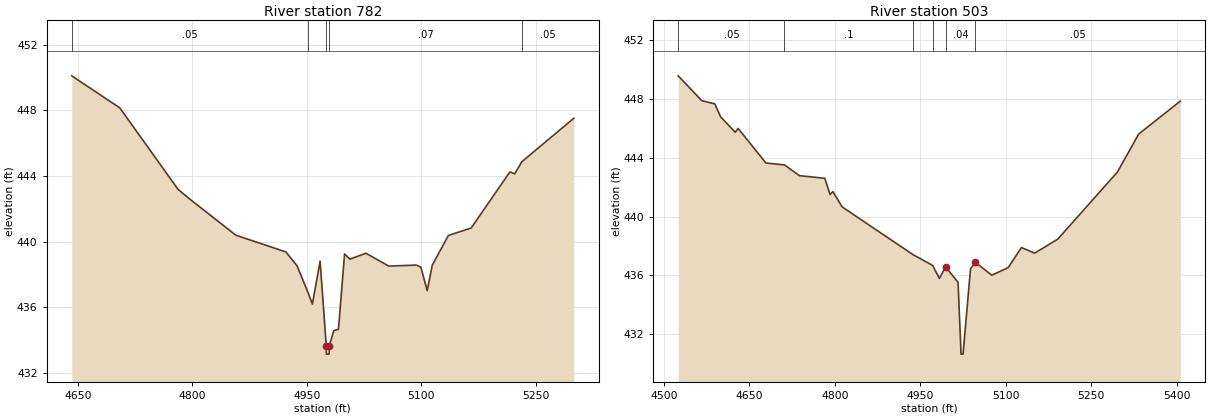
Type RM Length L Ch R = 1 ,782     ,279,279,279
BEGIN DESCRIPTION:
Mapping XS 92629297
END DESCRIPTION:
XS GIS Cut Line= 3
       2739783.6       6897775.8      2740126.43      6897726.83
      2740385.71      6897552.94
#Sta/Elev= 30
  4641.7   450.1  4704.7  448.15  4781.1  443.19  4795.6  442.63  4856.9   440.4
  4922.6  439.38  4937.1  438.54  4951.4  436.93  4957.3  436.21  4967.4  438.82
  4975.5  433.66  4975.7  433.16  4979.2  433.16  4979.5  433.66  4985.3  434.59
  4991.5  434.68  4999.5  439.26  5006.5  438.94  5027.5   439.3  5057.5  438.52
  5093.5  438.58  5099.6  438.45  5107.9  437.03  5114.5  438.57  5135.6  440.38
  5165.6  440.84  5216.3  444.25  5222.6  444.13    5232  444.87  5300.2  447.52
#Mann= 5 ,-1 , 0
  4641.7     .05       0  4951.4     .07       0  4975.5     .05       0
  4979.5     .07       0    5232     .05       0
Bank Sta=4975.5,4979.5
XS Rating Curve= 0 ,0
Exp/Cntr=0.3,0.1

Type RM Length L Ch R = 1 ,503     ,0,0,0
BEGIN DESCRIPTION:
Britton T1 1.0
END DESCRIPTION:
XS GIS Cut Line= 3
      2739852.73      6897888.29      2740287.53       6897966.2
      2740465.24      6897564.26
#Sta/Elev= 30
  4525.2  449.58  4566.5  447.89  4589.5  447.67  4599.6  446.79  4625.3  445.74
  4630.4     446  4679.1  443.65  4711.7  443.52  4737.9  442.79  4782.5  442.61
  4791.6  441.51  4796.7   441.7    4813  440.66  4937.2  437.42  4971.8  436.68
  4983.5   435.8  4994.5  436.58  5016.3  435.54  5021.6  430.65  5025.1  430.65
  5038.2  436.46  5046.7  436.89  5075.5  436.02  5104.2  436.53  5127.5   437.9
  5150.8  437.52  5191.3  438.47  5296.1  443.04  5333.4  445.62  5406.4  447.86
#Mann= 6 ,-1 , 0
  4525.2     .05       0  4711.7      .1       0  4937.2     .05       0
  4971.8     .07       0  4994.5     .04       0  5046.7     .05       0
Bank Sta=4994.5,5046.7
XS Rating Curve= 0 ,0
Exp/Cntr=0.3,0.1

Chan Stop Cuts=-1
Use User Specified Reach Order=0
Composite Channel Slope=5