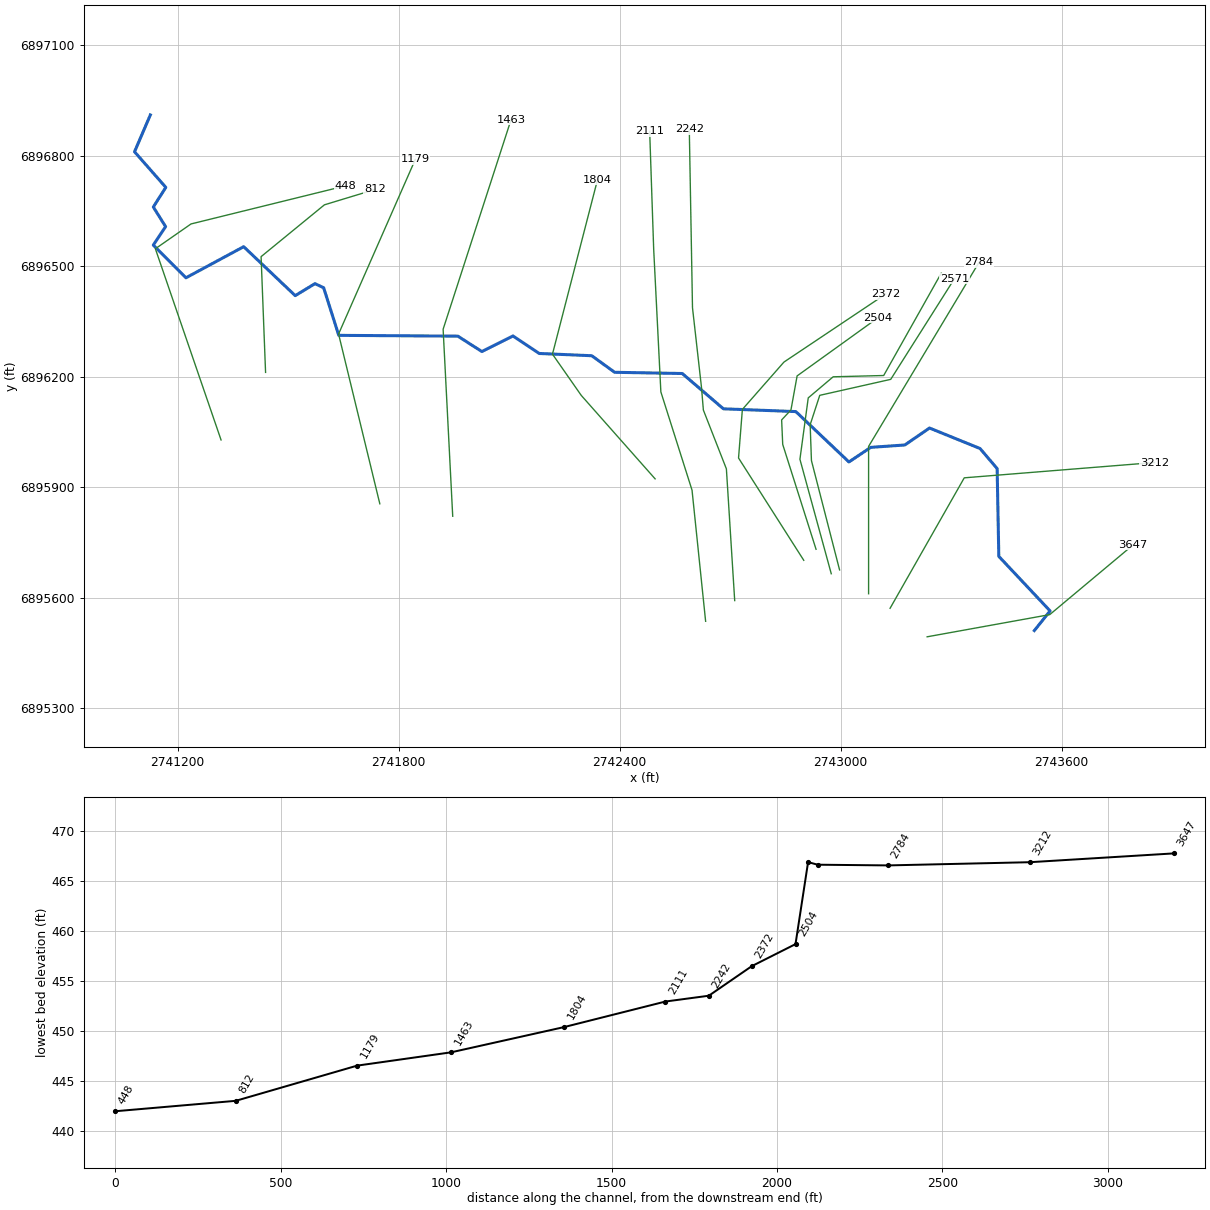
--- Britton T2.prj (project) ---

Proj Title=Britton T2 Base Level Engineering
Current Plan=p01
Default Exp/Contr=0.3,0.1
English Units
Geom File=g01
Flow File=f01
Plan File=p01
BEGIN DESCRIPTION:
Britton T2
END DESCRIPTION:

--- Britton T2.p01 (plan) ---

Plan Title=Multiple Run
Short Identifier=Multiple
Geom File=g01
Flow File=f01
Subcritical Flow
K Sum by GR= 0
Std Step Tol= 0.01
Critical Tol= 0.01
Num of Std Step Trials= 20
Max Error Tol= 0.3
Flow Tol Ratio= 0.001
Split Flow NTrial= 30
Split Flow Tol= 0.02
Split Flow Ratio= 0.02
Log Output Level= 0
Friction Slope Method= 1
Unsteady Friction Slope Method= 2
Unsteady Bridges Friction Slope Method= 1
Parabolic Critical Depth
Global Vel Dist=  1 , 1 , 1
Global Log Level= 0
CheckData=True
Encroach Param= -1, 0, 0, 0
BEGIN DESCRIPTION:
Multiple Run
END DESCRIPTION:

--- Britton T2.f01 (steady flow) ---

Flow Title=Multiple
Number of Profiles=7
Profile Names=10-year,25-year,50-year,1pct_min,100-year,1pct_plu,500-year
River Rch & RM= Britton T2,Reach-1,3647
     279     357     419     245     488     974     663
Boundary for River Rch & Prof#=Britton T2,Reach-1,1
Up Type=0
Dn Type=3
Dn Slope=0.005
Boundary for River Rch & Prof#=Britton T2,Reach-1,2
Up Type=0
Dn Type=3
Dn Slope=0.005
Boundary for River Rch & Prof#=Britton T2,Reach-1,3
Up Type=0
Dn Type=3
Dn Slope=0.005
Boundary for River Rch & Prof#=Britton T2,Reach-1,4
Up Type=0
Dn Type=3
Dn Slope=0.005
Boundary for River Rch & Prof#=Britton T2,Reach-1,5
Up Type=0
Dn Type=3
Dn Slope=0.005
Boundary for River Rch & Prof#=Britton T2,Reach-1,6
Up Type=0
Dn Type=3
Dn Slope=0.005
Boundary for River Rch & Prof#=Britton T2,Reach-1,7
Up Type=0
Dn Type=3
Dn Slope=0.005

--- Britton T2.g01 (geometry) ---

Geom Title=Existing Conditions

River Reach=Britton T2,Reach-1
Reach XY= 30
      2743526.00      6895511.00      2743568.75      6895564.33
      2743429.54      6895712.46      2743425.01      6895950.72
      2743378.58      6896005.29      2743241.40      6896060.91
      2743174.41      6896014.88      2743081.89      6896008.44
      2743022.58      6895968.79      2742878.45      6896105.54
      2742681.86      6896113.07      2742570.14      6896208.93
      2742386.51      6896212.22      2742324.43      6896257.21
      2742181.93      6896263.30      2742110.58      6896310.85
      2742026.01      6896268.59      2741960.84      6896310.34
      2741637.53      6896312.51      2741596.48      6896441.82
      2741572.87      6896452.92      2741519.34      6896420.31
      2741379.41      6896553.23      2741222.56      6896468.77
      2741133.98      6896557.64      2741167.44      6896607.67
      2741134.03      6896661.00      2741167.99      6896714.33
      2741083.07      6896810.93      2741126.00      6896911.00

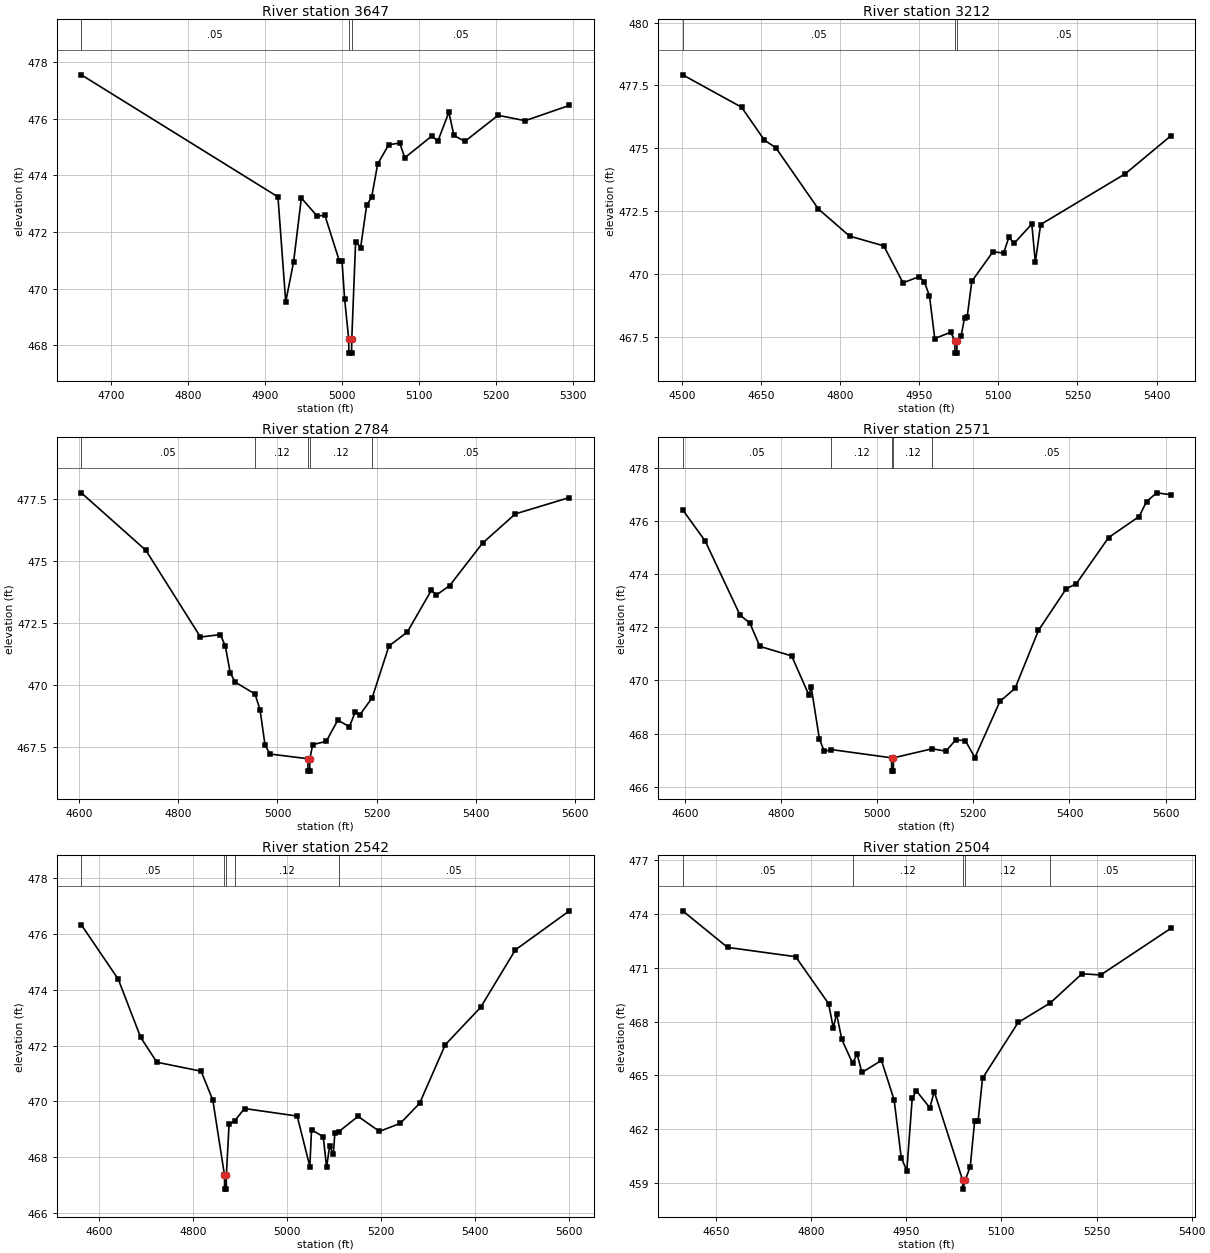
Type RM Length L Ch R = 1,3647,435,435,435
BEGIN DESCRIPTION:
Britton T2 6.0
END DESCRIPTION:
XS GIS Cut Line= 3
      2743235.02      6895494.11      2743567.81      6895554.33
      2743794.19      6895743.64
#Sta/Elev= 30
  4661.8  477.55  4916.9  473.24  4927.0  469.53  4937.2  470.94  4947.3  473.20
  4967.7  472.56  4977.8  472.59  4996.5  470.98  5000.0  470.98  5003.4  469.64
  5008.7  468.22  5008.9  467.72  5012.4  467.72  5012.7  468.22  5017.7  471.66
  5024.2  471.45  5032.0  472.94  5038.5  473.23  5046.3  474.40  5060.6  475.08
  5074.9  475.14  5081.5  474.62  5116.6  475.39  5124.4  475.21  5138.7  476.23
  5145.2  475.41  5159.5  475.20  5202.5  476.12  5237.6  475.93  5295.1  476.47
#Mann=3,-1,0
  4661.8    0.05       0  5008.7    0.04       0  5012.7    0.05       0
Bank Sta=5008.7,5012.7
Exp/Cntr=0.3,0.1

Type RM Length L Ch R = 1,3212,428,428,428
BEGIN DESCRIPTION:
Mapping XS 2c285fca
END DESCRIPTION:
XS GIS Cut Line= 3
      2743134.34      6895571.50      2743335.75      6895925.71
      2743852.01      6895967.29
#Sta/Elev= 30
  4501.6  477.92  4613.3  476.63  4656.5  475.32  4678.1  475.02  4758.8  472.58
  4818.0  471.50  4882.8  471.11  4919.3  469.64  4949.4  469.88  4959.5  469.69
  4969.5  469.12  4979.5  467.42  5009.6  467.67  5017.7  467.34  5017.9  466.84
  5021.4  466.84  5021.7  467.34  5029.7  467.54  5036.0  468.25  5041.0  468.29
  5049.8  469.70  5089.9  470.88  5110.0  470.82  5120.0  471.45  5130.0  471.21
  5163.5  471.98  5170.2  470.46  5180.2  471.96  5340.7  473.98  5427.0  475.49
#Mann=3,-1,0
  4501.6    0.05       0  5017.7    0.05       0  5021.7    0.05       0
Bank Sta=5017.7,5021.7
Exp/Cntr=0.3,0.1

Type RM Length L Ch R = 1,2784,213,213,213
BEGIN DESCRIPTION:
Britton T2 5.0
END DESCRIPTION:
XS GIS Cut Line= 3
      2743076.00      6895611.04      2743076.00      6896011.00
      2743376.02      6896511.04
#Sta/Elev= 30
  4604.9  477.75  4734.9  475.43  4844.9  471.93  4884.9  472.03  4894.9  471.57
  4904.9  470.48  4914.9  470.11  4954.8  469.63  4964.9  468.99  4974.9  467.57
  4984.9  467.21  5061.2  467.02  5061.4  466.52  5064.9  466.52  5065.2  467.02
  5070.9  467.59  5098.2  467.72  5121.5  468.58  5144.8  468.31  5156.5  468.90
  5166.2  468.80  5190.7  469.48  5224.5  471.57  5261.4  472.13  5310.0  473.82
  5319.7  473.62  5346.9  474.01  5413.0  475.72  5479.1  476.90  5588.0  477.56
#Mann=5,-1,0
  4604.9    0.05       0  4954.8    0.12       0  5061.2    0.07       0
  5065.2    0.12       0  5190.7    0.05       0
Bank Sta=5061.2,5065.2
Exp/Cntr=0.3,0.1

Type RM Length L Ch R = 1,2571,29,29,29
BEGIN DESCRIPTION:
Mapping XS c8293966
END DESCRIPTION:
XS GIS Cut Line= 6
      2742997.22      6895675.67      2742920.82      6895972.58
      2742917.35      6896069.81      2742943.39      6896149.67
      2743136.10      6896193.07      2743309.26      6896466.68
#Sta/Elev= 30
  4595.8  476.41  4642.6  475.24  4714.9  472.46  4735.5  472.15  4756.2  471.28
  4822.4  470.92  4857.9  469.46  4863.1  469.74  4880.1  467.79  4890.4  467.33
  4905.0  467.40  5030.1  467.09  5030.3  466.59  5033.8  466.59  5034.1  467.09
  5114.4  467.43  5143.2  467.34  5163.2  467.76  5183.3  467.74  5203.3  467.10
  5255.3  469.21  5286.8  469.70  5335.5  471.88  5393.1  473.44  5414.5  473.64
  5481.3  475.37  5544.8  476.16  5560.1  476.72  5581.3  477.05  5610.6  476.98
#Mann=5,-1,0
  4595.8    0.05       0  4905.0    0.12       0  5030.1    0.07       0
  5034.1    0.12       0  5114.4    0.05       0
Bank Sta=5030.1,5034.1
Exp/Cntr=0.3,0.1

Type RM Length L Ch R = 1,2542,38,38,38
BEGIN DESCRIPTION:
Mapping XS 25052203
END DESCRIPTION:
XS GIS Cut Line= 6
      2742974.65      6895665.27      2742889.57      6895976.06
      2742912.14      6896142.72      2742979.85      6896200.02
      2743117.00      6896203.49      2743273.23      6896481.24
#Sta/Elev= 30
  4562.7  476.33  4641.2  474.38  4689.0  472.29  4723.5  471.40  4817.5  471.08
  4842.5  470.04  4867.3  467.35  4867.6  466.85  4871.1  466.85  4871.3  467.35
  4877.0  469.17  4889.5  469.31  4909.9  469.74  5022.0  469.47  5048.9  467.66
  5052.5  468.98  5077.4  468.73  5084.5  467.63  5090.8  468.38  5099.0  468.12
  5102.1  468.87  5110.4  468.91  5151.5  469.46  5196.9  468.92  5241.5  469.21
  5282.5  469.93  5337.1  472.03  5412.3  473.37  5486.2  475.43  5601.2  476.83
#Mann=5,-1,0
  4562.7    0.05       0  4867.3    0.07       0  4871.3    0.05       0
  4889.5    0.12       0  5110.4    0.05       0
Bank Sta=4867.3,4871.3
Exp/Cntr=0.3,0.1

Type RM Length L Ch R = 1,2504,132,132,132
BEGIN DESCRIPTION:
Mapping XS 48e15bea
END DESCRIPTION:
XS GIS Cut Line= 6
      2742933.32      6895731.77      2742842.83      6896016.51
      2742839.92      6896082.94      2742865.23      6896110.04
      2742881.94      6896202.40      2743101.30      6896360.15
#Sta/Elev= 30
  4597.7  474.18  4668.4  472.14  4775.7  471.62  4827.7  469.00  4835.1  467.65
  4840.3  468.43  4848.6  467.00  4865.6  465.67  4872.6  466.19  4880.2  465.16
  4911.0  465.83  4931.0  463.63  4942.2  460.41  4951.0  459.68  4959.5  463.71
  4965.9  464.14  4987.3  463.19  4994.2  464.09  5039.0  459.15  5039.3  458.65
  5043.0  459.15  5051.0  459.91  5057.9  462.44  5063.3  462.44  5070.4  464.84
  5126.5  467.95  5177.2  469.04  5227.1  470.67  5256.6  470.60  5367.1  473.20
#Mann=5,-1,0
  4597.7    0.05       0  4865.6    0.12       0  5039.0    0.07       0
  5043.0    0.12       0  5177.2    0.05       0
Bank Sta=5039,5043
Exp/Cntr=0.3,0.1

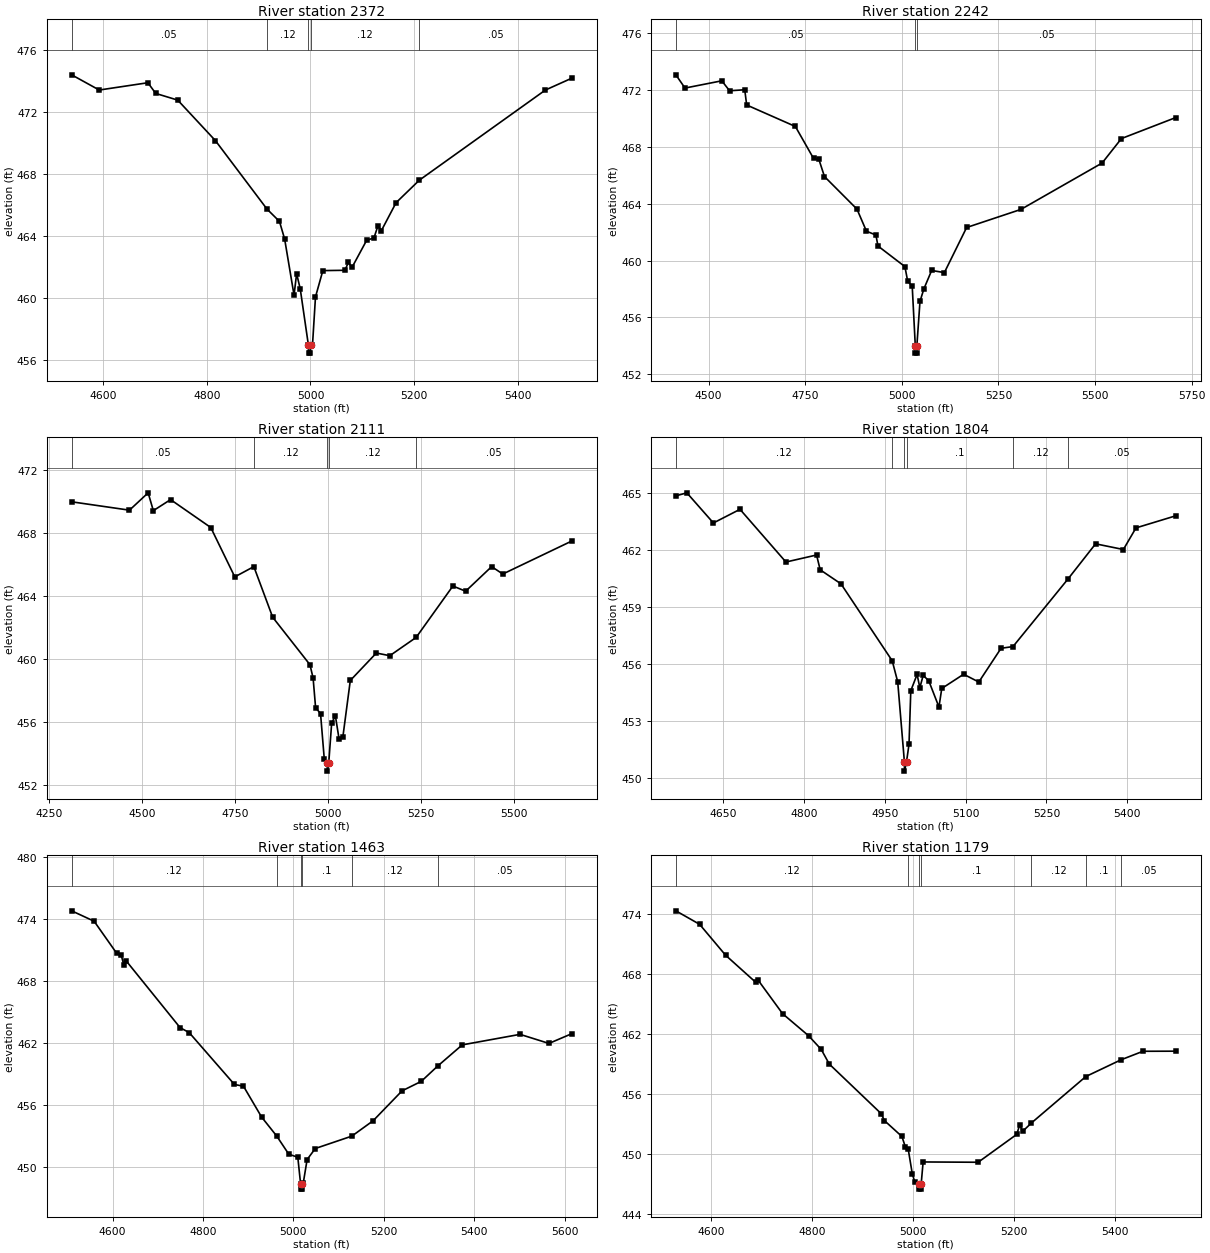
Type RM Length L Ch R = 1,2372,130,130,130
BEGIN DESCRIPTION:
Mapping XS 6413bf5e
END DESCRIPTION:
XS GIS Cut Line= 5
      2742899.97      6895701.78      2742722.90      6895979.53
      2742733.32      6896111.47      2742846.17      6896239.95
      2743122.44      6896424.71
#Sta/Elev= 30
  4539.1  474.39  4592.3  473.41  4686.2  473.88  4701.4  473.19  4743.8  472.76
  4816.5  470.15  4916.0  465.74  4940.2  464.94  4950.2  463.80  4968.3  460.19
  4973.3  461.57  4980.3  460.59  4996.1  456.95  4996.3  456.45  4999.8  456.45
  5000.1  456.95  5003.9  456.95  5009.7  460.07  5023.9  461.77  5066.6  461.79
  5073.3  462.31  5080.1  461.97  5108.4  463.72  5122.6  463.88  5130.2  464.65
  5136.8  464.34  5165.3  466.15  5210.2  467.60  5453.5  473.41  5504.2  474.17
#Mann=5,-1,0
  4539.1    0.05       0  4916.0    0.12       0  4996.1    0.07       0
  5000.1    0.12       0  5210.2    0.05       0
Bank Sta=4996.1,5000.1
Exp/Cntr=0.3,0.1

Type RM Length L Ch R = 1,2242,131,131,131
BEGIN DESCRIPTION:
Mapping XS d3679865
END DESCRIPTION:
XS GIS Cut Line= 6
      2742712.49      6895592.39      2742689.92      6895950.02
      2742627.42      6896109.74      2742622.21      6896172.24
      2742597.90      6896387.52      2742589.22      6896871.92
#Sta/Elev= 30
  4415.5  473.05  4439.1  472.12  4534.4  472.63  4554.4  471.93  4593.7  472.00
  4598.7  470.93  4724.7  469.42  4771.8  467.17  4785.6  467.10  4800.0  465.90
  4884.1  463.61  4908.6  462.06  4933.1  461.79  4938.4  461.02  5008.1  459.57
  5015.4  458.53  5027.0  458.21  5035.0  453.99  5035.3  453.49  5038.8  453.49
  5039.0  453.99  5047.1  457.12  5057.1  458.00  5077.3  459.30  5110.2  459.15
  5167.8  462.32  5308.2  463.59  5518.3  466.85  5568.3  468.57  5709.2  470.05
#Mann=3,-1,0
  4415.5    0.05       0  5035.0    0.05       0  5039.0    0.05       0
Bank Sta=5035,5039
Exp/Cntr=0.3,0.1

Type RM Length L Ch R = 1,2111,307,307,307
BEGIN DESCRIPTION:
Mapping XS 313f1bd7
END DESCRIPTION:
XS GIS Cut Line= 5
      2742633.55      6895536.26      2742596.66      6895892.12
      2742512.02      6896159.04      2742492.49      6896547.50
      2742481.65      6896866.28
#Sta/Elev= 30
  4309.9  469.99  4465.5  469.46  4515.7  470.56  4529.7  469.43  4576.1  470.13
  4684.3  468.36  4748.9  465.23  4800.2  465.88  4850.9  462.67  4951.2  459.66
  4959.7  458.81  4966.4  456.93  4979.7  456.56  4989.7  453.69  4997.7  453.41
  4998.0  452.91  5001.7  453.41  5009.7  455.97  5019.7  456.41  5029.7  454.93
  5039.8  455.08  5059.8  458.66  5129.9  460.40  5166.1  460.23  5237.0  461.39
  5335.9  464.65  5370.2  464.32  5440.2  465.88  5470.2  465.41  5655.6  467.50
#Mann=5,-1,0
  4309.9    0.05       0  4800.2    0.12       0  4997.7    0.07       0
  5001.7    0.12       0  5237.0    0.05       0
Bank Sta=4997.7,5001.7
Exp/Cntr=0.3,0.1

Type RM Length L Ch R = 1,1804,341,341,341
BEGIN DESCRIPTION:
Mapping XS 42d03a7f
END DESCRIPTION:
XS GIS Cut Line= 4
      2742496.43      6895922.90      2742295.88      6896149.49
      2742217.75      6896261.47      2742340.14      6896735.39
#Sta/Elev= 30
  4561.9  464.87  4582.3  465.03  4631.6  463.44  4681.0  464.16  4766.3  461.38
  4823.2  461.75  4829.9  460.97  4868.5  460.23  4963.7  456.17  4973.9  455.06
  4986.3  450.85  4986.5  450.35  4990.3  450.85  4994.9  451.77  4998.2  454.59
  5009.9  455.45  5015.0  454.75  5021.2  455.40  5031.5  455.12  5050.5  453.73
  5055.7  454.71  5096.3  455.46  5124.5  455.05  5165.8  456.83  5188.0  456.92
  5289.7  460.47  5341.4  462.34  5393.0  462.04  5416.4  463.18  5490.5  463.82
#Mann=6,-1,0
  4561.9    0.12       0  4963.7     0.1       0  4986.3    0.07       0
  4990.3     0.1       0  5188.0    0.12       0  5289.7    0.05       0
Bank Sta=4986.3,4990.3
Exp/Cntr=0.3,0.1

Type RM Length L Ch R = 1,1463,284,284,284
BEGIN DESCRIPTION:
Mapping XS 958b5406
END DESCRIPTION:
XS GIS Cut Line= 3
      2741946.92      6895821.37      2741920.88      6896329.18
      2742105.21      6896897.77
#Sta/Elev= 30
  4509.4  474.82  4559.1  473.81  4609.2  470.69  4619.2  470.49  4624.6  469.61
  4629.6  469.99  4749.3  463.49  4769.4  463.01  4869.5  457.98  4889.5  457.81
  4929.6  454.82  4963.0  452.98  4989.7  451.22  5009.7  450.92  5015.9  448.33
  5016.1  447.83  5019.6  447.83  5019.9  448.33  5021.7  448.40  5030.3  450.70
  5048.4  451.77  5129.2  452.97  5176.3  454.46  5240.3  457.36  5282.8  458.28
  5319.0  459.76  5373.5  461.82  5501.4  462.84  5565.3  461.96  5615.6  462.90
#Mann=6,-1,0
  4509.4    0.12       0  4963.0     0.1       0  5015.9    0.07       0
  5019.9     0.1       0  5129.2    0.12       0  5319.0    0.05       0
Bank Sta=5015.9,5019.9
Exp/Cntr=0.3,0.1

Type RM Length L Ch R = 1,1179,367,367,367
BEGIN DESCRIPTION:
Mapping XS 27b4ea2c
END DESCRIPTION:
XS GIS Cut Line= 3
      2741749.01      6895855.21      2741637.02      6896316.16
      2741845.36      6896790.14
#Sta/Elev= 30
  4529.5  474.36  4576.6  473.01  4628.1  469.92  4687.6  467.22  4692.7  467.42
  4741.3  464.06  4792.7  461.86  4818.0  460.48  4833.9  459.02  4936.8  454.06
  4943.3  453.36  4978.0  451.77  4985.1  450.69  4990.4  450.54  4998.5  448.06
  5003.8  447.17  5012.2  447.00  5012.4  446.50  5015.9  446.50  5016.2  447.00
  5020.1  449.22  5129.3  449.19  5205.8  451.98  5211.9  452.96  5217.3  452.27
  5234.9  453.12  5342.9  457.77  5412.9  459.45  5456.3  460.30  5521.6  460.31
#Mann=7,-1,0
  4529.5    0.12       0  4990.4     0.1       0  5012.2    0.07       0
  5016.2     0.1       0  5234.9    0.12       0  5342.9     0.1       0
  5412.9    0.05       0
Bank Sta=5012.2,5016.2
Exp/Cntr=0.3,0.1

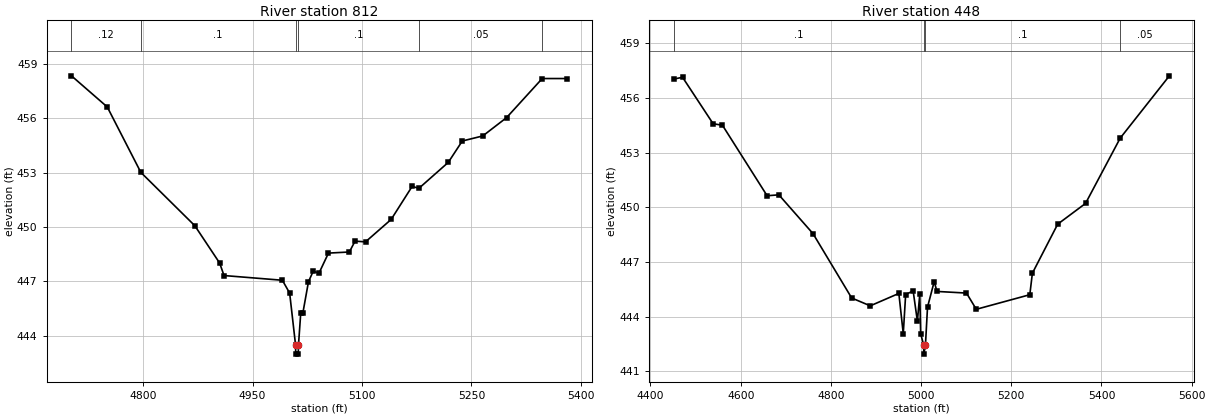
Type RM Length L Ch R = 1,812,364,364,364
BEGIN DESCRIPTION:
Mapping XS e0748807
END DESCRIPTION:
XS GIS Cut Line= 4
      2741438.82      6896211.98      2741426.66      6896526.23
      2741598.54      6896666.86      2741735.69      6896708.52
#Sta/Elev= 30
  4701.6  458.35  4750.7  456.63  4796.7  453.02  4870.8  450.07  4904.8  448.01
  4910.8  447.32  4990.8  447.06  5000.8  446.35  5008.9  443.48  5009.1  442.98
  5012.6  442.98  5012.9  443.48  5016.0  445.25  5018.9  445.25  5026.6  446.98
  5033.1  447.56  5041.0  447.45  5054.0  448.56  5082.6  448.62  5090.5  449.22
  5104.8  449.18  5140.0  450.42  5168.7  452.24  5178.1  452.14  5218.3  453.57
  5237.5  454.75  5265.6  455.03  5298.2  456.04  5347.1  458.20  5381.5  458.20
#Mann=6,-1,0
  4701.6    0.12       0  4796.7     0.1       0  5008.9    0.07       0
  5012.9     0.1       0  5178.1    0.05       0  5347.1     0.1       0
Bank Sta=5008.9,5012.9
Exp/Cntr=0.3,0.1

Type RM Length L Ch R = 1,448,0,0,0
BEGIN DESCRIPTION:
Britton T2 1.0
END DESCRIPTION:
XS GIS Cut Line= 4
      2741317.98      6896028.49      2741139.64      6896547.61
      2741236.46      6896614.99      2741656.51      6896718.59
#Sta/Elev= 30
  4451.1  457.03  4471.1  457.13  4538.9  454.58  4559.5  454.50  4658.6  450.63
  4684.6  450.68  4760.4  448.55  4846.1  445.02  4887.3  444.59  4950.7  445.27
  4960.5  443.06  4965.8  445.21  4982.4  445.41  4991.8  443.75  4997.1  445.22
  4999.1  443.06  5005.7  442.44  5006.0  441.94  5009.7  442.44  5014.3  444.52
  5029.1  445.92  5035.2  445.38  5100.7  445.29  5122.4  444.40  5241.1  445.20
  5246.8  446.38  5302.9  449.07  5364.7  450.21  5441.5  453.79  5550.6  457.21
#Mann=4,-1,0
  4451.1     0.1       0  5005.7    0.07       0  5009.7     0.1       0
  5441.5    0.05       0
Bank Sta=5005.7,5009.7
Exp/Cntr=0.3,0.1

Chan Stop Cuts=-1