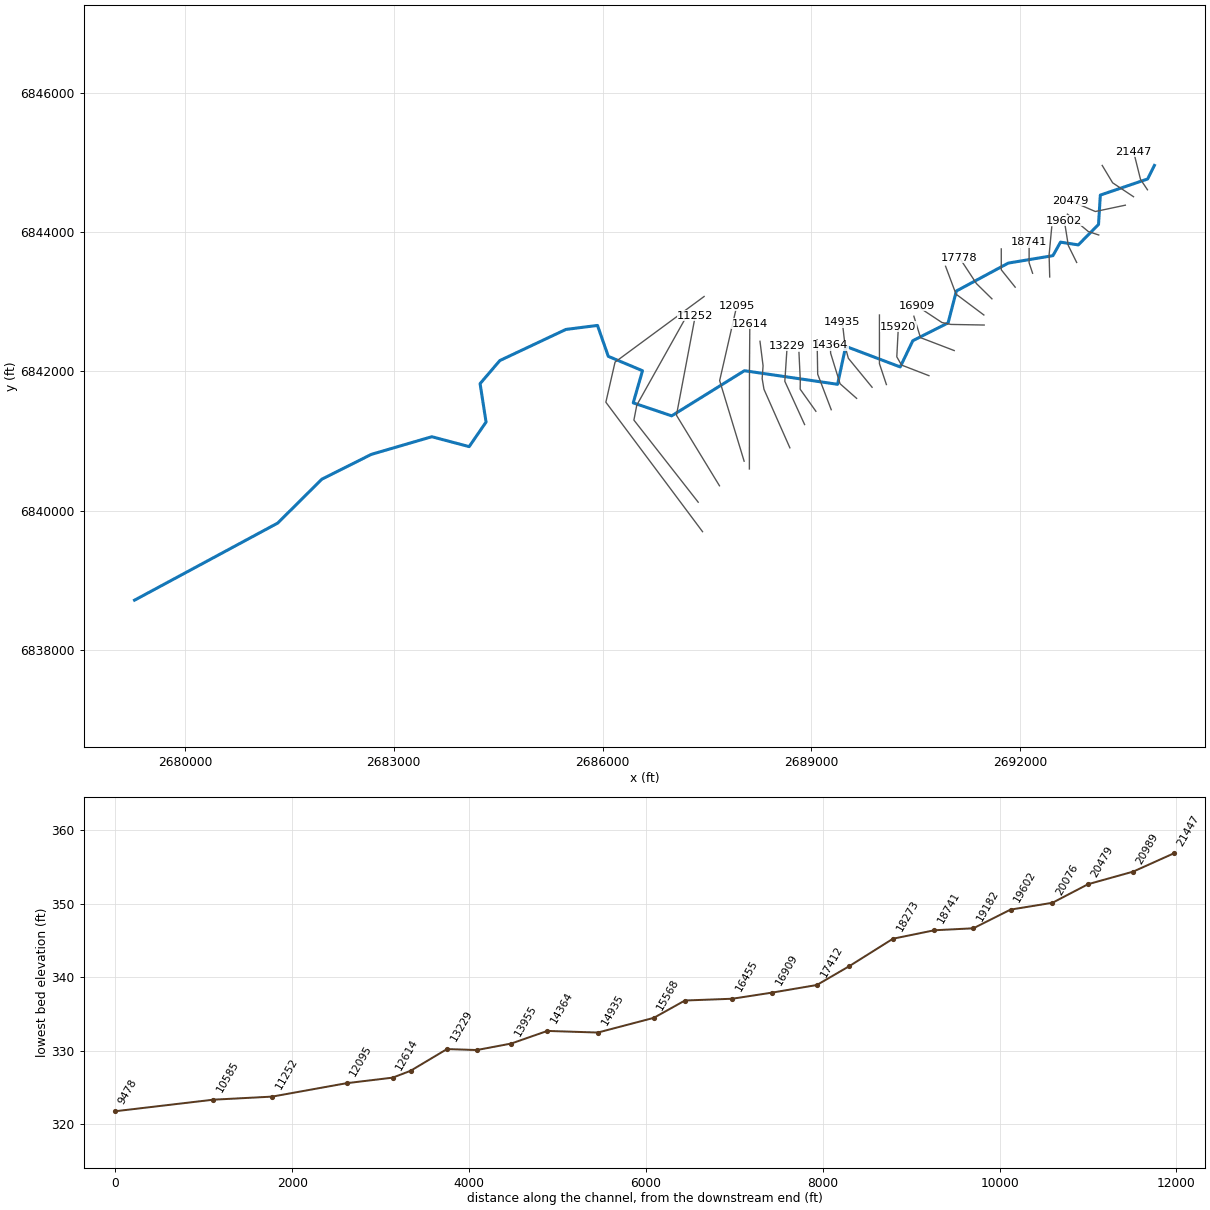
--- CCT1.prj (project) ---

Proj Title=CCT1 Base Level Engineering
Current Plan=p01
Default Exp/Contr=0.3,0.1
English Units
Geom File=g01
Flow File=f01
Plan File=p01
BEGIN DESCRIPTION:
CCT1
END DESCRIPTION:

--- CCT1.p01 (plan) ---

Plan Title=Multiple Run
Short Identifier=Multiple
Geom File=g01
Flow File=f01
Subcritical Flow
K Sum by GR= 0
Std Step Tol= 0.01
Critical Tol= 0.01
Num of Std Step Trials= 20
Max Error Tol= 0.3
Flow Tol Ratio= 0.001
Split Flow NTrial= 30
Split Flow Tol= 0.02
Split Flow Ratio= 0.02
Log Output Level= 0
Friction Slope Method= 1
Unsteady Friction Slope Method= 2
Unsteady Bridges Friction Slope Method= 1
Parabolic Critical Depth
Global Vel Dist=  1 , 1 , 1
Global Log Level= 0
CheckData=True
Encroach Param= -1, 0, 0, 0
BEGIN DESCRIPTION:
Multiple Run
END DESCRIPTION:

--- CCT1.f01 (steady flow) ---

Flow Title=Multiple
Number of Profiles=7
Profile Names=10-year,25-year,50-year,1pct_min,100-year,1pct_plu,500-year
River Rch & RM= CCT1,Reach-1,21447
     552     729     868     513    1023    2041    1420
River Rch & RM= CCT1,Reach-1,17778
     762    1029    1244     745    1487    2966    2124
River Rch & RM= CCT1,Reach-1,15920
    1006    1374    1674    1009    2013    4017    2913
Boundary for River Rch & Prof#=CCT1,Reach-1,1
Up Type=0
Dn Type=3
Dn Slope=0.005
Boundary for River Rch & Prof#=CCT1,Reach-1,2
Up Type=0
Dn Type=3
Dn Slope=0.005
Boundary for River Rch & Prof#=CCT1,Reach-1,3
Up Type=0
Dn Type=3
Dn Slope=0.005
Boundary for River Rch & Prof#=CCT1,Reach-1,4
Up Type=0
Dn Type=3
Dn Slope=0.005
Boundary for River Rch & Prof#=CCT1,Reach-1,5
Up Type=0
Dn Type=3
Dn Slope=0.005
Boundary for River Rch & Prof#=CCT1,Reach-1,6
Up Type=0
Dn Type=3
Dn Slope=0.005
Boundary for River Rch & Prof#=CCT1,Reach-1,7
Up Type=0
Dn Type=3
Dn Slope=0.005

--- CCT1.g01 (geometry) ---

Geom Title=Existing Conditions

River Reach=CCT1,Reach-1
Reach XY= 30
      2693926.00      6844961.00      2693828.71      6844766.28
      2693149.01      6844534.47      2693122.93      6844112.43
      2692832.83      6843818.80      2692577.42      6843857.96
      2692467.54      6843663.62      2691827.50      6843557.39
      2691081.25      6843155.56      2690962.48      6842697.59
      2690455.53      6842441.50      2690274.61      6842064.03
      2689491.88      6842360.49      2689374.77      6841814.43
      2688036.44      6842009.96      2686991.42      6841361.03
      2686439.52      6841547.62      2686572.52      6842009.74
      2686081.18      6842216.44      2685926.00      6842661.00
      2685472.33      6842603.30      2684523.11      6842155.85
      2684239.61      6841824.21      2684325.40      6841271.62
      2684082.45      6840918.64      2683546.03      6841060.93
      2682677.55      6840807.25      2681966.32      6840450.24
      2681332.06      6839819.14      2679276.00      6838711.00

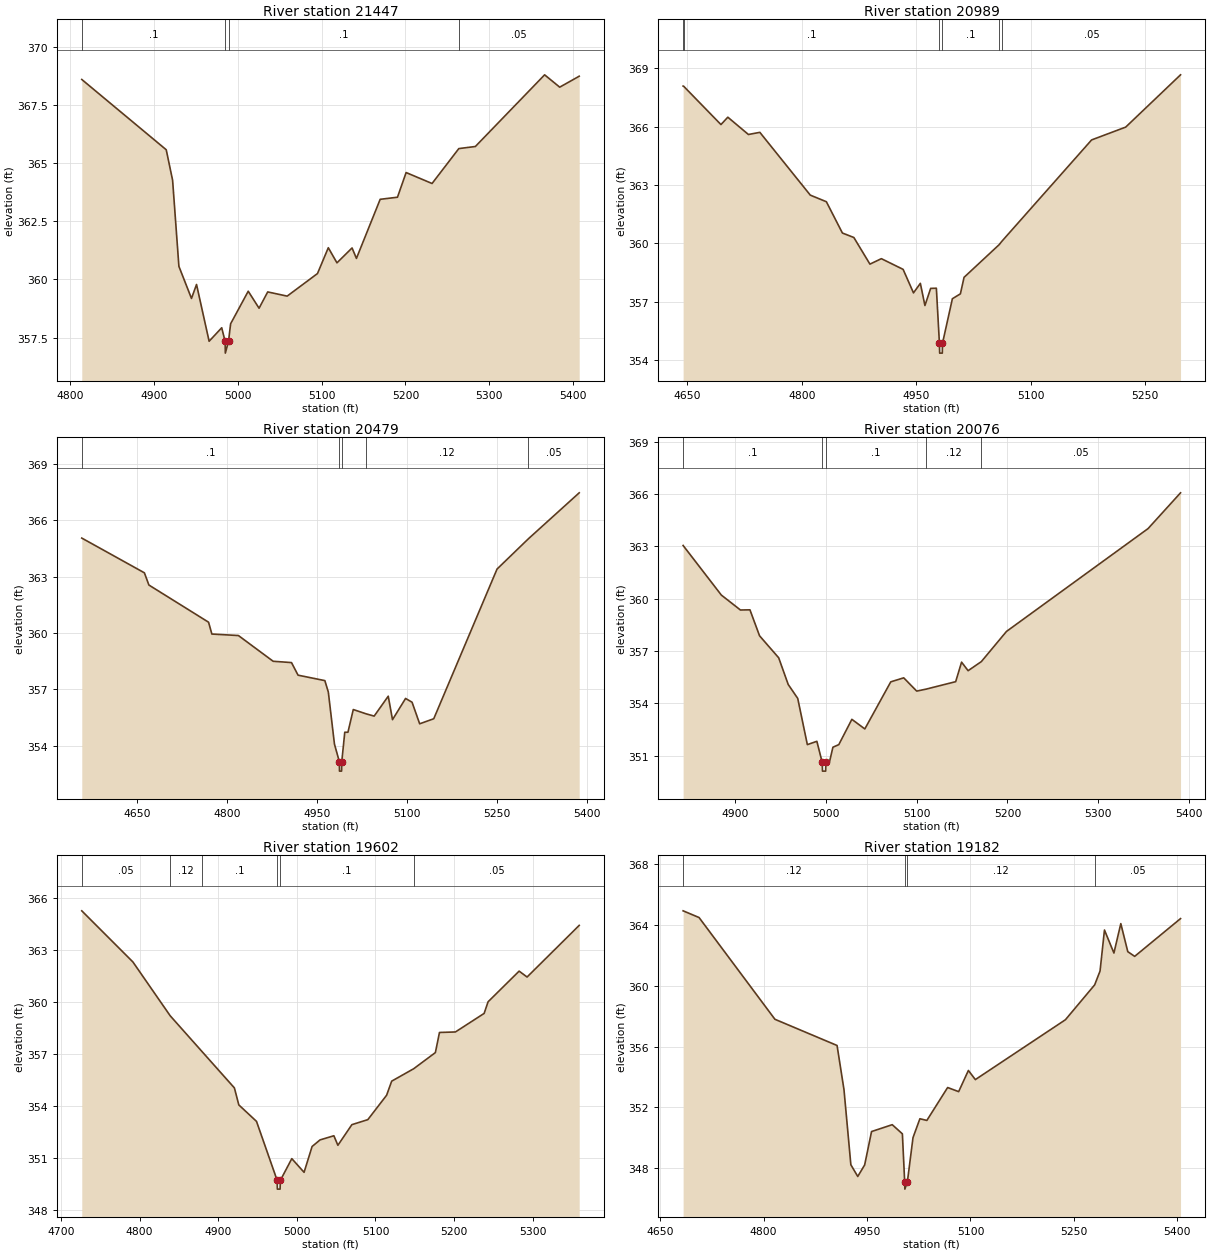
Type RM Length L Ch R = 1,21447,458,458,458
BEGIN DESCRIPTION:
CCT1 32.0
END DESCRIPTION:
XS GIS Cut Line= 3
      2693826.00      6844611.01      2693726.00      6844761.00
      2693626.00      6845161.02
#Sta/Elev= 30
  4814.4  368.59  4915.0  365.57  4922.6  364.26  4930.1  360.56  4945.1  359.18
  4951.1  359.78  4966.1  357.34  4981.1  357.92  4985.2  357.33  4985.4  356.83
  4989.2  357.33  4991.7  358.09  5012.7  359.49  5025.6  358.76  5035.9  359.46
  5059.1  359.28  5095.2  360.25  5108.1  361.36  5118.4  360.71  5136.4  361.35
  5141.6  360.90  5169.9  363.44  5190.5  363.53  5200.8  364.59  5231.7  364.12
  5263.6  365.62  5283.3  365.71  5365.8  368.79  5383.8  368.26  5407.0  368.73
#Mann=4,-1,0
  4814.4     0.1       0  4985.2    0.07       0  4989.2     0.1       0
  5263.6    0.05       0
Bank Sta=4985.2,4989.2
Exp/Cntr=0.3,0.1

Type RM Length L Ch R = 1,20989,510,510,510
BEGIN DESCRIPTION:
CCT1 31.0
END DESCRIPTION:
XS GIS Cut Line= 3
      2693625.99      6844511.01      2693326.00      6844711.00
      2693175.99      6844961.01
#Sta/Elev= 30
  4644.4  368.09  4644.9  368.09  4694.0  366.11  4703.0  366.49  4730.0  365.60
  4745.0  365.71  4811.1  362.48  4832.2  362.14  4853.2  360.53  4868.2  360.30
  4889.3  358.93  4904.3  359.21  4932.8  358.66  4946.4  357.45  4955.4  357.94
  4961.4  356.80  4968.9  357.68  4976.4  357.69  4980.4  354.85  4980.7  354.35
  4984.2  354.35  4984.4  354.85  4997.4  357.15  5007.9  357.40  5012.7  358.25
  5058.7  359.93  5062.6  360.12  5179.9  365.32  5224.6  365.98  5296.5  368.67
#Mann=6,-1,0
  4644.4    0.05       0  4644.9     0.1       0  4980.4    0.07       0
  4984.4     0.1       0  5058.7    0.12       0  5062.6    0.05       0
Bank Sta=4980.4,4984.4
Exp/Cntr=0.3,0.1

Type RM Length L Ch R = 1,20479,403,403,403
BEGIN DESCRIPTION:
Mapping XS 311de2bf
END DESCRIPTION:
XS GIS Cut Line= 3
      2693508.17      6844389.64      2693077.34      6844298.61
      2692720.21      6844452.96
#Sta/Elev= 30
  4558.0  365.05  4662.4  363.20  4669.9  362.55  4769.4  360.57  4774.9  359.94
  4819.2  359.86  4877.1  358.49  4907.7  358.42  4918.6  357.75  4963.3  357.46
  4969.1  356.85  4979.3  354.08  4987.5  353.14  4987.7  352.64  4991.2  352.64
  4991.5  353.14  4996.5  354.71  5001.8  354.71  5010.7  355.92  5032.2  355.69
  5045.5  355.57  5069.0  356.63  5076.1  355.38  5097.9  356.51  5108.7  356.31
  5121.4  355.16  5144.9  355.43  5250.4  363.40  5302.6  365.01  5387.4  367.46
#Mann=5,-1,0
  4558.0     0.1       0  4987.5    0.07       0  4991.5     0.1       0
  5032.2    0.12       0  5302.6    0.05       0
Bank Sta=4987.5,4991.5
Exp/Cntr=0.3,0.1

Type RM Length L Ch R = 1,20076,474,474,474
BEGIN DESCRIPTION:
CCT1 29.0
END DESCRIPTION:
XS GIS Cut Line= 3
      2693125.96      6843961.01      2692976.00      6844011.00
      2692675.98      6844261.01
#Sta/Elev= 30
  4842.3  363.05  4884.4  360.21  4905.5  359.35  4916.0  359.36  4926.6  357.87
  4947.7  356.61  4958.2  355.08  4968.7  354.28  4979.3  351.63  4989.8  351.82
  4995.7  350.61  4996.0  350.11  4999.5  350.11  4999.7  350.61  5003.6  350.61
  5007.5  351.48  5014.0  351.63  5028.4  353.08  5042.7  352.53  5071.3  355.23
  5085.6  355.46  5099.9  354.70  5110.1  354.81  5142.9  355.24  5149.4  356.36
  5156.6  355.87  5171.2  356.39  5198.9  358.12  5355.1  364.02  5390.9  366.07
#Mann=5,-1,0
  4842.3     0.1       0  4995.7    0.07       0  4999.7     0.1       0
  5110.1    0.12       0  5171.2    0.05       0
Bank Sta=4995.7,4999.7
Exp/Cntr=0.3,0.1

Type RM Length L Ch R = 1,19602,420,420,420
BEGIN DESCRIPTION:
Mapping XS 37184d90
END DESCRIPTION:
XS GIS Cut Line= 3
      2692809.02      6843566.32      2692689.25      6843809.33
      2692632.04      6844166.46
#Sta/Elev= 30
  4726.5  365.24  4791.5  362.29  4839.0  359.18  4879.0  357.14  4920.6  355.02
  4926.2  354.04  4948.7  353.09  4975.0  349.68  4975.2  349.18  4978.7  349.18
  4979.0  349.68  4993.6  350.94  5009.2  350.15  5019.4  351.64  5029.5  352.02
  5047.1  352.26  5052.2  351.71  5070.0  352.90  5090.3  353.19  5114.2  354.60
  5120.6  355.41  5148.7  356.13  5176.2  357.06  5181.4  358.22  5201.7  358.25
  5238.2  359.32  5243.2  359.99  5282.7  361.76  5292.8  361.42  5359.1  364.40
#Mann=6,-1,0
  4726.5    0.05       0  4839.0    0.12       0  4879.0     0.1       0
  4975.0    0.07       0  4979.0     0.1       0  5148.7    0.05       0
Bank Sta=4975,4979
Exp/Cntr=0.3,0.1

Type RM Length L Ch R = 1,19182,441,441,441
BEGIN DESCRIPTION:
Mapping XS a6246194
END DESCRIPTION:
XS GIS Cut Line= 3
      2692421.89      6843357.92      2692413.21      6843675.65
      2692451.29      6844077.20
#Sta/Elev= 30
  4683.4  364.91  4706.5  364.47  4816.5  357.79  4906.6  356.07  4916.6  353.18
  4926.6  348.24  4936.6  347.47  4946.6  348.23  4956.6  350.42  4986.6  350.87
  5001.3  350.27  5004.6  347.14  5004.9  346.64  5008.6  347.14  5016.7  350.02
  5026.7  351.26  5036.8  351.15  5066.9  353.31  5082.9  353.04  5097.0  354.43
  5107.1  353.83  5237.7  357.76  5280.1  360.05  5287.9  360.96  5294.3  363.65
  5308.0  362.14  5318.0  364.07  5328.1  362.23  5338.1  361.92  5404.6  364.40
#Mann=4,-1,0
  4683.4    0.12       0  5004.6    0.07       0  5008.6    0.12       0
  5280.1    0.05       0
Bank Sta=5004.6,5008.6
Exp/Cntr=0.3,0.1

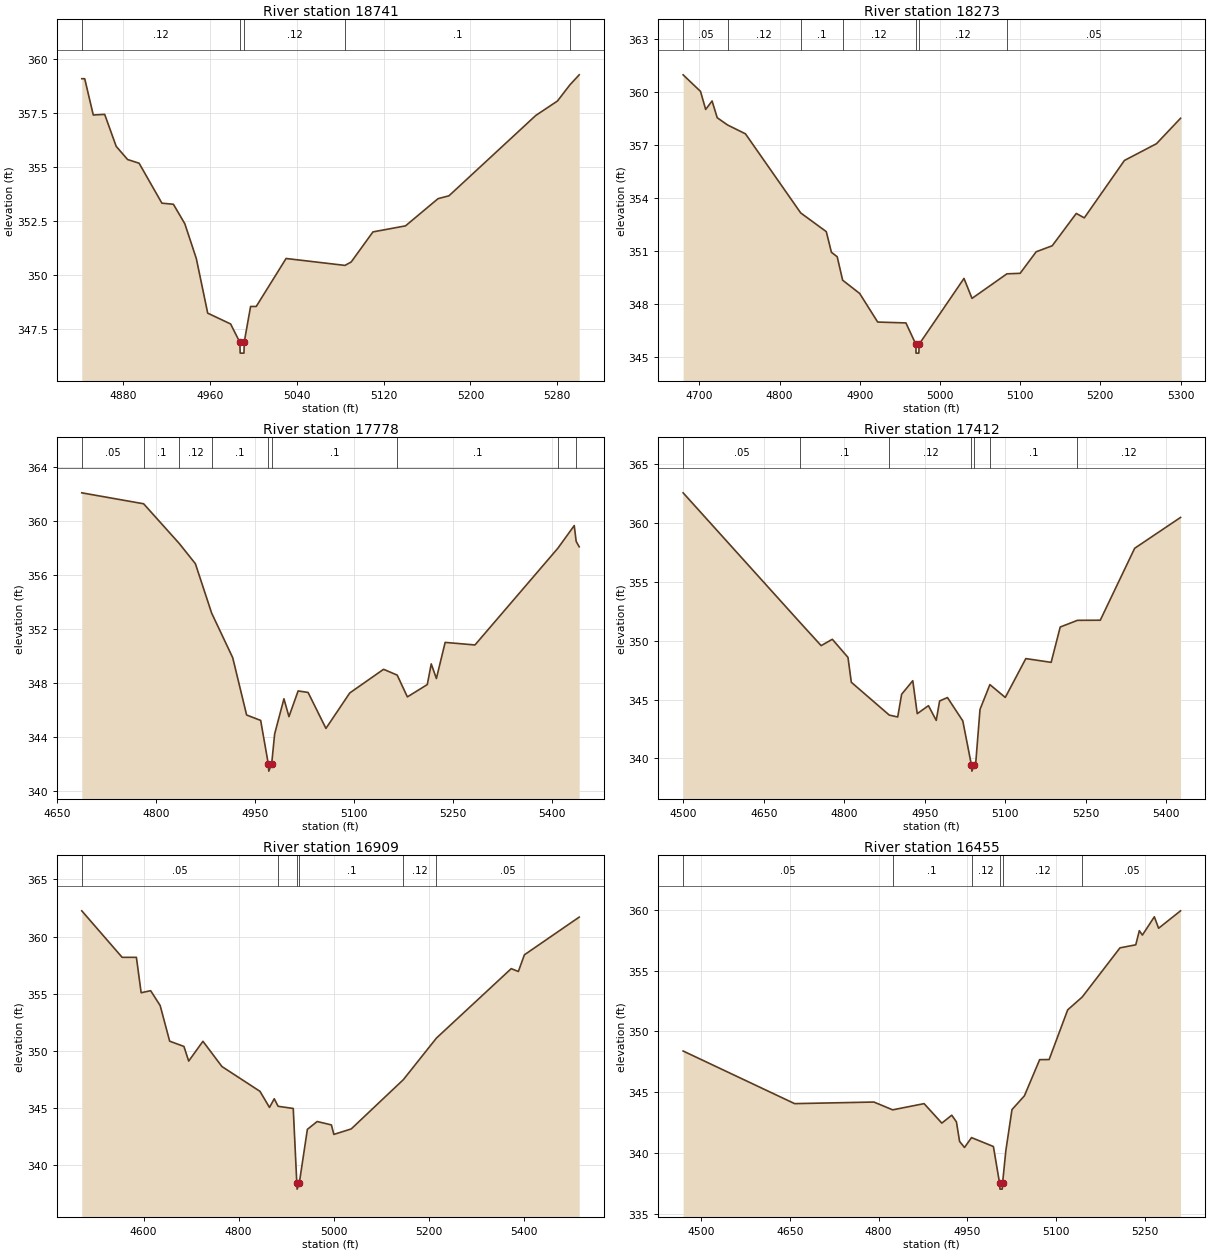
Type RM Length L Ch R = 1,18741,468,468,468
BEGIN DESCRIPTION:
CCT1 26.0
END DESCRIPTION:
XS GIS Cut Line= 3
      2692176.01      6843410.96      2692126.00      6843561.00
      2692126.00      6843861.04
#Sta/Elev= 30
  4842.0  359.07  4844.7  359.07  4852.6  357.39  4863.1  357.42  4873.7  355.94
  4884.2  355.33  4894.8  355.16  4915.8  353.31  4926.4  353.26  4936.9  352.36
  4947.5  350.75  4958.0  348.22  4979.1  347.72  4987.6  346.87  4987.9  346.37
  4991.4  346.37  4991.6  346.87  4997.5  348.53  5002.7  348.53  5030.2  350.75
  5084.4  350.43  5090.2  350.59  5110.2  351.98  5140.2  352.26  5170.2  353.52
  5180.2  353.65  5260.2  357.37  5280.2  358.04  5291.7  358.79  5300.2  359.25
#Mann=5,-1,0
  4842.0    0.12       0  4987.6    0.07       0  4991.6    0.12       0
  5084.4     0.1       0  5291.7    0.05       0
Bank Sta=4987.6,4991.6
Exp/Cntr=0.3,0.1

Type RM Length L Ch R = 1,18273,495,495,495
BEGIN DESCRIPTION:
CCT1 25.0
END DESCRIPTION:
XS GIS Cut Line= 3
      2691926.03      6843210.97      2691726.00      6843461.00
      2691726.00      6843761.00
#Sta/Elev= 30
  4679.8  360.98  4701.5  360.04  4707.9  359.02  4715.9  359.50  4722.3  358.55
  4735.2  358.14  4757.5  357.64  4826.4  353.16  4858.3  352.10  4864.7  350.93
  4871.9  350.68  4878.7  349.35  4899.9  348.60  4922.4  346.98  4957.6  346.93
  4970.0  345.72  4970.2  345.22  4973.7  345.22  4974.0  345.72  5030.0  349.45
  5040.0  348.32  5083.5  349.71  5100.0  349.74  5120.0  350.96  5140.0  351.30
  5170.0  353.13  5180.0  352.88  5230.0  356.13  5270.0  357.08  5300.0  358.52
#Mann=7,-1,0
  4679.8    0.05       0  4735.2    0.12       0  4826.4     0.1       0
  4878.7    0.12       0  4970.0    0.07       0  4974.0    0.12       0
  5083.5    0.05       0
Bank Sta=4970,4974
Exp/Cntr=0.3,0.1

Type RM Length L Ch R = 1,17778,366,366,366
BEGIN DESCRIPTION:
Mapping XS ff3233bb
END DESCRIPTION:
XS GIS Cut Line= 3
      2691592.03      6843043.39      2691369.78      6843262.17
      2691126.72      6843631.97
#Sta/Elev= 30
  4686.9  362.06  4780.7  361.25  4834.8  358.31  4859.2  356.82  4883.9  353.16
  4915.8  349.87  4936.9  345.63  4958.2  345.23  4969.9  341.98  4970.5  341.48
  4974.8  341.98  4979.4  344.23  4993.5  346.83  5001.1  345.51  5015.0  347.41
  5030.1  347.30  5057.2  344.64  5093.3  347.26  5144.6  349.01  5165.3  348.58
  5180.7  346.97  5210.9  347.88  5216.9  349.41  5224.7  348.33  5238.0  351.00
  5283.2  350.81  5408.9  357.96  5433.8  359.64  5436.7  358.47  5441.3  358.07
#Mann=9,-1,0
  4686.9    0.05       0  4780.7     0.1       0  4834.8    0.12       0
  4883.9     0.1       0  4969.9    0.07       0  4974.8     0.1       0
  5165.3     0.1       0  5408.9    0.12       0  5436.7     0.1       0
Bank Sta=4969.9,4974.8
Exp/Cntr=0.3,0.1

Type RM Length L Ch R = 1,17412,503,503,503
BEGIN DESCRIPTION:
CCT1 23.0
END DESCRIPTION:
XS GIS Cut Line= 3
      2691475.97      6842811.02      2691076.00      6843111.00
      2690925.99      6843511.03
#Sta/Elev= 30
  4499.6  362.56  4717.9  351.53  4756.9  349.58  4777.7  350.12  4806.9  348.58
  4813.1  346.47  4883.9  343.68  4899.6  343.52  4906.9  345.45  4927.7  346.60
  4936.0  343.80  4956.9  344.48  4971.4  343.23  4977.7  344.88  4992.3  345.17
  5020.9  343.19  5037.1  339.42  5037.8  338.92  5042.1  339.42  5045.0  339.59
  5053.0  344.16  5071.4  346.27  5100.1  345.18  5138.4  348.48  5185.6  348.16
  5202.5  351.16  5234.7  351.73  5277.2  351.74  5341.3  357.85  5426.8  360.47
#Mann=7,-1,0
  4499.6    0.05       0  4717.9     0.1       0  4883.9    0.12       0
  5037.1    0.07       0  5042.1    0.12       0  5071.4     0.1       0
  5234.7    0.12       0
Bank Sta=5037.1,5042.1
Exp/Cntr=0.3,0.1

Type RM Length L Ch R = 1,16909,454,454,454
BEGIN DESCRIPTION:
Mapping XS 6a91ca7f
END DESCRIPTION:
XS GIS Cut Line= 4
      2691480.87      6842666.68      2691001.72      6842675.36
      2690873.25      6842703.14      2690509.82      6842943.70
#Sta/Elev= 30
  4470.0  362.25  4554.9  358.18  4584.9  358.18  4594.9  355.08  4614.9  355.26
  4634.9  353.96  4654.9  350.84  4684.9  350.38  4694.9  349.10  4724.9  350.83
  4764.9  348.62  4844.9  346.45  4864.9  345.04  4874.9  345.80  4883.1  345.14
  4914.9  344.95  4922.4  338.39  4923.0  337.89  4927.5  338.39  4944.6  343.12
  4965.3  343.81  4995.2  343.51  5000.3  342.68  5036.9  343.16  5146.5  347.47
  5216.1  351.11  5373.5  357.19  5388.5  356.94  5401.2  358.40  5516.5  361.70
#Mann=6,-1,0
  4470.0    0.05       0  4883.1     0.1       0  4922.4    0.07       0
  4927.5     0.1       0  5146.5    0.12       0  5216.1    0.05       0
Bank Sta=4922.4,4927.5
Exp/Cntr=0.3,0.1

Type RM Length L Ch R = 1,16455,535,535,535
BEGIN DESCRIPTION:
Mapping XS 6532900e
END DESCRIPTION:
XS GIS Cut Line= 3
      2691050.12      6842299.66      2690565.73      6842485.43
      2690470.61      6842793.28
#Sta/Elev= 30
  4469.4  348.39  4657.9  344.07  4792.0  344.20  4823.7  343.56  4876.8  344.07
  4906.8  342.47  4923.6  343.12  4931.5  342.57  4936.8  340.97  4945.1  340.47
  4957.0  341.28  4994.0  340.55  5004.4  337.55  5005.1  337.05  5008.9  337.05
  5009.5  337.55  5015.0  340.20  5025.4  343.58  5046.4  344.71  5072.2  347.68
  5088.2  347.69  5119.6  351.77  5144.1  352.82  5208.0  356.86  5234.7  357.11
  5240.7  358.27  5245.9  357.91  5266.1  359.41  5273.3  358.47  5310.4  359.90
#Mann=6,-1,0
  4469.4    0.05       0  4823.7     0.1       0  4957.0    0.12       0
  5004.4    0.07       0  5009.5    0.12       0  5144.1    0.05       0
Bank Sta=5004.4,5009.5
Exp/Cntr=0.3,0.1

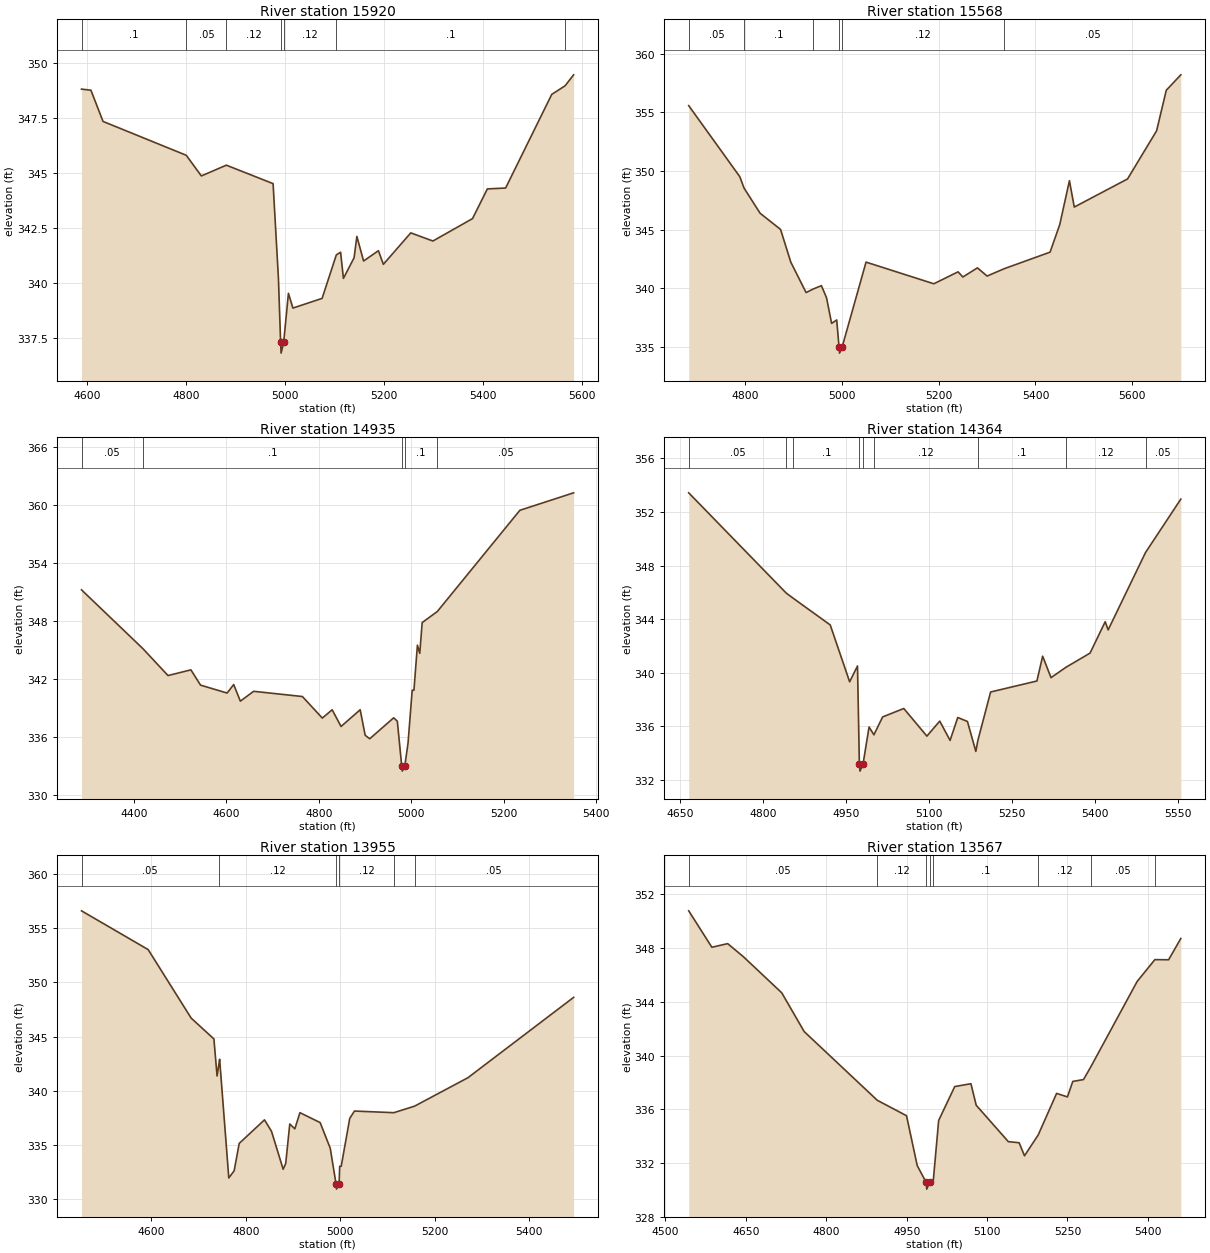
Type RM Length L Ch R = 1,15920,352,352,352
BEGIN DESCRIPTION:
Mapping XS b029a78f
END DESCRIPTION:
XS GIS Cut Line= 4
      2690687.24      6841938.57      2690293.16      6842091.34
      2690225.45      6842209.39      2690248.02      6842645.16
#Sta/Elev= 30
  4588.6  348.82  4607.6  348.77  4632.1  347.35  4800.4  345.81  4830.9  344.87
  4881.5  345.36  4976.0  344.52  4986.8  340.21  4991.2  337.31  4992.2  336.81
  4997.4  337.31  5007.0  339.53  5016.1  338.86  5075.1  339.30  5103.9  341.28
  5112.5  341.40  5118.2  340.21  5139.8  341.15  5145.4  342.12  5159.0  341.00
  5189.0  341.47  5199.0  340.85  5254.4  342.28  5299.2  341.91  5379.3  342.93
  5409.3  344.28  5446.2  344.32  5539.5  348.58  5566.4  348.97  5583.7  349.47
#Mann=7,-1,0
  4588.6     0.1       0  4800.4    0.05       0  4881.5    0.12       0
  4991.2    0.07       0  4997.4    0.12       0  5103.9     0.1       0
  5566.4    0.12       0
Bank Sta=4991.2,4997.4
Exp/Cntr=0.3,0.1

Type RM Length L Ch R = 1,15568,633,633,633
BEGIN DESCRIPTION:
CCT1 19.0
END DESCRIPTION:
XS GIS Cut Line= 3
      2690075.99      6841811.04      2689976.00      6842111.00
      2689976.00      6842811.01
#Sta/Elev= 30
  4683.9  355.58  4789.3  349.52  4798.2  348.54  4831.4  346.39  4873.6  345.01
  4894.7  342.22  4926.3  339.62  4941.4  339.93  4957.9  340.21  4968.5  339.18
  4979.0  336.99  4989.5  337.28  4994.4  334.95  4995.4  334.45  5000.6  334.95
  5050.1  342.22  5190.1  340.37  5240.1  341.39  5250.1  340.95  5280.1  341.73
  5300.1  341.03  5335.6  341.66  5430.1  343.07  5450.1  345.42  5470.1  349.17
  5480.1  346.92  5590.1  349.32  5650.1  353.43  5670.1  356.89  5700.1  358.21
#Mann=6,-1,0
  4683.9    0.05       0  4798.2     0.1       0  4941.4    0.12       0
  4994.4    0.07       0  5000.6    0.12       0  5335.6    0.05       0
Bank Sta=4994.4,5000.6
Exp/Cntr=0.3,0.1

Type RM Length L Ch R = 1,14935,571,571,571
BEGIN DESCRIPTION:
Mapping XS 3552e009
END DESCRIPTION:
XS GIS Cut Line= 4
      2689870.40      6841772.26      2689529.27      6842188.91
      2689482.40      6842363.39      2689443.40      6842706.53
#Sta/Elev= 30
  4286.7  351.21  4419.8  345.11  4473.8  342.34  4523.3  342.93  4544.2  341.35
  4601.6  340.53  4615.9  341.41  4630.3  339.69  4659.0  340.71  4764.5  340.17
  4807.6  337.94  4828.9  338.80  4848.1  337.07  4889.5  338.80  4900.3  336.16
  4910.2  335.80  4962.0  337.97  4969.9  337.61  4979.4  332.95  4980.5  332.45
  4985.9  332.95  4993.0  335.34  5002.0  340.82  5005.8  340.82  5013.3  345.48
  5018.4  344.64  5023.6  347.82  5056.4  348.97  5234.9  359.44  5351.2  361.25
#Mann=5,-1,0
  4286.7    0.05       0  4419.8     0.1       0  4979.4    0.07       0
  4985.9     0.1       0  5056.4    0.05       0
Bank Sta=4979.4,4985.9
Exp/Cntr=0.3,0.1

Type RM Length L Ch R = 1,14364,409,409,409
BEGIN DESCRIPTION:
Mapping XS 49c26384
END DESCRIPTION:
XS GIS Cut Line= 4
      2689648.17      6841612.54      2689410.35      6841822.59
      2689274.93      6842261.82      2689271.46      6842374.63
#Sta/Elev= 30
  4665.5  353.42  4841.7  345.95  4854.4  345.56  4921.4  343.57  4956.5  339.33
  4970.7  340.51  4974.1  333.17  4975.2  332.67  4980.6  333.17  4991.6  335.96
  5000.4  335.38  5016.1  336.71  5054.4  337.34  5096.2  335.28  5119.4  336.40
  5138.1  334.96  5152.0  336.67  5169.5  336.37  5184.7  334.14  5188.3  334.95
  5211.4  338.57  5295.1  339.39  5305.5  341.24  5320.6  339.64  5348.3  340.43
  5391.2  341.47  5418.6  343.81  5423.9  343.20  5491.5  348.97  5555.3  352.95
#Mann=9,-1,0
  4665.5    0.05       0  4841.7    0.12       0  4854.4     0.1       0
  4974.1    0.07       0  4980.6     0.1       0  5000.4    0.12       0
  5188.3     0.1       0  5348.3    0.12       0  5491.5    0.05       0
Bank Sta=4974.1,4980.6
Exp/Cntr=0.3,0.1

Type RM Length L Ch R = 1,13955,388,388,388
BEGIN DESCRIPTION:
Mapping XS a21a30fa
END DESCRIPTION:
XS GIS Cut Line= 3
      2689283.63      6841449.28      2689089.17      6841959.74
      2689080.49      6842454.52
#Sta/Elev= 30
  4452.6  356.58  4593.6  353.01  4684.6  346.70  4732.7  344.78  4739.4  341.37
  4743.5  342.54  4744.8  342.91  4764.2  331.98  4775.5  332.64  4786.2  335.16
  4839.7  337.33  4854.5  336.28  4879.2  332.78  4884.6  333.31  4893.2  336.95
  4903.9  336.50  4914.7  337.99  4957.4  337.08  4978.8  334.72  4991.0  331.45
  4992.0  330.95  4997.6  331.45  4998.8  333.05  5002.0  333.05  5020.1  337.47
  5030.1  338.14  5113.4  337.99  5157.2  338.59  5270.1  341.21  5493.7  348.61
#Mann=6,-1,0
  4452.6    0.05       0  4743.5    0.12       0  4991.0    0.07       0
  4997.6    0.12       0  5113.4     0.1       0  5157.2    0.05       0
Bank Sta=4991,4997.6
Exp/Cntr=0.3,0.1

Type RM Length L Ch R = 1,13567,338,338,338
BEGIN DESCRIPTION:
Mapping XS 982f2227
END DESCRIPTION:
XS GIS Cut Line= 4
      2689063.12      6841426.75      2688837.43      6841744.46
      2688839.17      6841876.41      2688820.07      6842272.28
#Sta/Elev= 30
  4543.4  350.77  4586.6  348.06  4616.1  348.33  4645.6  347.35  4717.0  344.67
  4758.8  341.79  4895.1  336.68  4949.7  335.53  4969.7  331.82  4986.4  330.57
  4987.4  330.07  4993.0  330.57  4999.5  330.64  5009.7  335.18  5039.7  337.70
  5069.9  337.91  5079.7  336.31  5139.7  333.60  5159.8  333.52  5169.8  332.55
  5195.4  334.10  5229.7  337.19  5249.9  336.93  5259.9  338.08  5279.9  338.22
  5293.3  339.15  5380.0  345.52  5413.0  347.14  5438.6  347.13  5461.4  348.71
#Mann=8,-1,0
  4543.4    0.05       0  4895.1    0.12       0  4986.4    0.07       0
  4993.0    0.12       0  4999.5     0.1       0  5195.4    0.12       0
  5293.3    0.05       0  5413.0     0.1       0
Bank Sta=4986.4,4993
Exp/Cntr=0.3,0.1

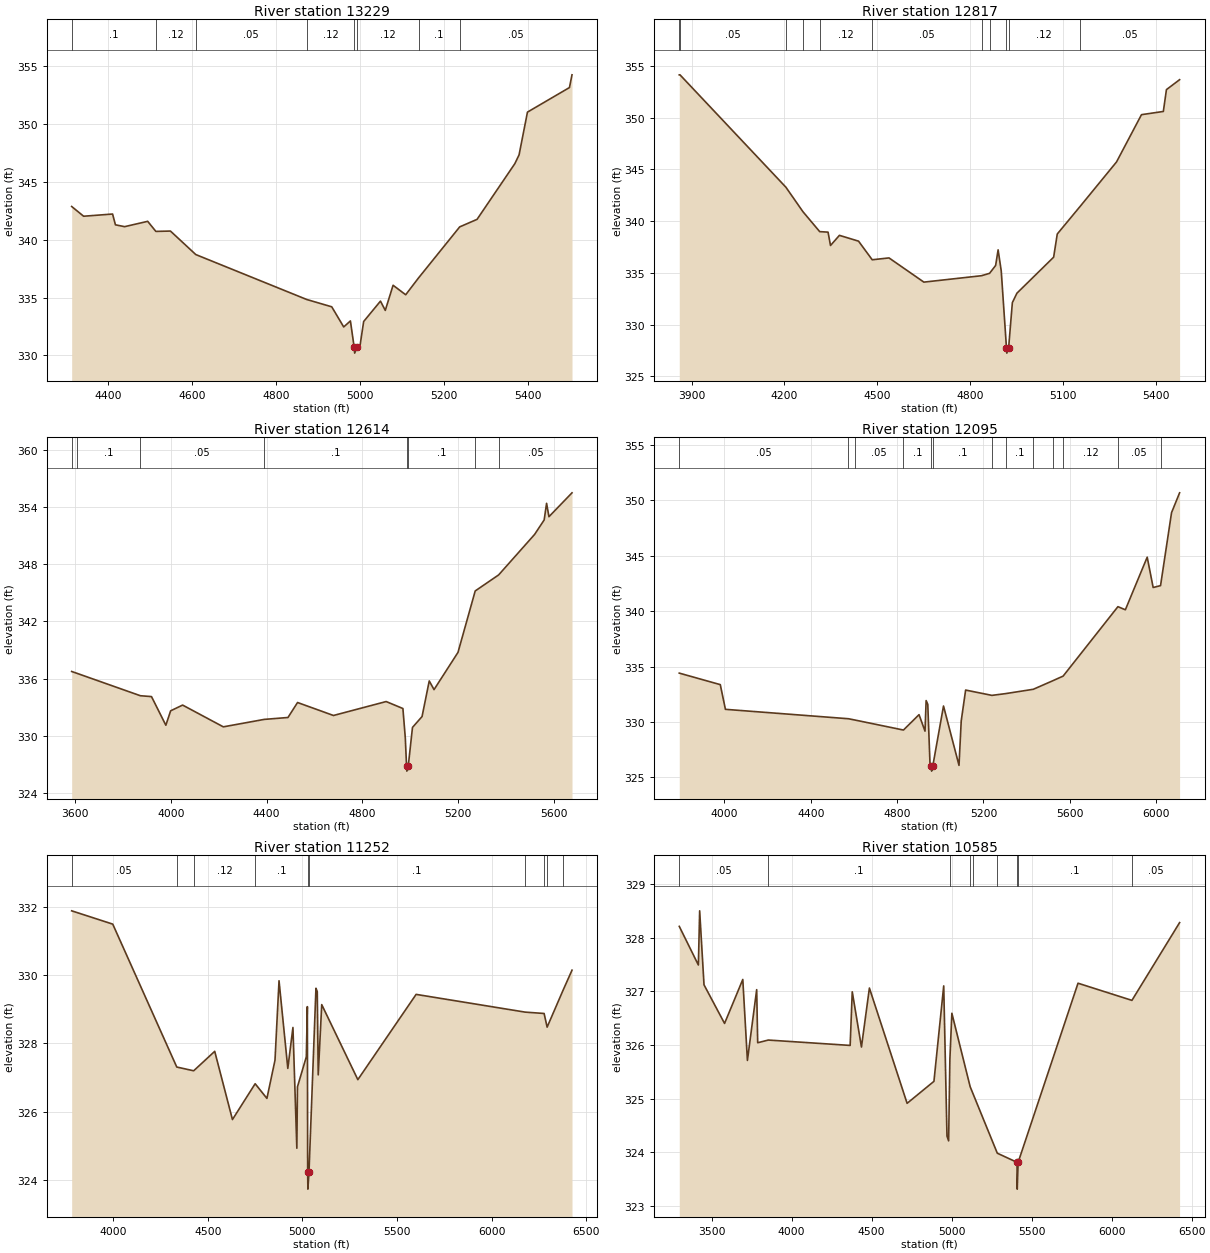
Type RM Length L Ch R = 1,13229,412,412,412
BEGIN DESCRIPTION:
Mapping XS 6fb7bd09
END DESCRIPTION:
XS GIS Cut Line= 3
      2688900.99      6841236.01      2688616.94      6841857.66
      2688650.73      6842367.07
#Sta/Elev= 30
  4312.2  342.86  4340.7  342.02  4409.8  342.21  4416.6  341.28  4438.6  341.12
  4493.6  341.58  4513.1  340.71  4547.9  340.74  4608.4  338.71  4873.2  334.83
  4932.8  334.20  4961.4  332.46  4977.4  332.98  4986.4  330.70  4987.5  330.20
  4993.3  330.70  4999.8  330.72  5009.0  332.93  5049.1  334.69  5060.6  333.89
  5079.2  336.06  5109.3  335.24  5139.9  336.69  5238.2  341.10  5279.6  341.75
  5369.8  346.56  5379.9  347.32  5399.9  351.01  5500.1  353.13  5506.2  354.23
#Mann=8,-1,0
  4312.2     0.1       0  4513.1    0.12       0  4608.4    0.05       0
  4873.2    0.12       0  4986.4    0.07       0  4993.3    0.12       0
  5139.9     0.1       0  5238.2    0.05       0
Bank Sta=4986.4,4993.3
Exp/Cntr=0.3,0.1

Type RM Length L Ch R = 1,12817,203,203,203
BEGIN DESCRIPTION:
Mapping XS 9916bd0c
END DESCRIPTION:
XS GIS Cut Line= 5
      2688689.43      6840901.61      2688317.46      6841743.07
      2688291.42      6841896.72      2688304.44      6842081.61
      2688260.18      6842433.13
#Sta/Elev= 30
  3860.3  354.13  3862.6  354.13  4204.6  343.27  4259.5  340.91  4313.7  338.98
  4340.7  338.93  4348.6  337.64  4377.4  338.62  4439.1  338.06  4483.3  336.26
  4537.5  336.44  4650.1  334.10  4836.2  334.72  4862.2  334.95  4881.8  335.71
  4889.8  337.22  4899.9  335.18  4916.8  327.74  4917.9  327.24  4923.7  327.74
  4935.8  332.12  4950.5  333.03  5069.1  336.51  5080.8  338.75  5153.6  341.38
  5272.1  345.71  5352.7  350.28  5423.3  350.59  5433.3  352.70  5475.8  353.66
#Mann=11,-1,0
  3860.3    0.12       0  3862.6    0.05       0  4204.6    0.12       0
  4259.5    0.05       0  4313.7    0.12       0  4483.3    0.05       0
  4836.2     0.1       0  4862.2    0.12       0  4916.8    0.07       0
  4923.7    0.12       0  5153.6    0.05       0
Bank Sta=4916.8,4923.7
Exp/Cntr=0.3,0.1

Type RM Length L Ch R = 1,12614,519,519,519
BEGIN DESCRIPTION:
Mapping XS 6bba21bd
END DESCRIPTION:
XS GIS Cut Line= 3
      2688107.86      6840597.73      2688109.13      6842003.49
      2688114.33      6842687.21
#Sta/Elev= 30
  3586.3  336.75  3607.0  336.57  3873.2  334.21  3919.6  334.12  3979.6  331.12
  3999.6  332.63  4049.6  333.23  4219.6  330.95  4390.3  331.73  4489.6  331.93
  4529.6  333.50  4679.6  332.14  4899.6  333.60  4969.6  332.87  4979.6  329.79
  4984.9  326.81  4985.9  326.31  4991.8  326.81  5009.6  330.89  5049.6  332.03
  5079.6  335.76  5099.6  334.85  5199.6  338.75  5271.6  345.19  5369.5  346.87
  5519.6  351.11  5559.6  352.63  5569.6  354.37  5579.6  352.97  5675.8  355.47
#Mann=8,-1,0
  3586.3    0.12       0  3607.0     0.1       0  3873.2    0.05       0
  4390.3     0.1       0  4984.9    0.07       0  4991.8     0.1       0
  5271.6    0.12       0  5369.5    0.05       0
Bank Sta=4984.9,4991.8
Exp/Cntr=0.3,0.1

Type RM Length L Ch R = 1,12095,843,843,843
BEGIN DESCRIPTION:
Mapping XS 8388f1f2
END DESCRIPTION:
XS GIS Cut Line= 3
      2688032.39      6840709.23      2687680.83      6841868.07
      2687927.90      6842947.36
#Sta/Elev= 30
  3790.6  334.41  3980.6  333.37  4004.4  331.14  4574.5  330.29  4602.9  330.18
  4829.3  329.27  4901.5  330.66  4929.2  329.17  4934.4  331.93  4942.0  331.59
  4952.4  326.18  4958.6  326.06  4959.7  325.56  4965.6  326.06  5014.9  331.44
  5086.7  326.08  5097.0  330.10  5117.4  332.88  5239.1  332.40  5303.1  332.56
  5430.9  332.95  5520.0  333.71  5569.1  334.14  5823.0  340.41  5857.5  340.13
  5958.7  344.88  5986.3  342.14  6020.5  342.31  6071.5  348.90  6108.8  350.69
#Mann=13,-1,0
  3790.6    0.05       0  4574.5    0.12       0  4602.9    0.05       0
  4829.3     0.1       0  4958.6    0.07       0  4965.6     0.1       0
  5239.1    0.12       0  5303.1     0.1       0  5430.9    0.12       0
  5520.0    0.05       0  5569.1    0.12       0  5823.0    0.05       0
  6020.5     0.1       0
Bank Sta=4958.6,4965.6
Exp/Cntr=0.3,0.1

Type RM Length L Ch R = 1,11252,667,667,667
BEGIN DESCRIPTION:
Mapping XS 87665e5e
END DESCRIPTION:
XS GIS Cut Line= 3
      2687678.23      6840355.74      2687060.17      6841369.64
      2687331.01      6842800.20
#Sta/Elev= 30
  3781.2  331.89  3998.2  331.50  4336.4  327.31  4425.7  327.20  4536.9  327.77
  4630.6  325.77  4750.6  326.82  4812.7  326.39  4855.4  327.51  4876.7  329.84
  4923.1  327.27  4950.2  328.47  4970.8  324.93  4974.1  326.73  5020.9  327.61
  5026.4  329.08  5028.0  324.23  5029.1  323.73  5035.0  324.23  5071.8  329.62
  5078.7  329.52  5083.8  327.08  5102.3  329.14  5293.1  326.94  5601.0  329.44
  6177.0  328.92  6277.2  328.88  6293.2  328.48  6377.3  329.56  6424.6  330.15
#Mann=10,-1,0
  3781.2    0.05       0  4336.4     0.1       0  4425.7    0.12       0
  4750.6     0.1       0  5028.0    0.07       0  5035.0     0.1       0
  6177.0    0.12       0  6277.2    0.05       0  6293.2    0.12       0
  6377.3    0.05       0
Bank Sta=5028,5035
Exp/Cntr=0.3,0.1

Type RM Length L Ch R = 1,10585,1107,1107,1107
BEGIN DESCRIPTION:
Mapping XS 4e09f422
END DESCRIPTION:
XS GIS Cut Line= 4
      2687372.66      6840119.65      2686449.06      6841300.19
      2686490.73      6841515.47      2687178.21      6842744.60
#Sta/Elev= 30
  3298.5  328.21  3417.8  327.49  3425.9  328.50  3453.1  327.12  3581.5  326.40
  3695.4  327.22  3724.3  325.71  3782.2  327.03  3788.5  326.04  3854.8  326.09
  4366.3  325.99  4379.4  326.99  4436.9  325.96  4486.6  327.06  4722.2  324.91
  4889.9  325.32  4951.0  327.10  4971.4  324.30  4981.6  324.21  4989.5  325.73
  5001.9  326.59  5116.2  325.22  5136.7  325.07  5285.8  323.98  5409.1  323.81
  5410.2  323.31  5416.1  323.81  5790.3  327.15  6127.1  326.83  6425.0  328.28
#Mann=9,-1,0
  3298.5    0.05       0  3854.8     0.1       0  4989.5    0.12       0
  5116.2     0.1       0  5136.7    0.12       0  5285.8     0.1       0
  5409.1    0.07       0  5416.1     0.1       0  6127.1    0.05       0
Bank Sta=5409.1,5416.1
Exp/Cntr=0.3,0.1

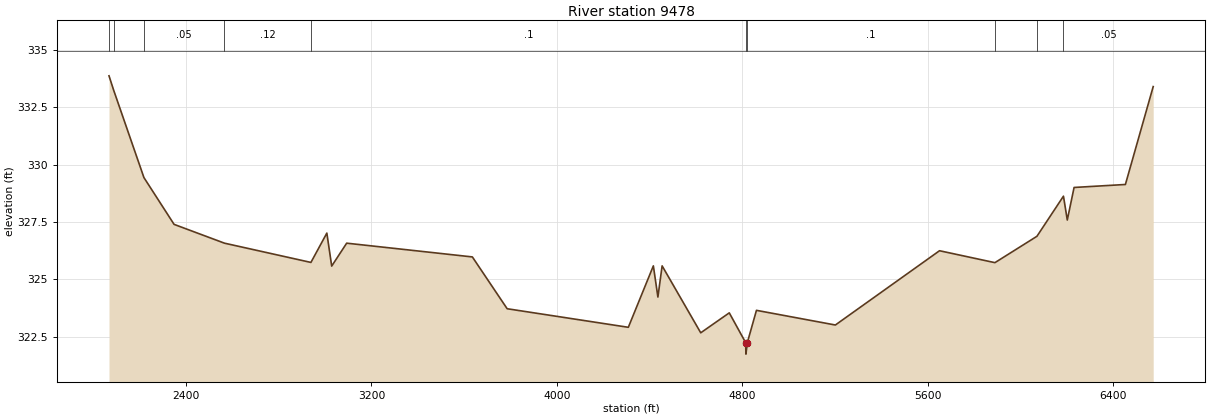
Type RM Length L Ch R = 1,9478,0,0,0
BEGIN DESCRIPTION:
Mapping XS e8365774
END DESCRIPTION:
XS GIS Cut Line= 4
      2687435.17      6839696.03      2686046.28      6841557.14
      2686178.23      6842133.52      2687457.68      6843076.98
#Sta/Elev= 30
  2068.4  333.88  2088.6  333.25  2219.1  329.44  2349.1  327.40  2566.4  326.58
  2939.2  325.74  3007.9  327.02  3028.8  325.58  3093.4  326.58  3635.4  325.98
  3785.5  323.72  4308.1  322.91  4416.0  325.59  4435.6  324.23  4453.8  325.59
  4620.3  322.67  4743.4  323.54  4814.1  322.24  4815.2  321.74  4821.2  322.24
  4860.6  323.65  5200.9  323.01  5650.1  326.25  5889.0  325.73  6070.2  326.88
  6184.6  328.63  6201.1  327.59  6230.4  329.01  6451.7  329.14  6571.6  333.41
#Mann=10,-1,0
  2068.4     0.1       0  2088.6    0.12       0  2219.1    0.05       0
  2566.4    0.12       0  2939.2     0.1       0  4814.1    0.07       0
  4821.2     0.1       0  5889.0    0.05       0  6070.2    0.12       0
  6184.6    0.05       0
Bank Sta=4814.1,4821.2
Exp/Cntr=0.3,0.1

Chan Stop Cuts=-1