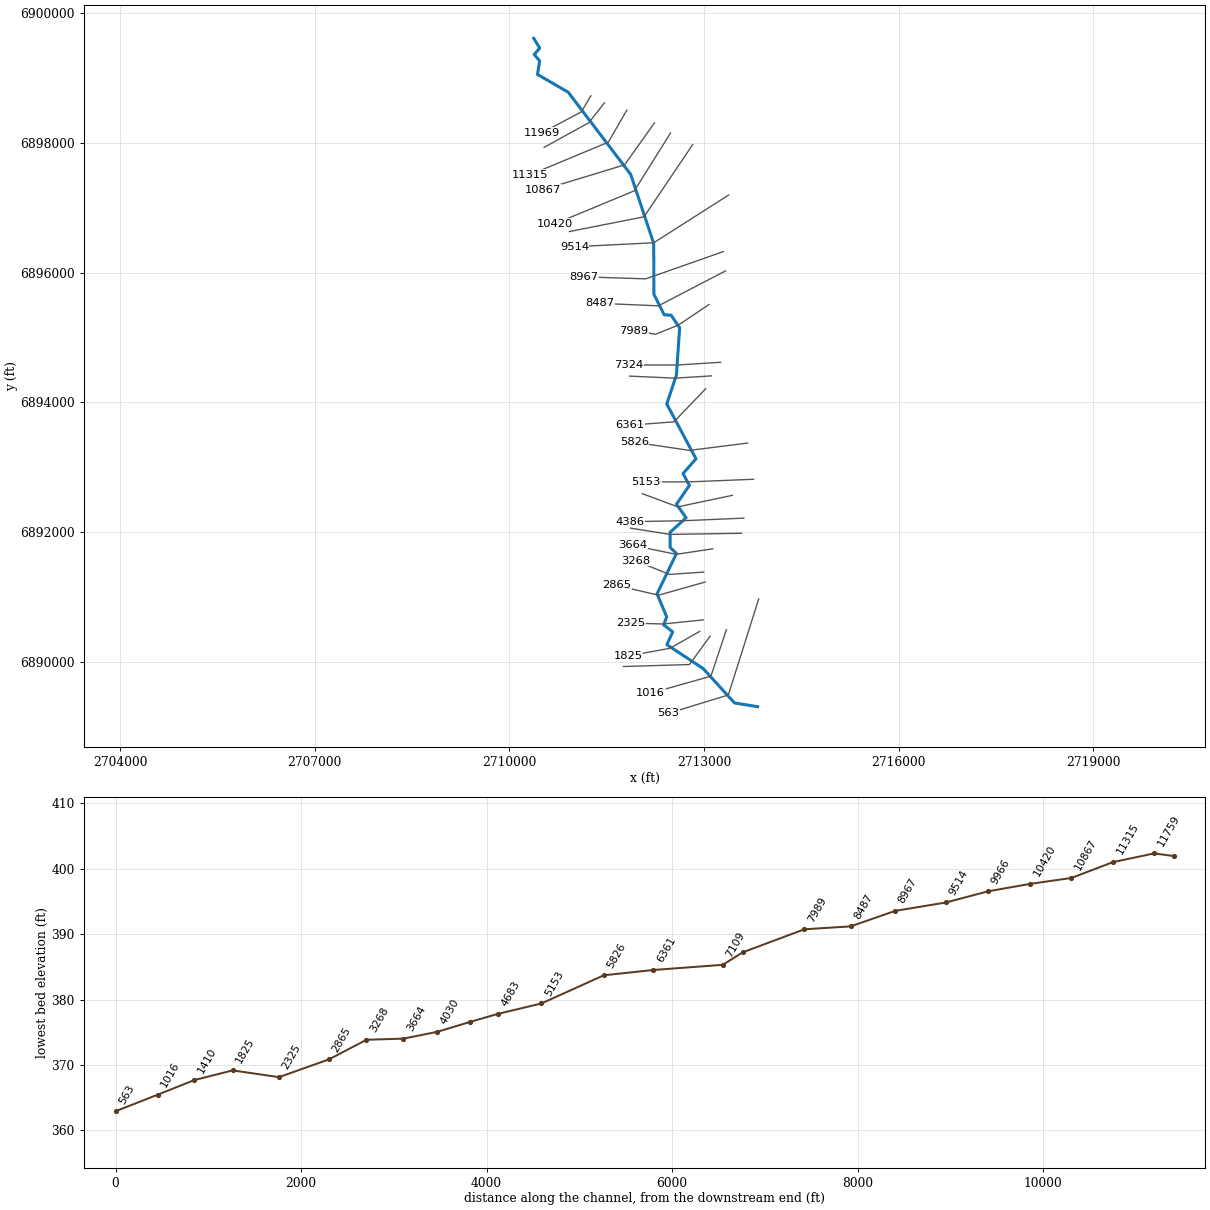
--- CCT10.prj (project) ---

Proj Title=CCT10 Base Level Engineering
Current Plan=p01
Default Exp/Contr=0.3,0.1
English Units
Geom File=g01
Flow File=f01
Plan File=p01
BEGIN DESCRIPTION:
CCT10
END DESCRIPTION:

--- CCT10.p01 (plan) ---

Plan Title=Multiple Run
Short Identifier=Multiple
Geom File=g01
Flow File=f01
Subcritical Flow
K Sum by GR= 0
Std Step Tol= 0.01
Critical Tol= 0.01
Num of Std Step Trials= 20
Max Error Tol= 0.3
Flow Tol Ratio= 0.001
Split Flow NTrial= 30
Split Flow Tol= 0.02
Split Flow Ratio= 0.02
Log Output Level= 0
Friction Slope Method= 1
Unsteady Friction Slope Method= 2
Unsteady Bridges Friction Slope Method= 1
Parabolic Critical Depth
Global Vel Dist=  1 , 1 , 1
Global Log Level= 0
CheckData=True
Encroach Param= -1, 0, 0, 0
BEGIN DESCRIPTION:
Multiple Run
END DESCRIPTION:

--- CCT10.f01 (steady flow) ---

Flow Title=Multiple
Number of Profiles=7
Profile Names=10-year,25-year,50-year,1pct_min,100-year,1pct_plu,500-year
River Rch & RM= CCT10,Reach-1,11969
     660     872    1040     614    1225    2445    1700
River Rch & RM= CCT10,Reach-1,7989
     890    1198    1446     863    1722    3437    2445
River Rch & RM= CCT10,Reach-1,3268
    1192    1629    1987    1198    2390    4768    3458
Boundary for River Rch & Prof#=CCT10,Reach-1,1
Up Type=0
Dn Type=3
Dn Slope=0.005
Boundary for River Rch & Prof#=CCT10,Reach-1,2
Up Type=0
Dn Type=3
Dn Slope=0.005
Boundary for River Rch & Prof#=CCT10,Reach-1,3
Up Type=0
Dn Type=3
Dn Slope=0.005
Boundary for River Rch & Prof#=CCT10,Reach-1,4
Up Type=0
Dn Type=3
Dn Slope=0.005
Boundary for River Rch & Prof#=CCT10,Reach-1,5
Up Type=0
Dn Type=3
Dn Slope=0.005
Boundary for River Rch & Prof#=CCT10,Reach-1,6
Up Type=0
Dn Type=3
Dn Slope=0.005
Boundary for River Rch & Prof#=CCT10,Reach-1,7
Up Type=0
Dn Type=3
Dn Slope=0.005

--- CCT10.g01 (geometry) ---

Geom Title=Existing Conditions

River Reach=CCT10,Reach-1
Reach XY= 30
      2710376.00      6899611.00      2710468.91      6899461.00
      2710383.12      6899361.00      2710468.18      6899264.42
      2710433.80      6899054.79      2710906.38      6898781.18
      2711870.52      6897513.44      2712224.78      6896450.50
      2712228.27      6895666.94      2712386.78      6895350.61
      2712492.70      6895344.62      2712624.80      6895150.50
      2712574.80      6894421.50      2712426.39      6893976.16
      2712876.43      6893131.35      2712677.42      6892904.57
      2712775.07      6892721.49      2712575.78      6892431.05
      2712724.97      6892221.63      2712477.64      6891999.17
      2712478.01      6891766.68      2712575.60      6891672.02
      2712276.77      6891050.31      2712425.74      6890694.97
      2712377.18      6890573.02      2712518.23      6890464.42
      2712427.61      6890267.03      2712989.22      6889897.38
      2713469.93      6889369.12      2713826.00      6889311.00

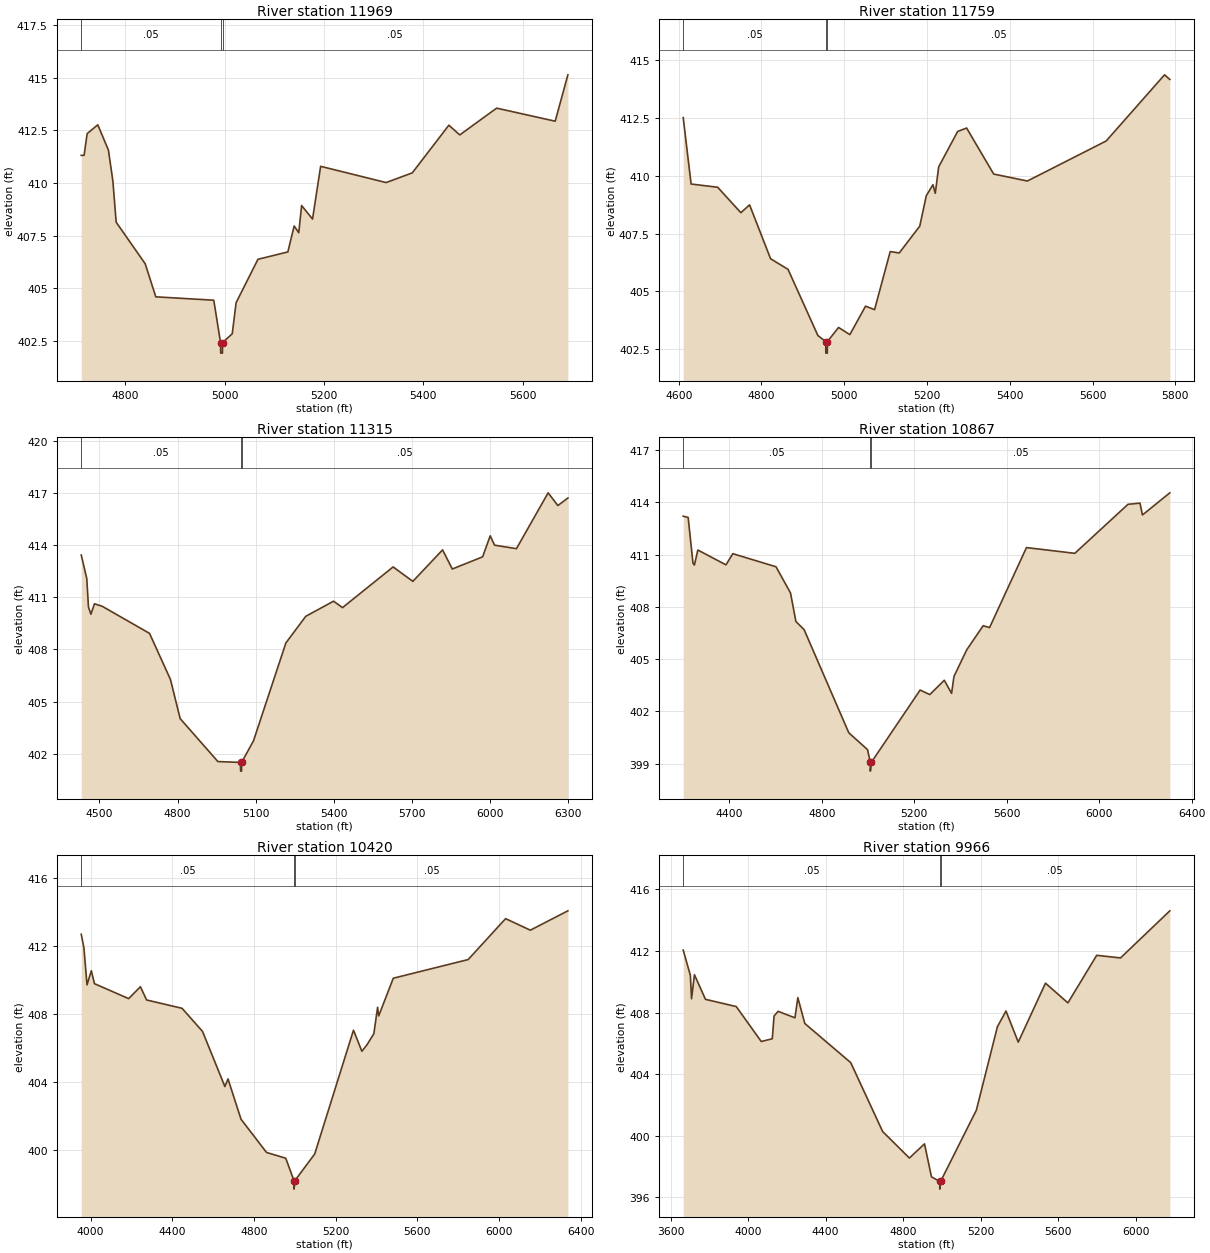
Type RM Length L Ch R = 1,11969,210,210,210
BEGIN DESCRIPTION:
CCT10 27.0
END DESCRIPTION:
XS GIS Cut Line= 3
      2711257.39      6898725.72      2711109.42      6898477.70
      2710499.37      6898153.60
#Sta/Elev= 30
  4711.2  411.31  4716.9  411.31  4723.1  412.34  4744.5  412.76  4765.9  411.56
  4774.9  410.09  4781.5  408.14  4839.9  406.17  4861.3  404.60  4978.0  404.44
  4991.6  402.43  4991.9  401.93  4995.4  401.93  4995.7  402.43  5015.2  402.85
  5022.9  404.32  5066.9  406.38  5127.1  406.73  5139.8  407.96  5149.1  407.64
  5154.8  408.93  5176.8  408.29  5193.1  410.79  5325.0  410.02  5377.6  410.48
  5451.2  412.74  5473.2  412.28  5547.4  413.55  5665.3  412.93  5690.8  415.13
#Mann=3,-1,0
  4711.2    0.05       0  4991.6    0.04       0  4995.7    0.05       0
Bank Sta=4991.6,4995.7
Exp/Cntr=0.3,0.1

Type RM Length L Ch R = 1,11759,444,444,444
BEGIN DESCRIPTION:
CCT10 26.0
END DESCRIPTION:
XS GIS Cut Line= 3
      2711465.72      6898617.21      2711226.00      6898311.00
      2710536.90      6897931.43
#Sta/Elev= 30
  4610.9  412.51  4630.0  409.64  4694.2  409.50  4750.2  408.40  4771.2  408.74
  4822.0  406.41  4864.2  405.95  4936.3  403.09  4955.2  402.83  4955.5  402.33
  4959.0  402.33  4959.4  402.83  4986.2  403.44  5013.5  403.13  5051.4  404.36
  5073.2  404.21  5111.0  406.72  5132.8  406.66  5182.4  407.82  5198.1  409.13
  5214.2  409.61  5219.9  409.24  5228.1  410.38  5273.8  411.91  5295.6  412.06
  5361.0  410.07  5442.4  409.77  5632.7  411.50  5773.7  414.36  5786.5  414.16
#Mann=3,-1,0
  4610.9    0.05       0  4955.2    0.04       0  4959.4    0.05       0
Bank Sta=4955.2,4959.4
Exp/Cntr=0.3,0.1

Type RM Length L Ch R = 1,11315,448,448,448
BEGIN DESCRIPTION:
CCT10 25.0
END DESCRIPTION:
XS GIS Cut Line= 3
      2711811.39      6898504.96      2711526.00      6898011.00
      2710325.97      6897510.99
#Sta/Elev= 30
  4430.0  413.42  4451.3  412.07  4457.7  410.44  4467.1  410.02  4480.8  410.62
  4510.2  410.48  4692.5  408.92  4772.9  406.27  4810.2  404.02  4955.3  401.55
  5042.2  401.50  5042.5  401.00  5046.1  401.00  5046.4  401.50  5092.0  402.74
  5216.6  408.37  5293.0  409.90  5399.7  410.77  5434.3  410.40  5628.8  412.74
  5704.6  411.91  5818.9  413.72  5856.3  412.62  5972.8  413.32  6002.0  414.53
  6018.8  413.99  6102.8  413.79  6224.6  417.00  6262.0  416.27  6300.5  416.70
#Mann=3,-1,0
  4430.0    0.05       0  5042.2    0.04       0  5046.4    0.05       0
Bank Sta=5042.2,5046.4
Exp/Cntr=0.3,0.1

Type RM Length L Ch R = 1,10867,447,447,447
BEGIN DESCRIPTION:
CCT10 24.0
END DESCRIPTION:
XS GIS Cut Line= 3
      2712237.11      6898308.44      2711776.00      6897661.00
      2710522.74      6897279.81
#Sta/Elev= 30
  4200.8  413.20  4222.2  413.13  4243.2  410.50  4249.4  410.40  4264.1  411.26
  4385.8  410.41  4415.3  411.05  4602.2  410.30  4664.9  408.80  4688.3  407.16
  4723.9  406.69  4917.0  400.78  4998.3  399.81  5009.9  399.08  5010.3  398.58
  5014.3  399.08  5225.6  403.23  5267.4  402.97  5330.1  403.79  5361.6  403.04
  5371.9  404.01  5427.3  405.54  5498.3  406.92  5525.9  406.81  5685.5  411.40
  5894.6  411.07  6124.5  413.88  6176.4  413.95  6187.2  413.27  6305.6  414.54
#Mann=3,-1,0
  4200.8    0.05       0  5009.9    0.04       0  5014.3    0.05       0
Bank Sta=5009.9,5014.3
Exp/Cntr=0.3,0.1

Type RM Length L Ch R = 1,10420,454,454,454
BEGIN DESCRIPTION:
CCT10 23.0
END DESCRIPTION:
XS GIS Cut Line= 3
      2712484.51      6898152.19      2711926.00      6897261.00
      2710696.28      6896750.27
#Sta/Elev= 30
  3954.1  412.68  3967.3  411.87  3982.3  409.70  4003.5  410.53  4018.8  409.77
  4186.2  408.89  4243.9  409.59  4274.1  408.81  4447.8  408.32  4548.0  406.96
  4657.6  403.71  4672.9  404.16  4736.5  401.79  4861.5  399.83  4955.7  399.49
  4995.9  398.17  4996.4  397.67  5000.4  398.17  5097.5  399.74  5287.4  407.03
  5328.5  405.79  5352.3  406.15  5387.1  406.82  5405.5  408.38  5410.9  407.87
  5482.3  410.09  5849.1  411.19  6032.4  413.60  6153.6  412.92  6337.4  414.06
#Mann=3,-1,0
  3954.1    0.05       0  4995.9    0.04       0  5000.4    0.05       0
Bank Sta=4995.9,5000.4
Exp/Cntr=0.3,0.1

Type RM Length L Ch R = 1,9966,452,452,452
BEGIN DESCRIPTION:
CCT10 22.0
END DESCRIPTION:
XS GIS Cut Line= 3
      2712824.78      6897972.14      2712076.00      6896861.00
      2710926.36      6896633.62
#Sta/Elev= 30
  3665.3  412.06  3702.3  410.42  3708.4  408.90  3723.3  410.46  3780.3  408.86
  3939.2  408.39  4068.2  406.12  4125.2  406.30  4134.1  407.77  4155.1  408.08
  4242.1  407.66  4257.0  408.97  4293.0  407.29  4529.9  404.75  4694.9  400.27
  4832.8  398.55  4910.8  399.47  4946.7  397.33  4989.4  397.03  4989.9  396.53
  4993.9  397.03  5178.5  401.66  5287.1  407.08  5331.4  408.10  5394.7  406.08
  5535.3  409.91  5651.0  408.63  5799.6  411.72  5922.6  411.55  6177.1  414.61
#Mann=3,-1,0
  3665.3    0.05       0  4989.4    0.04       0  4993.9    0.05       0
Bank Sta=4989.4,4993.9
Exp/Cntr=0.3,0.1

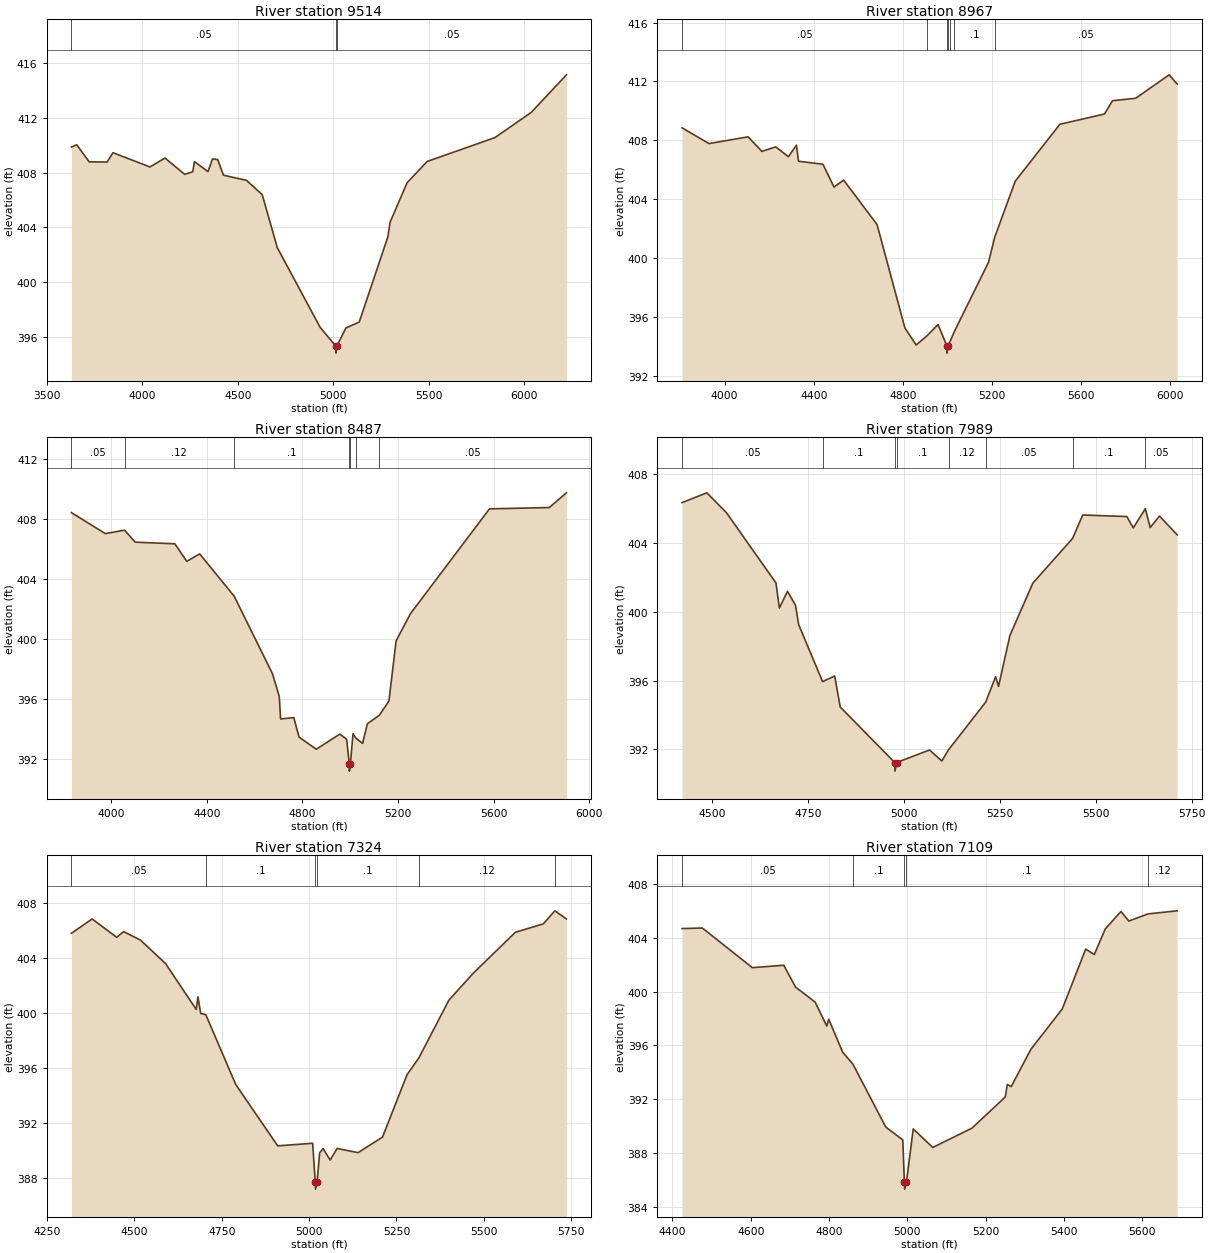
Type RM Length L Ch R = 1,9514,547,547,547
BEGIN DESCRIPTION:
CCT10 21.0
END DESCRIPTION:
XS GIS Cut Line= 3
      2713379.50      6897196.13      2712226.00      6896461.00
      2711001.89      6896399.25
#Sta/Elev= 30
  3627.7  409.86  3655.6  410.03  3720.9  408.78  3814.8  408.77  3845.3  409.45
  4039.1  408.41  4118.0  409.06  4221.1  407.87  4263.4  408.06  4272.2  408.80
  4343.3  408.07  4366.7  408.99  4393.8  408.95  4424.2  407.81  4545.3  407.43
  4627.4  406.39  4706.1  402.53  4930.4  396.72  5013.3  395.33  5013.7  394.83
  5017.9  395.33  5065.6  396.66  5135.7  397.10  5285.9  403.32  5297.1  404.37
  5386.0  407.25  5491.4  408.81  5846.6  410.55  6036.9  412.39  6221.2  415.13
#Mann=3,-1,0
  3627.7    0.05       0  5013.3    0.04       0  5017.9    0.05       0
Bank Sta=5013.3,5017.9
Exp/Cntr=0.3,0.1

Type RM Length L Ch R = 1,8967,480,480,480
BEGIN DESCRIPTION:
Mapping XS a1698780
END DESCRIPTION:
XS GIS Cut Line= 3
      2713298.95      6896324.43      2712101.00      6895904.28
      2711150.31      6895935.51
#Sta/Elev= 30
  3809.7  408.85  3930.3  407.78  4105.7  408.24  4167.7  407.25  4229.7  407.56
  4286.4  406.89  4322.7  407.67  4332.1  406.58  4441.4  406.38  4491.1  404.83
  4534.4  405.30  4684.1  402.29  4809.0  395.27  4859.6  394.10  4907.0  394.71
  4957.9  395.49  4997.3  394.05  4997.9  393.55  5002.1  394.05  5011.0  394.31
  5030.5  395.00  5184.3  399.72  5212.5  401.44  5304.3  405.23  5504.4  409.09
  5704.5  409.79  5740.2  410.69  5844.6  410.86  5994.7  412.45  6030.4  411.82
#Mann=7,-1,0
  3809.7    0.05       0  4907.0     0.1       0  4997.3    0.07       0
  5002.1     0.1       0  5011.0    0.05       0  5030.5     0.1       0
  5212.5    0.05       0
Bank Sta=4997.3,5002.1
Exp/Cntr=0.3,0.1

Type RM Length L Ch R = 1,8487,498,498,498
BEGIN DESCRIPTION:
Mapping XS d5746794
END DESCRIPTION:
XS GIS Cut Line= 3
      2713331.89      6896027.10      2712297.18      6895488.92
      2711394.40      6895527.11
#Sta/Elev= 30
  3834.0  408.42  3975.9  407.02  4056.0  407.25  4101.0  406.45  4266.6  406.34
  4316.4  405.17  4370.4  405.67  4514.8  402.84  4674.8  397.67  4703.1  396.16
  4708.7  394.66  4763.8  394.75  4785.9  393.45  4857.8  392.64  4956.6  393.65
  4984.8  393.31  4995.8  391.68  4996.3  391.18  5000.6  391.68  5011.5  393.68
  5022.7  393.39  5051.5  393.03  5071.6  394.34  5121.9  394.91  5161.6  395.85
  5191.7  399.87  5251.7  401.68  5582.0  408.67  5832.2  408.76  5903.9  409.74
#Mann=7,-1,0
  3834.0    0.05       0  4056.0    0.12       0  4514.8     0.1       0
  4995.8    0.07       0  5000.6     0.1       0  5022.7    0.12       0
  5121.9    0.05       0
Bank Sta=4995.8,5000.6
Exp/Cntr=0.3,0.1

Type RM Length L Ch R = 1,7989,665,665,665
BEGIN DESCRIPTION:
Mapping XS 94b7f558
END DESCRIPTION:
XS GIS Cut Line= 4
      2713078.07      6895509.39      2712604.13      6895191.69
      2712255.17      6895051.07      2711916.65      6895103.15
#Sta/Elev= 30
  4422.9  406.36  4487.2  406.93  4538.2  405.78  4667.3  401.69  4676.3  400.23
  4697.3  401.20  4718.3  400.39  4726.4  399.27  4788.7  395.95  4820.4  396.27
  4834.7  394.47  4976.8  391.24  4977.3  390.74  4981.6  391.24  5067.3  391.97
  5099.3  391.33  5117.1  391.99  5213.5  394.75  5239.4  396.23  5247.1  395.67
  5276.7  398.63  5336.5  401.68  5439.7  404.27  5466.4  405.64  5581.3  405.55
  5598.0  404.89  5629.4  406.01  5642.0  404.91  5666.3  405.58  5712.2  404.49
#Mann=8,-1,0
  4422.9    0.05       0  4788.7     0.1       0  4976.8    0.07       0
  4981.6     0.1       0  5117.1    0.12       0  5213.5    0.05       0
  5439.7     0.1       0  5629.4    0.05       0
Bank Sta=4976.8,4981.6
Exp/Cntr=0.3,0.1

Type RM Length L Ch R = 1,7324,215,215,215
BEGIN DESCRIPTION:
Mapping XS 24e73f25
END DESCRIPTION:
XS GIS Cut Line= 3
      2713255.21      6894618.78      2712598.92      6894577.11
      2711839.74      6894577.11
#Sta/Elev= 30
  4319.8  405.79  4379.1  406.83  4449.3  405.50  4469.3  405.91  4517.9  405.29
  4589.6  403.58  4677.0  400.26  4682.0  401.18  4689.8  399.97  4704.5  399.88
  4790.0  394.82  4910.2  390.36  5010.3  390.55  5017.7  387.72  5018.4  387.22
  5022.9  387.72  5030.3  389.86  5040.3  390.16  5060.3  389.33  5080.3  390.17
  5140.3  389.87  5210.3  391.00  5280.3  395.52  5314.2  396.74  5400.3  400.94
  5470.3  402.90  5590.3  405.86  5670.3  406.47  5703.5  407.42  5736.6  406.83
#Mann=6,-1,0
  4319.8    0.05       0  4704.5     0.1       0  5017.7    0.07       0
  5022.9     0.1       0  5314.2    0.12       0  5703.5     0.1       0
Bank Sta=5017.7,5022.9
Exp/Cntr=0.3,0.1

Type RM Length L Ch R = 1,7109,748,748,748
BEGIN DESCRIPTION:
Mapping XS e88fcc4b
END DESCRIPTION:
XS GIS Cut Line= 3
      2713114.99      6894409.05      2712552.51      6894374.33
      2711852.85      6894405.58
#Sta/Elev= 30
  4424.7  404.70  4476.5  404.74  4604.0  401.79  4684.2  401.97  4714.2  400.35
  4764.3  399.23  4794.1  397.45  4799.1  397.95  4834.5  395.51  4860.8  394.61
  4944.7  389.93  4988.2  388.97  4992.2  385.81  4992.9  385.31  4997.4  385.81
  5014.8  389.79  5064.8  388.41  5164.9  389.85  5249.9  392.17  5255.0  393.10
  5265.0  392.94  5315.1  395.71  5395.2  398.71  5455.2  403.17  5477.1  402.77
  5505.3  404.68  5545.3  405.97  5565.3  405.26  5614.1  405.79  5688.6  406.02
#Mann=5,-1,0
  4424.7    0.05       0  4860.8     0.1       0  4992.2    0.07       0
  4997.4     0.1       0  5614.1    0.12       0
Bank Sta=4992.2,4997.4
Exp/Cntr=0.3,0.1

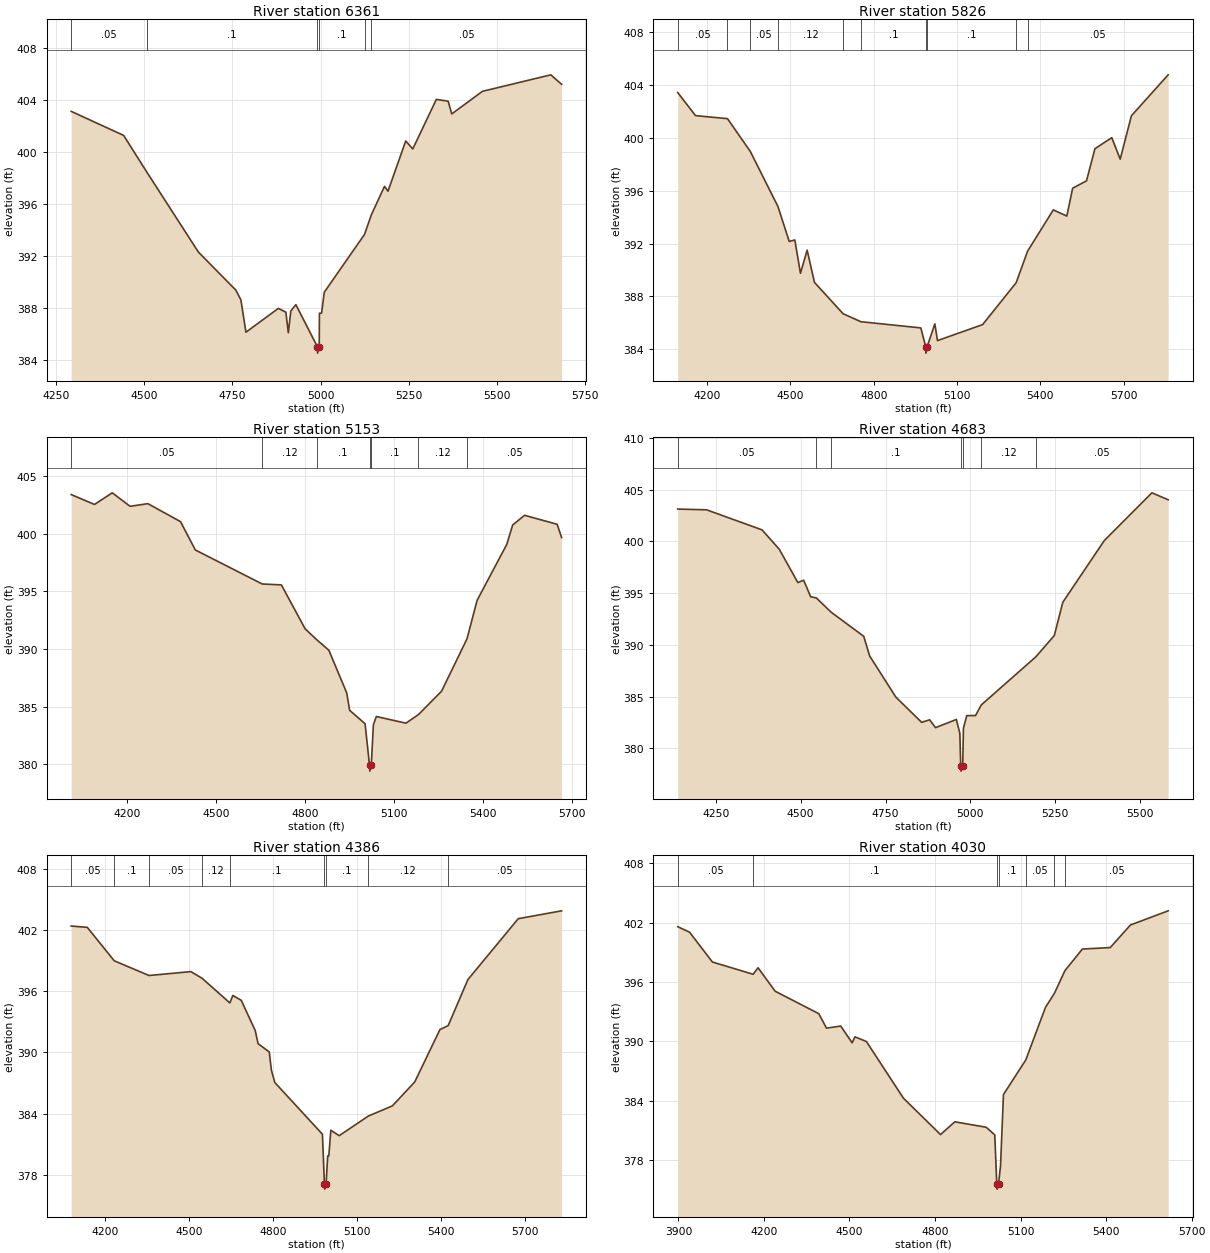
Type RM Length L Ch R = 1,6361,535,535,535
BEGIN DESCRIPTION:
CCT10 14.0
END DESCRIPTION:
XS GIS Cut Line= 3
      2713026.02      6894211.02      2712536.48      6893701.20
      2711855.48      6893648.99
#Sta/Elev= 30
  4293.2  403.12  4441.8  401.27  4507.0  398.47  4653.8  392.29  4760.1  389.36
  4774.2  388.61  4788.4  386.13  4880.2  387.96  4901.6  387.67  4908.5  386.09
  4915.7  387.77  4929.9  388.25  4990.7  385.02  4991.5  384.52  4996.1  385.02
  4996.7  387.59  5002.7  387.59  5010.5  389.21  5124.4  393.65  5143.7  395.15
  5181.0  397.35  5191.0  396.98  5241.2  400.84  5261.2  400.23  5328.0  404.04
  5361.5  403.90  5371.6  402.92  5458.6  404.66  5652.4  405.93  5683.0  405.20
#Mann=6,-1,0
  4293.2    0.05       0  4507.0     0.1       0  4990.7    0.07       0
  4996.1     0.1       0  5124.4    0.12       0  5143.7    0.05       0
Bank Sta=4990.7,4996.1
Exp/Cntr=0.3,0.1

Type RM Length L Ch R = 1,5826,673,673,673
BEGIN DESCRIPTION:
CCT10 13.0
END DESCRIPTION:
XS GIS Cut Line= 3
      2713674.30      6893374.03      2712776.00      6893261.00
      2711925.17      6893387.04
#Sta/Elev= 30
  4094.5  403.45  4158.6  401.70  4273.6  401.47  4355.7  398.99  4455.2  394.82
  4495.9  392.17  4516.1  392.28  4536.3  389.76  4560.4  391.51  4586.7  389.07
  4689.5  386.70  4753.7  386.09  4969.6  385.62  4987.0  384.21  4987.9  383.71
  4992.6  384.21  5020.1  385.93  5029.6  384.66  5192.0  385.87  5312.7  389.04
  5353.9  391.43  5446.6  394.56  5495.2  394.09  5516.1  396.20  5566.0  396.76
  5596.3  399.19  5657.0  400.03  5687.3  398.40  5727.7  401.69  5860.0  404.79
#Mann=10,-1,0
  4094.5    0.05       0  4273.6    0.12       0  4355.7    0.05       0
  4455.2    0.12       0  4689.5    0.05       0  4753.7     0.1       0
  4987.0    0.07       0  4992.6     0.1       0  5312.7    0.12       0
  5353.9    0.05       0
Bank Sta=4987,4992.6
Exp/Cntr=0.3,0.1

Type RM Length L Ch R = 1,5153,470,470,470
BEGIN DESCRIPTION:
CCT10 12.0
END DESCRIPTION:
XS GIS Cut Line= 3
      2713764.50      6892815.98      2712776.80      6892776.13
      2712110.91      6892774.31
#Sta/Elev= 30
  4011.5  403.40  4090.1  402.54  4150.1  403.55  4210.2  402.38  4270.2  402.61
  4380.3  401.05  4430.3  398.59  4655.9  395.64  4720.6  395.56  4800.6  391.75
  4840.4  390.79  4880.7  389.89  4940.8  386.20  4950.8  384.68  5002.9  383.51
  5017.9  379.90  5018.8  379.40  5023.8  379.90  5030.8  383.41  5040.8  384.14
  5140.8  383.56  5183.0  384.31  5260.8  386.33  5346.7  390.88  5380.8  394.22
  5480.8  399.07  5500.8  400.76  5540.8  401.60  5650.8  400.82  5665.9  399.67
#Mann=7,-1,0
  4011.5    0.05       0  4655.9    0.12       0  4840.4     0.1       0
  5017.9    0.07       0  5023.8     0.1       0  5183.0    0.12       0
  5346.7    0.05       0
Bank Sta=5017.9,5023.8
Exp/Cntr=0.3,0.1

Type RM Length L Ch R = 1,4683,297,297,297
BEGIN DESCRIPTION:
CCT10 10.0
END DESCRIPTION:
XS GIS Cut Line= 3
      2713439.04      6892568.59      2712595.57      6892390.81
      2712049.71      6892594.13
#Sta/Elev= 30
  4138.0  403.12  4222.9  403.05  4386.4  401.11  4436.9  399.25  4491.8  396.02
  4509.0  396.25  4529.5  394.65  4546.2  394.54  4589.6  393.17  4685.9  390.83
  4703.2  388.94  4780.4  384.96  4856.5  382.52  4879.9  382.77  4897.4  382.01
  4958.7  382.80  4968.9  381.47  4971.5  378.31  4972.4  377.81  4977.4  378.31
  4979.5  381.95  4989.3  383.17  5015.2  383.18  5032.0  384.20  5193.1  388.86
  5247.2  390.91  5272.2  394.12  5394.4  400.08  5534.5  404.69  5582.5  404.02
#Mann=7,-1,0
  4138.0    0.05       0  4546.2    0.12       0  4589.6     0.1       0
  4971.5    0.07       0  4977.4     0.1       0  5032.0    0.12       0
  5193.1    0.05       0
Bank Sta=4971.5,4977.4
Exp/Cntr=0.3,0.1

Type RM Length L Ch R = 1,4386,356,356,356
BEGIN DESCRIPTION:
CCT10 9.0
END DESCRIPTION:
XS GIS Cut Line= 3
      2713613.46      6892217.02      2712693.22      6892177.27
      2711860.95      6892162.33
#Sta/Elev= 30
  4078.9  402.38  4136.4  402.25  4232.9  398.97  4357.1  397.53  4506.8  397.91
  4547.3  397.25  4646.3  394.84  4656.9  395.57  4686.9  395.10  4737.0  392.13
  4747.0  390.85  4787.0  390.04  4794.9  388.23  4807.0  387.04  4977.2  381.97
  4984.3  377.09  4985.2  376.59  4990.2  377.09  4996.1  379.85  5000.0  379.85
  5007.2  382.36  5037.2  381.83  5141.2  383.75  5227.3  384.75  5307.3  387.10
  5397.3  392.23  5426.8  392.62  5497.3  397.13  5677.3  403.10  5832.4  403.87
#Mann=9,-1,0
  4078.9    0.05       0  4232.9     0.1       0  4357.1    0.05       0
  4547.3    0.12       0  4646.3     0.1       0  4984.3    0.07       0
  4990.2     0.1       0  5141.2    0.12       0  5426.8    0.05       0
Bank Sta=4984.3,4990.2
Exp/Cntr=0.3,0.1

Type RM Length L Ch R = 1,4030,366,366,366
BEGIN DESCRIPTION:
CCT10 8.0
END DESCRIPTION:
XS GIS Cut Line= 3
      2713577.63      6891983.62      2712475.37      6891966.58
      2711865.40      6892063.38
#Sta/Elev= 30
  3897.6  401.58  3939.2  401.02  4019.2  398.01  4162.2  396.77  4179.3  397.43
  4239.3  395.06  4392.4  392.79  4419.3  391.33  4469.3  391.54  4509.3  389.85
  4519.3  390.45  4559.3  389.98  4689.3  384.25  4819.3  380.58  4869.4  381.87
  4979.4  381.32  5009.5  380.55  5016.6  375.57  5017.6  375.07  5022.6  375.57
  5029.7  377.43  5039.9  384.62  5118.3  388.12  5187.2  393.42  5218.9  394.86
  5255.4  397.13  5316.8  399.32  5414.5  399.47  5485.4  401.75  5617.6  403.18
#Mann=7,-1,0
  3897.6    0.05       0  4162.2     0.1       0  5016.6    0.07       0
  5022.6     0.1       0  5118.3    0.05       0  5218.9    0.12       0
  5255.4    0.05       0
Bank Sta=5016.6,5022.6
Exp/Cntr=0.3,0.1

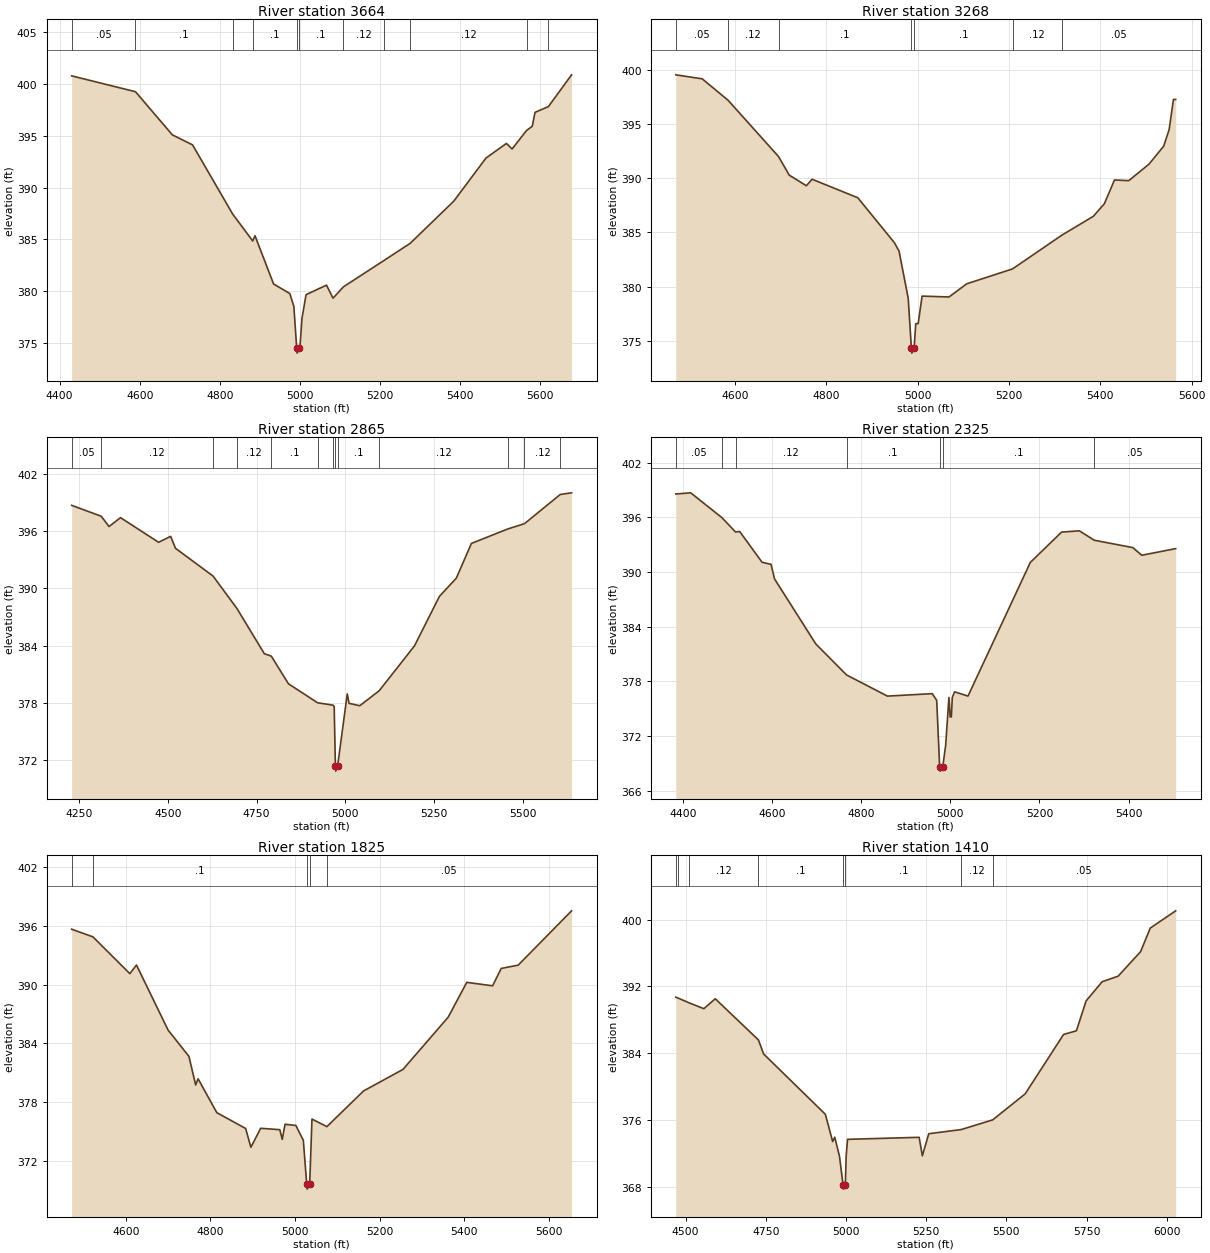
Type RM Length L Ch R = 1,3664,396,396,396
BEGIN DESCRIPTION:
CCT10 7.0
END DESCRIPTION:
XS GIS Cut Line= 3
      2713134.52      6891744.47      2712571.06      6891659.05
      2711906.68      6891796.28
#Sta/Elev= 30
  4430.1  400.78  4589.5  399.25  4681.5  395.09  4732.0  394.12  4832.1  387.45
  4882.2  384.85  4887.9  385.36  4934.3  380.70  4974.8  379.78  4984.9  378.54
  4992.0  374.53  4993.0  374.03  4998.0  374.53  5000.0  374.53  5005.2  377.39
  5015.4  379.67  5066.4  380.59  5082.8  379.33  5108.5  380.42  5210.1  382.97
  5275.6  384.63  5384.2  388.69  5464.7  392.85  5515.7  394.26  5529.9  393.73
  5566.2  395.52  5580.1  395.91  5587.2  397.26  5620.4  397.81  5678.4  400.88
#Mann=11,-1,0
  4430.1    0.05       0  4589.5     0.1       0  4832.1    0.12       0
  4882.2     0.1       0  4992.0    0.07       0  4998.0     0.1       0
  5108.5    0.12       0  5210.1     0.1       0  5275.6    0.12       0
  5566.2    0.05       0  5620.4    0.12       0
Bank Sta=4992,4998
Exp/Cntr=0.3,0.1

Type RM Length L Ch R = 1,3268,403,403,403
BEGIN DESCRIPTION:
Mapping XS 4d595d81
END DESCRIPTION:
XS GIS Cut Line= 3
      2712993.90      6891385.96      2712467.87      6891349.51
      2711941.85      6891563.04
#Sta/Elev= 30
  4470.0  399.53  4528.0  399.16  4584.5  397.19  4695.2  391.99  4718.5  390.28
  4756.1  389.30  4768.6  389.90  4868.8  388.19  4949.0  384.04  4959.1  383.27
  4979.1  378.94  4986.1  374.36  4987.1  373.86  4992.2  374.36  4995.7  376.58
  5001.0  376.58  5009.6  379.12  5068.6  379.04  5107.2  380.25  5207.8  381.63
  5315.7  384.74  5384.6  386.48  5408.7  387.63  5431.0  389.83  5462.3  389.77
  5506.6  391.29  5538.9  392.96  5550.7  394.48  5560.1  397.26  5565.0  397.26
#Mann=7,-1,0
  4470.0    0.05       0  4584.5    0.12       0  4695.2     0.1       0
  4986.1    0.07       0  4992.2     0.1       0  5207.8    0.12       0
  5315.7    0.05       0
Bank Sta=4986.1,4992.2
Exp/Cntr=0.3,0.1

Type RM Length L Ch R = 1,2865,540,540,540
BEGIN DESCRIPTION:
Mapping XS 1729757f
END DESCRIPTION:
XS GIS Cut Line= 3
      2713017.36      6891232.32      2712298.60      6891029.19
      2711655.40      6891180.23
#Sta/Elev= 30
  4229.5  398.71  4312.6  397.57  4334.8  396.49  4367.1  397.42  4474.2  394.84
  4508.2  395.46  4521.9  394.21  4627.7  391.30  4694.8  387.91  4772.0  383.17
  4791.7  382.91  4839.9  380.02  4921.9  378.03  4965.2  377.78  4968.7  377.64
  4972.1  371.37  4973.1  370.87  4978.2  371.37  5005.5  378.96  5010.6  377.97
  5040.7  377.72  5095.4  379.29  5194.8  383.99  5265.1  389.18  5312.7  391.09
  5355.1  394.72  5457.2  396.23  5504.5  396.79  5605.4  399.85  5637.1  400.02
#Mann=13,-1,0
  4229.5    0.05       0  4312.6    0.12       0  4627.7     0.1       0
  4694.8    0.12       0  4791.7     0.1       0  4921.9    0.12       0
  4965.2     0.1       0  4972.1    0.07       0  4978.2     0.1       0
  5095.4    0.12       0  5457.2    0.05       0  5504.5    0.12       0
  5605.4     0.1       0
Bank Sta=4972.1,4978.2
Exp/Cntr=0.3,0.1

Type RM Length L Ch R = 1,2325,500,500,500
BEGIN DESCRIPTION:
CCT10 5.0
END DESCRIPTION:
XS GIS Cut Line= 3
      2712988.74      6890648.99      2712375.48      6890585.89
      2711869.96      6890599.48
#Sta/Elev= 30
  4383.5  398.55  4417.1  398.68  4487.1  395.96  4517.8  394.38  4527.0  394.44
  4577.3  391.06  4597.4  390.84  4605.2  389.24  4697.9  382.10  4767.0  378.70
  4858.7  376.38  4959.3  376.65  4969.3  375.91  4975.9  368.65  4977.0  368.15
  4982.9  368.65  4989.4  370.99  4996.7  376.23  4999.5  374.10  5002.1  374.10
  5004.3  376.23  5009.5  376.85  5039.5  376.38  5179.5  391.05  5249.6  394.37
  5289.6  394.51  5323.0  393.48  5409.6  392.67  5429.6  391.83  5505.7  392.56
#Mann=7,-1,0
  4383.5    0.05       0  4487.1     0.1       0  4517.8    0.12       0
  4767.0     0.1       0  4975.9    0.07       0  4982.9     0.1       0
  5323.0    0.05       0
Bank Sta=4975.9,4982.9
Exp/Cntr=0.3,0.1

Type RM Length L Ch R = 1,1825,415,415,415
BEGIN DESCRIPTION:
CCT10 4.0
END DESCRIPTION:
XS GIS Cut Line= 3
      2712934.03      6890471.91      2712476.00      6890211.00
      2711832.42      6890094.29
#Sta/Elev= 30
  4472.3  395.63  4522.6  394.85  4609.7  391.11  4625.5  391.98  4700.2  385.36
  4749.4  382.69  4765.3  379.78  4771.0  380.41  4815.3  376.96  4883.4  375.35
  4895.8  373.44  4918.9  375.37  4964.1  375.23  4969.9  374.24  4976.4  375.78
  5002.0  375.66  5019.7  374.15  5027.7  369.68  5028.8  369.18  5034.7  369.68
  5040.1  376.31  5075.4  375.54  5162.0  379.17  5255.1  381.36  5362.0  386.68
  5405.9  390.22  5466.9  389.87  5487.3  391.64  5527.3  391.97  5653.5  397.50
#Mann=5,-1,0
  4472.3    0.12       0  4522.6     0.1       0  5027.7    0.07       0
  5034.7     0.1       0  5075.4    0.05       0
Bank Sta=5027.7,5034.7
Exp/Cntr=0.3,0.1

Type RM Length L Ch R = 1,1410,394,394,394
BEGIN DESCRIPTION:
CCT10 3.0
END DESCRIPTION:
XS GIS Cut Line= 3
      2713092.89      6890396.41      2712776.00      6889961.00
      2711756.89      6889930.23
#Sta/Elev= 30
  4469.4  390.70  4475.0  390.62  4511.2  390.02  4557.0  389.32  4592.6  390.51
  4727.2  385.57  4743.3  383.89  4935.7  376.66  4958.4  373.39  4965.0  373.91
  4979.7  371.63  4990.9  368.19  4992.0  367.69  4997.9  368.19  5000.6  371.67
  5004.8  373.66  5228.0  373.90  5238.0  371.69  5258.0  374.33  5359.0  374.83
  5457.1  375.99  5558.2  379.10  5678.2  386.23  5718.2  386.67  5748.3  390.25
  5798.3  392.55  5848.3  393.22  5918.3  396.16  5948.3  398.98  6027.5  401.05
#Mann=8,-1,0
  4469.4    0.12       0  4475.0     0.1       0  4511.2    0.12       0
  4727.2     0.1       0  4990.9    0.07       0  4997.9     0.1       0
  5359.0    0.12       0  5457.1    0.05       0
Bank Sta=4990.9,4997.9
Exp/Cntr=0.3,0.1

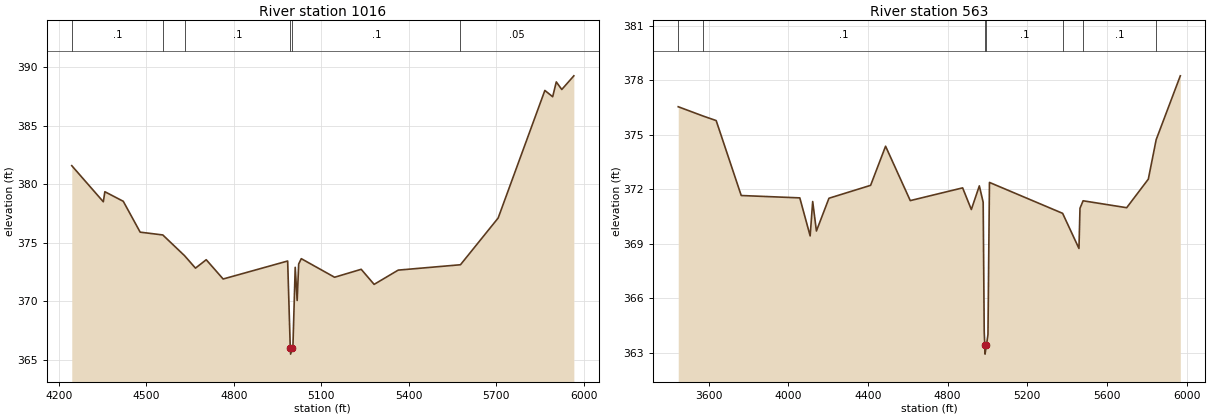
Type RM Length L Ch R = 1,1016,453,453,453
BEGIN DESCRIPTION:
CCT10 2.0
END DESCRIPTION:
XS GIS Cut Line= 3
      2713345.47      6890497.93      2713106.37      6889781.16
      2712176.17      6889518.77
#Sta/Elev= 30
  4244.4  381.59  4352.6  378.50  4357.9  379.36  4421.1  378.54  4479.0  375.90
  4556.6  375.66  4631.1  373.89  4668.7  372.82  4705.6  373.54  4763.6  371.89
  4984.9  373.43  4993.9  365.96  4995.0  365.46  5000.9  365.96  5002.8  365.96
  5010.8  372.89  5017.5  370.05  5022.7  373.17  5031.6  373.63  5145.9  372.04
  5237.1  372.72  5281.5  371.43  5364.0  372.65  5577.6  373.11  5706.9  377.11
  5867.1  388.03  5893.9  387.49  5906.3  388.76  5925.1  388.11  5966.5  389.28
#Mann=6,-1,0
  4244.4     0.1       0  4556.6    0.12       0  4631.1     0.1       0
  4993.9    0.07       0  5000.9     0.1       0  5577.6    0.05       0
Bank Sta=4993.9,5000.9
Exp/Cntr=0.3,0.1

Type RM Length L Ch R = 1,563,0,0,0
BEGIN DESCRIPTION:
CCT10 1.0
END DESCRIPTION:
XS GIS Cut Line= 3
      2713843.57      6890972.61      2713375.50      6889492.04
      2712449.83      6889208.22
#Sta/Elev= 30
  3447.2  376.54  3571.9  376.03  3637.7  375.78  3763.5  371.66  4057.6  371.53
  4109.6  369.44  4122.3  371.33  4141.1  369.71  4204.0  371.51  4413.2  372.22
  4488.3  374.37  4612.3  371.38  4875.2  372.08  4918.9  370.89  4959.1  372.19
  4978.3  371.29  4983.6  364.17  4986.4  363.44  4987.7  362.94  4994.8  363.44
  5002.4  364.01  5009.9  372.38  5377.3  370.68  5459.3  368.75  5464.5  370.96
  5480.1  371.37  5698.9  370.99  5807.6  372.56  5847.0  374.73  5968.2  378.24
#Mann=7,-1,0
  3447.2    0.05       0  3571.9     0.1       0  4986.4    0.07       0
  4994.8     0.1       0  5377.3    0.12       0  5480.1     0.1       0
  5847.0    0.05       0
Bank Sta=4986.4,4994.8
Exp/Cntr=0.3,0.1

Chan Stop Cuts=-1