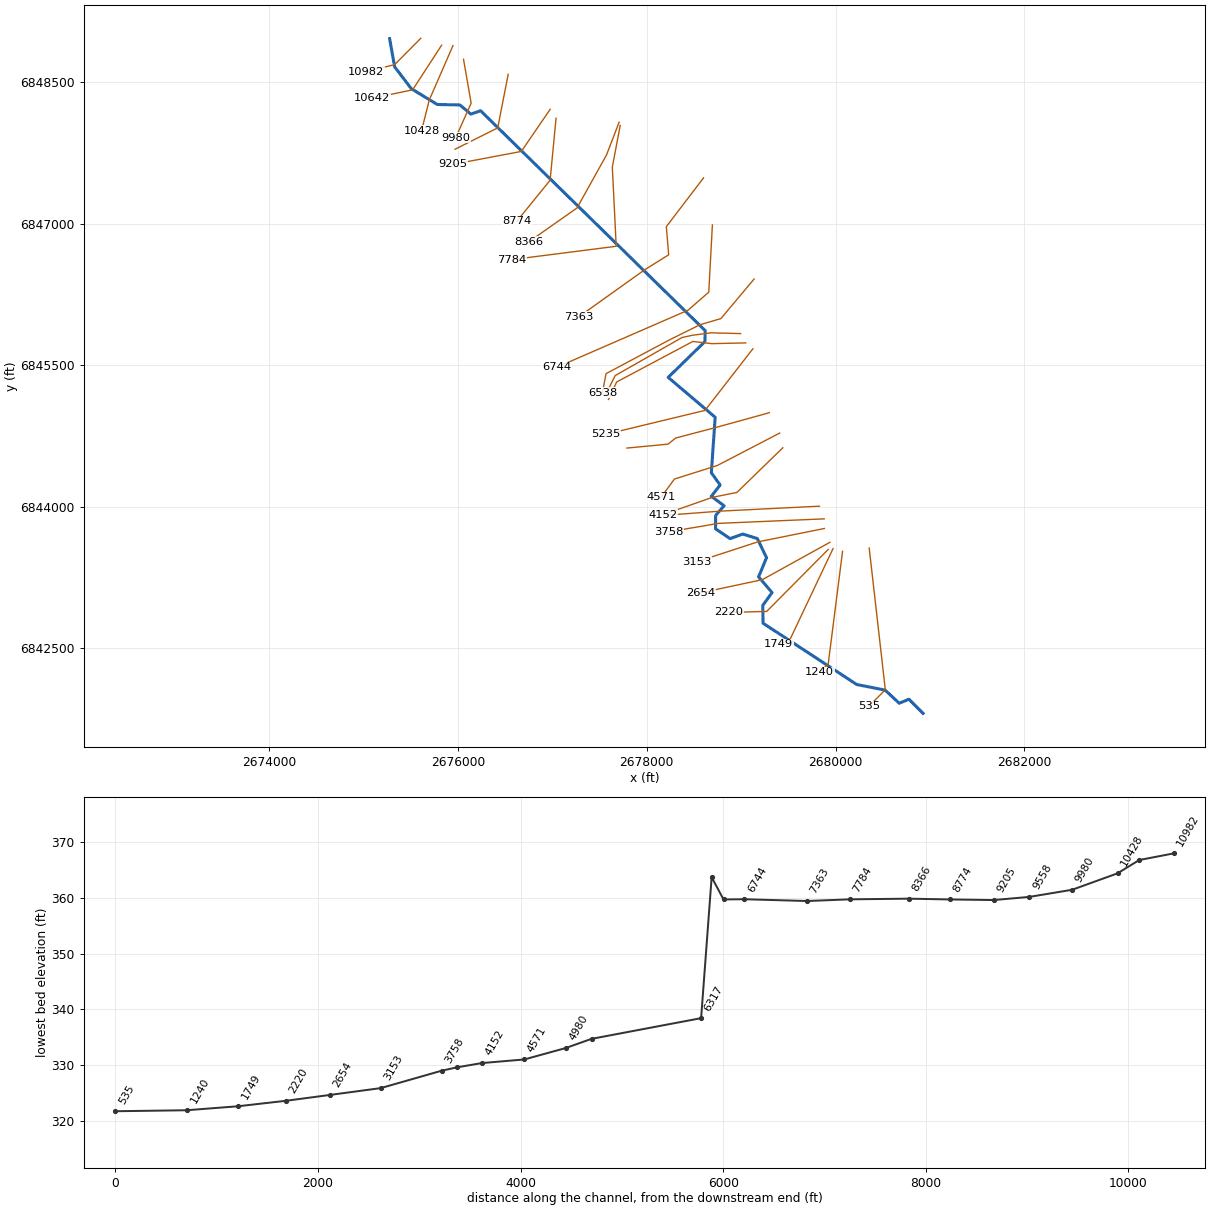
--- CCT2.prj (project) ---

Proj Title=CCT2 Base Level Engineering
Current Plan=p01
Default Exp/Contr=0.3,0.1
English Units
Geom File=g01
Flow File=f01
Plan File=p01
Y Axis Title=Elevation
X Axis Title(PF)=Main Channel Distance
X Axis Title(XS)=Station
BEGIN DESCRIPTION:
CCT2
END DESCRIPTION:
DSS Export Rating Curves= 0
DSS Export Rating Curve Sorted= 0
DSS Export Volume Flow Curves= 0
DXF OffsetX= 0
DXF OffsetY= 0
DXF ScaleX= 1
DXF ScaleY= 10

--- CCT2.p01 (plan) ---

Plan Title=Multiple Run
Short Identifier=Multiple
Geom File=g01
Flow File=f01
Subcritical Flow
K Sum by GR= 0
Std Step Tol= 0.01
Critical Tol= 0.01
Num of Std Step Trials= 20
Max Error Tol= 0.3
Flow Tol Ratio= 0.001
Split Flow NTrial= 30
Split Flow Tol= 0.02
Split Flow Ratio= 0.02
Log Output Level= 0
Friction Slope Method= 1
Unsteady Friction Slope Method= 2
Unsteady Bridges Friction Slope Method= 1
Parabolic Critical Depth
Global Vel Dist=  1 , 1 , 1
Global Log Level= 0
CheckData=True
Encroach Param= -1, 0, 0, 0
BEGIN DESCRIPTION:
Multiple Run
END DESCRIPTION:

--- CCT2.f01 (steady flow) ---

Flow Title=Multiple
Program Version=4.10
Number of Profiles= 7
Profile Names=10-year,25-year,50-year,1pct_min,100-year,1pct_plu,500-year
River Rch & RM=CCT2,Reach-1         ,10982
     388     504     594     348     693    1383     944
River Rch & RM=CCT2,Reach-1         ,8774
     573     761     911     540    1078    2150    1509
River Rch & RM=CCT2,Reach-1         ,7363
     676     906    1090     650    1296    2586    1833
River Rch & RM=CCT2,Reach-1         ,6317
     840    1142    1389     836    1669    3330    2410
Boundary for River Rch & Prof#=CCT2,Reach-1         , 1
Up Type= 0
Dn Type= 3
Dn Slope=0.005
Boundary for River Rch & Prof#=CCT2,Reach-1         , 2
Up Type= 0
Dn Type= 3
Dn Slope=0.005
Boundary for River Rch & Prof#=CCT2,Reach-1         , 3
Up Type= 0
Dn Type= 3
Dn Slope=0.005
Boundary for River Rch & Prof#=CCT2,Reach-1         , 4
Up Type= 0
Dn Type= 3
Dn Slope=0.005
Boundary for River Rch & Prof#=CCT2,Reach-1         , 5
Up Type= 0
Dn Type= 3
Dn Slope=0.005
Boundary for River Rch & Prof#=CCT2,Reach-1         , 6
Up Type= 0
Dn Type= 3
Dn Slope=0.005
Boundary for River Rch & Prof#=CCT2,Reach-1         , 7
Up Type= 0
Dn Type= 3
Dn Slope=0.005
DSS Import GetInterval= 0
DSS Import GetPeak= 0
DSS Import FillOption= 0

--- CCT2.g01 (geometry) ---

Geom Title=Existing Conditions
Program Version=4.10

River Reach=CCT2            ,Reach-1
Reach XY= 30
        2675276.        6848961.      2675329.75      6848662.55
      2675505.91      6848430.79      2675781.93      6848263.24
      2676020.14      6848258.93      2676136.64      6848161.65
      2676239.38      6848197.46      2678618.24      6845867.17
      2678615.57      6845751.21      2678226.53      6845371.69
       2678724.1       6844949.1      2678683.33       6844360.9
      2678776.46      6844231.16        2678683.      6844110.78
        2678819.      6844011.22      2678729.55      6843909.53
      2678727.97      6843766.67      2678882.11       6843662.8
      2679015.83       6843711.5      2679170.29      6843663.59
      2679268.25      6843460.91      2679183.84      6843257.73
       2679326.5      6843090.94      2679228.07      6842955.14
      2679231.21      6842766.45      2680223.58      6842116.54
      2680524.53      6842057.46      2680672.61      6841918.59
        2680776.        6841961.        2680926.        6841811.

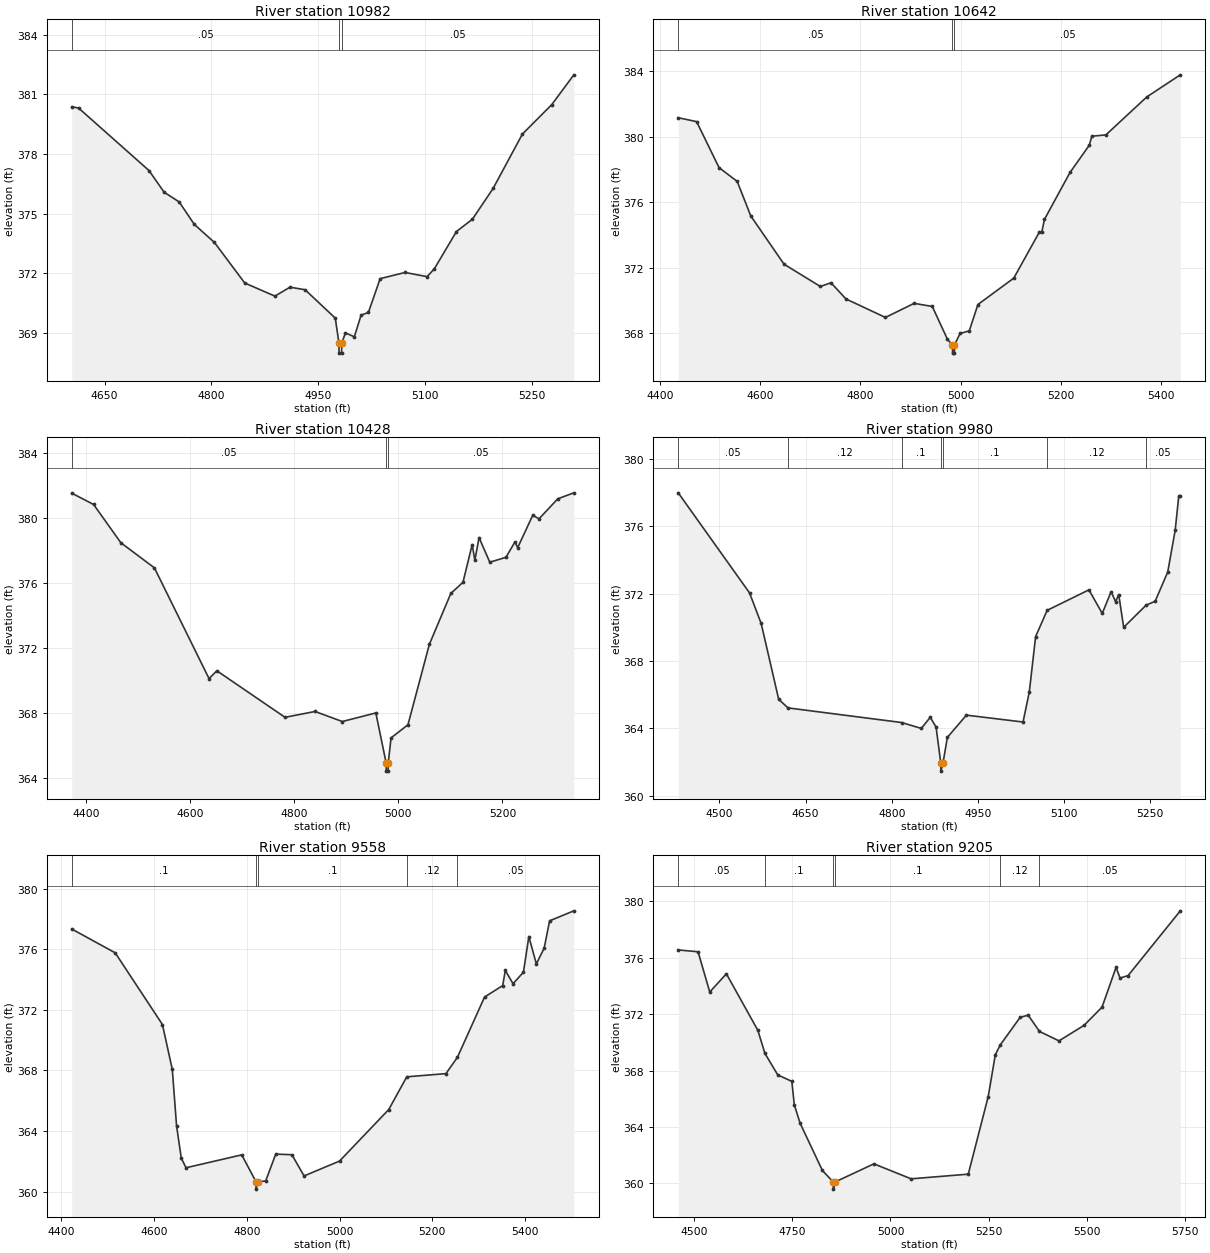
Type RM Length L Ch R = 1 ,10982   ,340,340,340
BEGIN DESCRIPTION:
CCT2 24.0
END DESCRIPTION:
XS GIS Cut Line= 3
      2675605.72      6848964.69      2675329.66      6848686.02
      2675025.95      6848610.99
#Sta/Elev= 30
  4603.8  380.38  4613.3  380.32  4712.3  377.17  4733.5  376.08  4754.7  375.59
  4775.9  374.46  4804.2  373.55  4846.7  371.51  4889.1  370.85  4910.3   371.3
  4931.5  371.17  4973.9  369.74    4979  368.48  4979.2  367.98  4982.7  367.98
    4983  368.48  4988.1     369  5000.6   368.8  5010.1  369.89  5020.4  370.03
  5036.9  371.73  5071.9  372.04  5102.8  371.83  5113.1  372.23    5144   374.1
  5166.4  374.72  5195.5  376.27  5236.7  379.01  5277.9  380.49  5308.9  381.99
#Mann= 3 ,-1 , 0
  4603.8     .05       0    4979     .04       0    4983     .05       0
Bank Sta=4979,4983
XS Rating Curve= 0 ,0
Exp/Cntr=0.3,0.1

Type RM Length L Ch R = 1 ,10642   ,214,214,214
BEGIN DESCRIPTION:
CCT2 23.0
END DESCRIPTION:
XS GIS Cut Line= 3
      2675827.05      6848891.74      2675519.95      6848419.16
      2675090.54      6848329.35
#Sta/Elev= 30
  4436.4  381.17  4473.1  380.93  4517.9  378.12  4554.1  377.28  4581.2  375.17
  4647.7  372.22  4720.2  370.86  4741.3  371.09  4771.2   370.1    4850  368.97
  4907.3  369.83  4943.6  369.64  4973.9  367.63  4983.9  367.29  4984.1  366.79
  4987.6  366.79  4987.9  367.29    4999  367.99  5017.4  368.15  5034.7  369.76
  5106.2  371.37  5157.1  374.17  5162.2  374.18  5167.5  374.96  5218.6  377.83
    5257  379.49  5262.1  380.04  5290.1  380.12  5371.8  382.44  5438.7  383.79
#Mann= 3 ,-1 , 0
  4436.4     .05       0  4983.9     .04       0  4987.9     .05       0
Bank Sta=4983.9,4987.9
XS Rating Curve= 0 ,0
Exp/Cntr=0.3,0.1

Type RM Length L Ch R = 1 ,10428   ,448,448,448
BEGIN DESCRIPTION:
CCT2 22.0
END DESCRIPTION:
XS GIS Cut Line= 3
      2675946.85      6848886.55      2675696.13      6848311.32
      2675613.89       6847984.4
#Sta/Elev= 30
  4372.5  381.55  4414.5  380.85  4466.8  378.49  4531.3  376.94  4636.2  370.11
  4651.3  370.59  4782.2  367.72  4839.9  368.08  4892.2  367.46  4956.7  367.99
  4976.5   364.9  4976.8   364.4  4980.3   364.4  4980.5   364.9  4985.9  366.45
  5018.4  367.26  5059.5  372.22  5100.7  375.36  5124.1  376.05  5141.8  378.38
  5146.9  377.41    5155  378.81  5175.6  377.29  5206.6  377.59    5224  378.54
  5229.2  378.19  5258.1  380.18  5270.3  379.97  5306.2   381.2  5337.1  381.57
#Mann= 3 ,-1 , 0
  4372.5     .05       0  4976.5     .04       0  4980.5     .05       0
Bank Sta=4976.5,4980.5
XS Rating Curve= 0 ,0
Exp/Cntr=0.3,0.1

Type RM Length L Ch R = 1 ,9980    ,422,422,422
BEGIN DESCRIPTION:
CCT2 21.0
END DESCRIPTION:
XS GIS Cut Line= 3
      2676058.82      6848743.31      2676139.55      6848277.17
      2675976.01      6847911.01
#Sta/Elev= 30
  4428.2     378  4552.3  372.05  4572.6  370.23  4603.1  365.72  4619.3  365.21
  4817.2  364.34  4851.4  363.99  4866.9  364.65  4877.1  364.07  4885.2  361.95
  4885.5  361.45  4889.2  361.95  4896.8  363.46  4929.9  364.78  5028.5  364.37
  5039.4  366.16  5050.4  369.45  5070.4  371.01  5143.2  372.23  5166.4  370.83
  5181.8  372.12  5189.6  371.53  5195.1  371.95  5203.7     370  5242.8  371.32
  5258.5  371.55  5280.4  373.29  5293.4  375.78  5299.6  377.81  5302.3  377.81
#Mann= 7 ,-1 , 0
  4428.2     .05       0  4619.3     .12       0  4817.2      .1       0
  4885.2     .07       0  4889.2      .1       0  5070.4     .12       0
  5242.8     .05       0
Bank Sta=4885.2,4889.2
XS Rating Curve= 0 ,0
Exp/Cntr=0.3,0.1

Type RM Length L Ch R = 1 ,9558    ,353,353,353
BEGIN DESCRIPTION:
CCT2 20.0
END DESCRIPTION:
XS GIS Cut Line= 3
       2676531.7      6848582.95      2676421.21      6848015.81
      2675969.19      6847789.53
#Sta/Elev= 30
  4422.2  377.33  4515.9  375.76  4617.8  371.03  4639.1  368.07  4648.3  364.35
  4658.5  362.21  4668.7  361.58  4788.9  362.43  4819.5  360.67  4819.8  360.17
  4823.5  360.67  4840.5   360.7  4862.3  362.48  4897.2  362.44  4923.4  361.04
  4999.9  362.02  5106.1  365.42    5145  367.58  5229.5  367.79  5254.4  368.87
  5312.8  372.84    5352   373.6  5357.6   374.6  5374.3  373.72  5396.7  374.48
  5408.4  376.83  5424.6  375.03  5441.4  376.06  5453.2  377.87  5505.5  378.53
#Mann= 5 ,-1 , 0
  4422.2      .1       0  4819.5     .07       0  4823.5      .1       0
    5145     .12       0  5254.4     .05       0
Bank Sta=4819.5,4823.5
XS Rating Curve= 0 ,0
Exp/Cntr=0.3,0.1

Type RM Length L Ch R = 1 ,9205    ,431,431,431
BEGIN DESCRIPTION:
Mapping XS 2704b3a0
END DESCRIPTION:
XS GIS Cut Line= 3
      2676976.36      6848212.27      2676670.86      6847766.15
      2675945.11      6847628.95
#Sta/Elev= 30
  4459.3  376.54  4509.8  376.41  4539.6  373.56    4582  374.85  4662.1  370.85
  4680.2  369.21  4712.9  367.69  4748.8  367.23  4754.9  365.59  4769.8  364.27
  4826.6  360.92  4854.4   360.1  4854.7   359.6  4858.4   360.1  4957.8  361.39
  5052.7  360.33  5198.3  360.66  5249.2  366.16  5267.2  369.11  5279.5   369.8
  5330.6  371.77    5351  371.92  5379.8  370.77  5429.4   370.1  5493.4   371.2
  5539.2  372.49  5574.9  375.31    5585  374.55  5605.4  374.72  5738.6  379.31
#Mann= 6 ,-1 , 0
  4459.3     .05       0  4680.2      .1       0  4854.4     .07       0
  4858.4      .1       0  5279.5     .12       0  5379.8     .05       0
Bank Sta=4854.4,4858.4
XS Rating Curve= 0 ,0
Exp/Cntr=0.3,0.1

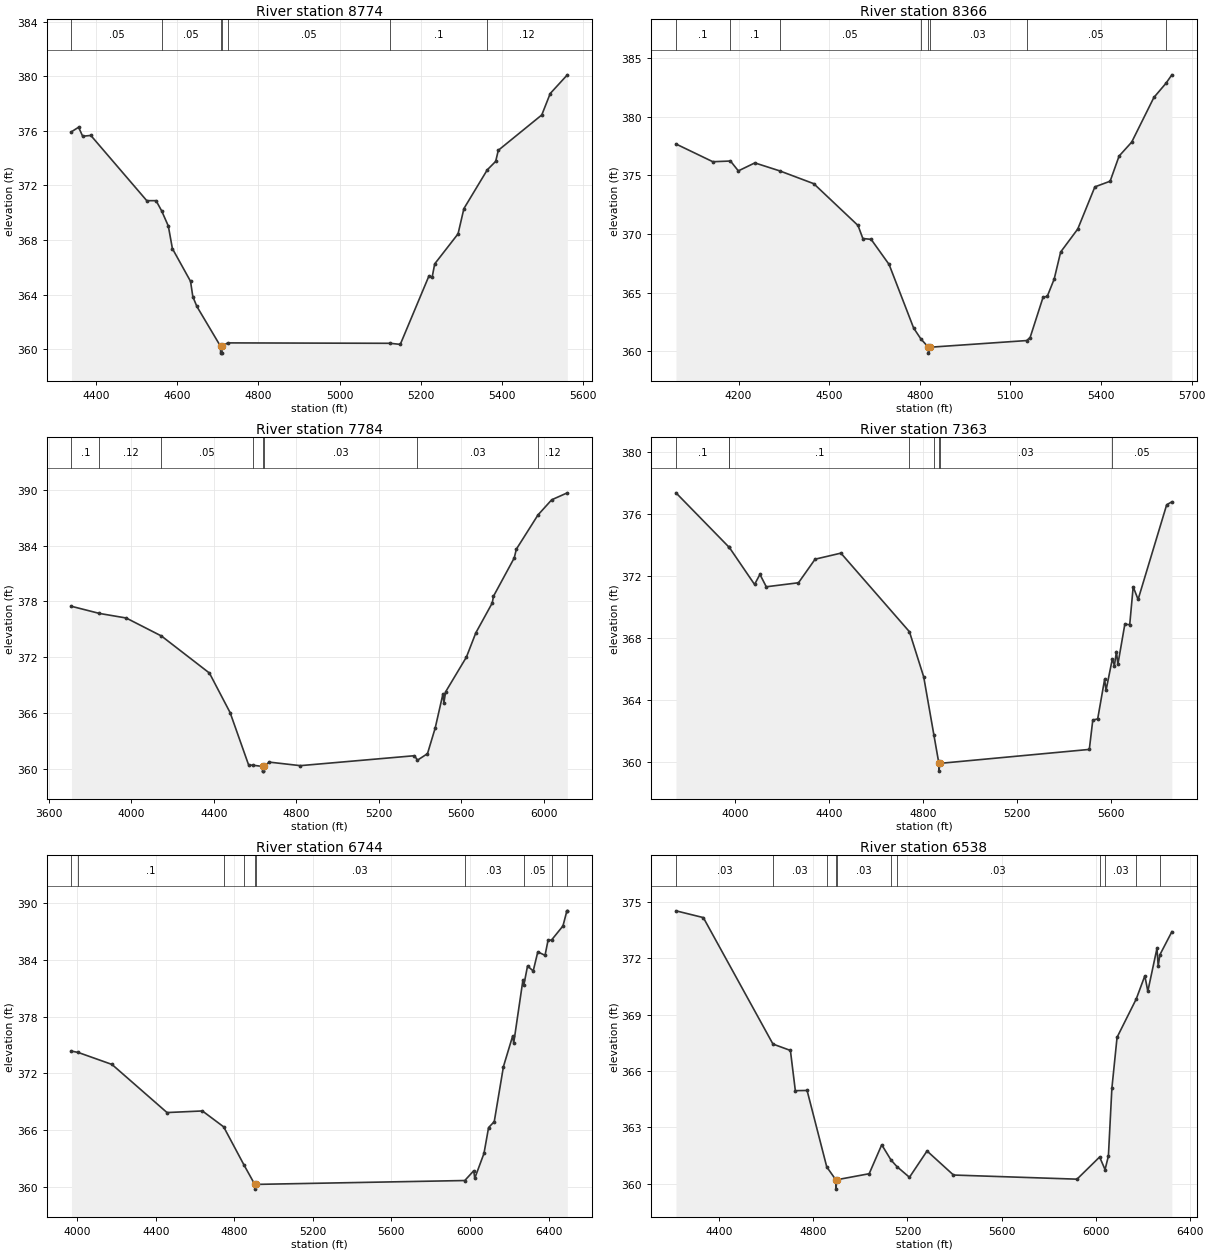
Type RM Length L Ch R = 1 ,8774    ,408,408,408
BEGIN DESCRIPTION:
CCT2 19.0
END DESCRIPTION:
XS GIS Cut Line= 3
      2677038.86       6848118.5        2676976.        6847461.
      2676622.67      6847025.37
#Sta/Elev= 30
  4339.5  375.93  4357.1  376.26  4367.1   375.6  4387.2  375.66    4525  370.88
  4547.9  370.88  4561.7  370.13  4578.1  369.02  4588.1  367.37  4632.8  364.97
  4638.4  363.85  4648.4  363.13  4706.7  360.21  4706.9  359.71  4710.4  359.71
  4710.7  360.21  4724.3  360.46  5124.6  360.43  5149.4  360.35  5219.8  365.35
  5227.8  365.26  5234.2  366.25  5291.7  368.45  5306.1   370.3  5363.7  373.14
  5384.4  373.76  5390.8  374.57  5497.9  377.16  5518.7  378.73  5560.9   380.1
#Mann= 7 ,-1 , 0
  4339.5     .05       0  4561.7     .05       0  4706.7     .05       0
  4710.7     .03       0  4724.3     .05       0  5124.6      .1       0
  5363.7     .12       0
Bank Sta=4706.7,4710.7
XS Rating Curve= 0 ,0
Exp/Cntr=0.3,0.1

Type RM Length L Ch R = 1 ,8366    ,582,582,582
BEGIN DESCRIPTION:
CCT2 18.0
END DESCRIPTION:
XS GIS Cut Line= 4
      2677706.67      6848075.19        2677573.       6847728.6
      2677261.08      6847167.14      2676747.22      6846806.05
#Sta/Elev= 30
  3992.7  377.66  4114.7  376.15  4173.1  376.21  4199.2  375.37  4253.8  376.05
  4336.2  375.37  4448.9  374.28  4595.4  370.72  4611.4  369.61  4638.8  369.54
  4698.3   367.4  4779.5  361.99  4803.2  361.07  4828.4  360.35  4828.7  359.85
  4832.4  360.35  5153.5  360.92  5165.2  361.18  5208.2  364.62  5221.9  364.68
  5244.9  366.16  5266.3  368.46  5322.9  370.42  5379.6  374.01  5430.1  374.49
  5459.7  376.63  5501.5  377.82  5574.9  381.62  5614.6  382.82  5634.5  383.55
#Mann= 8 ,-1 , 0
  3992.7      .1       0  4173.1      .1       0  4336.2     .05       0
  4803.2     .03       0  4828.4     .03       0  4832.4     .03       0
  5153.5     .05       0  5614.6     .12       0
Bank Sta=4828.4,4832.4
XS Rating Curve= 0 ,0
Exp/Cntr=0.3,0.1

Type RM Length L Ch R = 1 ,7784    ,421,421,421
BEGIN DESCRIPTION:
CCT2 17.0
END DESCRIPTION:
XS GIS Cut Line= 4
      2677718.41      6848041.63      2677634.82      6847600.74
        2677676.        6846761.      2676570.68      6846619.78
#Sta/Elev= 30
  3710.5  377.48  3846.4  376.71  3975.8  376.22  4146.8  374.28  4379.3  370.29
  4479.4  366.04  4569.5  360.38  4589.2  360.37  4637.6  360.23  4637.8  359.73
  4641.3  359.73  4641.6  360.23  4669.6   360.7  4819.8  360.32    5373  361.39
  5387.9  360.91  5436.3  361.61  5473.8  364.38    5511  368.02    5516   367.1
  5524.2  368.27    5625  372.01  5670.6  374.62  5750.3  377.84  5756.1  378.56
  5856.9  382.69    5867  383.63    5972  387.32  6038.4  388.95  6114.3   389.7
#Mann= 8 ,-1 , 0
  3710.5      .1       0  3846.4     .12       0  4146.8     .05       0
  4589.2     .03       0  4637.6     .03       0  4641.6     .03       0
  5387.9     .03       0    5972     .12       0
Bank Sta=4637.6,4641.6
XS Rating Curve= 0 ,0
Exp/Cntr=0.3,0.1

Type RM Length L Ch R = 1 ,7363    ,619,619,619
BEGIN DESCRIPTION:
CCT2 16.0
END DESCRIPTION:
XS GIS Cut Line= 5
      2678600.98      6847485.97      2678206.72      6846969.17
      2678231.86      6846670.91        2677976.        6846511.
      2677275.99      6846010.99
#Sta/Elev= 30
  3749.2  377.38    3976  373.86  3976.3  373.86  4083.8  371.47  4106.6  372.12
  4133.7  371.32  4270.8  371.58  4341.5   373.1  4451.4  373.49  4743.2  368.42
  4803.9  365.51  4847.1  361.78  4868.5  359.93  4868.8  359.43  4872.6  359.93
    5509  360.83  5523.8  362.72  5544.7   362.8  5574.1  365.34  5580.3  364.65
    5607  366.66  5615.9  366.24  5624.5  367.14  5630.7  366.32  5660.2   368.9
  5681.1  368.88  5695.8  371.32  5716.7   370.5  5838.4  376.61  5860.5   376.8
#Mann= 8 ,-1 , 0
  3749.2      .1       0    3976     .12       0  3976.3      .1       0
  4743.2     .03       0  4847.1     .03       0  4868.5     .03       0
  4872.6     .03       0    5607     .05       0
Bank Sta=4868.5,4872.6
XS Rating Curve= 0 ,0
Exp/Cntr=0.3,0.1

Type RM Length L Ch R = 1 ,6744    ,206,206,206
BEGIN DESCRIPTION:
Mapping XS 19cb1012
END DESCRIPTION:
XS GIS Cut Line= 4
       2678694.5      6846986.95      2678656.31      6846275.13
      2678437.56      6846084.15      2677041.72      6845476.51
#Sta/Elev= 30
  3970.4  374.35  4004.5  374.21  4176.7  372.94  4457.1  367.85  4637.3  368.02
  4745.5  366.34  4849.5  362.29    4904  360.25  4904.5  359.75  4908.7  360.25
  5973.6  360.66  6019.1  361.69  6024.5   360.9  6071.4  363.53  6094.8  366.26
  6123.7  366.89  6170.6  372.72  6217.5  375.95  6222.9  375.22  6269.8  381.87
  6274.1  381.31  6293.2  383.35  6322.1  382.83  6345.5  384.85  6382.3  384.48
  6397.8  386.08  6415.4   386.1  6473.6  387.59  6493.7  389.19    6496  389.19
#Mann= 10 ,-1 , 0
  3970.4     .12       0  4004.5      .1       0  4745.5     .03       0
  4849.5     .03       0    4904     .03       0  4908.7     .03       0
  5973.6     .03       0  6274.1     .05       0  6415.4      .1       0
  6493.7     .05       0
Bank Sta=4904,4908.7
XS Rating Curve= 0 ,0
Exp/Cntr=0.3,0.1

Type RM Length L Ch R = 1 ,6538    ,117,117,117
BEGIN DESCRIPTION:
Mapping XS 2259a1cc
END DESCRIPTION:
XS GIS Cut Line= 6
      2679136.34      6846414.01      2678784.78      6845994.74
      2678563.42      6845929.64       2678237.9      6845768.18
      2677568.63      6845411.41      2677529.56      6845210.85
#Sta/Elev= 30
  4217.7  374.52  4333.8  374.16  4629.2  367.43  4703.2  367.09  4724.1  364.95
    4774  364.96  4857.5  360.89  4895.7  360.21  4896.2  359.71  4900.4  360.21
  5037.4  360.53  5090.7  362.07    5130  361.26  5155.1  360.91  5208.3  360.34
  5282.9  361.74  5395.1  360.46  5919.2  360.24  6015.2  361.42  6038.2  360.75
  6052.4  361.47  6067.2  365.08  6089.2  367.79  6170.6  369.83    6207  371.06
  6219.7  370.24  6258.6  372.53  6263.7  371.58  6270.8  372.18  6321.7  373.41
#Mann= 11 ,-1 , 0
  4217.7     .03       0  4629.2     .03       0  4857.5     .03       0
  4895.7     .03       0  4900.4     .03       0    5130     .03       0
  5155.1     .03       0  6015.2     .03       0  6038.2     .03       0
  6170.6     .05       0  6270.8     .12       0
Bank Sta=4895.7,4900.4
XS Rating Curve= 0 ,0
Exp/Cntr=0.3,0.1

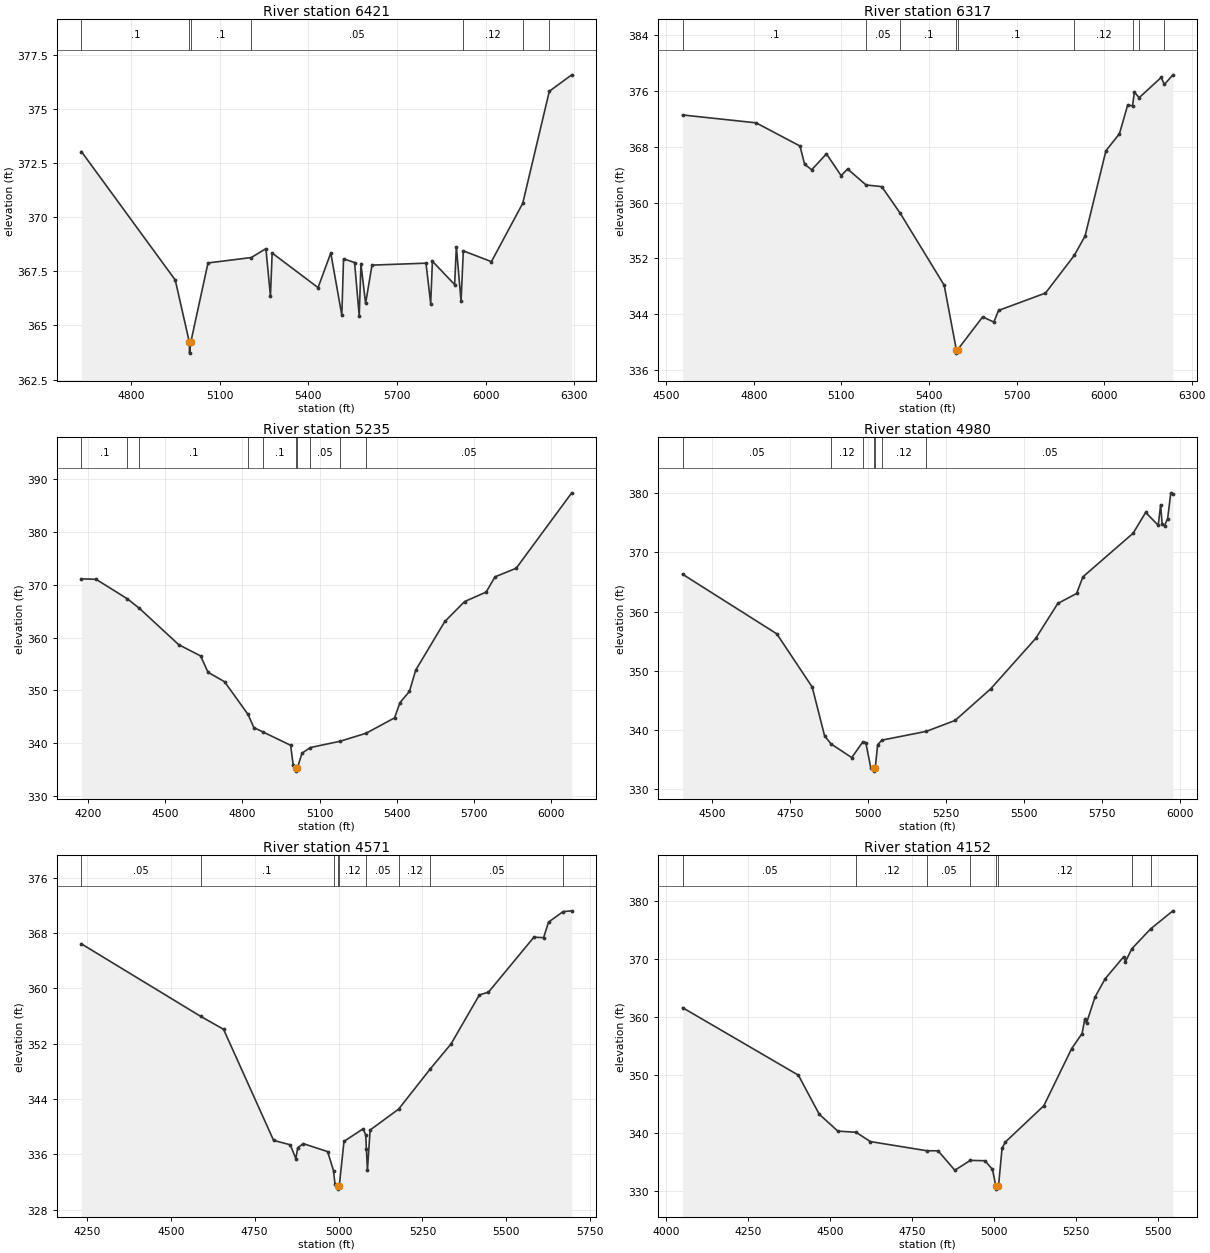
Type RM Length L Ch R = 1 ,6421    ,104,104,104
BEGIN DESCRIPTION:
Mapping XS 38124e6f
END DESCRIPTION:
XS GIS Cut Line= 6
      2678993.12      6845835.89      2678680.61       6845843.7
      2678480.09      6845817.66      2678373.32      6845794.22
      2677664.99      6845390.58      2677566.87      6845194.34
#Sta/Elev= 30
  4632.8  373.04  4950.2   367.1    4998  364.22  4998.5  363.72  5002.7  364.22
    5061  367.89  5207.3  368.14  5256.9  368.55  5272.3  366.35    5278  368.35
  5433.3  366.75  5476.4  368.35  5513.8  365.47  5519.5  368.08  5556.9  367.91
  5572.6  365.44  5578.4  367.84  5594.2  366.02  5615.8  367.79  5798.5  367.88
  5814.4  366.01  5820.2  367.97  5895.4  366.89  5901.2  368.64  5917.1  366.12
  5924.8  368.45  6019.8  367.95  6125.8  370.65  6215.7  375.83  6291.6  376.59
#Mann= 7 ,-1 , 0
  4632.8      .1       0    4998     .07       0  5002.7      .1       0
  5207.3     .05       0  5924.8     .12       0  6125.8     .05       0
  6215.7     .12       0
Bank Sta=4998,5002.7
XS Rating Curve= 0 ,0
Exp/Cntr=0.3,0.1

Type RM Length L Ch R = 1 ,6317    ,1082,1082,1082
BEGIN DESCRIPTION:
Mapping XS 5860f9b0
END DESCRIPTION:
XS GIS Cut Line= 5
      2679047.78      6845736.93      2678688.42      6845729.12
       2678487.9      6845752.56      2677680.61      6845322.87
      2677594.69      6845138.01
#Sta/Elev= 30
  4556.1  372.57  4807.9  371.44  4958.3  368.11  4974.1  365.49  4998.5  364.71
  5048.9  366.99  5099.2  363.86  5121.3  364.82  5184.7  362.52  5238.2  362.29
  5301.7  358.46  5452.2  348.14  5493.8  338.89  5494.3  338.39  5498.5  338.89
    5584  343.59  5622.3  342.85  5638.6  344.52  5799.3  347.01  5897.8  352.41
  5934.9   355.2  6006.4  367.44  6052.7  369.88  6081.1  374.03  6097.4  373.86
  6103.9  375.85  6120.2  375.05  6195.5  377.95  6206.6  376.95  6235.8  378.33
#Mann= 9 ,-1 , 0
  4556.1      .1       0  5184.7     .05       0  5301.7      .1       0
  5493.8     .07       0  5498.5      .1       0  5897.8     .12       0
  6097.4     .05       0  6120.2     .12       0  6206.6     .05       0
Bank Sta=5493.8,5498.5
XS Rating Curve= 0 ,0
Exp/Cntr=0.3,0.1

Type RM Length L Ch R = 1 ,5235    ,255,255,255
BEGIN DESCRIPTION:
Mapping XS f03bf9ab
END DESCRIPTION:
XS GIS Cut Line= 3
       2679123.3      6845674.41      2678616.57      6845021.85
      2677566.06      6844768.19
#Sta/Elev= 30
  4173.8  371.14  4230.8  371.05  4352.4  367.35  4399.6  365.53  4552.1  358.65
  4637.2  356.52  4666.1  353.42  4730.4  351.63  4821.8  345.42  4844.4  342.93
  4881.1  342.07  4987.4  339.57  4997.4  335.81  5008.4  335.17    5009  334.67
  5013.3  335.17  5031.5  338.07    5064  339.14    5180  340.34  5281.2  341.86
  5391.5  344.77  5412.8  347.67  5449.5  349.79  5473.8  353.82    5587  363.05
  5664.1  366.83  5747.8  368.63  5782.4  371.52  5864.7  373.15  6080.7  387.45
#Mann= 10 ,-1 , 0
  4173.8      .1       0  4352.4     .12       0  4399.6      .1       0
  4821.8     .05       0  4881.1      .1       0  5008.4     .07       0
  5013.3      .1       0    5064     .05       0    5180     .12       0
  5281.2     .05       0
Bank Sta=5008.4,5013.3
XS Rating Curve= 0 ,0
Exp/Cntr=0.3,0.1

Type RM Length L Ch R = 1 ,4980    ,409,409,409
BEGIN DESCRIPTION:
Mapping XS 2dcfb626
END DESCRIPTION:
XS GIS Cut Line= 5
      2679297.84      6844997.36       2678732.7       6844841.1
      2678305.61      6844729.12      2678224.88      6844664.01
      2677789.23      6844622.52
#Sta/Elev= 30
  4406.8  366.31  4708.2  356.24  4821.6  347.24  4861.1  339.01  4881.7  337.62
  4948.2  335.31  4983.7  337.98  4993.1  337.84  5009.2  333.55  5018.2  333.52
  5018.9  333.02  5023.2  333.52  5031.1  337.49  5044.7  338.26  5187.1  339.75
  5279.2   341.6  5392.9  346.94  5536.8  355.46  5607.6  361.37  5667.8  363.06
  5687.9  365.87  5848.7  373.25  5888.8  376.77    5929  374.59  5936.7  378.02
  5941.7  374.73  5949.1  374.53  5959.2  375.73  5969.2  380.08    5976  379.93
#Mann= 7 ,-1 , 0
  4406.8     .05       0  4881.7     .12       0  4983.7      .1       0
  5018.2     .07       0  5023.2      .1       0  5044.7     .12       0
  5187.1     .05       0
Bank Sta=5018.2,5023.2
XS Rating Curve= 0 ,0
Exp/Cntr=0.3,0.1

Type RM Length L Ch R = 1 ,4571    ,419,419,419
BEGIN DESCRIPTION:
Mapping XS 855e984b
END DESCRIPTION:
XS GIS Cut Line= 4
      2679407.16       6844781.2      2678745.72      6844437.45
      2678292.59      6844294.22      2678150.17      6844100.01
#Sta/Elev= 30
  4233.7  366.44  4588.7  355.97  4657.3  354.09  4806.5  338.02  4856.3  337.38
  4872.8  335.38  4878.4  336.94  4894.9  337.55  4967.5   336.4  4985.1  333.65
  4989.3  331.76  4997.3  331.47  4997.9  330.97  5002.4  331.47  5016.3  337.88
  5073.2  339.69    5081  338.82  5083.1  336.77  5086.2  333.74  5094.2  339.52
  5179.1  342.54  5273.9  348.38  5335.4  351.97  5419.9  359.06    5447  359.46
  5582.4  367.41  5611.3  367.34    5626  369.59  5669.6  371.11  5695.2  371.22
#Mann= 9 ,-1 , 0
  4233.7     .05       0  4588.7      .1       0  4985.1     .12       0
  4997.3     .07       0  5002.4     .12       0  5083.1     .05       0
  5179.1     .12       0  5273.9     .05       0  5669.6    .075       0
Bank Sta=4997.3,5002.4
XS Rating Curve= 0 ,0
Exp/Cntr=0.3,0.1

Type RM Length L Ch R = 1 ,4152    ,243,243,243
BEGIN DESCRIPTION:
Mapping XS a4fc7197
END DESCRIPTION:
XS GIS Cut Line= 4
      2679440.19      6844625.42      2678954.05       6844152.3
      2678693.63      6844100.21      2678174.98      6843917.92
#Sta/Elev= 30
  4050.6  361.56  4403.3  349.94  4466.8  343.22  4523.4  340.31    4579  340.11
  4622.4  338.51  4794.4  336.93    4829  336.92  4879.9  333.57  4927.1  335.27
  4971.7  335.21  4994.5  333.73    5005  330.82  5005.7  330.32  5010.1  330.82
  5013.2     331  5023.8  337.33  5033.3   338.4    5151  344.67  5235.8  354.51
  5267.6  357.11  5275.8  359.58  5281.1   358.9  5306.8  363.36  5337.8  366.53
  5394.4  370.33  5399.7  369.47  5418.9  371.69  5476.7  375.14  5544.3  378.23
#Mann= 8 ,-1 , 0
  4050.6     .05       0    4579     .12       0  4794.4     .05       0
  4927.1     .12       0    5005     .07       0  5010.1     .12       0
  5418.9    .075       0  5476.7     .12       0
Bank Sta=5005,5010.1
XS Rating Curve= 0 ,0
Exp/Cntr=0.3,0.1

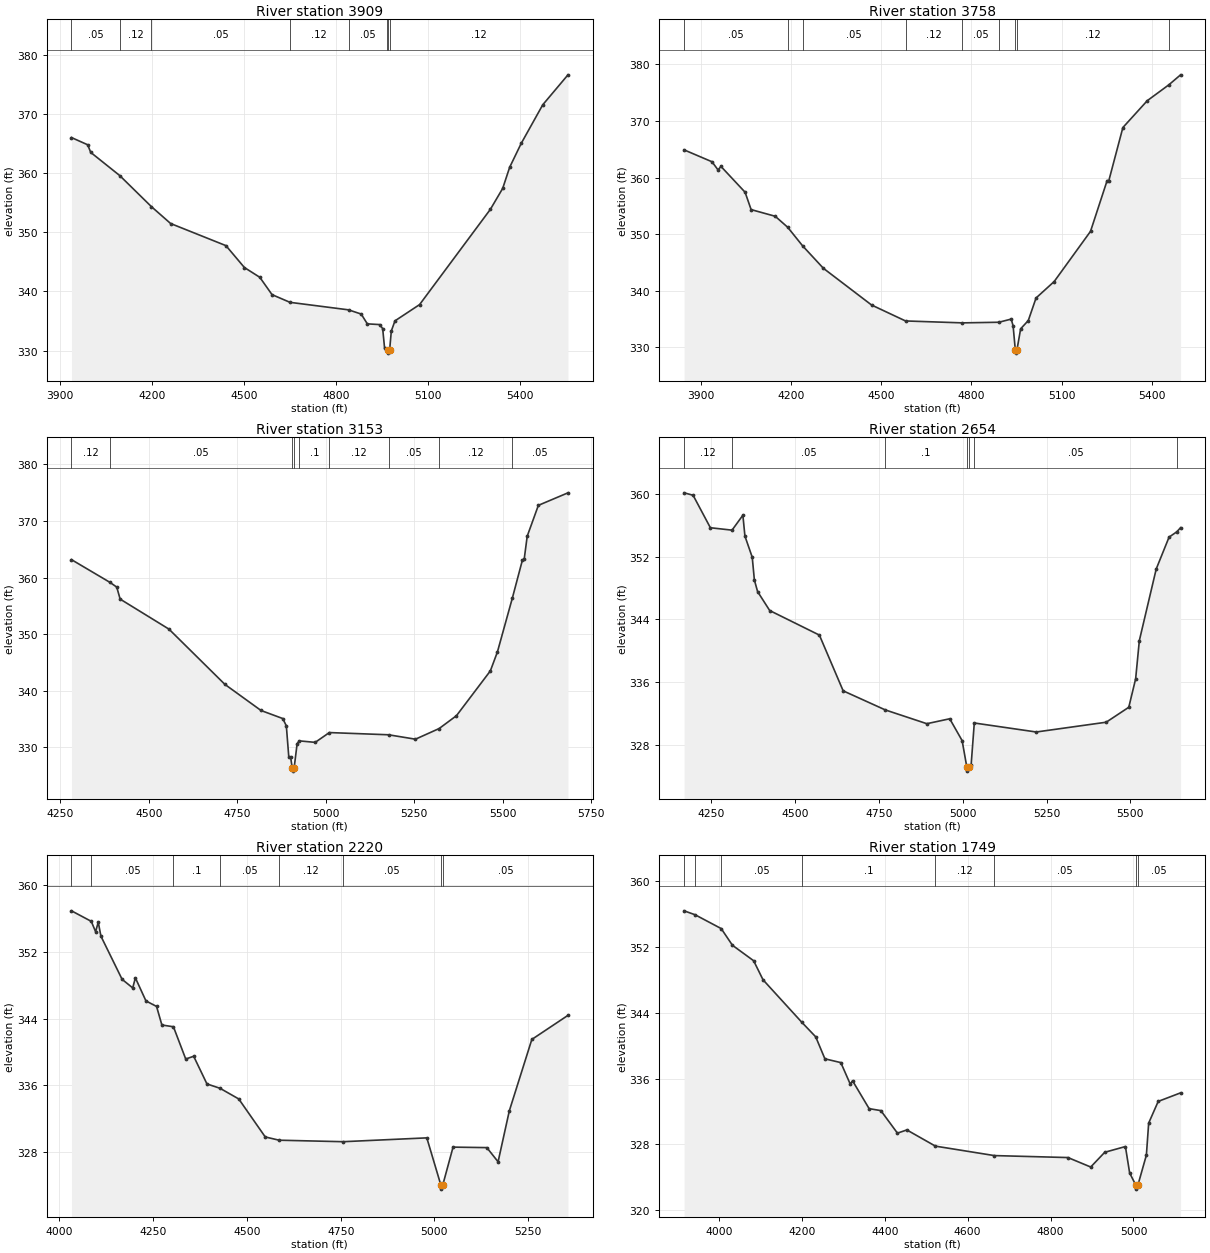
Type RM Length L Ch R = 1 ,3909    ,151,151,151
BEGIN DESCRIPTION:
Mapping XS da19db70
END DESCRIPTION:
XS GIS Cut Line= 3
      2679828.59      6844006.89      2678784.78      6843954.81
      2678214.03      6843911.41
#Sta/Elev= 30
  3938.5  366.02  3991.2   364.8  4001.2  363.51  4095.5   359.6    4199  354.33
  4261.5  351.48  4441.7  347.74  4501.8  344.04  4551.9  342.39  4591.9  339.45
  4650.4  338.15  4841.1  336.88  4882.3  336.17  4902.3  334.51  4942.3  334.39
  4952.3  333.71  4958.6  330.38  4965.4  330.23  4969.8  330.06  4970.5  329.56
  4974.9  330.06  4980.5  333.31  4992.4  335.02  5072.6  337.77  5303.3  353.89
  5343.4  357.43    5366  360.99  5403.6  365.03  5473.8  371.56    5556  376.63
#Mann= 8 ,-1 , 0
  3938.5     .05       0  4095.5     .12       0    4199     .05       0
  4650.4     .12       0  4841.1     .05       0  4965.4     .12       0
  4969.8     .07       0  4974.9     .12       0
Bank Sta=4969.8,4974.9
XS Rating Curve= 0 ,0
Exp/Cntr=0.3,0.1

Type RM Length L Ch R = 1 ,3758    ,605,605,605
BEGIN DESCRIPTION:
Mapping XS 8f8e2c47
END DESCRIPTION:
XS GIS Cut Line= 3
      2679878.48      6843872.35      2678760.91       6843824.6
      2678236.87      6843735.82
#Sta/Elev= 30
  3845.5   364.9  3938.1   362.8  3958.1  361.37  3968.1  361.97  4048.2  357.41
  4068.2  354.34  4148.3  353.16  4189.7  351.22  4239.5  347.92  4308.4  343.96
  4468.5  337.47  4581.4  334.65  4770.7  334.31  4891.6  334.42  4932.7  334.98
    4939  333.77  4946.4  329.46  4947.1  328.96  4951.5  329.46    4964  333.26
  4989.4  334.72  5015.2  338.71  5075.5  341.62  5196.2  350.49  5251.5  359.48
  5256.6  359.36  5303.8  368.85  5384.9   373.6  5456.5   376.4  5495.6  378.17
#Mann= 9 ,-1 , 0
  3845.5     .05       0  4189.7     .12       0  4239.5     .05       0
  4581.4     .12       0  4770.7     .05       0  4891.6     .12       0
  4946.4     .07       0  4951.5     .12       0  5456.5     .05       0
Bank Sta=4946.4,4951.5
XS Rating Curve= 0 ,0
Exp/Cntr=0.3,0.1

Type RM Length L Ch R = 1 ,3153    ,499,499,499
BEGIN DESCRIPTION:
Mapping XS d4dec6d5
END DESCRIPTION:
XS GIS Cut Line= 4
      2679880.71      6843770.35       2679277.4      6843648.82
      2679177.57      6843629.29      2678526.57      6843416.63
#Sta/Elev= 30
    4282  363.17  4390.8  359.15  4409.8  358.32  4419.4   356.2  4557.2   350.9
  4715.2  341.14  4817.2  336.53  4878.5  335.11  4888.7  333.82  4895.6  328.34
  4900.7  328.34  4905.4  326.32  4906.1  325.82  4910.6  326.32  4919.2  330.69
  4925.8  331.16  4970.2   330.9  5010.2  332.63  5177.2  332.24  5253.3  331.46
  5320.2  333.34  5369.1  335.61  5464.8  343.52  5484.7  346.86  5526.8  356.35
  5555.2  363.06  5560.4  363.26  5568.9  367.31  5600.4  372.76    5684  374.97
#Mann= 9 ,-1 , 0
    4282     .12       0  4390.8     .05       0  4905.4     .07       0
  4910.6     .05       0  4925.8      .1       0  5010.2     .12       0
  5177.2     .05       0  5320.2     .12       0  5526.8     .05       0
Bank Sta=4905.4,4910.6
XS Rating Curve= 0 ,0
Exp/Cntr=0.3,0.1

Type RM Length L Ch R = 1 ,2654    ,434,434,434
BEGIN DESCRIPTION:
Mapping XS ebb8efd3
END DESCRIPTION:
XS GIS Cut Line= 3
      2679939.45      6843624.08      2679224.19      6843228.25
      2678574.86      6843089.36
#Sta/Elev= 30
  4168.3  360.16  4195.1  359.85  4246.7   355.7  4311.3  355.39  4343.7   357.3
  4349.8  354.63  4371.6  351.93    4378  349.02  4387.6  347.54  4423.7  345.12
    4572  341.98  4642.9  334.86  4768.7  332.42  4892.6  330.66  4960.9  331.29
  4997.9   328.5    5012   325.1  5012.7   324.6  5017.2   325.1  5024.8   325.4
  5034.2  330.75  5219.1   329.6  5427.8  330.85  5495.2  332.76  5515.7   336.4
  5526.7  341.28  5577.1  350.43  5615.4   354.5  5638.5  355.18  5649.8  355.71
#Mann= 7 ,-1 , 0
  4168.3     .12       0  4311.3     .05       0  4768.7      .1       0
    5012     .07       0  5017.2      .1       0  5034.2     .05       0
  5638.5    .075       0
Bank Sta=5012,5017.2
XS Rating Curve= 0 ,0
Exp/Cntr=0.3,0.1

Type RM Length L Ch R = 1 ,2220    ,471,471,471
BEGIN DESCRIPTION:
Mapping XS 0cfa102b
END DESCRIPTION:
XS GIS Cut Line= 3
      2679920.35      6843547.56      2679269.33      6842891.33
      2678869.64      6842880.95
#Sta/Elev= 30
    4032  356.94  4084.7  355.68  4096.3  354.44  4103.4  355.58  4110.5   353.9
    4167  348.72  4195.3  347.69  4202.4   348.9  4230.6  346.13  4258.9  345.47
  4273.1  343.24  4303.9  343.03  4336.7  339.16  4357.9  339.49  4393.3  336.17
  4428.1  335.65  4478.1  334.37  4548.8  329.81  4585.8  329.42  4756.5  329.24
  4979.7   329.7  5017.1  324.05  5017.8  323.55  5022.3  324.05  5049.7  328.59
  5139.8  328.53  5169.8  326.83  5199.8  332.95  5259.8  341.51  5356.2   344.4
#Mann= 8 ,-1 , 0
    4032     .12       0  4084.7     .05       0  4303.9      .1       0
  4428.1     .05       0  4585.8     .12       0  4756.5     .05       0
  5017.1     .03       0  5022.3     .05       0
Bank Sta=5017.1,5022.3
XS Rating Curve= 0 ,0
Exp/Cntr=0.3,0.1

Type RM Length L Ch R = 1 ,1749    ,509,509,509
BEGIN DESCRIPTION:
Mapping XS 0345afe5
END DESCRIPTION:
XS GIS Cut Line= 3
      2679972.46      6843558.01      2679519.33      6842599.66
      2679394.31      6842542.36
#Sta/Elev= 30
    3916  356.42  3942.6  355.94  4005.5  354.26  4032.6  352.23  4083.7  350.35
  4106.4  348.03    4200  342.86  4233.5  341.09  4255.6  338.42    4294  337.96
  4316.8  335.34  4322.3  335.75  4362.3  332.36  4390.6  332.12  4430.6  329.38
  4453.3  329.77  4522.2   327.8  4664.3  326.65  4841.9  326.41  4896.8  325.26
  4930.6  327.05  4980.5  327.75  4990.7  324.54  5005.4  323.07  5006.2  322.57
  5010.7  323.07  5031.1  326.71  5036.6   330.6  5059.6  333.24  5113.6  334.28
#Mann= 8 ,-1 , 0
    3916      .1       0  3942.6     .12       0  4005.5     .05       0
    4200      .1       0  4522.2     .12       0  4664.3     .05       0
  5005.4     .03       0  5010.7     .05       0
Bank Sta=5005.4,5010.7
XS Rating Curve= 0 ,0
Exp/Cntr=0.3,0.1

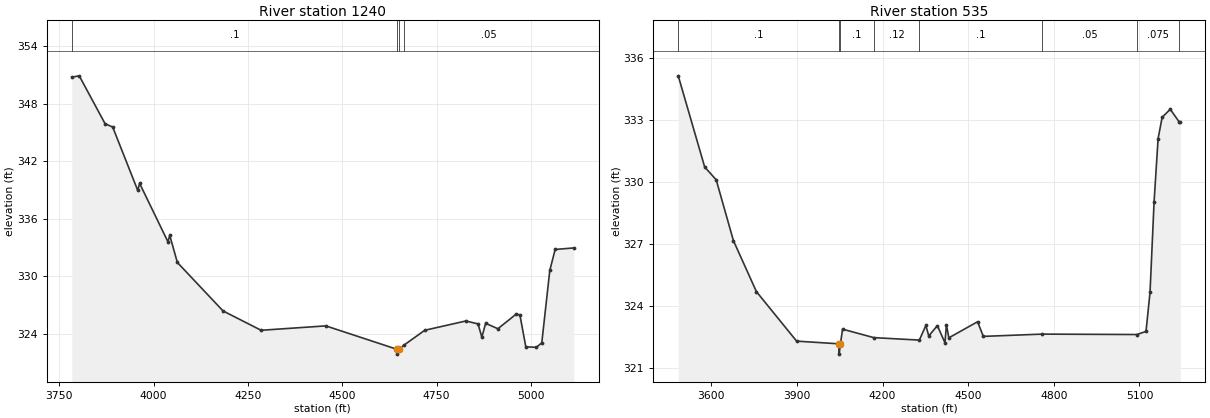
Type RM Length L Ch R = 1 ,1240    ,705,705,705
BEGIN DESCRIPTION:
Mapping XS 42681449
END DESCRIPTION:
XS GIS Cut Line= 3
      2680073.15      6843528.49      2679921.24      6842334.91
      2679831.66      6842245.32
#Sta/Elev= 30
  3783.5  350.77  3803.3  350.91  3871.7  345.91  3891.9  345.56  3958.2  338.95
  3963.2  339.68  4038.1  333.59  4043.1  334.24  4063.2  331.42  4184.2  326.36
    4285  324.34  4456.4   324.8  4645.3  322.35    4646  321.85  4650.6  322.35
  4663.8   322.8  4718.5  324.34  4827.2  325.31  4859.6  325.01  4869.7  323.62
  4879.8  325.07  4912.2   324.5  4960.4  326.02  4970.5  325.95  4986.2  322.61
  5014.4  322.56  5028.5  323.04  5049.7  330.59  5063.9  332.78  5113.4  332.94
#Mann= 4 ,-1 , 0
  3783.5      .1       0  4645.3     .03       0  4650.6      .1       0
  4663.8     .05       0
Bank Sta=4645.3,4650.6
XS Rating Curve= 0 ,0
Exp/Cntr=0.3,0.1

Type RM Length L Ch R = 1 ,535     ,0,0,0
BEGIN DESCRIPTION:
CCT2 1.0
END DESCRIPTION:
XS GIS Cut Line= 3
      2680355.27      6843563.16        2680526.        6842061.
      2680351.01      6841886.01
#Sta/Elev= 30
  3483.9  335.16  3576.6  330.74  3616.9  330.12  3677.3  327.17  3757.8   324.7
  3898.7   322.3    4047  322.17  4047.8  321.67  4052.3  322.17  4059.7  322.88
  4169.1  322.47  4328.8  322.35  4351.6  323.06  4361.7  322.55  4391.9  323.05
  4418.6  322.22  4423.6   323.1  4432.1  322.46  4532.8  323.24  4552.9  322.53
  4758.8  322.64  5090.9  322.62    5123  322.77  5137.1  324.67  5151.3  329.05
  5165.4  332.12  5179.6  333.15  5207.9  333.54    5239  332.93  5243.2  332.93
#Mann= 8 ,-1 , 0
  3483.9      .1       0    4047     .03       0  4052.3      .1       0
  4169.1     .12       0  4328.8      .1       0  4758.8     .05       0
  5090.9    .075       0    5239     .05       0
Bank Sta=4047,4052.3
XS Rating Curve= 0 ,0
Exp/Cntr=0.3,0.1

Chan Stop Cuts=-1
Use User Specified Reach Order=0
Composite Channel Slope=5