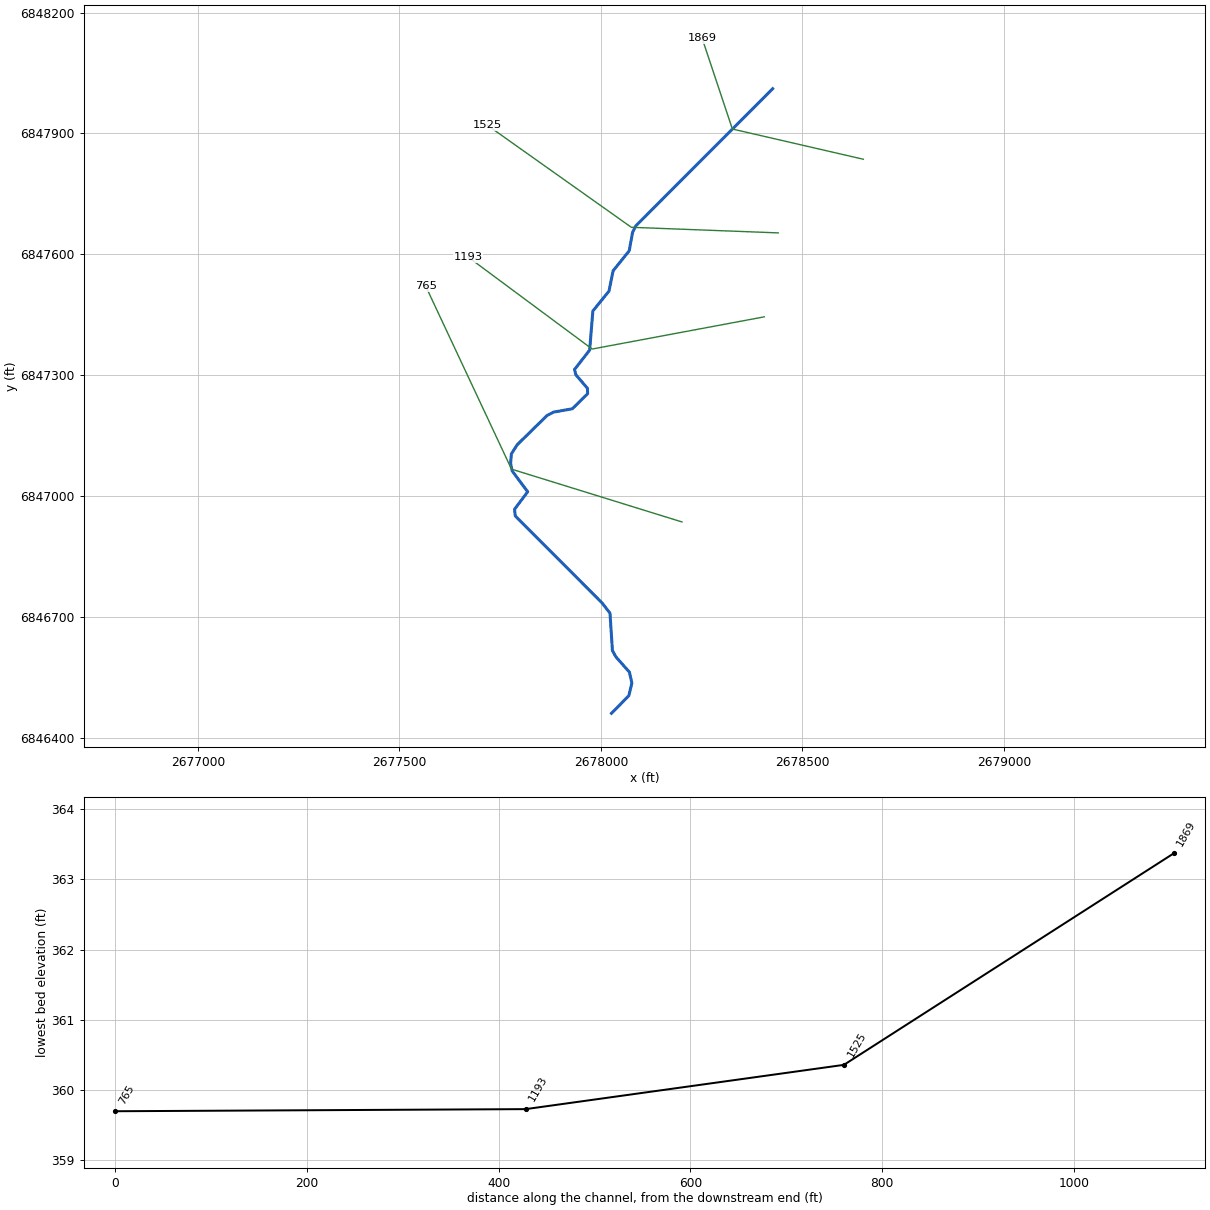
--- CCT2_1.prj (project) ---

Proj Title=CCT2_1 Base Level Engineering
Current Plan=p01
Default Exp/Contr=0.3,0.1
English Units
Geom File=g01
Flow File=f01
Plan File=p01
BEGIN DESCRIPTION:
CCT2_1
END DESCRIPTION:

--- CCT2_1.p01 (plan) ---

Plan Title=Multiple Run
Short Identifier=Multiple
Geom File=g01
Flow File=f01
Subcritical Flow
K Sum by GR= 0
Std Step Tol= 0.01
Critical Tol= 0.01
Num of Std Step Trials= 20
Max Error Tol= 0.3
Flow Tol Ratio= 0.001
Split Flow NTrial= 30
Split Flow Tol= 0.02
Split Flow Ratio= 0.02
Log Output Level= 0
Friction Slope Method= 1
Unsteady Friction Slope Method= 2
Unsteady Bridges Friction Slope Method= 1
Parabolic Critical Depth
Global Vel Dist=  1 , 1 , 1
Global Log Level= 0
CheckData=True
Encroach Param= -1, 0, 0, 0
BEGIN DESCRIPTION:
Multiple Run
END DESCRIPTION:

--- CCT2_1.f01 (steady flow) ---

Flow Title=Multiple
Number of Profiles=7
Profile Names=10-year,25-year,50-year,1pct_min,100-year,1pct_plu,500-year
River Rch & RM= CCT2_1,Reach-1,1869
     111     133     149      83     166     331     205
River Rch & RM= CCT2_1,Reach-1,1525
     192     239     274     157     313     624     405
Boundary for River Rch & Prof#=CCT2_1,Reach-1,1
Up Type=0
Dn Type=3
Dn Slope=0.005
Boundary for River Rch & Prof#=CCT2_1,Reach-1,2
Up Type=0
Dn Type=3
Dn Slope=0.005
Boundary for River Rch & Prof#=CCT2_1,Reach-1,3
Up Type=0
Dn Type=3
Dn Slope=0.005
Boundary for River Rch & Prof#=CCT2_1,Reach-1,4
Up Type=0
Dn Type=3
Dn Slope=0.005
Boundary for River Rch & Prof#=CCT2_1,Reach-1,5
Up Type=0
Dn Type=3
Dn Slope=0.005
Boundary for River Rch & Prof#=CCT2_1,Reach-1,6
Up Type=0
Dn Type=3
Dn Slope=0.005
Boundary for River Rch & Prof#=CCT2_1,Reach-1,7
Up Type=0
Dn Type=3
Dn Slope=0.005

--- CCT2_1.g01 (geometry) ---

Geom Title=Existing Conditions

River Reach=CCT2_1,Reach-1
Reach XY= 30
      2678426.00      6848011.00      2678086.48      6847670.80
      2678078.51      6847654.96      2678070.01      6847608.77
      2678030.15      6847559.28      2678019.89      6847508.82
      2677979.82      6847459.41      2677971.92      6847362.50
      2677934.29      6847314.21      2677937.86      6847300.92
      2677966.47      6847267.50      2677966.82      6847254.05
      2677928.83      6847216.86      2677882.12      6847208.47
      2677866.33      6847200.23      2677792.21      6847127.71
      2677777.65      6847104.96      2677775.75      6847081.16
      2677779.56      6847062.65      2677818.16      6847010.91
      2677785.60      6846967.66      2677787.24      6846951.00
      2678003.12      6846734.52      2678022.39      6846709.50
      2678028.37      6846616.96      2678036.92      6846601.34
      2678070.63      6846563.22      2678076.61      6846536.05
      2678069.05      6846504.85      2678026.00      6846461.00

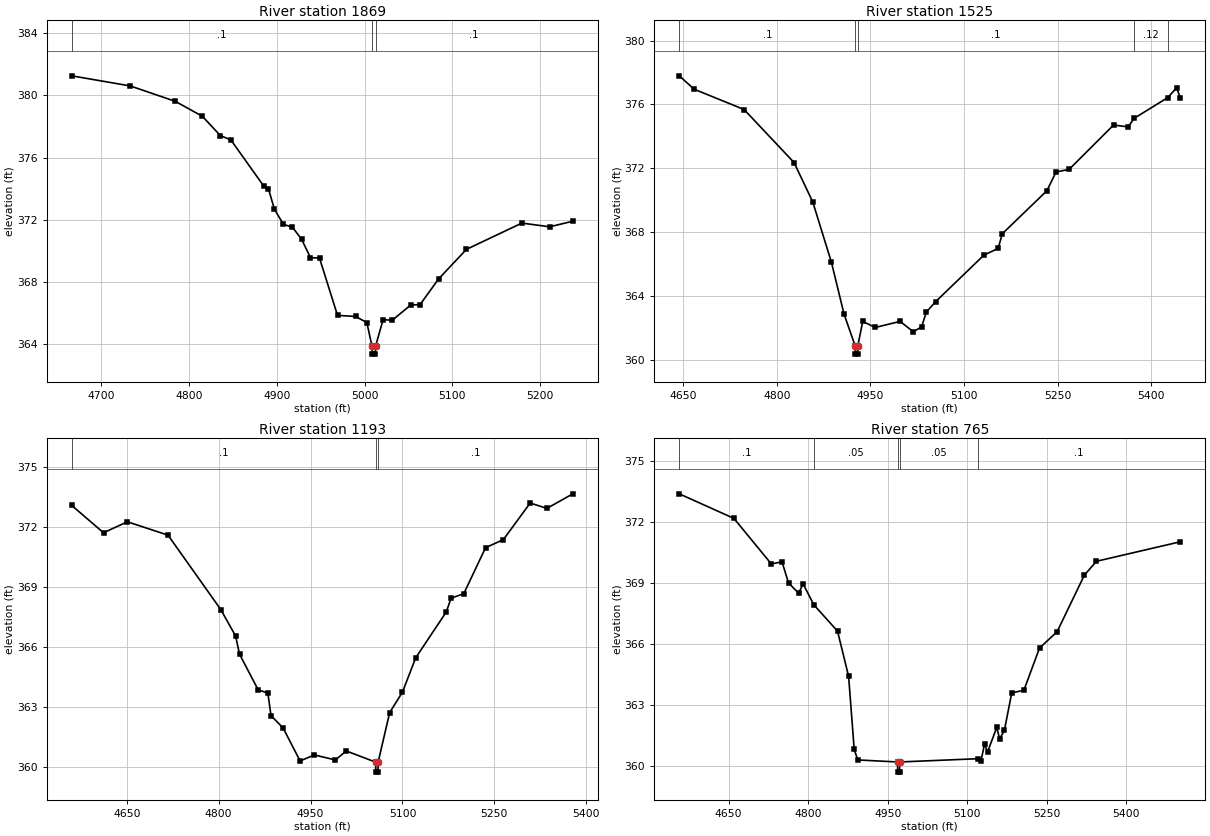
Type RM Length L Ch R = 1,1869,344,344,344
BEGIN DESCRIPTION:
CCT2_1 3.0
END DESCRIPTION:
XS GIS Cut Line= 3
      2678650.96      6847836.01      2678326.00      6847911.00
      2678250.99      6848136.03
#Sta/Elev= 30
  4666.5  381.25  4733.2  380.60  4784.5  379.61  4815.3  378.65  4835.8  377.41
  4847.8  377.13  4885.4  374.15  4890.5  374.00  4897.4  372.67  4907.6  371.71
  4917.9  371.52  4928.2  370.76  4938.4  369.57  4948.7  369.54  4969.2  365.86
  4989.7  365.79  5002.6  365.40  5008.5  363.87  5008.8  363.37  5012.3  363.37
  5012.5  363.87  5021.1  365.58  5031.6  365.55  5052.7  366.53  5063.2  366.55
  5084.3  368.20  5116.0  370.10  5179.2  371.79  5210.8  371.55  5237.2  371.91
#Mann=3,-1,0
  4666.5     0.1       0  5008.5    0.07       0  5012.5     0.1       0
Bank Sta=5008.5,5012.5
Exp/Cntr=0.3,0.1

Type RM Length L Ch R = 1,1525,332,332,332
BEGIN DESCRIPTION:
Mapping XS c3817bcc
END DESCRIPTION:
XS GIS Cut Line= 3
      2678439.87      6847653.27      2678075.33      6847667.16
      2677717.66      6847920.66
#Sta/Elev= 30
  4643.6  377.79  4667.5  376.95  4747.5  375.68  4827.6  372.36  4857.6  369.89
  4887.6  366.10  4907.7  362.87  4925.7  360.86  4925.9  360.36  4929.4  360.36
  4929.7  360.86  4937.7  362.41  4957.7  362.03  4997.7  362.41  5018.7  361.76
  5032.1  362.07  5039.6  362.99  5054.4  363.64  5131.9  366.56  5154.7  366.98
  5161.4  367.90  5232.8  370.59  5247.6  371.77  5268.5  371.93  5339.8  374.71
  5363.0  374.59  5372.8  375.13  5426.7  376.43  5440.7  377.04  5446.8  376.41
#Mann=5,-1,0
  4643.6     0.1       0  4925.7    0.07       0  4929.7     0.1       0
  5372.8    0.12       0  5426.7     0.1       0
Bank Sta=4925.7,4929.7
Exp/Cntr=0.3,0.1

Type RM Length L Ch R = 1,1193,428,428,428
BEGIN DESCRIPTION:
Mapping XS 678bae06
END DESCRIPTION:
XS GIS Cut Line= 3
      2678405.21      6847444.94      2677978.11      6847365.08
      2677670.07      6847593.51
#Sta/Elev= 30
  4560.1  373.09  4612.0  371.72  4650.9  372.27  4717.3  371.60  4803.5  367.87
  4827.6  366.55  4834.0  365.64  4864.5  363.85  4880.3  363.69  4885.4  362.56
  4905.2  361.94  4932.9  360.29  4956.1  360.59  4990.6  360.34  5008.2  360.79
  5056.3  360.23  5056.5  359.73  5060.0  359.73  5060.3  360.23  5079.1  362.71
  5100.0  363.74  5121.7  365.46  5171.5  367.75  5179.3  368.44  5200.1  368.67
  5235.6  370.97  5264.8  371.38  5308.5  373.21  5335.8  372.94  5378.1  373.67
#Mann=3,-1,0
  4560.1     0.1       0  5056.3    0.07       0  5060.3     0.1       0
Bank Sta=5056.3,5060.3
Exp/Cntr=0.3,0.1

Type RM Length L Ch R = 1,765,0,0,0
BEGIN DESCRIPTION:
CCT2_1 1.0
END DESCRIPTION:
XS GIS Cut Line= 3
      2678201.03      6846935.99      2677777.97      6847067.05
      2677564.90      6847521.37
#Sta/Elev= 30
  4557.1  373.40  4660.2  372.19  4730.6  369.95  4750.8  370.05  4763.2  369.01
  4782.2  368.51  4790.6  368.97  4810.7  367.94  4855.5  366.64  4876.4  364.41
  4886.9  360.82  4893.6  360.30  4968.7  360.20  4968.9  359.70  4972.4  359.70
  4972.7  360.20  5120.1  360.36  5125.9  360.26  5132.8  361.09  5138.3  360.69
  5155.6  361.90  5161.1  361.34  5170.0  361.75  5183.9  363.60  5206.8  363.73
  5236.3  365.81  5269.4  366.61  5320.9  369.40  5343.7  370.08  5501.8  371.04
#Mann=5,-1,0
  4557.1     0.1       0  4810.7    0.05       0  4968.7    0.03       0
  4972.7    0.05       0  5120.1     0.1       0
Bank Sta=4968.7,4972.7
Exp/Cntr=0.3,0.1

Chan Stop Cuts=-1