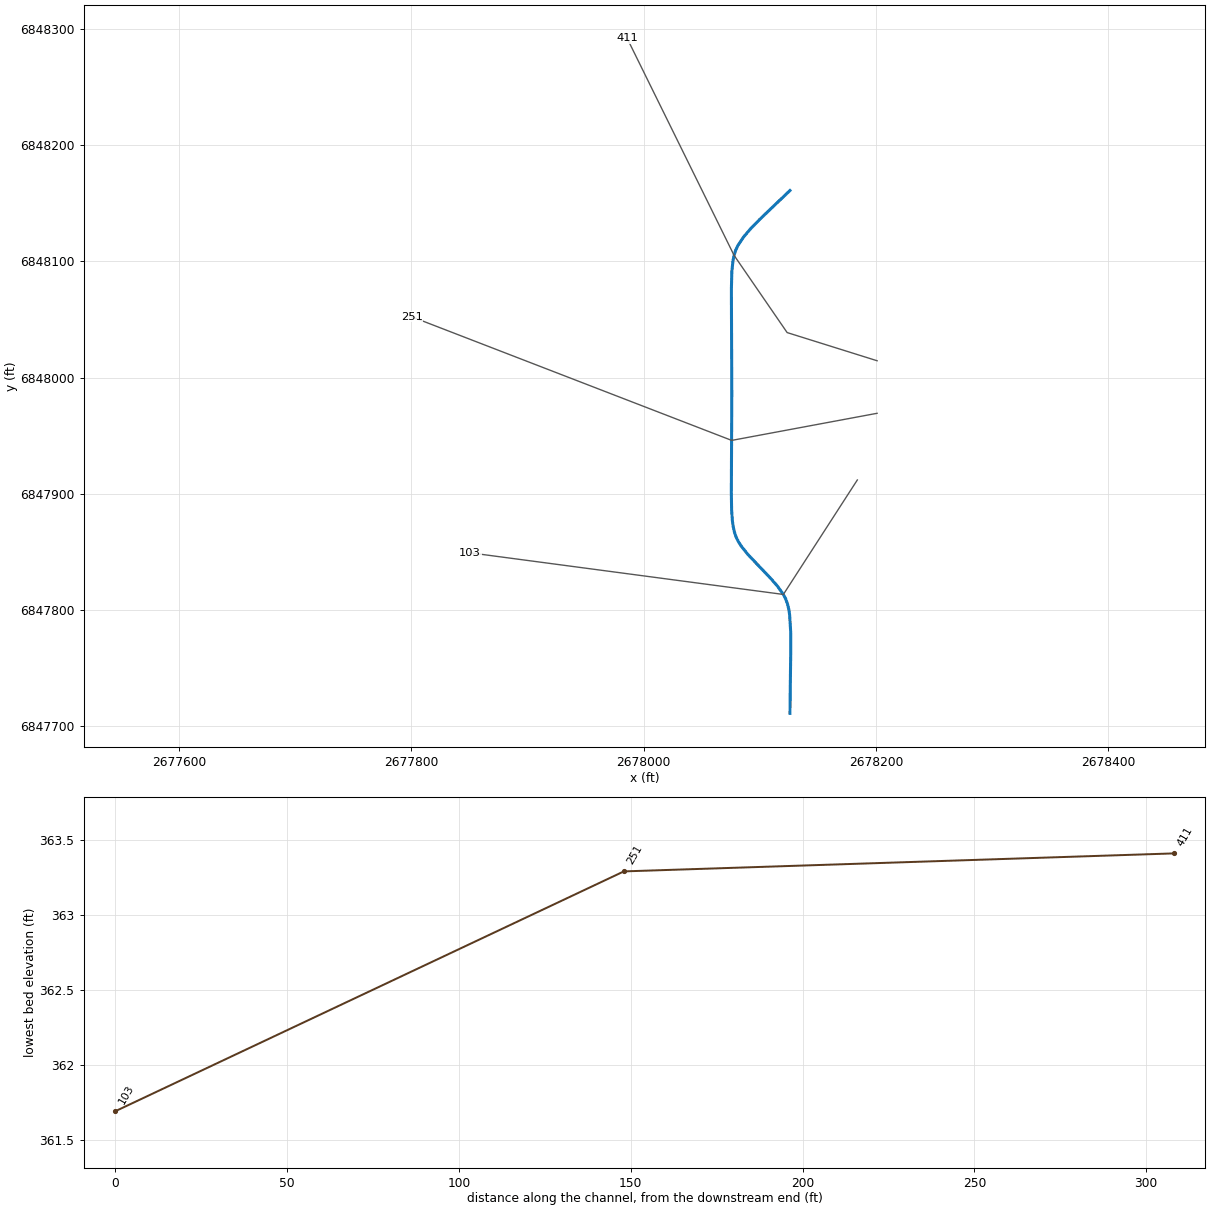
--- CCT2_1_1.prj (project) ---

Proj Title=CCT2_1_1 Base Level Engineering
Current Plan=p01
Default Exp/Contr=0.3,0.1
English Units
Geom File=g01
Flow File=f01
Plan File=p01
BEGIN DESCRIPTION:
CCT2_1_1
END DESCRIPTION:

--- CCT2_1_1.p01 (plan) ---

Plan Title=Multiple Run
Short Identifier=Multiple
Geom File=g01
Flow File=f01
Subcritical Flow
K Sum by GR= 0
Std Step Tol= 0.01
Critical Tol= 0.01
Num of Std Step Trials= 20
Max Error Tol= 0.3
Flow Tol Ratio= 0.001
Split Flow NTrial= 30
Split Flow Tol= 0.02
Split Flow Ratio= 0.02
Log Output Level= 0
Friction Slope Method= 1
Unsteady Friction Slope Method= 2
Unsteady Bridges Friction Slope Method= 1
Parabolic Critical Depth
Global Vel Dist=  1 , 1 , 1
Global Log Level= 0
CheckData=True
Encroach Param= -1, 0, 0, 0
BEGIN DESCRIPTION:
Multiple Run
END DESCRIPTION:

--- CCT2_1_1.f01 (steady flow) ---

Flow Title=Multiple
Number of Profiles=7
Profile Names=10-year,25-year,50-year,1pct_min,100-year,1pct_plu,500-year
River Rch & RM= CCT2_1_1,Reach-1,411
     105     125     139      78     155     309     189
Boundary for River Rch & Prof#=CCT2_1_1,Reach-1,1
Up Type=0
Dn Type=3
Dn Slope=0.005
Boundary for River Rch & Prof#=CCT2_1_1,Reach-1,2
Up Type=0
Dn Type=3
Dn Slope=0.005
Boundary for River Rch & Prof#=CCT2_1_1,Reach-1,3
Up Type=0
Dn Type=3
Dn Slope=0.005
Boundary for River Rch & Prof#=CCT2_1_1,Reach-1,4
Up Type=0
Dn Type=3
Dn Slope=0.005
Boundary for River Rch & Prof#=CCT2_1_1,Reach-1,5
Up Type=0
Dn Type=3
Dn Slope=0.005
Boundary for River Rch & Prof#=CCT2_1_1,Reach-1,6
Up Type=0
Dn Type=3
Dn Slope=0.005
Boundary for River Rch & Prof#=CCT2_1_1,Reach-1,7
Up Type=0
Dn Type=3
Dn Slope=0.005

--- CCT2_1_1.g01 (geometry) ---

Geom Title=Existing Conditions

River Reach=CCT2_1_1,Reach-1
Reach XY= 30
      2678126.00      6848161.00      2678100.11      6848136.29
      2678092.08      6848128.06      2678086.05      6848120.98
      2678081.14      6848113.59      2678079.29      6848109.64
      2678077.89      6848105.22      2678076.96      6848100.60
      2678075.98      6848091.01      2678075.59      6848076.17
      2678075.95      6847986.00      2678075.55      6847900.81
      2678075.79      6847885.91      2678076.51      6847876.21
      2678077.20      6847871.50      2678078.24      6847866.93
      2678079.75      6847862.55      2678081.71      6847858.65
      2678084.10      6847854.93      2678089.74      6847847.83
      2678109.06      6847827.55      2678115.14      6847820.64
      2678120.32      6847813.36      2678122.33      6847809.48
      2678123.90      6847805.13      2678124.98      6847800.58
      2678125.71      6847795.88      2678126.63      6847781.26
      2678126.70      6847766.29      2678126.00      6847711.00

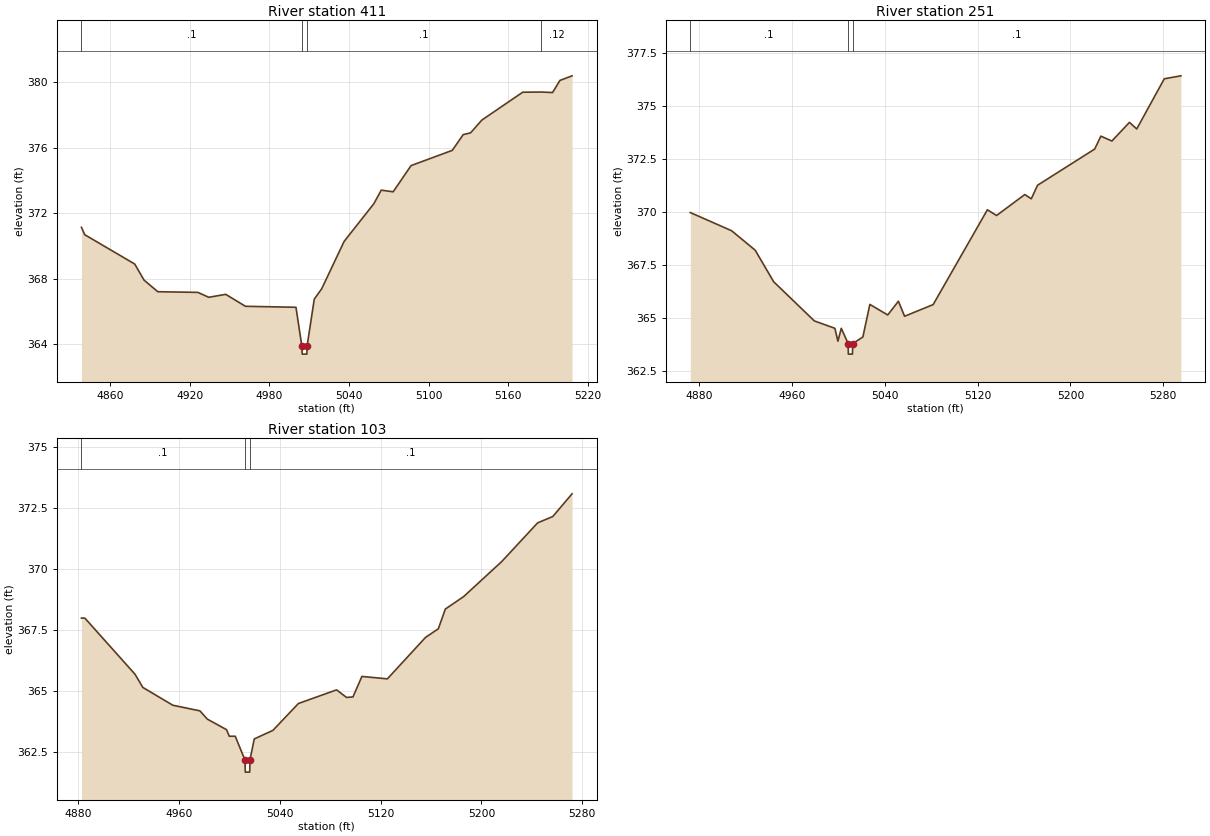
Type RM Length L Ch R = 1,411,160,160,160
BEGIN DESCRIPTION:
CCT2_1_1 0.1
END DESCRIPTION:
XS GIS Cut Line= 4
      2678201.01      6848014.49      2678123.58      6848038.74
      2678077.89      6848105.22      2677985.88      6848291.98
#Sta/Elev= 30
  4838.2  371.15  4840.7  370.70  4878.4  368.91  4885.4  367.93  4895.8  367.22
  4926.0  367.18  4934.2  366.88  4947.0  367.06  4961.9  366.33  5000.0  366.27
  5004.4  363.91  5004.7  363.41  5008.2  363.41  5008.4  363.91  5013.8  366.77
  5019.4  367.40  5036.3  370.29  5058.7  372.59  5064.3  373.42  5073.3  373.32
  5086.8  374.92  5117.9  375.85  5126.1  376.81  5131.7  376.92  5140.2  377.70
  5171.0  379.40  5185.0  379.41  5193.5  379.38  5199.1  380.12  5208.2  380.40
#Mann=4,-1,0
  4838.2     0.1       0  5004.4    0.07       0  5008.4     0.1       0
  5185.0    0.12       0
Bank Sta=5004.4,5008.4
Exp/Cntr=0.3,0.1

Type RM Length L Ch R = 1,251,148,148,148
BEGIN DESCRIPTION:
CCT2_1_1 0.2
END DESCRIPTION:
XS GIS Cut Line= 3
      2678201.00      6847969.27      2678075.86      6847945.94
      2677800.58      6848052.29
#Sta/Elev= 30
  4872.7  369.98  4908.3  369.12  4928.6  368.20  4944.5  366.71  4979.5  364.86
  4997.2  364.51  4999.8  363.90  5002.7  364.51  5008.6  363.79  5008.8  363.29
  5012.3  363.29  5012.6  363.79  5021.3  364.10  5027.3  365.64  5042.7  365.14
  5051.9  365.79  5057.2  365.08  5081.8  365.63  5128.5  370.11  5136.4  369.84
  5160.7  370.83  5166.3  370.63  5171.7  371.27  5220.9  372.98  5226.2  373.59
  5235.7  373.36  5250.8  374.24  5257.1  373.93  5280.8  376.30  5295.1  376.44
#Mann=3,-1,0
  4872.7     0.1       0  5008.6    0.07       0  5012.6     0.1       0
Bank Sta=5008.6,5012.6
Exp/Cntr=0.3,0.1

Type RM Length L Ch R = 1,103,0,0,0
BEGIN DESCRIPTION:
CCT2_1_1 0.0
END DESCRIPTION:
XS GIS Cut Line= 3
      2678183.98      6847911.88      2678120.32      6847813.36
      2677850.79      6847849.17
#Sta/Elev= 30
  4882.7  368.00  4885.4  368.00  4925.2  365.70  4931.4  365.16  4955.2  364.43
  4976.7  364.20  4982.6  363.86  4997.8  363.43  5000.0  363.16  5004.7  363.16
  5012.4  362.19  5012.7  361.69  5016.2  361.69  5016.4  362.19  5019.8  363.05
  5034.6  363.40  5054.8  364.50  5085.1  365.06  5093.0  364.75  5098.1  364.77
  5105.2  365.61  5125.4  365.51  5155.7  367.21  5165.8  367.56  5171.4  368.37
  5185.9  368.88  5216.2  370.32  5244.6  371.90  5256.6  372.16  5271.9  373.09
#Mann=3,-1,0
  4882.7     0.1       0  5012.4    0.07       0  5016.4     0.1       0
Bank Sta=5012.4,5016.4
Exp/Cntr=0.3,0.1

Chan Stop Cuts=-1