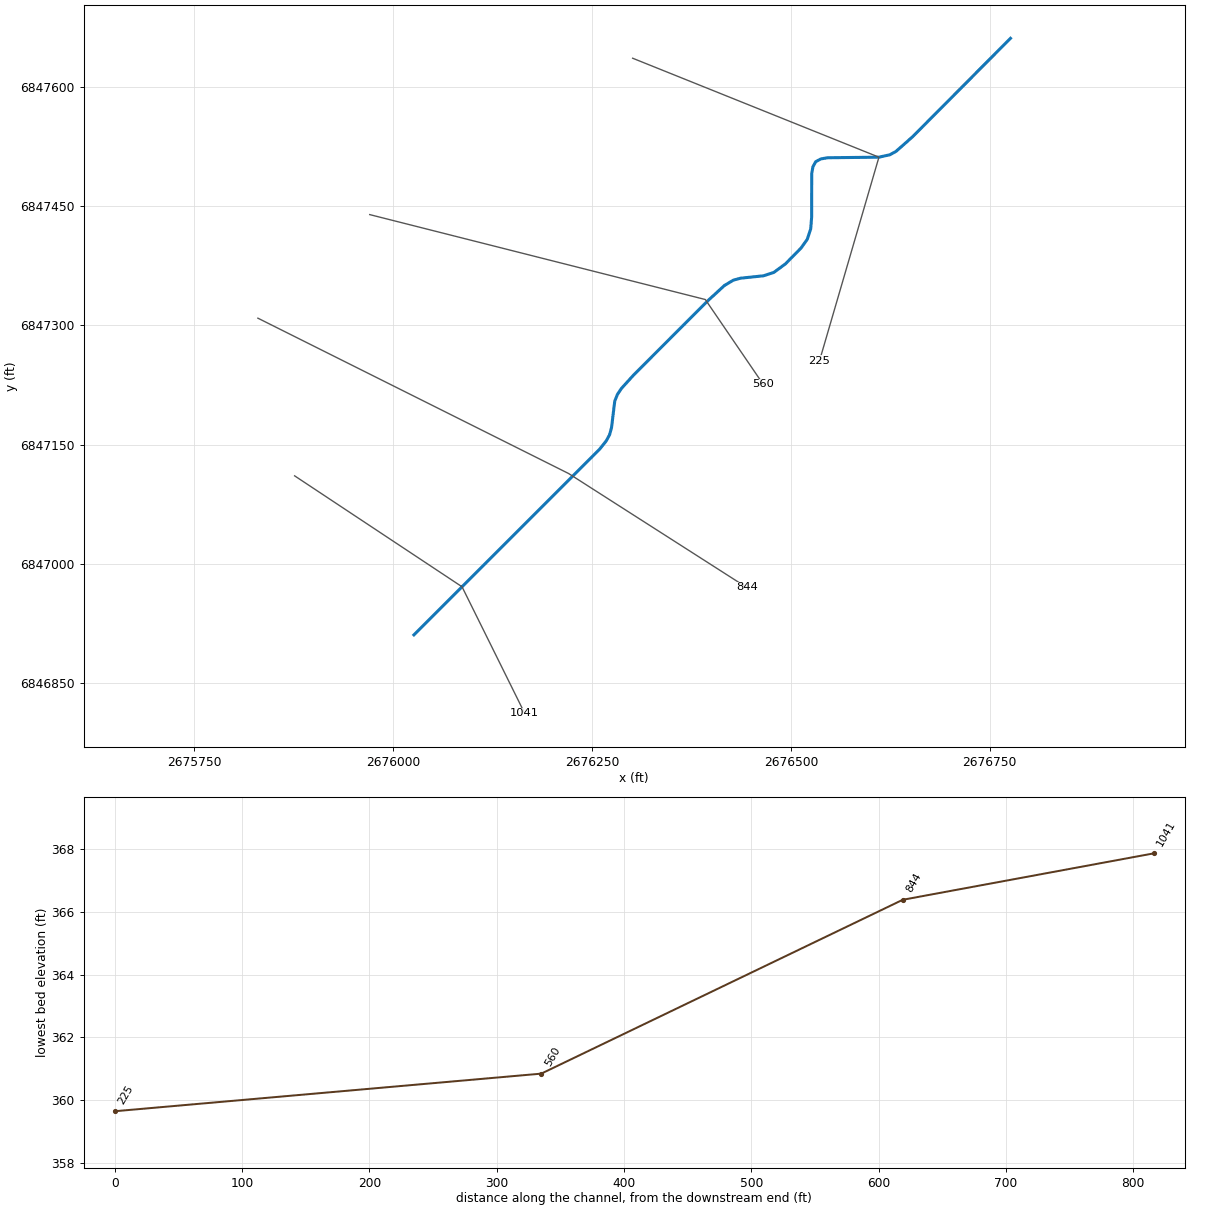
--- CCT2_2.prj (project) ---

Proj Title=CCT2_2 Base Level Engineering
Current Plan=p01
Default Exp/Contr=0.3,0.1
English Units
Geom File=g01
Flow File=f01
Plan File=p01
BEGIN DESCRIPTION:
CCT2_2
END DESCRIPTION:

--- CCT2_2.p01 (plan) ---

Plan Title=Multiple Run
Short Identifier=Multiple
Geom File=g01
Flow File=f01
Subcritical Flow
K Sum by GR= 0
Std Step Tol= 0.01
Critical Tol= 0.01
Num of Std Step Trials= 20
Max Error Tol= 0.3
Flow Tol Ratio= 0.001
Split Flow NTrial= 30
Split Flow Tol= 0.02
Split Flow Ratio= 0.02
Log Output Level= 0
Friction Slope Method= 1
Unsteady Friction Slope Method= 2
Unsteady Bridges Friction Slope Method= 1
Parabolic Critical Depth
Global Vel Dist=  1 , 1 , 1
Global Log Level= 0
CheckData=True
Encroach Param= -1, 0, 0, 0
BEGIN DESCRIPTION:
Multiple Run
END DESCRIPTION:

--- CCT2_2.f01 (steady flow) ---

Flow Title=Multiple
Number of Profiles=7
Profile Names=10-year,25-year,50-year,1pct_min,100-year,1pct_plu,500-year
River Rch & RM= CCT2_2,Reach-1,1041
     102     121     135      75     149     298     183
Boundary for River Rch & Prof#=CCT2_2,Reach-1,1
Up Type=0
Dn Type=3
Dn Slope=0.005
Boundary for River Rch & Prof#=CCT2_2,Reach-1,2
Up Type=0
Dn Type=3
Dn Slope=0.005
Boundary for River Rch & Prof#=CCT2_2,Reach-1,3
Up Type=0
Dn Type=3
Dn Slope=0.005
Boundary for River Rch & Prof#=CCT2_2,Reach-1,4
Up Type=0
Dn Type=3
Dn Slope=0.005
Boundary for River Rch & Prof#=CCT2_2,Reach-1,5
Up Type=0
Dn Type=3
Dn Slope=0.005
Boundary for River Rch & Prof#=CCT2_2,Reach-1,6
Up Type=0
Dn Type=3
Dn Slope=0.005
Boundary for River Rch & Prof#=CCT2_2,Reach-1,7
Up Type=0
Dn Type=3
Dn Slope=0.005

--- CCT2_2.g01 (geometry) ---

Geom Title=Existing Conditions

River Reach=CCT2_2,Reach-1
Reach XY= 30
      2676026.00      6846911.00      2676259.35      6847144.33
      2676267.84      6847154.95      2676272.02      6847162.65
      2676274.45      6847171.64      2676278.53      6847204.95
      2676281.86      6847213.29      2676286.78      6847220.68
      2676302.30      6847237.82      2676395.84      6847331.38
      2676416.34      6847350.21      2676427.68      6847357.01
      2676436.69      6847359.43      2676465.53      6847362.48
      2676478.57      6847366.74      2676493.12      6847377.47
      2676512.73      6847397.38      2676520.55      6847408.39
      2676524.85      6847421.45      2676526.03      6847436.09
      2676526.13      6847490.95      2676527.62      6847499.41
      2676531.11      6847505.89      2676537.58      6847509.38
      2676546.05      6847510.87      2676610.64      6847511.58
      2676624.43      6847514.64      2676632.12      6847518.88
      2676652.86      6847537.18      2676776.00      6847661.00

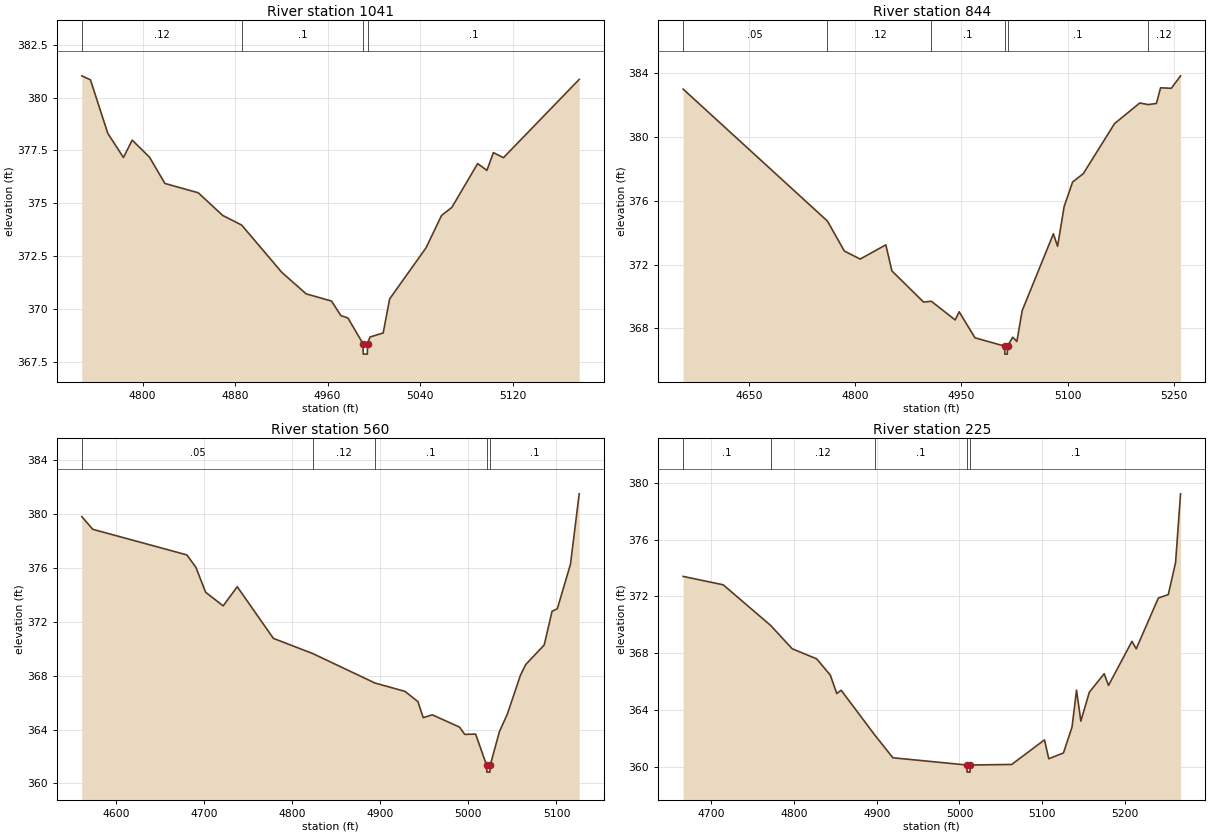
Type RM Length L Ch R = 1,1041,197,197,197
BEGIN DESCRIPTION:
CCT2_2 2.0
END DESCRIPTION:
XS GIS Cut Line= 3
      2675876.03      6847110.98      2676086.51      6846971.50
      2676165.32      6846812.34
#Sta/Elev= 30
  4747.5  381.03  4755.0  380.84  4770.0  378.31  4783.5  377.17  4791.1  377.99
  4806.1  377.18  4819.4  375.94  4848.2  375.50  4869.3  374.43  4885.8  373.97
  4920.4  371.74  4941.5  370.72  4963.4  370.38  4971.6  369.69  4977.6  369.58
  4990.6  368.37  4990.9  367.87  4994.4  367.87  4994.6  368.37  4996.7  368.68
  5008.1  368.87  5013.7  370.48  5045.2  372.90  5058.6  374.43  5067.5  374.81
  5089.8  376.88  5097.8  376.56  5103.4  377.40  5112.1  377.16  5177.6  380.86
#Mann=4,-1,0
  4747.5    0.12       0  4885.8     0.1       0  4990.6    0.07       0
  4994.6     0.1       0
Bank Sta=4990.6,4994.6
Exp/Cntr=0.3,0.1

Type RM Length L Ch R = 1,844,284,284,284
BEGIN DESCRIPTION:
Mapping XS 0a44ab32
END DESCRIPTION:
XS GIS Cut Line= 3
      2675829.89      6847309.18      2676220.50      6847113.88
      2676444.49      6846970.62
#Sta/Elev= 30
  4557.0  382.98  4760.8  374.72  4784.8  372.84  4807.1  372.34  4843.3  373.23
  4851.9  371.60  4896.6  369.65  4907.5  369.70  4941.3  368.53  4946.9  369.04
  4969.3  367.41  5011.2  366.89  5011.4  366.39  5014.9  366.39  5015.2  366.89
  5022.5  367.45  5028.4  367.18  5035.9  369.11  5080.0  373.92  5085.9  373.14
  5095.2  375.63  5107.1  377.16  5122.3  377.69  5166.4  380.82  5202.0  382.11
  5213.9  382.01  5225.5  382.08  5231.4  383.06  5246.6  383.03  5259.6  383.81
#Mann=6,-1,0
  4557.0    0.05       0  4760.8    0.12       0  4907.5     0.1       0
  5011.2    0.07       0  5015.2     0.1       0  5213.9    0.12       0
Bank Sta=5011.2,5015.2
Exp/Cntr=0.3,0.1

Type RM Length L Ch R = 1,560,335,335,335
BEGIN DESCRIPTION:
Mapping XS 12e9149e
END DESCRIPTION:
XS GIS Cut Line= 3
      2675970.47      6847439.40      2676392.37      6847332.63
      2676465.23      6847225.93
#Sta/Elev= 30
  4561.4  379.79  4573.8  378.85  4680.6  376.95  4690.9  376.03  4701.9  374.18
  4721.8  373.17  4737.8  374.59  4778.8  370.76  4823.6  369.63  4894.0  367.45
  4928.1  366.83  4942.8  366.07  4948.8  364.88  4959.1  365.09  4990.0  364.18
  4995.9  363.64  5008.3  363.66  5020.8  361.34  5021.0  360.84  5024.5  360.84
  5024.8  361.34  5035.3  363.85  5044.2  365.13  5059.1  368.02  5065.1  368.82
  5086.1  370.27  5095.0  372.77  5101.0  372.96  5115.9  376.26  5125.8  381.48
#Mann=5,-1,0
  4561.4    0.05       0  4823.6    0.12       0  4894.0     0.1       0
  5020.8    0.07       0  5024.8     0.1       0
Bank Sta=5020.8,5024.8
Exp/Cntr=0.3,0.1

Type RM Length L Ch R = 1,225,0,0,0
BEGIN DESCRIPTION:
CCT2_2 1.0
END DESCRIPTION:
XS GIS Cut Line= 3
      2676301.00      6847636.00      2676610.64      6847511.58
      2676535.83      6847255.28
#Sta/Elev= 30
  4666.3  373.41  4714.7  372.82  4772.0  369.96  4798.0  368.32  4827.6  367.61
  4844.1  366.46  4851.8  365.17  4857.2  365.40  4897.5  362.27  4919.6  360.65
  5009.0  360.14  5009.3  359.64  5012.8  359.64  5013.0  360.14  5063.1  360.18
  5102.7  361.91  5107.9  360.58  5125.6  360.99  5136.0  362.82  5141.4  365.41
  5146.6  363.23  5156.9  365.27  5174.8  366.56  5180.0  365.74  5208.3  368.84
  5213.5  368.32  5240.2  371.89  5252.2  372.13  5261.0  374.38  5267.0  379.22
#Mann=5,-1,0
  4666.3     0.1       0  4772.0    0.12       0  4897.5     0.1       0
  5009.0    0.07       0  5013.0     0.1       0
Bank Sta=5009,5013
Exp/Cntr=0.3,0.1

Chan Stop Cuts=-1