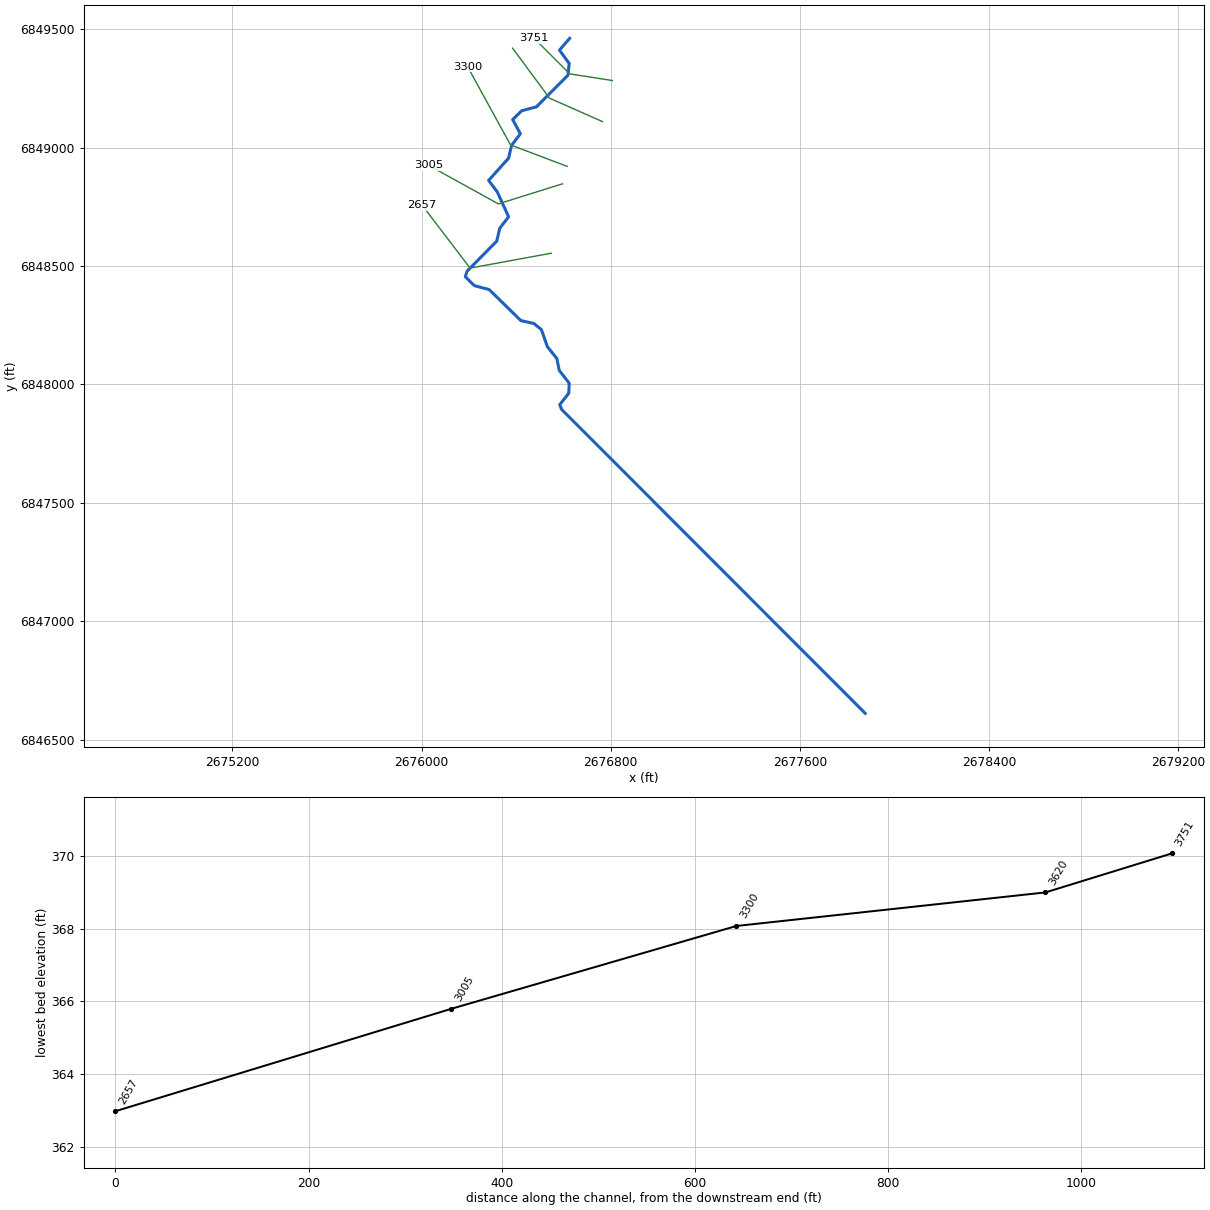
--- CCT2_3.prj (project) ---

Proj Title=CCT2_3 Base Level Engineering
Current Plan=p01
Default Exp/Contr=0.3,0.1
English Units
Geom File=g01
Flow File=f01
Plan File=p01
BEGIN DESCRIPTION:
CCT2_3
END DESCRIPTION:

--- CCT2_3.p01 (plan) ---

Plan Title=Multiple Run
Short Identifier=Multiple
Geom File=g01
Flow File=f01
Subcritical Flow
K Sum by GR= 0
Std Step Tol= 0.01
Critical Tol= 0.01
Num of Std Step Trials= 20
Max Error Tol= 0.3
Flow Tol Ratio= 0.001
Split Flow NTrial= 30
Split Flow Tol= 0.02
Split Flow Ratio= 0.02
Log Output Level= 0
Friction Slope Method= 1
Unsteady Friction Slope Method= 2
Unsteady Bridges Friction Slope Method= 1
Parabolic Critical Depth
Global Vel Dist=  1 , 1 , 1
Global Log Level= 0
CheckData=True
Encroach Param= -1, 0, 0, 0
BEGIN DESCRIPTION:
Multiple Run
END DESCRIPTION:

--- CCT2_3.f01 (steady flow) ---

Flow Title=Multiple
Number of Profiles=7
Profile Names=10-year,25-year,50-year,1pct_min,100-year,1pct_plu,500-year
River Rch & RM= CCT2_3,Reach-1,3751
     219     275     316     181     362     722     473
Boundary for River Rch & Prof#=CCT2_3,Reach-1,1
Up Type=0
Dn Type=3
Dn Slope=0.005
Boundary for River Rch & Prof#=CCT2_3,Reach-1,2
Up Type=0
Dn Type=3
Dn Slope=0.005
Boundary for River Rch & Prof#=CCT2_3,Reach-1,3
Up Type=0
Dn Type=3
Dn Slope=0.005
Boundary for River Rch & Prof#=CCT2_3,Reach-1,4
Up Type=0
Dn Type=3
Dn Slope=0.005
Boundary for River Rch & Prof#=CCT2_3,Reach-1,5
Up Type=0
Dn Type=3
Dn Slope=0.005
Boundary for River Rch & Prof#=CCT2_3,Reach-1,6
Up Type=0
Dn Type=3
Dn Slope=0.005
Boundary for River Rch & Prof#=CCT2_3,Reach-1,7
Up Type=0
Dn Type=3
Dn Slope=0.005

--- CCT2_3.g01 (geometry) ---

Geom Title=Existing Conditions

River Reach=CCT2_3,Reach-1
Reach XY= 30
      2676626.00      6849461.00      2676582.95      6849411.12
      2676624.14      6849354.96      2676618.51      6849304.95
      2676485.65      6849171.78      2676423.17      6849155.14
      2676385.18      6849117.95      2676417.75      6849057.78
      2676380.44      6849009.35      2676367.84      6848954.95
      2676283.30      6848861.08      2676319.62      6848813.29
      2676367.98      6848707.69      2676330.45      6848659.35
      2676317.88      6848604.95      2676192.16      6848477.58
      2676184.84      6848454.05      2676223.14      6848416.86
      2676285.64      6848400.22      2676419.97      6848269.17
      2676474.57      6848257.11      2676506.38      6848231.47
      2676532.11      6848158.84      2676571.85      6848109.28
      2676582.16      6848058.80      2676624.16      6848004.87
      2676622.38      6847962.63      2676583.91      6847914.23
      2676592.30      6847894.30      2677876.00      6846611.00

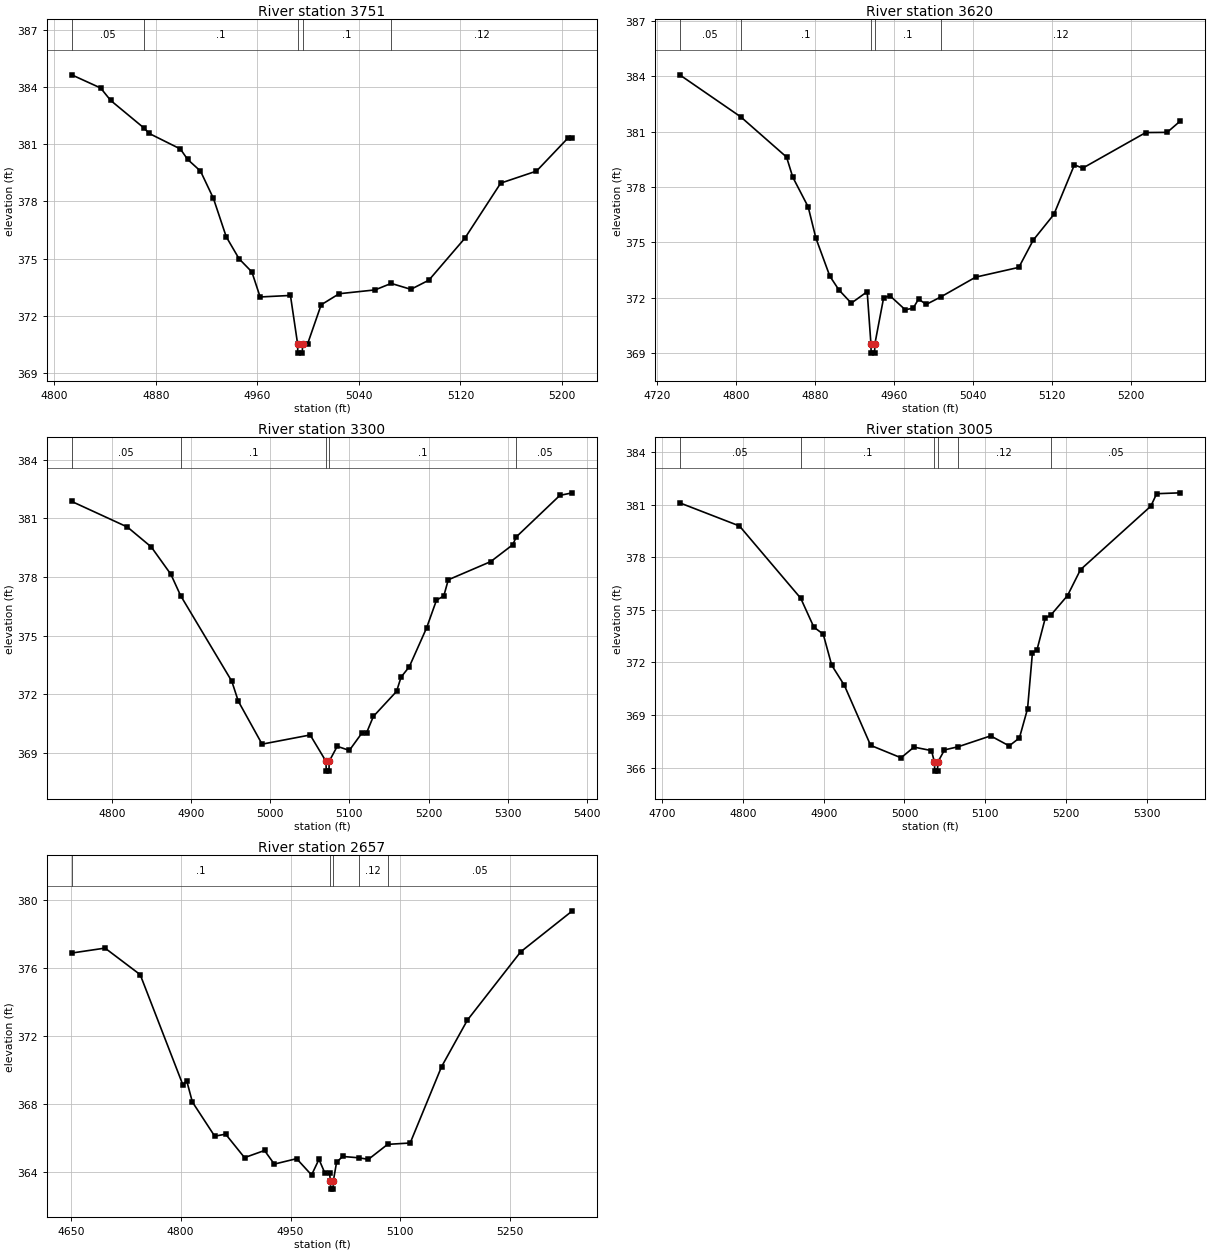
Type RM Length L Ch R = 1,3751,131,131,131
BEGIN DESCRIPTION:
CCT2_3 3.0
END DESCRIPTION:
XS GIS Cut Line= 3
      2676806.33      6849282.94      2676626.00      6849311.00
      2676476.02      6849460.98
#Sta/Elev= 30
  4813.6  384.63  4836.4  383.94  4844.3  383.29  4870.3  381.86  4874.7  381.56
  4899.2  380.75  4905.0  380.20  4915.1  379.59  4925.3  378.16  4935.4  376.15
  4945.5  375.00  4955.6  374.31  4962.1  373.00  4986.0  373.08  4991.6  370.56
  4991.8  370.06  4995.3  370.06  4995.6  370.56  4999.6  370.56  5010.2  372.59
  5024.4  373.17  5052.7  373.37  5065.4  373.71  5080.9  373.40  5095.1  373.88
  5123.4  376.07  5151.7  378.96  5179.9  379.59  5204.7  381.32  5208.2  381.32
#Mann=5,-1,0
  4813.6    0.05       0  4870.3     0.1       0  4991.6    0.07       0
  4995.6     0.1       0  5065.4    0.12       0
Bank Sta=4991.6,4995.6
Exp/Cntr=0.3,0.1

Type RM Length L Ch R = 1,3620,320,320,320
BEGIN DESCRIPTION:
Mapping XS 450b58d6
END DESCRIPTION:
XS GIS Cut Line= 3
      2676765.09      6849109.32      2676541.09      6849208.30
      2676384.84      6849419.24
#Sta/Elev= 30
  4742.6  384.08  4804.5  381.80  4850.9  379.62  4857.2  378.53  4872.8  376.92
  4880.6  375.23  4894.7  373.17  4903.9  372.42  4916.5  371.70  4932.6  372.32
  4936.4  369.49  4936.6  368.99  4940.1  368.99  4940.4  369.49  4949.3  372.00
  4955.9  372.09  4971.2  371.34  4979.2  371.43  4984.7  371.92  4992.4  371.63
  5007.3  372.04  5042.5  373.11  5086.3  373.64  5100.9  375.12  5121.8  376.51
  5142.6  379.20  5151.0  379.02  5214.9  380.95  5236.6  380.96  5250.0  381.58
#Mann=5,-1,0
  4742.6    0.05       0  4804.5     0.1       0  4936.4    0.07       0
  4940.4     0.1       0  5007.3    0.12       0
Bank Sta=4936.4,4940.4
Exp/Cntr=0.3,0.1

Type RM Length L Ch R = 1,3300,295,295,295
BEGIN DESCRIPTION:
CCT2_3 2.0
END DESCRIPTION:
XS GIS Cut Line= 3
      2676615.31      6848920.54      2676376.00      6849011.00
      2676194.32      6849341.52
#Sta/Elev= 30
  4748.9  381.87  4819.3  380.56  4849.5  379.54  4874.3  378.14  4886.6  377.05
  4951.3  372.67  4959.5  371.65  4989.6  369.45  5050.4  369.92  5070.4  368.57
  5070.7  368.07  5074.2  368.07  5074.4  368.57  5084.6  369.34  5099.9  369.13
  5116.0  370.03  5121.7  370.03  5130.3  370.87  5159.6  372.15  5165.3  372.88
  5175.7  373.41  5197.5  375.39  5210.1  376.82  5219.3  377.03  5225.0  377.86
  5278.6  378.79  5306.4  379.65  5311.1  380.06  5366.1  382.18  5381.9  382.31
#Mann=5,-1,0
  4748.9    0.05       0  4886.6     0.1       0  5070.4    0.07       0
  5074.4     0.1       0  5311.1    0.05       0
Bank Sta=5070.4,5074.4
Exp/Cntr=0.3,0.1

Type RM Length L Ch R = 1,3005,348,348,348
BEGIN DESCRIPTION:
Mapping XS 69b7a7ca
END DESCRIPTION:
XS GIS Cut Line= 3
      2676595.75      6848846.74      2676324.52      6848762.12
      2676030.23      6848924.41
#Sta/Elev= 30
  4721.6  381.10  4795.6  379.78  4871.5  375.66  4887.8  374.01  4899.4  373.61
  4909.9  371.84  4925.6  370.69  4958.1  367.27  4995.8  366.56  5011.8  367.17
  5033.5  366.97  5037.2  366.30  5037.5  365.80  5041.0  365.80  5041.2  366.30
  5049.6  367.01  5066.5  367.19  5106.8  367.81  5129.7  367.24  5142.4  367.69
  5152.5  369.36  5158.5  372.53  5164.2  372.72  5174.5  374.54  5181.0  374.68
  5202.0  375.81  5218.1  377.29  5305.2  380.91  5312.4  381.62  5341.8  381.67
#Mann=6,-1,0
  4721.6    0.05       0  4871.5     0.1       0  5037.2    0.07       0
  5041.2     0.1       0  5066.5    0.12       0  5181.0    0.05       0
Bank Sta=5037.2,5041.2
Exp/Cntr=0.3,0.1

Type RM Length L Ch R = 1,2657,0,0,0
BEGIN DESCRIPTION:
CCT2_3 1.0
END DESCRIPTION:
XS GIS Cut Line= 3
      2676548.00      6848553.78      2676205.00      6848490.96
      2676001.81      6848756.93
#Sta/Elev= 30
  4651.3  376.86  4696.8  377.15  4744.8  375.59  4803.1  369.11  4808.2  369.37
  4816.0  368.11  4846.5  366.10  4861.4  366.22  4887.2  364.84  4914.5  365.26
  4927.8  364.46  4958.3  364.78  4978.7  363.82  4988.8  364.74  4997.0  363.92
  5003.2  363.92  5004.5  363.49  5004.7  362.99  5008.2  362.99  5008.5  363.49
  5012.8  364.56  5021.0  364.91  5043.2  364.83  5056.3  364.74  5082.5  365.62
  5113.3  365.70  5156.1  370.18  5191.4  372.92  5264.1  376.93  5334.7  379.34
#Mann=5,-1,0
  4651.3     0.1       0  5004.5    0.07       0  5008.5     0.1       0
  5043.2    0.12       0  5082.5    0.05       0
Bank Sta=5004.5,5008.5
Exp/Cntr=0.3,0.1

Chan Stop Cuts=-1