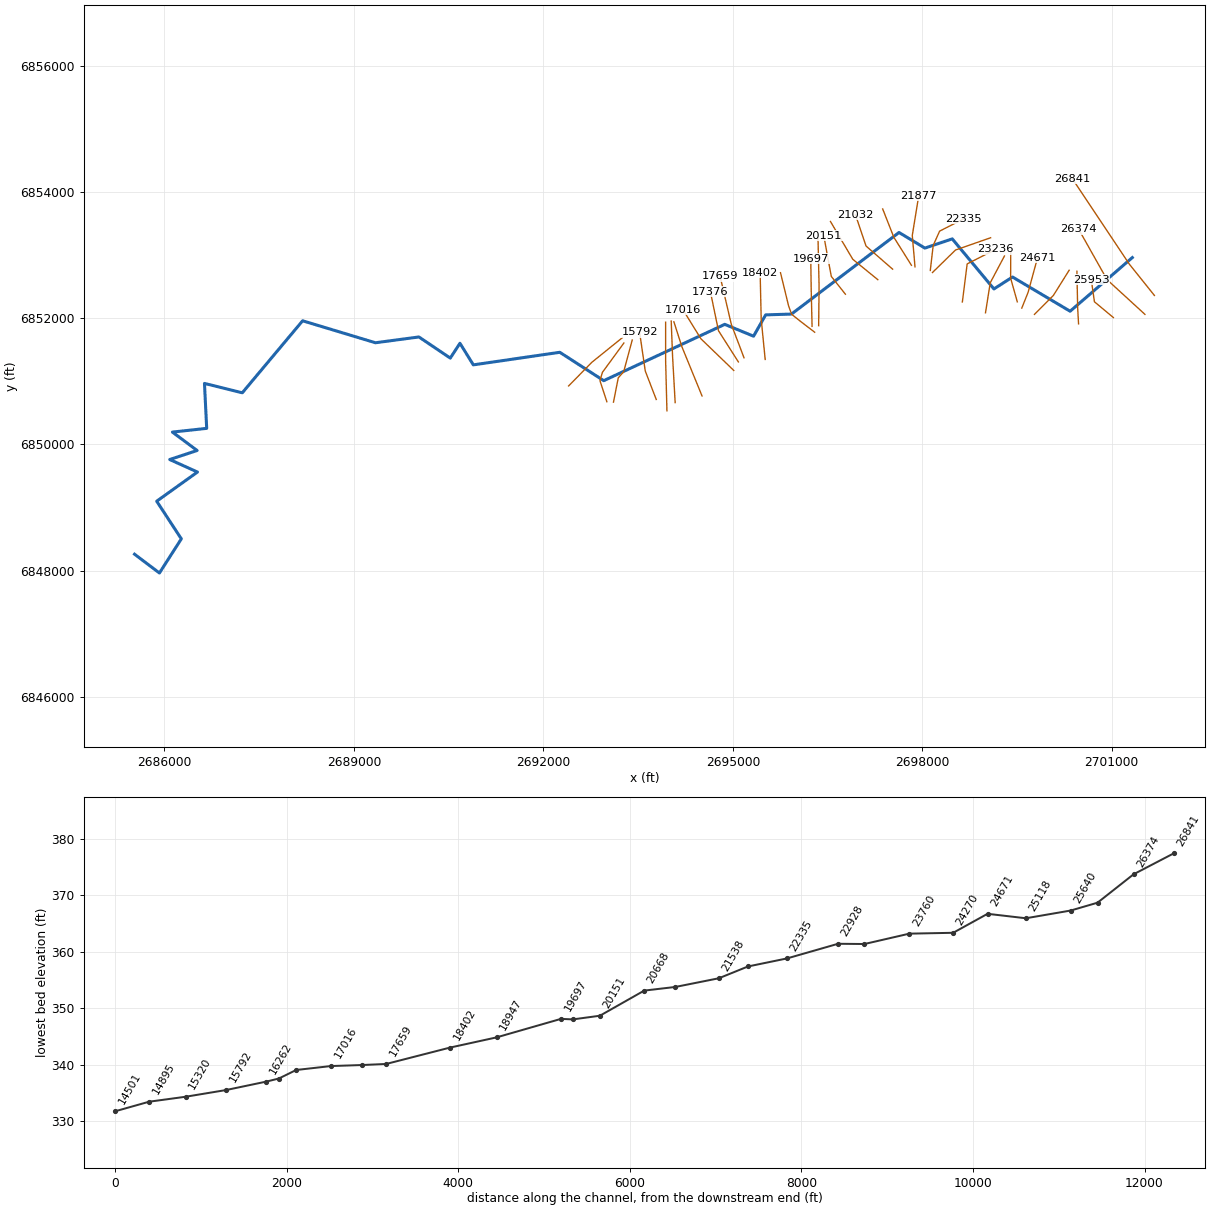
--- CCT3.prj (project) ---

Proj Title=CCT3 Base Level Engineering
Current Plan=p01
Default Exp/Contr=0.3,0.1
English Units
Geom File=g01
Flow File=f01
Plan File=p01
Y Axis Title=Elevation
X Axis Title(PF)=Main Channel Distance
X Axis Title(XS)=Station
BEGIN DESCRIPTION:
CCT3
END DESCRIPTION:
DSS Export Rating Curves= 0
DSS Export Rating Curve Sorted= 0
DSS Export Volume Flow Curves= 0
DXF OffsetX= 0
DXF OffsetY= 0
DXF ScaleX= 1
DXF ScaleY= 10

--- CCT3.p01 (plan) ---

Plan Title=Multiple Run
Short Identifier=Multiple
Geom File=g01
Flow File=f01
Subcritical Flow
K Sum by GR= 0
Std Step Tol= 0.01
Critical Tol= 0.01
Num of Std Step Trials= 20
Max Error Tol= 0.3
Flow Tol Ratio= 0.001
Split Flow NTrial= 30
Split Flow Tol= 0.02
Split Flow Ratio= 0.02
Log Output Level= 0
Friction Slope Method= 1
Unsteady Friction Slope Method= 2
Unsteady Bridges Friction Slope Method= 1
Parabolic Critical Depth
Global Vel Dist=  1 , 1 , 1
Global Log Level= 0
CheckData=True
Encroach Param= -1, 0, 0, 0
BEGIN DESCRIPTION:
Multiple Run
END DESCRIPTION:

--- CCT3.f01 (steady flow) ---

Flow Title=Multiple
Program Version=4.10
Number of Profiles= 7
Profile Names=10-year,25-year,50-year,1pct_min,100-year,1pct_plu,500-year
River Rch & RM=CCT3,Reach-1         ,26841
     551     733     879     523    1043    2081    1468
River Rch & RM=CCT3,Reach-1         ,23236
     869    1183    1440     868    1733    3457    2508
River Rch & RM=CCT3,Reach-1         ,18402
    1127    1554    1908    1159    2312    4613    3396
River Rch & RM=CCT3,Reach-1         ,14501
    1174    1627    2003    1219    2433    4855    3595
River Rch & RM=CCT3,Reach-1         ,13934
    1370    1904    2348    1431    2855    5697    4227
Boundary for River Rch & Prof#=CCT3,Reach-1         , 1
Up Type= 0
Dn Type= 3
Dn Slope=0.005
Boundary for River Rch & Prof#=CCT3,Reach-1         , 2
Up Type= 0
Dn Type= 3
Dn Slope=0.005
Boundary for River Rch & Prof#=CCT3,Reach-1         , 3
Up Type= 0
Dn Type= 3
Dn Slope=0.005
Boundary for River Rch & Prof#=CCT3,Reach-1         , 4
Up Type= 0
Dn Type= 3
Dn Slope=0.005
Boundary for River Rch & Prof#=CCT3,Reach-1         , 5
Up Type= 0
Dn Type= 3
Dn Slope=0.005
Boundary for River Rch & Prof#=CCT3,Reach-1         , 6
Up Type= 0
Dn Type= 3
Dn Slope=0.005
Boundary for River Rch & Prof#=CCT3,Reach-1         , 7
Up Type= 0
Dn Type= 3
Dn Slope=0.005
DSS Import GetInterval= 0
DSS Import GetPeak= 0
DSS Import FillOption= 0

--- CCT3.g01 (geometry) ---

Geom Title=Existing Conditions

River Reach=CCT3,Reach-1
Reach XY= 30
      2701326.00      6852961.00      2700341.21      6852110.89
      2699429.03      6852653.25      2699134.28      6852464.06
      2698474.78      6853257.57      2698041.26      6853111.37
      2697631.86      6853358.94      2695928.53      6852066.03
      2695519.81      6852053.18      2695328.37      6851715.61
      2694872.43      6851903.08      2692956.04      6851010.75
      2692260.17      6851460.34      2690891.07      6851261.18
      2690679.00      6851603.24      2690525.92      6851368.30
      2690029.40      6851703.17      2689341.27      6851611.36
      2688187.54      6851959.64      2687232.45      6850818.64
      2686633.48      6850967.09      2686668.55      6850254.93
      2686126.18      6850195.94      2686517.06      6849904.32
      2686083.06      6849761.00      2686522.92      6849562.67
      2685877.05      6849100.57      2686267.01      6848503.93
      2685920.11      6847962.96      2685526.00      6848261.00

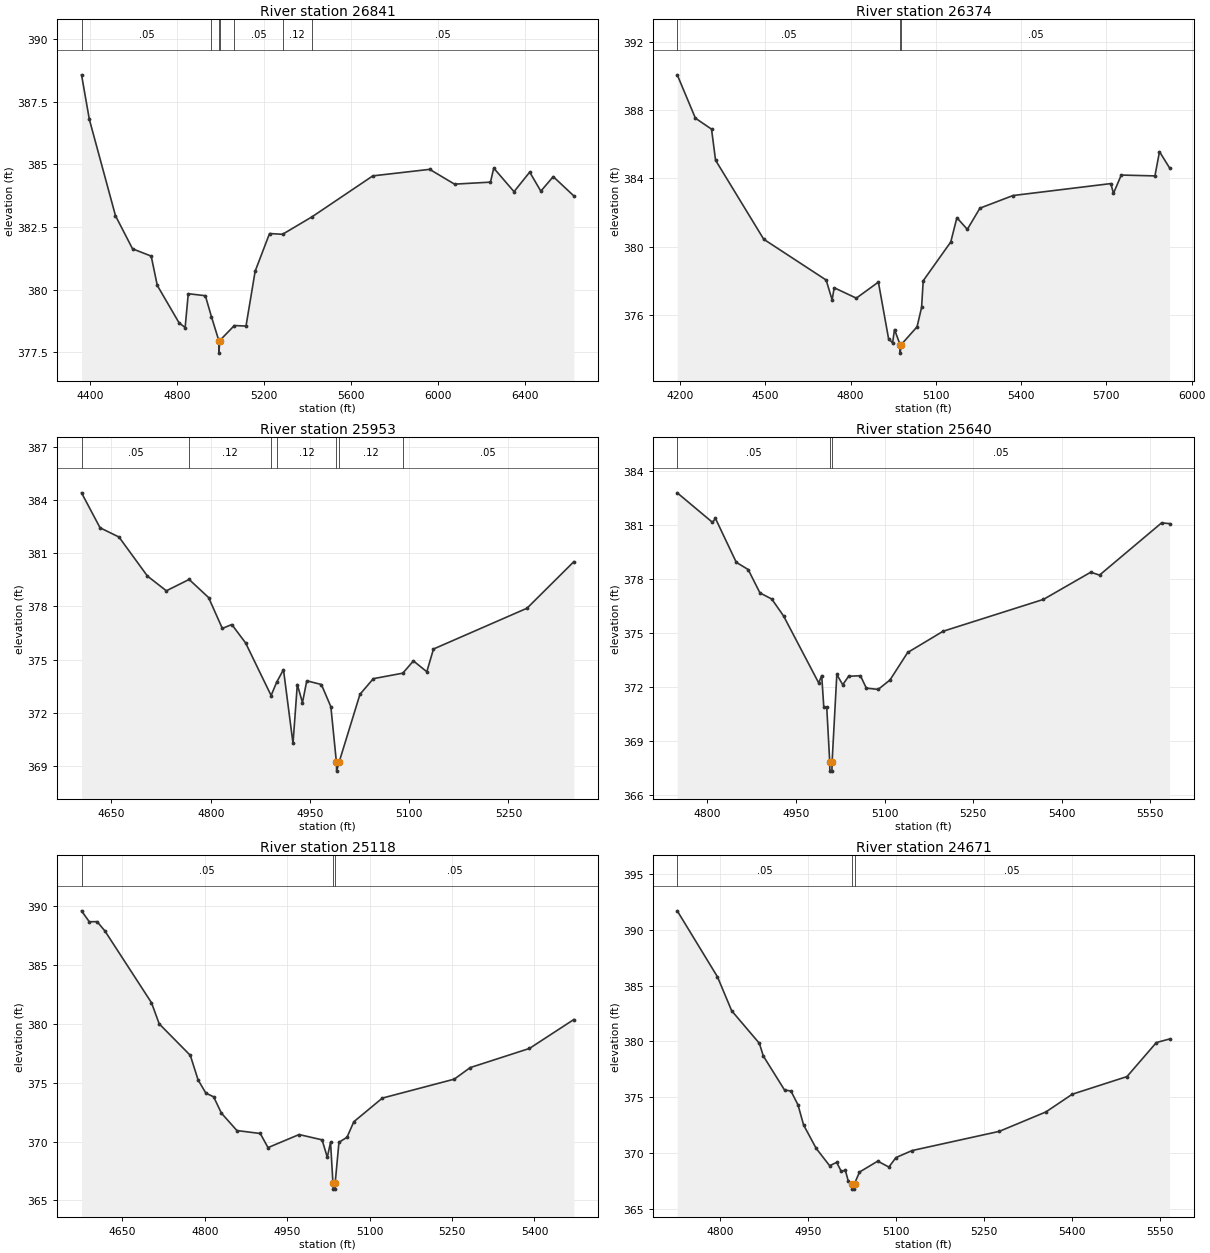
Type RM Length L Ch R = 1,26841,467,467,467
BEGIN DESCRIPTION:
CCT3 46.0
END DESCRIPTION:
XS GIS Cut Line= 3
      2701676.00      6852361.00      2701276.00      6852861.00
      2700376.01      6854210.99
#Sta/Elev= 30
  4360.2  388.57  4396.2  386.79  4516.3  382.95  4594.7  381.63  4680.4  381.34
  4708.4  380.17  4808.4  378.68  4836.4  378.49  4850.8  379.84  4929.3  379.76
  4957.4  378.92  4991.3  377.97  4991.6  377.47  4995.3  377.97  5062.5  378.57
  5116.2  378.55  5158.3  380.74  5224.4  382.24  5284.2  382.21  5420.2  382.91
  5699.1  384.54  5960.5  384.80  6074.7  384.21  6239.9  384.29  6254.9  384.85
  6348.1  383.91  6420.2  384.69  6471.3  383.93  6528.4  384.51  6623.0  383.74
#Mann=7,-1,0
  4360.2    0.05       0  4957.4    0.12       0  4991.3    0.07       0
  4995.3    0.12       0  5062.5    0.05       0  5284.2    0.12       0
  5420.2    0.05       0
Bank Sta=4991.3,4995.3
Exp/Cntr=0.3,0.1

Type RM Length L Ch R = 1,26374,421,421,421
BEGIN DESCRIPTION:
CCT3 45.0
END DESCRIPTION:
XS GIS Cut Line= 3
      2701526.03      6852060.98      2700926.00      6852611.00
      2700475.98      6853411.04
#Sta/Elev= 30
  4190.3  390.07  4254.2  387.53  4310.9  386.89  4325.1  385.07  4494.6  380.44
  4714.2  378.05  4735.1  376.89  4742.5  377.60  4820.2  376.99  4897.9  377.93
  4933.7  374.62  4947.9  374.37  4954.6  375.15  4974.2  374.27  4974.5  373.77
  4978.2  374.27  5033.9  375.31  5049.9  376.45  5055.6  378.01  5152.5  380.28
  5174.1  381.70  5210.8  381.02  5255.1  382.26  5371.4  383.00  5715.6  383.70
  5724.9  383.13  5752.3  384.20  5870.8  384.15  5886.8  385.57  5922.2  384.62
#Mann=3,-1,0
  4190.3    0.05       0  4974.2    0.04       0  4978.2    0.05       0
Bank Sta=4974.2,4978.2
Exp/Cntr=0.3,0.1

Type RM Length L Ch R = 1,25953,313,313,313
BEGIN DESCRIPTION:
CCT3 44.0
END DESCRIPTION:
XS GIS Cut Line= 3
      2701025.99      6852011.01      2700726.00      6852261.00
      2700676.01      6852610.95
#Sta/Elev= 30
  4604.8  384.40  4632.8  382.43  4661.4  381.91  4704.4  379.71  4733.0  378.88
  4767.4  379.52  4796.8  378.50  4817.6  376.76  4831.9  376.98  4852.8  375.94
  4891.3  372.98  4899.7  373.73  4910.0  374.44  4924.4  370.28  4930.9  373.60
  4938.7  372.58  4945.2  373.81  4967.3  373.60  4981.6  372.35  4990.0  369.22
  4990.3  368.72  4994.0  369.22  5025.6  373.05  5045.8  373.93  5090.3  374.24
  5106.4  374.93  5126.6  374.32  5136.7  375.60  5278.1  377.90  5348.8  380.52
#Mann=7,-1,0
  4604.8    0.05       0  4767.4    0.12       0  4891.3    0.05       0
  4899.7    0.12       0  4990.0    0.07       0  4994.0    0.12       0
  5090.3    0.05       0
Bank Sta=4990,4994
Exp/Cntr=0.3,0.1

Type RM Length L Ch R = 1,25640,522,522,522
BEGIN DESCRIPTION:
CCT3 43.0
END DESCRIPTION:
XS GIS Cut Line= 3
      2700474.59      6851911.13      2700460.60      6852161.95
      2700448.54      6852744.52
#Sta/Elev= 30
  4748.8  382.79  4808.5  381.15  4813.5  381.37  4848.8  378.93  4868.9  378.53
  4888.9  377.23  4908.9  376.89  4928.9  375.95  4988.4  372.23  4993.5  372.64
  4997.0  370.90  5002.0  370.90  5007.1  367.83  5007.3  367.33  5010.8  367.33
  5011.1  367.83  5019.1  372.70  5029.1  372.13  5039.1  372.60  5059.1  372.63
  5069.1  371.94  5089.1  371.87  5109.1  372.39  5139.1  373.92  5199.1  375.10
  5369.1  376.87  5449.2  378.38  5464.1  378.22  5569.2  381.12  5582.7  381.08
#Mann=3,-1,0
  4748.8    0.05       0  5007.1    0.05       0  5011.1    0.05       0
Bank Sta=5007.1,5011.1
Exp/Cntr=0.3,0.1

Type RM Length L Ch R = 1,25118,447,447,447
BEGIN DESCRIPTION:
CCT3 42.0
END DESCRIPTION:
XS GIS Cut Line= 3
      2699776.00      6852061.00      2700076.00      6852361.00
      2700326.02      6852761.03
#Sta/Elev= 30
  4575.7  389.62  4589.8  388.69  4604.0  388.70  4618.1  387.92  4703.0  381.81
  4717.1  380.01  4773.7  377.33  4787.8  375.25  4802.0  374.12  4816.1  373.81
  4830.3  372.42  4858.5  370.94  4901.0  370.69  4915.1  369.49  4971.7  370.60
  5013.5  370.15  5023.0  368.67  5028.9  369.95  5033.3  366.46  5033.6  365.96
  5037.1  365.96  5037.3  366.46  5044.2  369.94  5058.9  370.37  5071.3  371.69
  5123.2  373.70  5254.1  375.31  5283.0  376.29  5390.9  377.92  5471.7  380.38
#Mann=3,-1,0
  4575.7    0.05       0  5033.3    0.05       0  5037.3    0.05       0
Bank Sta=5033.3,5037.3
Exp/Cntr=0.3,0.1

Type RM Length L Ch R = 1,24671,401,401,401
BEGIN DESCRIPTION:
CCT3 41.0
END DESCRIPTION:
XS GIS Cut Line= 3
      2699576.02      6852161.04      2699676.00      6852411.00
      2699826.00      6852961.00
#Sta/Elev= 30
  4726.9  391.70  4795.5  385.78  4819.7  382.74  4866.9  379.82  4873.6  378.69
  4909.9  375.63  4920.7  375.55  4932.8  374.30  4942.3  372.50  4963.8  370.40
  4986.7  368.85  4998.7  369.15  5006.5  368.34  5013.4  368.45  5018.6  367.45
  5025.2  367.25  5025.5  366.75  5029.0  366.75  5029.2  367.25  5037.6  368.28
  5068.7  369.26  5087.7  368.73  5099.8  369.58  5127.4  370.21  5276.0  371.93
  5355.4  373.67  5400.4  375.26  5493.6  376.84  5543.7  379.89  5566.2  380.21
#Mann=3,-1,0
  4726.9    0.05       0  5025.2   0.035       0  5029.2    0.05       0
Bank Sta=5025.2,5029.2
Exp/Cntr=0.3,0.1

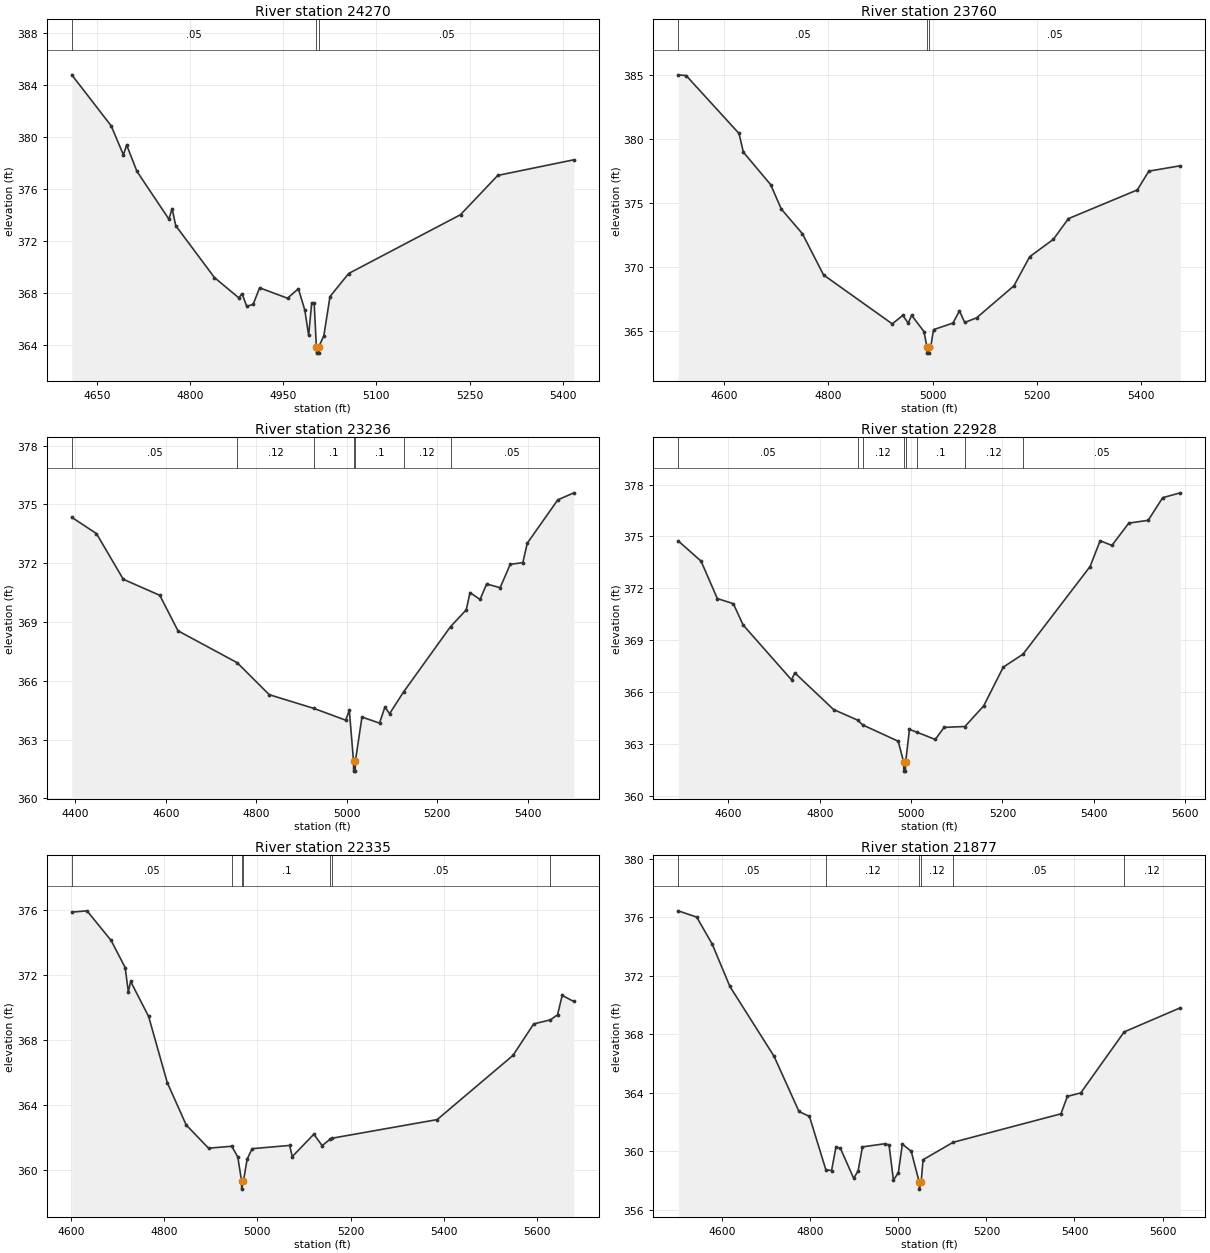
Type RM Length L Ch R = 1,24270,510,510,510
BEGIN DESCRIPTION:
CCT3 40.0
END DESCRIPTION:
XS GIS Cut Line= 3
      2699504.68      6852260.00      2699398.86      6852635.47
      2699401.00      6853053.37
#Sta/Elev= 30
  4609.9  384.77  4673.3  380.85  4693.0  378.62  4698.2  379.38  4714.8  377.35
  4766.2  373.68  4771.4  374.49  4777.2  373.18  4839.5  369.19  4878.7  367.63
  4883.9  367.95  4891.5  366.98  4901.8  367.13  4912.2  368.40  4957.1  367.60
  4974.6  368.33  4985.0  366.68  4991.1  364.74  4996.0  367.24  5000.0  367.24
  5003.5  363.88  5003.8  363.38  5007.3  363.38  5007.5  363.88  5015.5  364.70
  5025.5  367.73  5055.5  369.50  5235.5  374.02  5295.5  377.04  5417.9  378.24
#Mann=3,-1,0
  4609.9    0.05       0  5003.5    0.04       0  5007.5    0.05       0
Bank Sta=5003.5,5007.5
Exp/Cntr=0.3,0.1

Type RM Length L Ch R = 1,23760,524,524,524
BEGIN DESCRIPTION:
CCT3 39.0
END DESCRIPTION:
XS GIS Cut Line= 3
      2699001.01      6852086.03      2699076.00      6852561.00
      2699300.98      6852985.97
#Sta/Elev= 30
  4512.9  385.02  4528.1  384.96  4629.3  380.43  4637.7  378.96  4690.0  376.42
  4710.3  374.51  4750.8  372.58  4791.3  369.35  4922.9  365.52  4943.1  366.19
  4953.3  365.58  4960.0  366.19  4983.6  364.92  4989.2  363.73  4989.5  363.23
  4993.0  363.23  4993.2  363.73  4996.6  363.73  5001.9  365.07  5039.0  365.58
  5051.6  366.54  5061.6  365.63  5084.3  365.99  5155.9  368.50  5186.1  370.78
  5231.4  372.14  5260.3  373.76  5392.3  376.01  5414.3  377.48  5474.6  377.90
#Mann=3,-1,0
  4512.9    0.05       0  4989.2    0.04       0  4993.2    0.05       0
Bank Sta=4989.2,4993.2
Exp/Cntr=0.3,0.1

Type RM Length L Ch R = 1,23236,308,308,308
BEGIN DESCRIPTION:
CCT3 38.0
END DESCRIPTION:
XS GIS Cut Line= 3
      2698634.60      6852258.12      2698710.93      6852860.81
      2699157.59      6853089.28
#Sta/Elev= 30
  4392.5  374.34  4447.1  373.51  4506.3  371.18  4586.9  370.36  4627.2  368.55
  4758.1  366.92  4828.8  365.29  4927.4  364.59  4997.6  363.99  5005.7  364.49
  5015.0  361.89  5015.2  361.39  5018.7  361.39  5019.0  361.89  5033.6  364.15
  5072.4  363.84  5084.3  364.66  5094.6  364.32  5125.5  365.43  5229.2  368.76
  5264.0  369.62  5272.3  370.50  5294.5  370.15  5309.0  370.94  5338.9  370.75
  5361.1  371.94  5389.0  372.03  5398.8  373.02  5466.2  375.23  5501.7  375.59
#Mann=7,-1,0
  4392.5    0.05       0  4758.1    0.12       0  4927.4     0.1       0
  5015.0    0.07       0  5019.0     0.1       0  5125.5    0.12       0
  5229.2    0.05       0
Bank Sta=5015,5019
Exp/Cntr=0.3,0.1

Type RM Length L Ch R = 1,22928,593,593,593
BEGIN DESCRIPTION:
CCT3 37.0
END DESCRIPTION:
XS GIS Cut Line= 3
      2698161.50      6852724.69      2698526.08      6853081.03
      2699082.40      6853275.42
#Sta/Elev= 30
  4490.2  374.74  4540.2  373.57  4575.7  371.41  4610.9  371.11  4632.2  369.88
  4738.2  366.71  4745.4  367.11  4830.3  364.99  4882.8  364.38  4894.1  364.10
  4971.7  363.16  4983.9  361.93  4984.1  361.43  4987.6  361.43  4987.9  361.93
  4996.4  363.84  5013.8  363.67  5052.9  363.26  5072.2  363.96  5117.8  364.01
  5158.8  365.20  5201.7  367.44  5244.9  368.19  5391.8  373.26  5413.8  374.75
  5439.5  374.48  5476.6  375.77  5519.0  375.93  5550.7  377.24  5589.3  377.52
#Mann=8,-1,0
  4490.2    0.05       0  4882.8     0.1       0  4894.1    0.12       0
  4983.9    0.07       0  4987.9    0.12       0  5013.8     0.1       0
  5117.8    0.12       0  5244.9    0.05       0
Bank Sta=4983.9,4987.9
Exp/Cntr=0.3,0.1

Type RM Length L Ch R = 1,22335,458,458,458
BEGIN DESCRIPTION:
CCT3 36.0
END DESCRIPTION:
XS GIS Cut Line= 4
      2698126.79      6852757.27      2698172.79      6853152.70
      2698274.35      6853380.08      2698657.18      6853575.40
#Sta/Elev= 30
  4601.9  375.89  4634.6  375.97  4686.2  374.15  4716.4  372.48  4723.2  370.99
  4728.2  371.62  4766.7  369.47  4806.7  365.40  4847.3  362.79  4895.3  361.36
  4945.0  361.48  4958.0  360.82  4966.1  359.34  4966.3  358.84  4970.1  359.34
  4978.1  360.69  4988.9  361.33  5069.2  361.53  5074.8  360.84  5121.1  362.22
  5138.9  361.52  5156.4  361.92  5159.3  361.97  5385.6  363.12  5548.2  367.07
  5592.7  369.01  5628.6  369.26  5643.8  369.57  5653.8  370.76  5678.8  370.39
#Mann=7,-1,0
  4601.9    0.05       0  4945.0     0.1       0  4966.1    0.07       0
  4970.1     0.1       0  5156.4    0.12       0  5159.3    0.05       0
  5628.6    0.12       0
Bank Sta=4966.1,4970.1
Exp/Cntr=0.3,0.1

Type RM Length L Ch R = 1,21877,339,339,339
BEGIN DESCRIPTION:
CCT3 35.0
END DESCRIPTION:
XS GIS Cut Line= 3
      2697884.60      6852814.10      2697841.77      6853312.16
      2697944.32      6853944.19
#Sta/Elev= 30
  4500.1  376.43  4542.1  376.00  4577.3  374.15  4617.4  371.26  4717.8  366.48
  4774.3  362.71  4798.1  362.37  4835.3  358.73  4848.3  358.67  4858.3  360.28
  4868.4  360.19  4898.5  358.14  4908.5  358.64  4918.5  360.29  4968.7  360.50
  4978.8  360.43  4988.8  358.02  5000.0  358.52  5009.0  360.48  5029.2  359.99
  5047.2  357.90  5047.7  357.40  5051.8  357.90  5056.1  359.41  5124.2  360.60
  5369.2  362.55  5383.8  363.74  5414.2  363.98  5512.8  368.15  5640.3  369.80
#Mann=6,-1,0
  4500.1    0.05       0  4835.3    0.12       0  5047.2    0.07       0
  5051.8    0.12       0  5124.2    0.05       0  5512.8    0.12       0
Bank Sta=5047.2,5051.8
Exp/Cntr=0.3,0.1

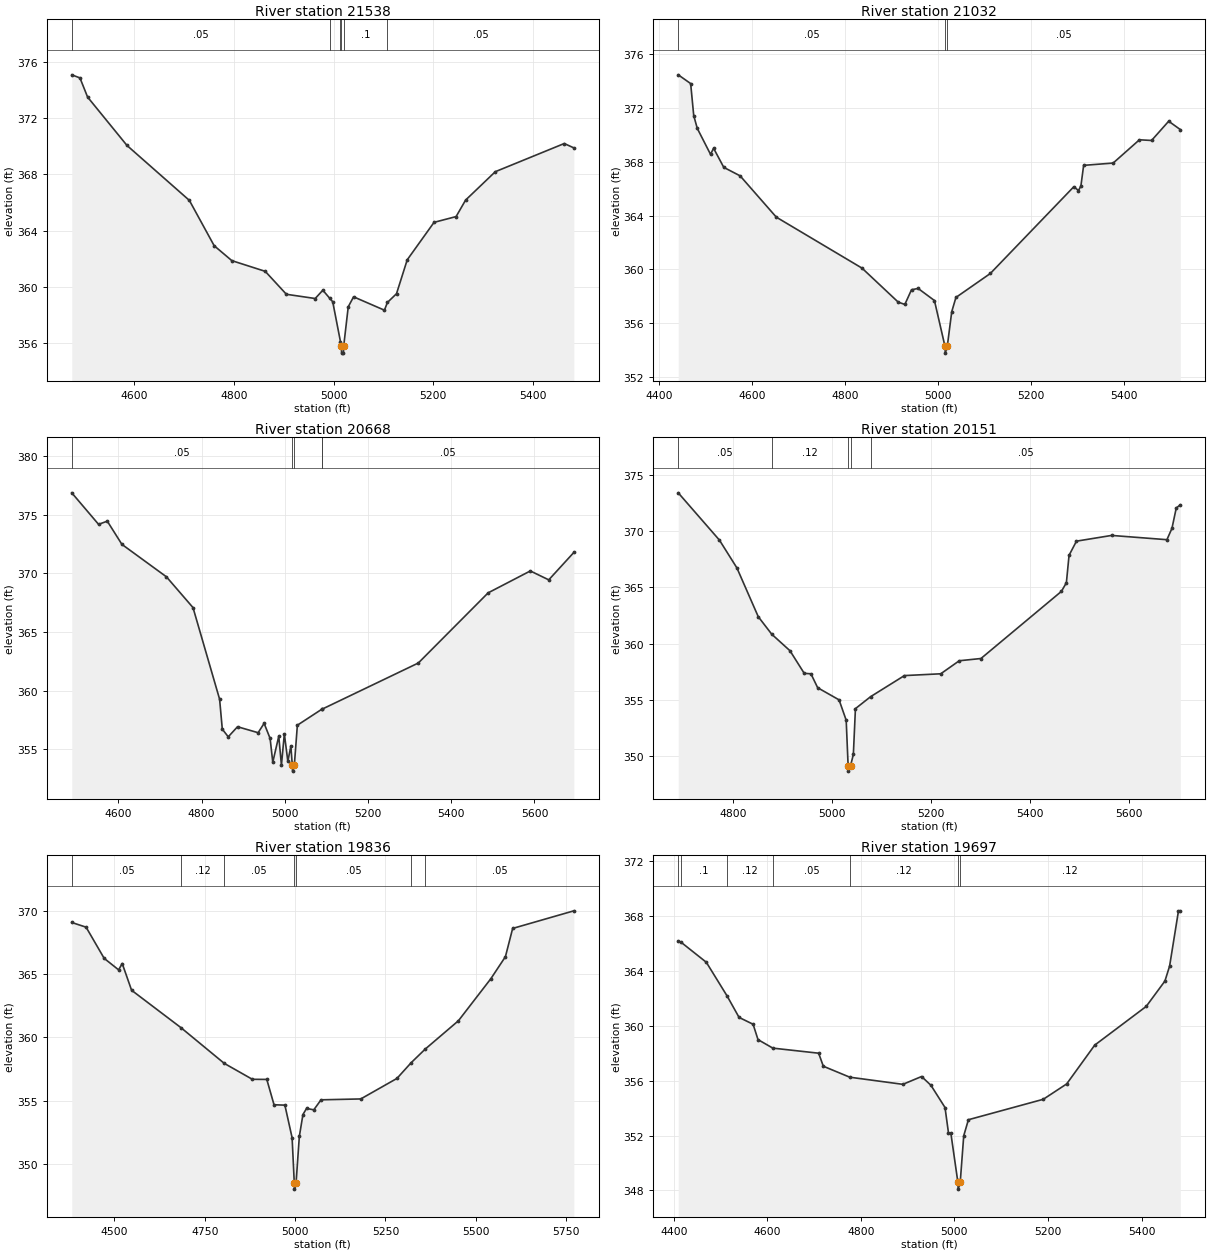
Type RM Length L Ch R = 1,21538,506,506,506
BEGIN DESCRIPTION:
CCT3 34.0
END DESCRIPTION:
XS GIS Cut Line= 3
      2697827.99      6852839.35      2697549.31      6853283.57
      2697373.14      6853731.69
#Sta/Elev= 30
  4475.6  375.08  4492.0  374.86  4507.3  373.50  4586.3  370.06  4711.2  366.16
  4760.9  362.94  4796.3  361.88  4863.2  361.12  4905.6  359.49  4963.3  359.19
  4978.6  359.78  4992.3  359.21  4998.4  358.96  5013.9  356.13  5015.6  355.81
  5016.2  355.31  5019.9  355.31  5020.4  355.81  5029.5  358.60  5040.2  359.31
  5102.0  358.36  5108.0  358.91  5126.2  359.53  5147.7  361.94  5201.4  364.60
  5245.6  365.01  5264.6  366.18  5324.2  368.20  5462.3  370.20  5481.5  369.89
#Mann=6,-1,0
  4475.6    0.05       0  4992.3    0.12       0  5013.9     0.1       0
  5015.6    0.07       0  5020.4     0.1       0  5108.0    0.05       0
Bank Sta=5015.6,5020.4
Exp/Cntr=0.3,0.1

Type RM Length L Ch R = 1,21032,364,364,364
BEGIN DESCRIPTION:
CCT3 33.0
END DESCRIPTION:
XS GIS Cut Line= 3
      2697530.23      6852777.73      2697109.31      6853144.21
      2696942.34      6853637.83
#Sta/Elev= 30
  4441.9  374.46  4468.6  373.81  4475.2  371.43  4482.8  370.48  4511.3  368.55
  4517.9  369.00  4539.8  367.58  4574.9  366.95  4652.7  363.88  4836.9  360.09
  4914.8  357.56  4929.0  357.39  4943.3  358.48  4957.5  358.58  4992.6  357.68
  5015.3  354.27  5015.9  353.77  5020.2  354.27  5029.8  356.85  5038.8  357.91
  5112.7  359.69  5292.2  366.14  5302.2  365.86  5307.4  366.19  5313.3  367.73
  5376.7  367.90  5433.2  369.63  5459.3  369.58  5496.1  371.01  5521.1  370.39
#Mann=3,-1,0
  4441.9    0.05       0  5015.3    0.04       0  5020.2    0.05       0
Bank Sta=5015.3,5020.2
Exp/Cntr=0.3,0.1

Type RM Length L Ch R = 1,20668,517,517,517
BEGIN DESCRIPTION:
CCT3 32.0
END DESCRIPTION:
XS GIS Cut Line= 3
      2697295.89      6852611.03      2696899.15      6852934.81
      2696545.90      6853532.88
#Sta/Elev= 30
  4487.9  376.88  4552.3  374.19  4573.3  374.46  4608.4  372.48  4715.4  369.71
  4779.3  367.08  4843.2  359.26  4849.7  356.70  4864.0  356.05  4886.3  356.91
  4935.8  356.40  4950.2  357.20  4964.6  355.91  4971.0  353.88  4985.4  356.10
  4991.8  353.63  4998.8  356.30  5007.2  353.96  5014.5  355.26  5017.9  353.62
  5018.5  353.12  5022.8  353.62  5030.1  357.04  5089.1  358.41  5089.5  358.41
  5320.8  362.35  5488.6  368.34  5590.0  370.21  5634.3  369.45  5694.6  371.79
#Mann=5,-1,0
  4487.9    0.05       0  5017.9    0.04       0  5022.8    0.05       0
  5089.1    0.12       0  5089.5    0.05       0
Bank Sta=5017.9,5022.8
Exp/Cntr=0.3,0.1

Type RM Length L Ch R = 1,20151,315,315,315
BEGIN DESCRIPTION:
CCT3 31.0
END DESCRIPTION:
XS GIS Cut Line= 3
      2696782.76      6852380.56      2696559.23      6852662.69
      2696440.19      6853307.65
#Sta/Elev= 30
  4688.8  373.42  4772.2  369.21  4807.5  366.74  4850.7  362.40  4878.0  360.84
  4914.9  359.37  4943.7  357.36  4957.3  357.32  4970.9  356.08  5014.2  355.00
  5028.6  353.19  5032.5  349.16  5033.2  348.66  5037.5  349.16  5043.1  350.14
  5047.3  354.22  5078.2  355.29  5146.4  357.16  5219.9  357.32  5257.4  358.48
  5301.3  358.68  5464.0  364.65  5474.1  365.42  5479.5  367.86  5494.5  369.12
  5565.6  369.63  5677.5  369.25  5687.7  370.26  5696.4  372.07  5704.6  372.35
#Mann=5,-1,0
  4688.8    0.05       0  4878.0    0.12       0  5032.5    0.07       0
  5037.5    0.12       0  5078.2    0.05       0
Bank Sta=5032.5,5037.5
Exp/Cntr=0.3,0.1

Type RM Length L Ch R = 1,19836,139,139,139
BEGIN DESCRIPTION:
Mapping XS f58395bb
END DESCRIPTION:
XS GIS Cut Line= 3
      2696359.14      6851881.43      2696366.08      6852502.96
      2696348.72      6853270.30
#Sta/Elev= 30
  4382.1  369.06  4421.7  368.69  4471.7  366.23  4511.7  365.32  4521.7  365.82
  4547.6  363.71  4684.5  360.75  4803.9  357.94  4881.7  356.68  4921.7  356.67
  4941.7  354.67  4971.7  354.64  4991.7  352.07  4997.7  348.51  4998.3  348.01
  5002.7  348.51  5011.7  352.17  5021.7  353.90  5031.7  354.38  5051.7  354.27
  5071.7  355.06  5181.7  355.13  5281.8  356.75  5321.1  357.99  5359.8  359.06
  5451.8  361.30  5541.8  364.63  5581.9  366.36  5601.9  368.59  5771.2  369.98
#Mann=7,-1,0
  4382.1    0.05       0  4684.5    0.12       0  4803.9    0.05       0
  4997.7    0.05       0  5002.7    0.05       0  5321.1    0.12       0
  5359.8    0.05       0
Bank Sta=4997.7,5002.7
Exp/Cntr=0.3,0.1

Type RM Length L Ch R = 1,19697,750,750,750
BEGIN DESCRIPTION:
Mapping XS f6691464
END DESCRIPTION:
XS GIS Cut Line= 3
      2696254.97      6851871.01      2696241.08      6852450.88
      2696234.14      6852943.90
#Sta/Elev= 30
  4409.7  366.18  4416.1  366.09  4469.7  364.64  4514.0  362.19  4539.7  360.62
  4569.7  360.12  4580.2  359.00  4611.9  358.38  4709.8  358.01  4719.8  357.06
  4776.4  356.26  4889.8  355.74  4929.8  356.31  4949.8  355.67  4979.9  354.05
  4987.3  352.20  4992.3  352.20  5007.4  348.60  5008.0  348.10  5012.4  348.60
  5019.9  351.99  5029.9  353.16  5189.9  354.65  5239.9  355.77  5299.9  358.60
  5409.9  361.42  5449.9  363.27  5459.9  364.36  5478.9  368.39  5482.8  368.39
#Mann=7,-1,0
  4409.7    0.05       0  4416.1     0.1       0  4514.0    0.12       0
  4611.9    0.05       0  4776.4    0.12       0  5007.4    0.07       0
  5012.4    0.12       0
Bank Sta=5007.4,5012.4
Exp/Cntr=0.3,0.1

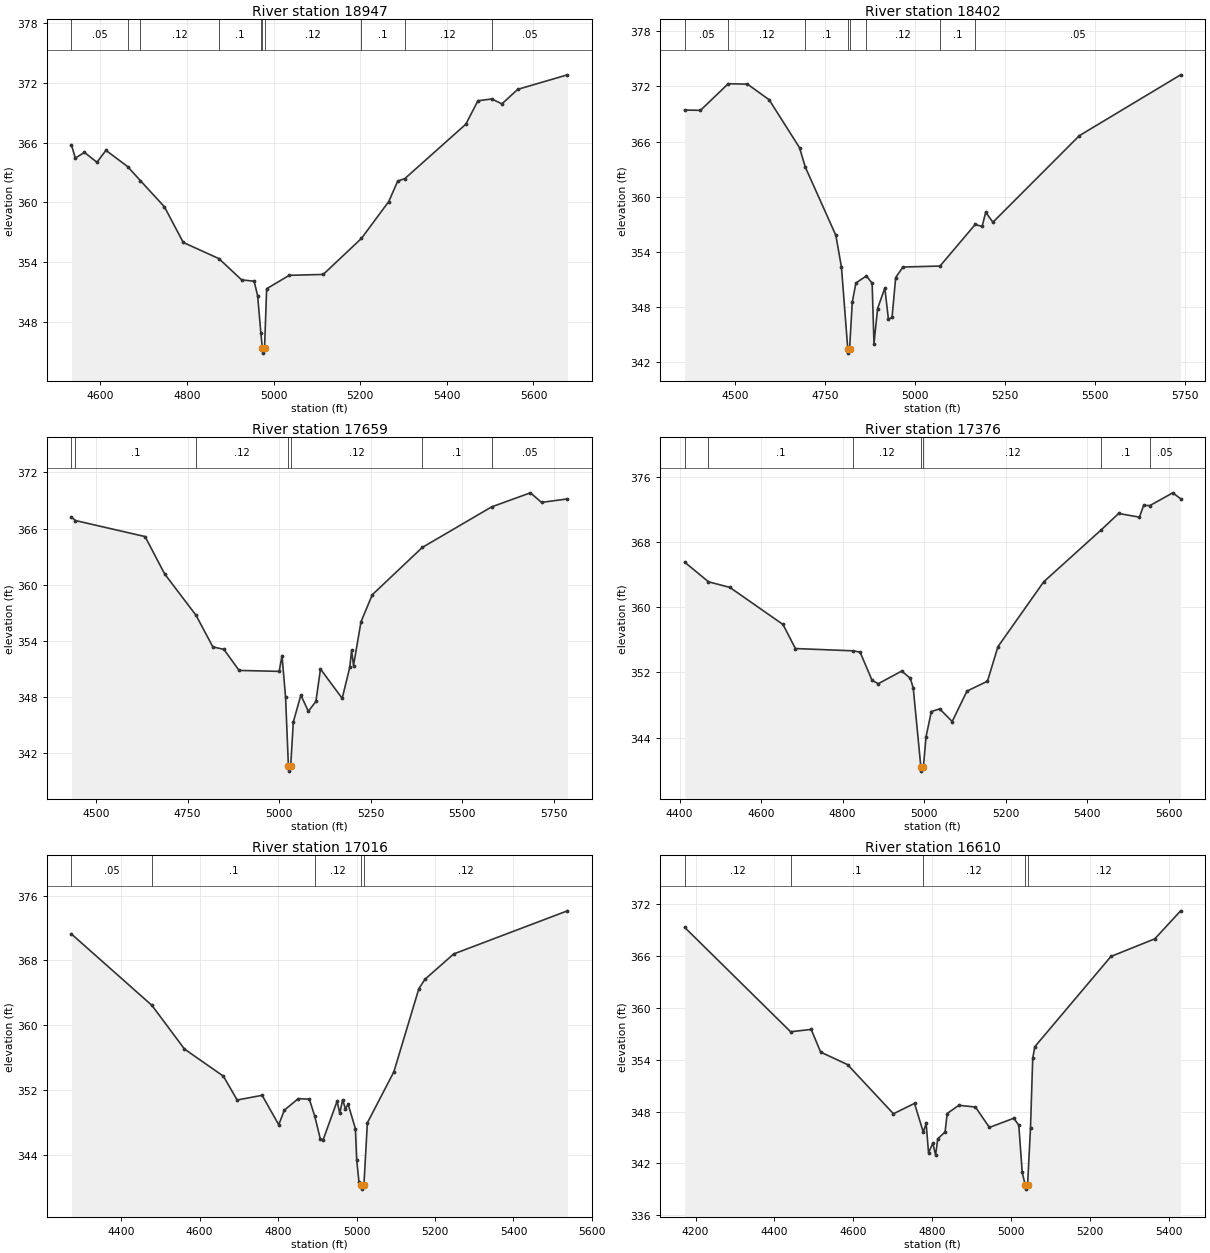
Type RM Length L Ch R = 1,18947,545,545,545
BEGIN DESCRIPTION:
Mapping XS 02ddecfe
END DESCRIPTION:
XS GIS Cut Line= 5
      2696295.73      6851778.73      2696090.65      6851935.62
      2695932.06      6852061.99      2695883.45      6852193.94
      2695754.97      6852721.72
#Sta/Elev= 30
  4533.6  365.77  4542.6  364.45  4563.4  365.03  4592.4  364.03  4613.2  365.23
  4663.1  363.60  4692.7  362.18  4748.3  359.54  4791.6  355.96  4874.1  354.33
  4926.4  352.19  4955.2  352.06  4963.3  350.60  4970.8  346.84  4974.2  345.32
  4974.9  344.82  4979.3  345.32  4984.1  351.30  5036.2  352.65  5114.7  352.74
  5203.0  356.37  5266.0  360.08  5286.6  362.13  5303.2  362.39  5443.8  367.86
  5471.8  370.22  5503.6  370.40  5527.2  369.91  5563.8  371.37  5678.4  372.83
#Mann=10,-1,0
  4533.6    0.05       0  4663.1     0.1       0  4692.7    0.12       0
  4874.1     0.1       0  4970.8    0.12       0  4974.2    0.07       0
  4979.3    0.12       0  5203.0     0.1       0  5303.2    0.12       0
  5503.6    0.05       0
Bank Sta=4974.2,4979.3
Exp/Cntr=0.3,0.1

Type RM Length L Ch R = 1,18402,743,743,743
BEGIN DESCRIPTION:
CCT3 27.0
END DESCRIPTION:
XS GIS Cut Line= 3
      2695512.40      6851347.24      2695449.24      6851984.42
      2695432.49      6852722.63
#Sta/Elev= 30
  4359.7  369.43  4403.7  369.40  4480.8  372.29  4534.3  372.25  4594.6  370.55
  4679.0  365.34  4695.1  363.23  4780.0  355.81  4795.6  352.35  4813.1  343.50
  4813.8  343.00  4818.2  343.50  4825.7  348.55  4835.8  350.63  4864.9  351.39
  4880.9  350.60  4886.0  344.03  4896.1  347.85  4916.2  350.08  4926.2  346.67
  4936.3  346.90  4946.3  351.21  4966.4  352.36  5069.6  352.47  5167.4  356.99
  5186.6  356.77  5196.6  358.32  5216.6  357.23  5456.7  366.64  5738.4  373.26
#Mann=8,-1,0
  4359.7    0.05       0  4480.8    0.12       0  4695.1     0.1       0
  4813.1    0.07       0  4818.2     0.1       0  4864.9    0.12       0
  5069.6     0.1       0  5167.4    0.05       0
Bank Sta=4813.1,4818.2
Exp/Cntr=0.3,0.1

Type RM Length L Ch R = 1,17659,283,283,283
BEGIN DESCRIPTION:
CCT3 25.0
END DESCRIPTION:
XS GIS Cut Line= 3
      2695177.15      6851373.02      2694976.00      6851903.46
      2694796.93      6852669.92
#Sta/Elev= 30
  4432.7  367.22  4443.7  366.85  4633.7  365.14  4687.2  361.15  4773.0  356.73
  4818.8  353.36  4848.9  353.10  4890.4  350.85  5000.0  350.75  5007.7  352.43
  5017.4  347.98  5025.2  340.60  5026.2  340.10  5031.3  340.60  5038.5  345.34
  5059.1  348.21  5079.6  346.49  5100.2  347.54  5112.7  351.00  5172.0  347.87
  5192.6  351.17  5197.8  352.99  5202.9  351.37  5223.4  356.05  5254.2  358.93
  5390.8  363.98  5580.1  368.31  5686.0  369.81  5716.3  368.79  5787.1  369.16
#Mann=7,-1,0
  4432.7    0.05       0  4443.7     0.1       0  4773.0    0.12       0
  5025.2    0.07       0  5031.3    0.12       0  5390.8     0.1       0
  5580.1    0.05       0
Bank Sta=5025.2,5031.3
Exp/Cntr=0.3,0.1

Type RM Length L Ch R = 1,17376,360,360,360
BEGIN DESCRIPTION:
Mapping XS 6361c678
END DESCRIPTION:
XS GIS Cut Line= 3
      2695087.75      6851307.91      2694772.62      6851802.73
      2694645.02      6852419.93
#Sta/Elev= 30
  4412.6  365.52  4471.1  363.11  4523.6  362.42  4653.9  357.88  4684.4  354.93
  4826.2  354.65  4843.1  354.49  4872.3  351.05  4887.6  350.62  4945.1  352.17
  4966.3  351.29  4973.5  350.08  4992.2  340.41  4993.2  339.91  4998.4  340.41
  5004.9  344.13  5017.9  347.21  5038.3  347.54  5069.0  345.99  5105.4  349.72
  5155.6  350.93  5181.3  355.16  5293.6  363.11  5435.2  369.50  5477.4  371.48
  5528.5  371.03  5538.7  372.47  5554.2  372.45  5610.2  374.01  5629.5  373.29
#Mann=7,-1,0
  4412.6    0.05       0  4471.1     0.1       0  4826.2    0.12       0
  4992.2    0.07       0  4998.4    0.12       0  5435.2     0.1       0
  5554.2    0.05       0
Bank Sta=4992.2,4998.4
Exp/Cntr=0.3,0.1

Type RM Length L Ch R = 1,17016,406,406,406
BEGIN DESCRIPTION:
Mapping XS cc324ea7
END DESCRIPTION:
XS GIS Cut Line= 3
      2695014.81      6851172.52      2694493.98      6851675.13
      2694210.56      6852135.36
#Sta/Elev= 30
  4273.3  371.27  4478.4  362.45  4561.4  357.05  4660.5  353.70  4695.7  350.75
  4759.3  351.33  4801.7  347.69  4815.9  349.49  4851.4  350.92  4879.7  350.85
  4893.4  348.76  4908.0  345.87  4914.9  345.84  4950.4  350.60  4957.3  349.10
  4964.5  350.78  4971.5  349.69  4978.7  350.20  4997.1  347.20  5000.4  343.33
  5006.3  340.58  5012.6  340.23  5013.6  339.73  5018.8  340.23  5027.6  347.93
  5095.1  354.23  5158.9  364.52  5174.3  365.67  5247.7  368.81  5537.6  374.14
#Mann=5,-1,0
  4273.3    0.05       0  4478.4     0.1       0  4893.4    0.12       0
  5012.6    0.07       0  5018.8    0.12       0
Bank Sta=5012.6,5018.8
Exp/Cntr=0.3,0.1

Type RM Length L Ch R = 1,16610,203,203,203
BEGIN DESCRIPTION:
Mapping XS d5debc1b
END DESCRIPTION:
XS GIS Cut Line= 3
      2694512.22      6850768.86      2694191.89      6851552.73
      2694066.91      6851943.32
#Sta/Elev= 30
  4172.3  369.32  4440.8  357.24  4493.0  357.51  4517.0  354.88  4585.1  353.44
  4701.4  347.75  4754.8  348.95  4777.1  345.62  4784.3  346.64  4790.4  343.23
  4801.2  344.34  4808.3  342.98  4813.7  344.85  4832.3  345.65  4837.7  347.78
  4867.1  348.73  4909.2  348.53  4944.6  346.17  5006.4  347.23  5019.1  346.43
  5027.8  340.97  5035.2  339.53  5036.2  339.03  5041.4  339.53  5048.8  346.16
  5054.4  354.17  5059.7  355.51  5252.6  365.95  5363.8  367.99  5429.2  371.23
#Mann=5,-1,0
  4172.3    0.12       0  4440.8     0.1       0  4777.1    0.12       0
  5035.2    0.07       0  5041.4    0.12       0
Bank Sta=5035.2,5041.4
Exp/Cntr=0.3,0.1

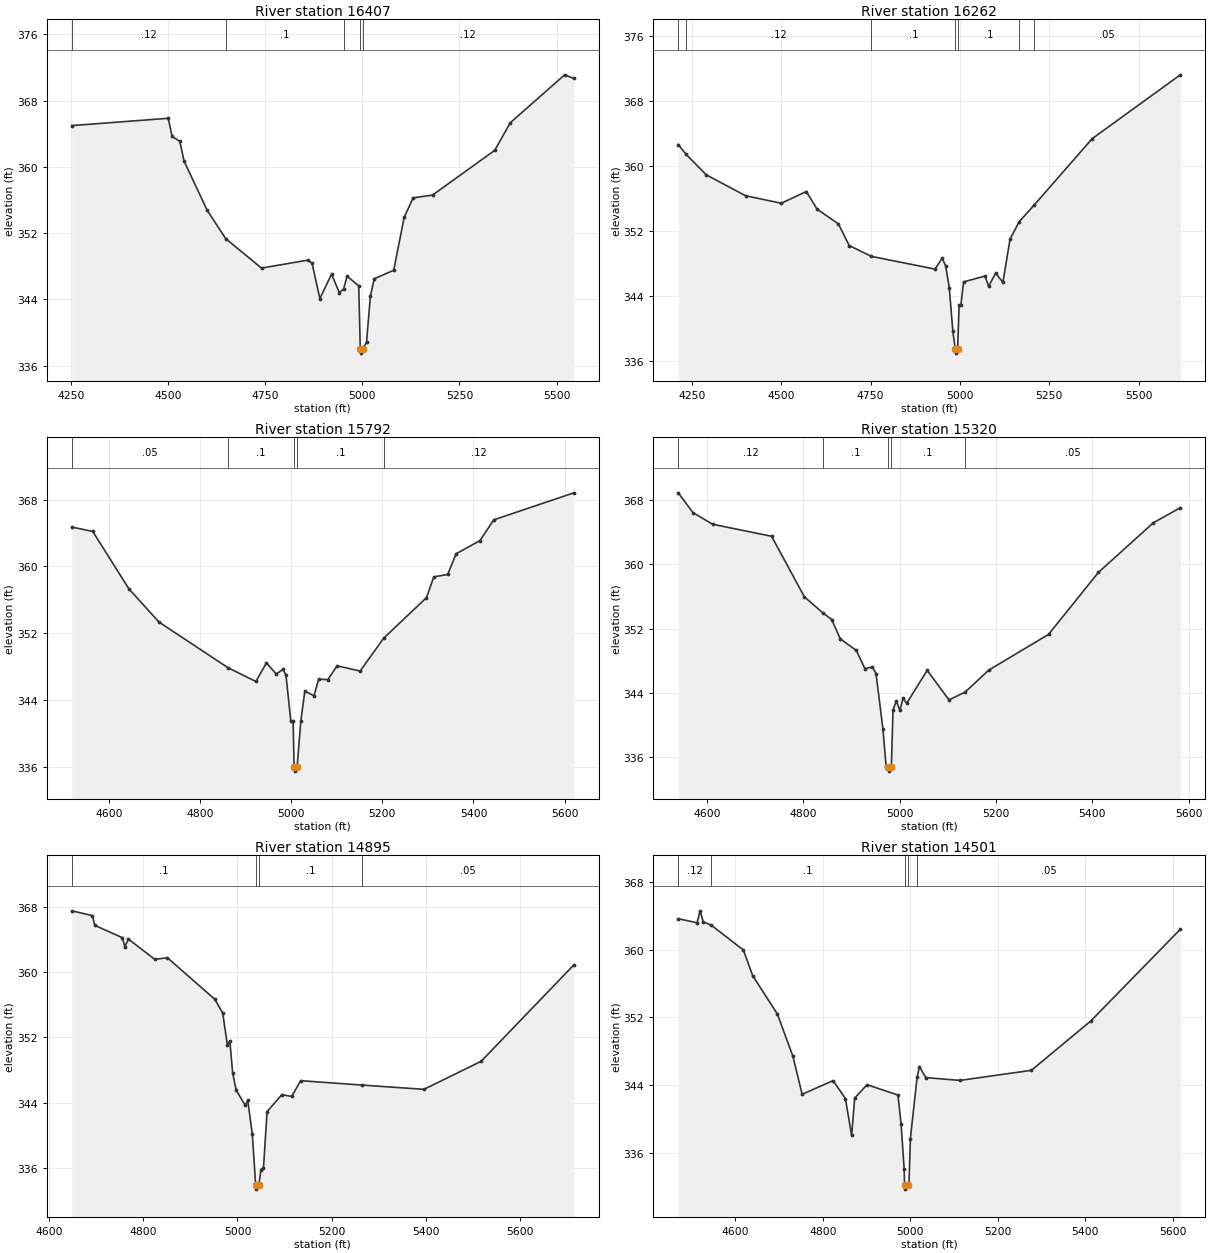
Type RM Length L Ch R = 1,16407,145,145,145
BEGIN DESCRIPTION:
Mapping XS da7b2164
END DESCRIPTION:
XS GIS Cut Line= 3
      2694086.86      6850662.93      2694045.19      6851410.37
      2694024.36      6851954.68
#Sta/Elev= 30
  4251.3  364.99  4499.8  365.87  4509.8  363.68  4529.8  363.07  4540.5  360.71
  4599.9  354.78  4647.7  351.34  4740.1  347.78  4860.3  348.75  4870.3  348.35
  4890.4  344.09  4920.4  347.05  4940.4  344.83  4951.4  345.25  4960.5  346.80
  4990.5  345.64  4994.5  338.01  4995.5  337.51  5001.0  338.01  5010.5  338.82
  5020.5  344.39  5030.5  346.49  5080.6  347.52  5107.6  353.92  5130.6  356.26
  5180.7  356.60  5340.8  362.00  5380.8  365.33  5520.9  371.12  5544.6  370.68
#Mann=5,-1,0
  4251.3    0.12       0  4647.7     0.1       0  4951.4    0.12       0
  4994.5    0.07       0  5001.0    0.12       0
Bank Sta=4994.5,5001
Exp/Cntr=0.3,0.1

Type RM Length L Ch R = 1,16262,470,470,470
BEGIN DESCRIPTION:
Mapping XS 6cd0d902
END DESCRIPTION:
XS GIS Cut Line= 3
      2693956.65      6850532.74      2693936.05      6851320.87
      2693935.82      6851937.47
#Sta/Elev= 30
  4211.6  362.68  4232.7  361.51  4289.9  358.95  4399.9  356.37  4500.0  355.44
  4570.0  356.89  4600.0  354.72  4660.0  352.89  4690.0  350.23  4752.4  348.89
  4930.1  347.33  4950.1  348.66  4960.1  347.72  4970.1  345.00  4980.1  339.65
  4986.9  337.47  4987.9  336.97  4993.4  337.47  4997.6  342.88  5002.6  342.88
  5010.1  345.75  5070.1  346.47  5080.1  345.22  5100.1  346.83  5120.1  345.69
  5140.1  351.01  5165.4  353.15  5207.4  355.21  5370.1  363.41  5616.6  371.27
#Mann=7,-1,0
  4211.6    0.05       0  4232.7    0.12       0  4752.4     0.1       0
  4986.9    0.07       0  4993.4     0.1       0  5165.4    0.12       0
  5207.4    0.05       0
Bank Sta=4986.9,4993.4
Exp/Cntr=0.3,0.1

Type RM Length L Ch R = 1,15792,472,472,472
BEGIN DESCRIPTION:
Mapping XS 036defda
END DESCRIPTION:
XS GIS Cut Line= 3
      2693787.37      6850712.48      2693612.90      6851165.58
      2693524.36      6851774.95
#Sta/Elev= 30
  4518.9  364.71  4565.0  364.18  4644.3  357.30  4710.2  353.33  4861.5  347.86
  4922.7  346.21  4945.9  348.44  4967.4  347.11  4982.7  347.67  4988.8  346.96
  4999.3  341.50  5004.4  341.50  5006.6  335.97  5007.7  335.47  5013.2  335.97
  5021.4  341.51  5030.1  345.05  5050.3  344.50  5060.4  346.49  5080.6  346.43
  5100.9  348.09  5151.4  347.46  5203.3  351.41  5296.9  356.25  5313.1  358.74
  5343.4  359.03  5362.0  361.51  5414.1  363.08  5444.4  365.57  5620.2  368.81
#Mann=5,-1,0
  4518.9    0.05       0  4861.5     0.1       0  5006.6    0.07       0
  5013.2     0.1       0  5203.3    0.12       0
Bank Sta=5006.6,5013.2
Exp/Cntr=0.3,0.1

Type RM Length L Ch R = 1,15320,425,425,425
BEGIN DESCRIPTION:
Mapping XS 26e37305
END DESCRIPTION:
XS GIS Cut Line= 4
      2693110.29      6850670.77      2693185.82      6851056.21
      2693271.76      6851152.56      2693407.17      6851655.17
#Sta/Elev= 30
  4540.1  368.88  4570.9  366.41  4611.7  364.97  4733.9  363.48  4802.0  355.95
  4840.0  353.97  4858.6  353.13  4876.6  350.72  4910.0  349.28  4927.6  347.02
  4943.3  347.23  4950.8  346.39  4965.0  339.56  4971.7  334.86  4975.9  334.78
  4977.0  334.28  4982.6  334.78  4986.0  341.86  4992.9  343.03  5000.2  341.83
  5006.9  343.33  5014.4  342.72  5057.0  346.81  5102.2  343.14  5135.7  344.10
  5184.6  346.83  5308.9  351.28  5412.5  358.99  5526.4  365.15  5582.5  367.03
#Mann=5,-1,0
  4540.1    0.12       0  4840.0     0.1       0  4975.9    0.07       0
  4982.6     0.1       0  5135.7    0.05       0
Bank Sta=4975.9,4982.6
Exp/Cntr=0.3,0.1

Type RM Length L Ch R = 1,14895,394,394,394
BEGIN DESCRIPTION:
Mapping XS 6aa669f2
END DESCRIPTION:
XS GIS Cut Line= 4
      2693005.35      6850676.79      2692895.97      6851010.11
      2692935.04      6851142.92      2693275.06      6851607.54
#Sta/Elev= 30
  4648.5  367.48  4692.1  366.90  4697.4  365.70  4755.8  364.19  4761.1  363.10
  4768.7  364.02  4824.7  361.53  4851.3  361.74  4952.0  356.64  4968.7  354.96
  4978.6  351.03  4983.8  351.55  4989.7  347.66  4997.1  345.54  5016.5  343.65
  5021.7  344.31  5031.5  340.10  5038.6  333.90  5039.6  333.40  5045.3  333.90
  5049.9  335.80  5055.1  335.98  5062.8  342.89  5094.0  344.97  5114.9  344.75
  5134.1  346.68  5264.7  346.14  5395.6  345.62  5516.8  349.05  5713.5  360.86
#Mann=4,-1,0
  4648.5     0.1       0  5038.6    0.07       0  5045.3     0.1       0
  5264.7    0.05       0
Bank Sta=5038.6,5045.3
Exp/Cntr=0.3,0.1

Type RM Length L Ch R = 1,14501,567,567,567
BEGIN DESCRIPTION:
Mapping XS 9a9ed93b
END DESCRIPTION:
XS GIS Cut Line= 3
      2692399.47      6850926.81      2692767.50      6851301.78
      2693252.29      6851693.07
#Sta/Elev= 30
  4469.1  363.67  4512.1  363.19  4519.1  364.60  4526.2  363.31  4544.7  362.90
  4618.1  359.97  4639.4  356.94  4695.9  352.40  4731.2  347.44  4752.5  342.92
  4823.2  344.53  4851.5  342.42  4865.7  338.06  4872.7  342.48  4901.0  344.05
  4971.7  342.83  4978.8  339.43  4985.8  334.14  4986.8  332.21  4987.9  331.71
  4994.2  332.21  4996.8  332.21  5000.1  337.69  5015.4  344.93  5020.9  346.19
  5035.3  344.89  5113.7  344.56  5276.8  345.75  5412.7  351.58  5617.5  362.42
#Mann=5,-1,0
  4469.1    0.12       0  4544.7     0.1       0  4986.8    0.07       0
  4994.2     0.1       0  5015.4    0.05       0
Bank Sta=4986.8,4994.2
Exp/Cntr=0.3,0.1