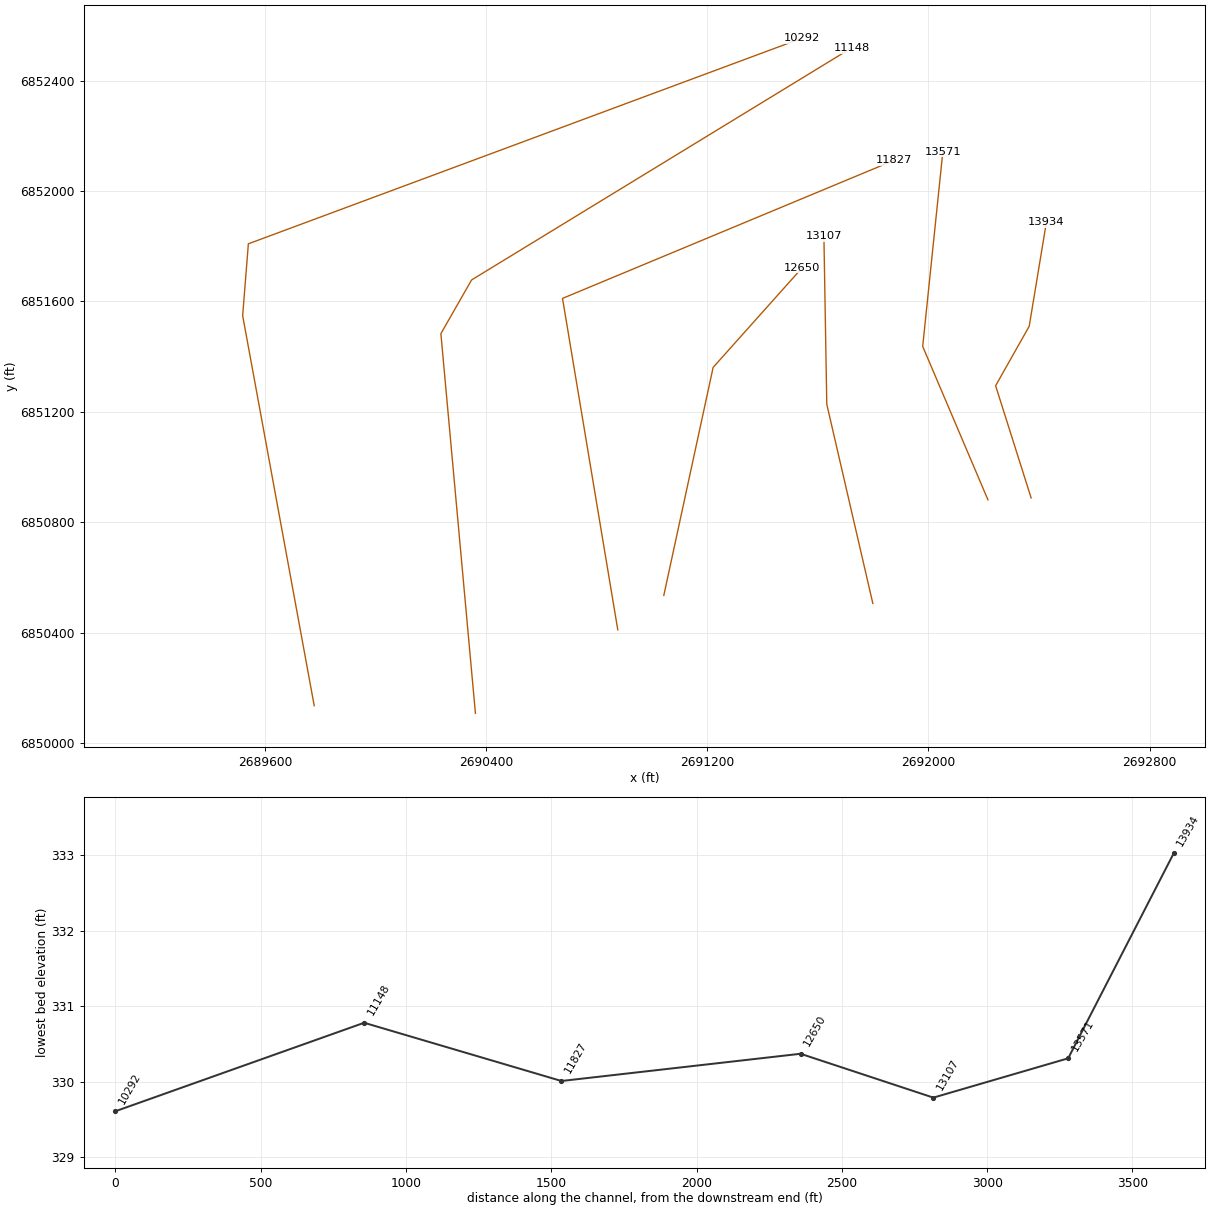
HEC-RAS study CCT3.prj: CCT3 Base Level Engineering

--- CCT3.g01 (geometry) --- (continued)

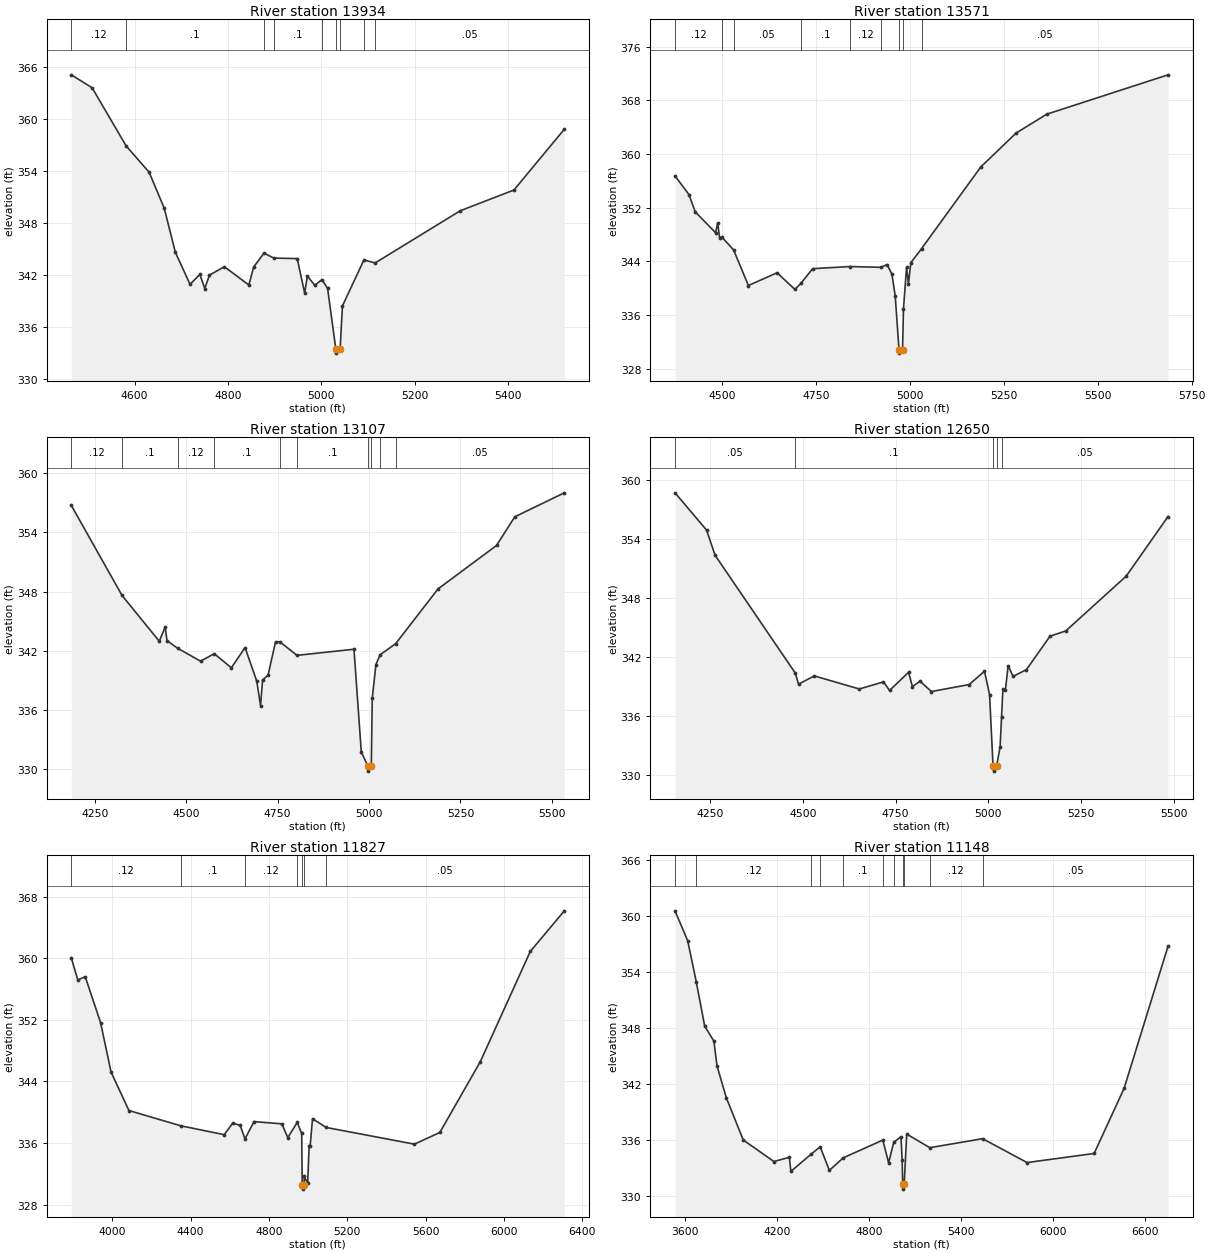
Type RM Length L Ch R = 1,13934,363,363,363
BEGIN DESCRIPTION:
Mapping XS 4f809bbc
END DESCRIPTION:
XS GIS Cut Line= 4
      2692371.66      6850888.60      2692243.20      6851294.83
      2692364.72      6851510.11      2692427.02      6851887.33
#Sta/Elev= 30
  4464.7  365.11  4509.2  363.62  4582.0  356.92  4631.3  353.88  4663.6  349.74
  4687.5  344.64  4718.9  340.95  4739.9  342.10  4750.4  340.47  4760.5  342.02
  4792.4  342.98  4844.8  340.88  4855.3  342.97  4877.3  344.55  4898.1  343.98
  4948.4  343.92  4964.3  339.95  4970.1  341.91  4986.0  340.84  5001.3  341.50
  5013.4  340.49  5031.0  333.52  5032.3  333.02  5040.3  333.52  5045.2  338.46
  5091.2  343.76  5115.3  343.42  5297.6  349.44  5412.5  351.83  5520.3  358.84
#Mann=9,-1,0
  4464.7    0.12       0  4582.0     0.1       0  4877.3    0.05       0
  4898.1     0.1       0  5001.3    0.05       0  5031.0    0.07       0
  5040.3    0.05       0  5091.2     0.1       0  5115.3    0.05       0
Bank Sta=5031,5040.3
Exp/Cntr=0.3,0.1

Type RM Length L Ch R = 1,13571,464,464,464
BEGIN DESCRIPTION:
Mapping XS bfee9e11
END DESCRIPTION:
XS GIS Cut Line= 3
      2692215.43      6850881.61      2691979.31      6851437.20
      2692052.22      6852142.05
#Sta/Elev= 30
  4374.8  356.73  4411.9  353.95  4428.5  351.38  4482.8  348.26  4488.3  349.72
  4493.7  347.46  4499.5  347.61  4530.8  345.69  4570.1  340.39  4646.5  342.29
  4693.8  339.81  4710.1  340.73  4741.1  342.90  4840.4  343.22  4923.4  343.10
  4939.2  343.52  4952.0  342.11  4960.9  338.86  4971.0  330.81  4972.3  330.31
  4980.4  330.81  4982.9  336.91  4991.1  343.11  4996.2  340.67  5002.4  343.79
  5031.0  345.89  5188.8  358.07  5282.7  363.12  5364.3  365.93  5687.1  371.80
#Mann=9,-1,0
  4374.8    0.12       0  4499.5     0.1       0  4530.8    0.05       0
  4710.1     0.1       0  4840.4    0.12       0  4923.4     0.1       0
  4971.0    0.07       0  4980.4     0.1       0  5031.0    0.05       0
Bank Sta=4971,4980.4
Exp/Cntr=0.3,0.1

Type RM Length L Ch R = 1,13107,457,457,457
BEGIN DESCRIPTION:
Mapping XS c77026a6
END DESCRIPTION:
XS GIS Cut Line= 3
      2691798.93      6850506.37      2691632.26      6851227.73
      2691621.85      6851836.57
#Sta/Elev= 30
  4185.2  356.73  4324.1  347.60  4426.0  342.96  4442.0  344.40  4447.1  343.02
  4476.5  342.24  4538.9  340.94  4576.4  341.70  4623.2  340.27  4660.8  342.32
  4692.9  338.89  4703.1  336.44  4708.7  339.04  4723.7  339.53  4744.2  342.91
  4756.5  342.89  4802.8  341.53  4958.8  342.15  4978.8  331.74  4996.8  330.29
  4998.2  329.79  5006.2  330.29  5008.8  337.18  5018.9  340.60  5030.2  341.58
  5073.0  342.72  5188.9  348.27  5348.9  352.67  5398.9  355.58  5534.5  358.01
#Mann=10,-1,0
  4185.2    0.12       0  4324.1     0.1       0  4476.5    0.12       0
  4576.4     0.1       0  4756.5    0.12       0  4802.8     0.1       0
  4996.8    0.07       0  5006.2     0.1       0  5030.2    0.12       0
  5073.0    0.05       0
Bank Sta=4996.8,5006.2
Exp/Cntr=0.3,0.1

Type RM Length L Ch R = 1,12650,823,823,823
BEGIN DESCRIPTION:
Mapping XS c04ec0c4
END DESCRIPTION:
XS GIS Cut Line= 3
      2691042.48      6850535.43      2691220.99      6851361.16
      2691543.72      6851722.52
#Sta/Elev= 30
  4155.2  358.69  4240.2  354.90  4263.2  352.34  4479.6  340.34  4488.3  339.22
  4530.6  340.06  4652.0  338.73  4717.3  339.45  4733.8  338.58  4785.0  340.43
  4795.2  338.97  4815.8  339.52  4846.4  338.47  4948.2  339.18  4989.6  340.53
  5003.3  338.16  5012.7  330.87  5014.1  330.37  5022.2  330.87  5031.7  332.83
  5035.6  335.87  5039.2  338.68  5045.9  338.60  5053.4  341.09  5066.8  340.01
  5102.7  340.70  5166.3  344.10  5208.9  344.64  5371.9  350.22  5484.5  356.28
#Mann=5,-1,0
  4155.2    0.05       0  4479.6     0.1       0  5012.7    0.07       0
  5022.2     0.1       0  5035.6    0.05       0
Bank Sta=5012.7,5022.2
Exp/Cntr=0.3,0.1

Type RM Length L Ch R = 1,11827,679,679,679
BEGIN DESCRIPTION:
CCT3 12.0
END DESCRIPTION:
XS GIS Cut Line= 3
      2690876.00      6850410.99      2690676.00      6851611.00
      2691876.03      6852111.01
#Sta/Elev= 30
  3791.0  360.05  3824.0  357.18  3862.0  357.60  3940.5  351.62  3993.8  345.22
  4085.0  340.22  4348.7  338.24  4571.6  337.08  4614.7  338.57  4652.7  338.30
  4677.5  336.54  4723.7  338.78  4865.6  338.49  4896.0  336.70  4944.1  338.67
  4967.0  337.24  4969.8  330.51  4971.1  330.01  4979.5  330.51  4979.7  331.67
  4997.4  330.76  5005.0  335.66  5010.3  335.66  5022.2  339.16  5091.8  338.02
  5542.2  335.85  5672.2  337.37  5879.1  346.58  6133.7  360.87  6307.6  366.15
#Mann=7,-1,0
  3791.0    0.12       0  4348.7     0.1       0  4677.5    0.12       0
  4944.1     0.1       0  4969.8    0.07       0  4979.5     0.1       0
  5091.8    0.05       0
Bank Sta=4969.8,4979.5
Exp/Cntr=0.3,0.1

Type RM Length L Ch R = 1,11148,856,856,856
BEGIN DESCRIPTION:
Mapping XS c47bed29
END DESCRIPTION:
XS GIS Cut Line= 4
      2690360.89      6850108.42      2690235.89      6851483.38
      2690347.00      6851677.82      2691721.49      6852517.78
#Sta/Elev= 30
  3536.1  360.52  3619.0  357.31  3674.4  352.96  3729.5  348.21  3789.7  346.59
  3809.8  343.96  3870.6  340.55  3981.1  336.03  4181.3  333.73  4281.7  334.18
  4291.8  332.68  4425.6  334.54  4482.6  335.30  4542.8  332.79  4633.8  334.13
  4891.3  336.02  4929.1  333.59  4962.4  335.78  5009.8  336.38  5017.6  333.89
  5020.8  331.28  5022.1  330.78  5030.5  331.28  5047.2  336.66  5198.2  335.21
  5542.4  336.17  5832.2  333.62  6269.5  334.59  6465.0  341.55  6751.5  356.74
#Mann=11,-1,0
  3536.1    0.05       0  3674.4    0.12       0  4425.6     0.1       0
  4482.6    0.12       0  4633.8     0.1       0  4891.3    0.12       0
  4962.4     0.1       0  5020.8    0.07       0  5030.5     0.1       0
  5198.2    0.12       0  5542.4    0.05       0
Bank Sta=5020.8,5030.5
Exp/Cntr=0.3,0.1

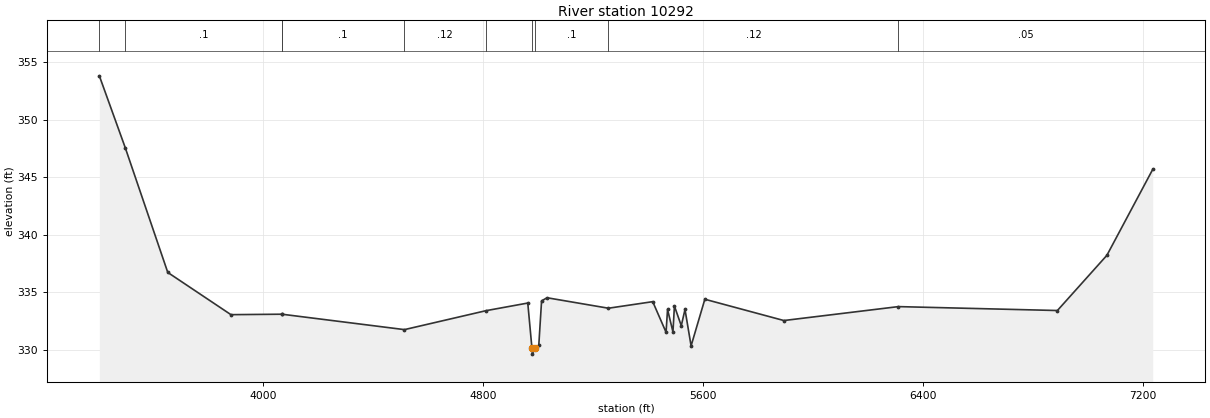
Type RM Length L Ch R = 1,10292,0,0,0
BEGIN DESCRIPTION:
Mapping XS ab308bd2
END DESCRIPTION:
XS GIS Cut Line= 4
      2689777.56      6850136.13      2689518.62      6851548.43
      2689539.27      6851808.65      2691541.18      6852552.72
#Sta/Elev= 30
  3403.8  353.80  3498.1  347.55  3652.8  336.71  3882.6  333.04  4067.9  333.08
  4068.0  333.08  4513.9  331.74  4811.3  333.39  4962.6  334.05  4977.8  330.11
  4979.2  329.61  4987.5  330.11  5002.7  330.39  5012.8  334.24  5032.8  334.51
  5256.0  333.60  5417.2  334.17  5465.7  331.51  5471.1  333.49  5490.8  331.54
  5496.1  333.79  5521.1  332.08  5534.6  333.49  5556.8  330.33  5606.8  334.38
  5894.4  332.53  6311.0  333.74  6889.5  333.40  7069.6  338.20  7236.4  345.67
#Mann=10,-1,0
  3403.8    0.05       0  3498.1     0.1       0  4067.9    0.12       0
  4068.0     0.1       0  4513.9    0.12       0  4811.3     0.1       0
  4977.8    0.07       0  4987.5     0.1       0  5256.0    0.12       0
  6311.0    0.05       0
Bank Sta=4977.8,4987.5
Exp/Cntr=0.3,0.1

Chan Stop Cuts=-1