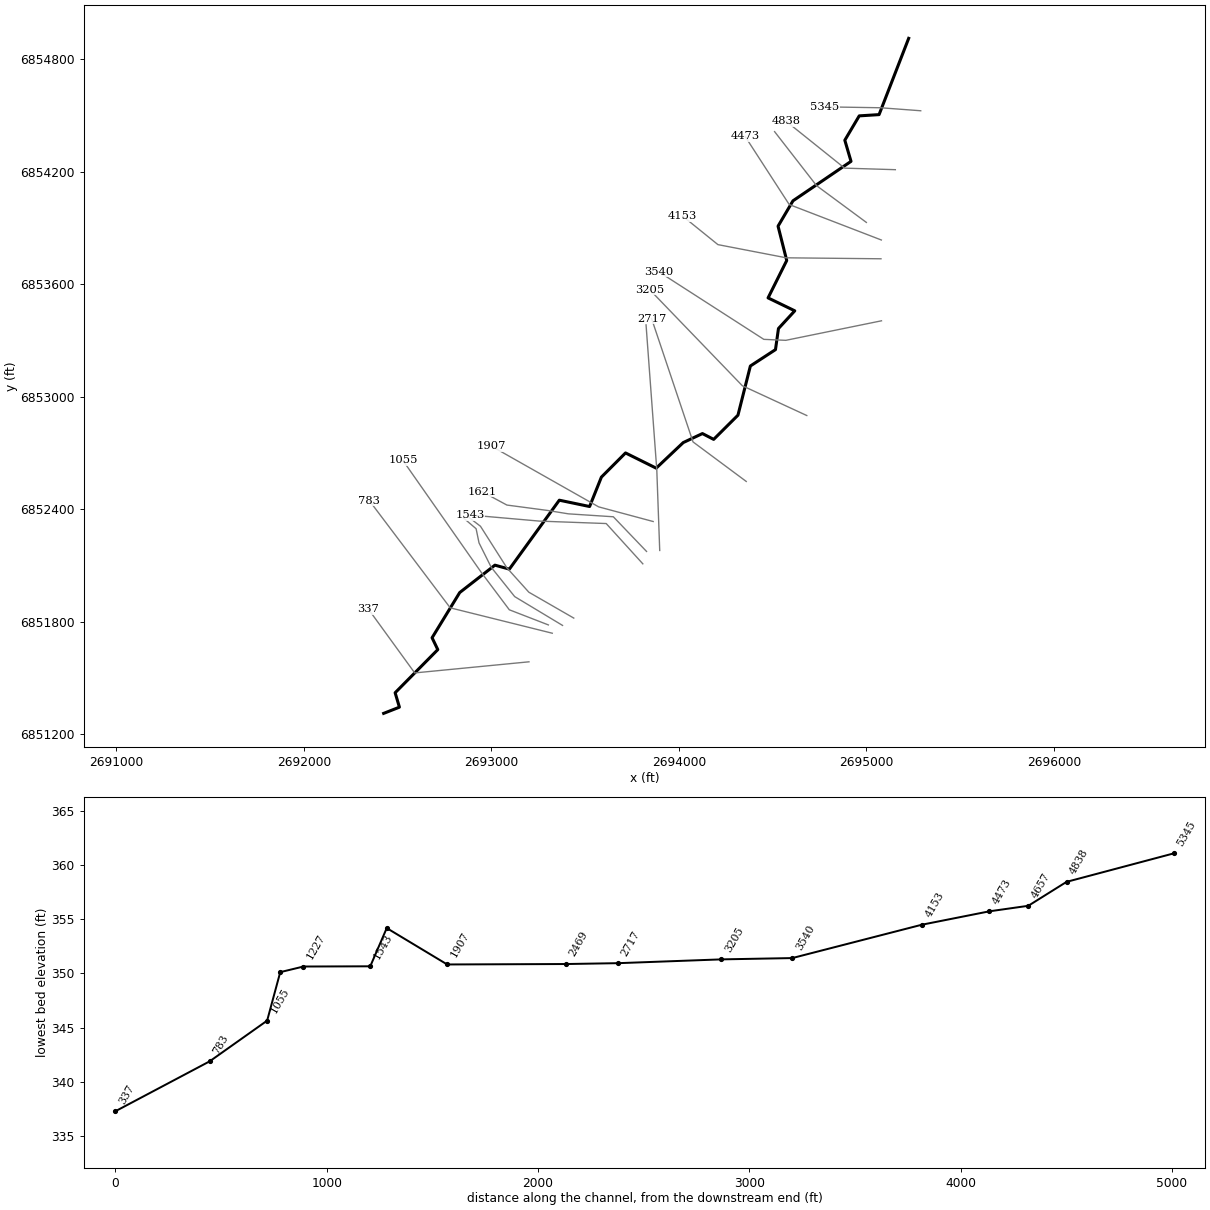
--- CCT3_1.prj (project) ---

Proj Title=CCT3_1 Base Level Engineering
Current Plan=p01
Default Exp/Contr=0.3,0.1
English Units
Geom File=g01
Flow File=f01
Plan File=p01
BEGIN DESCRIPTION:
CCT3_1
END DESCRIPTION:

--- CCT3_1.p01 (plan) ---

Plan Title=Multiple Run
Short Identifier=Multiple
Geom File=g01
Flow File=f01
Subcritical Flow
K Sum by GR= 0
Std Step Tol= 0.01
Critical Tol= 0.01
Num of Std Step Trials= 20
Max Error Tol= 0.3
Flow Tol Ratio= 0.001
Split Flow NTrial= 30
Split Flow Tol= 0.02
Split Flow Ratio= 0.02
Log Output Level= 0
Friction Slope Method= 1
Unsteady Friction Slope Method= 2
Unsteady Bridges Friction Slope Method= 1
Parabolic Critical Depth
Global Vel Dist=  1 , 1 , 1
Global Log Level= 0
CheckData=True
Encroach Param= -1, 0, 0, 0
BEGIN DESCRIPTION:
Multiple Run
END DESCRIPTION:

--- CCT3_1.f01 (steady flow) ---

Flow Title=Multiple
Number of Profiles=7
Profile Names=10-year,25-year,50-year,1pct_min,100-year,1pct_plu,500-year
River Rch & RM= CCT3_1,Reach-1,5345
     295     372     429     245     490     977     638
River Rch & RM= CCT3_1,Reach-1,4473
     344     438     509     294     586    1169     775
River Rch & RM= CCT3_1,Reach-1,1055
     435     567     670     393     783    1563    1071
Boundary for River Rch & Prof#=CCT3_1,Reach-1,1
Up Type=0
Dn Type=3
Dn Slope=0.005
Boundary for River Rch & Prof#=CCT3_1,Reach-1,2
Up Type=0
Dn Type=3
Dn Slope=0.005
Boundary for River Rch & Prof#=CCT3_1,Reach-1,3
Up Type=0
Dn Type=3
Dn Slope=0.005
Boundary for River Rch & Prof#=CCT3_1,Reach-1,4
Up Type=0
Dn Type=3
Dn Slope=0.005
Boundary for River Rch & Prof#=CCT3_1,Reach-1,5
Up Type=0
Dn Type=3
Dn Slope=0.005
Boundary for River Rch & Prof#=CCT3_1,Reach-1,6
Up Type=0
Dn Type=3
Dn Slope=0.005
Boundary for River Rch & Prof#=CCT3_1,Reach-1,7
Up Type=0
Dn Type=3
Dn Slope=0.005

--- CCT3_1.g01 (geometry) ---

Geom Title=Existing Conditions

River Reach=CCT3_1,Reach-1
Reach XY= 30
      2695226.00      6854911.00      2695068.14      6854504.20
      2694962.32      6854497.49      2694885.43      6854367.62
      2694918.51      6854254.93      2694608.95      6854044.51
      2694529.34      6853909.28      2694575.63      6853726.27
      2694476.12      6853526.76      2694618.48      6853457.88
      2694531.56      6853363.42      2694515.61      6853250.90
      2694381.73      6853163.55      2694315.52      6852901.20
      2694186.00      6852772.24      2694126.09      6852803.22
      2694023.71      6852755.19      2693879.41      6852618.77
      2693715.94      6852699.92      2693587.24      6852571.00
      2693524.39      6852414.13      2693362.78      6852447.88
      2693096.39      6852080.21      2693019.41      6852101.43
      2692831.65      6851955.37      2692684.25      6851714.23
      2692714.76      6851651.00      2692487.23      6851421.00
      2692510.06      6851344.03      2692426.00      6851311.00

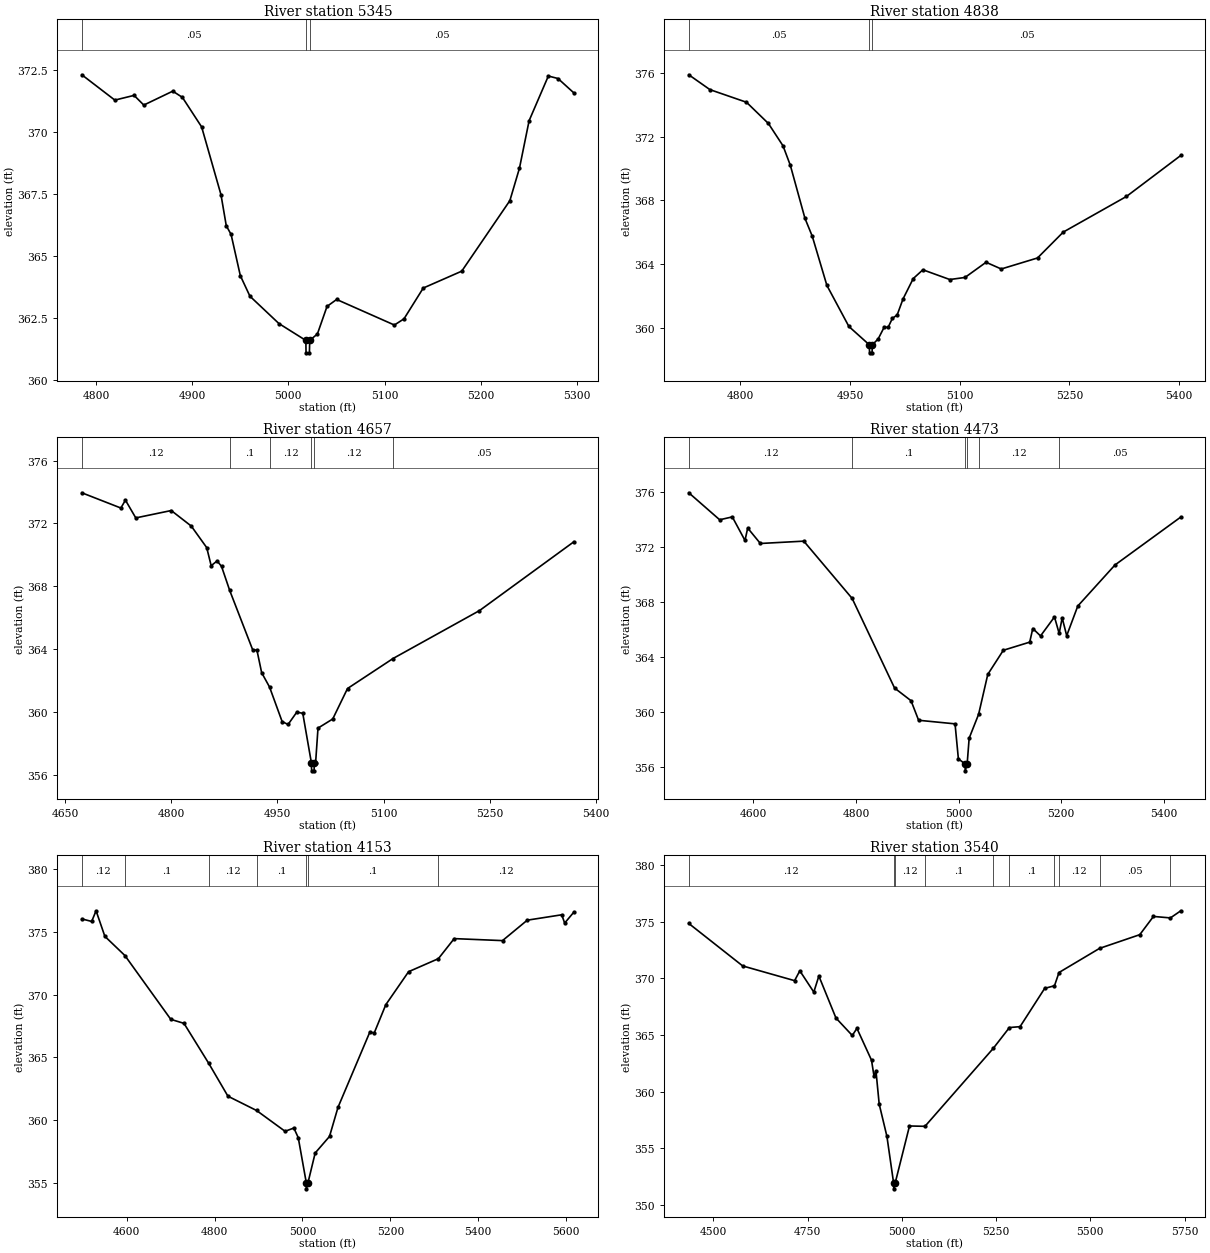
Type RM Length L Ch R = 1,5345,507,507,507
BEGIN DESCRIPTION:
CCT3_1 12.0
END DESCRIPTION:
XS GIS Cut Line= 3
      2695290.20      6854524.77      2695076.19      6854540.77
      2694779.53      6854545.58
#Sta/Elev= 30
  4785.4  372.29  4819.7  371.27  4839.7  371.46  4849.8  371.07  4879.9  371.63
  4889.9  371.38  4909.9  370.19  4930.0  367.46  4935.5  366.21  4940.5  365.86
  4950.1  364.20  4960.1  363.37  4990.2  362.27  5018.2  361.59  5018.4  361.09
  5021.9  361.09  5022.2  361.59  5030.2  361.85  5040.2  362.96  5050.2  363.24
  5110.2  362.21  5120.2  362.46  5140.2  363.70  5180.2  364.38  5230.2  367.22
  5240.2  368.53  5250.2  370.44  5270.2  372.24  5280.2  372.14  5296.7  371.56
#Mann=3,-1,0
  4785.4    0.05       0  5018.2    0.04       0  5022.2    0.05       0
Bank Sta=5018.2,5022.2
Exp/Cntr=0.3,0.1

Type RM Length L Ch R = 1,4838,181,181,181
BEGIN DESCRIPTION:
CCT3_1 11.0
END DESCRIPTION:
XS GIS Cut Line= 3
      2695154.85      6854210.53      2694884.48      6854218.72
      2694570.40      6854470.43
#Sta/Elev= 30
  4729.5  375.87  4758.4  374.94  4808.4  374.15  4838.4  372.82  4858.4  371.42
  4868.4  370.20  4888.4  366.88  4898.4  365.76  4918.4  362.68  4948.5  360.11
  4976.5  358.96  4976.7  358.46  4980.2  358.46  4980.5  358.96  4988.5  359.33
  4996.7  360.06  5002.2  360.06  5008.0  360.62  5014.5  360.83  5022.5  361.83
  5036.5  363.11  5049.7  363.66  5086.5  363.05  5107.3  363.18  5136.1  364.13
  5156.9  363.71  5206.5  364.40  5241.7  366.02  5328.1  368.25  5402.5  370.82
#Mann=3,-1,0
  4729.5    0.05       0  4976.5    0.04       0  4980.5    0.05       0
Bank Sta=4976.5,4980.5
Exp/Cntr=0.3,0.1

Type RM Length L Ch R = 1,4657,184,184,184
BEGIN DESCRIPTION:
Mapping XS 95802370
END DESCRIPTION:
XS GIS Cut Line= 3
      2695000.33      6853929.26      2694734.68      6854125.46
      2694510.87      6854413.47
#Sta/Elev= 30
  4673.7  373.95  4728.8  372.98  4735.3  373.48  4749.9  372.35  4800.0  372.82
  4828.3  371.83  4850.1  370.46  4856.4  369.31  4864.8  369.61  4871.0  369.27
  4882.6  367.73  4914.9  363.97  4921.1  363.92  4927.7  362.50  4938.9  361.58
  4956.6  359.39  4965.0  359.20  4977.4  359.99  4985.8  359.91  4998.0  356.75
  4998.3  356.25  5001.8  356.25  5002.0  356.75  5003.9  356.75  5007.3  358.97
  5028.1  359.55  5049.0  361.49  5113.3  363.40  5235.4  366.45  5368.7  370.83
#Mann=6,-1,0
  4673.7    0.12       0  4882.6     0.1       0  4938.9    0.12       0
  4998.0    0.07       0  5002.0    0.12       0  5113.3    0.05       0
Bank Sta=4998,5002
Exp/Cntr=0.3,0.1

Type RM Length L Ch R = 1,4473,320,320,320
BEGIN DESCRIPTION:
Mapping XS 11537b56
END DESCRIPTION:
XS GIS Cut Line= 3
      2695080.20      6853835.52      2694588.85      6854024.77
      2694353.83      6854387.67
#Sta/Elev= 30
  4474.1  375.92  4534.3  373.96  4558.9  374.17  4583.6  372.46  4588.9  373.36
  4613.6  372.24  4698.2  372.41  4792.5  368.25  4875.1  361.75  4907.2  360.83
  4922.0  359.41  4993.0  359.15  4999.5  356.61  5012.6  356.24  5012.8  355.74
  5016.6  356.24  5020.5  358.11  5038.9  359.84  5056.8  362.74  5087.1  364.49
  5138.5  365.08  5144.5  366.07  5159.6  365.53  5186.8  366.91  5195.9  365.71
  5201.8  366.84  5210.6  365.55  5232.2  367.70  5304.7  370.68  5433.0  374.16
#Mann=6,-1,0
  4474.1    0.12       0  4792.5     0.1       0  5012.6    0.07       0
  5016.6     0.1       0  5038.9    0.12       0  5195.9    0.05       0
Bank Sta=5012.6,5016.6
Exp/Cntr=0.3,0.1

Type RM Length L Ch R = 1,4153,613,613,613
BEGIN DESCRIPTION:
Mapping XS a7b252f6
END DESCRIPTION:
XS GIS Cut Line= 4
      2695078.42      6853735.36      2694573.22      6853740.56
      2694208.64      6853810.88      2694019.75      6853963.54
#Sta/Elev= 30
  4498.1  376.03  4520.5  375.83  4530.5  376.68  4550.5  374.64  4596.1  373.11
  4700.5  368.02  4730.5  367.70  4787.0  364.50  4830.5  361.89  4895.6  360.75
  4960.5  359.09  4980.5  359.35  4990.5  358.58  5008.7  355.00  5008.9  354.50
  5012.7  355.00  5029.0  357.36  5061.6  358.68  5080.9  361.00  5153.3  367.00
  5163.4  366.94  5189.7  369.19  5241.5  371.82  5309.3  372.86  5345.3  374.46
  5455.2  374.30  5511.5  375.93  5589.9  376.36  5596.6  375.70  5617.5  376.57
#Mann=7,-1,0
  4498.1    0.12       0  4596.1     0.1       0  4787.0    0.12       0
  4895.6     0.1       0  5008.7    0.07       0  5012.7     0.1       0
  5309.3    0.12       0
Bank Sta=5008.7,5012.7
Exp/Cntr=0.3,0.1

Type RM Length L Ch R = 1,3540,335,335,335
BEGIN DESCRIPTION:
Mapping XS 5a8932af
END DESCRIPTION:
XS GIS Cut Line= 4
      2695080.99      6853404.62      2694570.62      6853300.46
      2694453.43      6853305.67      2693892.28      6853666.78
#Sta/Elev= 30
  4434.6  374.85  4577.6  371.10  4715.3  369.80  4729.2  370.67  4766.3  368.79
  4779.7  370.21  4825.1  366.50  4868.4  364.96  4880.7  365.59  4919.4  362.78
  4926.1  361.36  4931.2  361.84  4939.8  358.90  4960.3  356.05  4978.1  351.92
  4978.4  351.42  4982.1  351.92  5020.2  356.97  5061.3  356.94  5242.4  363.82
  5285.3  365.66  5313.6  365.74  5378.9  369.12  5404.9  369.35  5416.9  370.52
  5524.5  372.65  5631.2  373.86  5667.5  375.47  5712.5  375.34  5740.1  375.97
#Mann=10,-1,0
  4434.6    0.12       0  4978.1    0.07       0  4982.1    0.12       0
  5061.3     0.1       0  5242.4    0.12       0  5285.3     0.1       0
  5404.9    0.05       0  5416.9    0.12       0  5524.5    0.05       0
  5712.5    0.12       0
Bank Sta=4978.1,4982.1
Exp/Cntr=0.3,0.1

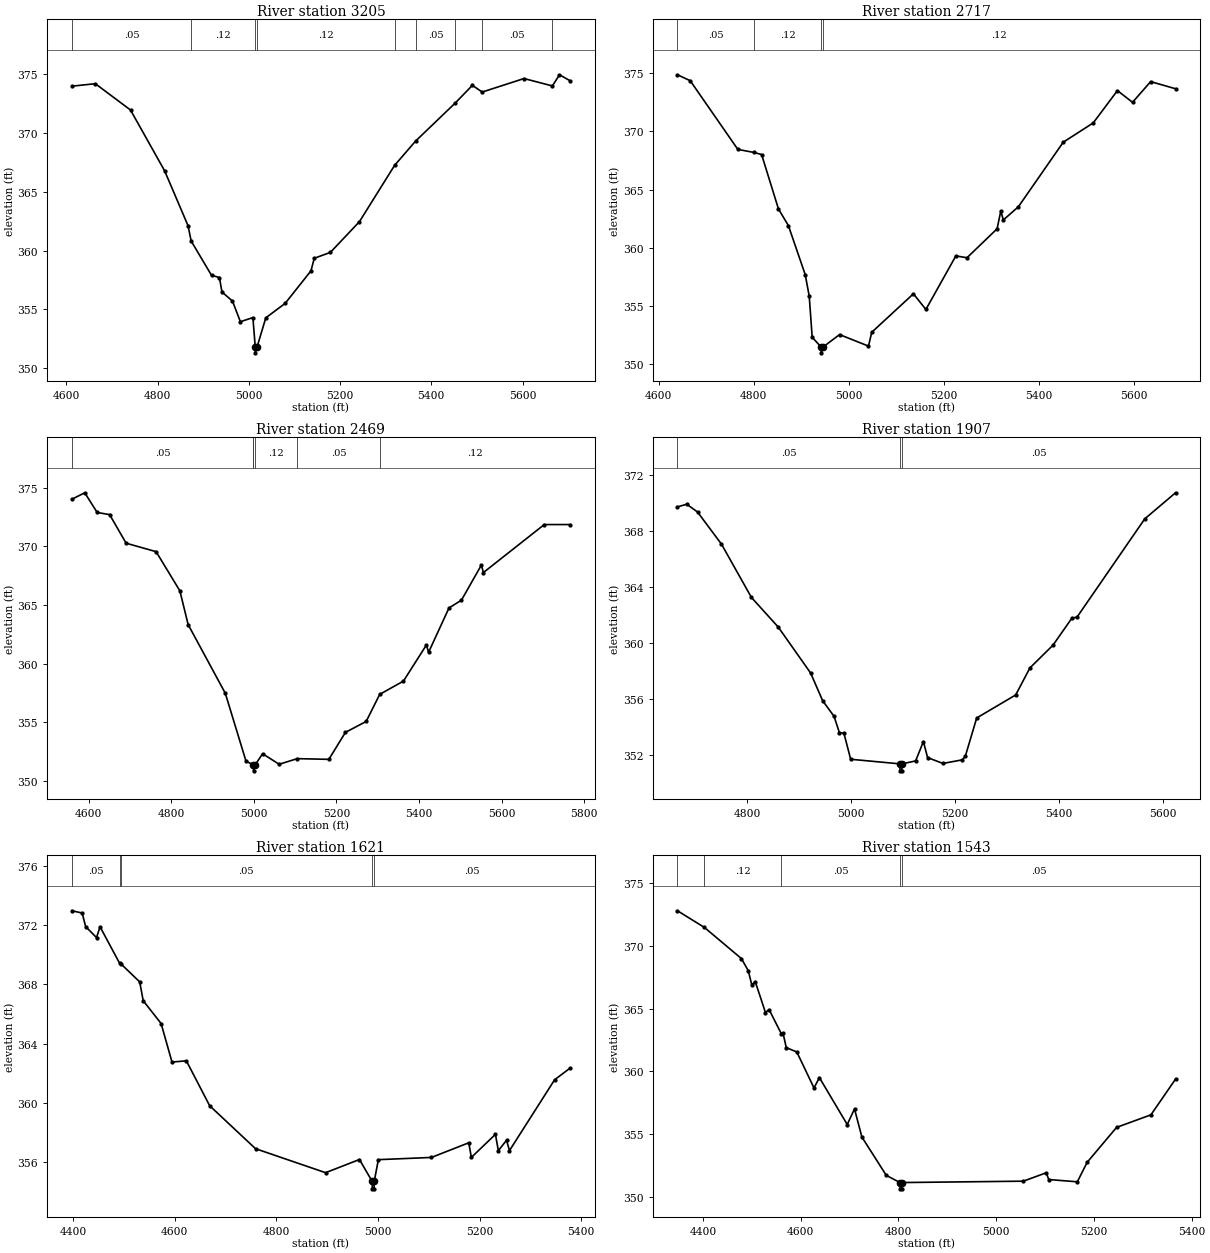
Type RM Length L Ch R = 1,3205,488,488,488
BEGIN DESCRIPTION:
Mapping XS 19b759f8
END DESCRIPTION:
XS GIS Cut Line= 3
      2694682.62      6852899.41      2694338.85      6853058.27
      2693844.03      6853571.33
#Sta/Elev= 30
  4612.3  374.00  4663.7  374.21  4740.8  371.97  4815.6  366.79  4866.9  362.12
  4873.7  360.82  4918.3  357.90  4935.7  357.71  4941.2  356.48  4964.2  355.71
  4981.6  353.95  5009.0  354.30  5014.2  351.80  5014.4  351.30  5018.2  351.80
  5037.3  354.28  5079.7  355.51  5136.3  358.28  5143.5  359.35  5178.8  359.85
  5242.6  362.47  5319.6  367.26  5365.4  369.32  5452.6  372.57  5490.0  374.07
  5511.6  373.50  5603.2  374.65  5665.4  374.02  5680.9  374.97  5703.8  374.47
#Mann=9,-1,0
  4612.3    0.05       0  4873.7    0.12       0  5014.2    0.07       0
  5018.2    0.12       0  5319.6     0.1       0  5365.4    0.05       0
  5452.6    0.12       0  5511.6    0.05       0  5665.4    0.12       0
Bank Sta=5014.2,5018.2
Exp/Cntr=0.3,0.1

Type RM Length L Ch R = 1,2717,248,248,248
BEGIN DESCRIPTION:
Mapping XS 475ab7d7
END DESCRIPTION:
XS GIS Cut Line= 3
      2694359.67      6852547.87      2694075.83      6852758.79
      2693854.75      6853416.82
#Sta/Elev= 30
  4639.6  374.87  4666.4  374.36  4766.6  368.45  4800.3  368.19  4816.6  368.01
  4852.1  363.32  4872.9  361.90  4908.4  357.67  4916.8  355.82  4923.0  352.29
  4941.8  351.45  4942.1  350.95  4945.8  351.45  4980.6  352.52  5041.4  351.53
  5048.3  352.72  5136.0  356.03  5162.2  354.68  5225.3  359.29  5248.7  359.13
  5312.0  361.62  5319.9  363.16  5325.1  362.38  5356.7  363.51  5451.2  369.07
  5514.3  370.73  5565.2  373.51  5596.9  372.50  5635.1  374.28  5687.4  373.67
#Mann=4,-1,0
  4639.6    0.05       0  4800.3    0.12       0  4941.8    0.07       0
  4945.8    0.12       0
Bank Sta=4941.8,4945.8
Exp/Cntr=0.3,0.1

Type RM Length L Ch R = 1,2469,562,562,562
BEGIN DESCRIPTION:
Mapping XS 8b857f67
END DESCRIPTION:
XS GIS Cut Line= 3
      2693898.31      6852179.80      2693882.69      6852609.49
      2693825.40      6853382.89
#Sta/Elev= 30
  4559.7  374.03  4590.9  374.58  4620.9  372.90  4651.0  372.72  4691.0  370.28
  4763.5  369.56  4821.1  366.22  4841.1  363.34  4931.1  357.48  4981.2  351.69
  4998.2  351.40  4999.2  351.37  4999.5  350.87  5003.2  351.37  5021.3  352.33
  5061.4  351.43  5105.3  351.91  5181.7  351.85  5221.8  354.15  5272.0  355.08
  5304.8  357.39  5362.2  358.52  5418.0  361.61  5423.0  360.97  5472.5  364.76
  5502.6  365.42  5550.8  368.41  5555.9  367.78  5703.1  371.87  5765.2  371.87
#Mann=6,-1,0
  4559.7    0.05       0  4998.2    0.12       0  4999.2    0.07       0
  5003.2    0.12       0  5105.3    0.05       0  5304.8    0.12       0
Bank Sta=4999.2,5003.2
Exp/Cntr=0.3,0.1

Type RM Length L Ch R = 1,1907,286,286,286
BEGIN DESCRIPTION:
Mapping XS 28a2dd98
END DESCRIPTION:
XS GIS Cut Line= 3
      2693863.30      6852334.23      2693572.51      6852412.35
      2693000.99      6852736.00
#Sta/Elev= 30
  4666.2  369.75  4684.1  369.94  4704.8  369.38  4750.8  367.08  4808.4  363.26
  4860.1  361.13  4922.3  357.84  4945.5  355.85  4967.3  354.74  4977.6  353.57
  4986.3  353.53  4999.3  351.66  5094.0  351.33  5094.2  350.83  5097.7  350.83
  5098.0  351.33  5124.2  351.54  5139.2  352.93  5147.2  351.78  5176.8  351.36
  5214.3  351.62  5220.0  351.90  5241.7  354.62  5316.7  356.27  5344.1  358.21
  5388.5  359.84  5424.9  361.78  5434.5  361.84  5564.9  368.89  5624.1  370.76
#Mann=3,-1,0
  4666.2    0.05       0  5094.0    0.04       0  5098.0    0.05       0
Bank Sta=5094,5098
Exp/Cntr=0.3,0.1

Type RM Length L Ch R = 1,1621,78,78,78
BEGIN DESCRIPTION:
Mapping XS 8a8c03bb
END DESCRIPTION:
XS GIS Cut Line= 6
      2693828.00      6852174.59      2693650.91      6852359.49
      2693411.33      6852375.11      2693299.35      6852393.34
      2693083.21      6852421.99      2692949.37      6852494.05
#Sta/Elev= 30
  4398.1  372.96  4418.3  372.81  4425.2  371.89  4446.6  371.15  4453.5  371.88
  4492.1  369.41  4493.8  369.40  4531.5  368.16  4538.4  366.89  4573.6  365.35
  4595.0  362.75  4623.3  362.83  4669.1  359.80  4759.3  356.90  4897.1  355.28
  4963.7  356.17  4988.8  354.69  4989.0  354.19  4992.5  354.19  4992.8  354.69
  5000.9  356.16  5105.4  356.31  5178.8  357.30  5183.8  356.31  5231.2  357.87
  5236.9  356.77  5253.1  357.47  5258.8  356.77  5347.5  361.55  5377.7  362.33
#Mann=5,-1,0
  4398.1    0.05       0  4492.1    0.12       0  4493.8    0.05       0
  4988.8    0.03       0  4992.8    0.05       0
Bank Sta=4988.8,4992.8
Exp/Cntr=0.3,0.1

Type RM Length L Ch R = 1,1543,316,316,316
BEGIN DESCRIPTION:
Mapping XS 52915bec
END DESCRIPTION:
XS GIS Cut Line= 4
      2693808.19      6852108.53      2693612.87      6852323.38
      2693256.97      6852336.40      2692885.89      6852368.95
#Sta/Elev= 30
  4347.9  372.79  4403.1  371.46  4478.6  368.99  4492.8  368.02  4499.9  366.89
  4507.0  367.16  4527.9  364.69  4535.3  364.93  4560.4  363.00  4563.7  363.08
  4570.5  361.90  4592.1  361.55  4627.2  358.69  4638.3  359.51  4695.2  355.78
  4710.1  357.02  4725.2  354.78  4775.2  351.73  4803.2  351.16  4803.5  350.66
  4807.0  350.66  4807.2  351.16  5055.6  351.27  5102.5  351.94  5107.5  351.40
  5166.0  351.22  5186.1  352.77  5246.3  355.55  5316.6  356.55  5366.9  359.39
#Mann=5,-1,0
  4347.9    0.05       0  4403.1    0.12       0  4560.4    0.05       0
  4803.2    0.03       0  4807.2    0.05       0
Bank Sta=4803.2,4807.2
Exp/Cntr=0.3,0.1

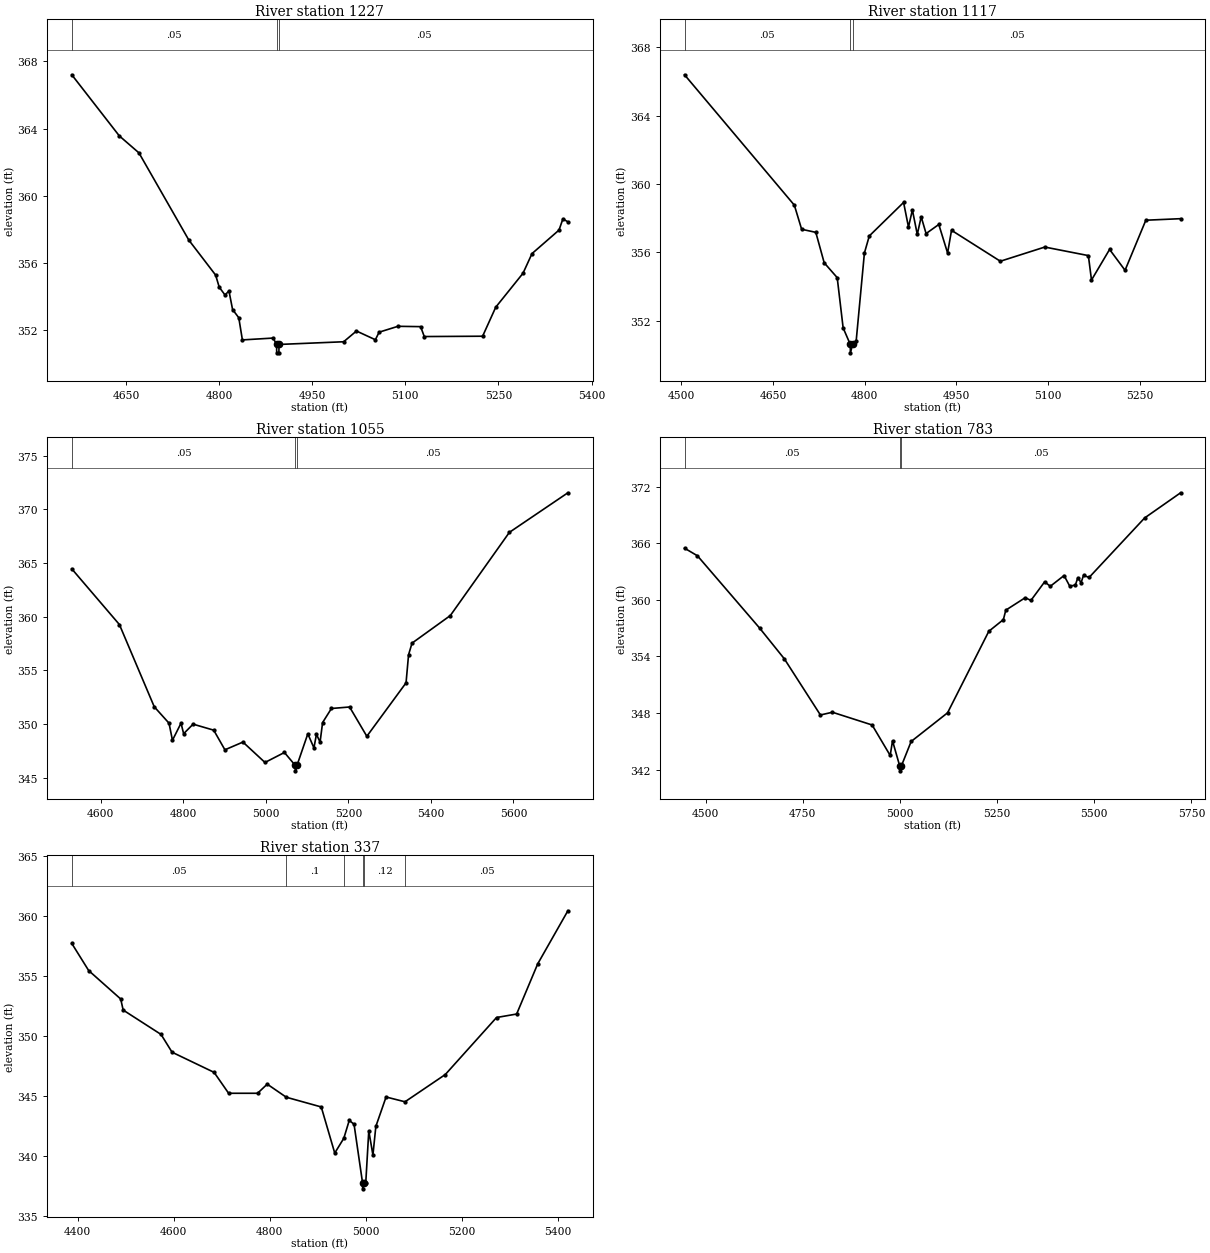
Type RM Length L Ch R = 1,1227,110,110,110
BEGIN DESCRIPTION:
Mapping XS 6af33aeb
END DESCRIPTION:
XS GIS Cut Line= 5
      2693439.88      6851819.17      2693200.29      6851957.20
      2693083.10      6852087.41      2692942.47      6852308.76
      2692874.73      6852360.87
#Sta/Elev= 30
  4562.5  367.20  4639.1  363.56  4670.7  362.55  4751.2  357.35  4794.3  355.27
  4800.1  354.55  4809.3  354.09  4815.8  354.32  4821.6  353.22  4831.6  352.73
  4837.4  351.41  4887.0  351.52  4892.5  351.14  4892.7  350.64  4896.2  350.64
  4896.5  351.14  5000.6  351.30  5021.2  351.94  5051.7  351.42  5057.7  351.87
  5088.1  352.22  5124.6  352.20  5130.5  351.61  5224.5  351.63  5245.7  353.36
  5289.6  355.38  5304.1  356.55  5347.6  357.95  5353.9  358.62  5361.9  358.44
#Mann=3,-1,0
  4562.5    0.05       0  4892.5    0.04       0  4896.5    0.05       0
Bank Sta=4892.5,4896.5
Exp/Cntr=0.3,0.1

Type RM Length L Ch R = 1,1117,62,62,62
BEGIN DESCRIPTION:
Mapping XS 6a0c977f
END DESCRIPTION:
XS GIS Cut Line= 6
      2693379.99      6851780.11      2693124.76      6851933.76
      2692999.76      6852090.01      2692934.66      6852220.22
      2692919.04      6852295.74      2692849.84      6852354.69
#Sta/Elev= 30
  4505.4  366.39  4685.1  358.76  4697.0  357.35  4720.2  357.17  4733.9  355.39
  4755.2  354.52  4764.9  351.58  4776.5  350.62  4776.8  350.12  4780.5  350.62
  4786.3  350.84  4799.7  355.96  4807.7  356.96  4863.8  358.92  4871.8  357.48
  4878.2  358.48  4886.2  357.05  4892.6  358.08  4900.6  357.10  4921.4  357.63
  4935.8  355.96  4942.2  357.29  5022.1  355.48  5094.8  356.31  5166.1  355.81
  5171.2  354.38  5200.8  356.17  5226.1  354.95  5260.1  357.88  5317.0  357.97
#Mann=3,-1,0
  4505.4    0.05       0  4776.5    0.04       0  4780.5    0.05       0
Bank Sta=4776.5,4780.5
Exp/Cntr=0.3,0.1

Type RM Length L Ch R = 1,1055,272,272,272
BEGIN DESCRIPTION:
Mapping XS c5ecc3e0
END DESCRIPTION:
XS GIS Cut Line= 4
      2693304.47      6851782.72      2693096.12      6851863.45
      2692947.68      6852061.37      2692528.39      6852660.36
#Sta/Elev= 30
  4529.8  364.46  4645.2  359.27  4729.6  351.61  4765.4  350.08  4773.7  348.49
  4794.5  350.08  4800.8  349.10  4823.7  349.99  4873.7  349.43  4900.8  347.60
  4944.5  348.32  4997.9  346.42  5045.0  347.35  5071.4  346.14  5071.7  345.64
  5075.4  346.14  5101.7  349.09  5116.5  347.78  5122.6  349.04  5131.4  348.32
  5137.5  350.14  5158.9  351.45  5202.9  351.59  5244.7  348.86  5339.7  353.84
  5345.8  356.46  5354.2  357.54  5447.0  360.11  5590.0  367.86  5731.8  371.55
#Mann=3,-1,0
  4529.8    0.05       0  5071.4    0.04       0  5075.4    0.05       0
Bank Sta=5071.4,5075.4
Exp/Cntr=0.3,0.1

Type RM Length L Ch R = 1,783,446,446,446
BEGIN DESCRIPTION:
Mapping XS 358ab9a0
END DESCRIPTION:
XS GIS Cut Line= 3
      2693325.25      6851738.46      2692781.01      6851873.87
      2692350.13      6852444.92
#Sta/Elev= 30
  4445.8  365.48  4479.1  364.67  4639.2  357.00  4702.6  353.75  4795.4  347.80
  4826.3  348.09  4928.4  346.74  4974.9  343.51  4980.9  345.06  4999.5  342.38
  4999.7  341.88  5003.5  342.38  5028.8  344.99  5122.5  348.03  5228.6  356.67
  5266.1  357.91  5272.3  358.91  5322.3  360.23  5336.9  359.94  5372.2  361.91
  5386.8  361.44  5422.2  362.58  5436.8  361.45  5451.3  361.57  5457.6  362.35
  5465.9  361.82  5472.2  362.59  5486.7  362.38  5629.4  368.68  5722.0  371.35
#Mann=3,-1,0
  4445.8    0.05       0  4999.5    0.04       0  5003.5    0.05       0
Bank Sta=4999.5,5003.5
Exp/Cntr=0.3,0.1

Type RM Length L Ch R = 1,337,0,0,0
BEGIN DESCRIPTION:
CCT3_1 1.0
END DESCRIPTION:
XS GIS Cut Line= 3
      2693201.05      6851586.00      2692591.73      6851526.73
      2692344.47      6851867.35
#Sta/Elev= 30
  4387.8  357.71  4423.0  355.45  4489.7  353.08  4494.8  352.16  4573.7  350.13
  4596.6  348.65  4684.2  346.97  4714.4  345.23  4774.7  345.23  4794.8  345.99
  4834.5  344.90  4907.3  344.09  4935.4  340.25  4954.3  341.48  4965.6  342.97
  4975.6  342.65  4993.3  337.77  4993.6  337.27  4997.3  337.77  5000.0  337.77
  5006.3  342.11  5014.9  340.08  5021.0  342.47  5042.3  344.92  5081.7  344.52
  5165.6  346.79  5272.3  351.54  5314.2  351.83  5358.1  356.01  5420.9  360.43
#Mann=6,-1,0
  4387.8    0.05       0  4834.5     0.1       0  4954.3    0.12       0
  4993.3    0.07       0  4997.3    0.12       0  5081.7    0.05       0
Bank Sta=4993.3,4997.3
Exp/Cntr=0.3,0.1

Chan Stop Cuts=-1