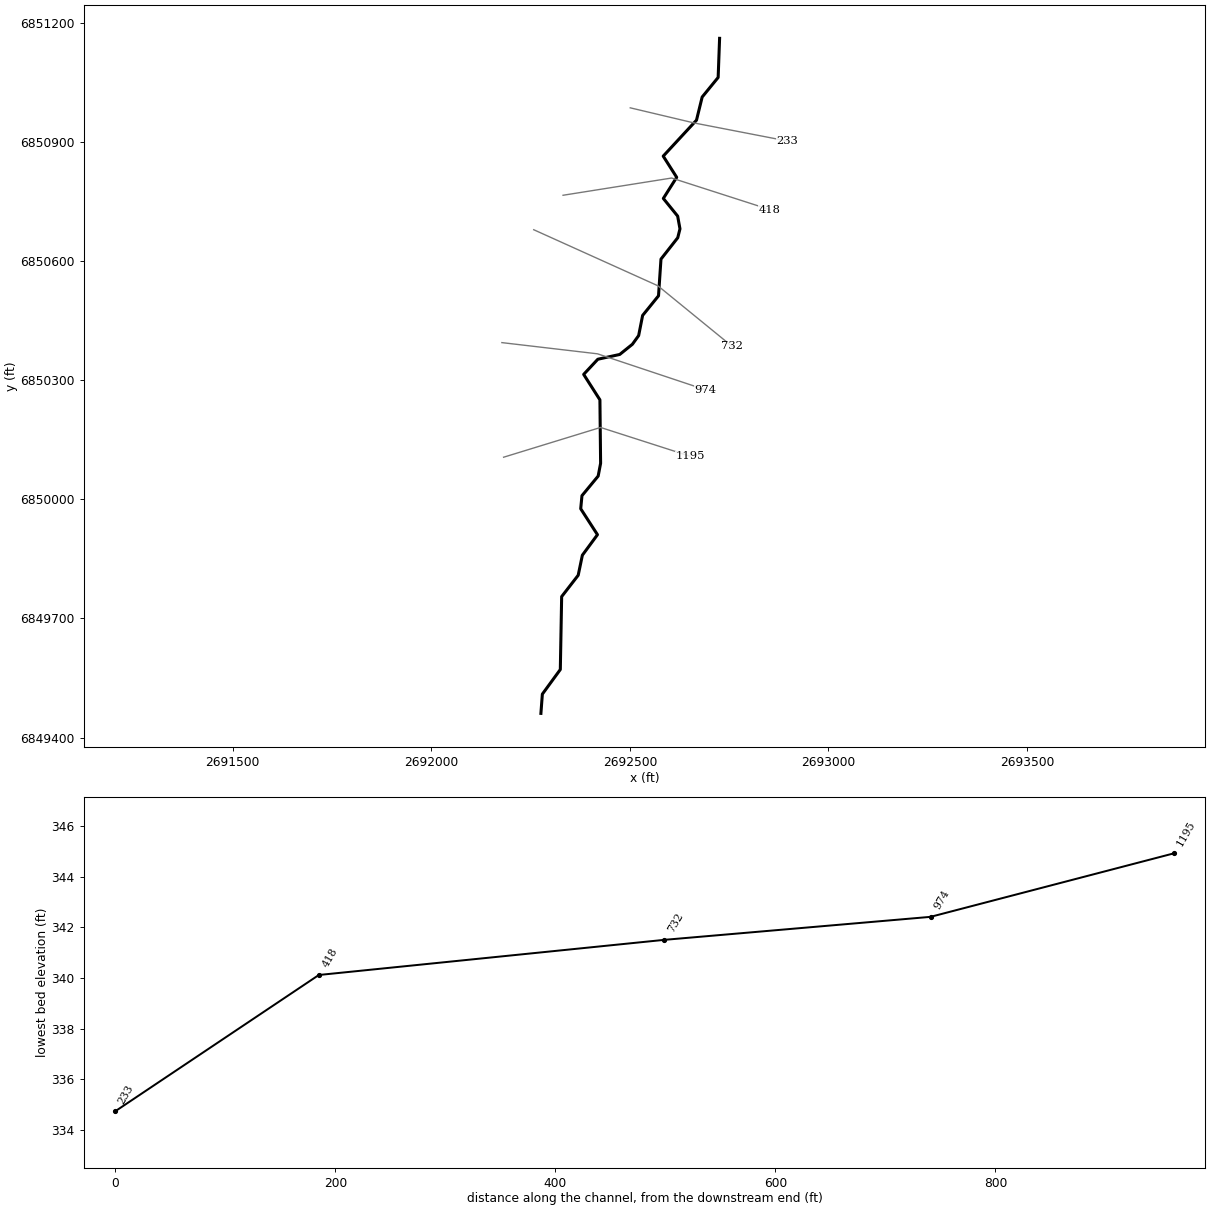
--- CCT3_2.prj (project) ---

Proj Title=CCT3_2 Base Level Engineering
Current Plan=p01
Default Exp/Contr=0.3,0.1
English Units
Geom File=g01
Flow File=f01
Plan File=p01
BEGIN DESCRIPTION:
CCT3_2
END DESCRIPTION:

--- CCT3_2.p01 (plan) ---

Plan Title=Multiple Run
Short Identifier=Multiple
Geom File=g01
Flow File=f01
Subcritical Flow
K Sum by GR= 0
Std Step Tol= 0.01
Critical Tol= 0.01
Num of Std Step Trials= 20
Max Error Tol= 0.3
Flow Tol Ratio= 0.001
Split Flow NTrial= 30
Split Flow Tol= 0.02
Split Flow Ratio= 0.02
Log Output Level= 0
Friction Slope Method= 1
Unsteady Friction Slope Method= 2
Unsteady Bridges Friction Slope Method= 1
Parabolic Critical Depth
Global Vel Dist=  1 , 1 , 1
Global Log Level= 0
CheckData=True
Encroach Param= -1, 0, 0, 0
BEGIN DESCRIPTION:
Multiple Run
END DESCRIPTION:

--- CCT3_2.f01 (steady flow) ---

Flow Title=Multiple
Number of Profiles=7
Profile Names=10-year,25-year,50-year,1pct_min,100-year,1pct_plu,500-year
River Rch & RM= CCT3_2,Reach-1,1195
     206     256     294     168     335     669     434
Boundary for River Rch & Prof#=CCT3_2,Reach-1,1
Up Type=0
Dn Type=3
Dn Slope=0.005
Boundary for River Rch & Prof#=CCT3_2,Reach-1,2
Up Type=0
Dn Type=3
Dn Slope=0.005
Boundary for River Rch & Prof#=CCT3_2,Reach-1,3
Up Type=0
Dn Type=3
Dn Slope=0.005
Boundary for River Rch & Prof#=CCT3_2,Reach-1,4
Up Type=0
Dn Type=3
Dn Slope=0.005
Boundary for River Rch & Prof#=CCT3_2,Reach-1,5
Up Type=0
Dn Type=3
Dn Slope=0.005
Boundary for River Rch & Prof#=CCT3_2,Reach-1,6
Up Type=0
Dn Type=3
Dn Slope=0.005
Boundary for River Rch & Prof#=CCT3_2,Reach-1,7
Up Type=0
Dn Type=3
Dn Slope=0.005

--- CCT3_2.g01 (geometry) ---

Geom Title=Existing Conditions

River Reach=CCT3_2,Reach-1
Reach XY= 30
      2692276.00      6849461.00      2692279.65      6849509.49
      2692324.88      6849571.46      2692328.24      6849755.07
      2692369.91      6849808.83      2692380.42      6849859.36
      2692418.44      6849911.00      2692376.23      6849976.34
      2692379.40      6850009.25      2692420.22      6850058.65
      2692426.35      6850090.85      2692424.61      6850250.57
      2692383.69      6850314.67      2692419.33      6850352.84
      2692474.51      6850364.89      2692506.37      6850390.53
      2692522.14      6850412.42      2692532.15      6850463.15
      2692572.18      6850512.58      2692578.38      6850605.03
      2692620.60      6850658.83      2692626.21      6850681.21
      2692620.37      6850713.30      2692584.31      6850757.77
      2692617.96      6850811.00      2692584.00      6850864.33
      2692667.83      6850954.94      2692682.11      6851013.18
      2692722.37      6851062.50      2692726.00      6851161.00

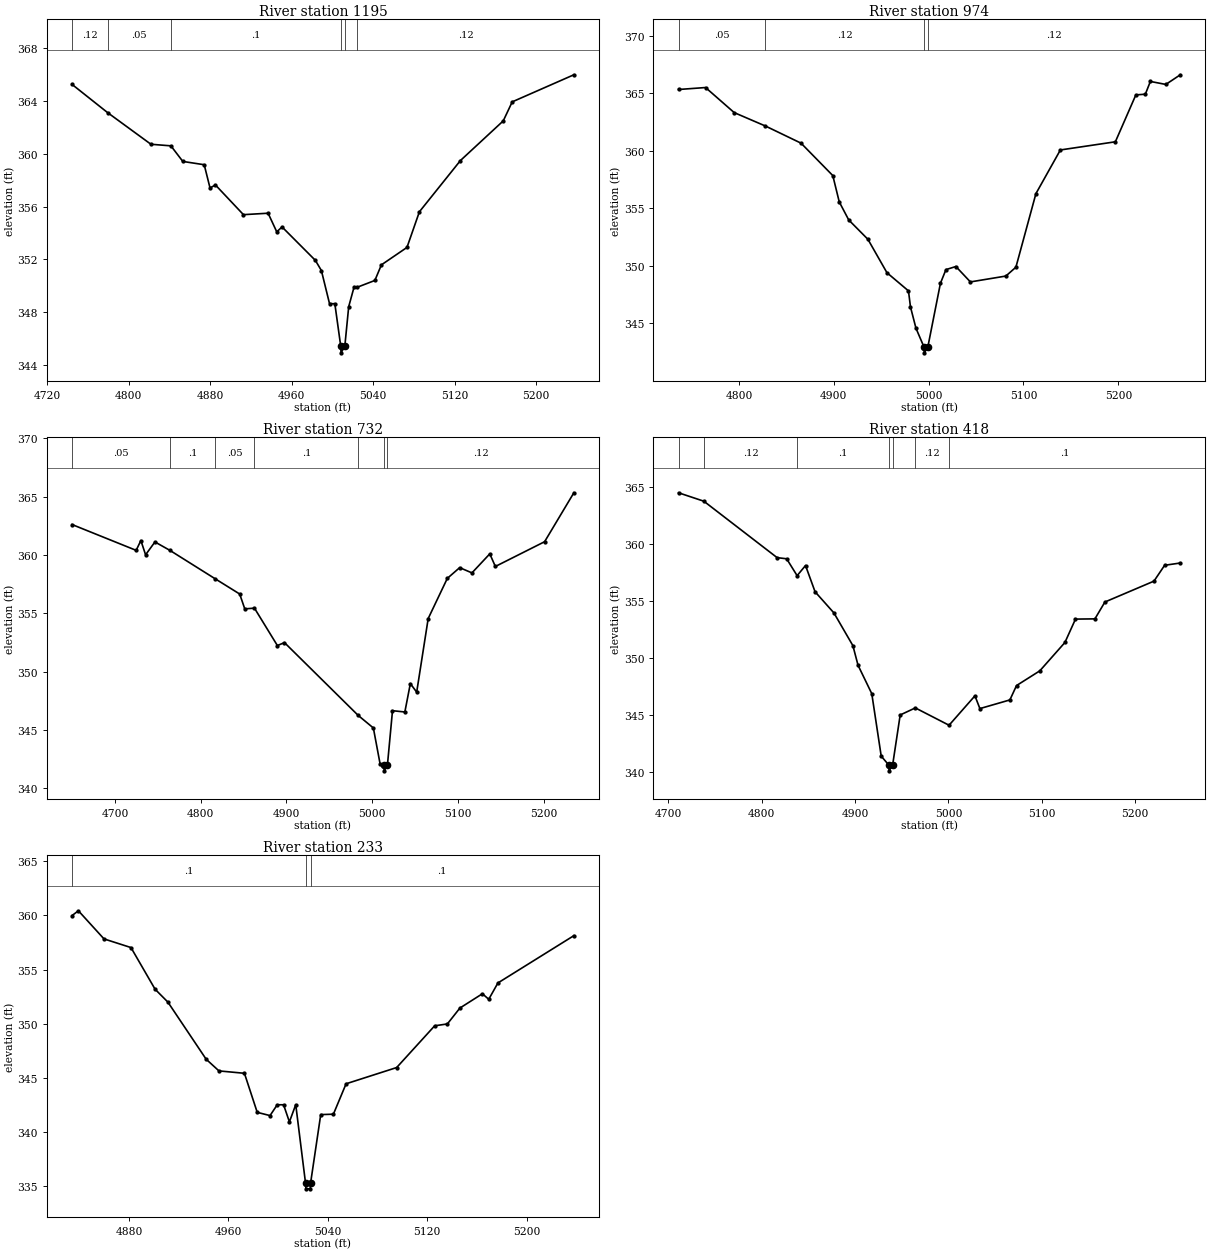
Type RM Length L Ch R = 1,1195,221,221,221
BEGIN DESCRIPTION:
CCT3_2 3.0
END DESCRIPTION:
XS GIS Cut Line= 3
      2692182.04      6850106.10      2692426.19      6850181.06
      2692651.94      6850108.57
#Sta/Elev= 30
  4744.6  365.25  4779.4  363.12  4822.0  360.72  4841.6  360.60  4853.3  359.42
  4874.3  359.17  4880.0  357.41  4885.3  357.64  4912.8  355.39  4937.0  355.50
  4945.5  354.09  4950.7  354.46  4983.4  351.93  4989.3  351.16  4997.3  348.65
  5002.5  348.65  5008.3  345.43  5008.6  344.93  5012.3  345.43  5016.1  348.42
  5021.3  349.89  5024.3  349.89  5041.8  350.41  5048.2  351.59  5073.3  352.91
  5085.5  355.61  5125.8  359.49  5167.8  362.49  5176.6  363.93  5237.1  365.98
#Mann=6,-1,0
  4744.6    0.12       0  4779.4    0.05       0  4841.6     0.1       0
  5008.3    0.07       0  5012.3     0.1       0  5024.3    0.12       0
Bank Sta=5008.3,5012.3
Exp/Cntr=0.3,0.1

Type RM Length L Ch R = 1,974,242,242,242
BEGIN DESCRIPTION:
Mapping XS a938b2c2
END DESCRIPTION:
XS GIS Cut Line= 3
      2692177.68      6850394.71      2692418.55      6850366.50
      2692690.52      6850275.84
#Sta/Elev= 30
  4736.2  365.33  4764.7  365.50  4794.9  363.32  4827.9  362.15  4865.4  360.66
  4898.9  357.84  4905.7  355.55  4915.7  353.98  4935.9  352.30  4956.0  349.39
  4978.7  347.81  4980.8  346.42  4986.6  344.56  4995.1  342.92  4995.4  342.42
  4999.1  342.92  5012.4  348.47  5018.2  349.66  5028.7  349.93  5044.0  348.59
  5081.4  349.10  5092.0  349.87  5113.1  356.27  5138.9  360.07  5196.9  360.78
  5218.5  364.86  5228.5  364.92  5233.8  366.03  5250.1  365.77  5265.4  366.61
#Mann=4,-1,0
  4736.2    0.05       0  4827.9    0.12       0  4995.1    0.07       0
  4999.1    0.12       0
Bank Sta=4995.1,4999.1
Exp/Cntr=0.3,0.1

Type RM Length L Ch R = 1,732,314,314,314
BEGIN DESCRIPTION:
Mapping XS 023c66f9
END DESCRIPTION:
XS GIS Cut Line= 3
      2692257.93      6850679.01      2692570.46      6850537.94
      2692757.96      6850384.93
#Sta/Elev= 30
  4650.1  362.60  4724.8  360.39  4730.3  361.23  4735.8  360.01  4746.7  361.11
  4764.1  360.39  4816.6  357.97  4845.5  356.65  4851.4  355.38  4862.7  355.44
  4889.4  352.24  4897.7  352.49  4983.7  346.25  5001.3  345.18  5009.2  342.08
  5013.7  342.01  5013.9  341.51  5017.7  342.01  5023.6  346.66  5038.0  346.55
  5044.4  348.98  5051.8  348.25  5065.2  354.55  5087.5  357.99  5101.9  358.91
  5116.2  358.46  5137.0  360.09  5143.5  359.01  5200.9  361.13  5235.0  365.32
#Mann=7,-1,0
  4650.1    0.05       0  4764.1     0.1       0  4816.6    0.05       0
  4862.7     0.1       0  4983.7    0.12       0  5013.7    0.07       0
  5017.7    0.12       0
Bank Sta=5013.7,5017.7
Exp/Cntr=0.3,0.1

Type RM Length L Ch R = 1,418,185,185,185
BEGIN DESCRIPTION:
Mapping XS dc3e9385
END DESCRIPTION:
XS GIS Cut Line= 3
      2692331.76      6850765.81      2692605.18      6850809.21
      2692852.83      6850729.53
#Sta/Elev= 30
  4711.2  364.51  4738.3  363.77  4816.7  358.82  4826.9  358.72  4838.1  357.24
  4847.1  358.13  4857.3  355.83  4877.5  353.97  4897.8  351.10  4903.3  349.38
  4918.0  346.89  4928.1  341.41  4936.3  340.62  4936.5  340.12  4940.3  340.62
  4948.4  345.02  4964.6  345.64  5000.7  344.12  5028.4  346.70  5033.7  345.58
  5065.8  346.34  5072.9  347.60  5097.8  348.89  5124.7  351.38  5136.0  353.43
  5156.8  353.45  5167.5  354.93  5220.0  356.76  5231.4  358.15  5248.2  358.35
#Mann=7,-1,0
  4711.2    0.05       0  4738.3    0.12       0  4838.1     0.1       0
  4936.3    0.07       0  4940.3     0.1       0  4964.6    0.12       0
  5000.7     0.1       0
Bank Sta=4936.3,4940.3
Exp/Cntr=0.3,0.1

Type RM Length L Ch R = 1,233,0,0,0
BEGIN DESCRIPTION:
CCT3_2 1.0
END DESCRIPTION:
XS GIS Cut Line= 3
      2692500.99      6850986.00      2692662.33      6850947.78
      2692895.98      6850902.53
#Sta/Elev= 30
  4834.2  359.99  4839.3  360.43  4859.9  357.83  4881.6  357.03  4901.0  353.18
  4911.3  351.99  4942.1  346.71  4952.4  345.63  4972.9  345.41  4983.2  341.80
  4993.5  341.50  4999.3  342.50  5004.4  342.50  5009.1  340.92  5014.2  342.51
  5022.1  335.23  5022.4  334.73  5025.9  334.73  5026.1  335.23  5034.3  341.59
  5044.5  341.63  5054.7  344.44  5095.4  345.94  5126.0  349.80  5136.2  349.97
  5146.3  351.44  5164.4  352.76  5169.5  352.25  5176.9  353.76  5238.0  358.13
#Mann=3,-1,0
  4834.2     0.1       0  5022.1    0.07       0  5026.1     0.1       0
Bank Sta=5022.1,5026.1
Exp/Cntr=0.3,0.1

Chan Stop Cuts=-1