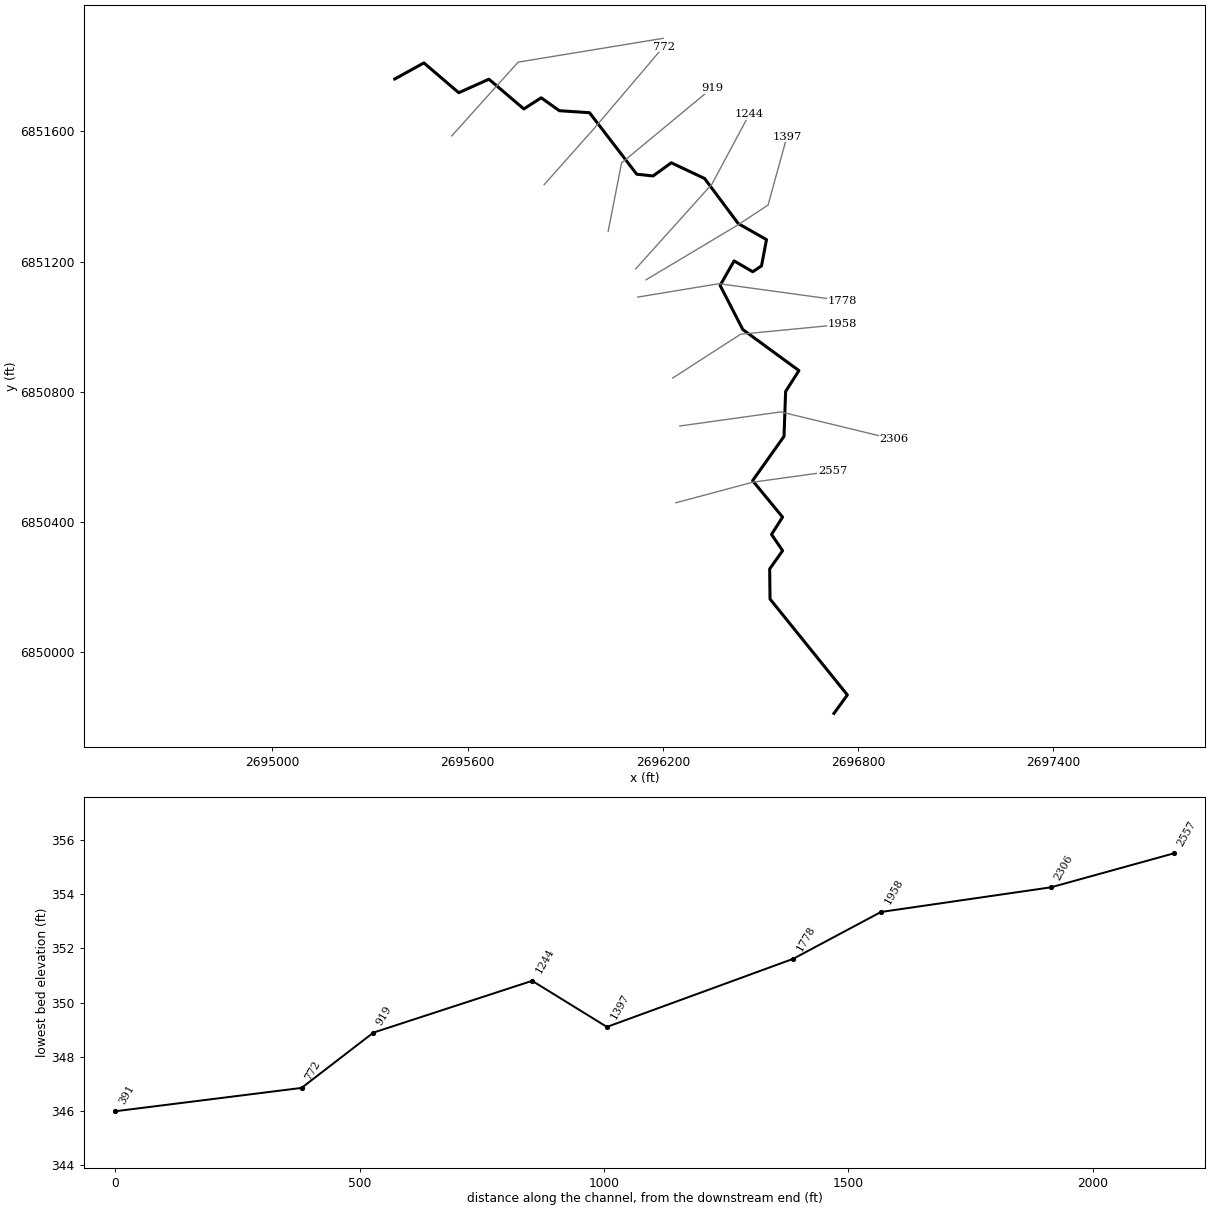
--- CCT3_3.prj (project) ---

Proj Title=CCT3_3 Base Level Engineering
Current Plan=p01
Default Exp/Contr=0.3,0.1
English Units
Geom File=g01
Flow File=f01
Plan File=p01
BEGIN DESCRIPTION:
CCT3_3
END DESCRIPTION:

--- CCT3_3.p01 (plan) ---

Plan Title=Multiple Run
Short Identifier=Multiple
Geom File=g01
Flow File=f01
Subcritical Flow
K Sum by GR= 0
Std Step Tol= 0.01
Critical Tol= 0.01
Num of Std Step Trials= 20
Max Error Tol= 0.3
Flow Tol Ratio= 0.001
Split Flow NTrial= 30
Split Flow Tol= 0.02
Split Flow Ratio= 0.02
Log Output Level= 0
Friction Slope Method= 1
Unsteady Friction Slope Method= 2
Unsteady Bridges Friction Slope Method= 1
Parabolic Critical Depth
Global Vel Dist=  1 , 1 , 1
Global Log Level= 0
CheckData=True
Encroach Param= -1, 0, 0, 0
BEGIN DESCRIPTION:
Multiple Run
END DESCRIPTION:

--- CCT3_3.f01 (steady flow) ---

Flow Title=Multiple
Number of Profiles=7
Profile Names=10-year,25-year,50-year,1pct_min,100-year,1pct_plu,500-year
River Rch & RM= CCT3_3,Reach-1,2557
     365     474     558     327     652    1301     888
Boundary for River Rch & Prof#=CCT3_3,Reach-1,1
Up Type=0
Dn Type=3
Dn Slope=0.005
Boundary for River Rch & Prof#=CCT3_3,Reach-1,2
Up Type=0
Dn Type=3
Dn Slope=0.005
Boundary for River Rch & Prof#=CCT3_3,Reach-1,3
Up Type=0
Dn Type=3
Dn Slope=0.005
Boundary for River Rch & Prof#=CCT3_3,Reach-1,4
Up Type=0
Dn Type=3
Dn Slope=0.005
Boundary for River Rch & Prof#=CCT3_3,Reach-1,5
Up Type=0
Dn Type=3
Dn Slope=0.005
Boundary for River Rch & Prof#=CCT3_3,Reach-1,6
Up Type=0
Dn Type=3
Dn Slope=0.005
Boundary for River Rch & Prof#=CCT3_3,Reach-1,7
Up Type=0
Dn Type=3
Dn Slope=0.005

--- CCT3_3.g01 (geometry) ---

Geom Title=Existing Conditions

River Reach=CCT3_3,Reach-1
Reach XY= 30
      2696726.00      6849811.00      2696767.23      6849867.67
      2696529.47      6850162.50      2696528.35      6850255.11
      2696568.21      6850311.10      2696534.04      6850361.00
      2696568.00      6850414.33      2696475.90      6850526.36
      2696572.44      6850662.47      2696577.41      6850800.57
      2696618.31      6850864.67      2696445.77      6850990.87
      2696376.01      6851126.53      2696418.96      6851201.81
      2696476.26      6851168.48      2696503.30      6851186.65
      2696518.61      6851267.27      2696431.66      6851316.64
      2696328.30      6851455.20      2696226.00      6851503.44
      2696169.91      6851462.97      2696119.67      6851468.38
      2695974.51      6851657.40      2695881.89      6851663.55
      2695825.90      6851703.20      2695772.67      6851669.01
      2695665.36      6851760.34      2695572.60      6851718.83
      2695465.45      6851810.49      2695376.00      6851761.00

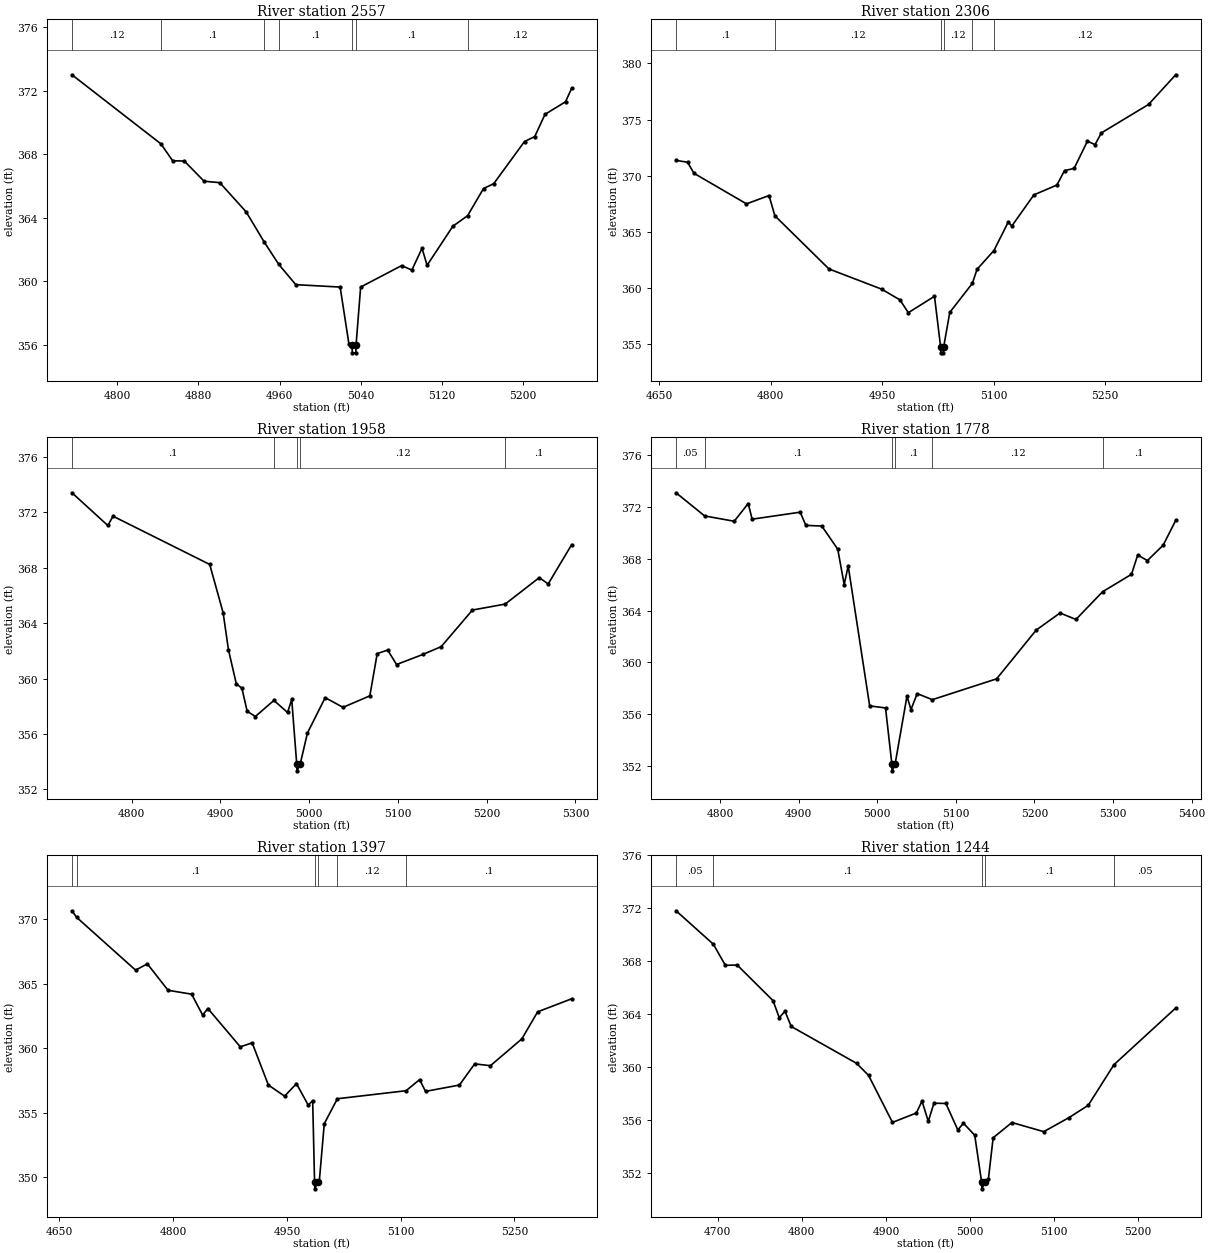
Type RM Length L Ch R = 1,2557,251,251,251
BEGIN DESCRIPTION:
CCT3_3 5.0
END DESCRIPTION:
XS GIS Cut Line= 3
      2696240.19      6850458.36      2696476.56      6850521.64
      2696721.94      6850555.46
#Sta/Elev= 30
  4755.3  373.00  4843.0  368.65  4854.5  367.59  4866.1  367.57  4885.5  366.30
  4901.0  366.21  4927.0  364.37  4944.8  362.47  4959.2  361.06  4975.9  359.79
  5019.6  359.64  5028.3  356.04  5031.3  356.00  5031.6  355.50  5035.1  355.50
  5035.3  356.00  5039.8  359.64  5080.2  360.99  5090.3  360.71  5100.3  362.08
  5105.3  361.01  5130.7  363.47  5145.2  364.13  5160.9  365.84  5171.0  366.15
  5201.3  368.80  5211.4  369.11  5221.5  370.51  5241.7  371.30  5247.7  372.14
#Mann=7,-1,0
  4755.3    0.12       0  4843.0     0.1       0  4944.8    0.12       0
  4959.2     0.1       0  5031.3    0.07       0  5035.3     0.1       0
  5145.2    0.12       0
Bank Sta=5031.3,5035.3
Exp/Cntr=0.3,0.1

Type RM Length L Ch R = 1,2306,348,348,348
BEGIN DESCRIPTION:
Mapping XS d88a14df
END DESCRIPTION:
XS GIS Cut Line= 3
      2696252.15      6850694.33      2696562.52      6850737.74
      2696911.44      6850653.22
#Sta/Elev= 30
  4672.7  371.37  4688.2  371.20  4696.8  370.22  4767.5  367.50  4797.8  368.24
  4805.7  366.44  4878.5  361.71  4949.2  359.92  4974.0  358.96  4985.3  357.82
  5020.5  359.28  5028.8  354.75  5029.1  354.25  5032.6  354.25  5032.8  354.75
  5041.1  357.85  5071.5  360.43  5077.8  361.68  5100.5  363.35  5119.6  365.86
  5124.7  365.54  5154.3  368.30  5185.2  369.17  5195.5  370.46  5208.4  370.65
  5226.3  373.07  5236.6  372.77  5245.1  373.81  5308.6  376.34  5345.1  378.98
#Mann=6,-1,0
  4672.7     0.1       0  4805.7    0.12       0  5028.8    0.07       0
  5032.8    0.12       0  5071.5     0.1       0  5100.5    0.12       0
Bank Sta=5028.8,5032.8
Exp/Cntr=0.3,0.1

Type RM Length L Ch R = 1,1958,180,180,180
BEGIN DESCRIPTION:
Mapping XS d272f34c
END DESCRIPTION:
XS GIS Cut Line= 3
      2696230.50      6850841.91      2696438.83      6850976.46
      2696752.27      6851006.72
#Sta/Elev= 30
  4732.7  373.40  4773.1  371.04  4779.0  371.71  4887.9  368.23  4903.0  364.75
  4909.0  362.08  4917.8  359.63  4924.2  359.29  4930.1  357.64  4939.3  357.26
  4960.2  358.42  4975.6  357.55  4980.3  358.49  4985.9  353.84  4986.2  353.34
  4989.9  353.84  4998.0  356.07  5018.0  358.62  5038.1  357.92  5068.3  358.75
  5076.6  361.80  5088.4  362.05  5098.4  361.01  5128.6  361.75  5148.7  362.30
  5183.9  364.94  5220.8  365.37  5259.2  367.28  5269.2  366.82  5295.6  369.65
#Mann=5,-1,0
  4732.7     0.1       0  4960.2    0.12       0  4985.9    0.07       0
  4989.9    0.12       0  5220.8     0.1       0
Bank Sta=4985.9,4989.9
Exp/Cntr=0.3,0.1

Type RM Length L Ch R = 1,1778,381,381,381
BEGIN DESCRIPTION:
Mapping XS 0935f01f
END DESCRIPTION:
XS GIS Cut Line= 3
      2696123.04      6851090.61      2696372.57      6851131.84
      2696751.71      6851079.84
#Sta/Elev= 30
  4744.0  373.10  4780.4  371.31  4818.0  370.90  4835.8  372.27  4840.8  371.06
  4901.9  371.60  4909.2  370.58  4929.4  370.53  4949.7  368.74  4957.9  366.01
  4963.0  367.45  4990.3  356.63  5010.5  356.47  5018.6  352.11  5018.8  351.61
  5022.6  352.11  5037.8  357.39  5042.8  356.34  5050.8  357.58  5070.0  357.11
  5151.8  358.72  5202.2  362.49  5232.5  363.81  5252.7  363.31  5286.6  365.45
  5323.4  366.80  5331.3  368.29  5343.6  367.86  5363.7  369.05  5379.6  370.96
#Mann=6,-1,0
  4744.0    0.05       0  4780.4     0.1       0  5018.6    0.07       0
  5022.6     0.1       0  5070.0    0.12       0  5286.6     0.1       0
Bank Sta=5018.6,5022.6
Exp/Cntr=0.3,0.1

Type RM Length L Ch R = 1,1397,153,153,153
BEGIN DESCRIPTION:
Mapping XS 531846fb
END DESCRIPTION:
XS GIS Cut Line= 4
      2696148.05      6851143.57      2696427.98      6851310.66
      2696523.46      6851373.59      2696581.48      6851584.18
#Sta/Elev= 30
  4666.5  370.64  4672.7  370.13  4750.4  366.04  4765.9  366.53  4793.2  364.48
  4824.3  364.18  4838.8  362.56  4845.7  363.07  4888.5  360.10  4904.1  360.41
  4925.5  357.14  4946.9  356.28  4962.5  357.25  4978.1  355.58  4983.9  355.94
  4986.4  349.60  4986.7  349.10  4990.4  349.60  4992.5  349.60  4999.2  354.15
  5016.5  356.08  5107.0  356.70  5124.9  357.56  5132.7  356.65  5177.4  357.14
  5197.5  358.78  5218.3  358.64  5259.8  360.72  5280.5  362.81  5325.3  363.82
#Mann=6,-1,0
  4666.5    0.05       0  4672.7     0.1       0  4986.4    0.07       0
  4990.4     0.1       0  5016.5    0.12       0  5107.0     0.1       0
Bank Sta=4986.4,4990.4
Exp/Cntr=0.3,0.1

Type RM Length L Ch R = 1,1244,325,325,325
BEGIN DESCRIPTION:
Mapping XS 68f21573
END DESCRIPTION:
XS GIS Cut Line= 3
      2696116.50      6851177.43      2696350.86      6851437.83
      2696465.87      6851652.65
#Sta/Elev= 30
  4650.5  371.81  4694.9  369.28  4709.1  367.69  4723.2  367.71  4765.8  365.02
  4773.2  363.73  4780.0  364.22  4787.4  363.07  4865.2  360.28  4879.4  359.37
  4907.8  355.82  4936.2  356.53  4942.9  357.43  4950.4  355.90  4957.1  357.27
  4971.3  357.25  4985.5  355.25  4992.2  355.76  5005.6  354.85  5013.8  351.30
  5014.0  350.80  5017.8  351.30  5021.9  351.56  5027.5  354.66  5049.8  355.81
  5087.7  355.12  5117.9  356.19  5140.5  357.11  5171.1  360.18  5244.5  364.46
#Mann=5,-1,0
  4650.5    0.05       0  4694.9     0.1       0  5013.8    0.07       0
  5017.8     0.1       0  5171.1    0.05       0
Bank Sta=5013.8,5017.8
Exp/Cntr=0.3,0.1

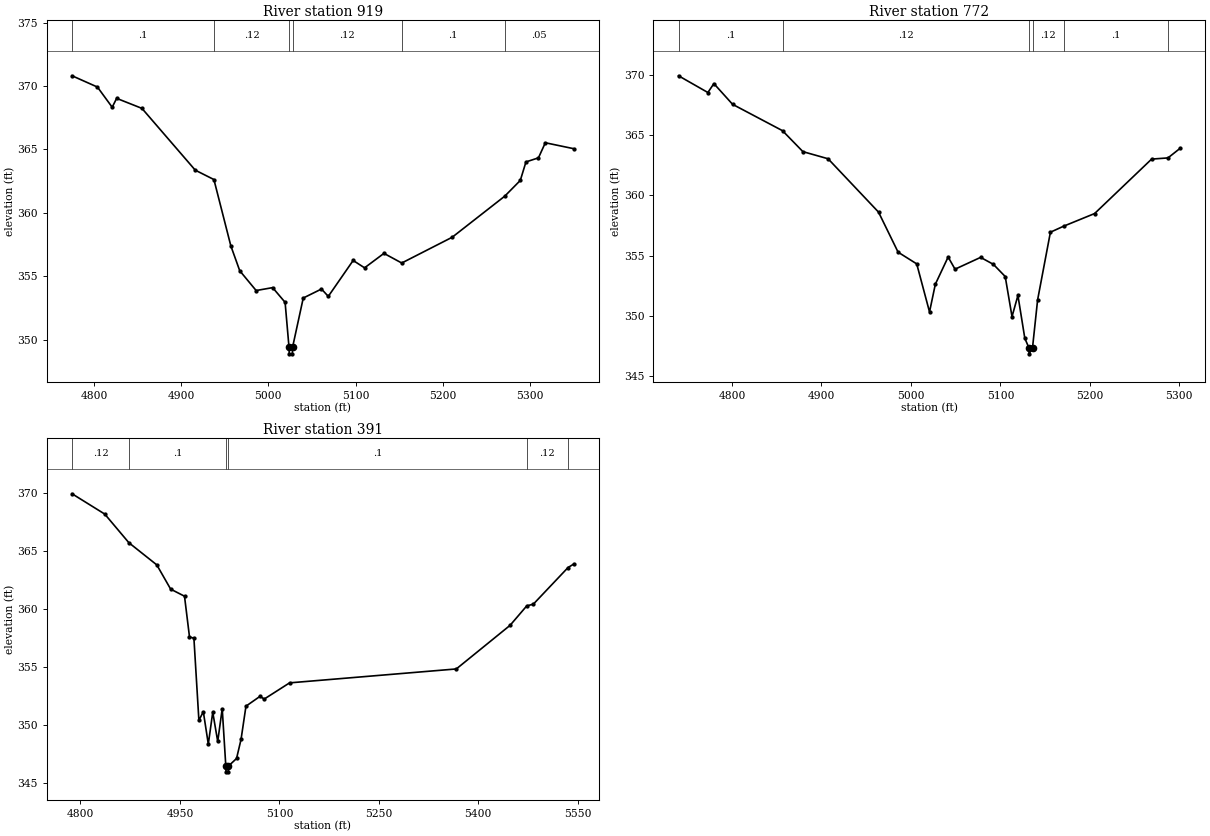
Type RM Length L Ch R = 1,919,147,147,147
BEGIN DESCRIPTION:
Mapping XS e733b224
END DESCRIPTION:
XS GIS Cut Line= 3
      2696031.85      6851292.43      2696073.09      6851502.93
      2696350.89      6851732.99
#Sta/Elev= 30
  4775.0  370.81  4804.1  369.92  4821.0  368.33  4826.1  369.03  4855.1  368.24
  4916.2  363.37  4937.6  362.63  4957.0  357.40  4967.2  355.44  4986.0  353.88
  5004.9  354.11  5019.2  352.95  5023.7  349.39  5024.0  348.89  5027.5  348.89
  5027.7  349.39  5040.0  353.29  5060.9  354.00  5068.7  353.42  5097.2  356.25
  5110.3  355.67  5132.5  356.81  5152.9  356.05  5210.7  358.08  5271.0  361.32
  5288.8  362.56  5295.3  364.02  5309.6  364.34  5317.5  365.53  5350.2  365.06
#Mann=6,-1,0
  4775.0     0.1       0  4937.6    0.12       0  5023.7    0.07       0
  5027.7    0.12       0  5152.9     0.1       0  5271.0    0.05       0
Bank Sta=5023.7,5027.7
Exp/Cntr=0.3,0.1

Type RM Length L Ch R = 1,772,381,381,381
BEGIN DESCRIPTION:
Mapping XS 68ae65c6
END DESCRIPTION:
XS GIS Cut Line= 3
      2695835.11      6851436.10      2695987.87      6851607.97
      2696202.05      6851860.14
#Sta/Elev= 30
  4740.3  369.94  4773.1  368.55  4779.8  369.29  4800.7  367.57  4856.5  365.38
  4879.3  363.64  4907.4  363.05  4963.8  358.62  4985.7  355.29  5006.5  354.32
  5020.8  350.33  5027.3  352.63  5041.6  354.89  5049.3  353.88  5077.9  354.86
  5092.2  354.28  5105.4  353.27  5113.0  349.94  5119.6  351.70  5127.3  348.14
  5131.9  347.35  5132.1  346.85  5135.9  347.35  5141.6  351.33  5155.9  356.95
  5170.7  357.45  5205.3  358.50  5269.0  363.02  5287.3  363.12  5301.1  363.93
#Mann=6,-1,0
  4740.3     0.1       0  4856.5    0.12       0  5131.9    0.07       0
  5135.9    0.12       0  5170.7     0.1       0  5287.3    0.05       0
Bank Sta=5131.9,5135.9
Exp/Cntr=0.3,0.1

Type RM Length L Ch R = 1,391,0,0,0
BEGIN DESCRIPTION:
CCT3_3 1.0
END DESCRIPTION:
XS GIS Cut Line= 3
      2695551.01      6851586.01      2695755.23      6851812.83
      2696200.96      6851885.99
#Sta/Elev= 30
  4787.3  369.96  4836.6  368.21  4873.0  365.74  4915.1  363.83  4936.0  361.74
  4956.9  361.13  4964.4  357.63  4971.1  357.50  4978.6  350.43  4985.3  351.17
  4992.8  348.38  4999.5  351.13  5007.0  348.61  5013.8  351.43  5019.2  346.49
  5019.5  345.99  5023.0  345.99  5023.2  346.49  5035.4  347.14  5042.2  348.79
  5049.6  351.65  5070.6  352.49  5077.3  352.27  5115.4  353.66  5366.9  354.86
  5448.0  358.62  5473.2  360.30  5483.0  360.44  5535.4  363.60  5544.2  363.91
#Mann=6,-1,0
  4787.3    0.12       0  4873.0     0.1       0  5019.2    0.07       0
  5023.2     0.1       0  5473.2    0.12       0  5535.4     0.1       0
Bank Sta=5019.2,5023.2
Exp/Cntr=0.3,0.1

Chan Stop Cuts=-1