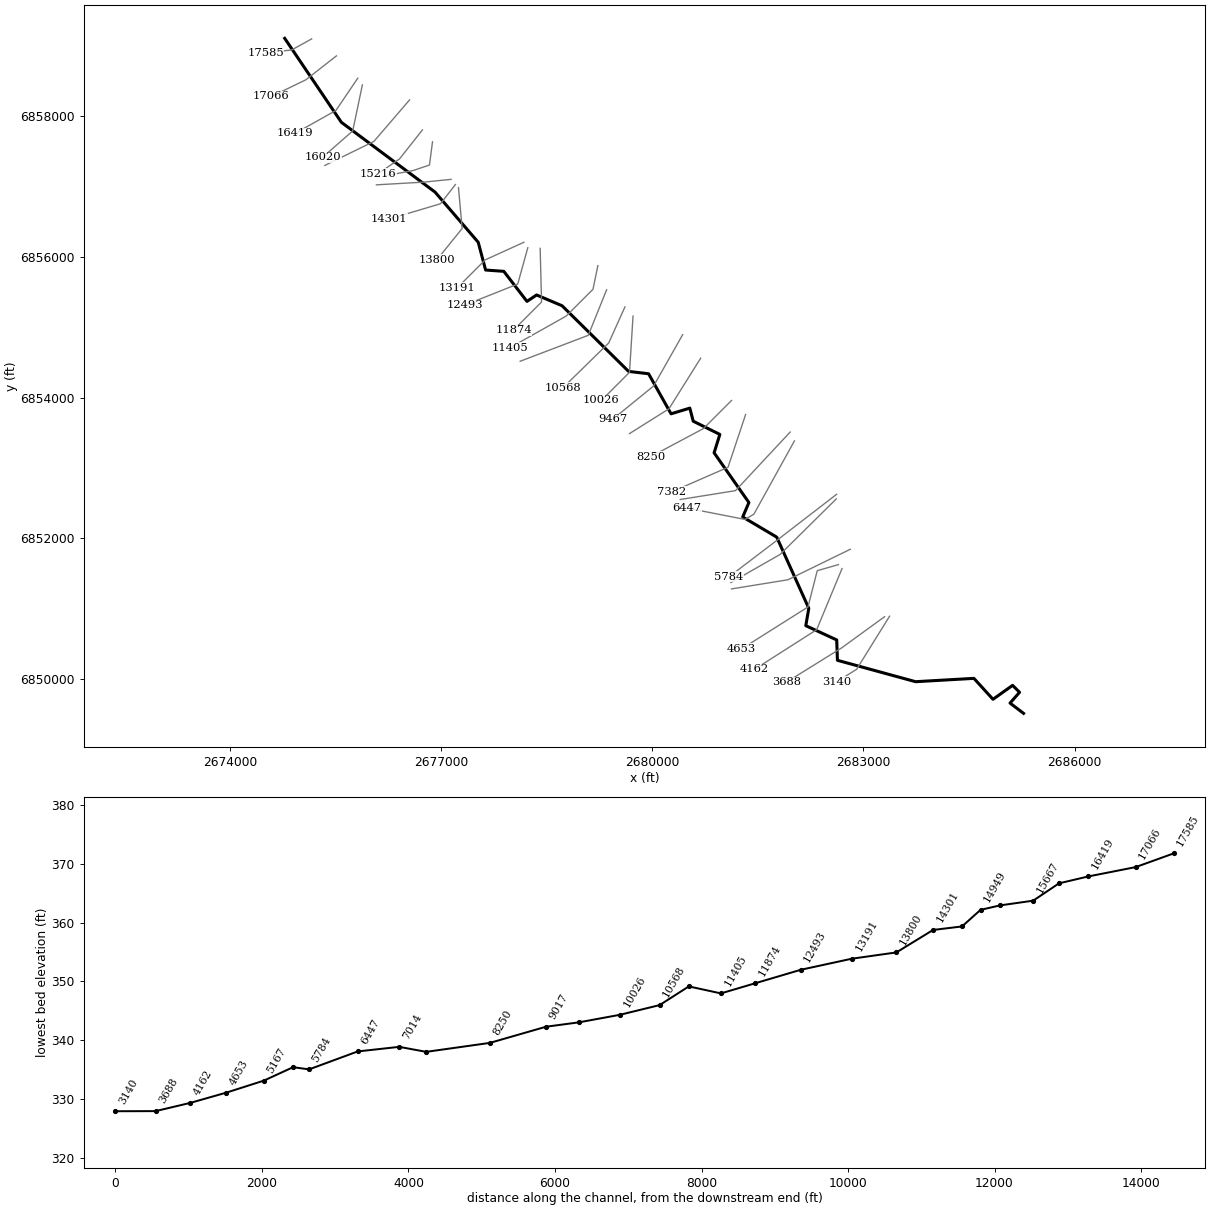
--- CCT4.prj (project) ---

Proj Title=CCT4 Base Level Engineering
Current Plan=p01
Default Exp/Contr=0.3,0.1
English Units
Geom File=g01
Flow File=f01
Plan File=p01
Y Axis Title=Elevation
X Axis Title(PF)=Main Channel Distance
X Axis Title(XS)=Station
BEGIN DESCRIPTION:
CCT4
END DESCRIPTION:
DSS Export Rating Curves= 0
DSS Export Rating Curve Sorted= 0
DSS Export Volume Flow Curves= 0
DXF OffsetX= 0
DXF OffsetY= 0
DXF ScaleX= 1
DXF ScaleY= 10

--- CCT4.p01 (plan) ---

Plan Title=Multiple Run
Short Identifier=Multiple
Geom File=g01
Flow File=f01
Subcritical Flow
K Sum by GR= 0
Std Step Tol= 0.01
Critical Tol= 0.01
Num of Std Step Trials= 20
Max Error Tol= 0.3
Flow Tol Ratio= 0.001
Split Flow NTrial= 30
Split Flow Tol= 0.02
Split Flow Ratio= 0.02
Log Output Level= 0
Friction Slope Method= 1
Unsteady Friction Slope Method= 2
Unsteady Bridges Friction Slope Method= 1
Parabolic Critical Depth
Global Vel Dist=  1 , 1 , 1
Global Log Level= 0
CheckData=True
Encroach Param= -1, 0, 0, 0
BEGIN DESCRIPTION:
Multiple Run
END DESCRIPTION:

--- CCT4.f01 (steady flow) ---

Flow Title=Multiple
Program Version=4.10
Number of Profiles= 7
Profile Names=10-year,25-year,50-year,1pct_min,100-year,1pct_plu,500-year
River Rch & RM=CCT4,Reach-1         ,17585
     623     840    1015     609    1216    2426    1742
River Rch & RM=CCT4,Reach-1         ,14301
     970    1339    1645    1001    1996    3983    2943
River Rch & RM=CCT4,Reach-1         ,11405
    1266    1771    2195    1346    2686    5360    4025
River Rch & RM=CCT4,Reach-1         ,9467
    1457    2043    2537    1557    3107    6200    4666
River Rch & RM=CCT4,Reach-1         ,5784
    1518    2127    2640    1619    3230    6444    4840
Boundary for River Rch & Prof#=CCT4,Reach-1         , 1
Up Type= 0
Dn Type= 3
Dn Slope=0.005
Boundary for River Rch & Prof#=CCT4,Reach-1         , 2
Up Type= 0
Dn Type= 3
Dn Slope=0.005
Boundary for River Rch & Prof#=CCT4,Reach-1         , 3
Up Type= 0
Dn Type= 3
Dn Slope=0.005
Boundary for River Rch & Prof#=CCT4,Reach-1         , 4
Up Type= 0
Dn Type= 3
Dn Slope=0.005
Boundary for River Rch & Prof#=CCT4,Reach-1         , 5
Up Type= 0
Dn Type= 3
Dn Slope=0.005
Boundary for River Rch & Prof#=CCT4,Reach-1         , 6
Up Type= 0
Dn Type= 3
Dn Slope=0.005
Boundary for River Rch & Prof#=CCT4,Reach-1         , 7
Up Type= 0
Dn Type= 3
Dn Slope=0.005
DSS Import GetInterval= 0
DSS Import GetPeak= 0
DSS Import FillOption= 0

--- CCT4.g01 (geometry) ---

Geom Title=Existing Conditions
Program Version=4.10

River Reach=CCT4            ,Reach-1
Reach XY= 30
        2674776.        6859111.      2675581.59      6857916.61
       2676912.6       6856924.3        2677526.        6856211.
      2677631.04      6855816.08      2677889.38      6855797.46
        2678219.      6855369.83      2678355.62      6855461.37
      2678717.72      6855307.93      2679662.62      6854374.53
      2679946.92      6854340.86      2680266.29      6853771.18
      2680533.07      6853852.01      2680581.19      6853666.44
      2680960.03      6853477.86      2680878.05      6853216.86
      2681372.55      6852509.51      2681284.82        6852304.
      2681768.19      6852017.23      2682223.77      6851005.07
      2682181.09      6850758.16      2682620.39      6850555.41
      2682630.63      6850265.64      2683741.22      6849961.52
      2684570.15      6850008.94      2684841.22      6849711.23
      2685119.97      6849909.42      2685218.93      6849811.01
      2685083.48      6849657.42        2685276.        6849511.

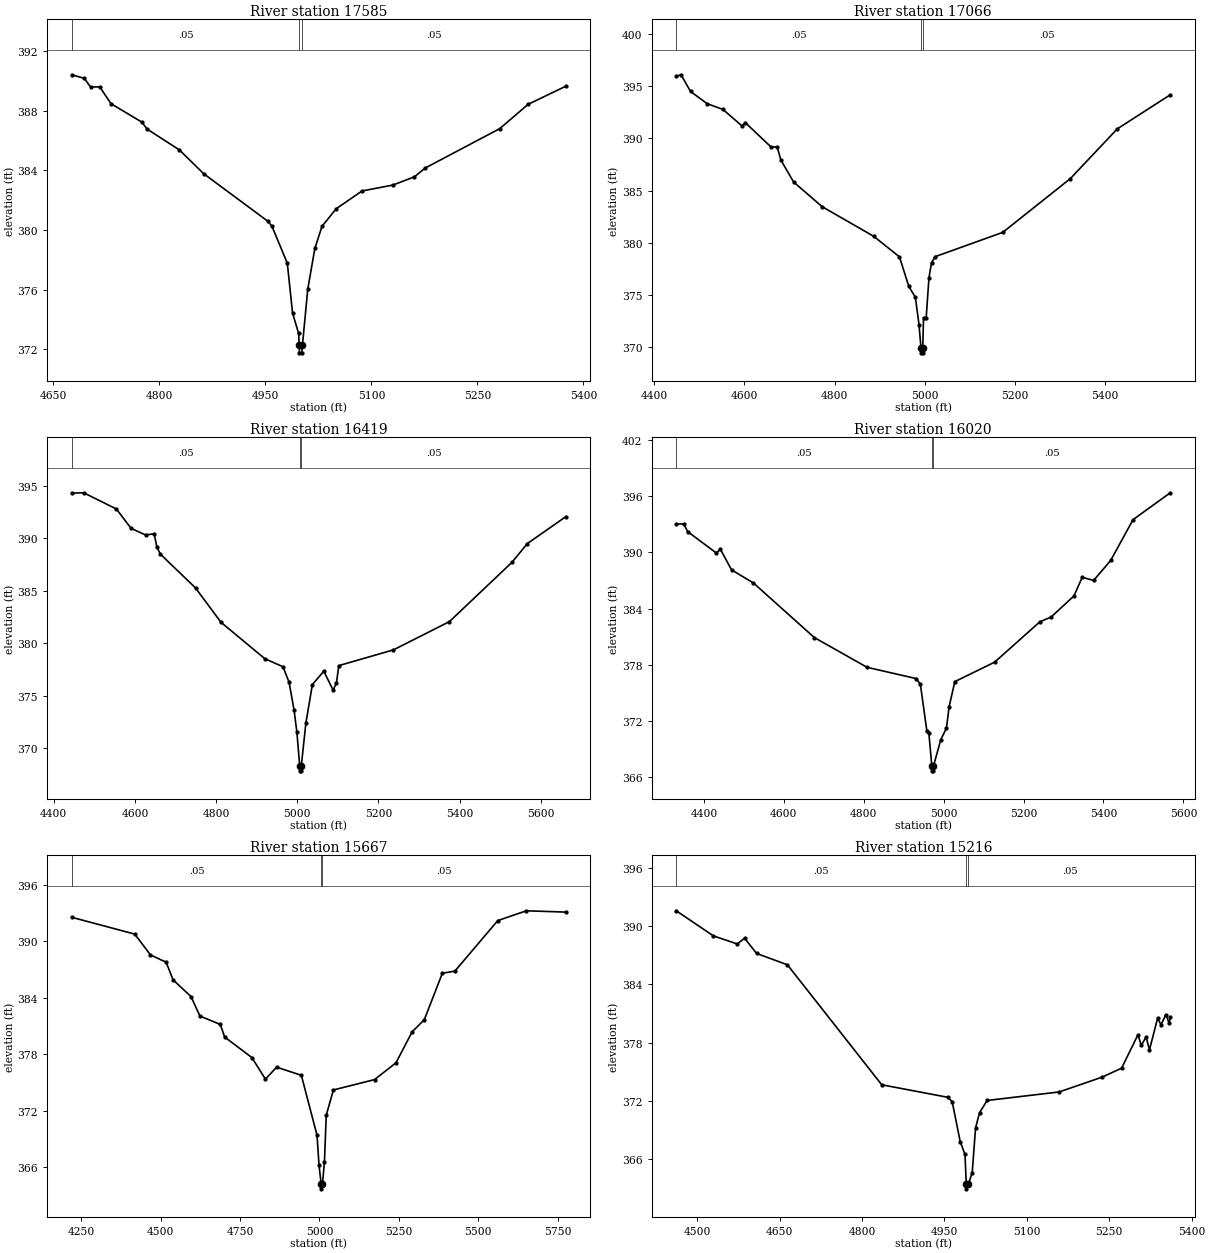
Type RM Length L Ch R = 1 ,17585   ,519,519,519
BEGIN DESCRIPTION:
CCT4 36.0
END DESCRIPTION:
XS GIS Cut Line= 3
      2675159.37      6859103.19      2674875.86      6858945.94
      2674503.16      6858903.55
#Sta/Elev= 30
  4675.8   390.4  4693.7  390.16  4702.5  389.58  4715.5  389.59  4731.5  388.46
    4775  387.23  4782.6  386.76  4828.3  385.36  4862.6  383.77  4953.5  380.58
  4959.2  380.25    4981  377.77  4988.4  374.44    4997  373.06  4997.9  372.26
  4998.2  371.76  5001.7  371.76  5001.9  372.26  5002.4  372.26  5009.9  376.01
    5020  378.76  5030.1  380.24  5050.2  381.42  5086.7  382.61  5130.7  383.01
  5160.9  383.56  5176.2  384.15  5281.7  386.79  5321.9  388.42  5375.1  389.63
#Mann= 3 ,-1 , 0
  4675.8     .05       0  4997.9     .04       0  5001.9     .05       0
Bank Sta=4997.9,5001.9
XS Rating Curve= 0 ,0
Exp/Cntr=0.3,0.1

Type RM Length L Ch R = 1 ,17066   ,647,647,647
BEGIN DESCRIPTION:
CCT4 35.0
END DESCRIPTION:
XS GIS Cut Line= 3
      2675510.93      6858861.43      2675077.07      6858521.45
      2674586.43      6858284.17
#Sta/Elev= 30
  4448.8  395.98  4459.5  396.11  4480.5  394.51  4517.3  393.34  4552.6  392.78
  4594.8   391.2  4602.3  391.51  4658.4  389.21  4672.9  389.17    4681  387.93
  4709.2  385.82  4772.7  383.45    4887  380.61  4944.1  378.64  4964.9   375.8
  4979.4  374.76  4987.5  372.13  4991.8  369.93  4992.1  369.43  4995.6  369.43
  4995.8  369.93  4997.5  372.81  5003.4  372.81  5009.6  376.65  5015.2  378.07
  5023.4  378.66  5173.3  380.99  5323.3  386.15  5427.4  390.92    5545  394.19
#Mann= 3 ,-1 , 0
  4448.8     .05       0  4991.8     .04       0  4995.8     .05       0
Bank Sta=4991.8,4995.8
XS Rating Curve= 0 ,0
Exp/Cntr=0.3,0.1

Type RM Length L Ch R = 1 ,16419   ,399,399,399
BEGIN DESCRIPTION:
CCT4 34.0
END DESCRIPTION:
XS GIS Cut Line= 3
      2675814.79      6858544.63      2675503.01      6858084.51
      2674926.01      6857761.01
#Sta/Elev= 30
  4444.2  394.29  4473.8  394.32  4554.6  392.77  4590.5  390.93  4626.5   390.3
  4647.5  390.42  4653.9  389.18  4662.4  388.49  4749.3  385.26  4812.2  381.98
  4920.1  378.52  4964.9  377.75  4979.9  376.27  4992.2  373.61  4999.1  371.52
    5006  368.34  5006.3  367.84  5009.8  367.84    5010  368.34  5021.3   372.4
  5037.3  376.06  5065.4  377.33  5088.3  375.53  5096.6  376.22  5102.3  377.86
    5237  379.36  5374.9  382.05  5529.1   387.7  5566.8  389.48  5661.5  392.04
#Mann= 3 ,-1 , 0
  4444.2     .05       0    5006     .04       0    5010     .05       0
Bank Sta=5006,5010
XS Rating Curve= 0 ,0
Exp/Cntr=0.3,0.1

Type RM Length L Ch R = 1 ,16020   ,353,353,353
BEGIN DESCRIPTION:
CCT4 32.0
END DESCRIPTION:
XS GIS Cut Line= 3
      2675879.88      6858449.11      2675742.51      6857793.96
      2675315.64      6857420.47
#Sta/Elev= 30
  4330.6  393.02  4349.1  393.05  4359.3  392.22  4430.8  389.94  4441.1  390.34
    4469  388.14    4524  386.73  4676.1  380.91  4808.1  377.73  4931.5  376.52
  4941.7  375.91  4957.8  370.97  4962.9   370.7  4970.4  367.17  4970.6  366.67
  4974.1  366.67  4974.4  367.17  4992.8     370    5007  371.24  5013.7  373.54
  5027.9   376.2  5127.6  378.28  5240.5  382.58    5269   383.1    5326  385.35
  5346.8  387.34  5375.3  387.01    5418  389.14    5474   393.5  5567.2  396.37
#Mann= 3 ,-1 , 0
  4330.6     .05       0  4970.4     .04       0  4974.4     .05       0
Bank Sta=4970.4,4974.4
XS Rating Curve= 0 ,0
Exp/Cntr=0.3,0.1

Type RM Length L Ch R = 1 ,15667   ,451,451,451
BEGIN DESCRIPTION:
CCT4 31.0
END DESCRIPTION:
XS GIS Cut Line= 3
      2676551.03      6858236.03      2676042.82      6857644.32
        2675346.      6857303.27
#Sta/Elev= 30
    4220  392.56  4418.7  390.77  4468.1  388.56  4517.4  387.79  4539.4  385.91
  4595.7  384.14  4623.9  382.07    4688  381.18  4701.8  379.84  4787.4  377.66
  4830.2  375.37  4865.3  376.64  4943.2  375.78  4992.6  369.41  4998.9  366.22
  5005.6  364.22  5005.8  363.72  5009.6  364.22    5016  366.58  5021.6  371.53
  5044.1  374.22  5173.6  375.32  5241.1   377.1  5291.7  380.37  5330.5  381.69
  5387.3  386.62  5426.7  386.84  5561.8  392.21  5651.8  393.25  5775.8  393.11
#Mann= 3 ,-1 , 0
    4220     .05       0  5005.6     .04       0  5009.6     .05       0
Bank Sta=5005.6,5009.6
XS Rating Curve= 0 ,0
Exp/Cntr=0.3,0.1

Type RM Length L Ch R = 1 ,15216   ,267,267,267
BEGIN DESCRIPTION:
Mapping XS 48c90ae3
END DESCRIPTION:
XS GIS Cut Line= 3
      2676733.27      6857808.66      2676407.73      6857396.31
       2676100.3      6857184.14
#Sta/Elev= 30
  4462.1  391.59  4529.8     389  4573.1  388.17  4586.5  388.76  4608.3  387.19
  4664.4  386.02    4836  373.65  4956.1  372.36  4964.2  371.91  4978.7   367.8
  4987.5  366.47  4989.8  363.42  4990.1  362.92  4993.8  363.42  5000.6  364.59
  5006.7  369.19  5013.9  370.76  5027.7  372.03  5158.8  372.91  5236.6  374.43
  5272.4  375.36  5302.2  378.81  5308.2   377.7    5317  378.58  5323.1  377.25
    5338  380.53  5344.1  379.83  5352.9  380.88  5358.9  380.02    5361  380.59
#Mann= 3 ,-1 , 0
  4462.1     .05       0  4989.8     .04       0  4993.8     .05       0
Bank Sta=4989.8,4993.8
XS Rating Curve= 0 ,0
Exp/Cntr=0.3,0.1

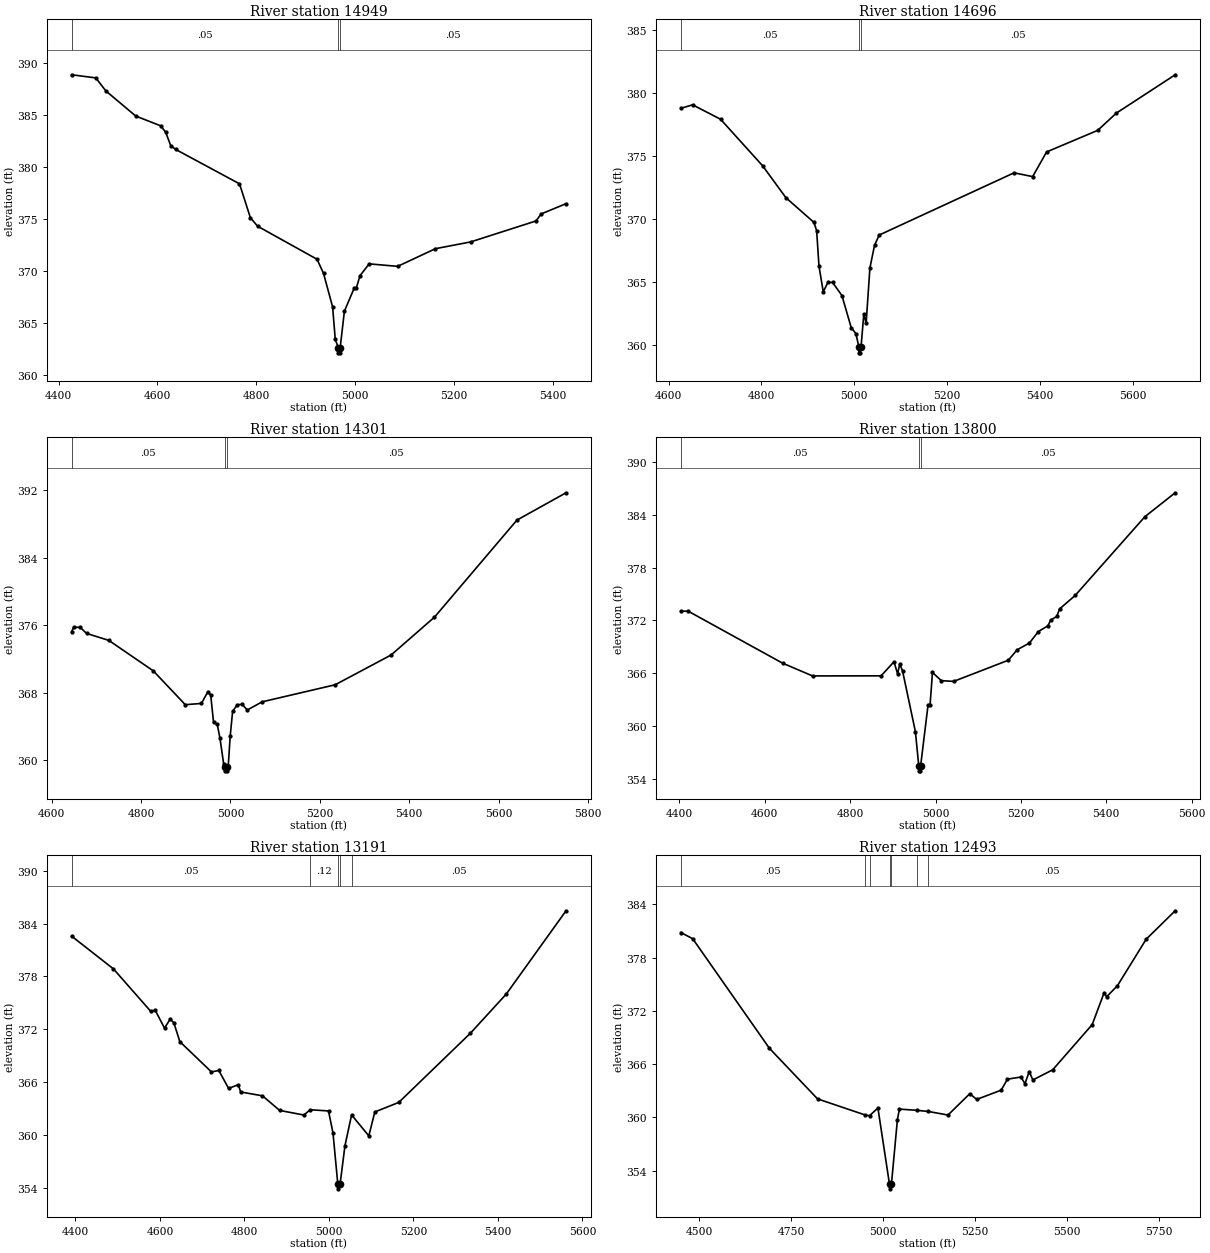
Type RM Length L Ch R = 1 ,14949   ,253,253,253
BEGIN DESCRIPTION:
Mapping XS 092c2c3d
END DESCRIPTION:
XS GIS Cut Line= 4
      2676876.48      6857639.41      2676833.07       6857309.5
      2676603.04      6857231.38      2676186.39      6857153.26
#Sta/Elev= 30
  4426.6  388.91  4475.4  388.61  4495.6  387.36  4556.1  384.94  4606.5     384
  4616.6  383.39  4626.8   382.1  4636.8  381.73  4765.9  378.42  4787.9  375.16
  4802.6  374.34  4922.8  371.16  4935.8   369.8  4954.2  366.58  4959.5  363.48
  4965.5  362.66  4965.7  362.16  4969.2  362.16  4969.5  362.66    4978  366.16
  4998.1  368.42  5002.3  368.42  5009.5  369.58  5028.1  370.72  5085.7  370.48
  5162.1  372.18  5233.3  372.83  5365.6  374.85  5375.7  375.52  5426.2  376.51
#Mann= 3 ,-1 , 0
  4426.6     .05       0  4965.5     .03       0  4969.5     .05       0
Bank Sta=4965.5,4969.5
XS Rating Curve= 0 ,0
Exp/Cntr=0.3,0.1

Type RM Length L Ch R = 1 ,14696   ,395,395,395
BEGIN DESCRIPTION:
Mapping XS fd237797
END DESCRIPTION:
XS GIS Cut Line= 3
      2677141.28      6857105.52      2676754.95      6857066.45
      2676079.47      6857027.48
#Sta/Elev= 30
  4626.3  378.79  4651.7  379.07    4712  377.92  4802.5  374.22  4852.7  371.68
    4913  369.72  4918.9  369.06  4923.9  366.25  4933.1  364.19  4943.2  364.95
  4953.2  364.94  4973.3   363.9  4993.4  361.34  5003.5  360.87  5009.6  359.84
  5009.8  359.34  5013.3  359.34  5013.6  359.84  5014.6  359.84  5020.5  362.43
  5025.5  361.69  5033.6  366.09  5043.6  367.89  5053.6  368.71  5344.1  373.66
  5384.2  373.36  5414.2  375.32  5524.4  377.04  5564.5  378.41  5691.2  381.46
#Mann= 3 ,-1 , 0
  4626.3     .05       0  5009.6     .04       0  5013.6     .05       0
Bank Sta=5009.6,5013.6
XS Rating Curve= 0 ,0
Exp/Cntr=0.3,0.1

Type RM Length L Ch R = 1 ,14301   ,501,501,501
BEGIN DESCRIPTION:
Mapping XS 3b867872
END DESCRIPTION:
XS GIS Cut Line= 3
        2677202.      6857031.72      2676989.32      6856758.29
      2676260.62      6856541.41
#Sta/Elev= 30
  4644.5  375.24  4648.9  375.75  4663.4  375.75  4677.9  375.03  4727.7   374.2
  4827.2  370.59  4898.8  366.58  4934.9  366.73  4949.4  368.12  4955.7  367.73
  4962.1  364.48  4970.2  364.29  4976.5  362.59  4984.7  359.56  4987.5  359.24
  4987.8  358.74  4991.3  358.74  4991.5  359.24  4994.9  359.24  4999.3  362.84
  5004.8   365.8  5015.2  366.57  5025.7  366.63  5037.7  365.95  5070.8  366.92
  5234.3  368.94  5359.5  372.47  5456.7  376.96  5641.2  388.46  5751.2   391.7
#Mann= 3 ,-1 , 0
  4644.5     .05       0  4987.5     .04       0  4991.5     .05       0
Bank Sta=4987.5,4991.5
XS Rating Curve= 0 ,0
Exp/Cntr=0.3,0.1

Type RM Length L Ch R = 1 ,13800   ,609,609,609
BEGIN DESCRIPTION:
Mapping XS 19030496
END DESCRIPTION:
XS GIS Cut Line= 3
       2677245.4       6856988.3      2677297.48      6856406.73
      2676937.26       6855959.7
#Sta/Elev= 30
  4403.4  373.06  4420.8  373.05  4641.7  367.15  4711.9   365.7  4872.6  365.71
  4902.7  367.31  4911.2  365.94  4916.2  367.04  4922.8  366.27  4952.9  359.37
  4960.9  355.42  4961.2  354.92  4964.7  354.92    4965  355.42  4982.6  362.43
  4987.3  362.43  4992.9  366.09  5013.7  365.16  5042.5  365.08  5170.5  367.48
  5191.3  368.67  5220.1  369.44  5240.9  370.74  5263.3  371.39  5269.7  372.03
  5284.1  372.46  5290.5   373.3  5327.2  374.84  5490.4  383.78  5561.4   386.5
#Mann= 3 ,-1 , 0
  4403.4     .05       0  4960.9     .04       0    4965     .05       0
Bank Sta=4960.9,4965
XS Rating Curve= 0 ,0
Exp/Cntr=0.3,0.1

Type RM Length L Ch R = 1 ,13191   ,698,698,698
BEGIN DESCRIPTION:
CCT4 26.0
END DESCRIPTION:
XS GIS Cut Line= 3
      2678175.99        6856211.        2677626.        6855961.
      2677226.02      6855561.02
#Sta/Elev= 30
  4391.3  382.56  4490.2  378.84    4578  374.04    4589  374.14    4611  372.11
  4624.2  373.14    4633  372.72  4647.2  370.58  4721.9  367.14  4739.5   367.3
  4762.6  365.26  4785.6  365.69  4791.1  364.86  4842.8  364.42  4883.4  362.76
  4940.5  362.24  4955.9  362.84    4999   362.7  5009.6   360.2  5021.1  354.35
  5021.8  353.85  5026.3  354.35  5037.9  358.74  5053.6  362.25  5094.4  359.87
  5108.6  362.59  5165.2  363.67  5334.9  371.54  5419.7  375.99  5561.1  385.45
#Mann= 5 ,-1 , 0
  4391.3     .05       0  4955.9     .12       0  5021.1     .07       0
  5026.3     .12       0  5053.6     .05       0
Bank Sta=5021.1,5026.3
XS Rating Curve= 0 ,0
Exp/Cntr=0.3,0.1

Type RM Length L Ch R = 1 ,12493   ,619,619,619
BEGIN DESCRIPTION:
Mapping XS ab656af9
END DESCRIPTION:
XS GIS Cut Line= 3
      2678230.63      6856133.26      2678087.41       6855616.8
      2677336.58      6855317.33
#Sta/Elev= 30
  4450.6  380.82  4482.8  380.13  4691.6  367.78  4822.4  362.09  4951.6  360.28
  4963.7  360.19  4986.6  361.06  5018.1  352.46  5018.8  351.96  5023.3  352.46
  5039.6  359.76    5045  360.94  5092.5   360.8    5124  360.67  5177.1  360.27
  5236.4  362.67  5255.2  362.03  5321.8  363.07  5338.8  364.31  5375.7  364.55
  5386.4  363.79  5398.1  365.17  5407.9  364.22  5461.8  365.36  5569.4  370.46
  5601.7  374.05  5608.3  373.58    5638  374.84  5716.1  380.07  5794.9  383.27
#Mann= 7 ,-1 , 0
  4450.6     .05       0  4951.6     .12       0  4963.7      .1       0
  5018.1     .07       0  5023.3      .1       0  5092.5     .12       0
    5124     .05       0
Bank Sta=5018.1,5023.3
XS Rating Curve= 0 ,0
Exp/Cntr=0.3,0.1

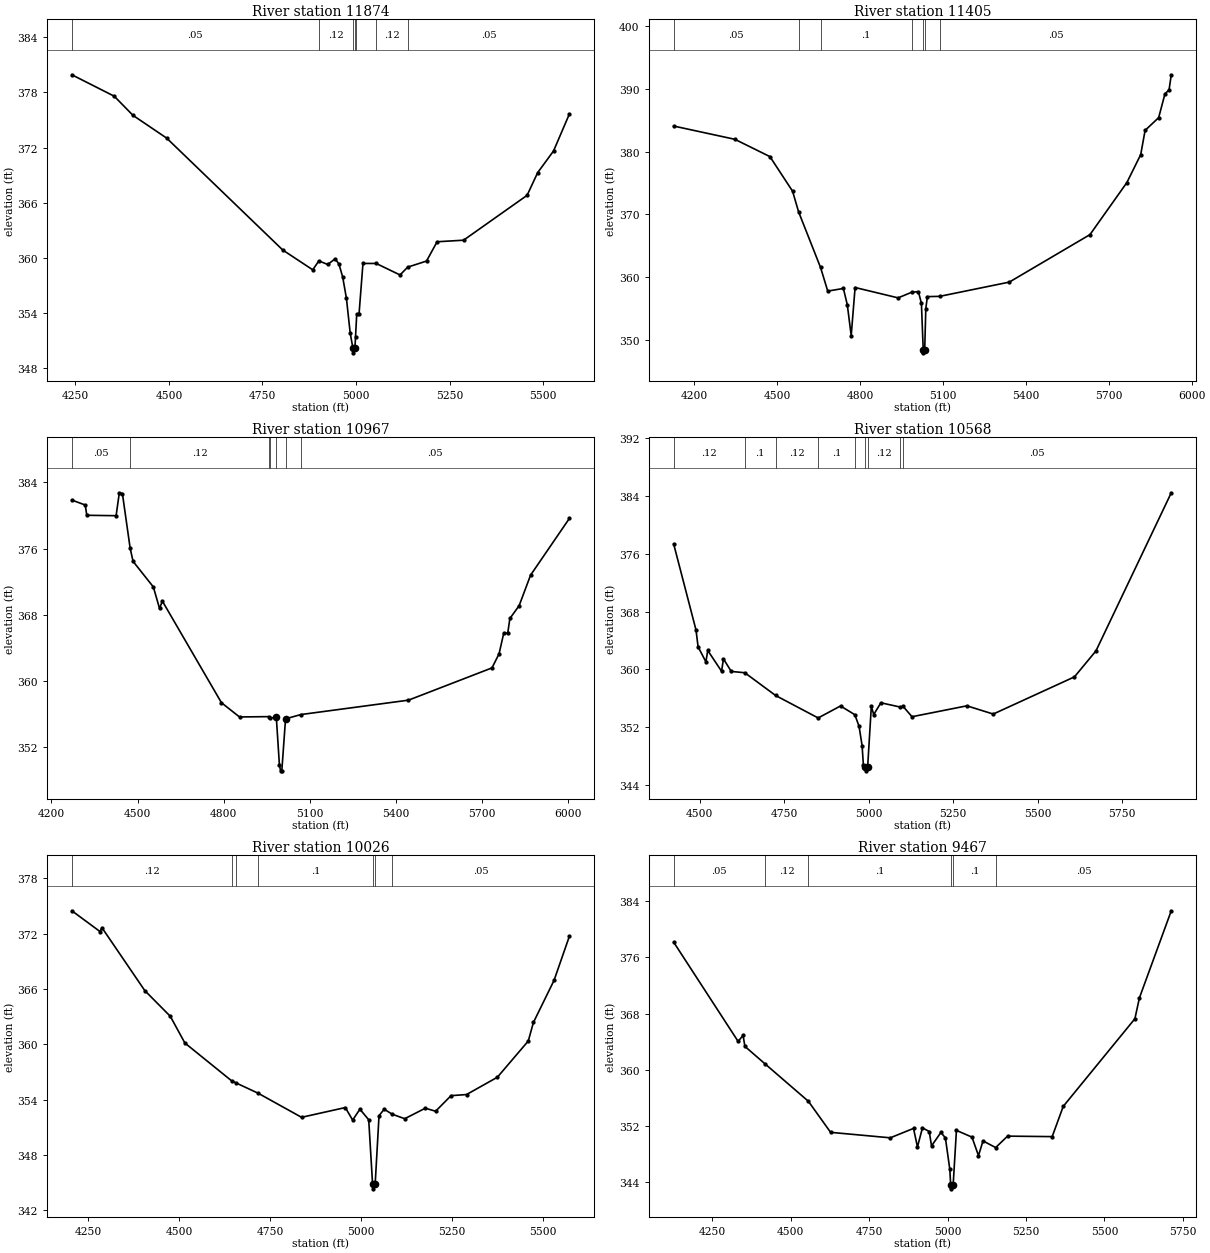
Type RM Length L Ch R = 1 ,11874   ,469,469,469
BEGIN DESCRIPTION:
CCT4 23.0
END DESCRIPTION:
XS GIS Cut Line= 3
      2678406.11      6856124.18        2678426.        6855361.
      2678026.02      6854961.02
#Sta/Elev= 30
  4240.8  379.92    4354  377.59    4404  375.51  4494.1  373.03  4804.2  360.86
  4884.2  358.71  4900.6  359.68  4924.2  359.29  4944.2  359.91  4954.2  359.33
  4964.2  357.93  4974.2  355.61  4984.2  351.86  4991.5  350.18  4992.3  349.68
  4996.9  350.18  4998.5   351.4  5001.7  353.85  5007.8  353.85  5018.4   359.4
  5053.7   359.4  5117.4  358.15  5137.8     359  5188.1  359.66  5216.4  361.76
  5287.1  361.93  5456.8  366.81  5485.1  369.28  5527.5  371.64  5569.9  375.67
#Mann= 7 ,-1 , 0
  4240.8     .05       0  4900.6     .12       0  4991.5     .07       0
  4996.9     .12       0  4998.5      .1       0  5053.7     .12       0
  5137.8     .05       0
Bank Sta=4991.5,4996.9
XS Rating Curve= 0 ,0
Exp/Cntr=0.3,0.1

Type RM Length L Ch R = 1 ,11405   ,438,438,438
BEGIN DESCRIPTION:
CCT4 22.0
END DESCRIPTION:
XS GIS Cut Line= 4
      2679226.37      6855878.89      2679157.01      6855542.01
        2678776.        6855161.      2677975.96      6854710.98
#Sta/Elev= 30
  4125.5  384.09  4346.7  381.98  4473.7  379.22  4555.7  373.71  4577.5  370.42
    4657  361.55    4683  357.79  4739.6  358.21  4753.7  355.63  4767.9  350.71
    4782  358.36  4937.6  356.71  4987.7  357.62  5011.1   357.7    5022  355.84
  5028.5  348.45  5029.3  347.95  5033.9  348.45  5037.9  355.01  5043.6  356.91
  5087.9  356.95    5340  359.22    5632  366.79  5765.5  375.08  5815.6  379.54
  5831.5   383.4  5880.6  385.43  5903.2   389.2  5918.2  389.86  5926.2  392.26
#Mann= 7 ,-1 , 0
  4125.5     .05       0  4577.5     .12       0    4657      .1       0
  4987.7     .12       0  5028.5     .07       0  5033.9     .12       0
  5087.9     .05       0
Bank Sta=5028.5,5033.9
XS Rating Curve= 0 ,0
Exp/Cntr=0.3,0.1

Type RM Length L Ch R = 1 ,10967   ,399,399,399
BEGIN DESCRIPTION:
Mapping XS 419fb6b9
END DESCRIPTION:
XS GIS Cut Line= 3
      2679350.42      6855534.29      2679090.02      6854887.63
      2678122.16      6854518.72
#Sta/Elev= 30
  4271.3  381.86  4317.9  381.26  4323.3  380.02  4425.4  379.97  4436.6  382.74
  4447.3  382.65  4474.4  376.02  4484.5  374.45  4555.1  371.36  4576.7  368.76
  4586.5  369.65  4792.3  357.37  4855.2  355.65  4957.2  355.69  4962.4  355.53
  4983.4  355.59  4994.1  349.87  4998.1  349.14  5002.5  349.14  5015.5  355.42
  5068.7  355.94  5443.6  357.68  5734.5  361.58  5759.2  363.29  5775.4  365.78
  5789.3  365.78  5796.8  367.55  5828.9  369.09  5868.9  372.79  6004.2  379.65
#Mann= 7 ,-1 , 0
  4271.3     .05       0  4474.4     .12       0  4957.2     .05       0
  4962.4     .12       0  4983.4     .07       0  5015.5     .12       0
  5068.7     .05       0
Bank Sta=4983.4,5015.5
XS Rating Curve= 0 ,0
Exp/Cntr=0.3,0.1

Type RM Length L Ch R = 1 ,10568   ,542,542,542
BEGIN DESCRIPTION:
Mapping XS 43aacc8f
END DESCRIPTION:
XS GIS Cut Line= 3
      2679610.84      6855291.25      2679380.82      6854779.12
      2678730.39      6854141.71
#Sta/Elev= 30
    4423  377.35  4489.1  365.44  4495.2  363.12  4518.3  361.05  4523.8  362.62
  4564.7  359.74  4570.2  361.46  4593.3  359.72  4633.4  359.54  4724.5  356.39
  4850.4  353.28  4916.6  354.94  4958.9  353.73  4971.4  352.13  4980.4  349.46
  4984.2  346.76  4990.3  346.46  4991.3  345.96  4996.8  346.46  5007.7  354.88
  5014.8  353.75    5036  355.38    5094  354.78  5101.8  354.88    5128  353.45
  5290.5  354.96  5368.4  353.82  5608.7  358.97  5672.4  362.57  5895.1  384.45
#Mann= 9 ,-1 , 0
    4423     .12       0  4633.4      .1       0  4724.5     .12       0
  4850.4      .1       0  4958.9     .12       0  4990.3     .07       0
  4996.8     .12       0    5094      .1       0  5101.8     .05       0
Bank Sta=4990.3,4996.8
XS Rating Curve= 0 ,0
Exp/Cntr=0.3,0.1

Type RM Length L Ch R = 1 ,10026   ,559,559,559
BEGIN DESCRIPTION:
CCT4 19.0
END DESCRIPTION:
XS GIS Cut Line= 3
        2679726.      6855160.97        2679676.        6854361.
      2679276.01      6853961.01
#Sta/Elev= 30
  4205.9  374.48  4283.5  372.22  4288.5  372.65  4406.3  365.82  4476.4  363.03
  4516.5  360.13  4644.9  356.03  4655.9  355.82  4717.5  354.69  4837.1  352.07
  4957.3  353.13  4977.4  351.77  4997.4  352.95  5021.6   351.8  5032.2  344.81
  5033.3  344.31  5039.3  344.81  5049.9  352.24    5064  352.95  5086.4   352.4
  5120.6  351.92  5177.1  353.06  5205.4  352.73  5247.8  354.42  5290.3  354.54
  5375.1  356.42    5460  360.35  5474.1  362.36  5530.7  366.92  5573.1  371.73
#Mann= 7 ,-1 , 0
  4205.9     .12       0  4644.9     .05       0  4655.9     .12       0
  4717.5      .1       0  5032.2     .07       0  5039.3      .1       0
  5086.4     .05       0
Bank Sta=5032.2,5039.3
XS Rating Curve= 0 ,0
Exp/Cntr=0.3,0.1

Type RM Length L Ch R = 1 ,9467    ,450,450,450
BEGIN DESCRIPTION:
Mapping XS d27054f5
END DESCRIPTION:
XS GIS Cut Line= 3
      2680431.15      6854896.28      2680018.84      6854167.14
      2679438.44      6853695.03
#Sta/Elev= 30
    4127  378.17  4332.3  364.04  4348.2  364.89  4353.9  363.33  4417.5  360.86
  4556.2  355.51  4627.1  351.08  4817.3   350.3  4891.3  351.64  4903.9     349
  4919.8  351.72  4941.5   351.2  4948.7  349.14  4978.5  351.06  4992.9   350.3
    5007  345.81  5009.8  343.53    5011  343.03  5017.6  343.53  5028.1  351.36
  5077.6   350.4  5098.4  347.76  5112.8  349.86  5153.1  348.91  5191.1  350.54
  5333.3  350.47  5368.5  354.78  5596.9  367.27  5611.3  370.24  5712.8  382.65
#Mann= 6 ,-1 , 0
    4127     .05       0  4417.5     .12       0  4556.2      .1       0
  5009.8     .07       0  5017.6      .1       0  5153.1     .05       0
Bank Sta=5009.8,5017.6
XS Rating Curve= 0 ,0
Exp/Cntr=0.3,0.1

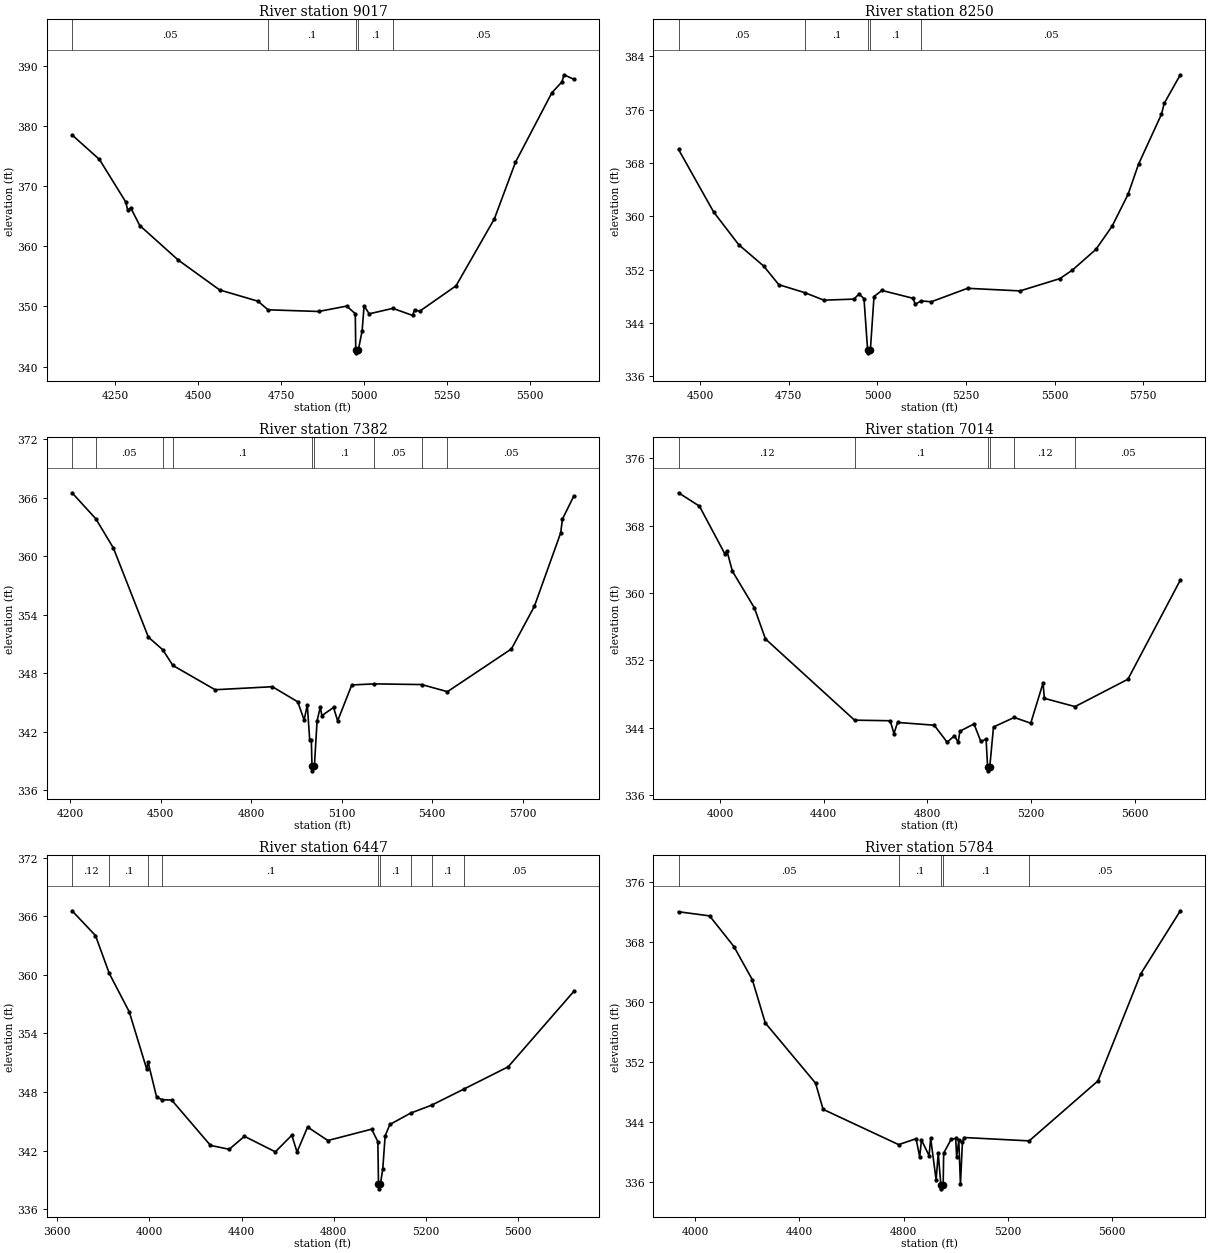
Type RM Length L Ch R = 1 ,9017    ,767,767,767
BEGIN DESCRIPTION:
Mapping XS 71c430fc
END DESCRIPTION:
XS GIS Cut Line= 3
      2680687.23      6854562.09      2680235.85      6853841.62
      2679675.96      6853490.06
#Sta/Elev= 30
  4119.9  378.58  4202.4  374.49  4281.4  367.43  4287.3   366.1  4296.7  366.41
  4323.8  363.49  4439.8  357.73  4564.3  352.76  4679.8  350.88  4710.2  349.45
  4862.5  349.17  4947.3  350.07  4972.9  348.79  4974.3  342.78  4975.5  342.28
  4982.1  342.78  4993.5  345.93  4999.4  350.11  5014.8  348.78  5086.1  349.69
  5145.5  348.51  5151.4  349.43  5166.7  349.21  5276.3  353.44  5391.7  364.59
  5455.4  374.04  5564.9   385.6  5595.5  387.43  5601.4   388.6  5631.2  387.85
#Mann= 5 ,-1 , 0
  4119.9     .05       0  4710.2      .1       0  4974.3     .07       0
  4982.1      .1       0  5086.1     .05       0
Bank Sta=4974.3,4982.1
XS Rating Curve= 0 ,0
Exp/Cntr=0.3,0.1

Type RM Length L Ch R = 1 ,8250    ,868,868,868
BEGIN DESCRIPTION:
CCT4 15.0
END DESCRIPTION:
XS GIS Cut Line= 3
      2681125.99      6853960.99        2680726.        6853561.
      2679975.98      6853160.99
#Sta/Elev= 30
  4438.7  370.04  4537.7  360.66  4608.4  355.76  4679.1  352.54  4721.5  349.76
  4796.3  348.53  4848.8  347.43  4933.7  347.59  4947.8  348.36  4961.9  347.66
  4972.1  340.03  4973.3  339.53    4980  340.03  4990.2  347.98  5012.5  348.89
  5100.4  347.71  5106.4  346.82  5123.3  347.32  5151.7  347.19  5254.1  349.21
  5402.1  348.82  5514.4  350.66  5550.1  351.95  5616.4  355.06  5661.7  358.51
    5707  363.31  5736.4  367.82  5801.2  375.32    5809  376.96  5854.4  381.24
#Mann= 5 ,-1 , 0
  4438.7     .05       0  4796.3      .1       0  4972.1     .07       0
    4980      .1       0  5123.3     .05       0
Bank Sta=4972.1,4980
XS Rating Curve= 0 ,0
Exp/Cntr=0.3,0.1

Type RM Length L Ch R = 1 ,7382    ,368,368,368
BEGIN DESCRIPTION:
CCT4 14.0
END DESCRIPTION:
XS GIS Cut Line= 3
        2681326.        6853761.        2681076.        6853011.
      2680275.98      6852660.99
#Sta/Elev= 30
  4205.6   366.5  4284.5  363.83  4342.6  360.84  4458.6  351.71  4506.2  350.42
  4539.8  348.81  4679.9  346.32  4869.7  346.63    4954  345.08  4975.1  343.21
  4985.6  344.77  4993.5  341.17  4998.9  341.17  5001.1  338.51  5002.3  338.01
  5009.1  338.51    5018  343.13  5028.5  344.53    5034  343.67  5072.6   344.5
  5086.2  343.13    5133  346.81  5208.2  346.92    5365  346.85  5450.2  346.12
  5662.4   350.5  5738.4  354.86  5825.7  362.39  5831.6  363.81  5869.4  366.17
#Mann= 9 ,-1 , 0
  4205.6     .12       0  4284.5     .05       0  4506.2     .12       0
  4539.8      .1       0  5001.1     .07       0  5009.1      .1       0
  5208.2     .05       0    5365     .12       0  5450.2     .05       0
Bank Sta=5001.1,5009.1
XS Rating Curve= 0 ,0
Exp/Cntr=0.3,0.1

Type RM Length L Ch R = 1 ,7014    ,567,567,567
BEGIN DESCRIPTION:
Mapping XS 6e227abb
END DESCRIPTION:
XS GIS Cut Line= 3
      2681958.93      6853511.75      2681182.03      6852678.43
      2680396.45      6852552.56
#Sta/Elev= 30
    3840  371.89  3920.6   370.3  4019.3  364.59  4026.6     365  4047.6  362.58
  4132.6  358.21  4175.1  354.53  4518.7  344.88  4656.3  344.81  4670.5  343.29
  4684.7  344.61  4825.9  344.28  4875.7  342.26    4904  343.02  4918.2  342.25
    4925  343.57  4979.3  344.43  5005.7  342.35  5025.9  342.62  5031.8  339.36
  5033.1  338.86  5040.2  339.36  5054.5  344.07  5134.4   345.2  5198.1  344.52
  5245.6  349.29  5250.6  347.47  5368.8  346.49  5572.8  349.74  5774.9  361.52
#Mann= 6 ,-1 , 0
    3840     .12       0  4518.7      .1       0  5031.8     .07       0
  5040.2      .1       0  5134.4     .12       0  5368.8     .05       0
Bank Sta=5031.8,5040.2
XS Rating Curve= 0 ,0
Exp/Cntr=0.3,0.1

Type RM Length L Ch R = 1 ,6447    ,663,663,663
BEGIN DESCRIPTION:
Mapping XS b667b7b7
END DESCRIPTION:
XS GIS Cut Line= 4
       2682019.7      6853385.88      2681443.64      6852344.45
      2681319.15      6852268.82       2680491.9      6852431.04
#Sta/Elev= 30
  3664.2  366.56  3765.9  364.02  3825.8  360.14  3912.5  356.21  3988.1  350.36
  3994.4  351.04  4031.6  347.45    4056  347.21  4096.8  347.17  4265.2  342.53
  4346.5  342.13  4412.6  343.46  4546.9  341.87  4618.3  343.57  4641.1  341.85
  4686.9  344.41  4774.9  343.03  4964.8  344.19    4992  342.91  4994.7  338.58
  4995.9  338.08  5003.2  338.58  5013.4  340.15  5023.6  343.51    5044  344.67
  5134.7  345.84  5225.5  346.65  5367.3  348.32  5557.8  350.58    5843  358.31
#Mann= 9 ,-1 , 0
  3664.2     .12       0  3825.8      .1       0  3994.4     .12       0
    4056      .1       0  4994.7     .07       0  5003.2      .1       0
  5134.7     .05       0  5225.5      .1       0  5367.3     .05       0
Bank Sta=4994.7,5003.2
XS Rating Curve= 0 ,0
Exp/Cntr=0.3,0.1

Type RM Length L Ch R = 1 ,5784    ,219,219,219
BEGIN DESCRIPTION:
CCT4 11.0
END DESCRIPTION:
XS GIS Cut Line= 3
      2682618.64      6852626.33      2681776.49      6851976.21
       2681090.6      6851453.76
#Sta/Elev= 30
  3936.1  372.01  4055.3  371.46  4148.6  367.37  4219.3  362.94  4269.1  357.17
    4462  349.14    4491  345.64  4781.1  340.93  4847.9  341.72  4861.7  339.29
  4868.7  341.55  4897.7  339.46    4904  341.75  4924.8  336.22    4933  339.76
  4943.1  335.53  4944.4  335.03  4951.9  335.53  4953.8  339.79  4982.8  341.66
    5000  341.75  5003.6  339.33  5011.9  341.51  5018.2  335.65  5025.8  341.26
  5032.7  341.88    5282  341.43  5546.2  349.44  5710.4  363.73  5862.2  372.14
#Mann= 5 ,-1 , 0
  3936.1     .05       0  4781.1      .1       0  4943.1     .07       0
  4951.9      .1       0    5282     .05       0
Bank Sta=4943.1,4951.9
XS Rating Curve= 0 ,0
Exp/Cntr=0.3,0.1

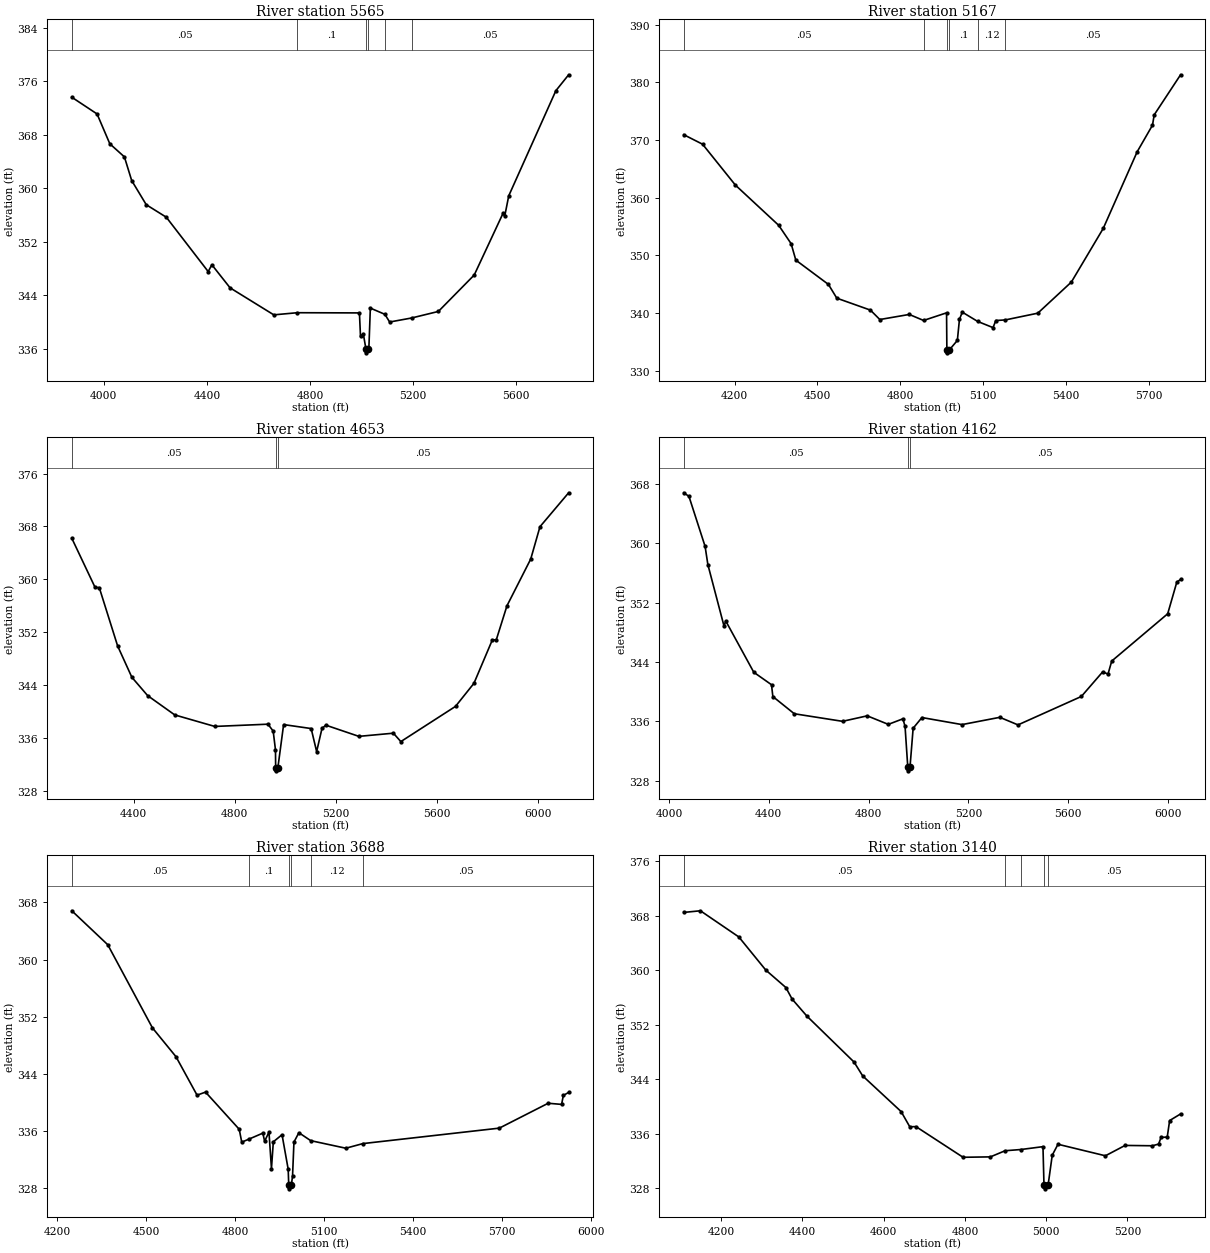
Type RM Length L Ch R = 1 ,5565    ,398,398,398
BEGIN DESCRIPTION:
CCT4 10.0
END DESCRIPTION:
XS GIS Cut Line= 3
      2682614.33      6852561.24       2681815.1      6851770.63
      2681116.89      6851371.98
#Sta/Elev= 30
  3875.8  373.62  3973.8  371.12  4023.3  366.66  4079.9   364.7  4108.2  361.16
  4164.7  357.55  4242.5  355.68  4405.1  347.55  4419.3  348.57    4490  345.12
  4659.7  341.08  4751.1   341.4    4992  341.37  4996.2  337.85    5007  338.26
  5017.6   335.9  5018.8   335.4  5026.4   335.9  5028.6  336.04  5034.4  342.09
  5090.8  341.16  5109.3  340.01  5194.4  340.61  5298.4  341.59  5437.6  347.04
  5549.9  356.31  5555.7   355.8  5571.5  358.88  5754.4   374.6    5804  376.98
#Mann= 6 ,-1 , 0
  3875.8     .05       0  4751.1      .1       0  5017.6     .07       0
  5026.4      .1       0  5090.8     .12       0  5194.4     .05       0
Bank Sta=5017.6,5026.4
XS Rating Curve= 0 ,0
Exp/Cntr=0.3,0.1

Type RM Length L Ch R = 1 ,5167    ,514,514,514
BEGIN DESCRIPTION:
CCT4 9.0
END DESCRIPTION:
XS GIS Cut Line= 3
      2682813.96      6851845.09        2681926.        6851411.
       2681125.6      6851280.86
#Sta/Elev= 30
  4015.7  370.91  4083.9  369.26  4202.7  362.18  4359.6  355.21  4404.6  352.03
  4421.6  349.18  4539.7  344.97    4570  342.59  4691.8  340.52  4725.8  338.89
  4832.4  339.77  4884.3  338.73  4967.5  340.05  4968.6  333.62  4969.9  333.12
  4977.5  333.62  5006.6  335.27  5014.2  338.92  5024.4  340.17  5080.2  338.56
  5135.8  337.49  5145.9  338.72  5180.1  338.82  5297.9  339.99  5419.5  345.38
  5534.9  354.67  5657.9  367.96  5713.3  372.56  5719.5  374.35    5815  381.29
#Mann= 6 ,-1 , 0
  4015.7     .05       0  4884.3      .1       0  4968.6     .07       0
  4977.5      .1       0  5080.2     .12       0  5180.1     .05       0
Bank Sta=4968.6,4977.5
XS Rating Curve= 0 ,0
Exp/Cntr=0.3,0.1

Type RM Length L Ch R = 1 ,4653    ,491,491,491
BEGIN DESCRIPTION:
CCT4 8.0
END DESCRIPTION:
XS GIS Cut Line= 4
      2682644.34       6851626.3       2682343.7      6851540.01
      2682212.28      6851024.17      2681264.55      6850425.65
#Sta/Elev= 30
  4154.9  366.21  4246.8   358.8  4263.6  358.75  4336.2  349.94  4392.5  345.21
  4454.9  342.44  4562.2  339.52  4720.6  337.78    4931  338.12  4951.7  337.08
  4960.8  334.24  4961.5  331.57  4962.8  331.07  4970.4  331.57    4993  338.06
    5102  337.46  5123.7  333.98  5144.9  337.49  5160.2  337.97  5290.8  336.28
  5427.3  336.76  5456.9  335.49  5673.2  340.81  5746.2   344.3  5819.1  350.87
  5834.4  350.85  5876.8  356.01  5970.9  363.08  6007.4  367.96  6120.9  373.09
#Mann= 3 ,-1 , 0
  4154.9     .05       0  4961.5     .04       0  4970.4     .05       0
Bank Sta=4961.5,4970.4
XS Rating Curve= 0 ,0
Exp/Cntr=0.3,0.1

Type RM Length L Ch R = 1 ,4162    ,474,474,474
BEGIN DESCRIPTION:
CCT4 7.0
END DESCRIPTION:
XS GIS Cut Line= 3
      2682695.74      6851570.23      2682335.99      6850701.26
        2681451.        6850136.
#Sta/Elev= 30
  4059.5  366.79  4080.3  366.31  4145.1  359.56  4156.1  357.12    4221  348.81
  4227.6  349.53  4340.1  342.61  4411.1  340.93  4416.5  339.34  4502.4  337.02
  4695.6     336  4794.6  336.74  4879.1  335.59  4937.7  336.34  4946.2  335.31
  4957.1  329.83  4958.4  329.33    4966  329.83  4978.6  335.07  5013.8  336.51
  5174.5  335.56  5325.9  336.54  5398.7  335.52  5652.6  339.35  5737.9  342.66
  5759.4  342.37  5774.3  344.12  5998.5  350.49  6034.9  354.74  6050.1  355.12
#Mann= 3 ,-1 , 0
  4059.5     .05       0  4957.1     .04       0    4966     .05       0
Bank Sta=4957.1,4966
XS Rating Curve= 0 ,0
Exp/Cntr=0.3,0.1

Type RM Length L Ch R = 1 ,3688    ,548,548,548
BEGIN DESCRIPTION:
CCT4 6.0
END DESCRIPTION:
XS GIS Cut Line= 3
        2683301.        6850886.       2682693.5      6850444.31
      2681907.28      6849955.65
#Sta/Elev= 30
  4248.9  366.82  4370.2  362.07  4520.9  350.45  4600.5  346.41  4671.6  341.03
  4700.2  341.46  4813.9  336.26  4822.4  334.46    4846  334.87  4893.5  335.72
  4899.6  334.59  4914.3  335.86  4922.7  330.77    4929  334.51  4958.4   335.5
  4979.2  330.66    4981  328.43  4982.3  327.93  4989.9  328.43  4993.9  329.77
  4998.6  334.47  5015.2  335.78  5055.2  334.67  5173.7  333.61  5231.5  334.26
  5691.7  336.42  5856.6   339.9  5901.9  339.74  5907.8  340.99  5925.7  341.42
#Mann= 6 ,-1 , 0
  4248.9     .05       0    4846      .1       0    4981     .07       0
  4989.9      .1       0  5055.2     .12       0  5231.5     .05       0
Bank Sta=4981,4989.9
XS Rating Curve= 0 ,0
Exp/Cntr=0.3,0.1

Type RM Length L Ch R = 1 ,3140    ,454,454,454
BEGIN DESCRIPTION:
CCT4 5.0
END DESCRIPTION:
XS GIS Cut Line= 3
      2683371.63      6850892.48      2682902.88      6850137.27
      2682620.32      6849960.42
#Sta/Elev= 30
  4108.4  368.47  4149.4  368.71  4243.9  364.87  4310.2  360.01  4359.6  357.45
    4375  355.75  4411.6  353.24  4527.4  346.51  4548.6  344.48  4643.1  339.25
  4664.4  337.02  4679.7  337.04  4795.5  332.54  4862.8   332.6  4898.9   333.5
  4937.9  333.68  4992.1   334.1  4994.6  328.41    4996  327.91  5004.6  328.41
  5014.9  332.84    5029  334.45  5145.7  332.76  5194.1  334.28  5261.3  334.23
  5276.6  334.48  5282.5  335.45  5297.8  335.51  5303.7  337.93  5330.6   338.9
#Mann= 5 ,-1 , 0
  4108.4     .05       0  4898.9      .1       0  4937.9     .05       0
  4994.6     .03       0  5004.6     .05       0
Bank Sta=4994.6,5004.6
XS Rating Curve= 0 ,0
Exp/Cntr=0.3,0.1