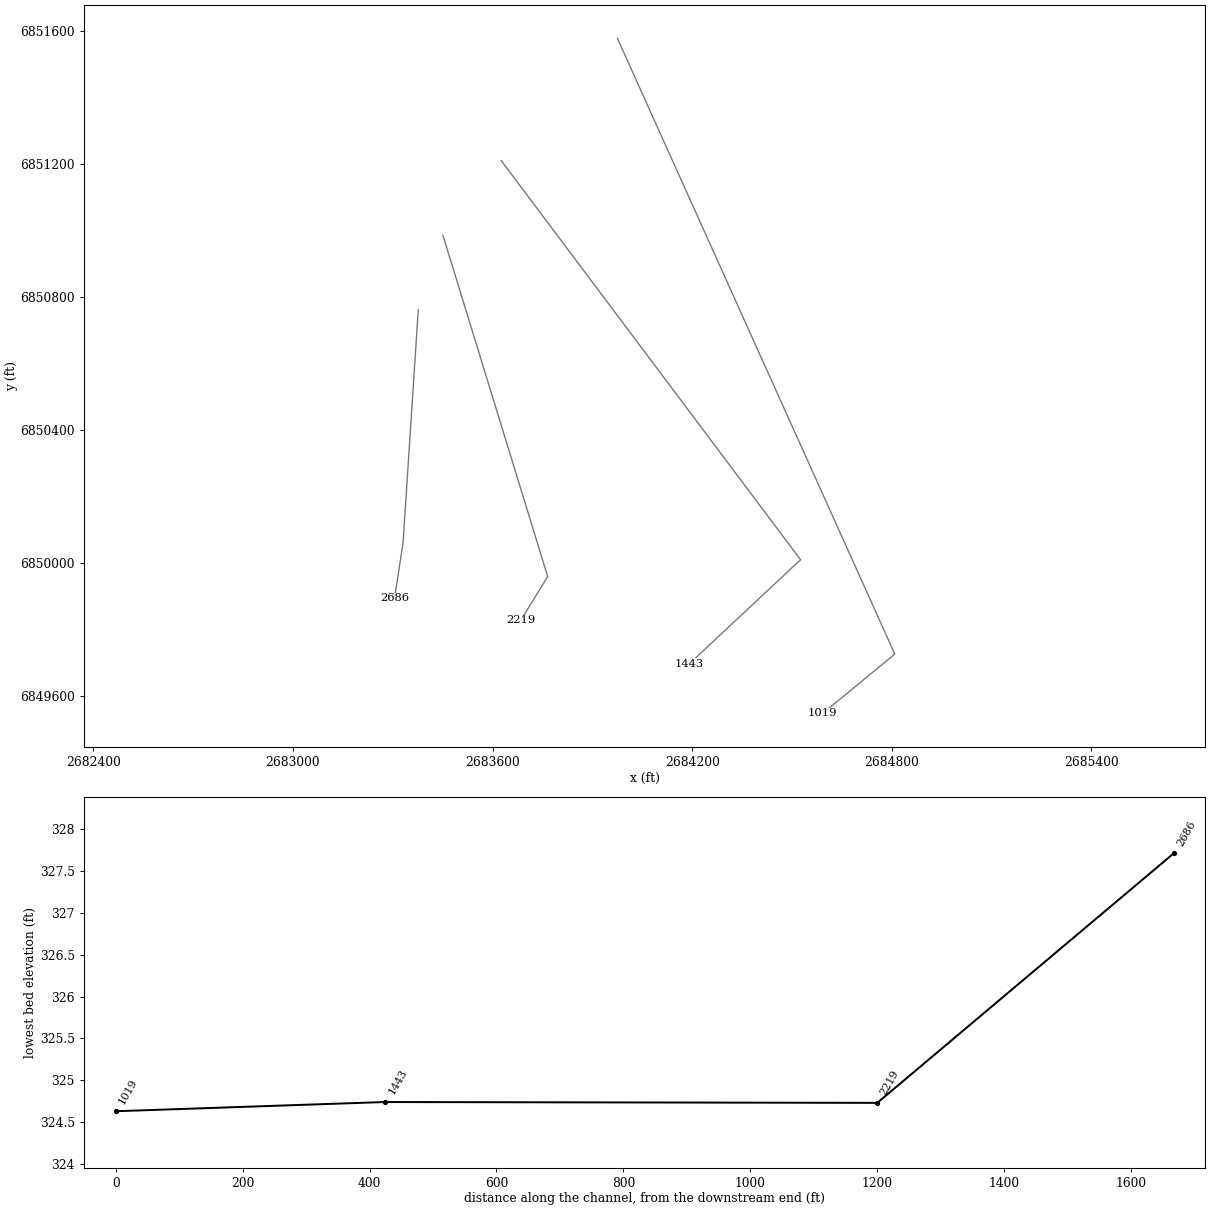
HEC-RAS study CCT4.prj: CCT4 Base Level Engineering

--- CCT4.g01 (geometry) --- (continued)

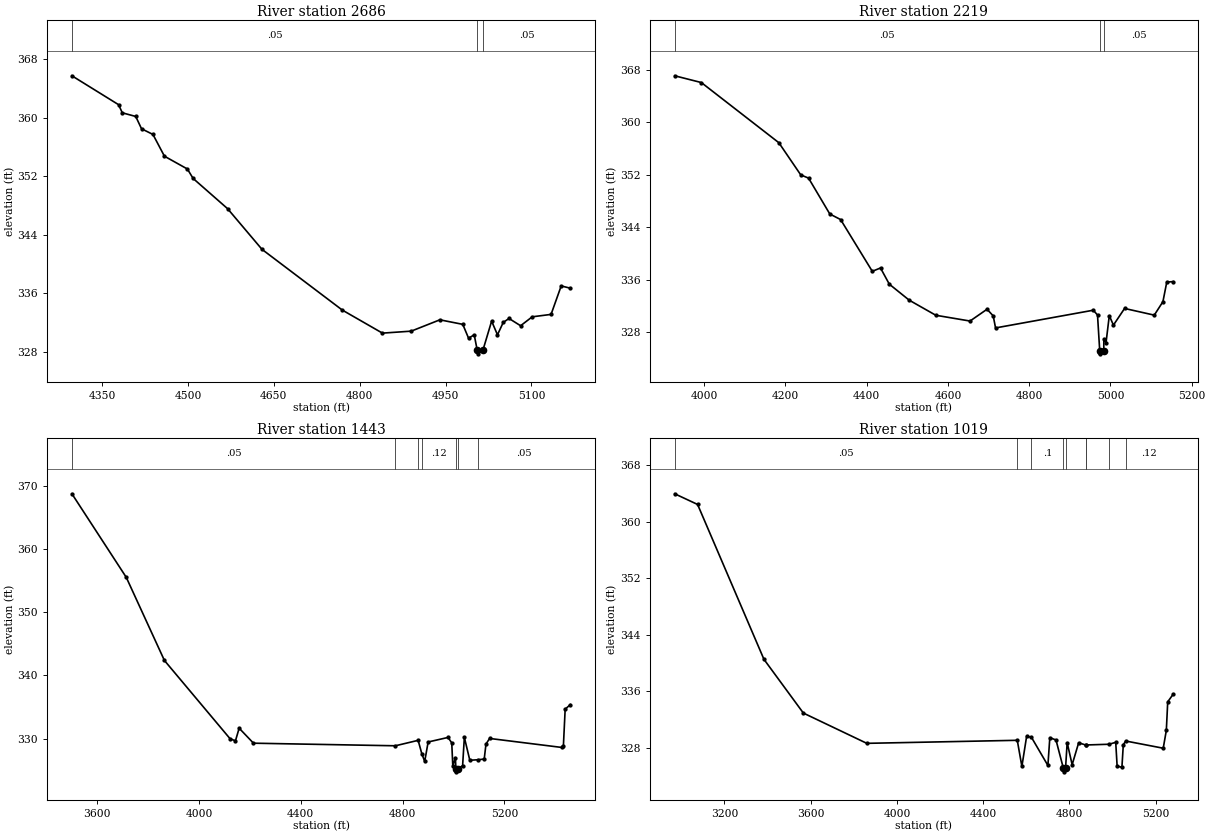
Type RM Length L Ch R = 1 ,2686    ,467,467,467
BEGIN DESCRIPTION:
CCT4 4.0
END DESCRIPTION:
XS GIS Cut Line= 3
      2683376.84      6850762.29      2683331.04      6850061.09
      2683305.51      6849895.14
#Sta/Elev= 30
  4297.3  365.71  4378.8  361.76  4385.3  360.65  4408.8  360.15  4418.9  358.47
  4438.9  357.69  4458.9  354.72    4499  352.97    4509  351.68  4569.2  347.55
  4629.3  341.99  4769.6  333.69  4839.7  330.54  4889.9  330.81    4940  332.36
    4980  331.74  4990.1  329.85    5000  330.31  5005.2  328.21  5006.6  327.71
  5015.2  328.21  5030.4  332.18  5040.6  330.31  5050.7  332.01  5060.8  332.54
    5081  331.55  5101.3  332.77  5134.2   333.1  5151.9  336.99  5167.9  336.68
#Mann= 3 ,-1 , 0
  4297.3     .05       0  5005.2     .03       0  5015.2     .05       0
Bank Sta=5005.2,5015.2
XS Rating Curve= 0 ,0
Exp/Cntr=0.3,0.1

Type RM Length L Ch R = 1 ,2219    ,776,776,776
BEGIN DESCRIPTION:
CCT4 3.0
END DESCRIPTION:
XS GIS Cut Line= 3
        2683451.      6850986.01      2683765.81      6849960.55
      2683684.98      6849829.12
#Sta/Elev= 30
  3927.3  367.12  3992.8  366.09  4183.6  356.92  4237.6  352.01  4256.8  351.52
  4309.1  346.05  4335.7   345.2  4413.7  337.31  4433.9  337.82  4455.6  335.35
  4504.6  332.91  4570.1  330.61  4654.3  329.73  4696.2  331.53  4711.4  330.51
  4717.1  328.68  4957.7  331.38  4968.1  330.65  4973.5  325.23  4974.9  324.73
  4983.5  325.23  4983.7  326.95  4989.1  326.45  4997.1  330.55  5007.3  329.11
  5034.7  331.65  5107.8  330.63  5129.1  332.68  5138.6  335.67  5154.3  335.74
#Mann= 3 ,-1 , 0
  3927.3     .05       0  4973.5     .04       0  4983.5     .05       0
Bank Sta=4973.5,4983.5
XS Rating Curve= 0 ,0
Exp/Cntr=0.3,0.1

Type RM Length L Ch R = 1 ,1443    ,424,424,424
BEGIN DESCRIPTION:
CCT4 2.0
END DESCRIPTION:
XS GIS Cut Line= 3
      2683625.97      6851211.03        2684526.        6850011.
      2684190.94      6849697.49
#Sta/Elev= 30
  3500.5  368.71  3714.1   355.5  3864.1  342.35  4122.4  329.96  4143.3  329.65
  4157.8  331.64  4214.1  329.27  4771.7  328.86  4861.2  329.72  4875.7  327.59
    4887  326.39  4900.5  329.46  4978.7  330.18  4993.3  329.32  4997.4  325.64
  5007.6  326.99  5009.5  325.24  5010.9  324.74  5019.5  325.24    5036  325.73
  5042.8  330.19  5064.3  326.57  5095.2  326.65  5120.9  326.76  5127.8  329.13
    5142  330.02  5425.1   328.6  5432.1  328.88    5439  334.65  5459.4  335.37
#Mann= 7 ,-1 , 0
  3500.5     .05       0  4771.7     .12       0  4861.2     .05       0
  4875.7     .12       0  5009.5     .07       0  5019.5     .12       0
  5095.2     .05       0
Bank Sta=5009.5,5019.5
XS Rating Curve= 0 ,0
Exp/Cntr=0.3,0.1

Type RM Length L Ch R = 1 ,1019    ,0,0,0
BEGIN DESCRIPTION:
CCT4 1.0
END DESCRIPTION:
XS GIS Cut Line= 3
      2683975.37      6851578.23      2684809.21      6849727.39
      2684592.65      6849549.12
#Sta/Elev= 30
    2970  363.95  3076.1  362.44  3383.7  340.54  3566.4  332.94  3860.5  328.66
    4558  329.09  4579.3  325.39  4601.2  329.63  4623.1  329.54  4699.9  325.53
  4708.8  329.46  4737.4  329.14  4771.6  325.13    4773  324.63  4781.7  325.13
  4789.2  328.76  4812.3  325.64  4842.5  328.74  4876.7  328.41  4877.6  328.43
  4982.9  328.53  5014.3   328.8  5020.8  325.43    5043  325.28  5049.4  328.46
  5060.5  328.99  5234.5  327.97  5248.9   330.5  5255.3  334.53  5280.5   335.6
#Mann= 9 ,-1 , 0
    2970     .05       0    4558     .12       0  4623.1      .1       0
  4771.6     .03       0  4781.7      .1       0  4876.7     .05       0
  4877.6     .12       0  4982.9     .05       0  5060.5     .12       0
Bank Sta=4771.6,4781.7
XS Rating Curve= 0 ,0
Exp/Cntr=0.3,0.1

Chan Stop Cuts=-1
Use User Specified Reach Order=0
Composite Channel Slope=5