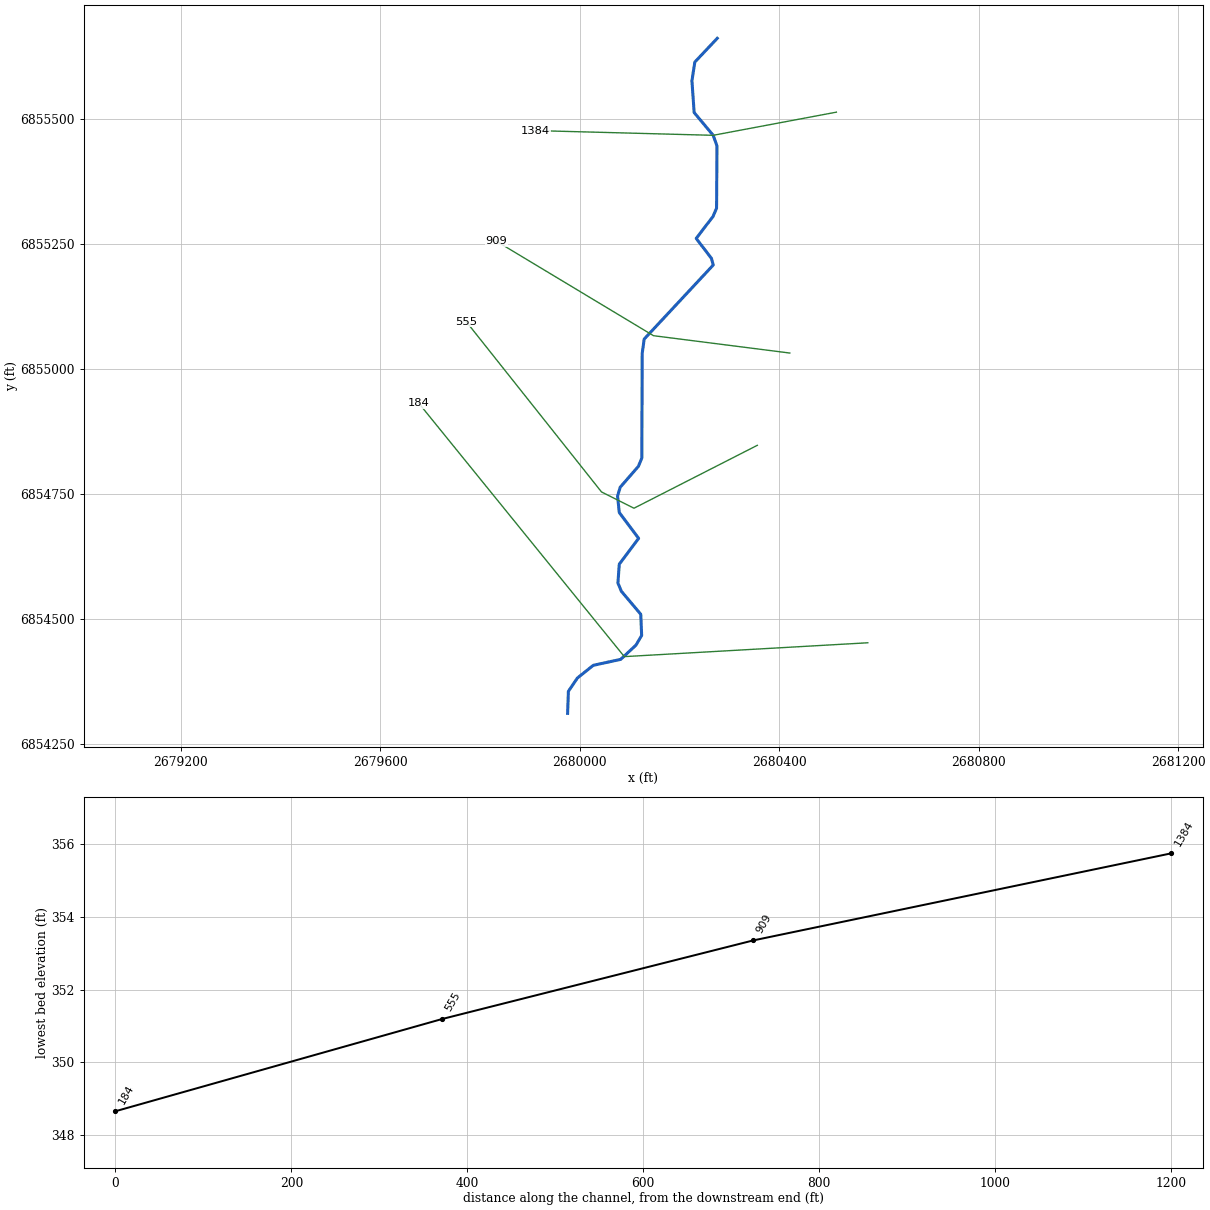
--- CCT4_2.prj (project) ---

Proj Title=CCT4_2 Base Level Engineering
Current Plan=p01
Default Exp/Contr=0.3,0.1
English Units
Geom File=g01
Flow File=f01
Plan File=p01
BEGIN DESCRIPTION:
CCT4_2
END DESCRIPTION:

--- CCT4_2.p01 (plan) ---

Plan Title=Multiple Run
Short Identifier=Multiple
Geom File=g01
Flow File=f01
Subcritical Flow
K Sum by GR= 0
Std Step Tol= 0.01
Critical Tol= 0.01
Num of Std Step Trials= 20
Max Error Tol= 0.3
Flow Tol Ratio= 0.001
Split Flow NTrial= 30
Split Flow Tol= 0.02
Split Flow Ratio= 0.02
Log Output Level= 0
Friction Slope Method= 1
Unsteady Friction Slope Method= 2
Unsteady Bridges Friction Slope Method= 1
Parabolic Critical Depth
Global Vel Dist=  1 , 1 , 1
Global Log Level= 0
CheckData=True
Encroach Param= -1, 0, 0, 0
BEGIN DESCRIPTION:
Multiple Run
END DESCRIPTION:

--- CCT4_2.f01 (steady flow) ---

Flow Title=Multiple
Number of Profiles=7
Profile Names=10-year,25-year,50-year,1pct_min,100-year,1pct_plu,500-year
River Rch & RM= CCT4_2,Reach-1,1384
     261     334     391     228     454     906     612
Boundary for River Rch & Prof#=CCT4_2,Reach-1,1
Up Type=0
Dn Type=3
Dn Slope=0.005
Boundary for River Rch & Prof#=CCT4_2,Reach-1,2
Up Type=0
Dn Type=3
Dn Slope=0.005
Boundary for River Rch & Prof#=CCT4_2,Reach-1,3
Up Type=0
Dn Type=3
Dn Slope=0.005
Boundary for River Rch & Prof#=CCT4_2,Reach-1,4
Up Type=0
Dn Type=3
Dn Slope=0.005
Boundary for River Rch & Prof#=CCT4_2,Reach-1,5
Up Type=0
Dn Type=3
Dn Slope=0.005
Boundary for River Rch & Prof#=CCT4_2,Reach-1,6
Up Type=0
Dn Type=3
Dn Slope=0.005
Boundary for River Rch & Prof#=CCT4_2,Reach-1,7
Up Type=0
Dn Type=3
Dn Slope=0.005

--- CCT4_2.g01 (geometry) ---

Geom Title=Existing Conditions

River Reach=CCT4_2,Reach-1
Reach XY= 30
      2680276.00      6855661.00      2680231.05      6855613.55
      2680225.27      6855576.04      2680229.70      6855512.59
      2680267.86      6855467.06      2680275.49      6855445.78
      2680274.64      6855321.44      2680267.57      6855304.81
      2680233.81      6855260.90      2680264.32      6855220.99
      2680268.01      6855207.66      2680129.54      6855059.54
      2680125.57      6855031.18      2680124.76      6854821.50
      2680117.81      6854804.92      2680081.40      6854763.17
      2680076.15      6854745.58      2680079.60      6854712.64
      2680118.38      6854661.00      2680079.61      6854609.36
      2680076.84      6854571.70      2680083.88      6854555.07
      2680122.64      6854509.24      2680124.45      6854466.85
      2680113.02      6854447.43      2680082.42      6854419.03
      2680027.50      6854407.13      2679995.56      6854381.63
      2679977.56      6854355.13      2679976.00      6854311.00

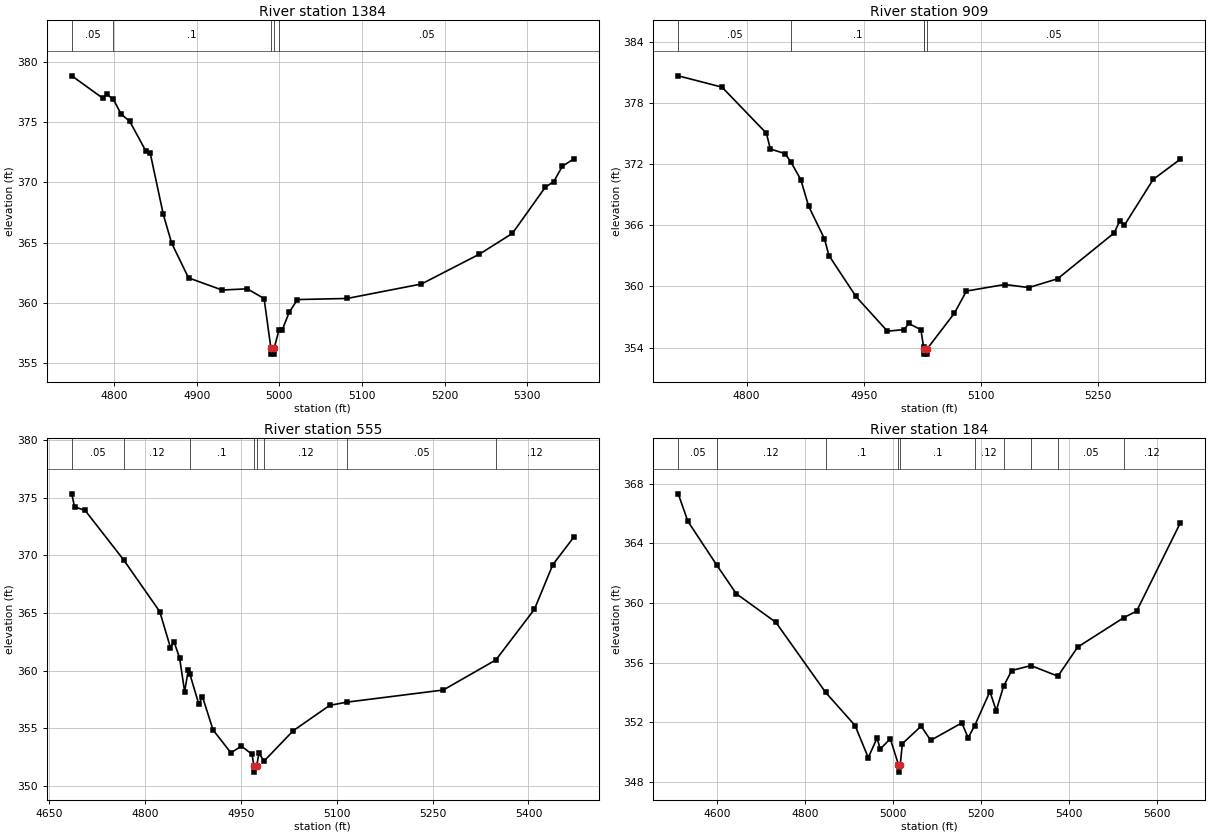
Type RM Length L Ch R = 1,1384,475,475,475
BEGIN DESCRIPTION:
CCT4_2 3.0
END DESCRIPTION:
XS GIS Cut Line= 3
      2680514.86      6855513.37      2680267.86      6855467.06
      2679911.59      6855476.49
#Sta/Elev= 30
  4748.7  378.84  4785.9  377.00  4791.0  377.30  4798.9  376.90  4808.6  375.65
  4818.8  375.07  4838.5  372.58  4843.6  372.44  4859.5  367.33  4869.6  364.95
  4890.0  362.07  4930.7  361.06  4961.2  361.16  4981.5  360.35  4989.7  356.24
  4990.0  355.74  4993.5  355.74  4993.7  356.24  4999.5  357.74  5003.4  357.74
  5011.9  359.22  5021.9  360.27  5081.9  360.36  5171.9  361.56  5241.9  364.03
  5282.0  365.76  5322.0  369.61  5332.0  370.05  5342.5  371.33  5356.4  371.95
#Mann=5,-1,0
  4748.7    0.05       0  4798.9     0.1       0  4989.7    0.05       0
  4993.7     0.1       0  4999.5    0.05       0
Bank Sta=4989.7,4993.7
Exp/Cntr=0.3,0.1

Type RM Length L Ch R = 1,909,354,354,354
BEGIN DESCRIPTION:
Mapping XS 6c73d4b9
END DESCRIPTION:
XS GIS Cut Line= 3
      2680421.56      6855031.61      2680148.13      6855066.33
      2679833.45      6855255.13
#Sta/Elev= 30
  4712.4  380.65  4768.4  379.54  4825.2  375.02  4830.3  373.47  4849.1  373.02
  4856.7  372.18  4869.2  370.48  4879.3  367.86  4899.5  364.67  4905.3  363.02
  4939.8  359.01  4980.1  355.60  5001.6  355.76  5007.4  356.36  5023.0  355.74
  5026.4  354.05  5026.8  353.85  5027.0  353.35  5030.5  353.35  5030.8  353.85
  5065.7  357.35  5081.3  359.54  5130.5  360.18  5161.0  359.88  5197.9  360.74
  5270.4  365.24  5277.6  366.44  5283.4  365.99  5320.3  370.49  5355.0  372.47
#Mann=5,-1,0
  4712.4    0.05       0  4856.7     0.1       0  5026.4    0.05       0
  5026.8    0.07       0  5030.8    0.05       0
Bank Sta=5026.8,5030.8
Exp/Cntr=0.3,0.1

Type RM Length L Ch R = 1,555,371,371,371
BEGIN DESCRIPTION:
Mapping XS 33fbd018
END DESCRIPTION:
XS GIS Cut Line= 4
      2680356.42      6854847.13      2680109.07      6854721.28
      2680043.96      6854753.83      2679772.71      6855094.52
#Sta/Elev= 30
  4685.2  375.32  4689.5  374.19  4706.1  373.88  4766.3  369.60  4823.0  365.10
  4839.6  361.99  4845.2  362.49  4854.0  361.09  4861.8  358.17  4867.5  360.02
  4870.0  359.70  4884.1  357.07  4889.7  357.74  4906.3  354.85  4934.2  352.87
  4950.8  353.44  4967.2  352.74  4970.5  351.69  4970.8  351.19  4974.5  351.69
  4978.1  352.83  4986.2  352.15  5031.6  354.77  5088.9  356.98  5116.1  357.26
  5266.7  358.31  5349.0  360.92  5409.3  365.31  5438.1  369.18  5471.0  371.57
#Mann=8,-1,0
  4685.2    0.05       0  4766.3    0.12       0  4870.0     0.1       0
  4970.5    0.07       0  4974.5     0.1       0  4986.2    0.12       0
  5116.1    0.05       0  5349.0    0.12       0
Bank Sta=4970.5,4974.5
Exp/Cntr=0.3,0.1

Type RM Length L Ch R = 1,184,0,0,0
BEGIN DESCRIPTION:
CCT4_2 1.0
END DESCRIPTION:
XS GIS Cut Line= 3
      2680577.82      6854452.18      2680089.70      6854424.48
      2679677.23      6854931.75
#Sta/Elev= 30
  4511.1  367.31  4533.0  365.47  4598.2  362.56  4643.1  360.62  4733.3  358.70
  4846.4  354.01  4913.6  351.78  4943.6  349.63  4963.6  350.94  4970.9  350.20
  4993.7  350.90  5012.3  349.16  5012.6  348.66  5016.3  349.16  5021.3  350.57
  5063.9  351.74  5085.7  350.79  5156.5  351.96  5170.9  350.96  5185.8  351.77
  5220.5  354.06  5234.8  352.78  5251.4  354.40  5270.0  355.47  5314.0  355.80
  5375.2  355.09  5420.2  357.04  5525.6  359.02  5554.4  359.45  5653.8  365.36
#Mann=10,-1,0
  4511.1    0.05       0  4598.2    0.12       0  4846.4     0.1       0
  5012.3    0.07       0  5016.3     0.1       0  5185.8    0.12       0
  5251.4     0.1       0  5314.0    0.12       0  5375.2    0.05       0
  5525.6    0.12       0
Bank Sta=5012.3,5016.3
Exp/Cntr=0.3,0.1

Chan Stop Cuts=-1