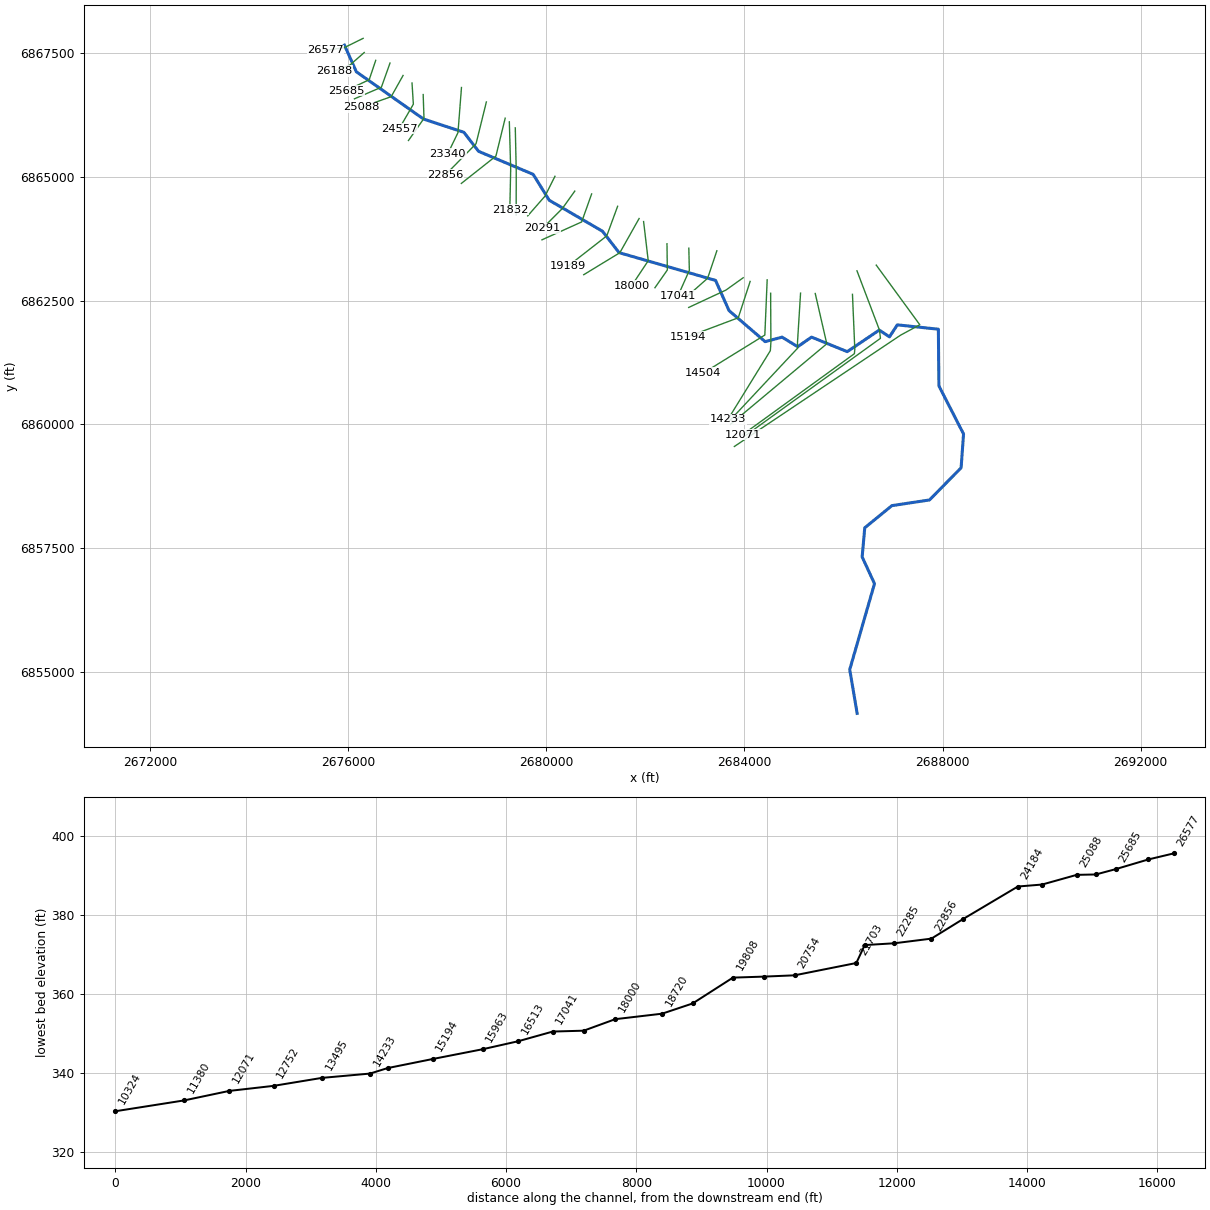
--- CCT5.prj (project) ---

Proj Title=CCT5 Base Level Engineering
Current Plan=p01
Default Exp/Contr=0.3,0.1
English Units
Geom File=g01
Flow File=f01
Plan File=p01
Y Axis Title=Elevation
X Axis Title(PF)=Main Channel Distance
X Axis Title(XS)=Station
BEGIN DESCRIPTION:
CCT5
END DESCRIPTION:
DSS Export Rating Curves= 0
DSS Export Rating Curve Sorted= 0
DSS Export Volume Flow Curves= 0
DXF OffsetX= 0
DXF OffsetY= 0
DXF ScaleX= 1
DXF ScaleY= 10

--- CCT5.p01 (plan) ---

Plan Title=Multiple Run
Short Identifier=Multiple
Geom File=g01
Flow File=f01
Subcritical Flow
K Sum by GR= 0
Std Step Tol= 0.01
Critical Tol= 0.01
Num of Std Step Trials= 20
Max Error Tol= 0.3
Flow Tol Ratio= 0.001
Split Flow NTrial= 30
Split Flow Tol= 0.02
Split Flow Ratio= 0.02
Log Output Level= 0
Friction Slope Method= 1
Unsteady Friction Slope Method= 2
Unsteady Bridges Friction Slope Method= 1
Parabolic Critical Depth
Global Vel Dist=  1 , 1 , 1
Global Log Level= 0
CheckData=True
Encroach Param= -1, 0, 0, 0
BEGIN DESCRIPTION:
Multiple Run
END DESCRIPTION:

--- CCT5.f01 (steady flow) ---

Flow Title=Multiple
Program Version=4.10
Number of Profiles= 7
Profile Names=10-year,25-year,50-year,1pct_min,100-year,1pct_plu,500-year
River Rch & RM=CCT5,Reach-1         ,26577
     451     596     711     421     840    1676    1173
River Rch & RM=CCT5,Reach-1         ,25685
     858    1179    1444     876    1748    3489    2565
River Rch & RM=CCT5,Reach-1         ,23340
     992    1373    1690    1030    2056    4102    3044
River Rch & RM=CCT5,Reach-1         ,20754
    1239    1733    2149    1318    2630    5247    3943
River Rch & RM=CCT5,Reach-1         ,17516
    1413    1981    2458    1508    3009    6004    4514
Boundary for River Rch & Prof#=CCT5,Reach-1         , 1
Up Type= 0
Dn Type= 3
Dn Slope=0.00252
Boundary for River Rch & Prof#=CCT5,Reach-1         , 2
Up Type= 0
Dn Type= 3
Dn Slope=0.00252
Boundary for River Rch & Prof#=CCT5,Reach-1         , 3
Up Type= 0
Dn Type= 3
Dn Slope=0.00252
Boundary for River Rch & Prof#=CCT5,Reach-1         , 4
Up Type= 0
Dn Type= 3
Dn Slope=0.00252
Boundary for River Rch & Prof#=CCT5,Reach-1         , 5
Up Type= 0
Dn Type= 3
Dn Slope=0.00252
Boundary for River Rch & Prof#=CCT5,Reach-1         , 6
Up Type= 0
Dn Type= 3
Dn Slope=0.00252
Boundary for River Rch & Prof#=CCT5,Reach-1         , 7
Up Type= 0
Dn Type= 3
Dn Slope=0.00252
DSS Import GetInterval= 0
DSS Import GetPeak= 0
DSS Import FillOption= 0

--- CCT5.g01 (geometry) ---

Geom Title=Existing Conditions
Program Version=4.10

River Reach=CCT5            ,Reach-1
Reach XY= 30
        2675926.        6867661.      2676166.32      6867121.78
      2677523.55      6866166.46      2678336.05      6865899.89
      2678634.48      6865514.46      2679736.02      6865049.77
      2680059.24      6864527.45      2681135.68      6863900.24
      2681469.63      6863468.37      2683417.52      6862907.54
      2683689.61      6862297.76      2684419.05      6861670.19
      2684759.96      6861760.83      2685075.91      6861568.31
      2685355.63      6861761.37       2686075.7      6861468.26
      2686722.43      6861903.52       2686928.3       6861766.6
      2687087.53       6862009.5      2687915.68      6861921.18
      2687926.49      6860776.49      2688423.94      6859805.15
       2688374.8       6859121.5      2687736.08      6858472.09
      2686977.46      6858357.48      2686429.53      6857909.55
      2686377.06      6857321.44      2686626.28      6856781.18
      2686126.51      6855045.79        2686276.        6854161.

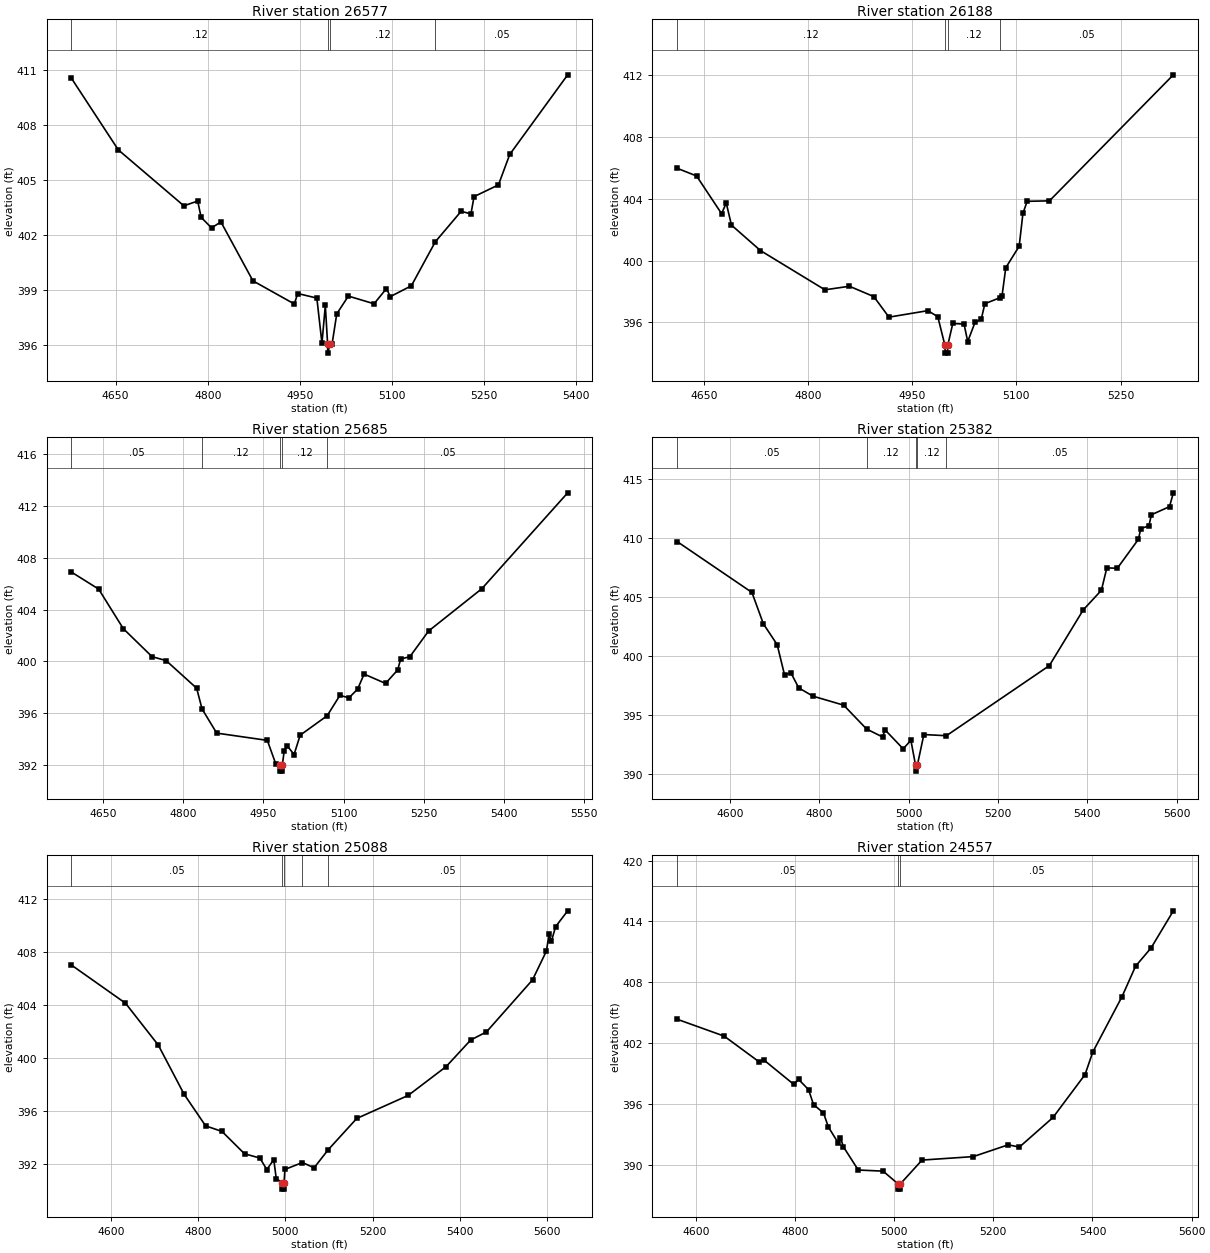
Type RM Length L Ch R = 1 ,26577   ,389,389,389
BEGIN DESCRIPTION:
CCT5 41.0
END DESCRIPTION:
XS GIS Cut Line= 3
      2676304.16      6867797.32        2675926.        6867611.
      2675544.59       6867552.1
#Sta/Elev= 30
  4578.3  410.52  4654.5  406.62  4761.2  403.57  4783.7  403.83  4789.3  402.94
  4806.2  402.37  4821.5  402.69  4873.6  399.48  4940.9  398.22  4946.5  398.79
  4977.6  398.54  4985.9  396.08  4991.4  398.14  4995.1  396.04  4995.3  395.54
  4999.1  396.04  5002.4  396.04    5010  397.68  5028.9  398.65  5070.7  398.23
  5090.9  399.06  5097.1  398.62  5131.4  399.21  5170.4  401.61  5212.4  403.27
  5228.4  403.13  5233.4  404.07  5273.1  404.71  5291.5  406.37  5385.8  410.71
#Mann= 4 ,-1 , 0
  4578.3     .12       0  4995.1     .07       0  4999.1     .12       0
  5170.4     .05       0
Bank Sta=4995.1,4999.1
XS Rating Curve= 0 ,0
Exp/Cntr=0.3,0.1

Type RM Length L Ch R = 1 ,26188   ,503,503,503
BEGIN DESCRIPTION:
CCT5 40.0
END DESCRIPTION:
XS GIS Cut Line= 3
      2676325.96      6867510.97      2676033.86      6867254.83
      2675729.42      6867138.24
#Sta/Elev= 30
  4611.5  405.98  4639.5  405.48  4675.5  403.04  4682.2  403.73  4689.7   402.3
  4731.5  400.65  4824.3  398.11  4859.6  398.34  4894.7  397.67  4916.5  396.34
  4972.5  396.76  4986.8  396.37  4997.1  394.51  4997.4  394.01  5000.9  394.01
  5001.1  394.51  5008.4  395.93  5024.6  395.89  5029.9  394.76  5040.5  396.01
  5049.3  396.19  5054.6  397.21  5075.9  397.59  5079.3  397.71  5084.7  399.54
    5104  400.93  5109.4  403.06  5115.5  403.84  5147.6  403.87    5326  412.03
#Mann= 4 ,-1 , 0
  4611.5     .12       0  4997.1     .07       0  5001.1     .12       0
  5075.9     .05       0
Bank Sta=4997.1,5001.1
XS Rating Curve= 0 ,0
Exp/Cntr=0.3,0.1

Type RM Length L Ch R = 1 ,25685   ,303,303,303
BEGIN DESCRIPTION:
CCT5 39.0
END DESCRIPTION:
XS GIS Cut Line= 3
      2676557.64      6867352.84        2676426.        6866961.
      2675960.76      6866741.93
#Sta/Elev= 30
  4591.2  406.89    4642  405.58  4688.1  402.53  4741.9  400.37  4768.1  400.07
  4825.2  397.94  4835.3  396.34  4862.7  394.48  4957.3  393.92  4972.9  392.13
  4981.5  392.05  4981.7  391.55  4985.2  391.55  4985.5  392.05  4988.8   393.1
  4994.1  393.52  5007.3  392.83  5018.7  394.32  5069.2  395.82    5093  397.39
  5109.9   397.2  5126.1  397.87  5138.2  399.03  5178.3  398.31    5201  399.35
  5206.6  400.19  5223.8  400.37  5258.8  402.35  5358.3  405.61  5518.8     413
#Mann= 5 ,-1 , 0
  4591.2     .05       0  4835.3     .12       0  4981.5     .07       0
  4985.5     .12       0  5069.2     .05       0
Bank Sta=4981.5,4985.5
XS Rating Curve= 0 ,0
Exp/Cntr=0.3,0.1

Type RM Length L Ch R = 1 ,25382   ,294,294,294
BEGIN DESCRIPTION:
CCT5 38.0
END DESCRIPTION:
XS GIS Cut Line= 3
      2676845.84      6867297.32       2676672.1      6866809.54
      2676128.09      6866575.54
#Sta/Elev= 30
  4482.2  409.66  4649.5  405.35  4675.1  402.69  4705.9  400.93  4722.4  398.37
  4736.7  398.53  4754.3  397.26  4786.1  396.56  4854.7   395.8  4905.9  393.78
  4941.9   393.1  4947.2  393.71  4987.8   392.1  5005.1  392.82  5015.5  390.71
  5015.8  390.21  5019.5  390.71  5034.1  393.31  5084.5  393.21  5314.8  399.15
  5390.8  403.88  5431.2  405.53  5443.4  407.43  5466.9   407.4    5514  409.85
  5519.4  410.76  5537.5  410.99    5543  411.93  5583.6  412.62  5592.2  413.79
#Mann= 5 ,-1 , 0
  4482.2     .05       0  4905.9     .12       0  5015.5     .07       0
  5019.5     .12       0  5084.5     .05       0
Bank Sta=5015.5,5019.5
XS Rating Curve= 0 ,0
Exp/Cntr=0.3,0.1

Type RM Length L Ch R = 1 ,25088   ,531,531,531
BEGIN DESCRIPTION:
CCT5 37.0
END DESCRIPTION:
XS GIS Cut Line= 3
      2677109.73      6867047.31      2676869.96      6866619.18
      2676260.02      6866401.85
#Sta/Elev= 30
  4509.3  407.04  4633.2  404.16  4708.5  400.99  4767.8  397.27    4817  394.89
  4854.6  394.47  4906.2  392.78  4941.4  392.46  4957.4  391.59  4973.3  392.34
  4979.1  390.89    4993  390.61  4993.3  390.11  4996.8  390.11    4997  390.61
  4998.9   391.6  5039.1  392.12  5065.8  391.72    5098  393.08  5163.6  395.45
  5281.6  397.19  5368.7  399.37  5425.1  401.38  5461.2  401.99  5566.8  405.92
  5598.7   408.1  5604.7  409.36    5610  408.83  5619.9  409.95  5647.5  411.14
#Mann= 5 ,-1 , 0
  4509.3     .05       0    4993     .04       0    4997     .05       0
  5039.1     .12       0    5098     .05       0
Bank Sta=4993,4997
XS Rating Curve= 0 ,0
Exp/Cntr=0.3,0.1

Type RM Length L Ch R = 1 ,24557   ,373,373,373
BEGIN DESCRIPTION:
Mapping XS 4962b97b
END DESCRIPTION:
XS GIS Cut Line= 3
      2677290.34      6866895.57      2677317.35      6866466.65
      2677031.69      6865972.08
#Sta/Elev= 30
  4562.2  404.38    4657  402.72  4726.9  400.21  4737.1  400.37  4797.2  397.98
  4807.3  398.45  4827.3  397.45  4837.3  395.98  4857.3  395.16  4867.4  393.76
  4886.7  392.24  4891.7  392.72  4897.4  391.84  4927.5  389.54  4977.6  389.43
  5008.2  388.16  5008.5  387.66    5012  387.66  5012.2  388.16  5056.2  390.52
  5159.5  390.86  5229.9  392.02  5252.6   391.8  5320.3  394.71  5384.9  398.93
  5400.7  401.16  5459.6  406.61  5486.9   409.6  5518.2   411.4  5563.1  415.05
#Mann= 3 ,-1 , 0
  4562.2     .05       0  5008.2     .03       0  5012.2     .05       0
Bank Sta=5008.2,5012.2
XS Rating Curve= 0 ,0
Exp/Cntr=0.3,0.1

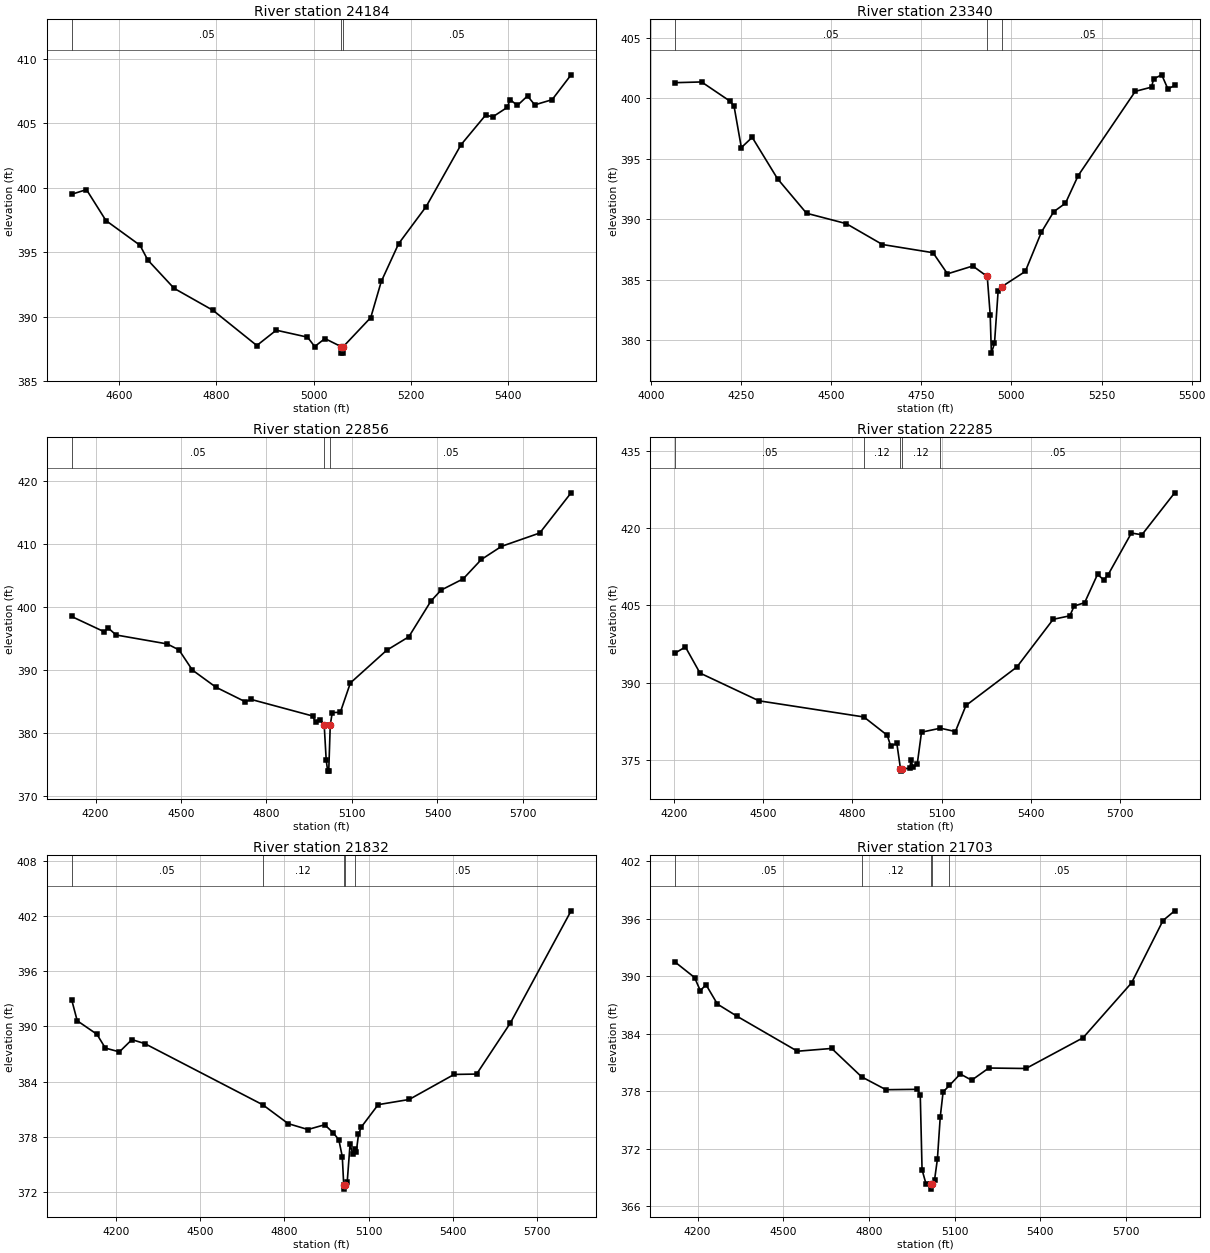
Type RM Length L Ch R = 1 ,24184   ,844,844,844
BEGIN DESCRIPTION:
Mapping XS e161c076
END DESCRIPTION:
XS GIS Cut Line= 3
      2677515.64      6866661.48      2677532.04      6866180.42
      2677218.88      6865733.69
#Sta/Elev= 30
  4502.3  399.49  4532.8  399.85  4572.8  397.45  4642.9  395.53  4658.8  394.39
  4712.9  392.19    4793  390.48    4883  387.75    4923  388.94  4987.2   388.4
  5002.1  387.67    5023  388.29  5056.7  387.66    5057  387.16  5060.5  387.16
  5060.7  387.66  5117.3  389.92  5138.9  392.72  5174.7  395.66  5231.3  398.54
  5302.8  403.33  5353.4  405.63  5368.2   405.5  5397.8  406.23  5403.9  406.84
  5418.7  406.38  5439.6  407.12  5454.5  406.43  5490.2  406.83  5529.2  408.76
#Mann= 3 ,-1 , 0
  4502.3     .05       0  5056.7     .03       0  5060.7     .05       0
Bank Sta=5056.7,5060.7
XS Rating Curve= 0 ,0
Exp/Cntr=0.3,0.1

Type RM Length L Ch R = 1 ,23340   ,484,484,484
BEGIN DESCRIPTION:
Mapping XS 515c2a65
END DESCRIPTION:
XS GIS Cut Line= 3
      2678288.78      6866803.83      2678218.17      6865893.14
      2678013.22      6865468.21
#Sta/Elev= 30
  4067.7  401.31  4140.8  401.37    4221  399.75    4231  399.34  4251.1  395.93
  4281.2  396.78  4351.4  393.35  4431.9  390.49    4542  389.63  4642.3   387.9
  4782.7  387.22  4822.8  385.47    4893  386.12  4933.1  385.25  4941.3  382.07
  4944.5   378.9  4953.2  379.71  4963.2  384.03  4973.2   384.4  5038.6  385.67
  5083.4  388.93  5117.5  390.62    5150  391.32  5185.3  393.61  5343.6  400.59
  5388.8  400.94  5394.4  401.62    5417  401.96  5434.1  400.79  5452.9  401.08
#Mann= 3 ,-1 , 0
  4067.7     .05       0  4933.1     .03       0  4973.2     .05       0
Bank Sta=4933.1,4973.2
XS Rating Curve= 0 ,0
Exp/Cntr=0.3,0.1

Type RM Length L Ch R = 1 ,22856   ,571,571,571
BEGIN DESCRIPTION:
Mapping XS 5f5001fa
END DESCRIPTION:
XS GIS Cut Line= 3
      2678791.21      6866512.36      2678582.89      6865668.64
      2677963.08      6865038.42
#Sta/Elev= 30
  4116.1  398.49  4230.8  396.06  4244.2  396.68    4272  395.56  4451.5  394.14
  4492.9  393.19  4539.8     390  4622.5  387.28  4725.2  384.98  4746.9  385.33
  4962.1  382.71  4972.4  381.71  4988.4  382.15  5002.5  381.32  5009.6   375.7
  5014.8  373.97  5018.5  373.97  5023.8  381.27  5030.8  383.26  5059.1  383.29
  5094.4  387.95  5221.7  393.13  5299.5  395.27  5377.2  400.94  5412.7  402.67
  5490.4  404.46  5554.1  407.53  5624.8  409.61  5759.1  411.73  5869.1   418.1
#Mann= 3 ,-1 , 0
  4116.1     .05       0  5002.5     .03       0  5023.8     .05       0
Bank Sta=5002.5,5023.8
XS Rating Curve= 0 ,0
Exp/Cntr=0.3,0.1

Type RM Length L Ch R = 1 ,22285   ,453,453,453
BEGIN DESCRIPTION:
Mapping XS 21785c3b
END DESCRIPTION:
XS GIS Cut Line= 3
      2679171.42      6866184.24      2678983.93      6865418.64
      2678286.01      6864866.56
#Sta/Elev= 30
  4204.8  395.73    4239  396.91    4288  391.84  4486.1  386.45  4838.7  383.31
  4917.3  379.75  4928.8  377.63  4949.4  378.18  4961.6  373.29  4962.2  372.79
  4966.5  373.29    4993  373.32    4997  375.02  5003.4  373.51  5017.8  374.08
  5032.3  380.35  5095.6  381.13  5146.1  380.48  5181.6  385.54  5352.8  393.02
  5474.7  402.28  5530.7  402.96  5545.2  404.86  5580.4  405.51  5623.7  411.01
  5644.5  409.94    5659  410.91  5737.5  419.04  5772.8   418.7  5882.9  426.85
#Mann= 5 ,-1 , 0
  4204.8     .05       0  4838.7     .12       0  4961.6     .07       0
  4966.5     .12       0  5095.6     .05       0
Bank Sta=4961.6,4966.5
XS Rating Curve= 0 ,0
Exp/Cntr=0.3,0.1

Type RM Length L Ch R = 1 ,21832   ,129,129,129
BEGIN DESCRIPTION:
Mapping XS d0849d4c
END DESCRIPTION:
XS GIS Cut Line= 3
      2679255.01      6866110.84        2679282.      6865148.58
      2679264.66       6864335.1
#Sta/Elev= 30
  4043.5  392.91  4063.3  390.62  4133.4  389.15  4163.4  387.65  4213.4  387.24
  4257.8  388.57  4303.4  388.14  4723.6  381.49  4813.6  379.45  4883.7  378.81
  4943.7  379.33  4974.6  378.42  4993.7  377.71  5006.1  375.86  5011.1  372.84
  5011.8  372.34  5016.3  372.84  5023.7  373.16  5033.7  377.22  5043.7  376.12
  5051.2  376.71  5055.8  376.37  5063.7  378.28  5073.7  379.08  5133.7  381.51
  5243.8  382.07  5403.8  384.79  5483.8  384.83  5603.9  390.38  5819.8  402.55
#Mann= 5 ,-1 , 0
  4043.5     .05       0  4723.6     .12       0  5011.1     .07       0
  5016.3     .12       0  5051.2     .05       0
Bank Sta=5011.1,5016.3
XS Rating Curve= 0 ,0
Exp/Cntr=0.3,0.1

Type RM Length L Ch R = 1 ,21703   ,949,949,949
BEGIN DESCRIPTION:
Mapping XS 0aa53bd7
END DESCRIPTION:
XS GIS Cut Line= 3
      2679375.11      6865988.77      2679394.11      6865123.33
      2679392.94      6864240.18
#Sta/Elev= 30
  4121.6  391.45  4189.4  389.85  4209.4  388.48  4229.4   389.1  4269.4  387.08
  4339.4  385.79  4549.5  382.17  4669.5  382.46  4774.3   379.5  4859.5  378.16
  4969.6   378.2  4979.6  377.62  4985.9  369.82  4999.6  368.36  5016.9   368.3
  5017.7   367.8  5022.2   368.3  5029.6  368.75  5039.6  370.92  5049.6  375.33
  5059.6  377.93  5081.9  378.61  5119.6   379.8  5159.6  379.15  5219.6  380.42
  5349.6  380.37  5549.6  383.57  5719.6   389.3  5829.6  395.79  5870.4   396.8
#Mann= 5 ,-1 , 0
  4121.6     .05       0  4774.3     .12       0  5016.9     .07       0
  5022.2     .12       0  5081.9     .05       0
Bank Sta=5016.9,5022.2
XS Rating Curve= 0 ,0
Exp/Cntr=0.3,0.1

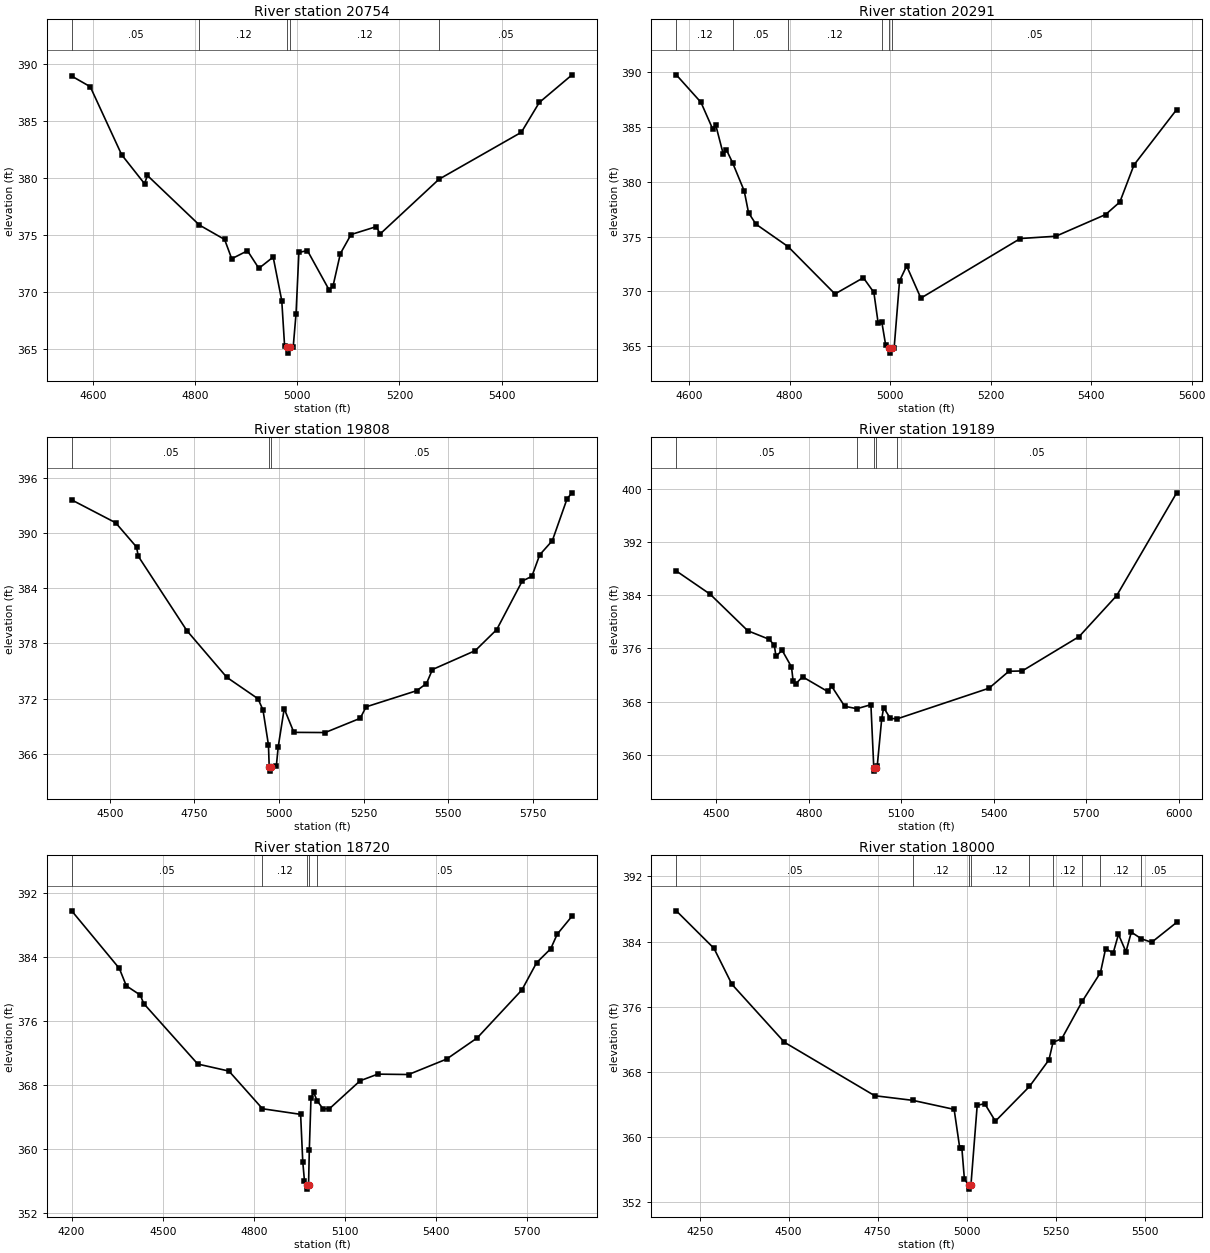
Type RM Length L Ch R = 1 ,20754   ,463,463,463
BEGIN DESCRIPTION:
CCT5 28.0
END DESCRIPTION:
XS GIS Cut Line= 3
      2680175.99      6865010.98        2679976.        6864611.
        2679626.        6864211.
#Sta/Elev= 30
  4558.9  388.93  4595.2     388  4656.7  382.04  4701.4  379.51    4707  380.23
  4808.7  375.89    4858  374.63  4871.9  372.94  4902.7  373.64    4925   372.1
    4953  373.09  4969.8  369.27  4975.3  365.33  4980.8  365.18  4981.7  364.68
  4986.6  365.18  4992.1  365.18  4997.7  368.12  5003.3  373.49  5019.9  373.66
  5062.6   370.2  5070.2  370.58  5084.4  373.39  5105.3  375.06  5154.6  375.75
  5162.2  375.11  5277.3   379.9  5438.4  384.01  5473.5  386.62  5537.6  389.04
#Mann= 5 ,-1 , 0
  4558.9     .05       0  4808.7     .12       0  4980.8     .07       0
  4986.6     .12       0  5277.3     .05       0
Bank Sta=4980.8,4986.6
XS Rating Curve= 0 ,0
Exp/Cntr=0.3,0.1

Type RM Length L Ch R = 1 ,20291   ,483,483,483
BEGIN DESCRIPTION:
CCT5 27.0
END DESCRIPTION:
XS GIS Cut Line= 3
        2680576.      6864710.99        2680326.        6864361.
        2679926.        6863961.
#Sta/Elev= 30
  4574.4  389.76  4623.5  387.25  4646.9  384.81    4653  385.16  4667.8  382.54
  4673.9  382.94  4686.4  381.74  4709.6  379.16  4718.2  377.17  4732.9  376.13
  4796.9  374.08  4890.2  369.76  4946.7  371.24  4967.6   369.9  4976.2  367.08
  4983.5  367.17    4991  365.12  4998.5  364.86  4999.4  364.36  5004.4  364.86
    5008  364.86  5018.7  370.95  5032.8  372.32  5061.1  369.38  5259.1  374.82
  5329.8  375.03  5428.8  377.01  5457.1  378.15  5485.3  381.54  5570.2  386.59
#Mann= 6 ,-1 , 0
  4574.4     .12       0  4686.4     .05       0  4796.9     .12       0
  4983.5     .05       0  4998.5     .03       0  5004.4     .05       0
Bank Sta=4998.5,5004.4
XS Rating Curve= 0 ,0
Exp/Cntr=0.3,0.1

Type RM Length L Ch R = 1 ,19808   ,619,619,619
BEGIN DESCRIPTION:
Mapping XS ce7e5d12
END DESCRIPTION:
XS GIS Cut Line= 3
      2680916.22      6864654.16      2680714.83       6864088.2
      2679912.79      6863727.11
#Sta/Elev= 30
  4386.7  393.63  4516.8  391.14  4578.5   388.5  4583.8  387.49  4727.4   379.4
  4845.4  374.32  4937.9  371.98  4952.6  370.76  4968.8  366.96    4971   364.6
    4972   364.1  4977.1   364.6  4992.2  364.69  4997.7  366.75  5015.4   370.9
    5044  368.32  5136.6   368.3  5240.1  369.85  5257.8   371.1  5407.6  372.86
  5436.3  373.64  5453.9  375.16  5580.6  377.22  5644.1  379.51  5719.5  384.79
  5748.1  385.31  5771.3  387.65  5808.6  389.19  5852.5  393.78    5867   394.4
#Mann= 3 ,-1 , 0
  4386.7     .05       0    4971     .04       0  4977.1     .05       0
Bank Sta=4971,4977.1
XS Rating Curve= 0 ,0
Exp/Cntr=0.3,0.1

Type RM Length L Ch R = 1 ,19189   ,469,469,469
BEGIN DESCRIPTION:
Mapping XS 9ddf55fb
END DESCRIPTION:
XS GIS Cut Line= 3
      2681440.54      6864404.22      2681221.77      6863806.95
      2680443.97       6863199.3
#Sta/Elev= 30
  4370.2  387.63    4480  384.14    4602  378.65  4671.8  377.36  4688.2  376.46
  4693.6   374.8  4713.4  375.72  4743.9  373.21  4749.3  371.05    4757  370.65
  4779.8  371.73  4860.7  369.54  4874.2  370.31  4916.4   367.3  4956.1  366.94
  5001.5  367.54  5010.8  358.06  5011.8  357.56    5017  358.06    5022  358.32
  5036.5   365.4  5042.8   367.1  5064.4  365.48    5087  365.42  5384.7  370.02
  5448.9  372.56  5492.3  372.61  5676.8  377.77  5798.9  383.94  5993.3  399.37
#Mann= 5 ,-1 , 0
  4370.2     .05       0  4956.1     .12       0  5010.8     .07       0
    5017     .12       0    5087     .05       0
Bank Sta=5010.8,5017
XS Rating Curve= 0 ,0
Exp/Cntr=0.3,0.1

Type RM Length L Ch R = 1 ,18720   ,720,720,720
BEGIN DESCRIPTION:
Mapping XS 7fae8849
END DESCRIPTION:
XS GIS Cut Line= 3
      2681874.57      6864157.68      2681485.66      6863466.68
      2680756.47      6863022.21
#Sta/Elev= 30
  4200.4  389.77  4357.2  382.57  4380.2  380.39  4426.1  379.24  4437.6  378.17
  4615.4  370.61    4718  369.73  4828.4  365.02  4953.9  364.32  4960.9  358.42
  4966.6  355.96  4973.5  355.47  4974.6  354.97    4980  355.47  4982.5  359.85
    4988  366.33  4996.7  367.08  5008.2  366.02  5027.6  365.01  5048.9  365.03
  5149.7  368.52  5207.8  369.35  5309.1   369.3  5434.3  371.23  5535.1  373.88
  5682.2  379.88  5730.7  383.29  5777.1  385.03  5798.4  386.85  5847.3  389.11
#Mann= 5 ,-1 , 0
  4200.4     .05       0  4828.4     .12       0  4973.5     .07       0
    4980     .12       0  5008.2     .05       0
Bank Sta=4973.5,4980
XS Rating Curve= 0 ,0
Exp/Cntr=0.3,0.1

Type RM Length L Ch R = 1 ,18000   ,484,484,484
BEGIN DESCRIPTION:
Mapping XS 38969948
END DESCRIPTION:
XS GIS Cut Line= 3
      2681965.05       6864096.2       2682058.8      6863304.57
      2681721.99      6862797.62
#Sta/Elev= 30
  4184.3  387.78  4290.2  383.17  4340.6  378.75  4488.3  371.62  4741.7  365.06
  4848.6  364.49  4964.9  363.38  4980.7  358.62  4986.6  358.62  4993.7  354.83
  5005.3  354.08  5006.3  353.58  5012.1  354.08  5029.7  363.88  5050.8  364.08
  5080.8  361.93  5176.6   366.2  5231.2  369.46  5242.7  371.62  5267.2  372.06
  5324.7  376.65    5376  380.19  5390.5  383.14  5411.6  382.58  5426.6  384.89
  5447.6  382.75  5462.7  385.16  5491.1  384.34  5519.8  383.91  5590.1  386.36
#Mann= 9 ,-1 , 0
  4184.3     .05       0  4848.6     .12       0  5005.3     .07       0
  5012.1     .12       0  5176.6     .05       0  5242.7     .12       0
  5324.7     .05       0    5376     .12       0  5491.1     .05       0
Bank Sta=5005.3,5012.1
XS Rating Curve= 0 ,0
Exp/Cntr=0.3,0.1

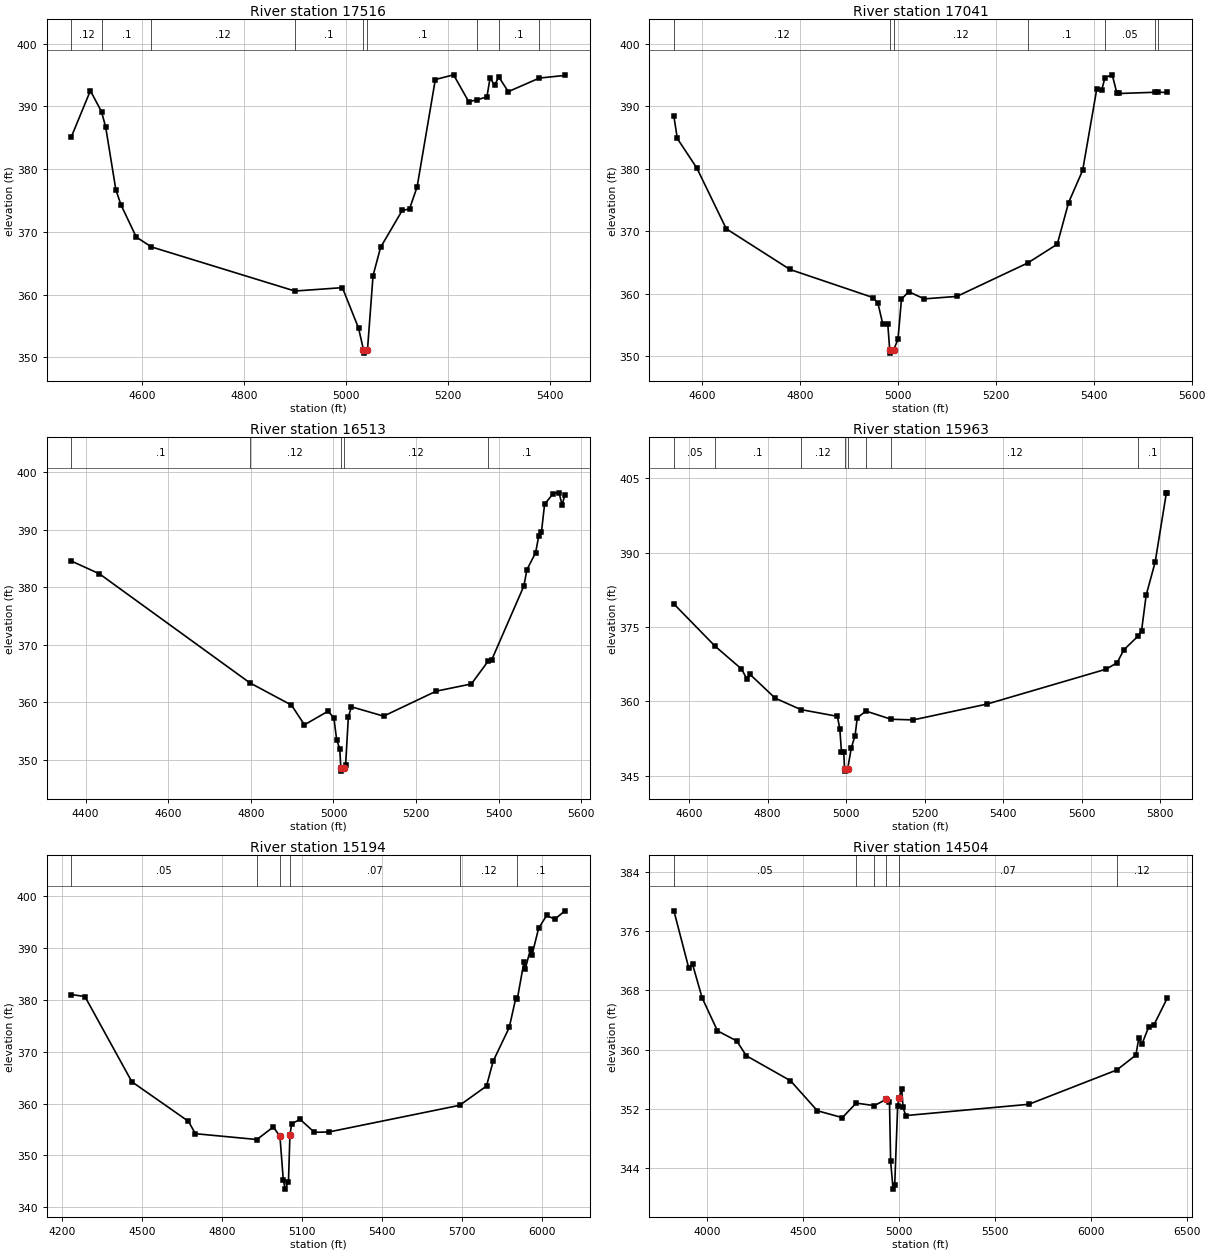
Type RM Length L Ch R = 1 ,17516   ,475,475,475
BEGIN DESCRIPTION:
Mapping XS 1a7ddf89
END DESCRIPTION:
XS GIS Cut Line= 3
      2682437.27       6863648.3      2682444.21      6863117.07
      2682194.23      6862759.46
#Sta/Elev= 30
  4462.1  385.15  4499.4  392.51  4521.3  389.15  4529.4  386.71  4549.4  376.69
  4559.4  374.31  4589.4  369.17  4619.2   367.6  4900.3  360.57  4993.4  361.11
  5025.2  354.64  5034.8  351.17  5035.9  350.67  5042.6  351.17  5053.5  363.02
  5068.3  367.53  5110.6  373.41    5125  373.66  5139.9  377.18  5175.6  394.29
  5211.4  395.04    5241  390.76  5257.9  391.06  5276.8  391.53  5282.9  394.55
  5291.6  393.39  5300.1  394.69  5318.6  392.36  5379.4  394.52  5429.7  394.95
#Mann= 9 ,-1 , 0
  4462.1     .12       0  4521.3      .1       0  4619.2     .12       0
  4900.3      .1       0  5034.8     .07       0  5042.6      .1       0
  5257.9     .05       0  5300.1      .1       0  5379.4     .05       0
Bank Sta=5034.8,5042.6
XS Rating Curve= 0 ,0
Exp/Cntr=0.3,0.1

Type RM Length L Ch R = 1 ,17041   ,528,528,528
BEGIN DESCRIPTION:
Mapping XS 9ff05639
END DESCRIPTION:
XS GIS Cut Line= 3
      2682878.24      6863557.99      2682888.66      6863110.12
      2682660.25      6862597.93
#Sta/Elev= 30
  4541.8  388.38  4548.8  384.84  4588.8  380.09  4648.8  370.38  4778.9  363.86
  4948.9  359.35  4958.9  358.41  4968.9  355.06  4978.9  355.15  4982.9  350.95
  4984.1  350.45  4990.8  350.95  4999.8  352.67  5006.9  359.09  5021.7   360.3
  5053.4  359.14  5120.2  359.54  5265.1   364.9  5325.3   367.9  5348.5  374.58
  5377.2  379.73  5405.9  392.69  5415.9  392.54  5422.9   394.6  5437.7  395.04
  5446.9  392.18  5452.4  392.05  5525.8  392.25  5531.3  392.26  5550.6  392.21
#Mann= 7 ,-1 , 0
  4541.8     .12       0  4982.9     .07       0  4990.8     .12       0
  5265.1      .1       0  5422.9     .05       0  5525.8     .12       0
  5531.3     .05       0
Bank Sta=4982.9,4990.8
XS Rating Curve= 0 ,0
Exp/Cntr=0.3,0.1

Type RM Length L Ch R = 1 ,16513   ,550,550,550
BEGIN DESCRIPTION:
Mapping XS 97a43413
END DESCRIPTION:
XS GIS Cut Line= 4
      2683444.22      6863505.98      2683281.02      6863019.84
      2683253.24      6862946.93      2682800.76      6862546.26
#Sta/Elev= 30
  4365.3  384.57  4433.4  382.34  4797.4  363.38  4898.3   359.5  4929.7  356.07
  4986.8  358.43    5001  357.29  5007.7  353.47  5015.2  351.89  5017.9  348.51
  5019.1  348.01  5025.9  348.51  5029.4   349.1  5036.1  357.48  5043.6   359.2
  5121.4  357.58  5248.5  361.92  5333.9  363.18  5375.2  367.21  5383.2  367.38
    5461  380.22  5468.5  383.08  5489.4  386.01    5497  388.92  5503.7  389.68
  5511.2  394.45  5532.1  396.32  5546.3  396.44  5553.5  394.36  5560.5  396.06
#Mann= 5 ,-1 , 0
  4365.3      .1       0  4797.4     .12       0  5017.9     .07       0
  5025.9     .12       0  5375.2      .1       0
Bank Sta=5017.9,5025.9
XS Rating Curve= 0 ,0
Exp/Cntr=0.3,0.1

Type RM Length L Ch R = 1 ,15963   ,769,769,769
BEGIN DESCRIPTION:
CCT5 17.0
END DESCRIPTION:
XS GIS Cut Line= 3
      2683976.04      6862961.03        2683626.        6862711.
      2682876.01        6862361.
#Sta/Elev= 30
  4561.3  379.65  4666.4  371.13  4733.4  366.57  4746.9  364.61  4755.5  365.45
  4819.4  360.67  4884.8  358.37  4977.9  357.01  4984.1  354.49  4988.4  349.73
  4994.2  349.73  4996.1  346.47  4997.3  345.97  5004.2  346.47  5013.5  350.69
    5023   353.1  5028.5  356.72  5050.7  358.07  5114.7  356.42  5171.2  356.29
  5359.6  359.49  5662.2   366.5  5690.6  367.79    5708  370.42    5744  373.16
  5752.9  374.18  5764.7   381.4  5787.6  388.07  5816.3  402.04  5819.1  402.04
#Mann= 8 ,-1 , 0
  4561.3     .05       0  4666.4      .1       0  4884.8     .12       0
  4996.1     .07       0  5004.2     .12       0  5050.7      .1       0
  5114.7     .12       0    5744      .1       0
Bank Sta=4996.1,5004.2
XS Rating Curve= 0 ,0
Exp/Cntr=0.3,0.1

Type RM Length L Ch R = 1 ,15194   ,690,690,690
BEGIN DESCRIPTION:
Mapping XS 18ce651b
END DESCRIPTION:
XS GIS Cut Line= 3
      2684116.02      6862886.81      2683876.42       6862152.4
        2682866.      6861772.19
#Sta/Elev= 30
  4233.9  381.02  4284.8  380.64  4460.9   364.2  4672.9  356.58  4699.5  354.18
  4930.2  353.06  4991.9  355.49  5016.6  353.66  5029.1  345.32  5036.1  343.49
  5048.6  344.94    5054  353.84  5060.3  356.08  5092.3  356.95  5145.8  354.45
  5199.7  354.51    5691  359.66  5791.7  363.37  5816.6  368.17    5877  374.67
  5901.9  380.42  5907.4   380.2  5932.1  387.28  5937.5  386.04    5957  389.84
  5962.4  388.68  5987.2   393.8  6017.5   396.3  6047.7  395.54    6086  397.17
#Mann= 6 ,-1 , 0
  4233.9     .05       0  4930.2     .12       0  5016.6     .05       0
    5054     .07       0    5691     .12       0  5907.4      .1       0
Bank Sta=5016.6,5054
XS Rating Curve= 0 ,0
Exp/Cntr=0.3,0.1

Type RM Length L Ch R = 1 ,14504   ,271,271,271
BEGIN DESCRIPTION:
Mapping XS c31795a5
END DESCRIPTION:
XS GIS Cut Line= 3
      2684459.75      6862918.01      2684412.88      6861803.44
      2683173.32      6861037.83
#Sta/Elev= 30
  3826.3  378.73  3903.4  371.06  3923.4  371.54  3973.4     367  4053.5  362.54
  4153.6  361.19  4203.6  359.19  4433.9  355.82    4574  351.77  4704.1  350.84
  4776.3   352.8    4871  352.46  4934.3  353.33  4949.9  352.97  4955.9  344.96
  4968.5   341.2  4977.2   341.8  4992.6  352.46  4998.5  353.43  5013.8  354.69
  5020.5  352.22  5035.1  351.12    5676  352.64  6134.8  357.27    6234  359.27
  6249.4  361.57  6264.8  360.71  6301.4   363.1  6328.6  363.37  6398.8  367.02
#Mann= 6 ,-1 , 0
  3826.3     .05       0  4776.3      .1       0    4871     .07       0
  4934.3     .05       0  4998.5     .07       0  6134.8     .12       0
Bank Sta=4934.3,4998.5
XS Rating Curve= 0 ,0
Exp/Cntr=0.3,0.1

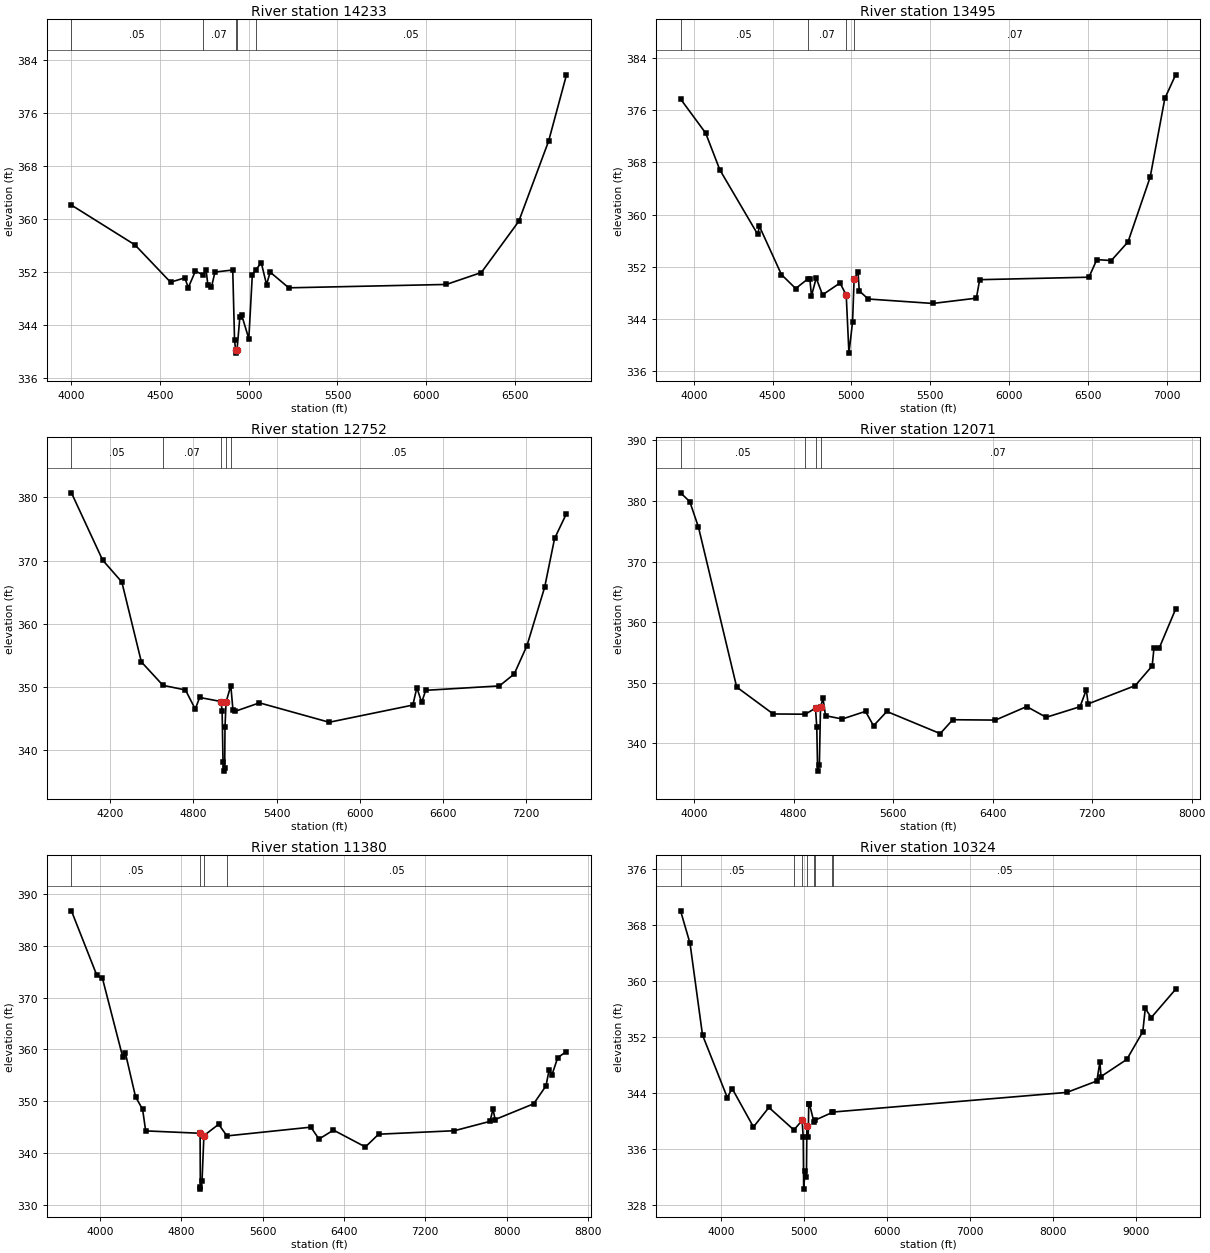
Type RM Length L Ch R = 1 ,14233   ,738,738,738
BEGIN DESCRIPTION:
Mapping XS c715589c
END DESCRIPTION:
XS GIS Cut Line= 4
       2684529.6      6862648.68      2684535.05      6861655.28
      2684524.06      6861488.36      2683671.21      6860105.62
#Sta/Elev= 30
  4003.1  362.16  4360.8  356.15  4560.8  350.52  4640.8  351.17  4660.8  349.71
  4700.8  352.21  4743.1  351.62  4760.8  352.39  4770.8  350.08  4790.8  349.76
  4810.8  352.05  4910.8  352.36  4920.8   341.8  4926.7  340.31  4927.9  339.81
  4934.9  340.31  4950.8  345.28  4960.8  345.57  5001.2  341.98  5020.9  351.66
  5041.1  352.39    5071  353.48    5101  350.16  5121.1  352.04    5226  349.67
  6112.4  350.18  6309.4  351.98  6519.9  359.71  6687.9  371.83  6788.4  381.83
#Mann= 5 ,-1 , 0
  4003.1     .05       0  4743.1     .07       0  4926.7     .05       0
  4934.9     .07       0  5041.1     .05       0
Bank Sta=4926.7,4934.9
XS Rating Curve= 0 ,0
Exp/Cntr=0.3,0.1

Type RM Length L Ch R = 1 ,13495   ,743,743,743
BEGIN DESCRIPTION:
Mapping XS e2dac2dd
END DESCRIPTION:
XS GIS Cut Line= 4
       2685133.8      6862649.78       2685071.3      6861644.58
      2685078.22      6861542.52       2683690.8       6860059.6
#Sta/Elev= 30
  3916.5  377.75  4075.6  372.52  4165.8  366.86  4406.2  356.95  4416.2  358.22
  4556.5  350.78  4646.7  348.64  4724.2  350.12  4736.9  350.04  4746.9  347.51
  4776.9  350.25    4817  347.67  4927.9  349.49  4967.3  347.65  4984.5  338.72
  5007.4  343.48  5017.4  350.13  5042.5  351.11  5049.9  348.29  5106.5  347.03
  5516.8  346.35  5792.8  347.16  5813.9     350    6507  350.38  6556.8  353.08
  6648.7  352.94  6754.7   355.8  6895.4  365.76  6988.2  377.83  7056.7  381.46
#Mann= 4 ,-1 , 0
  3916.5     .05       0  4724.2     .07       0  4967.3     .05       0
  5017.4     .07       0
Bank Sta=4967.3,5017.4
XS Rating Curve= 0 ,0
Exp/Cntr=0.3,0.1

Type RM Length L Ch R = 1 ,12752   ,681,681,681
BEGIN DESCRIPTION:
Mapping XS a14bdf95
END DESCRIPTION:
XS GIS Cut Line= 3
      2685430.13      6862642.91      2685663.33      6861626.82
      2683722.64       6860002.9
#Sta/Elev= 30
  3919.4  380.72  4144.4  370.09  4283.3  366.61  4424.1  353.98  4579.9  350.27
  4742.2  349.54  4813.1  346.52  4844.8  348.35  4999.2  347.71    5007  346.25
  5013.5   338.1  5018.3   336.7  5025.6   337.2  5027.8  343.69  5035.6  347.62
  5069.7  350.24  5085.1   346.4  5099.4  346.15  5276.4   347.5  5779.9  344.43
  6383.7  347.15  6412.3  349.89  6447.5  347.57  6476.1  349.48  7008.3  350.18
    7115  352.06  7207.4  356.56  7334.9  365.79  7406.5   373.5  7492.4  377.44
#Mann= 5 ,-1 , 0
  3919.4     .05       0  4579.9     .07       0  4999.2     .05       0
  5035.6     .07       0  5069.7     .05       0
Bank Sta=4999.2,5035.6
XS Rating Curve= 0 ,0
Exp/Cntr=0.3,0.1

Type RM Length L Ch R = 1 ,12071   ,691,691,691
BEGIN DESCRIPTION:
Mapping XS 961329fb
END DESCRIPTION:
XS GIS Cut Line= 4
      2686181.71      6862625.07      2686229.09      6861513.98
      2686220.25      6861426.19      2683969.84      6859794.38
#Sta/Elev= 30
  3891.1  381.33  3965.2  379.88  4035.3  375.65  4342.2  349.29  4635.8  344.85
  4893.3  344.81  4976.2   345.8  4986.2  342.64  4993.1  335.42  5007.2  336.51
  5016.2  345.98  5036.3  347.43  5056.4  344.56  5191.6  344.02    5378  345.28
  5442.5   342.9  5549.6  345.26  5978.7  341.61  6079.2   343.9  6422.5  343.84
  6673.8  346.07  6830.7   344.3  7102.9  346.05  7153.2  348.84  7167.9  346.51
  7546.7  349.53  7682.8  352.78  7697.5  355.81  7740.1  355.76  7871.2  362.15
#Mann= 4 ,-1 , 0
  3891.1     .05       0  4893.3     .07       0  4976.2     .05       0
  5016.2     .07       0
Bank Sta=4976.2,5016.2
XS Rating Curve= 0 ,0
Exp/Cntr=0.3,0.1

Type RM Length L Ch R = 1 ,11380   ,1056,1056,1056
BEGIN DESCRIPTION:
Mapping XS 826f1fac
END DESCRIPTION:
XS GIS Cut Line= 4
      2686272.61       6863100.7      2686727.27      6861902.01
       2686746.5      6861737.09      2683971.15      6859735.83
#Sta/Elev= 30
    3720  386.73  3970.1  374.28  4025.1  373.71  4225.4  358.45  4250.2  359.34
  4350.7  350.84  4420.3  348.41  4450.4  344.26  4985.7   343.8  4988.1  333.52
  4989.4  333.02    5005  334.68  5023.2  343.34  5168.1  345.53  5249.7  343.29
  6075.5  344.98    6155  342.68  6297.6  344.41  6611.7  341.16  6741.7  343.62
  7486.5  344.29  7837.5   346.1  7866.9  348.48  7887.8  346.45    8267  349.49
  8388.4  352.96  8417.9  355.93  8447.3  355.11  8503.8  358.41  8589.7  359.57
#Mann= 4 ,-1 , 0
    3720     .05       0  4985.7     .05       0  5023.2     .07       0
  5249.7     .05       0
Bank Sta=4985.7,5023.2
XS Rating Curve= 0 ,0
Exp/Cntr=0.3,0.1

Type RM Length L Ch R = 1 ,10324   ,0,0,0
BEGIN DESCRIPTION:
Mapping XS 619ef6a0
END DESCRIPTION:
XS GIS Cut Line= 4
      2686661.95      6863215.78      2687541.06      6862011.14
      2687153.39      6861801.57      2683796.86      6859552.25
#Sta/Elev= 30
  3508.7  370.01  3622.8  365.37  3773.5  352.28  4072.4  343.36  4131.1  344.64
  4388.3  339.15  4574.4  341.94  4875.9  338.73  4975.4  340.09  4988.5   337.7
  4993.9  330.28  5011.1  332.88  5027.3  331.97    5033  339.35  5049.2  337.75
  5054.9   342.4  5062.6   342.5  5117.4  339.87  5136.6  340.15  5339.5  341.23
    5352  341.29  8170.1  344.09  8531.2  345.72  8567.4  348.44  8580.9  346.35
  8892.4   348.8  9085.1  352.75  9115.1  356.07  9187.2  354.77  9481.2  358.81
#Mann= 8 ,-1 , 0
  3508.7     .05       0  4875.9     .07       0  4975.4     .05       0
    5033     .05       0  5117.4     .07       0  5136.6     .05       0
  5339.5     .12       0    5352     .05       0
Bank Sta=4975.4,5033
XS Rating Curve= 0 ,0
Exp/Cntr=0.3,0.1

Chan Stop Cuts=-1
Use User Specified Reach Order=0
Composite Channel Slope=5