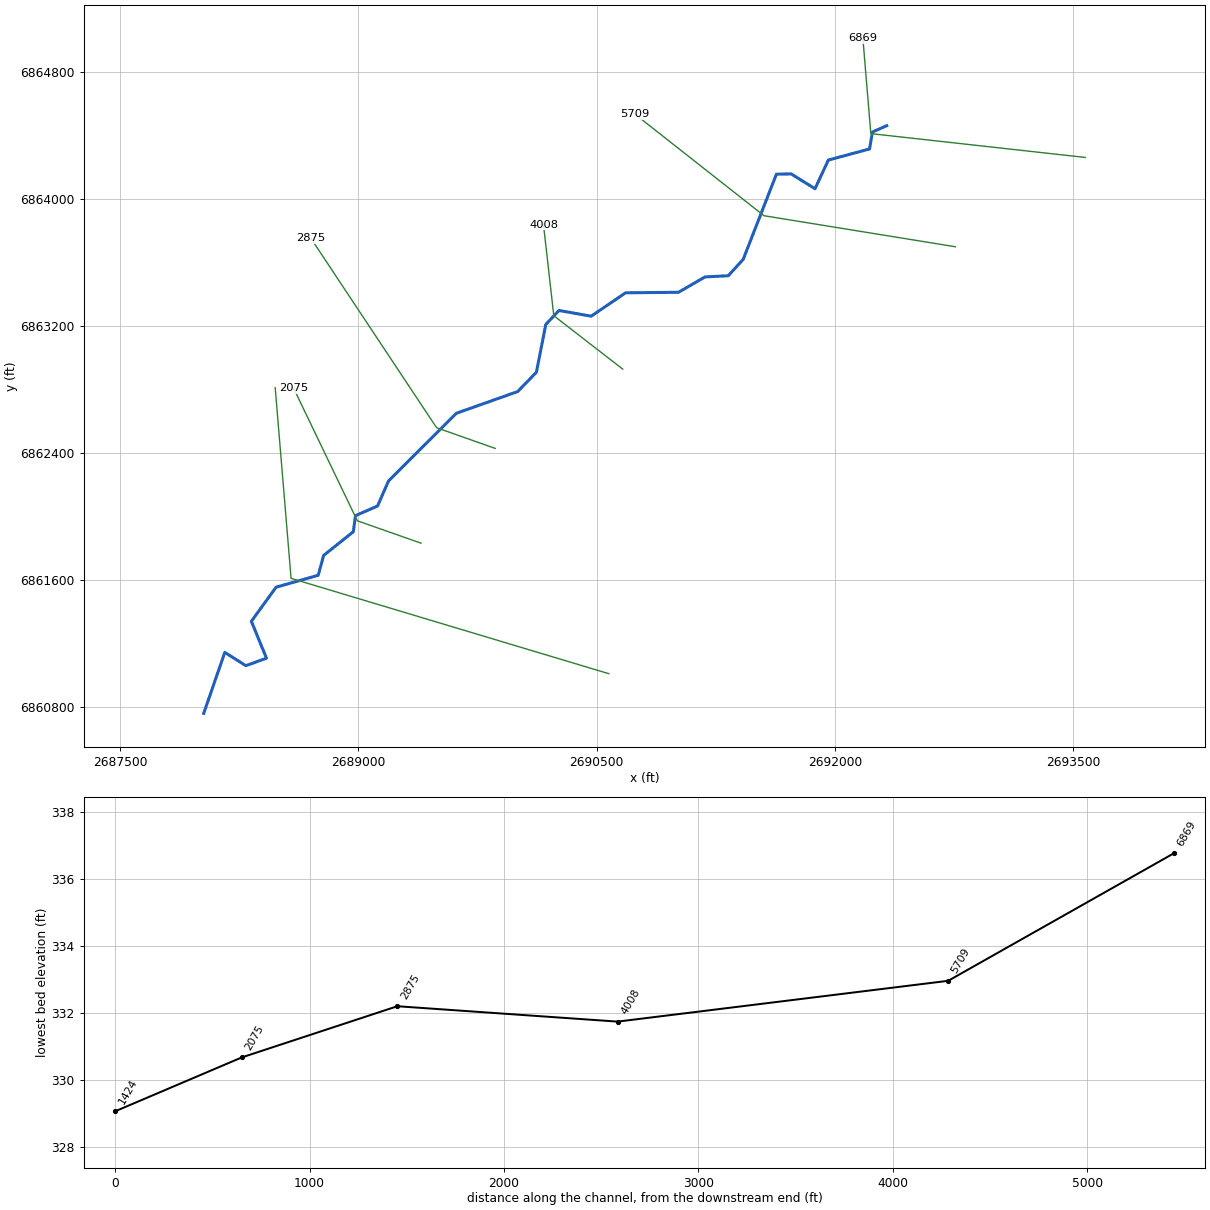
--- CCT5_1.prj (project) ---

Proj Title=CCT5_1 Base Level Engineering
Current Plan=p01
Default Exp/Contr=0.3,0.1
English Units
Geom File=g01
Flow File=f01
Plan File=p01
BEGIN DESCRIPTION:
CCT5_1
END DESCRIPTION:

--- CCT5_1.p01 (plan) ---

Plan Title=Multiple Run
Short Identifier=Multiple
Geom File=g01
Flow File=f01
Subcritical Flow
K Sum by GR= 0
Std Step Tol= 0.01
Critical Tol= 0.01
Num of Std Step Trials= 20
Max Error Tol= 0.3
Flow Tol Ratio= 0.001
Split Flow NTrial= 30
Split Flow Tol= 0.02
Split Flow Ratio= 0.02
Log Output Level= 0
Friction Slope Method= 1
Unsteady Friction Slope Method= 2
Unsteady Bridges Friction Slope Method= 1
Parabolic Critical Depth
Global Vel Dist=  1 , 1 , 1
Global Log Level= 0
CheckData=True
Encroach Param= -1, 0, 0, 0
BEGIN DESCRIPTION:
Multiple Run
END DESCRIPTION:

--- CCT5_1.f01 (steady flow) ---

Flow Title=Multiple
Number of Profiles=7
Profile Names=10-year,25-year,50-year,1pct_min,100-year,1pct_plu,500-year
River Rch & RM= CCT5_1,Reach-1,6869
     451     591     701     412     823    1641    1133
River Rch & RM= CCT5_1,Reach-1,2075
     866    1176    1429     859    1715    3422    2470
Boundary for River Rch & Prof#=CCT5_1,Reach-1,1
Up Type=0
Dn Type=3
Dn Slope=0.005
Boundary for River Rch & Prof#=CCT5_1,Reach-1,2
Up Type=0
Dn Type=3
Dn Slope=0.005
Boundary for River Rch & Prof#=CCT5_1,Reach-1,3
Up Type=0
Dn Type=3
Dn Slope=0.005
Boundary for River Rch & Prof#=CCT5_1,Reach-1,4
Up Type=0
Dn Type=3
Dn Slope=0.005
Boundary for River Rch & Prof#=CCT5_1,Reach-1,5
Up Type=0
Dn Type=3
Dn Slope=0.005
Boundary for River Rch & Prof#=CCT5_1,Reach-1,6
Up Type=0
Dn Type=3
Dn Slope=0.005
Boundary for River Rch & Prof#=CCT5_1,Reach-1,7
Up Type=0
Dn Type=3
Dn Slope=0.005

--- CCT5_1.g01 (geometry) ---

Geom Title=Existing Conditions

River Reach=CCT5_1,Reach-1
Reach XY= 30
      2692326.00      6864461.00      2692236.28      6864421.05
      2692217.85      6864314.37      2691958.78      6864244.76
      2691874.60      6864064.00      2691724.43      6864157.55
      2691631.54      6864155.57      2691422.51      6863619.47
      2691328.69      6863516.40      2691181.93      6863508.75
      2691015.50      6863412.20      2690681.93      6863408.76
      2690465.38      6863261.60      2690262.67      6863297.68
      2690179.61      6863209.52      2690120.53      6862908.55
      2690002.88      6862787.17      2689616.32      6862650.24
      2689189.55      6862224.24      2689120.42      6862066.58
      2688981.25      6862005.56      2688968.12      6861904.88
      2688781.26      6861755.52      2688746.64      6861630.42
      2688481.61      6861555.41      2688326.09      6861340.65
      2688421.05      6861108.42      2688291.22      6861061.25
      2688158.87      6861145.00      2688026.00      6860761.00

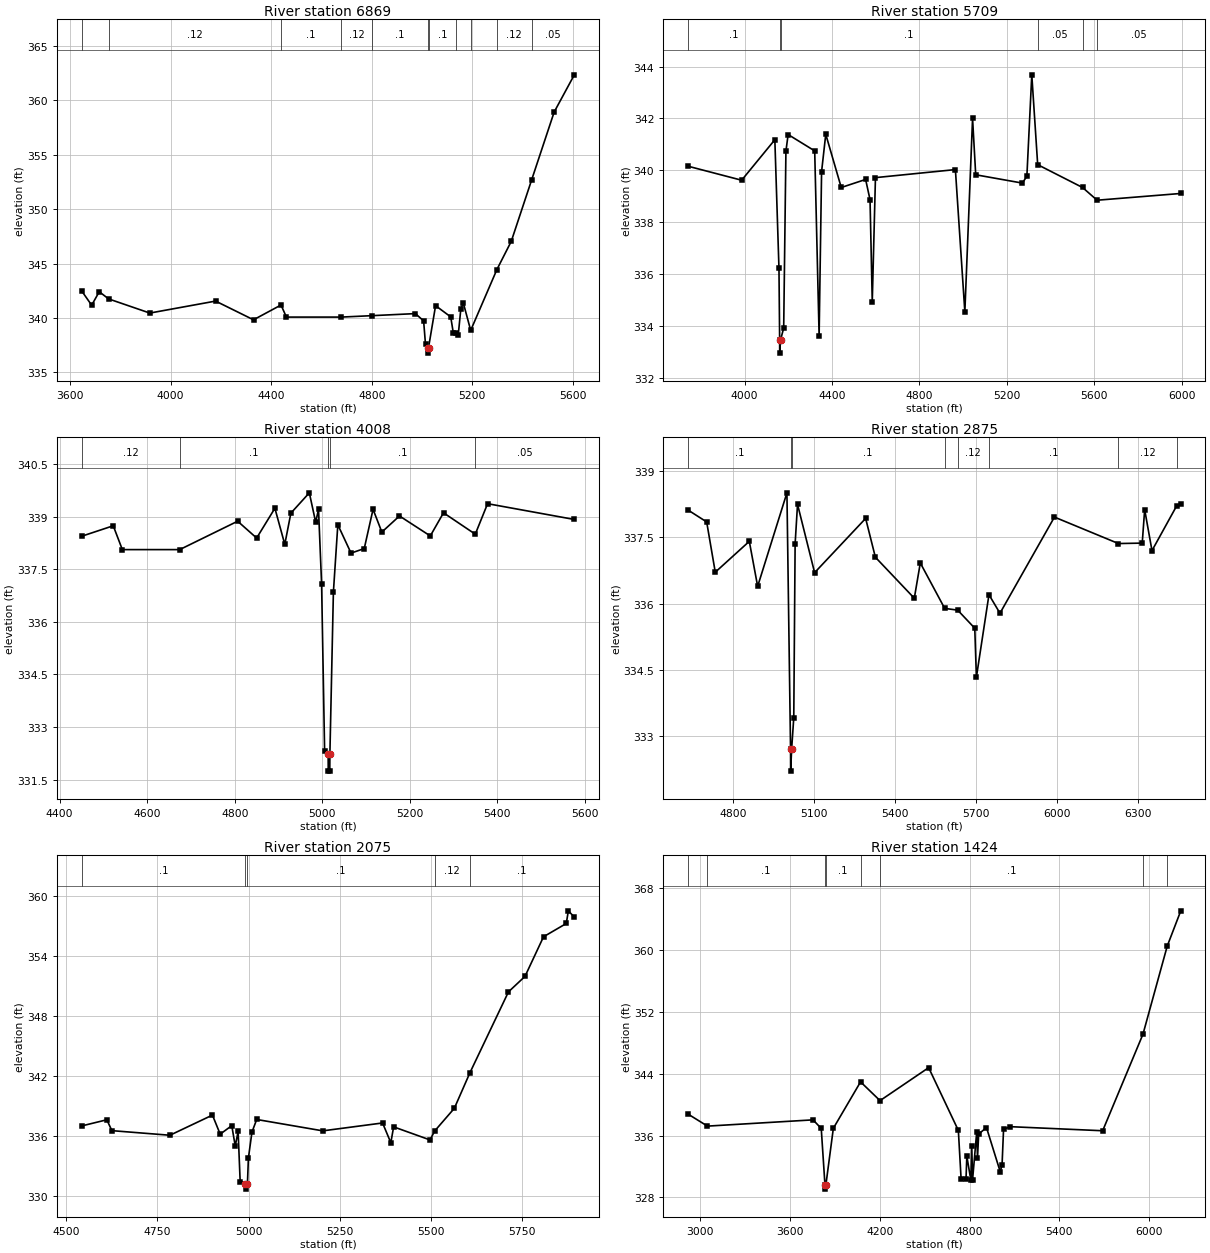
Type RM Length L Ch R = 1,6869,1160,1160,1160
BEGIN DESCRIPTION:
CCT5_1 9.0
END DESCRIPTION:
XS GIS Cut Line= 3
      2693575.95      6864261.01      2692226.00      6864411.00
      2692176.00      6865010.96
#Sta/Elev= 30
  3645.7  342.50  3685.9  341.17  3716.1  342.41  3753.3  341.75  3917.3  340.45
  4178.9  341.55  4329.8  339.83  4439.2  341.19  4460.6  340.08  4678.8  340.08
  4800.7  340.21  4973.8  340.40  5006.5  339.73  5014.0  337.57  5022.0  337.27
  5022.3  336.77  5026.0  337.27  5054.1  341.13  5114.3  340.10  5124.4  338.66
  5136.5  338.66  5144.4  338.47  5154.5  340.82  5164.5  341.37  5193.8  338.86
  5298.1  344.45  5355.2  347.04  5436.4  352.69  5525.8  358.91  5606.0  362.33
#Mann=11,-1,0
  3645.7     0.1       0  3753.3    0.12       0  4439.2     0.1       0
  4678.8    0.12       0  4800.7     0.1       0  5022.0    0.07       0
  5026.0     0.1       0  5136.5    0.12       0  5193.8     0.1       0
  5298.1    0.12       0  5436.4    0.05       0
Bank Sta=5022,5026
Exp/Cntr=0.3,0.1

Type RM Length L Ch R = 1,5709,1701,1701,1701
BEGIN DESCRIPTION:
Mapping XS fe8374e0
END DESCRIPTION:
XS GIS Cut Line= 3
      2692758.20      6863698.79      2691553.76      6863894.11
      2690740.52      6864533.86
#Sta/Elev= 30
  3741.3  340.16  3986.7  339.62  4138.6  341.18  4157.5  336.22  4160.6  333.46
  4160.8  332.96  4164.6  333.46  4179.1  333.93  4189.3  340.74  4199.4  341.38
  4321.0  340.75  4341.2  333.63  4352.5  339.95  4371.6  341.39  4442.5  339.34
  4554.0  339.65  4574.2  338.87  4584.4  334.94  4599.0  339.72  4964.8  340.03
  5008.1  334.55  5043.4  342.00  5057.8  339.83  5271.1  339.51  5291.9  339.77
  5314.4  343.68  5341.4  340.22  5546.7  339.34  5613.3  338.85  5996.2  339.11
#Mann=6,-1,0
  3741.3     0.1       0  4160.6    0.07       0  4164.6     0.1       0
  5341.4    0.05       0  5546.7    0.12       0  5613.3    0.05       0
Bank Sta=4160.6,4164.6
Exp/Cntr=0.3,0.1

Type RM Length L Ch R = 1,4008,1133,1133,1133
BEGIN DESCRIPTION:
Mapping XS 1aab573e
END DESCRIPTION:
XS GIS Cut Line= 3
      2690664.02      6862928.38      2690229.98      6863264.77
      2690165.09      6863837.97
#Sta/Elev= 30
  4450.0  338.44  4522.4  338.74  4543.2  338.06  4674.3  338.06  4806.7  338.87
  4850.1  338.39  4891.8  339.24  4914.4  338.21  4928.3  339.10  4970.5  339.68
  4985.0  338.84  4991.5  339.21  4998.5  337.09  5005.4  332.32  5013.5  332.24
  5013.7  331.74  5017.2  331.74  5017.5  332.24  5025.5  336.85  5035.6  338.77
  5065.8  337.96  5096.0  338.09  5116.1  339.21  5136.2  338.56  5176.5  339.02
  5246.9  338.45  5277.1  339.11  5349.7  338.50  5377.8  339.37  5576.0  338.92
#Mann=5,-1,0
  4450.0    0.12       0  4674.3     0.1       0  5013.5    0.07       0
  5017.5     0.1       0  5349.7    0.05       0
Bank Sta=5013.5,5017.5
Exp/Cntr=0.3,0.1

Type RM Length L Ch R = 1,2875,800,800,800
BEGIN DESCRIPTION:
Mapping XS b7fa7b69
END DESCRIPTION:
XS GIS Cut Line= 3
      2689861.06      6862429.26      2689492.13      6862559.47
      2688700.49      6863752.36
#Sta/Elev= 30
  4634.1  338.12  4703.1  337.85  4734.9  336.71  4860.8  337.41  4891.7  336.39
  5000.0  338.51  5013.4  332.70  5013.7  332.20  5017.4  332.70  5025.3  333.41
  5030.3  337.35  5039.2  338.25  5102.4  336.70  5291.2  337.93  5327.2  337.05
  5471.2  336.12  5493.4  336.92  5583.6  335.89  5631.7  335.85  5694.9  335.44
  5700.9  334.33  5747.4  336.20  5788.1  335.78  5989.6  337.96  6226.4  337.36
  6314.4  337.37  6323.4  338.13  6350.5  337.20  6441.4  338.21  6457.0  338.25
#Mann=8,-1,0
  4634.1     0.1       0  5013.4    0.07       0  5017.4     0.1       0
  5583.6    0.05       0  5631.7    0.12       0  5747.4     0.1       0
  6226.4    0.12       0  6441.4    0.05       0
Bank Sta=5013.4,5017.4
Exp/Cntr=0.3,0.1

Type RM Length L Ch R = 1,2075,651,651,651
BEGIN DESCRIPTION:
Mapping XS 1c99ee40
END DESCRIPTION:
XS GIS Cut Line= 3
      2689394.51      6861832.46      2688993.00      6861973.53
      2688592.27      6862807.48
#Sta/Elev= 30
  4542.3  337.00  4611.5  337.62  4625.5  336.53  4784.5  336.07  4901.1  338.09
  4922.3  336.18  4954.1  337.03  4963.6  334.99  4971.5  336.45  4977.1  331.43
  4991.4  331.17  4992.2  330.67  4997.0  331.17  4999.7  333.79  5009.4  336.38
  5022.4  337.65  5203.5  336.51  5367.5  337.30  5390.1  335.32  5397.8  336.91
  5497.6  335.60  5510.2  336.49  5564.2  338.77  5606.9  342.33  5712.6  350.44
  5757.9  351.99  5808.7  355.96  5871.1  357.29  5876.7  358.56  5893.1  357.93
#Mann=5,-1,0
  4542.3     0.1       0  4991.4    0.07       0  4997.0     0.1       0
  5510.2    0.12       0  5606.9     0.1       0
Bank Sta=4991.4,4997
Exp/Cntr=0.3,0.1

Type RM Length L Ch R = 1,1424,0,0,0
BEGIN DESCRIPTION:
CCT5_1 1.0
END DESCRIPTION:
XS GIS Cut Line= 3
      2690576.03      6861010.99      2688576.00      6861611.00
      2688476.00      6862811.05
#Sta/Elev= 30
  2919.0  338.78  3048.9  337.22  3754.3  338.03  3809.1  336.92  3834.1  329.56
  3835.0  329.06  3839.8  329.56  3890.0  336.94  4071.8  342.95  4201.9  340.52
  4526.8  344.79  4725.2  336.66  4743.5  330.39  4776.5  330.41  4781.8  333.33
  4808.7  330.22  4814.8  334.67  4820.0  330.22  4847.9  336.49  4853.1  333.05
  4860.9  336.19  4913.1  337.04  5004.5  331.34  5017.1  332.14  5027.2  336.79
  5069.8  337.15  5689.4  336.62  5958.8  349.13  6120.9  360.54  6211.3  365.10
#Mann=8,-1,0
  2919.0    0.12       0  3048.9     0.1       0  3834.1    0.07       0
  3839.8     0.1       0  4071.8    0.12       0  4201.9     0.1       0
  5958.8    0.12       0  6120.9     0.1       0
Bank Sta=3834.1,3839.8
Exp/Cntr=0.3,0.1

Chan Stop Cuts=-1