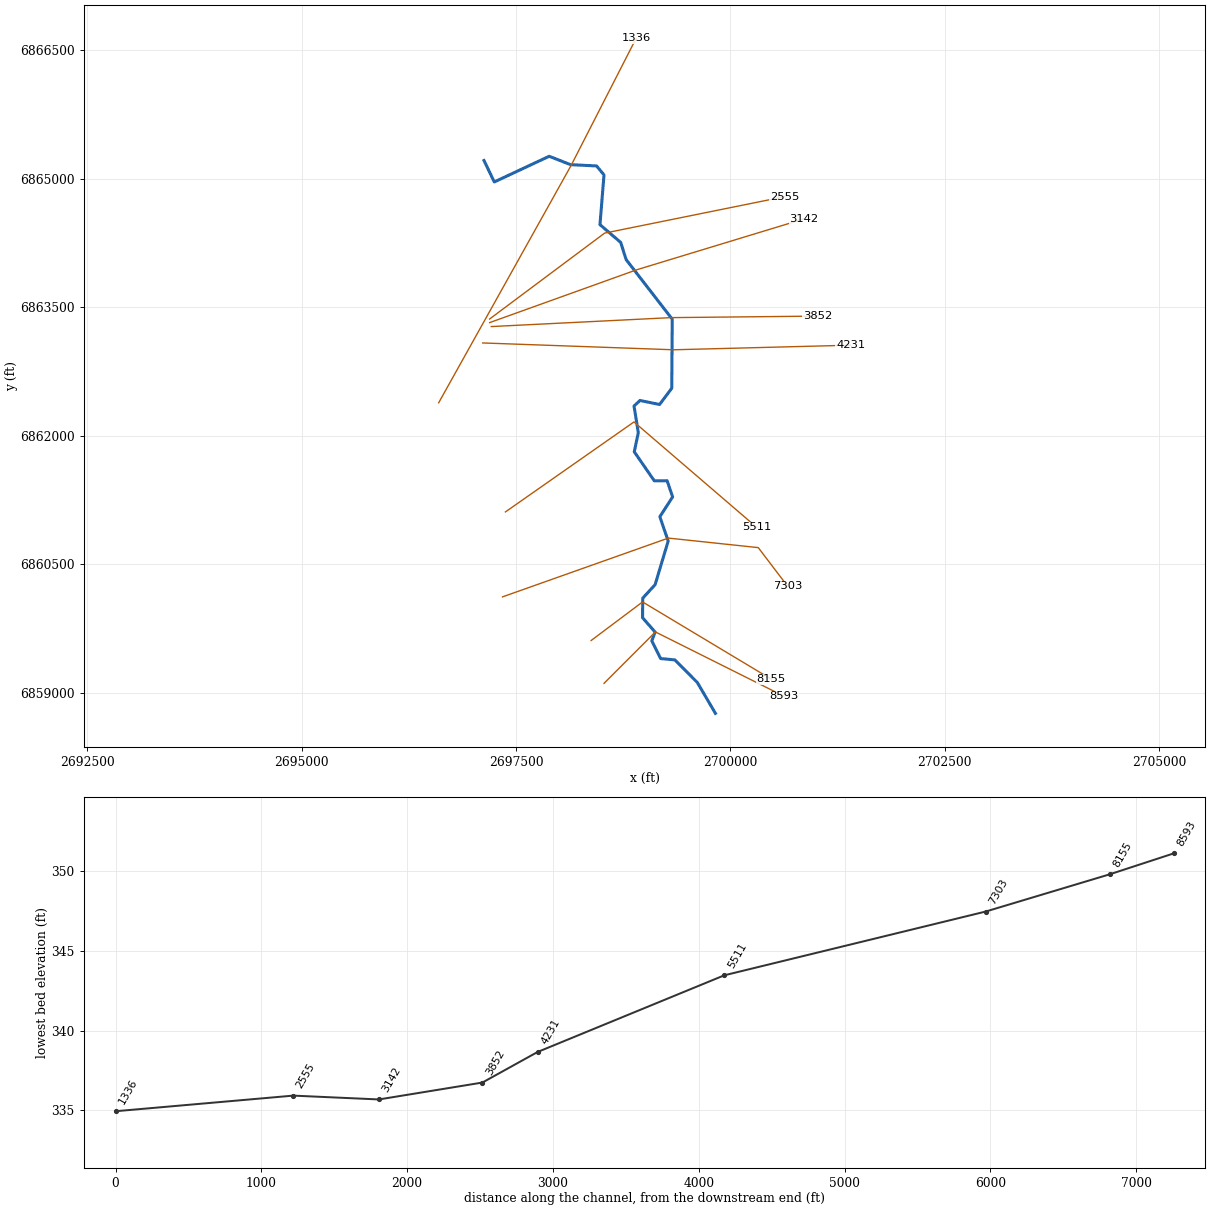
--- CCT6.prj (project) ---

Proj Title=CCT6 Base Level Engineering
Current Plan=p01
Default Exp/Contr=0.3,0.1
English Units
Geom File=g01
Flow File=f01
Plan File=p01
Y Axis Title=Elevation
X Axis Title(PF)=Main Channel Distance
X Axis Title(XS)=Station
BEGIN DESCRIPTION:
CCT6
END DESCRIPTION:
DSS Export Rating Curves= 0
DSS Export Rating Curve Sorted= 0
DSS Export Volume Flow Curves= 0
DXF OffsetX= 0
DXF OffsetY= 0
DXF ScaleX= 1
DXF ScaleY= 10

--- CCT6.p01 (plan) ---

Plan Title=Multiple Run
Short Identifier=Multiple
Geom File=g01
Flow File=f01
Subcritical Flow
K Sum by GR= 0
Std Step Tol= 0.01
Critical Tol= 0.01
Num of Std Step Trials= 20
Max Error Tol= 0.3
Flow Tol Ratio= 0.001
Split Flow NTrial= 30
Split Flow Tol= 0.02
Split Flow Ratio= 0.02
Log Output Level= 0
Friction Slope Method= 1
Unsteady Friction Slope Method= 2
Unsteady Bridges Friction Slope Method= 1
Parabolic Critical Depth
Global Vel Dist=  1 , 1 , 1
Global Log Level= 0
CheckData=True
Encroach Param= -1, 0, 0, 0
BEGIN DESCRIPTION:
Multiple Run
END DESCRIPTION:

--- CCT6.f01 (steady flow) ---

Flow Title=Multiple
Program Version=4.10
Number of Profiles= 7
Profile Names=10-year,25-year,50-year,1pct_min,100-year,1pct_plu,500-year
River Rch & RM=CCT6,Reach-1         ,8593
     484     639     762     451     901    1797    1256
River Rch & RM=CCT6,Reach-1         ,7303
     751    1016    1231     739    1475    2944    2119
River Rch & RM=CCT6,Reach-1         ,4231
    1076    1482    1819    1104    2204    4397    3236
River Rch & RM=CCT6,Reach-1         ,1336
    1528    2138    2651    1624    3241    6467    4849
Boundary for River Rch & Prof#=CCT6,Reach-1         , 1
Up Type= 0
Dn Type= 3
Dn Slope=0.0008
Boundary for River Rch & Prof#=CCT6,Reach-1         , 2
Up Type= 0
Dn Type= 3
Dn Slope=0.0008
Boundary for River Rch & Prof#=CCT6,Reach-1         , 3
Up Type= 0
Dn Type= 3
Dn Slope=0.0008
Boundary for River Rch & Prof#=CCT6,Reach-1         , 4
Up Type= 0
Dn Type= 3
Dn Slope=0.0008
Boundary for River Rch & Prof#=CCT6,Reach-1         , 5
Up Type= 0
Dn Type= 3
Dn Slope=0.0008
Boundary for River Rch & Prof#=CCT6,Reach-1         , 6
Up Type= 0
Dn Type= 3
Dn Slope=0.0008
Boundary for River Rch & Prof#=CCT6,Reach-1         , 7
Up Type= 0
Dn Type= 3
Dn Slope=0.0008
DSS Import GetInterval= 0
DSS Import GetPeak= 0
DSS Import FillOption= 0

--- CCT6.g01 (geometry) ---

Geom Title=Existing Conditions
Program Version=4.10

River Reach=CCT6            ,Reach-1
Reach XY= 30
        2699826.        6858761.      2699615.22      6859120.68
      2699352.82      6859384.95      2699186.51      6859400.48
      2699083.84       6859607.6      2699122.84      6859709.35
      2698976.01      6859876.36      2698977.97      6860105.11
      2699122.46      6860262.47      2699274.92      6860771.54
      2699177.61      6861054.96      2699326.41        6861286.
      2699262.61      6861475.12      2699112.76      6861474.12
      2698879.16      6861812.65      2698926.32      6862035.96
      2698876.33        6862346.      2698946.05      6862411.38
      2699174.36      6862364.15      2699316.51      6862554.45
      2699322.25      6863359.45      2698784.14      6864054.94
      2698720.74      6864255.53      2698479.13      6864462.63
      2698526.08      6865042.89      2698439.24      6865147.42
      2698136.51       6865162.2      2697886.68      6865260.25
      2697246.12      6864960.51        2697126.        6865211.

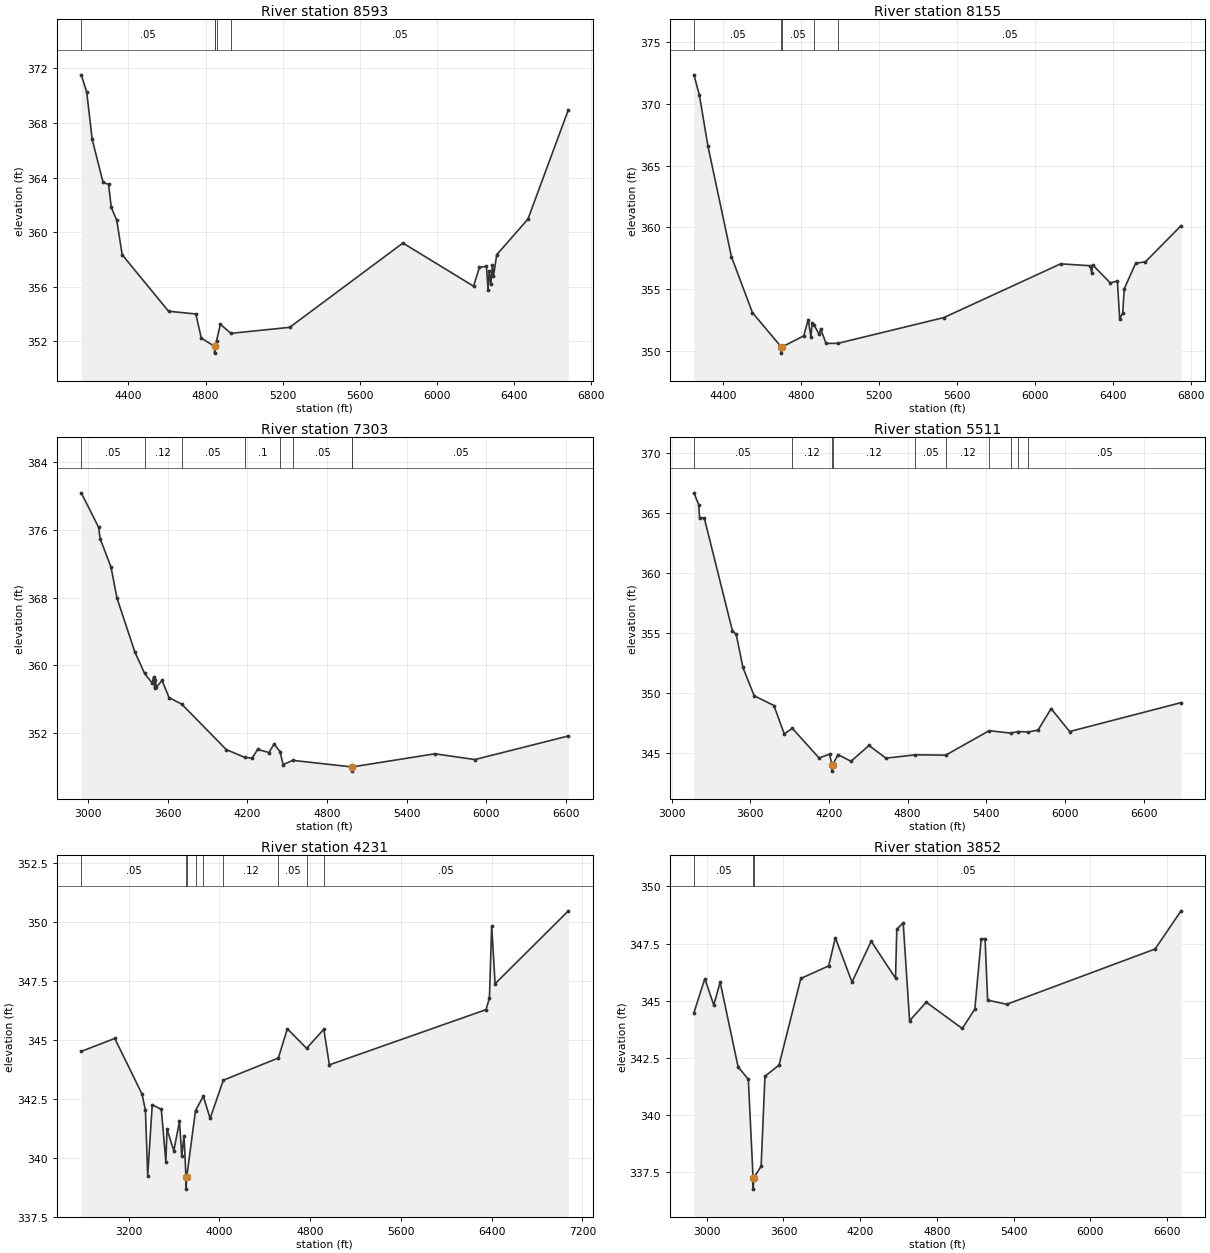
Type RM Length L Ch R = 1 ,8593    ,438,438,438
BEGIN DESCRIPTION:
CCT6 10.0
END DESCRIPTION:
XS GIS Cut Line= 3
        2698526.        6859111.        2699126.        6859711.
      2700626.02      6858960.99
#Sta/Elev= 30
  4155.4  371.53  4183.7  370.26    4212   366.8  4268.5  363.64  4296.8   363.5
    4311  361.81  4339.2  360.88  4367.5  358.34  4607.9   354.2  4749.4     354
  4777.6  352.23  4846.4  351.63  4846.6  351.13  4850.4  351.63  4856.9  352.05
  4876.6  353.24  4931.3  352.58  5235.9  353.02  5822.9   359.2    6189  356.04
  6219.8  357.42  6256.1   357.5  6264.5  355.74  6270.1  357.16  6278.5  356.17
  6286.9   357.6  6292.5  356.77  6309.2  358.34  6471.3  360.96    6681  368.98
#Mann= 5 ,-1 , 0
  4155.4     .05       0  4846.4     .04       0  4850.4     .05       0
  4856.9     .12       0  4931.3     .05       0
Bank Sta=4846.4,4850.4
XS Rating Curve= 0 ,0
Exp/Cntr=0.3,0.1

Type RM Length L Ch R = 1 ,8155    ,852,852,852
BEGIN DESCRIPTION:
CCT6 9.0
END DESCRIPTION:
XS GIS Cut Line= 3
      2698375.99      6859610.99        2698976.        6860061.
        2700476.        6859161.
#Sta/Elev= 30
    4251  372.36  4279.1  370.72  4322.9  366.59  4443.7  357.62    4551  353.11
    4699  350.32  4699.3  349.82    4703  350.32  4814.6  351.22  4837.5  352.54
    4851  351.15  4858.3  352.29  4867.2   352.1  4893.7  351.34    4901  351.77
  4929.1  350.61  4988.8  350.61  5533.6   352.7  6132.2  357.05  6283.8   356.9
  6291.6  356.34  6297.4  356.96  6386.8  355.51  6423.8  355.66  6435.4  352.61
    6451  353.05  6458.8  355.03  6517.1  357.09  6567.6  357.22  6750.3  360.14
#Mann= 5 ,-1 , 0
    4251     .05       0    4699     .05       0    4703     .05       0
  4867.2     .12       0  4988.8     .05       0
Bank Sta=4699,4703
XS Rating Curve= 0 ,0
Exp/Cntr=0.3,0.1

Type RM Length L Ch R = 1 ,7303    ,1792,1792,1792
BEGIN DESCRIPTION:
CCT6 8.0
END DESCRIPTION:
XS GIS Cut Line= 4
      2697342.35      6860120.25      2699276.81      6860805.97
      2700325.76      6860694.71      2700667.48       6860245.3
#Sta/Elev= 30
  2947.6  380.39  3078.8   376.3  3089.6  374.98  3171.6  371.61  3216.7  367.95
  3351.6  361.56  3425.3  359.03    3482  357.89  3492.6   358.6  3500.7  357.32
    3506  358.22  3513.8   357.4  3556.2  358.21  3609.3  356.17  3704.8   355.4
  4040.6  350.03  4180.4   349.1  4235.2  349.01  4277.1  350.05  4362.6  349.68
  4400.6  350.69    4446  349.78  4468.7  348.26  4542.7  348.75  4986.5  347.98
  4986.8  347.48  4990.5  347.98  5612.6  349.53  5914.3  348.85  6619.4  351.64
#Mann= 8 ,-1 , 0
  2947.6     .05       0  3425.3     .12       0  3704.8     .05       0
  4180.4      .1       0    4446     .12       0  4542.7     .05       0
  4986.5     .05       0  4990.5     .05       0
Bank Sta=4986.5,4990.5
XS Rating Curve= 0 ,0
Exp/Cntr=0.3,0.1

Type RM Length L Ch R = 1 ,5511    ,1280,1280,1280
BEGIN DESCRIPTION:
CCT6 7.0
END DESCRIPTION:
XS GIS Cut Line= 3
      2697376.01      6861111.01        2698876.        6862161.
      2700305.97      6860932.62
#Sta/Elev= 30
  3169.5  366.68  3206.1  365.69  3212.6  364.61  3248.4  364.59  3462.9  355.19
  3492.5  354.87  3543.1  352.13  3629.4  349.76  3779.8  348.95  3858.7  346.58
  3920.3  347.05  4123.8  344.58    4204  344.89  4222.9  343.98  4223.2  343.48
  4226.9  343.98  4268.1  344.86  4367.9   344.3  4504.8  345.62  4634.3  344.56
  4859.2  344.84  5090.3  344.81  5421.5  346.85  5586.9  346.65  5642.7  346.78
  5720.1  346.74  5794.4   346.9  5894.3  348.69  6035.8  346.78  6885.6  349.19
#Mann= 10 ,-1 , 0
  3169.5     .05       0  3920.3     .12       0  4222.9     .05       0
  4226.9     .12       0  4859.2     .05       0  5090.3     .12       0
  5421.5      .1       0  5586.9     .12       0  5642.7      .1       0
  5720.1     .05       0
Bank Sta=4222.9,4226.9
XS Rating Curve= 0 ,0
Exp/Cntr=0.3,0.1

Type RM Length L Ch R = 1 ,4231    ,379,379,379
BEGIN DESCRIPTION:
CCT6 6.0
END DESCRIPTION:
XS GIS Cut Line= 3
      2697110.93      6863082.44      2699337.28      6863002.72
      2701402.01      6863056.29
#Sta/Elev= 30
  2783.5  344.51  3078.8  345.06  3318.9   342.7  3348.9  342.02  3368.9  339.23
    3409  342.25    3489  342.05    3529  339.82  3539.1  341.21  3599.1   340.3
  3649.1  341.54  3669.1  340.08  3689.2  340.94  3706.2  339.17  3707.2  338.67
  3712.2  339.17  3790.4     342  3858.7  342.61  3919.3  341.67  4035.5  343.29
  4520.3  344.23  4599.7  345.47  4769.4  344.64    4921  345.45    4970  343.94
  6350.4  346.28  6380.5  346.77  6400.5  349.83  6430.5  347.38  7076.7  350.47
#Mann= 9 ,-1 , 0
  2783.5     .05       0  3706.2     .04       0  3712.2     .05       0
  3790.4     .12       0  3858.7     .05       0  4035.5     .12       0
  4520.3     .05       0  4769.4     .12       0    4921     .05       0
Bank Sta=3706.2,3712.2
XS Rating Curve= 0 ,0
Exp/Cntr=0.3,0.1

Type RM Length L Ch R = 1 ,3852    ,710,710,710
BEGIN DESCRIPTION:
CCT6 5.0
END DESCRIPTION:
XS GIS Cut Line= 3
      2697210.87      6863273.45      2699307.67      6863377.83
      2701018.98      6863395.71
#Sta/Elev= 30
  2899.3  344.47  2984.5  345.96  3054.6  344.81  3104.7  345.81  3244.9   342.1
    3325  341.56    3362  337.25    3363  336.75    3368  337.25  3425.1  337.75
  3455.1  341.69  3565.3  342.18  3735.5  345.97  3953.5  346.52  4005.8  347.75
    4136  345.81  4286.1   347.6  4476.4  345.98  4486.4  348.13  4536.5   348.4
  4586.5  344.12  4716.7  344.93  4998.7  343.78    5097  344.63    5147  347.71
    5177   347.7    5197  345.02    5347  344.84  6507.1  347.26  6710.1  348.93
#Mann= 3 ,-1 , 0
  2899.3     .05       0    3362     .05       0    3368     .05       0
Bank Sta=3362,3368
XS Rating Curve= 0 ,0
Exp/Cntr=0.3,0.1

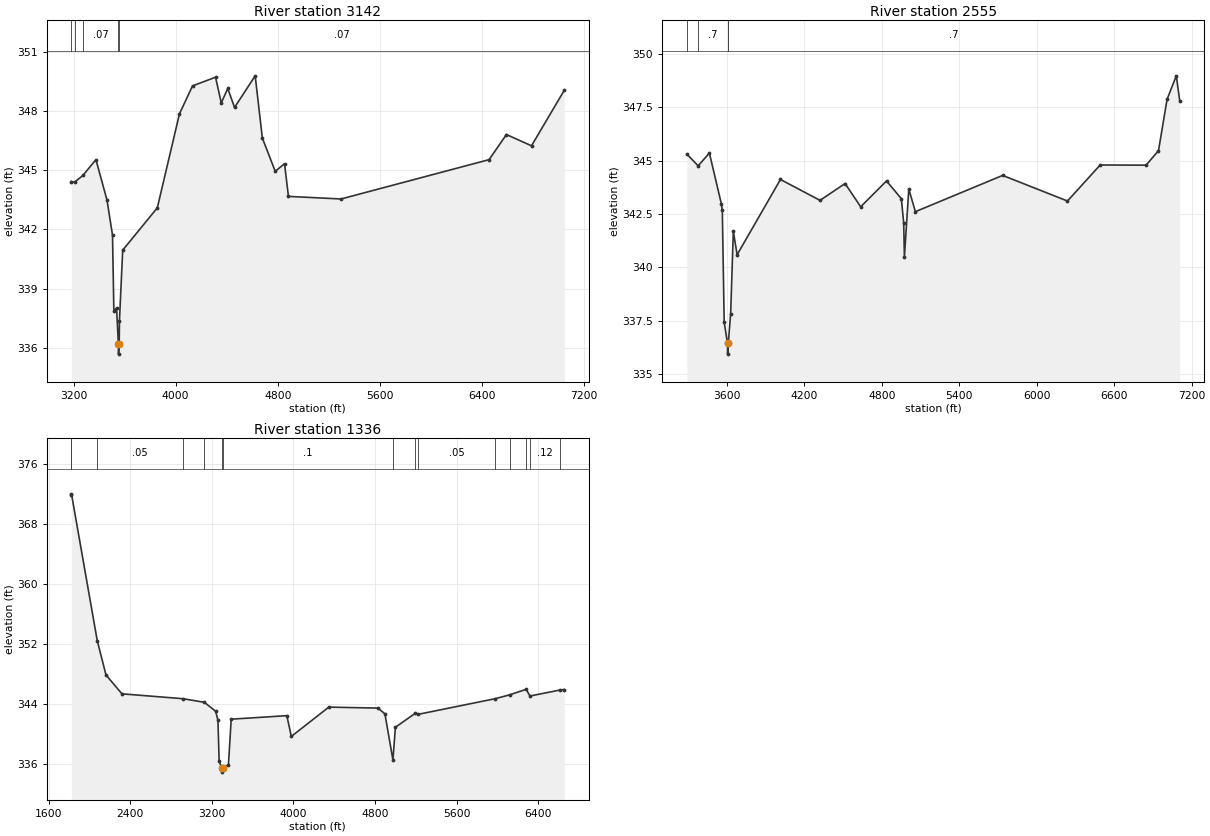
Type RM Length L Ch R = 1 ,3142    ,587,587,587
BEGIN DESCRIPTION:
CCT6 4.0
END DESCRIPTION:
XS GIS Cut Line= 3
      2697192.17      6863319.78      2698904.63      6863935.02
      2700859.71      6864529.87
#Sta/Elev= 30
  3182.1  344.42  3207.3  344.39  3272.8  344.73    3375  345.53  3461.9  343.48
  3504.9  341.71  3515.6  337.85  3536.8  338.03    3551  336.19    3552  335.69
  3557.1  336.19  3559.4  337.39  3584.8  340.95    3856  343.09  4029.8  347.85
  4131.9  349.26  4312.5   349.7  4357.1   348.4    4408  349.13  4461.3  348.17
    4623  349.77  4679.2  346.62    4780  344.94  4852.9  345.32  4883.6  343.67
  5295.8  343.54  6456.1  345.53    6592   346.8  6788.4  346.23  7045.3  349.04
#Mann= 5 ,-1 , 0
  3182.1     .05       0  3207.3     .12       0  3272.8     .07       0
    3551     .05       0  3557.1     .07       0
Bank Sta=3551,3557.1
XS Rating Curve= 0 ,0
Exp/Cntr=0.3,0.1

Type RM Length L Ch R = 1 ,2555    ,1219,1219,1219
BEGIN DESCRIPTION:
Mapping XS e916db17
END DESCRIPTION:
XS GIS Cut Line= 3
      2697191.21      6863361.31       2698533.3      6864363.73
      2700632.47      6864788.77
#Sta/Elev= 30
    3291  345.31  3378.8  344.76  3465.7  345.36  3559.1  342.96  3565.8  342.67
  3580.4  337.43    3606  336.43    3607  335.93  3612.1  336.43  3630.4  337.83
  3651.2  341.69  3680.4  340.59    4016  344.12  4322.5  343.14  4516.3  343.93
  4637.2  342.84  4837.3  344.05    4952  343.22  4970.1  342.09  4975.8  340.49
  5009.7  343.67  5060.7  342.61  5736.3  344.31  6238.2  343.11  6491.7   344.8
  6846.7  344.79    6943  345.47  7009.5  347.88  7080.9  348.98  7107.9  347.79
#Mann= 4 ,-1 , 0
    3291     .12       0  3378.8      .7       0    3606     .05       0
  3612.1      .7       0
Bank Sta=3606,3612.1
XS Rating Curve= 0 ,0
Exp/Cntr=0.3,0.1

Type RM Length L Ch R = 1 ,1336    ,0,0,0
BEGIN DESCRIPTION:
Mapping XS 9b4d5f00
END DESCRIPTION:
XS GIS Cut Line= 3
      2696597.53      6862384.56      2698142.67      6865153.66
      2698901.01      6866636.02
#Sta/Elev= 30
  1820.7  371.95  1822.1  372.06  2075.1  352.48    2161   347.9  2317.6  345.39
  2916.8  344.74  3126.2  344.26  3236.6  343.06  3259.1  341.87    3271  336.37
  3297.7  335.45  3299.1  334.95  3307.3  335.45  3361.9   335.9  3389.4  342.01
  3935.1  342.48    3979  339.71  4346.9  343.62  4829.1  343.49  4897.1  342.72
  4975.8  336.58    5000  340.93  5192.2  342.77  5217.1  342.64  5978.1  344.74
  6121.9  345.26  6282.7  345.99  6320.1   345.1  6619.2  345.91  6656.8  345.96
#Mann= 15 ,-1 , 0
  1820.7     .05       0  1822.1     .12       0  2075.1     .05       0
  2916.8     .12       0  3126.2      .1       0  3297.7     .07       0
  3307.3      .1       0  4975.8     .12       0  5192.2      .1       0
  5217.1     .05       0  5978.1      .1       0  6121.9     .12       0
  6282.7      .1       0  6320.1     .12       0  6619.2      .1       0
Bank Sta=3297.7,3307.3
XS Rating Curve= 0 ,0
Exp/Cntr=0.3,0.1

Chan Stop Cuts=-1
Use User Specified Reach Order=0
Composite Channel Slope=5