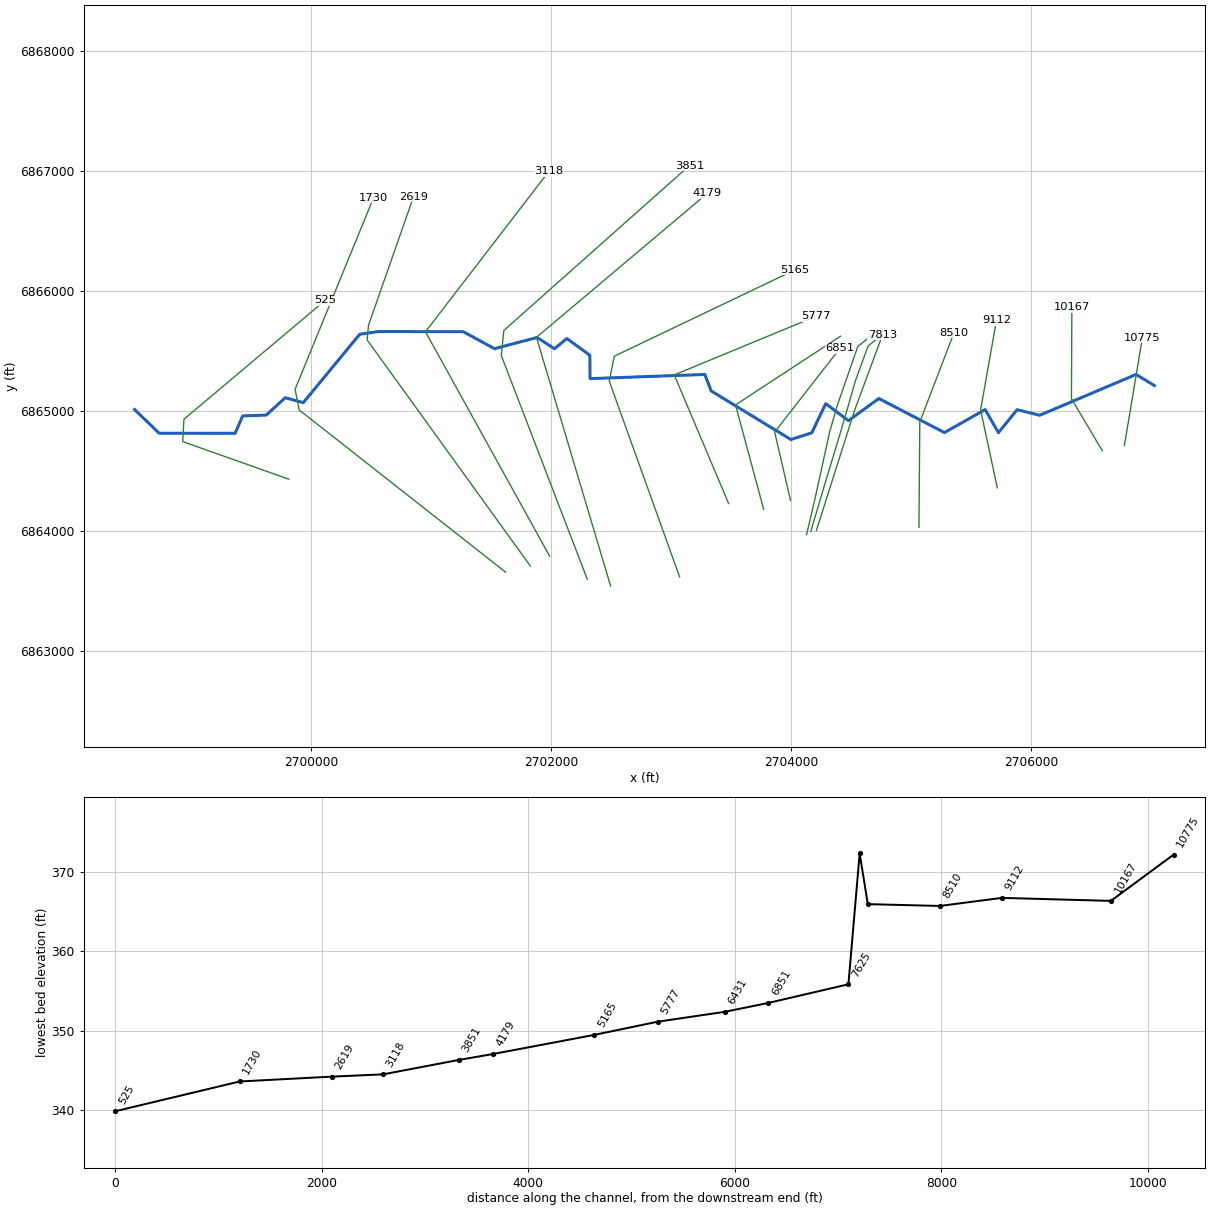
--- CCT6_1.prj (project) ---

Proj Title=CCT6_1 Base Level Engineering
Current Plan=p01
Default Exp/Contr=0.3,0.1
English Units
Geom File=g01
Flow File=f01
Plan File=p01
Y Axis Title=Elevation
X Axis Title(PF)=Main Channel Distance
X Axis Title(XS)=Station
BEGIN DESCRIPTION:
CCT6_1
END DESCRIPTION:
DSS Export Rating Curves= 0
DSS Export Rating Curve Sorted= 0
DSS Export Volume Flow Curves= 0
DXF OffsetX= 0
DXF OffsetY= 0
DXF ScaleX= 1
DXF ScaleY= 10

--- CCT6_1.p01 (plan) ---

Plan Title=Multiple Run
Short Identifier=Multiple
Geom File=g01
Flow File=f01
Subcritical Flow
K Sum by GR= 0
Std Step Tol= 0.01
Critical Tol= 0.01
Num of Std Step Trials= 20
Max Error Tol= 0.3
Flow Tol Ratio= 0.001
Split Flow NTrial= 30
Split Flow Tol= 0.02
Split Flow Ratio= 0.02
Log Output Level= 0
Friction Slope Method= 1
Unsteady Friction Slope Method= 2
Unsteady Bridges Friction Slope Method= 1
Parabolic Critical Depth
Global Vel Dist=  1 , 1 , 1
Global Log Level= 0
CheckData=True
Encroach Param= -1, 0, 0, 0
BEGIN DESCRIPTION:
Multiple Run
END DESCRIPTION:

--- CCT6_1.f01 (steady flow) ---

Flow Title=Multiple
Number of Profiles=7
Profile Names=10-year,25-year,50-year,1pct_min,100-year,1pct_plu,500-year
River Rch & RM= CCT6_1,Reach-1,10775
     492     648     772     456     910    1816    1265
River Rch & RM= CCT6_1,Reach-1,7734
     726     977    1180     706    1409    2811    2007
Boundary for River Rch & Prof#=CCT6_1,Reach-1,1
Up Type=0
Dn Type=3
Dn Slope=0.005
Boundary for River Rch & Prof#=CCT6_1,Reach-1,2
Up Type=0
Dn Type=3
Dn Slope=0.005
Boundary for River Rch & Prof#=CCT6_1,Reach-1,3
Up Type=0
Dn Type=3
Dn Slope=0.005
Boundary for River Rch & Prof#=CCT6_1,Reach-1,4
Up Type=0
Dn Type=3
Dn Slope=0.005
Boundary for River Rch & Prof#=CCT6_1,Reach-1,5
Up Type=0
Dn Type=3
Dn Slope=0.005
Boundary for River Rch & Prof#=CCT6_1,Reach-1,6
Up Type=0
Dn Type=3
Dn Slope=0.005
Boundary for River Rch & Prof#=CCT6_1,Reach-1,7
Up Type=0
Dn Type=3
Dn Slope=0.005

--- CCT6_1.g01 (geometry) ---

Geom Title=Existing Conditions
Program Version=4.10

River Reach=CCT6_1          ,Reach-1
Reach XY= 30
        2707026.        6865211.      2706872.67      6865303.41
      2706070.03      6864963.14      2705881.85      6865009.46
      2705725.77      6864817.97      2705615.55      6865010.48
      2705276.01      6864818.53      2704729.29      6865102.95
      2704475.99      6864918.07      2704286.57      6865060.12
      2704170.45      6864816.59       2703996.1       6864760.9
      2703331.26      6865166.48       2703279.7      6865303.32
      2702322.34      6865268.89      2702320.91      6865463.31
      2702129.23      6865603.15        2702026.      6865518.11
      2701881.05      6865611.85        2701526.      6865518.56
      2701265.32      6865660.25      2700555.82      6865661.29
      2700402.67      6865638.48      2699932.38      6865068.35
      2699781.86      6865109.43      2699624.48      6864964.74
      2699427.22      6864957.56      2699364.46      6864812.52
      2698731.96      6864813.14        2698526.        6865011.

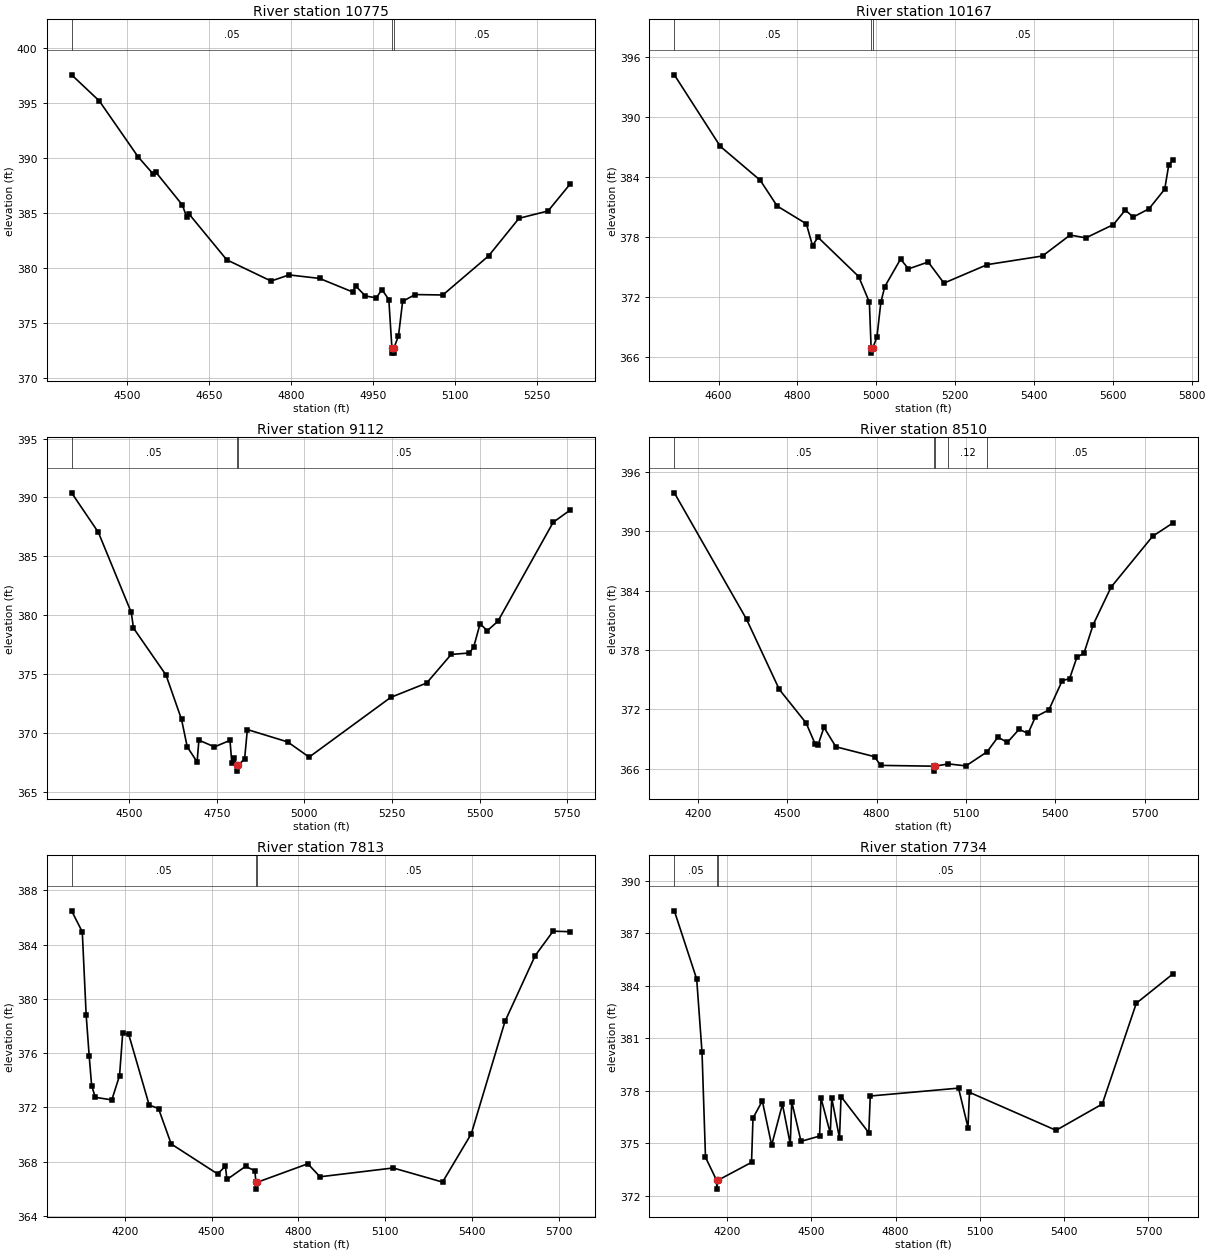
Type RM Length L Ch R = 1 ,10775   ,608,608,608
BEGIN DESCRIPTION:
CCT6_1 11.0
END DESCRIPTION:
XS GIS Cut Line= 3
        2706776.      6864711.01        2706876.        6865311.
        2706926.        6865611.
#Sta/Elev= 30
  4399.1   397.6  4449.8  395.22  4520.7  390.13  4548.6  388.54  4553.7   388.7
  4601.8  385.73  4609.4  384.66  4614.5  384.88  4682.9  380.74  4764.1   378.8
    4797  379.36  4852.8  379.04  4913.6   377.8  4918.7  378.37  4936.4  377.44
  4956.7  377.27  4966.8  378.03  4979.5  377.11  4985.1  372.73  4985.3  372.23
  4988.8  372.23  4989.1  372.73  4997.2  373.81  5004.8  376.95  5027.6  377.57
  5078.3  377.53    5162  381.09  5217.7  384.52  5270.9  385.19  5311.5  387.66
#Mann= 3 ,-1 , 0
  4399.1     .05       0  4985.1     .05       0  4989.1     .05       0
Bank Sta=4985.1,4989.1
XS Rating Curve= 0 ,0
Exp/Cntr=0.3,0.1

Type RM Length L Ch R = 1 ,10167   ,1055,1055,1055
BEGIN DESCRIPTION:
Mapping XS bbc6de63
END DESCRIPTION:
XS GIS Cut Line= 3
       2706591.4       6864667.5      2706334.43      6865101.57
       2706337.9      6865862.03
#Sta/Elev= 30
  4487.8  394.17  4604.3  387.03  4705.7  383.64  4748.6  381.07  4822.7  379.29
  4838.3  377.11  4852.1  377.95  4955.3  374.03  4982.5  371.47    4987  366.88
  4987.2  366.38    4991  366.88  5001.7  367.99  5011.7  371.47  5021.7  373.03
  5061.7  375.77  5081.7  374.79  5131.7  375.48  5171.7  373.37  5281.7  375.22
  5421.7  376.08  5491.7  378.17  5531.7  377.89  5601.7  379.22  5631.7  380.67
  5651.7  379.97  5691.7  380.79  5731.7  382.75  5741.7  385.13  5752.7  385.69
#Mann= 3 ,-1 , 0
  4487.8     .05       0    4987     .04       0    4991     .05       0
Bank Sta=4987,4991
XS Rating Curve= 0 ,0
Exp/Cntr=0.3,0.1

Type RM Length L Ch R = 1 ,9112    ,602,602,602
BEGIN DESCRIPTION:
Mapping XS 4d939e69
END DESCRIPTION:
XS GIS Cut Line= 3
      2705716.39      6864358.47      2705577.49      6865007.82
      2705709.43      6865754.31
#Sta/Elev= 30
  4336.2  390.39  4412.6  387.03  4506.4  380.23  4512.6  378.91  4605.4  374.92
  4649.7  371.15    4666  368.82  4694.1  367.54  4699.2  369.39  4743.6  368.82
  4787.9  369.37    4793  367.47    4799   367.9  4807.2  367.26  4807.4  366.76
  4811.2  367.26  4829.6   367.8  4837.4  370.29  4952.4  369.24  5013.6  367.95
  5246.2  373.02  5348.7  374.24  5418.7  376.67  5470.6  376.79  5482.9   377.3
  5501.1  379.28  5521.4  378.68  5551.8  379.48  5709.6  387.89  5758.3  388.93
#Mann= 3 ,-1 , 0
  4336.2     .05       0  4807.2     .04       0  4811.2     .05       0
Bank Sta=4807.2,4811.2
XS Rating Curve= 0 ,0
Exp/Cntr=0.3,0.1

Type RM Length L Ch R = 1 ,8510    ,697,697,697
BEGIN DESCRIPTION:
Mapping XS 2fab5651
END DESCRIPTION:
XS GIS Cut Line= 3
       2705063.6      6864028.61      2705070.54      6864907.12
      2705355.27       6865650.2
#Sta/Elev= 30
  4120.6  393.88    4363   381.1    4473     374    4563  370.61    4593  368.51
    4603  368.39    4623  370.16    4663   368.2    4793   367.2    4813  366.32
    4991  366.24  4991.3  365.74    4995  366.24  5040.8  366.47  5099.7  366.27
  5170.6  367.69  5206.8  369.17  5238.9  368.65  5278.1  369.97  5308.2  369.55
  5332.9  371.22  5378.1  371.93    5423  374.89  5447.6  375.09  5472.3  377.26
  5495.9  377.66    5527  380.56  5587.1  384.35  5726.6  389.49  5794.9  390.84
#Mann= 5 ,-1 , 0
  4120.6     .05       0    4991     .05       0    4995     .05       0
  5040.8     .12       0  5170.6     .05       0
Bank Sta=4991,4995
XS Rating Curve= 0 ,0
Exp/Cntr=0.3,0.1

Type RM Length L Ch R = 1 ,7813    ,79,79,79
BEGIN DESCRIPTION:
Mapping XS f7a63b55
END DESCRIPTION:
XS GIS Cut Line= 3
      2704209.14      6864003.03      2704525.96      6865001.24
      2704760.33       6865634.9
#Sta/Elev= 30
  4016.1  386.49    4053  384.94  4066.4  378.81  4076.9  375.78  4085.3  373.61
  4097.9  372.74    4155  372.55  4181.8  374.34  4192.6  377.46  4213.3  377.39
  4284.1  372.17  4316.4  371.91  4360.2   369.3  4520.5  367.09  4547.5  367.66
  4552.7  366.68  4617.2  367.65  4649.5  367.32  4652.8  366.47    4653  365.97
  4656.8  366.47  4832.3  367.84  4874.3  366.88  5127.1  367.53  5297.7  366.49
    5397  370.05  5513.3  378.33  5617.6  383.18  5679.7  384.99    5739  384.95
#Mann= 3 ,-1 , 0
  4016.1     .05       0  4652.8     .04       0  4656.8     .05       0
Bank Sta=4652.8,4656.8
XS Rating Curve= 0 ,0
Exp/Cntr=0.3,0.1

Type RM Length L Ch R = 1 ,7734    ,109,109,109
BEGIN DESCRIPTION:
Mapping XS 15e872fd
END DESCRIPTION:
XS GIS Cut Line= 6
      2704161.92      6863994.73      2704283.45      6864402.73
      2704422.34       6864862.8      2704535.18      6865253.42
      2704639.35      6865539.88       2704760.9      6865639.72
#Sta/Elev= 30
  4012.3  388.28  4091.9  384.38  4110.9  380.19  4123.2   374.2  4162.9  372.88
  4163.2  372.38  4166.9  372.88  4287.1  373.91  4292.3  376.44  4325.5  377.42
  4358.7  374.89  4397.1  377.23    4425  374.95  4430.2  377.37  4463.2  375.11
  4529.2  375.41  4534.4  377.58  4567.4  375.57  4572.6  377.58  4600.3  375.29
  4605.6  377.67  4704.5   375.6  4709.7   377.7  5023.9  378.15  5057.6   375.9
  5062.8  377.91    5371  375.74  5535.4  377.24  5656.7     383  5787.3  384.68
#Mann= 3 ,-1 , 0
  4012.3     .05       0  4162.9     .04       0  4166.9     .05       0
Bank Sta=4162.9,4166.9
XS Rating Curve= 0 ,0
Exp/Cntr=0.3,0.1

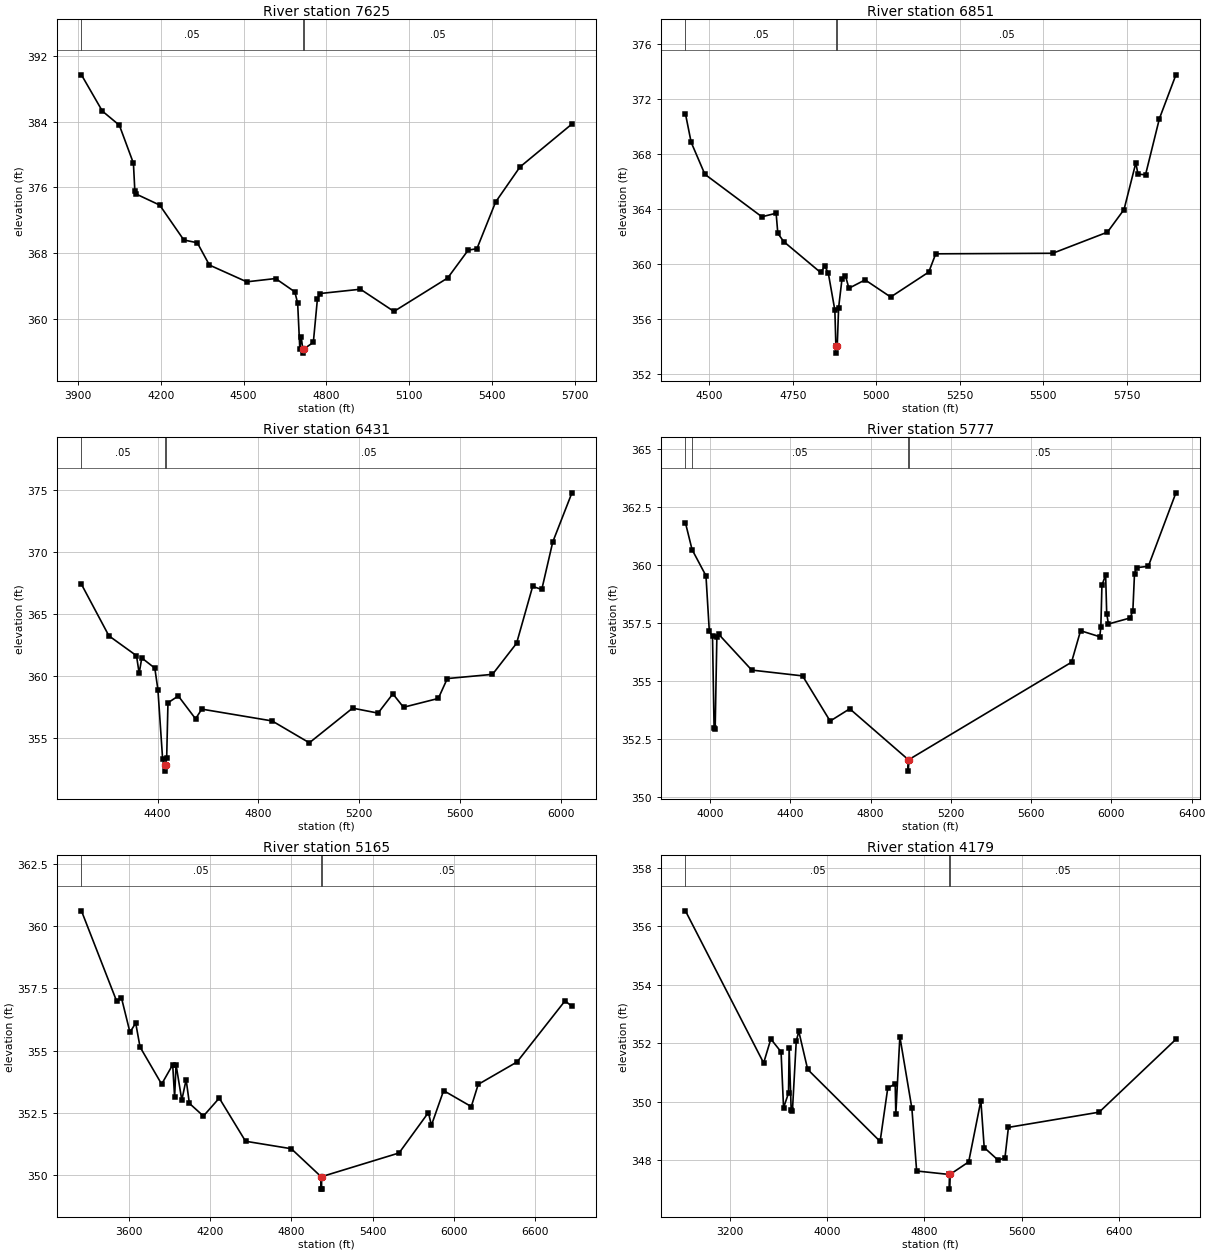
Type RM Length L Ch R = 1 ,7625    ,774,774,774
BEGIN DESCRIPTION:
Mapping XS 5892277f
END DESCRIPTION:
XS GIS Cut Line= 6
        2704127.      6863967.32      2704194.71      6864256.37
      2704319.71      6864826.69      2704384.81      6865050.64
      2704554.08      6865537.62      2704668.64      6865628.75
#Sta/Elev= 30
  3912.8  389.68  3988.5  385.27  4050.1  383.55    4101  378.93  4106.2  375.54
  4111.7  375.17  4196.2  373.84  4283.4   369.6  4332.3  369.26  4376.1  366.55
  4511.3  364.51  4615.8  364.91  4685.3  363.29  4695.6  361.93  4703.4   356.4
  4708.5  357.84    4714  356.34  4714.3  355.84    4718  356.34  4752.4  357.15
  4767.2  362.44  4777.5  363.09    4923  363.61  5044.3  360.91  5238.9  364.98
    5313  368.36  5344.7  368.54  5412.3  374.21  5500.4  378.47  5688.7   383.7
#Mann= 3 ,-1 , 0
  3912.8     .05       0    4714     .04       0    4718     .05       0
Bank Sta=4714,4718
XS Rating Curve= 0 ,0
Exp/Cntr=0.3,0.1

Type RM Length L Ch R = 1 ,6851    ,420,420,420
BEGIN DESCRIPTION:
Mapping XS 81d8dcb3
END DESCRIPTION:
XS GIS Cut Line= 3
      2703992.97      6864254.28      2703861.16      6864822.73
      2704404.57      6865520.84
#Sta/Elev= 30
  4428.7  370.95  4445.9  368.86  4486.9  366.53  4657.5  363.43  4700.2  363.69
  4705.3  362.22    4723  361.62  4833.3  359.37  4846.2  359.83  4856.5  359.31
    4876  356.62  4879.1  353.99  4879.4  353.49  4883.1  353.99  4887.3  356.81
  4897.5  358.92  4907.8  359.12  4918.1  358.22  4966.5  358.83  5043.1  357.58
  5157.1   359.4  5177.9  360.73  5528.1  360.77  5691.9  362.31  5741.6  363.96
  5776.9  367.36  5783.3  366.54  5805.9  366.49  5847.5  370.59  5896.9  373.78
#Mann= 3 ,-1 , 0
  4428.7     .05       0  4879.1    .035       0  4883.1     .05       0
Bank Sta=4879.1,4883.1
XS Rating Curve= 0 ,0
Exp/Cntr=0.3,0.1

Type RM Length L Ch R = 1 ,6431    ,654,654,654
BEGIN DESCRIPTION:
Mapping XS c462c5f9
END DESCRIPTION:
XS GIS Cut Line= 3
      2703769.12      6864179.82      2703534.75      6865049.59
      2704409.77      6865622.52
#Sta/Elev= 30
  4098.1  367.41  4207.1  363.26  4316.6  361.66  4327.2  360.24  4337.5  361.48
  4389.3  360.66  4401.6  358.93  4420.4  353.31  4428.7  352.87    4429  352.37
  4432.7  352.87  4436.4  353.46  4441.5  357.87  4482.5  358.42    4551  356.58
  4575.7  357.36  4854.9  356.41  5002.6  354.65  5174.3  357.44  5275.3  357.04
  5334.1  358.59  5376.3  357.51  5514.4  358.22  5550.2  359.82  5729.5  360.16
  5825.1  362.66  5888.9  367.24  5925.1  366.99  5968.6  370.81  6044.8  374.77
#Mann= 3 ,-1 , 0
  4098.1     .05       0  4428.7    .035       0  4432.7     .05       0
Bank Sta=4428.7,4432.7
XS Rating Curve= 0 ,0
Exp/Cntr=0.3,0.1

Type RM Length L Ch R = 1 ,5777    ,612,612,612
BEGIN DESCRIPTION:
Mapping XS bab5b898
END DESCRIPTION:
XS GIS Cut Line= 3
      2703477.47      6864226.64      2703024.33      6865299.59
      2704206.65      6865789.19
#Sta/Elev= 30
  3877.2  361.83  3910.3  360.67  3979.6  359.54  3996.3  357.14  4012.2  356.92
    4020  352.99  4025.4  352.94  4033.9  356.91  4043.7  357.01  4207.7  355.47
    4461  355.22  4598.4  353.27  4696.1   353.8  4987.2  351.61  4987.4  351.11
  4991.2  351.61  5801.4  355.81  5846.4  357.17    5942  356.91  5947.4  357.31
  5952.9  359.13  5971.3  359.58  5976.7   357.9  5985.4  357.46  6093.6  357.72
    6107  358.03  6115.2  359.63  6125.5  359.89  6184.1  359.95  6321.6  363.12
#Mann= 4 ,-1 , 0
  3877.2     .12       0  3910.3     .05       0  4987.2    .035       0
  4991.2     .05       0
Bank Sta=4987.2,4991.2
XS Rating Curve= 0 ,0
Exp/Cntr=0.3,0.1

Type RM Length L Ch R = 1 ,5165    ,986,986,986
BEGIN DESCRIPTION:
Mapping XS 7cad76c2
END DESCRIPTION:
XS GIS Cut Line= 4
      2703069.08      6863614.21      2702482.67      6865247.51
      2702524.33      6865455.84      2704031.21      6866175.87
#Sta/Elev= 30
  3251.6  360.61  3510.4     357  3546.4  357.13  3609.4  355.74  3651.9  356.11
  3683.8  355.15  3843.2  353.66  3924.7  354.44  3938.8  353.13  3949.4  354.44
  3991.9  353.02  4023.8  353.84  4047.7  352.89  4151.3  352.38  4268.2   353.1
    4462  351.37  4799.4  351.07  5019.1  349.95  5019.4  349.45  5022.9  349.45
  5023.1  349.95  5594.4   350.9  5810.8  352.52    5833  352.01    5923   353.4
  6127.1  352.76  6178.1  353.65  6464.7  354.55  6818.6     357  6869.5  356.78
#Mann= 3 ,-1 , 0
  3251.6     .05       0  5019.1     .04       0  5023.1     .05       0
Bank Sta=5019.1,5023.1
XS Rating Curve= 0 ,0
Exp/Cntr=0.3,0.1

Type RM Length L Ch R = 1 ,4179    ,328,328,328
BEGIN DESCRIPTION:
Mapping XS 957a8547
END DESCRIPTION:
XS GIS Cut Line= 3
       2702493.9      6863538.78       2701875.9      6865612.96
      2703300.32      6866814.49
#Sta/Elev= 30
  2836.9  356.53  3479.2  351.33  3538.3  352.15  3622.3  351.71  3642.7   349.8
  3683.4   350.3  3688.6  351.85  3705.3  349.72  3715.7   349.7    3747  352.08
  3767.9  352.41  3840.9  351.11  4435.7  348.65  4498.3  350.47  4559.4  350.62
  4564.6  349.58  4597.8  352.23  4696.5  349.78  4735.6  347.64  5004.9  347.52
  5005.1  347.02  5008.9  347.52  5162.9  347.95    5263  350.04  5290.4  348.44
  5404.7  348.01  5460.7  348.09  5489.3  349.13  6234.4  349.65  6864.7  352.14
#Mann= 3 ,-1 , 0
  2836.9     .05       0  5004.9     .04       0  5008.9     .05       0
Bank Sta=5004.9,5008.9
XS Rating Curve= 0 ,0
Exp/Cntr=0.3,0.1

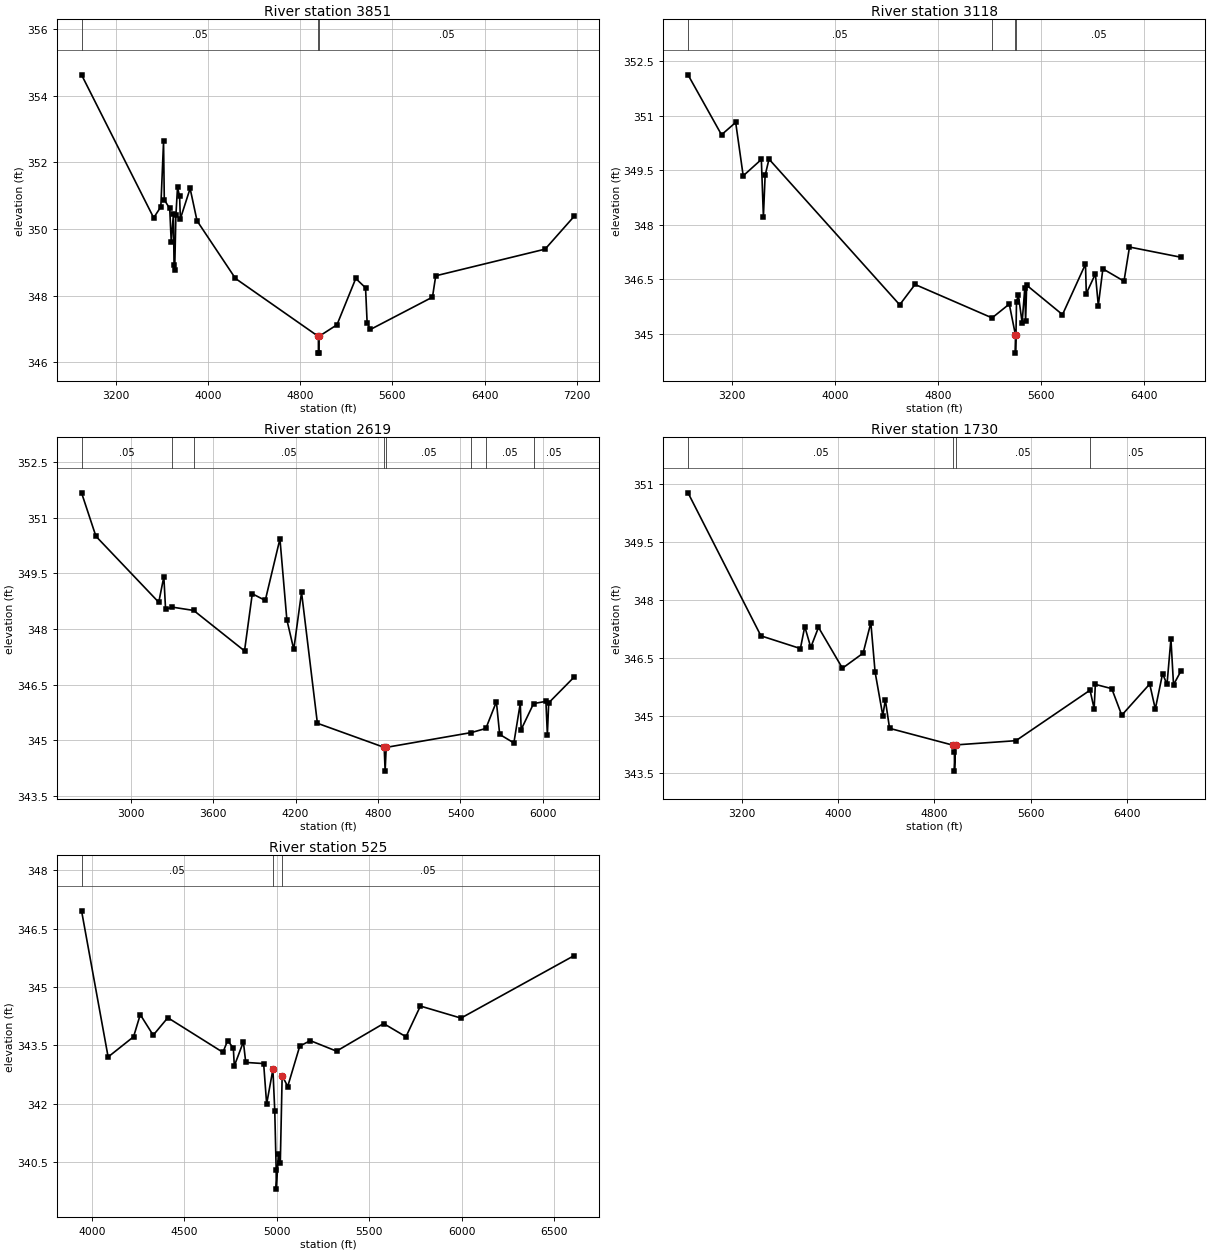
Type RM Length L Ch R = 1 ,3851    ,733,733,733
BEGIN DESCRIPTION:
Mapping XS 3c715e2d
END DESCRIPTION:
XS GIS Cut Line= 4
      2702298.79      6863596.77      2701582.72      6865461.72
      2701603.69        6865670.      2703149.78      6867044.86
#Sta/Elev= 30
  2902.7  354.63  3528.5  350.34  3590.7  350.67  3614.2  352.63  3620.7  350.88
  3667.8  350.62  3680.8  349.62  3699.9  350.45  3705.4  348.91  3710.8  348.76
  3721.3  350.41  3735.4  351.25  3753.5  350.99  3760.1  350.31  3844.8  351.22
  3904.8  350.25  4238.2  348.52    4958  346.78  4958.2  346.28  4961.7  346.28
    4962  346.78  5119.1  347.13  5282.2  348.52  5367.1  348.24  5380.9  347.19
  5409.3  346.99  5947.8  347.96  5976.2   348.6  6925.3   349.4  7178.7  350.39
#Mann= 3 ,-1 , 0
  2902.7     .05       0    4958     .04       0    4962     .05       0
Bank Sta=4958,4962
XS Rating Curve= 0 ,0
Exp/Cntr=0.3,0.1

Type RM Length L Ch R = 1 ,3118    ,499,499,499
BEGIN DESCRIPTION:
Mapping XS dfc70018
END DESCRIPTION:
XS GIS Cut Line= 3
       2701986.2      6863787.11      2700950.72      6865659.56
      2701978.93      6866996.76
#Sta/Elev= 30
  2858.2  352.12  3118.3  350.47  3228.3  350.81  3286.7  349.34  3427.6  349.79
  3443.6  348.21  3456.9  349.35  3487.1   349.8  4501.9  345.79    4621  346.35
  5219.2  345.43  5352.9  345.81  5400.8  344.96    5401  344.46  5404.8  344.96
  5409.1  345.88  5423.6  346.06  5452.6   345.3  5473.4  346.25  5479.7  345.34
  5487.9  346.33  5766.1  345.52  5944.7  346.91    5951   346.1  6021.6  346.64
  6044.3  345.77  6079.7  346.78  6243.7  346.44  6286.4  347.38  6684.7   347.1
#Mann= 4 ,-1 , 0
  2858.2     .05       0  5219.2     .05       0  5400.8     .04       0
  5404.8     .05       0
Bank Sta=5400.8,5404.8
XS Rating Curve= 0 ,0
Exp/Cntr=0.3,0.1

Type RM Length L Ch R = 1 ,2619    ,889,889,889
BEGIN DESCRIPTION:
Mapping XS d1e4e24e
END DESCRIPTION:
XS GIS Cut Line= 4
      2701825.13      6863705.49      2700464.17      6865592.28
      2700476.11      6865713.77      2700851.01      6866786.04
#Sta/Elev= 30
  2643.6  351.67    2748   350.5  3205.2  348.72  3242.2  349.41  3254.8  348.53
  3302.8  348.59  3459.3   348.5    3829  347.41  3885.5  348.95  3979.9  348.77
  4086.7  350.43    4137  348.25  4187.3  347.45  4243.8  348.99  4359.1  345.46
  4845.1  344.81  4851.8  344.17  4859.7  344.81    5480  345.21  5584.6  345.32
  5661.2  346.04  5685.1  345.16  5788.3  344.93    5835     346  5841.3  345.29
  5931.7  345.99  6021.4  346.05    6032  345.15  6041.7  346.01    6228  346.71
#Mann= 8 ,-1 , 0
  2643.6     .05       0  3302.8     .05       0  3459.3     .05       0
  4845.1     .04       0  4859.7     .05       0    5480     .05       0
  5584.6     .05       0  5931.7     .05       0
Bank Sta=4845.1,4859.7
XS Rating Curve= 0 ,0
Exp/Cntr=0.3,0.1

Type RM Length L Ch R = 1 ,1730    ,1205,1205,1205
BEGIN DESCRIPTION:
Mapping XS 77212448
END DESCRIPTION:
XS GIS Cut Line= 4
      2701619.34      6863654.06      2699897.56        6865008.
       2699864.3      6865180.43      2700517.89      6866776.75
#Sta/Elev= 30
    2755  350.78  3360.1  347.07  3687.9  346.74  3724.3  347.31    3774  346.77
  3838.1  347.29    4037  346.23  4208.6  346.62  4272.8  347.41  4308.1  346.13
  4372.2     345    4393  345.41  4428.3  344.67  4958.6  344.23  4966.7  344.06
    4967  343.56  4976.9  344.24  5477.3  344.35  6092.7  345.66  6126.5  345.18
  6136.7  345.81  6272.9   345.7  6355.8  345.01    6588  345.82  6634.4  345.17
  6694.8  346.09  6731.6  345.81  6764.1  346.99  6785.7   345.8  6845.9  346.15
#Mann= 4 ,-1 , 0
    2755     .05       0  4958.6     .04       0  4976.9     .05       0
  6092.7     .05       0
Bank Sta=4958.6,4976.9
XS Rating Curve= 0 ,0
Exp/Cntr=0.3,0.1

Type RM Length L Ch R = 1 ,525     ,0,0,0
BEGIN DESCRIPTION:
Mapping XS ad000b8f
END DESCRIPTION:
XS GIS Cut Line= 4
      2699811.55      6864430.25      2698927.36      6864743.66
      2698937.84      6864930.06      2700117.28      6865923.41
#Sta/Elev= 30
  3943.6  346.96  4087.4   343.2  4225.1  343.72  4261.3  344.29  4331.4  343.76
  4410.4  344.21  4708.6  343.32  4734.2  343.62    4765  343.43  4770.3  342.97
  4819.5  343.59  4832.1  343.06  4929.1  343.03  4945.3  341.99  4979.2  342.88
  4989.2  341.82  4996.9   340.3  4997.4   339.8  5009.2   340.7  5019.2  340.47
  5029.3  342.72  5059.3  342.44  5124.5  343.48  5181.7  343.62  5323.4  343.35
  5578.4  344.06  5699.3  343.72  5777.3  344.51  5997.1   344.2  6610.4  345.81
#Mann= 3 ,-1 , 0
  3943.6     .05       0  4979.2     .04       0  5029.3     .05       0
Bank Sta=4979.2,5029.3
XS Rating Curve= 0 ,0
Exp/Cntr=0.3,0.1

Chan Stop Cuts=-1
Use User Specified Reach Order=0
Composite Channel Slope=5