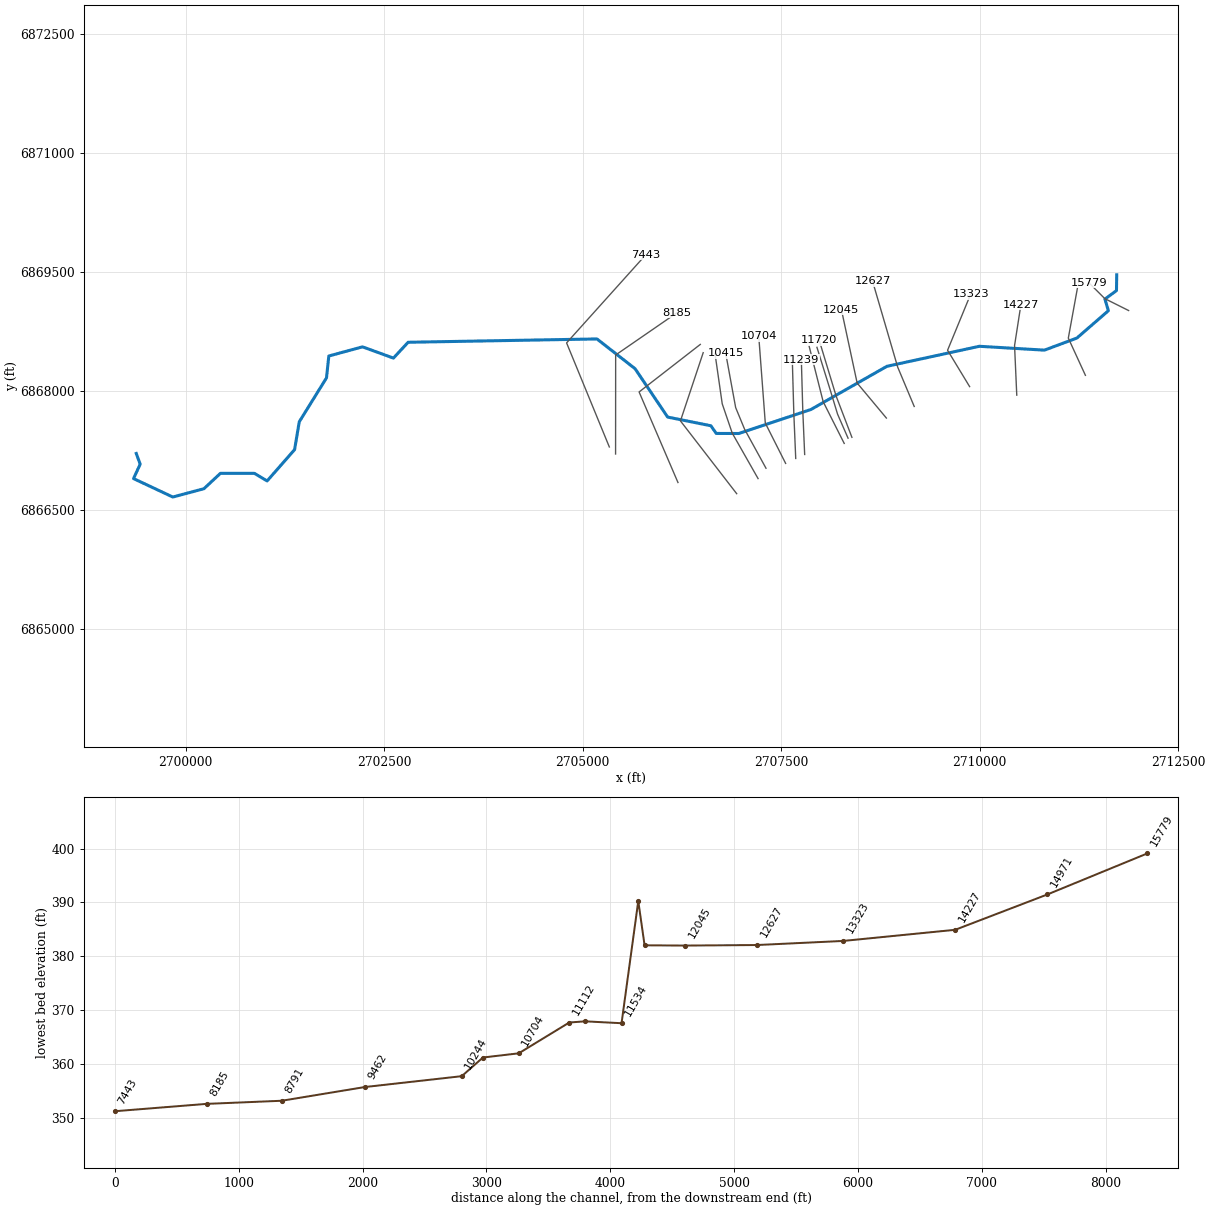
--- CCT7.prj (project) ---

Proj Title=CCT7 Base Level Engineering
Current Plan=p01
Default Exp/Contr=0.3,0.1
English Units
Geom File=g01
Flow File=f01
Plan File=p01
Y Axis Title=Elevation
X Axis Title(PF)=Main Channel Distance
X Axis Title(XS)=Station
BEGIN DESCRIPTION:
CCT7
END DESCRIPTION:
DSS File=dss
DSS Export Rating Curves= 0
DSS Export Rating Curve Sorted= 0
DSS Export Volume Flow Curves= 0
DXF OffsetX= 0
DXF OffsetY= 0
DXF ScaleX= 1
DXF ScaleY= 10

--- CCT7.p01 (plan) ---

Plan Title=Multiple Run
Program Version=4.10
Short Identifier=Multiple Run
Geom File=g01
Flow File=f01
Subcritical Flow
K Sum by GR= 0
Std Step Tol= 0.01
Critical Tol= 0.01
Num of Std Step Trials= 20
Max Error Tol= 0.3
Flow Tol Ratio= 0.001
Split Flow NTrial= 30
Split Flow Tol= 0.02
Split Flow Ratio= 0.02
Log Output Level= 0
Friction Slope Method= 1
Unsteady Friction Slope Method= 2
Unsteady Bridges Friction Slope Method= 1
Parabolic Critical Depth
Global Vel Dist= 1 , 1 , 1
Global Log Level= 0
CheckData=True
Encroach Param=-1 ,0,0, 0
BEGIN DESCRIPTION:
Multiple Run
END DESCRIPTION:
Computation Interval=1HOUR
Output Interval=1HOUR
Run HTab= 0
Run UNet= 0
Run PostProcess= 0
Run WQNet= 0
UNET Theta= 1
UNET Theta Warmup= 1
UNET ZTol= 0.02
UNET ZSATol= 0.05
UNET MxIter= 20
UNET MaxInSteps= 0
UNET DtIC= 0
UNET DtMin= 0
UNET MaxCRTS= 20
UNET WFStab= 2
UNET SFStab= 1
UNET WFX= 1
UNET SFX= 1
UNET DSS MLevel= 4
UNET DZMax Abort= 100
UNET Convert EG Bridges= 0
UNET Use Existing IB Tables=-1
UNET Froude Reduction=False
UNET Froude Limit= 1
UNET Froude Power= 10
UNET Time Slicing=0,0, 5
UNET Junction Losses=0
Instantaneous Interval=1HOUR
DSS File=dss
Write IC File= 0
Write IC File at Sim End=0
Echo Input=False
Echo Parameters=False
Echo Output=False
Write Detailed= 0
WQ AD Non Conservative
WQ ULTIMATE=-1
WQ Max Comp Step=1HOUR
WQ Output Interval=15MIN
WQ Output Selected Increments= 0
WQ Output face flow=0
WQ Output face velocity=0
WQ Output face area=0
WQ Output face dispersion=0
WQ Output cell volume=0
WQ Output cell surface area=0
WQ Output cell continuity=0
WQ Output cumulative cell continuity=0
WQ Output face conc=0
WQ Output face dconc_dx=0
WQ Output face courant=0
WQ Output face peclet=0
WQ Output face adv mass=0
WQ Output face disp mass=0
WQ Output cell mass=0
WQ Output cell source sink temp=0
WQ Output cell source sink nsm=0
WQ Output MaxMinRange=-1
WQ Daily Max Min Mean=-1
WQ Daily Range=0
WQ Daily Time=0
WQ Create Restart=0
WQ Fixed Restart=0
WQ System Summary=0
WQ Use Fixed Temperature=0
Sorting and Armoring Iterations= 10
XS Update Threshold= 0.02
Hydraulics Update Threshold= 0.02
Energy Slope Method= 1
Volume Change Method= 0
XS Weighting Method= 0
Number of US Weighted Cross Sections= 1
Number of DS Weighted Cross Sections= 1
Upstream XS Weight=0.25
Main XS Weight=0.5
Downstream XS Weight=0.25
Number of DS XS's Weighted with US Boundary= 1
Upstream Boundary Weight= 1
Weight of XSs Associated with US Boundary= 0
Number of US XS's Weighted with DS Boundary= 1
Downstream Boundary Weight= 0.5
Weight of XSs Associated with DS Boundary= 0.5
Sediment Output Level= 4
Mass or Volume Output= 0
Output Increment Type= 1
Profile and TS Output Increment= 10
XS Output Flag= 0
XS Output Increment= 10
Disregard all LS=0
Disregard all Conn=0
Disregard all Breaches=0
Disregard all Pumps=0

--- CCT7.f01 (steady flow) ---

Flow Title=Multiple
Number of Profiles=7
Profile Names=10-year,25-year,50-year,1pct_min,100-year,1pct_plu,500-year
River Rch & RM= CCT7,Reach-1,15779
     463     610     727     430     859    1714    1197
River Rch & RM= CCT7,Reach-1,11669
     614     824     993     594    1185    2365    1687
Boundary for River Rch & Prof#=CCT7,Reach-1,1
Up Type=0
Dn Type=3
Dn Slope=0.005
Boundary for River Rch & Prof#=CCT7,Reach-1,2
Up Type=0
Dn Type=3
Dn Slope=0.005
Boundary for River Rch & Prof#=CCT7,Reach-1,3
Up Type=0
Dn Type=3
Dn Slope=0.005
Boundary for River Rch & Prof#=CCT7,Reach-1,4
Up Type=0
Dn Type=3
Dn Slope=0.005
Boundary for River Rch & Prof#=CCT7,Reach-1,5
Up Type=0
Dn Type=3
Dn Slope=0.005
Boundary for River Rch & Prof#=CCT7,Reach-1,6
Up Type=0
Dn Type=3
Dn Slope=0.005
Boundary for River Rch & Prof#=CCT7,Reach-1,7
Up Type=0
Dn Type=3
Dn Slope=0.005

--- CCT7.g01 (geometry) ---

Geom Title=Existing Conditions
Program Version=4.10

River Reach=CCT7            ,Reach-1
Reach XY= 30
        2711726.        6869461.      2711722.96      6869262.42
      2711577.55      6869155.15      2711620.91       6869008.7
       2711224.5      6868664.61       2710815.5       6868512.2
       2709996.3      6868560.72      2708831.94      6868308.74
       2707874.5      6867764.62       2706965.5      6867462.22
      2706681.68      6867463.01      2706613.97       6867559.8
      2706069.83      6867668.86      2705659.62       6868278.1
      2705179.42       6868653.2      2702800.79      6868611.33
      2702615.57      6868412.03       2702226.1      6868553.69
      2701801.97      6868438.35      2701772.45      6868162.47
      2701429.54      6867609.54      2701370.46      6867258.58
      2701024.43      6866864.43      2700865.71        6866960.
      2700436.62       6866960.4      2700228.43      6866766.52
      2699836.44      6866662.04      2699342.28      6866894.29
      2699425.97      6867076.38        2699376.        6867211.

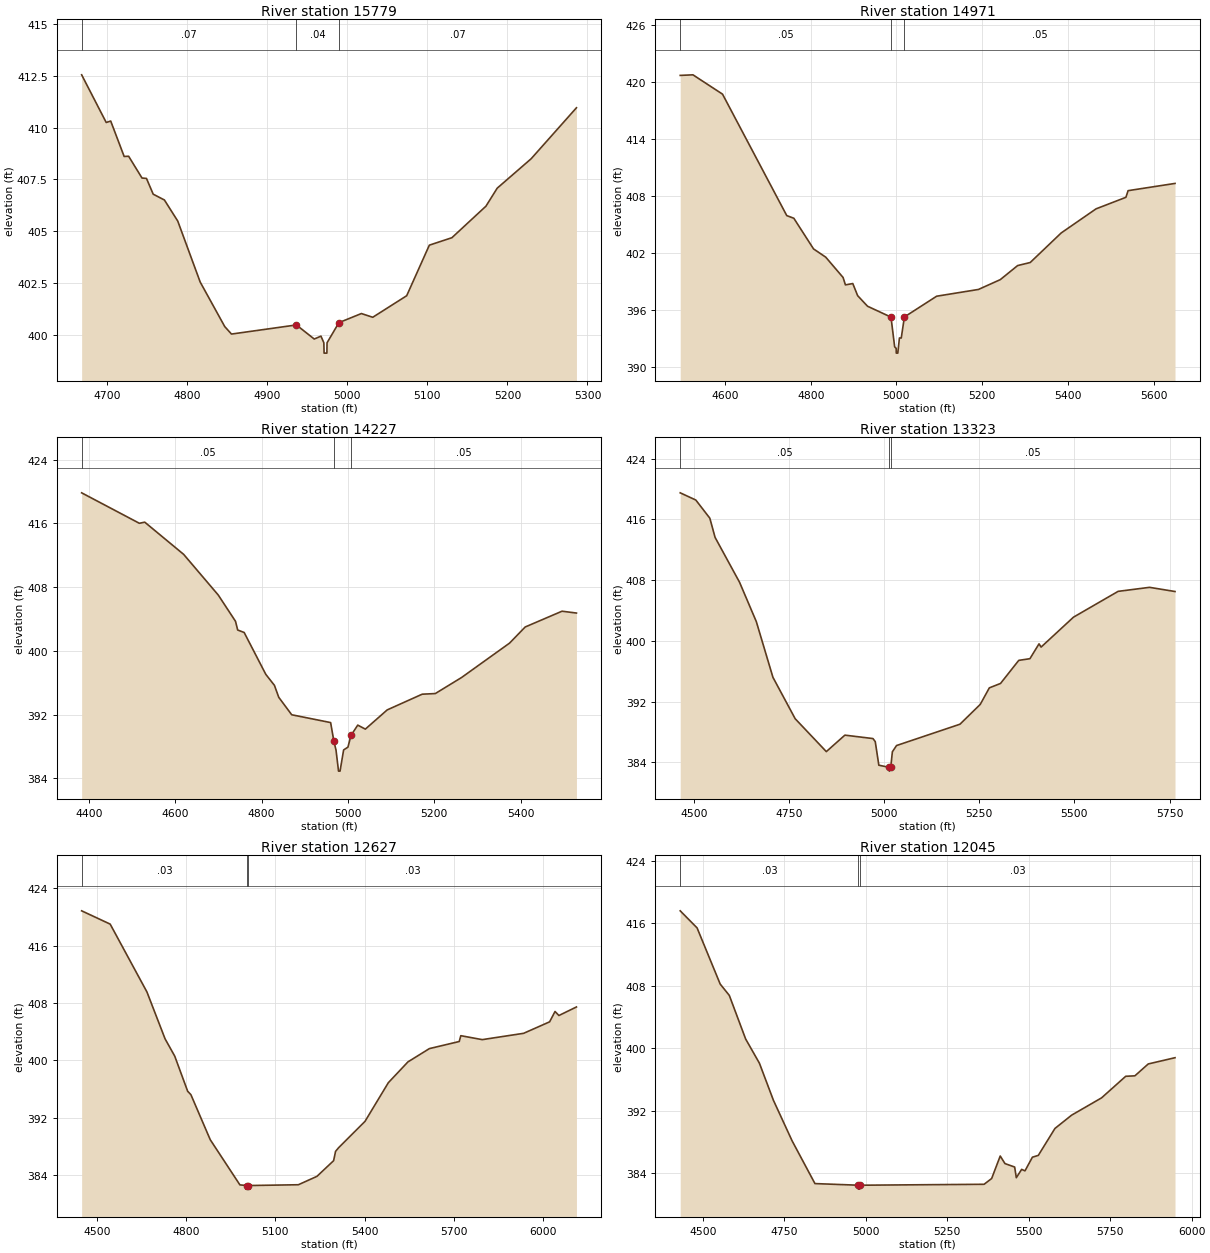
Type RM Length L Ch R = 1 ,15779   ,808,808,808
BEGIN DESCRIPTION:
CCT7 23.0
END DESCRIPTION:
XS GIS Cut Line= 3
      2711875.96      6869011.02        2711576.        6869161.
      2711376.01      6869360.99
#Sta/Elev= 30
    4668  412.55  4698.7  410.25  4704.3  410.32  4721.1  408.61  4726.7  408.62
  4743.4  407.57    4749  407.55  4757.4  406.79  4771.4  406.51  4788.1  405.49
  4816.1  402.55  4846.8   400.4  4855.2  400.04  4936.3  400.48  4958.6   399.8
    4967  399.94  4970.6  399.62  4970.9  399.12  4974.4  399.12  4974.6  399.62
  4989.4  400.59  5017.5  401.03  5031.7  400.85  5074.1  401.89  5102.4  404.33
  5130.6  404.69  5173.1  406.21  5187.2  407.08  5229.6   408.5  5286.2  410.96
#Mann= 3 ,-1 , 0
    4668     .07       0  4936.3     .04       0  4989.4     .07       0
Bank Sta=4936.3,4989.4
XS Rating Curve= 0 ,0
Exp/Cntr=0.3,0.1

Type RM Length L Ch R = 1 ,14971   ,744,744,744
BEGIN DESCRIPTION:
Mapping XS f1dd4682
END DESCRIPTION:
XS GIS Cut Line= 3
      2711331.62      6868195.05      2711116.35      6868663.78
      2711230.93      6869292.22
#Sta/Elev= 30
  4495.5  420.66  4525.2  420.72  4594.2  418.69  4744.1  405.93  4760.6  405.65
  4806.6  402.43  4835.1  401.56  4875.5  399.43    4881  398.65  4898.2  398.79
  4909.5  397.52  4932.5  396.41 4987.32 395.263  4995.9  392.14  4999.4  391.98
  4999.7  391.48  5003.2  391.48    5007  393.07  5011.3  393.07  5018.6  395.28
  5093.9  397.46  5191.4  398.17  5242.3   399.2  5282.9  400.68  5312.2     401
  5384.6  404.11  5465.9  406.64  5535.5  407.85  5540.6  408.55  5650.1  409.31
#Mann= 3 ,-1 , 0
  4495.5     .05       0 4987.32     .04       0  5018.6     .05       0
Bank Sta=4987.32,5018.6
XS Rating Curve= 0 ,0
Exp/Cntr=0.3,0.1

Type RM Length L Ch R = 1 ,14227   ,904,904,904
BEGIN DESCRIPTION:
Mapping XS 3d2d0366
END DESCRIPTION:
XS GIS Cut Line= 3
      2710467.04      6867945.05      2710439.27      6868570.03
      2710519.13      6869083.96
#Sta/Elev= 30
  4383.4  419.82    4517     416  4529.5  416.14  4619.6   412.1  4699.7     407
  4739.7   403.7  4744.7  402.61  4759.7   402.3  4809.8  397.05  4829.8  395.67
  4839.8  394.17  4869.8  391.98  4959.9     391  4967.4  388.67  4972.4  387.54
  4978.2  384.91  4981.7  384.91    4990  387.57    5000  387.92    5007  389.38
  5022.7  390.68  5040.3  390.18  5090.9  392.59  5171.9  394.56  5202.3  394.64
    5263  396.65  5374.3  400.97  5410.4  402.99  5495.7  404.97  5529.1  404.74
#Mann= 3 ,-1 , 0
  4383.4     .05       0  4967.4     .04       0    5007     .05       0
Bank Sta=4967.4,5007
XS Rating Curve= 0 ,0
Exp/Cntr=0.3,0.1

Type RM Length L Ch R = 1 ,13323   ,696,696,696
BEGIN DESCRIPTION:
Mapping XS edf5d1ad
END DESCRIPTION:
XS GIS Cut Line= 3
      2709873.29      6868052.68      2709595.52        6868511.
      2709886.51      6869217.71
#Sta/Elev= 30
  4464.2   419.5  4505.2  418.55    4542  416.16  4555.8  413.63  4620.1  407.72
  4664.2  402.53  4707.8   395.2  4766.3  389.74  4848.1  385.41  4896.9  387.58
  4970.6  387.13  4976.7  386.73  4986.1  383.62  5013.4  383.34  5013.7  382.84
  5017.4  383.34  5021.7  385.39  5032.6  386.21  5199.3  389.02  5252.6  391.63
  5276.5  393.81  5305.9  394.39  5353.8  397.43  5383.1  397.65  5407.1  399.61
  5412.5  399.18  5497.6  403.12  5614.9  406.52  5697.5  407.05  5764.4   406.5
#Mann= 3 ,-1 , 0
  4464.2     .05       0  5013.4     .03       0  5017.4     .05       0
Bank Sta=5013.4,5017.4
XS Rating Curve= 0 ,0
Exp/Cntr=0.3,0.1

Type RM Length L Ch R = 1 ,12627   ,582,582,582
BEGIN DESCRIPTION:
Mapping XS fc846004
END DESCRIPTION:
XS GIS Cut Line= 3
      2709175.39      6867802.65      2708967.04       6868299.2
      2708651.53       6869377.5
#Sta/Elev= 30
  4449.5  420.84  4545.3  418.99  4668.8  409.54  4729.7  403.01  4762.2   400.6
  4805.6  395.71  4816.4  395.24  4881.5  388.96  4981.1  382.67  5005.5  382.58
  5005.8  382.08  5009.3  382.08  5009.5  382.58  5177.4  382.69  5239.9  383.86
  5295.8  386.04  5302.4  387.34  5312.9  387.86  5401.3  391.52  5479.6   396.9
  5545.5   399.8  5617.5  401.65  5717.8  402.64  5723.1  403.45  5795.1   402.9
  5934.1  403.78  6021.4  405.38  6039.6  406.82  6052.6  406.26  6111.5  407.45
#Mann= 3 ,-1 , 0
  4449.5     .03       0  5005.5     .03       0  5009.5     .03       0
Bank Sta=5005.5,5009.5
XS Rating Curve= 0 ,0
Exp/Cntr=0.3,0.1

Type RM Length L Ch R = 1 ,12045   ,325,325,325
BEGIN DESCRIPTION:
Mapping XS a8e8a4f4
END DESCRIPTION:
XS GIS Cut Line= 3
       2708824.7      6867656.81      2708456.63      6868097.81
      2708258.71      6869021.42
#Sta/Elev= 30
    4430  417.62  4481.8  415.43  4552.7  408.24  4580.7  406.79  4630.8  401.21
  4673.1  398.11  4716.1  393.36  4773.4  388.17  4843.6  382.69    4977  382.48
  4977.2  381.98  4980.7  381.98    4981  382.48  5362.9   382.6  5386.1  383.34
  5412.4  386.22    5427  385.25  5456.7  384.81  5461.8  383.44  5478.1  384.51
  5488.4  384.32  5511.2  386.07  5529.3   386.3  5580.4  389.75  5631.5  391.45
  5723.6  393.67  5797.6  396.43  5825.8  396.49  5866.8  398.01    5949  398.81
#Mann= 3 ,-1 , 0
    4430     .03       0    4977     .03       0    4981     .03       0
Bank Sta=4977,4981
XS Rating Curve= 0 ,0
Exp/Cntr=0.3,0.1

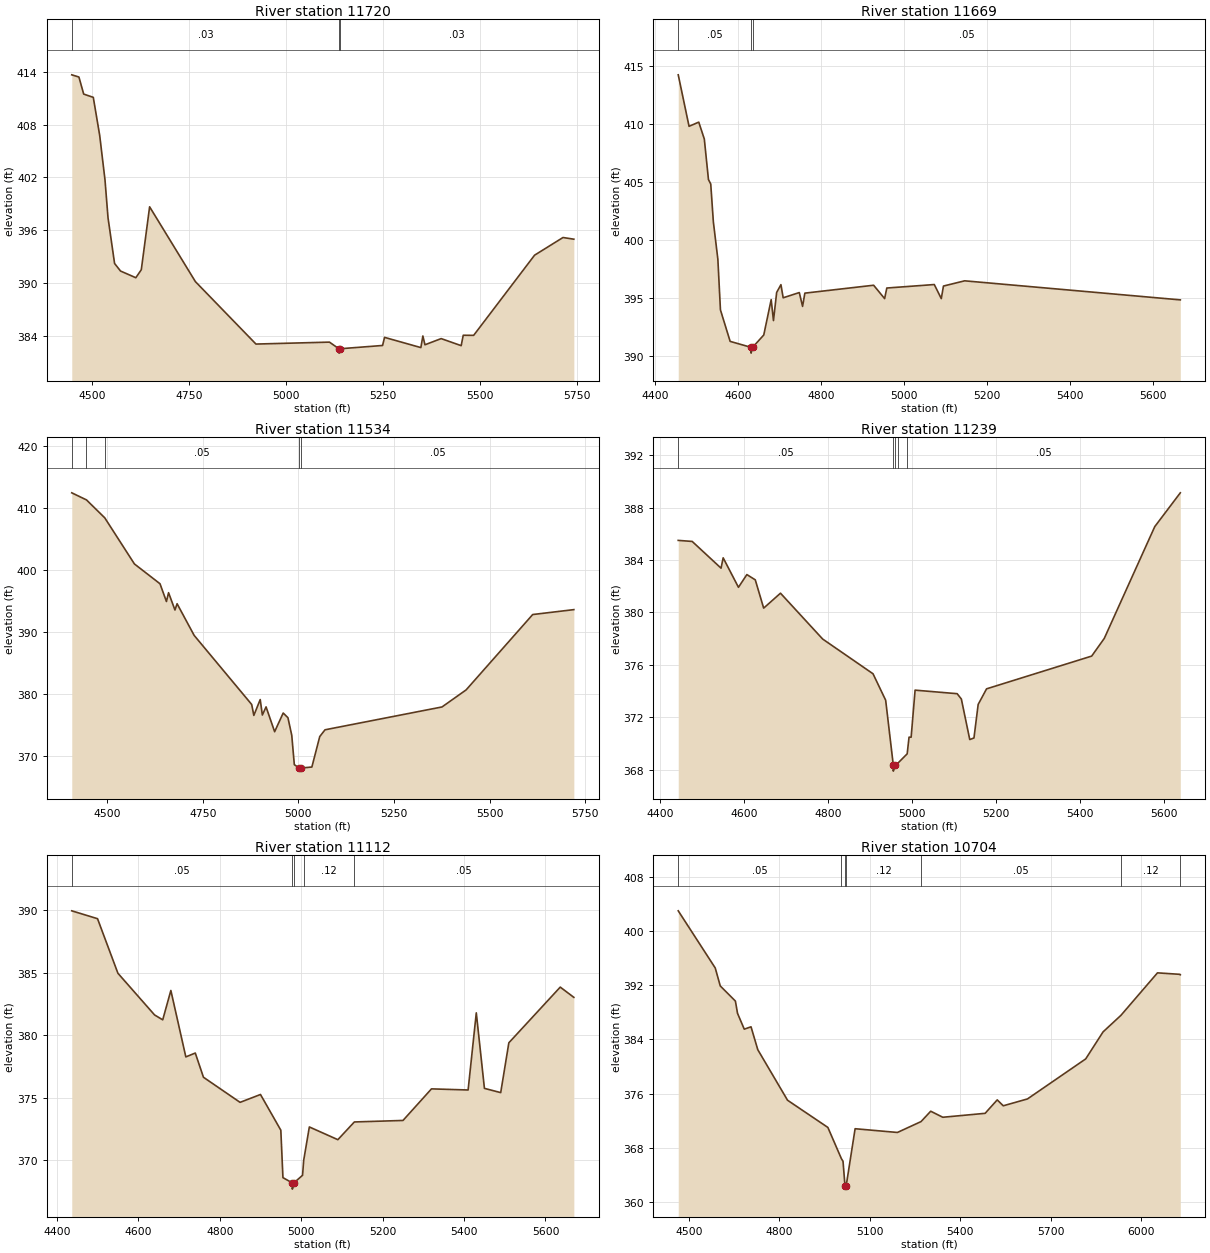
Type RM Length L Ch R = 1 ,11720   ,51,51,51
BEGIN DESCRIPTION:
Mapping XS ff5e2539
END DESCRIPTION:
XS GIS Cut Line= 3
      2708390.64      6867413.82      2708192.74      6867931.14
      2707977.99      6868637.74
#Sta/Elev= 30
  4448.6  413.66    4467  413.41  4479.3  411.47    4504   411.1  4520.5  406.77
  4534.1  401.73  4541.9  397.42  4558.8  392.22  4574.1  391.36  4613.5   390.6
  4627.6  391.51    4649  398.66  4766.8  390.16  4922.7  383.06  5111.9  383.28
  5136.2  382.53  5136.5  382.03  5140.2  382.53  5248.6   382.9  5253.8  383.82
  5347.2  382.66  5352.4  383.98  5357.7  382.98  5399.5  383.68    5451  382.88
  5456.3  384.06  5483.1  384.05  5639.9  393.16  5713.1  395.17    5741  394.98
#Mann= 3 ,-1 , 0
  4448.6     .03       0  5136.2     .03       0  5140.2     .03       0
Bank Sta=5136.2,5140.2
XS Rating Curve= 0 ,0
Exp/Cntr=0.3,0.1

Type RM Length L Ch R = 1 ,11669   ,135,135,135
BEGIN DESCRIPTION:
Mapping XS c8c50dca
END DESCRIPTION:
XS GIS Cut Line= 4
      2708342.03       6867403.4       2708210.1      6867705.45
      2708112.88      6868024.89      2707950.17      6868547.64
#Sta/Elev= 30
  4455.6   414.2  4481.7  409.77  4505.1  410.13  4518.5  408.68  4528.5  405.19
    4534  404.81  4540.3  401.56  4551.2  398.33  4557.4  393.98  4580.8  391.27
    4631  390.76  4631.3  390.26    4635  390.76  4661.9  391.82  4679.8  394.86
  4685.3  393.06    4693  395.48  4703.3  396.15  4708.7  395.02  4747.6  395.47
  4755.5  394.28    4761  395.42  4926.9   396.1  4953.4  394.95  4958.7  395.86
  5073.2  396.16  5090.1  394.95  5095.3  396.03  5146.5  396.48  5666.6  394.84
#Mann= 3 ,-1 , 0
  4455.6     .05       0    4631     .05       0    4635     .05       0
Bank Sta=4631,4635
XS Rating Curve= 0 ,0
Exp/Cntr=0.3,0.1

Type RM Length L Ch R = 1 ,11534   ,295,295,295
BEGIN DESCRIPTION:
Mapping XS 5366fabd
END DESCRIPTION:
XS GIS Cut Line= 3
      2708293.57       6867337.2      2708028.84      6867862.33
      2707850.93      6868565.28
#Sta/Elev= 30
  4407.2  412.38  4445.7  411.24  4493.5  408.35  4571.1  400.92    4638  397.73
  4654.8  394.87  4660.4  396.29  4677.1   393.5  4682.7  394.51  4727.3  389.41
  4877.8  378.28  4883.4  376.52  4900.1  379.07  4905.7  376.58  4915.4  377.89
  4937.8  373.89  4960.2   376.9  4972.6  376.15  4982.6  373.31  4989.3  368.58
  5002.2  368.04  5002.5  367.54  5006.2  368.04  5035.2   368.2  5055.8  373.11
  5069.6   374.2  5375.6  377.88  5438.7  380.63  5612.8  392.77  5720.4  393.56
#Mann= 5 ,-1 , 0
  4407.2     .05       0  4445.7     .12       0  4493.5     .05       0
  5002.2     .04       0  5006.2     .05       0
Bank Sta=5002.2,5006.2
XS Rating Curve= 0 ,0
Exp/Cntr=0.3,0.1

Type RM Length L Ch R = 1 ,11239   ,127,127,127
BEGIN DESCRIPTION:
Mapping XS 6ae937b7
END DESCRIPTION:
XS GIS Cut Line= 3
      2707795.52      6867197.88      2707771.97       6867747.2
      2707753.59      6868391.81
#Sta/Elev= 30
  4443.4   385.5  4476.6  385.42  4545.3  383.38  4550.3  384.17  4586.7  381.92
  4606.7  382.89  4626.7  382.49  4646.7  380.33  4686.7  381.47  4787.1  377.97
  4906.9  375.32    4937   373.3    4955  368.39  4955.2  367.89    4959  368.39
  4965.8  368.49  4988.2  369.21  4992.6  370.48  4997.6  370.48    5007  374.07
  5107.1   373.8  5117.1  373.39  5137.1   370.3  5147.1  370.42  5157.1  372.98
  5177.1  374.17  5427.2  376.67  5457.2  378.02  5577.3  386.55  5638.1  389.13
#Mann= 5 ,-1 , 0
  4443.4     .05       0    4955     .04       0    4959     .05       0
  4965.8     .12       0  4988.2     .05       0
Bank Sta=4955,4959
XS Rating Curve= 0 ,0
Exp/Cntr=0.3,0.1

Type RM Length L Ch R = 1 ,11112   ,408,408,408
BEGIN DESCRIPTION:
Mapping XS 70eafd2c
END DESCRIPTION:
XS GIS Cut Line= 3
      2707682.91      6867147.73      2707658.97      6867714.32
      2707640.09      6868380.65
#Sta/Elev= 30
  4436.1  389.96  4499.4  389.33  4549.5  384.96  4639.6  381.62  4659.6  381.23
  4679.6  383.58  4716.4  378.26  4739.6  378.57  4759.7  376.63  4849.7  374.62
  4899.8  375.25  4949.8  372.39    4955  368.59  4977.9  368.17  4978.1  367.67
  4981.9  368.17  5003.2  368.78    5006  369.98  5019.9  372.65  5089.9  371.63
  5130.5  373.05    5250  373.17    5320   375.7    5410  375.61  5430.1  381.79
  5450.1  375.74  5490.1   375.4  5510.1  379.39  5636.4  383.85  5669.8  383.03
#Mann= 5 ,-1 , 0
  4436.1     .05       0  4977.9     .05       0  4981.9     .05       0
    5006     .12       0  5130.5     .05       0
Bank Sta=4977.9,4981.9
XS Rating Curve= 0 ,0
Exp/Cntr=0.3,0.1

Type RM Length L Ch R = 1 ,10704   ,289,289,289
BEGIN DESCRIPTION:
Mapping XS 4dad7f0a
END DESCRIPTION:
XS GIS Cut Line= 3
      2707555.75      6867085.41      2707299.67      6867593.23
      2707217.24       6868686.5
#Sta/Elev= 30
  4464.8  402.95  4587.5  394.53  4604.2  391.88  4654.4  389.65  4661.4  387.85
  4683.8  385.51  4706.2  385.86  4728.6  382.49  4827.3  375.04  4961.1  371.03
  5005.8  366.44  5011.3  366.04  5017.8  362.44  5018.1  361.94  5021.8  362.44
  5051.4  370.84  5191.7  370.29    5270  371.89  5302.1  373.42  5342.2  372.53
  5482.6  373.11  5522.7  375.09  5542.7  374.22    5623  375.23  5816.2  381.13
  5873.7  385.11    5933  387.55  6054.2  393.81    6129  393.59  6129.9  393.53
#Mann= 7 ,-1 , 0
  4464.8     .05       0  5005.8     .12       0  5017.8     .04       0
  5021.8     .12       0    5270     .05       0    5933     .12       0
    6129     .05       0
Bank Sta=5017.8,5021.8
XS Rating Curve= 0 ,0
Exp/Cntr=0.3,0.1

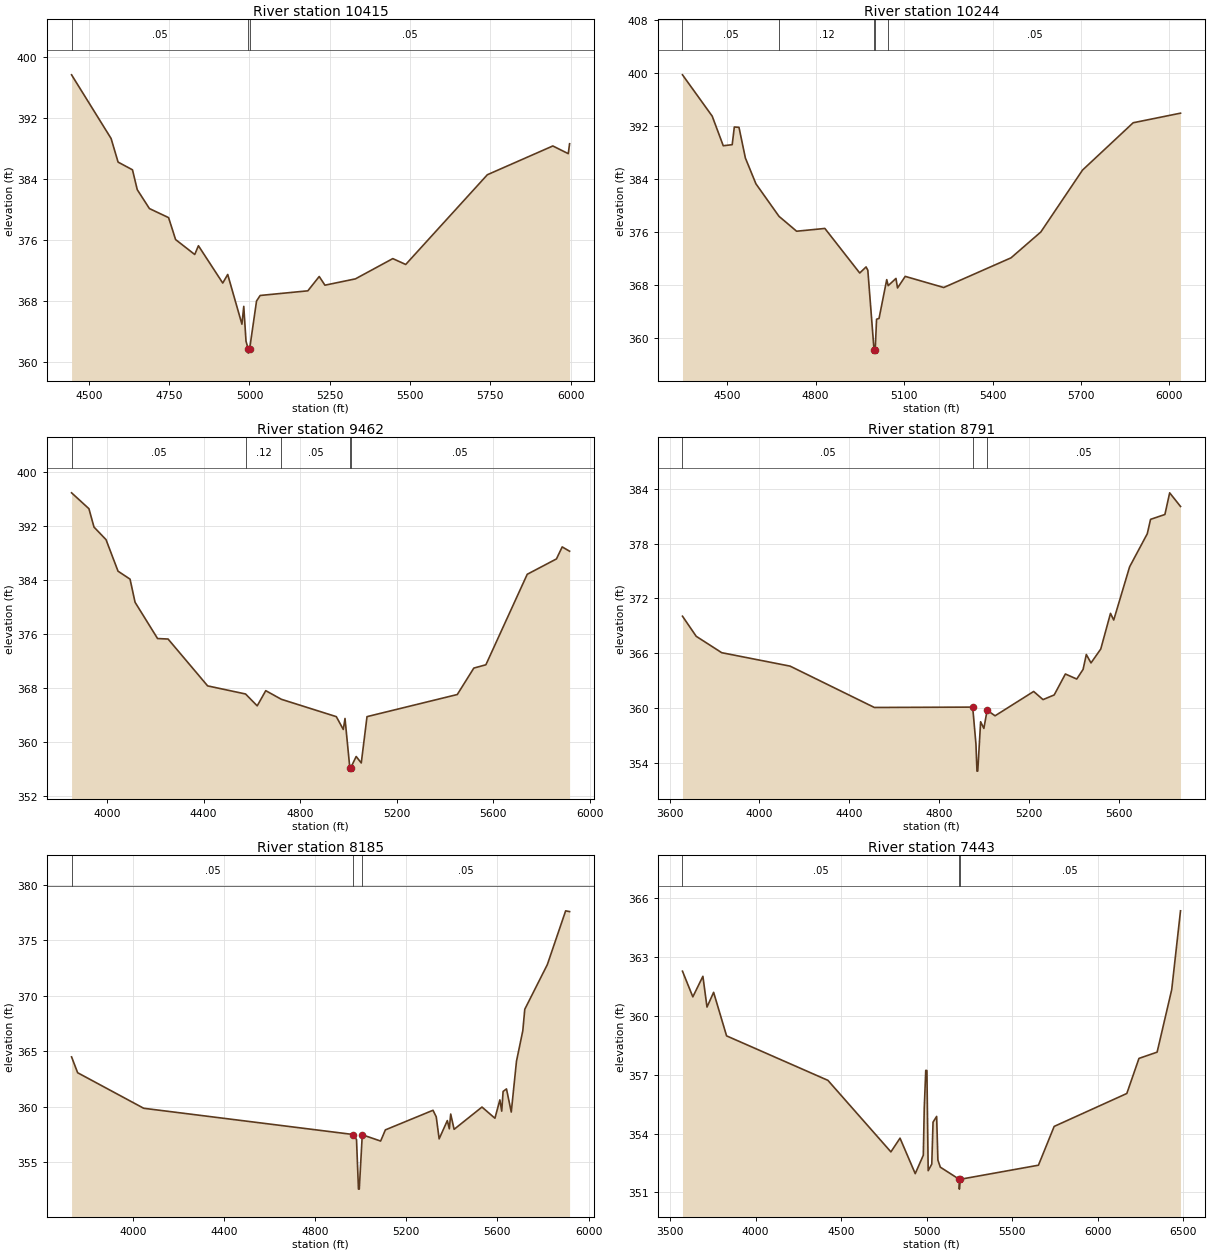
Type RM Length L Ch R = 1 ,10415   ,171,171,171
BEGIN DESCRIPTION:
Mapping XS deabc150
END DESCRIPTION:
XS GIS Cut Line= 4
      2707308.33      6867024.69      2707039.25      6867515.11
      2706926.41      6867788.55      2706800.78      6868473.02
#Sta/Elev= 30
    4446   397.7  4569.1  389.34  4590.9  386.24  4635.7  385.23  4650.6  382.62
  4688.5  380.14  4748.2  378.95    4770  376.07  4829.6  374.11  4841.1  375.26
  4916.9  370.36  4932.3  371.49  4976.6  364.96  4982.3   367.3  4989.3  362.73
  4996.4  361.66  4996.6  361.16  5000.4  361.66  5022.1     368  5033.4  368.73
  5181.9  369.34  5217.3  371.22  5235.1  370.08  5330.1  370.91  5446.5  373.57
  5486.7   372.8  5740.9  384.58  5944.9  388.36  5992.9  387.35  5997.1  388.65
#Mann= 3 ,-1 , 0
    4446     .05       0  4996.4     .05       0  5000.4     .05       0
Bank Sta=4996.4,5000.4
XS Rating Curve= 0 ,0
Exp/Cntr=0.3,0.1

Type RM Length L Ch R = 1 ,10244   ,782,782,782
BEGIN DESCRIPTION:
Mapping XS 2c91bf44
END DESCRIPTION:
XS GIS Cut Line= 4
      2707208.54      6866894.42        2706883.      6867467.37
      2706757.14      6867836.29      2706665.99      6868469.99
#Sta/Elev= 30
  4348.5  399.72  4449.3  393.48  4486.8  389.01  4517.1  389.17  4524.3  391.84
  4540.1  391.79  4561.8  387.16  4597.6  383.26  4675.8  378.35  4735.6   376.1
  4831.4  376.52  4949.6  369.79  4971.2  370.71  4977.1   370.2  4998.1  358.19
  4998.4  357.69  5002.1  358.19  5006.7  362.81  5015.1  362.93  5041.2  368.79
  5046.1  367.88  5072.5  368.97  5077.8  367.53  5103.9  369.28  5234.5   367.6
  5462.7  372.08  5563.7  375.98  5705.1  385.33  5876.9  392.48  6037.5  393.93
#Mann= 5 ,-1 , 0
  4348.5     .05       0  4675.8     .12       0  4998.1     .07       0
  5002.1     .12       0  5046.1     .05       0
Bank Sta=4998.1,5002.1
XS Rating Curve= 0 ,0
Exp/Cntr=0.3,0.1

Type RM Length L Ch R = 1 ,9462    ,671,671,671
BEGIN DESCRIPTION:
Mapping XS 51aa4606
END DESCRIPTION:
XS GIS Cut Line= 3
      2706939.21      6866704.13      2706230.88      6867620.79
      2706517.33      6868480.16
#Sta/Elev= 30
  3852.6  396.94  3924.5  394.59  3945.6  391.86  3995.4     390  4045.2  385.32
    4095  384.14  4115.8  380.71  4209.1  375.33  4252.6  375.26  4416.6  368.31
  4573.7  367.11  4622.1  365.35  4657.5   367.6  4722.3  366.32  4949.9  363.75
  4978.9  361.85    4986  363.48  5005.9  356.17  5006.2  355.67  5009.9  356.17
  5032.3  357.84  5053.4  356.88  5077.2  363.75  5451.4  367.03  5519.9  370.95
  5569.9  371.44  5741.3  384.86  5862.5  387.14  5886.2  388.92  5916.9  388.28
#Mann= 5 ,-1 , 0
  3852.6     .05       0  4573.7     .12       0  4722.3     .05       0
  5005.9     .04       0  5009.9     .05       0
Bank Sta=5005.9,5009.9
XS Rating Curve= 0 ,0
Exp/Cntr=0.3,0.1

Type RM Length L Ch R = 1 ,8791    ,606,606,606
BEGIN DESCRIPTION:
Mapping XS 0e7ceb43
END DESCRIPTION:
XS GIS Cut Line= 3
      2706199.63      6866844.76      2705710.04      6867985.38
      2706480.85      6868584.31
#Sta/Elev= 30
  3657.5  370.06  3718.7  367.86  3832.2  366.07  4136.7   364.6  4511.9  360.08
  4949.6  360.12  4964.1  356.08  4968.7  353.12  4972.2  353.12  4984.9  358.52
  4999.4  357.79  5013.9  359.78  5049.2  359.17  5221.1  361.83  5262.8  360.94
  5312.5  361.45  5362.3  363.74  5412.9  363.19  5441.1  364.24  5455.5  365.87
  5476.4  364.95  5519.8  366.47  5563.2  370.37  5577.5  369.64  5648.3  375.46
    5727  379.08  5741.5  380.65  5805.4  381.18  5826.6  383.55  5874.9  382.06
#Mann= 3 ,-1 , 0
  3657.5     .05       0  4949.6     .04       0  5013.9     .05       0
Bank Sta=4949.6,5013.9
XS Rating Curve= 0 ,0
Exp/Cntr=0.3,0.1

Type RM Length L Ch R = 1 ,8185    ,742,742,742
BEGIN DESCRIPTION:
Mapping XS da9b84e7
END DESCRIPTION:
XS GIS Cut Line= 3
      2705413.84      6867204.25      2705414.83      6868451.12
      2706187.95      6868983.92
#Sta/Elev= 30
  3731.2  364.48  3757.9  363.05  4047.9  359.84  4967.9  357.47  4981.8  357.01
  4990.4  352.54  4993.9  352.54  5007.1  357.45  5087.6  356.88  5108.5  357.89
  5317.5  359.66  5331.7  359.07  5344.5  357.08  5380.4  358.73  5389.2  357.99
  5395.2  359.32  5410.1  357.94  5532.5  359.95  5589.3  358.94    5611   360.6
  5619.1  359.58  5625.2  361.36    5640  361.59    5661   359.5  5683.9  364.09
  5711.7  366.85  5720.3  368.78  5819.2  372.81  5899.7  377.67    5917   377.6
#Mann= 3 ,-1 , 0
  3731.2     .05       0  4967.9     .04       0  5007.1     .05       0
#XS Ineff= 2 , 0
       0                  5317.5       0  359.66
Permanent Ineff=
       F       F
Bank Sta=4967.9,5007.1
XS Rating Curve= 0 ,0
Exp/Cntr=0.3,0.1

Type RM Length L Ch R = 1 ,7443    ,0,0,0
BEGIN DESCRIPTION:
Mapping XS 5edc8c58
END DESCRIPTION:
XS GIS Cut Line= 3
      2705335.06      6867292.63      2704796.85      6868603.43
      2705795.13      6869714.56
#Sta/Elev= 30
  3572.9  362.29  3633.4  360.98  3692.2  362.03  3716.2  360.46  3754.9  361.21
  3830.6  358.99  4422.9  356.72    4791  353.07  4844.3  353.77  4933.2  351.96
  4980.4   352.9  4985.9  355.29  4994.7  357.23  5001.4  357.22  5008.9  352.11
  5029.9  352.45  5037.3  354.59  5058.3  354.88  5065.7  352.65  5079.9  352.29
  5190.8  351.67  5191.1  351.17  5194.8  351.67  5653.3  352.39  5745.2  354.37
  6169.8  356.05  6240.8  357.84  6346.9  358.16  6432.2  361.35  6483.6  365.37
#Mann= 3 ,-1 , 0
  3572.9     .05       0  5190.8     .04       0  5194.8     .05       0
Bank Sta=5190.8,5194.8
XS Rating Curve= 0 ,0
Exp/Cntr=0.3,0.1

Chan Stop Cuts=-1
Use User Specified Reach Order=0
Composite Channel Slope=5