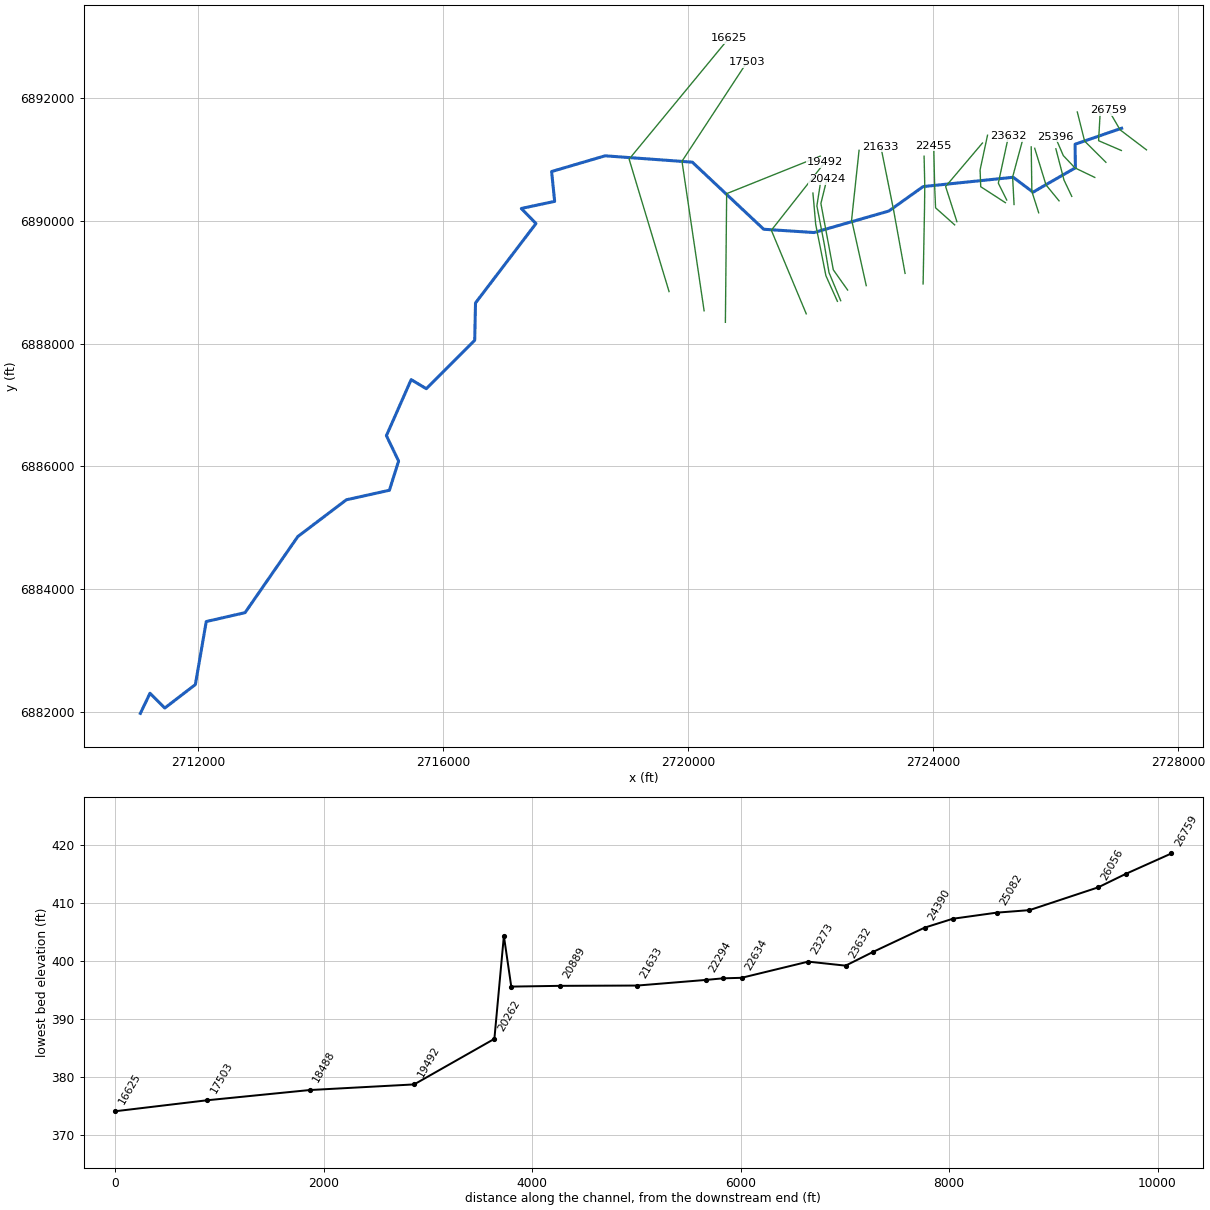
--- CCT8.prj (project) ---

Proj Title=CCT8 Base Level Engineering
Current Plan=p01
Default Exp/Contr=0.3,0.1
English Units
Geom File=g01
Flow File=f01
Plan File=p01
Y Axis Title=Elevation
X Axis Title(PF)=Main Channel Distance
X Axis Title(XS)=Station
BEGIN DESCRIPTION:
CCT8
END DESCRIPTION:
DSS Export Rating Curves= 0
DSS Export Rating Curve Sorted= 0
DSS Export Volume Flow Curves= 0
DXF OffsetX= 0
DXF OffsetY= 0
DXF ScaleX= 1
DXF ScaleY= 10

--- CCT8.p01 (plan) ---

Plan Title=Multiple Run
Short Identifier=Multiple
Geom File=g01
Flow File=f01
Subcritical Flow
K Sum by GR= 0
Std Step Tol= 0.01
Critical Tol= 0.01
Num of Std Step Trials= 20
Max Error Tol= 0.3
Flow Tol Ratio= 0.001
Split Flow NTrial= 30
Split Flow Tol= 0.02
Split Flow Ratio= 0.02
Log Output Level= 0
Friction Slope Method= 1
Unsteady Friction Slope Method= 2
Unsteady Bridges Friction Slope Method= 1
Parabolic Critical Depth
Global Vel Dist=  1 , 1 , 1
Global Log Level= 0
CheckData=True
Encroach Param= -1, 0, 0, 0
BEGIN DESCRIPTION:
Multiple Run
END DESCRIPTION:

--- CCT8.f01 (steady flow) ---

Flow Title=Multiple
Program Version=4.10
Number of Profiles= 7
Profile Names=10-year,25-year,50-year,1pct_min,100-year,1pct_plu,500-year
River Rch & RM=CCT8,Reach-1         ,26759
     471     620     738     437     872    1740    1214
River Rch & RM=CCT8,Reach-1         ,22634
     841    1153    1412     858    1712    3416    2514
River Rch & RM=CCT8,Reach-1         ,22455
    1033    1433    1767    1081    2156    4302    3208
River Rch & RM=CCT8,Reach-1         ,22294
    1148    1599    1978    1213    2420    4828    3618
River Rch & RM=CCT8,Reach-1         ,19492
    1177    1641    2030    1244    2483    4954    3713
River Rch & RM=CCT8,Reach-1         ,17503
    1229    1712    2117    1296    2586    5160    3860
Boundary for River Rch & Prof#=CCT8,Reach-1         , 1
Up Type= 0
Dn Type= 3
Dn Slope=0.005
Boundary for River Rch & Prof#=CCT8,Reach-1         , 2
Up Type= 0
Dn Type= 3
Dn Slope=0.005
Boundary for River Rch & Prof#=CCT8,Reach-1         , 3
Up Type= 0
Dn Type= 3
Dn Slope=0.005
Boundary for River Rch & Prof#=CCT8,Reach-1         , 4
Up Type= 0
Dn Type= 3
Dn Slope=0.005
Boundary for River Rch & Prof#=CCT8,Reach-1         , 5
Up Type= 0
Dn Type= 3
Dn Slope=0.005
Boundary for River Rch & Prof#=CCT8,Reach-1         , 6
Up Type= 0
Dn Type= 3
Dn Slope=0.005
Boundary for River Rch & Prof#=CCT8,Reach-1         , 7
Up Type= 0
Dn Type= 3
Dn Slope=0.005
DSS Import GetInterval= 0
DSS Import GetPeak= 0
DSS Import FillOption= 0

--- CCT8.g01 (geometry) ---

Geom Title=Existing Conditions
Program Version=4.10

River Reach=CCT8            ,Reach-1
Reach XY= 30
        2727076.        6891511.      2726315.98      6891249.77
      2726321.38      6890866.25      2725629.05      6890468.76
      2725305.94      6890711.51      2723836.46      6890559.86
        2723276.        6890161.      2722056.02      6889810.96
      2721234.48      6889864.51       2720069.5      6890957.91
      2718646.13      6891061.39      2717773.41      6890805.28
        2717823.      6890318.95      2717278.64      6890203.19
      2717518.23      6889957.59      2716531.46      6888663.45
      2716518.19      6888054.79      2715728.15      6887265.81
      2715481.37      6887413.78       2715077.1      6886500.45
      2715276.55      6886086.13        2715126.        6885611.
      2714423.57      6885455.48      2713631.11      6884855.89
      2712770.59      6883616.17      2712137.09      6883471.09
      2711959.58       6882444.2      2711460.09      6882061.53
       2711219.2      6882302.21      2711062.01       6881974.6

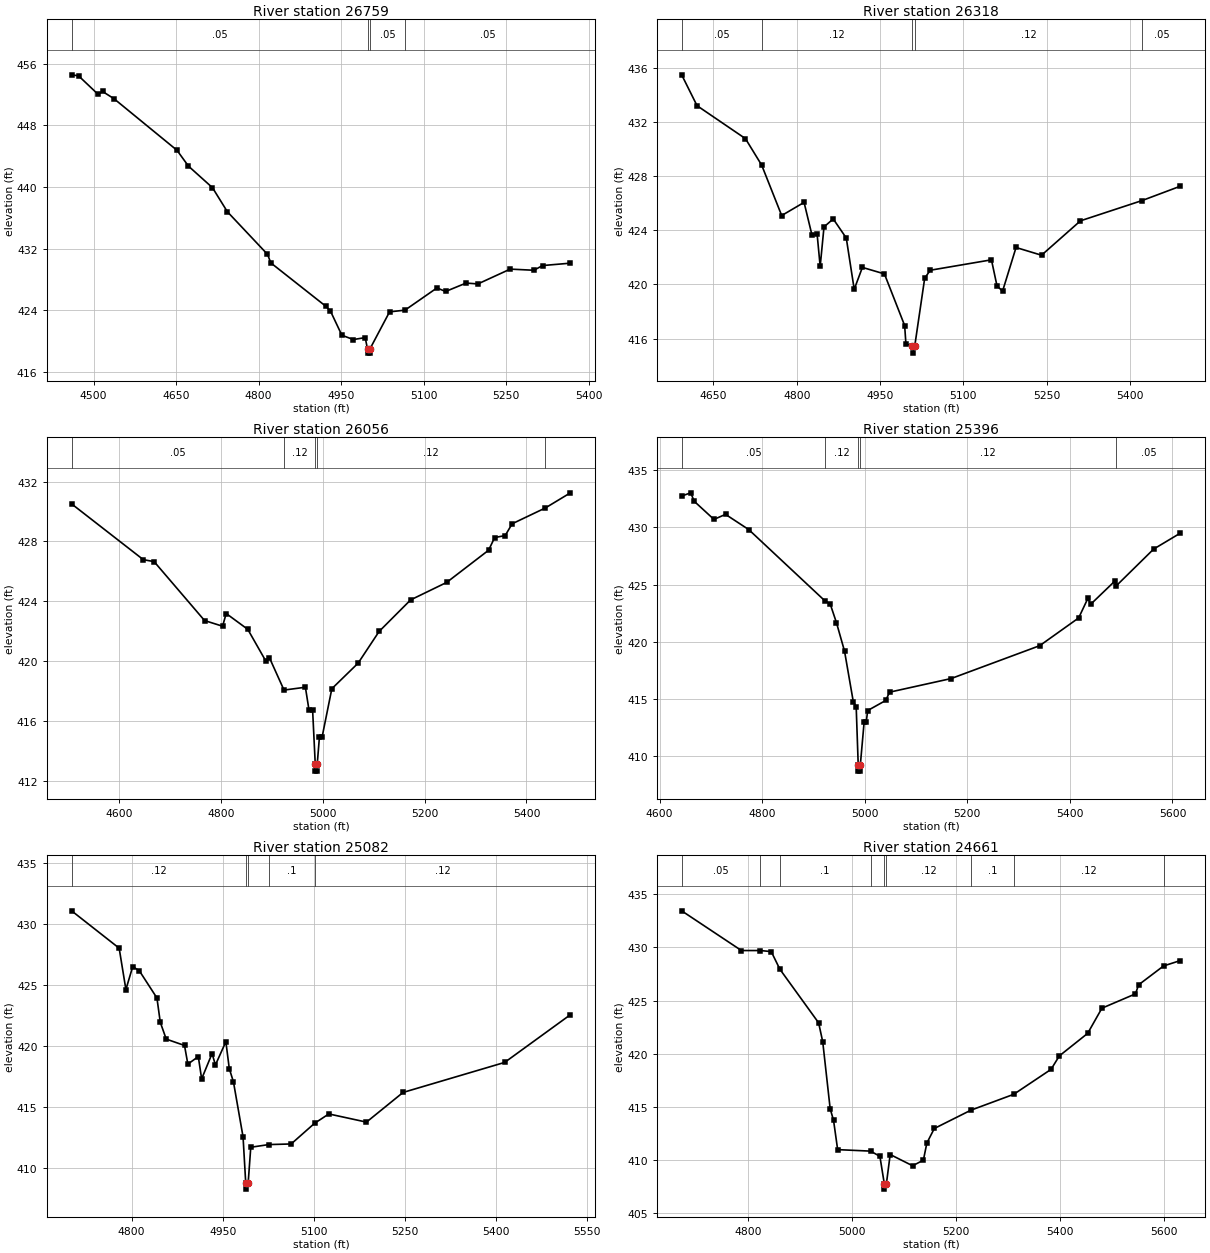
Type RM Length L Ch R = 1 ,26759   ,441,441,441
BEGIN DESCRIPTION:
CCT8 43.0
END DESCRIPTION:
XS GIS Cut Line= 3
       2727481.2      6891158.49      2727050.94      6891484.48
      2726866.34       6891801.2
#Sta/Elev= 30
  4460.2  454.54  4472.8  454.41  4508.2  452.02  4516.5  452.38  4537.3  451.44
  4651.7  444.76  4672.5  442.71  4716.2  439.91  4743.3  436.79  4816.1  431.28
  4822.3  430.16  4922.2  424.54  4930.5  423.93  4951.3  420.79  4972.1  420.23
  4993.7  420.48    4998  418.97  4998.2  418.47  5001.7  418.47    5002  418.97
    5038  423.82    5066  424.04  5124.1  426.92  5139.8  426.46    5177  427.55
  5198.5  427.44  5257.2  429.36  5300.2  429.21    5316  429.82  5366.6  430.13
#Mann= 4 ,-1 , 0
  4460.2     .05       0    4998     .07       0    5002     .05       0
    5066     .05       0
Bank Sta=4998,5002
XS Rating Curve= 0 ,0
Exp/Cntr=0.3,0.1

Type RM Length L Ch R = 1 ,26318   ,262,262,262
BEGIN DESCRIPTION:
Mapping XS 668ed22c
END DESCRIPTION:
XS GIS Cut Line= 3
      2727071.44       6891148.1      2726699.93      6891307.82
       2726727.7      6891800.84
#Sta/Elev= 30
  4592.8  435.48  4620.5   433.2  4707.6  430.77  4736.9  428.81  4772.9  425.09
  4813.2  426.06  4827.3  423.67  4836.7  423.72  4842.2  421.33  4849.1  424.25
  4865.7  424.84  4889.2  423.43  4903.5  419.64  4918.2  421.26  4957.9  420.78
  4994.3  416.97  4996.6  415.62  5008.4  415.43  5008.6  414.93  5012.4  415.43
  5030.4  420.46  5040.4  421.05  5150.6  421.82  5160.6   419.9  5170.6   419.5
  5194.9  422.73  5240.8  422.16  5310.9   424.7  5422.1   426.2    5491  427.26
#Mann= 5 ,-1 , 0
  4592.8     .05       0  4736.9     .12       0  5008.4     .07       0
  5012.4     .12       0  5422.1     .05       0
Bank Sta=5008.4,5012.4
XS Rating Curve= 0 ,0
Exp/Cntr=0.3,0.1

Type RM Length L Ch R = 1 ,26056   ,660,660,660
BEGIN DESCRIPTION:
Mapping XS a3f1930e
END DESCRIPTION:
XS GIS Cut Line= 3
      2726819.64      6890955.47      2726472.03      6891300.48
      2726352.69      6891775.25
#Sta/Elev= 30
    4507  430.51  4647.8  426.78    4669  426.65    4768  422.71  4803.4  422.33
  4810.5  423.18  4852.9  422.12  4888.3     420  4895.3  420.23    4924  418.06
    4966  418.25  4973.1  416.72  4980.2   416.7  4985.3  413.14  4985.5  412.64
    4989  412.64  4989.3  413.14  4993.6  414.94  4998.9  414.94  5017.9  418.15
  5069.5  419.86  5110.7  421.98  5172.6  424.09  5243.4  425.26  5325.6  427.41
  5337.6  428.26  5358.2  428.39  5371.9  429.18  5437.2  430.24  5486.3  431.25
#Mann= 5 ,-1 , 0
    4507     .05       0    4924     .12       0  4985.3     .07       0
  4989.3     .12       0  5437.2     .05       0
Bank Sta=4985.3,4989.3
XS Rating Curve= 0 ,0
Exp/Cntr=0.3,0.1

Type RM Length L Ch R = 1 ,25396   ,314,314,314
BEGIN DESCRIPTION:
Mapping XS a1004547
END DESCRIPTION:
XS GIS Cut Line= 4
      2726638.09      6890708.98      2726313.78      6890864.65
       2726124.4       6891064.4      2725990.25        6891374.
#Sta/Elev= 30
  4643.2  432.73  4660.8  433.01  4667.7  432.27  4706.1  430.69  4728.7  431.13
    4774   429.8  4922.7  423.57  4932.6  423.33    4945  421.67  4960.7  419.19
  4977.8  414.77  4983.4  414.35  4987.4  409.22  4987.6  408.72  4991.1  408.72
  4991.4  409.22  4998.9     413  5002.9     413  5005.9  414.01  5041.1  414.89
  5048.4  415.61  5168.5   416.8  5341.2  419.67  5417.1  422.09  5435.1   423.8
  5440.5  423.28  5487.5   425.3  5490.8  424.91  5563.3   428.1  5615.6   429.5
#Mann= 5 ,-1 , 0
  4643.2     .05       0  4922.7     .12       0  4987.4     .07       0
  4991.4     .12       0  5490.8     .05       0
Bank Sta=4987.4,4991.4
XS Rating Curve= 0 ,0
Exp/Cntr=0.3,0.1

Type RM Length L Ch R = 1 ,25082   ,421,421,421
BEGIN DESCRIPTION:
Mapping XS c847a10c
END DESCRIPTION:
XS GIS Cut Line= 3
      2726261.88      6890400.31      2726134.78      6890667.48
      2726002.47      6891175.99
#Sta/Elev= 30
  4701.1  431.09  4779.4  428.03  4790.5  424.64  4801.7  426.52  4812.6  426.18
  4841.6  423.95  4847.1  421.96  4856.9  420.58    4887  420.06  4892.5  418.53
  4909.7  419.15  4915.2  417.32  4932.4   419.4  4937.9  418.46  4955.1  420.37
  4960.7  418.17  4967.6  417.07  4983.4  412.57  4987.8  408.79    4988  408.29
  4991.8  408.79  4996.1  411.72  5025.8  411.94  5062.6  411.99  5101.1  413.68
  5124.6  414.45  5186.6  413.78  5246.8  416.21  5414.1  418.67  5522.4  422.58
#Mann= 5 ,-1 , 0
  4701.1     .12       0  4987.8     .07       0  4991.8     .12       0
  5025.8      .1       0  5101.1     .12       0
Bank Sta=4987.8,4991.8
XS Rating Curve= 0 ,0
Exp/Cntr=0.3,0.1

Type RM Length L Ch R = 1 ,24661   ,271,271,271
BEGIN DESCRIPTION:
Mapping XS 75aceed8
END DESCRIPTION:
XS GIS Cut Line= 3
      2726054.38      6890327.61      2725841.63      6890587.06
      2725657.44      6891183.76
#Sta/Elev= 30
  4672.5  433.45  4787.5  429.71    4824  429.71  4844.9  429.61  4861.5  427.95
  4936.1   422.9    4944  421.11  4958.3  414.81  4964.8  413.72  4972.7  410.96
    5036  410.82    5054  410.33  5062.5  407.74  5062.7  407.24  5066.5  407.74
  5073.8   410.5    5117  409.44  5137.7  409.97  5144.4  411.58  5158.7  412.95
  5228.9  414.67  5311.6  416.17  5383.4  418.52  5399.4  419.79  5453.9  421.91
  5481.3  424.28  5545.9  425.63  5551.9  426.48    5600  428.26  5632.5  428.77
#Mann= 9 ,-1 , 0
  4672.5     .05       0    4824     .12       0  4861.5      .1       0
    5036     .12       0  5062.5     .07       0  5066.5     .12       0
  5228.9      .1       0  5311.6     .12       0    5600     .05       0
Bank Sta=5062.5,5066.5
XS Rating Curve= 0 ,0
Exp/Cntr=0.3,0.1

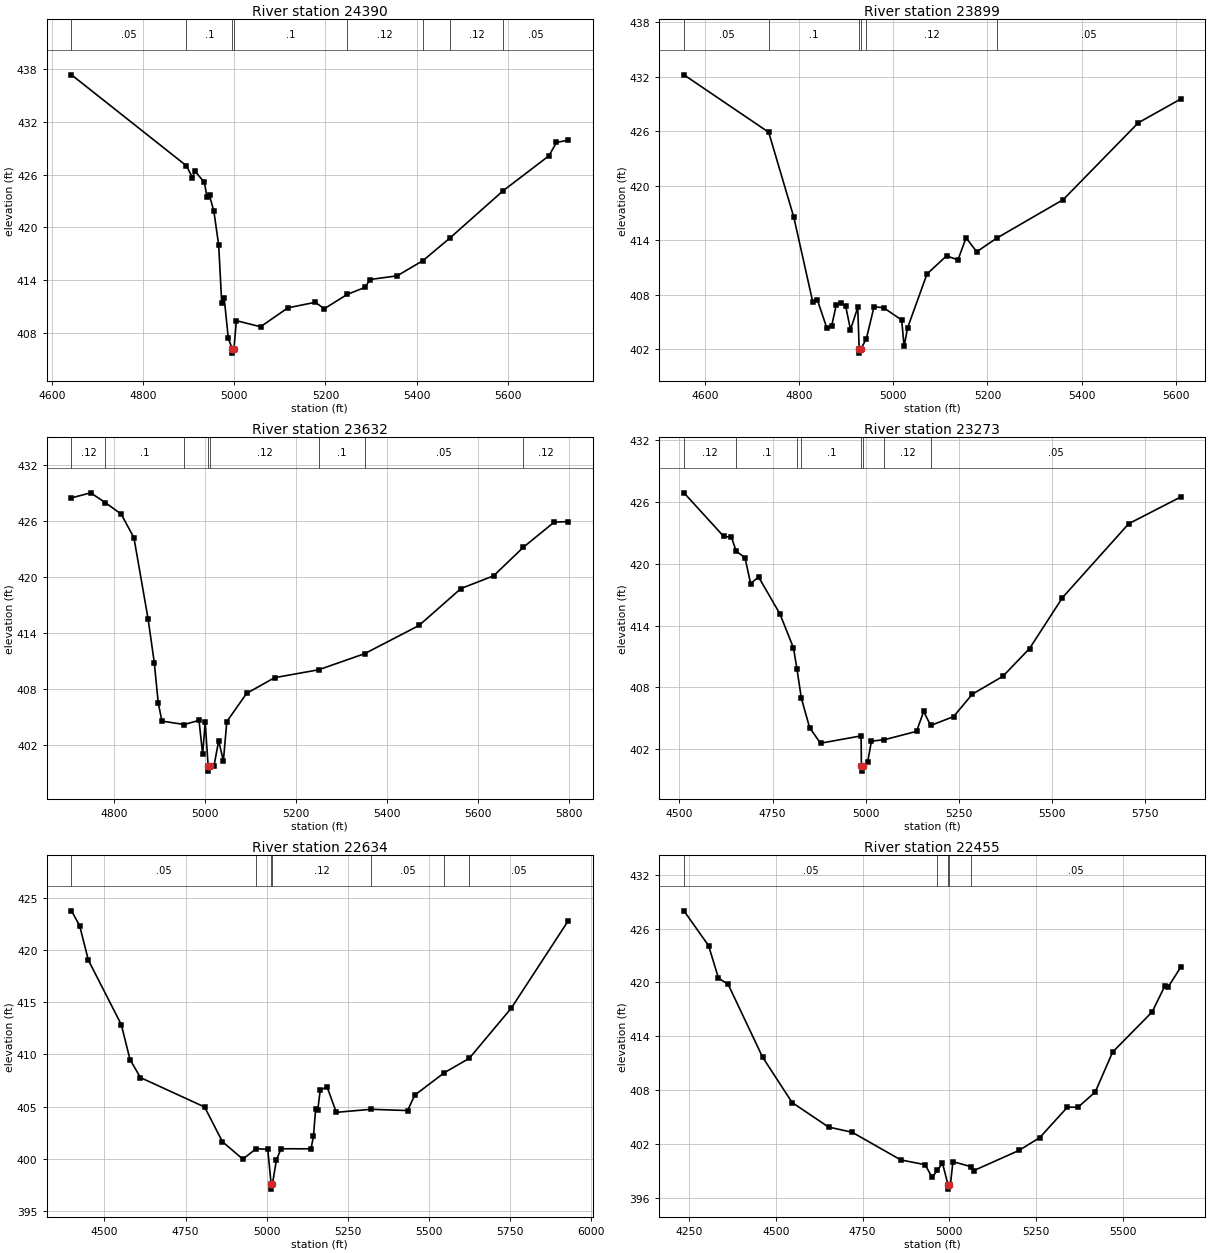
Type RM Length L Ch R = 1 ,24390   ,491,491,491
BEGIN DESCRIPTION:
Mapping XS 97773593
END DESCRIPTION:
XS GIS Cut Line= 3
      2725722.28      6890133.12      2725610.75       6890480.7
      2725600.38      6891206.59
#Sta/Elev= 30
  4642.1  437.36  4894.5  427.02  4907.9  425.67  4913.2  426.41  4933.9  425.14
    4940  423.42  4945.3  423.64  4954.9  421.83  4965.4     418  4972.1  411.43
  4977.4  412.03  4986.5  407.43    4995  406.21  4995.2  405.71    4999  406.21
  5004.3   409.4  5057.4  408.71  5117.5  410.86  5177.5  411.49  5197.5  410.76
  5247.9  412.39  5287.5   413.2  5297.5  414.08  5357.5   414.5  5414.4  416.24
  5473.2  418.79  5589.9  424.16  5690.9  428.15  5707.5  429.67  5733.1  429.93
#Mann= 8 ,-1 , 0
  4642.1     .05       0  4894.5      .1       0    4995     .07       0
    4999      .1       0  5247.9     .12       0  5414.4     .05       0
  5473.2     .12       0  5589.9     .05       0
Bank Sta=4995,4999
XS Rating Curve= 0 ,0
Exp/Cntr=0.3,0.1

Type RM Length L Ch R = 1 ,23899   ,267,267,267
BEGIN DESCRIPTION:
Mapping XS ed0612b8
END DESCRIPTION:
XS GIS Cut Line= 3
      2725320.19      6890268.02      2725296.84      6890716.78
      2725455.08      6891300.44
#Sta/Elev= 30
  4555.9  432.19  4735.8  425.87  4789.2   416.5  4829.2  407.22  4839.3   407.4
  4859.3  404.31  4869.3  404.53  4879.3  406.91  4889.3  407.13  4899.3  406.71
  4909.4  404.15  4924.8   406.6  4927.8  402.07  4928.1  401.57  4931.8  402.07
  4942.9  403.13  4959.4  406.67  4979.5  406.57    5018  405.22  5023.2   402.3
  5030.4  404.33  5071.8  410.28  5113.2  412.27  5137.5  411.83  5154.7  414.26
  5177.3  412.72  5219.4  414.21  5360.9  418.46  5520.2  426.91    5610  429.52
#Mann= 6 ,-1 , 0
  4555.9     .05       0  4735.8      .1       0  4927.8     .07       0
  4931.8      .1       0  4942.9     .12       0  5219.4     .05       0
Bank Sta=4927.8,4931.8
XS Rating Curve= 0 ,0
Exp/Cntr=0.3,0.1

Type RM Length L Ch R = 1 ,23632   ,359,359,359
BEGIN DESCRIPTION:
Mapping XS 34da53cc
END DESCRIPTION:
XS GIS Cut Line= 3
      2725200.88      6890340.57      2725063.36       6890615.6
      2725229.39      6891380.91
#Sta/Elev= 30
  4707.1  428.45  4749.1  428.99  4781.4  427.94  4816.2  426.71  4844.2  424.18
  4875.3  415.48  4888.9   410.8  4897.6  406.47  4905.7  404.54  4954.9  404.17
  4987.1  404.62  4995.1     401  5000.7  404.41  5007.2  399.68  5007.5  399.18
  5011.2  399.68  5020.1  399.77  5030.3  402.43  5040.6  400.27  5048.2  404.49
  5091.7  407.51  5153.1  409.19  5250.1  410.04  5350.8  411.76  5470.2  414.78
  5562.4  418.74  5634.1   420.1  5699.6  423.17  5767.1  425.85  5797.7  425.91
#Mann= 8 ,-1 , 0
  4707.1     .12       0  4781.4      .1       0  4954.9     .12       0
  5007.2     .07       0  5011.2     .12       0  5250.1      .1       0
  5350.8     .05       0  5699.6     .12       0
Bank Sta=5007.2,5011.2
XS Rating Curve= 0 ,0
Exp/Cntr=0.3,0.1

Type RM Length L Ch R = 1 ,23273   ,639,639,639
BEGIN DESCRIPTION:
Mapping XS 5d6327c2
END DESCRIPTION:
XS GIS Cut Line= 4
      2725179.06      6890297.42      2724776.32      6890557.82
       2724765.9      6890832.12       2724887.2      6891397.05
#Sta/Elev= 30
  4512.5  426.88  4618.9  422.66    4640  422.56  4652.4  421.23  4676.3  420.57
  4691.4  418.06  4712.6  418.72    4770  415.12  4806.2  411.83  4815.8  409.75
  4827.2  406.97  4849.6  404.08  4878.8  402.58  4987.6  403.29  4988.4  400.37
  4988.7  399.87  4992.4  400.37  5005.3  400.78  5015.3  402.78  5050.3  402.92
  5136.3  403.73  5155.4  405.66  5174.1   404.3  5235.5  405.16  5285.8  407.34
  5367.7  409.07  5439.3  411.77  5527.7  416.71  5705.2  423.88  5844.4  426.47
#Mann= 8 ,-1 , 0
  4512.5     .12       0  4652.4      .1       0  4815.8     .12       0
  4827.2      .1       0  4988.4     .07       0  4992.4      .1       0
  5050.3     .12       0  5174.1     .05       0
Bank Sta=4988.4,4992.4
XS Rating Curve= 0 ,0
Exp/Cntr=0.3,0.1

Type RM Length L Ch R = 1 ,22634   ,179,179,179
BEGIN DESCRIPTION:
Mapping XS fce7cbd4
END DESCRIPTION:
XS GIS Cut Line= 3
      2724387.44      6889988.35       2724203.4        6890561.
      2724804.12      6891269.65
#Sta/Elev= 30
  4398.5  423.76  4423.5  422.34  4450.4  419.04  4551.9  412.86  4578.8  409.51
  4610.9  407.78  4808.7  404.96  4863.5  401.64  4926.5  399.96  4968.1  400.98
  5003.3  400.89  5013.7  397.59    5014  397.09  5017.8  397.59    5030  399.89
  5044.3  400.96  5136.6  400.95  5144.2  402.15  5150.8  404.75  5157.4  404.68
  5165.1  406.59    5186  406.89  5214.6  404.45  5321.5  404.74  5434.2  404.62
  5456.3   406.1  5547.7  408.25  5624.5  409.63  5753.9  414.44    5929  422.79
#Mann= 7 ,-1 , 0
  4398.5     .05       0  4968.1     .12       0  5013.7     .07       0
  5017.8     .12       0  5321.5     .05       0  5547.7     .12       0
  5624.5     .05       0
Bank Sta=5013.7,5017.8
XS Rating Curve= 0 ,0
Exp/Cntr=0.3,0.1

Type RM Length L Ch R = 1 ,22455   ,161,161,161
BEGIN DESCRIPTION:
Mapping XS 3a47df0b
END DESCRIPTION:
XS GIS Cut Line= 4
      2724350.99      6889936.01      2724039.48      6890214.07
      2724024.58      6890561.84      2724009.06      6891226.72
#Sta/Elev= 30
  4235.2  427.97  4306.2  424.09  4334.7  420.48  4362.5  419.79  4461.7  411.69
    4547  406.63  4651.7  403.91  4719.7  403.33  4859.9  400.25  4929.9  399.72
    4950  398.32  4965.2  399.08    4980  399.88  4995.9   397.5  4996.2     397
    5000   397.5  5002.9   397.5    5010  400.06    5063  399.49    5070  399.06
  5200.1   401.3  5260.1  402.73  5340.1  406.13  5370.1   406.1  5420.1  407.81
  5470.1  412.25    5584  416.72  5620.2  419.58  5630.2   419.5  5665.9  421.68
#Mann= 5 ,-1 , 0
  4235.2     .05       0  4965.2     .12       0  4995.9     .07       0
    5000     .12       0    5063     .05       0
Bank Sta=4995.9,5000
XS Rating Curve= 0 ,0
Exp/Cntr=0.3,0.1

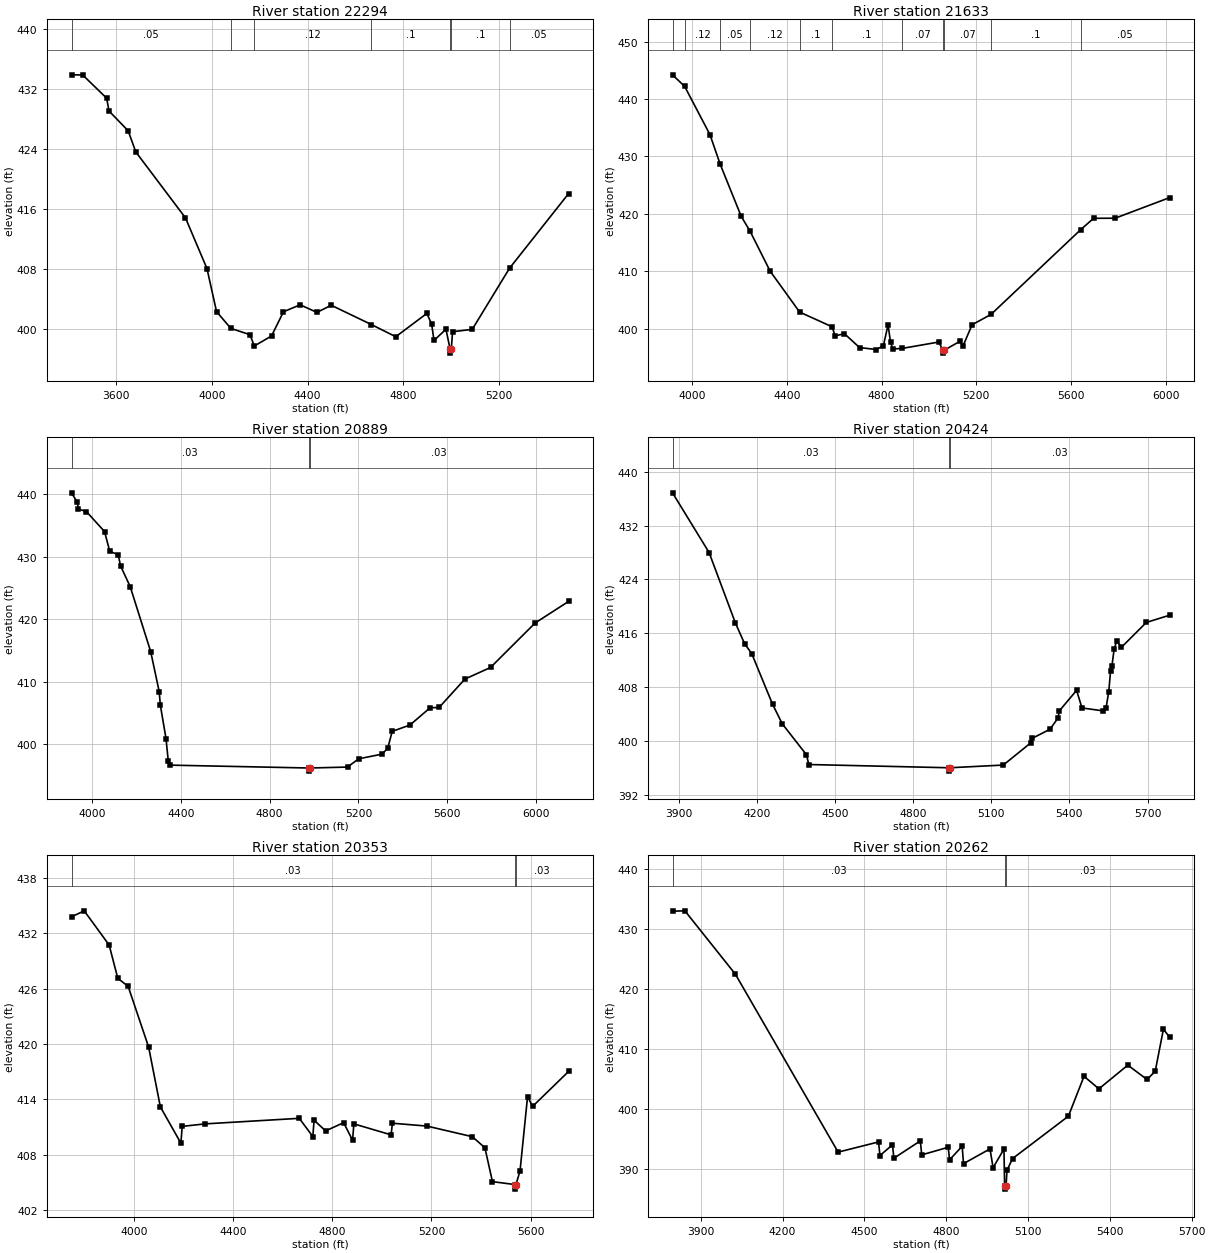
Type RM Length L Ch R = 1 ,22294   ,661,661,661
BEGIN DESCRIPTION:
Mapping XS 9aa78d29
END DESCRIPTION:
XS GIS Cut Line= 4
      2723836.01      6888974.06      2723858.85      6890191.47
      2723863.27       6890571.5      2723852.07      6891054.29
#Sta/Elev= 30
  3412.3  433.88  3459.2  433.86  3559.3  430.76  3569.3  429.05  3649.3  426.41
  3681.3  423.59  3889.3  414.78  3979.3  408.01  4019.3  402.27  4079.3  400.03
  4159.4  399.19  4177.2  397.68  4249.4  399.02  4299.4  402.25  4369.4  403.18
  4439.4  402.17  4499.4  403.12    4667  400.55  4769.5  398.92  4899.5  402.03
  4919.5  400.63  4929.5  398.42  4979.5  399.92  4997.1  397.23  4997.6  396.73
  5001.8  397.23  5007.2  399.59  5089.5   399.9  5245.6  408.06  5492.9  418.03
#Mann= 7 ,-1 , 0
  3412.3     .05       0  4079.3      .1       0  4177.2     .12       0
    4667      .1       0  4997.1     .07       0  5001.8      .1       0
  5245.6     .05       0
Bank Sta=4997.1,5001.8
XS Rating Curve= 0 ,0
Exp/Cntr=0.3,0.1

Type RM Length L Ch R = 1 ,21633   ,744,744,744
BEGIN DESCRIPTION:
Mapping XS e27fb5e0
END DESCRIPTION:
XS GIS Cut Line= 3
      2723541.59      6889145.48      2723350.62       6890195.8
      2723146.75       6891206.5
#Sta/Elev= 30
  3917.4  444.21  3968.8  442.19  4075.5   433.8    4119  428.61  4207.6  419.56
  4244.9  416.98  4329.6  410.03  4454.1  402.91  4590.9  400.35    4604  398.78
  4643.5  399.13    4707  396.73  4776.8  396.39  4807.3     397  4827.6   400.7
  4837.8  397.63  4847.9  396.49  4886.6  396.58  5041.3  397.69  5059.3  396.26
  5059.8  395.76  5064.1  396.26  5131.4  397.83  5143.3  396.96  5182.2   400.7
  5262.4  402.51  5640.8  417.26  5695.2  419.23    5786  419.25    6016  422.83
#Mann= 11 ,-1 , 0
  3917.4     .05       0  3968.8     .12       0    4119     .05       0
  4244.9     .12       0  4454.1      .1       0  4590.9      .1       0
  4886.6     .07       0  5059.3     .05       0  5064.1     .07       0
  5262.4      .1       0  5640.8     .05       0
Bank Sta=5059.3,5064.1
XS Rating Curve= 0 ,0
Exp/Cntr=0.3,0.1

Type RM Length L Ch R = 1 ,20889   ,465,465,465
BEGIN DESCRIPTION:
Mapping XS 96dab851
END DESCRIPTION:
XS GIS Cut Line= 3
      2722907.92      6888945.78       2722669.2      6890017.85
      2722790.72      6891150.62
#Sta/Elev= 30
  3908.3  440.26  3934.1  438.75  3939.7  437.66  3975.1  437.27  4057.1  434.05
  4080.4  430.89  4118.6  430.36    4129  428.56  4172.5  425.24  4264.7  414.84
    4303  408.43  4308.1  406.29  4333.7   400.9  4343.9  397.28  4351.6  396.67
  4976.5  396.21  4977.2  395.71  4981.7  396.21  5150.6  396.36  5200.9  397.68
  5305.6  398.43  5331.6  399.36  5351.8  402.07  5432.2   403.1  5522.7  405.86
    5563   405.9  5679.2  410.45  5794.3   412.3  5995.4  419.43  6145.9  422.88
#Mann= 3 ,-1 , 0
  3908.3     .03       0  4976.5     .03       0  4981.7     .03       0
Bank Sta=4976.5,4981.7
XS Rating Curve= 0 ,0
Exp/Cntr=0.3,0.1

Type RM Length L Ch R = 1 ,20424   ,71,71,71
BEGIN DESCRIPTION:
Mapping XS 1967379d
END DESCRIPTION:
XS GIS Cut Line= 5
      2722603.96      6888873.94      2722370.55      6889203.49
      2722236.58      6889917.32      2722167.88      6890284.59
      2722264.99       6890677.7
#Sta/Elev= 30
  3876.1  436.85  4016.5     428  4117.5  417.56  4153.1  414.46  4180.2  413.02
  4260.2   405.5  4297.8  402.58  4390.2  398.02  4399.5  396.56  4936.1  396.08
  4936.9  395.58  4941.4  396.08  5146.3  396.48  5251.6  399.77  5256.7  400.43
  5325.4  401.79  5355.9  403.43  5361.9  404.54  5427.7  407.56  5448.3  404.95
  5530.7  404.51    5541     405  5551.3  407.38  5558.1  410.44  5563.2  411.13
  5571.9  413.69  5582.2  414.92  5599.5  413.93  5695.5  417.63  5784.8   418.7
#Mann= 3 ,-1 , 0
  3876.1     .03       0  4936.1     .03       0  4941.4     .03       0
Bank Sta=4936.1,4941.4
XS Rating Curve= 0 ,0
Exp/Cntr=0.3,0.1

Type RM Length L Ch R = 1 ,20353   ,91,91,91
BEGIN DESCRIPTION:
Mapping XS 9e0e6c07
END DESCRIPTION:
XS GIS Cut Line= 5
      2722491.25      6888700.13      2722300.28      6889158.47
      2722223.89      6889616.81      2722102.36      6890245.28
      2722164.86      6890644.61
#Sta/Elev= 30
    3748  433.79  3799.2  434.44  3899.9  430.73  3934.6  427.13  3976.4  426.26
  4059.2  419.67  4106.4   413.2  4189.2  409.27  4194.6  411.09  4287.7  411.36
  4666.9  411.96  4721.5  409.99  4726.6  411.75  4773.3   410.6  4845.9  411.49
    4882  409.58  4887.1  411.36  5037.4  410.17  5042.5  411.43    5182  411.12
  5365.2  409.97  5415.8  408.77  5446.2   405.1  5535.8  404.79  5536.5  404.29
  5541.1  404.79  5557.5  406.26  5587.9  414.32  5608.1  413.25  5753.5  417.04
#Mann= 3 ,-1 , 0
    3748     .03       0  5535.8     .03       0  5541.1     .03       0
Bank Sta=5535.8,5541.1
XS Rating Curve= 0 ,0
Exp/Cntr=0.3,0.1

Type RM Length L Ch R = 1 ,20262   ,770,770,770
BEGIN DESCRIPTION:
Mapping XS e9768d02
END DESCRIPTION:
XS GIS Cut Line= 4
      2722437.42      6888689.74      2722249.93      6889106.39
      2722083.26       6889943.2      2722038.13      6890453.57
#Sta/Elev= 30
  3796.6  433.02    3842  433.08  4027.2  422.49  4403.8  392.78    4552  394.48
  4557.1  392.21  4603.1     394  4608.2  391.76  4705.2  394.66  4710.3  392.32
  4807.4  393.59  4812.5   391.5  4858.5  393.76  4863.6  390.86  4960.7  393.32
  4971.9  390.17  5011.8   393.3  5014.2   387.1    5015   386.6  5019.5   387.1
  5022.9  389.74  5043.3   391.7    5248  398.78  5305.3  405.44    5360  403.35
  5465.9  407.31  5536.2  404.91  5566.3  406.27  5596.4  413.31  5619.1  411.98
#Mann= 3 ,-1 , 0
  3796.6     .03       0  5014.2     .03       0  5019.5     .03       0
Bank Sta=5014.2,5019.5
XS Rating Curve= 0 ,0
Exp/Cntr=0.3,0.1

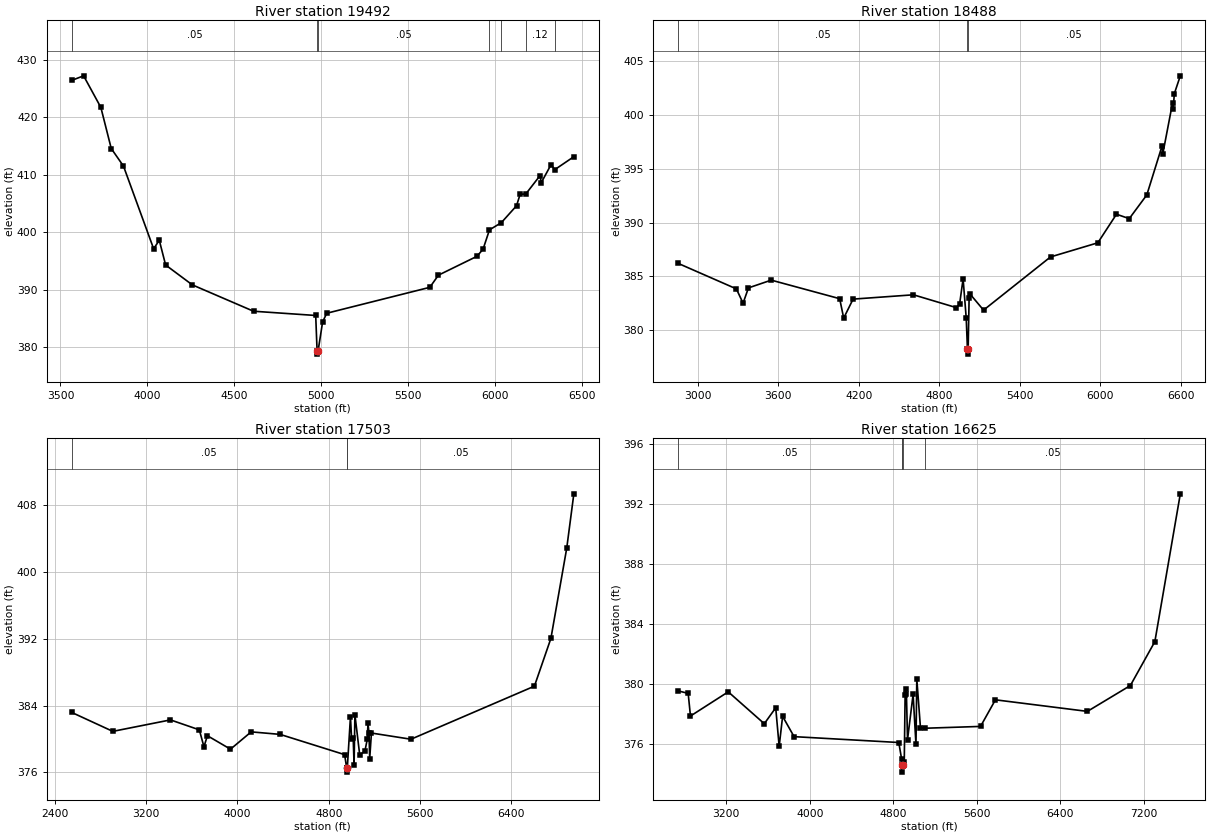
Type RM Length L Ch R = 1 ,19492   ,1004,1004,1004
BEGIN DESCRIPTION:
Mapping XS b9c5845a
END DESCRIPTION:
XS GIS Cut Line= 3
      2721928.73      6888486.64       2721359.3      6889847.71
      2722233.21      6890957.43
#Sta/Elev= 30
  3564.9  426.44    3633  427.23  3732.2  421.73    3792  414.57  3862.3  411.51
  4035.7  397.12  4068.3  398.59  4104.7  394.29  4258.3  390.83  4610.3  386.24
    4968   385.5    4976  379.27  4976.8  378.77  4981.4  379.27  5007.9   384.4
  5031.7  385.89  5624.3   390.4    5674  392.52  5895.3   395.8  5930.6  397.04
  5967.5  400.41  6035.7  401.66    6123   404.6  6143.8   406.6  6176.3  406.65
  6257.7  409.83  6265.7  408.65  6321.8  411.77  6342.9  410.89  6452.8  413.15
#Mann= 7 ,-1 , 0
  3564.9     .05       0    4976     .04       0  4981.4     .05       0
  5967.5     .12       0  6035.7     .05       0  6176.3     .12       0
  6342.9     .05       0
Bank Sta=4976,4981.4
XS Rating Curve= 0 ,0
Exp/Cntr=0.3,0.1

Type RM Length L Ch R = 1 ,18488   ,985,985,985
BEGIN DESCRIPTION:
Mapping XS 29435e78
END DESCRIPTION:
XS GIS Cut Line= 3
       2720609.3       6888347.7      2720630.14      6890444.93
      2722157.82      6891056.01
#Sta/Elev= 30
  2855.3  386.21  3288.6  383.85  3338.6  382.52  3378.6  383.94  3548.6  384.66
  4058.7  382.94  4088.7  381.14  4158.7   382.9  4608.7   383.3  4928.7  382.11
  4952.6  382.43  4978.8  384.78    5002  381.16  5011.1   378.3  5011.9   377.8
  5016.5   378.3  5023.6  382.97  5032.6  383.34  5131.3  381.88  5630.4  386.81
  5983.1  388.12  6122.1  390.77  6217.4  390.36  6348.3  392.56  6462.4  397.12
  6467.8  396.39  6540.5  401.11  6545.8  400.54    6553  401.93    6598   403.6
#Mann= 3 ,-1 , 0
  2855.3     .05       0  5011.1     .04       0  5016.5     .05       0
Bank Sta=5011.1,5016.5
XS Rating Curve= 0 ,0
Exp/Cntr=0.3,0.1

Type RM Length L Ch R = 1 ,17503   ,878,878,878
BEGIN DESCRIPTION:
Mapping XS 98f93994
END DESCRIPTION:
XS GIS Cut Line= 3
      2720262.08       6888535.2      2719900.97      6890972.71
      2720963.45      6892590.74
#Sta/Elev= 30
  2547.7  383.17  2907.4  380.91  3412.8  382.28  3665.6  381.09    3706  379.07
  3736.3  380.39  3938.5  378.78    4120  380.85  4373.2  380.55  4938.8  378.13
  4956.8  376.54  4957.6  376.04  4962.3  376.54  4989.9  382.65    5000  379.97
  5013.8  380.11  5021.7  376.94  5028.9  382.91    5071   378.1  5116.3  378.55
  5137.4  379.97  5143.4  381.85  5152.5   380.7  5158.5  377.63  5173.6  380.71
  5520.1  379.97  6601.9  386.31  6746.5  392.02  6885.2   402.8  6947.5  409.29
#Mann= 3 ,-1 , 0
  2547.7     .05       0  4956.8     .04       0  4962.3     .05       0
Bank Sta=4956.8,4962.3
XS Rating Curve= 0 ,0
Exp/Cntr=0.3,0.1

Type RM Length L Ch R = 1 ,16625   ,0,0,0
BEGIN DESCRIPTION:
Mapping XS 23f51e7a
END DESCRIPTION:
XS GIS Cut Line= 3
      2719689.76      6888848.98      2719038.28      6891007.27
       2720664.6      6892975.92
#Sta/Elev= 30
  2740.7  379.56  2835.9   379.4  2857.7  377.89  3219.5   379.5  3564.9  377.38
  3674.2  378.44  3707.2  375.87  3740.2  377.87    3850  376.52  4852.8  376.13
  4880.5     375  4882.9  374.66  4883.7  374.16  4888.5  374.66  4905.1  374.83
  4913.4  379.28  4918.6  379.68  4925.9  379.38  4936.4  376.32  4989.8  379.33
  5017.3     376  5025.2  380.36  5060.3  377.11  5107.9  377.08  5635.6   377.2
  5778.1  378.97  6658.8   378.2  7070.4  379.92  7304.9  382.84  7548.7  392.67
#Mann= 5 ,-1 , 0
  2740.7     .05       0  4880.5      .1       0  4882.9     .07       0
  4888.5      .1       0  5107.9     .05       0
Bank Sta=4882.9,4888.5
XS Rating Curve= 0 ,0
Exp/Cntr=0.3,0.1

Chan Stop Cuts=-1
Use User Specified Reach Order=0
Composite Channel Slope=5