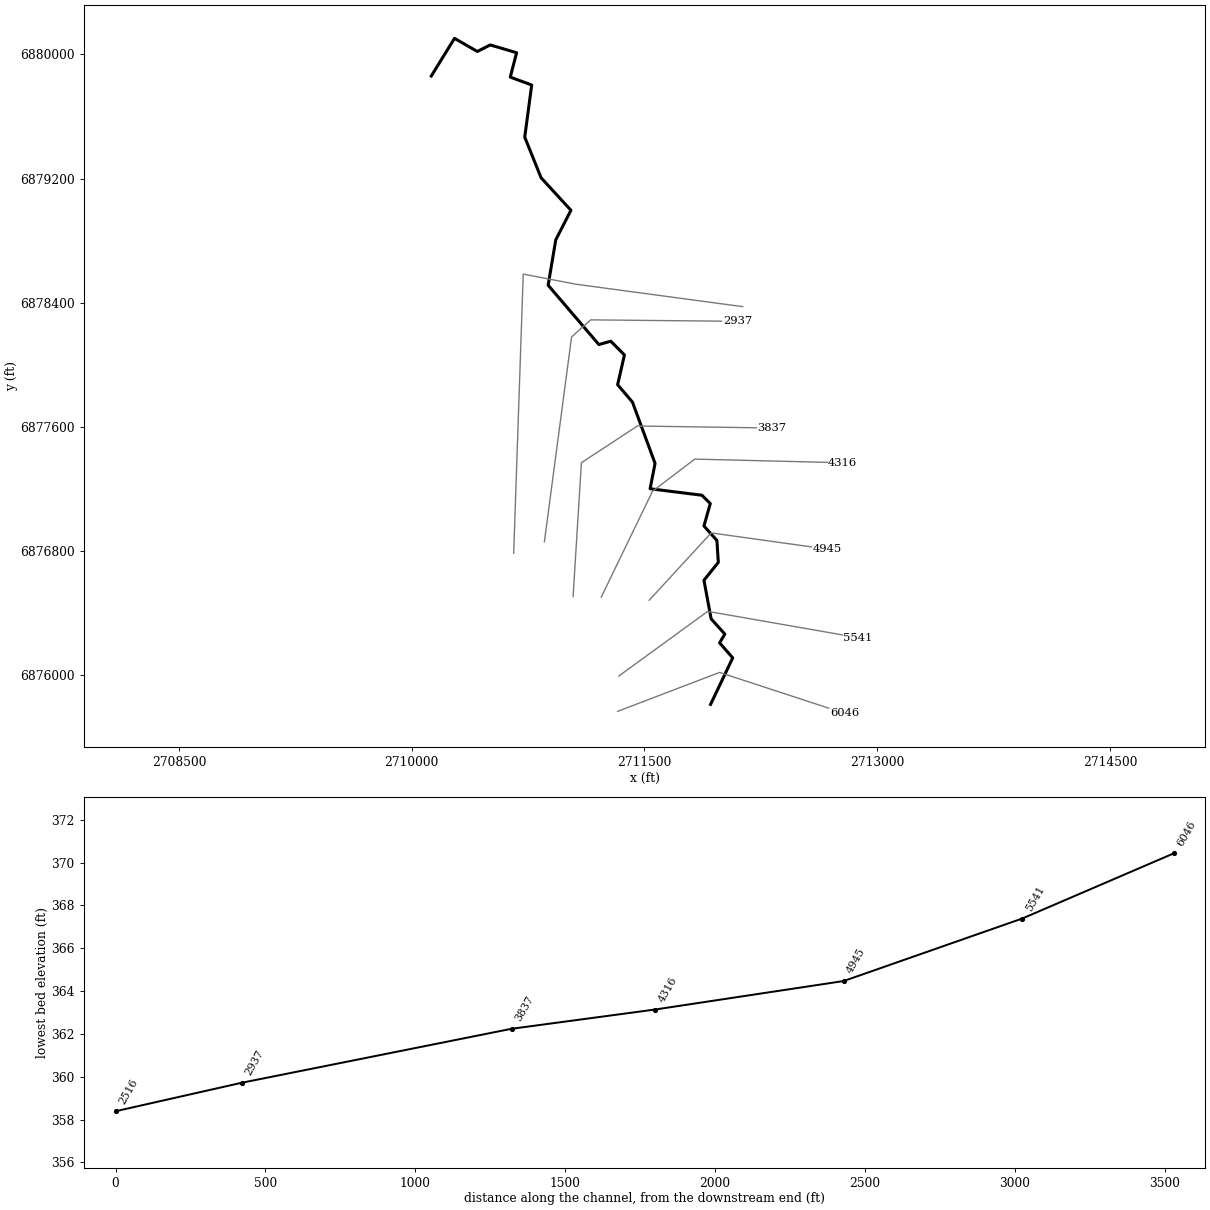
--- CCT8_1.prj (project) ---

Proj Title=CCT8_1 Base Level Engineering
Current Plan=p01
Default Exp/Contr=0.3,0.1
English Units
Geom File=g01
Flow File=f01
Plan File=p01
Y Axis Title=Elevation
X Axis Title(PF)=Main Channel Distance
X Axis Title(XS)=Station
BEGIN DESCRIPTION:
CCT8_1
END DESCRIPTION:
DSS Export Rating Curves= 0
DSS Export Rating Curve Sorted= 0
DSS Export Volume Flow Curves= 0
DXF OffsetX= 0
DXF OffsetY= 0
DXF ScaleX= 1
DXF ScaleY= 10

--- CCT8_1.p01 (plan) ---

Plan Title=Multiple Run
Short Identifier=Multiple
Geom File=g01
Flow File=f01
Subcritical Flow
K Sum by GR= 0
Std Step Tol= 0.01
Critical Tol= 0.01
Num of Std Step Trials= 20
Max Error Tol= 0.3
Flow Tol Ratio= 0.001
Split Flow NTrial= 30
Split Flow Tol= 0.02
Split Flow Ratio= 0.02
Log Output Level= 0
Friction Slope Method= 1
Unsteady Friction Slope Method= 2
Unsteady Bridges Friction Slope Method= 1
Parabolic Critical Depth
Global Vel Dist=  1 , 1 , 1
Global Log Level= 0
CheckData=True
Encroach Param= -1, 0, 0, 0
BEGIN DESCRIPTION:
Multiple Run
END DESCRIPTION:

--- CCT8_1.f01 (steady flow) ---

Flow Title=Multiple
Number of Profiles=7
Profile Names=10-year,25-year,50-year,1pct_min,100-year,1pct_plu,500-year
River Rch & RM= CCT8_1,Reach-1,6046
     570     764     920     550    1098    2190    1561
River Rch & RM= CCT8_1,Reach-1,5541
     795    1081    1316     795    1586    3164    2299
River Rch & RM= CCT8_1,Reach-1,4316
     993    1366    1675    1018    2030    4051    2981
Boundary for River Rch & Prof#=CCT8_1,Reach-1,1
Up Type=0
Dn Type=3
Dn Slope=0.005
Boundary for River Rch & Prof#=CCT8_1,Reach-1,2
Up Type=0
Dn Type=3
Dn Slope=0.005
Boundary for River Rch & Prof#=CCT8_1,Reach-1,3
Up Type=0
Dn Type=3
Dn Slope=0.005
Boundary for River Rch & Prof#=CCT8_1,Reach-1,4
Up Type=0
Dn Type=3
Dn Slope=0.005
Boundary for River Rch & Prof#=CCT8_1,Reach-1,5
Up Type=0
Dn Type=3
Dn Slope=0.005
Boundary for River Rch & Prof#=CCT8_1,Reach-1,6
Up Type=0
Dn Type=3
Dn Slope=0.005
Boundary for River Rch & Prof#=CCT8_1,Reach-1,7
Up Type=0
Dn Type=3
Dn Slope=0.005

--- CCT8_1.g01 (geometry) ---

Geom Title=Existing Conditions
Program Version=4.10

River Reach=CCT8_1          ,Reach-1
Reach XY= 30
        2711926.        6875811.      2712068.89      6876111.01
      2711984.03      6876207.67      2712017.98      6876264.33
      2711929.56      6876362.46      2711883.33       6876611.1
      2711975.98      6876726.36      2711966.67      6876867.67
      2711883.34       6876960.9      2711924.12      6877105.31
      2711870.36      6877159.03      2711536.28      6877200.84
      2711568.19      6877364.41      2711422.38       6877759.5
      2711326.94      6877871.48      2711370.91      6878063.33
      2711282.69       6878151.7        2711206.      6878130.37
      2710879.12      6878512.62      2710928.24      6878805.07
      2711026.05      6878995.66      2710833.86      6879204.83
      2710728.23      6879466.93      2710773.07      6879803.02
      2710634.97      6879853.94        2710676.        6880011.
      2710505.79      6880061.22      2710422.69      6880019.07
      2710275.67      6880103.81        2710126.        6879861.

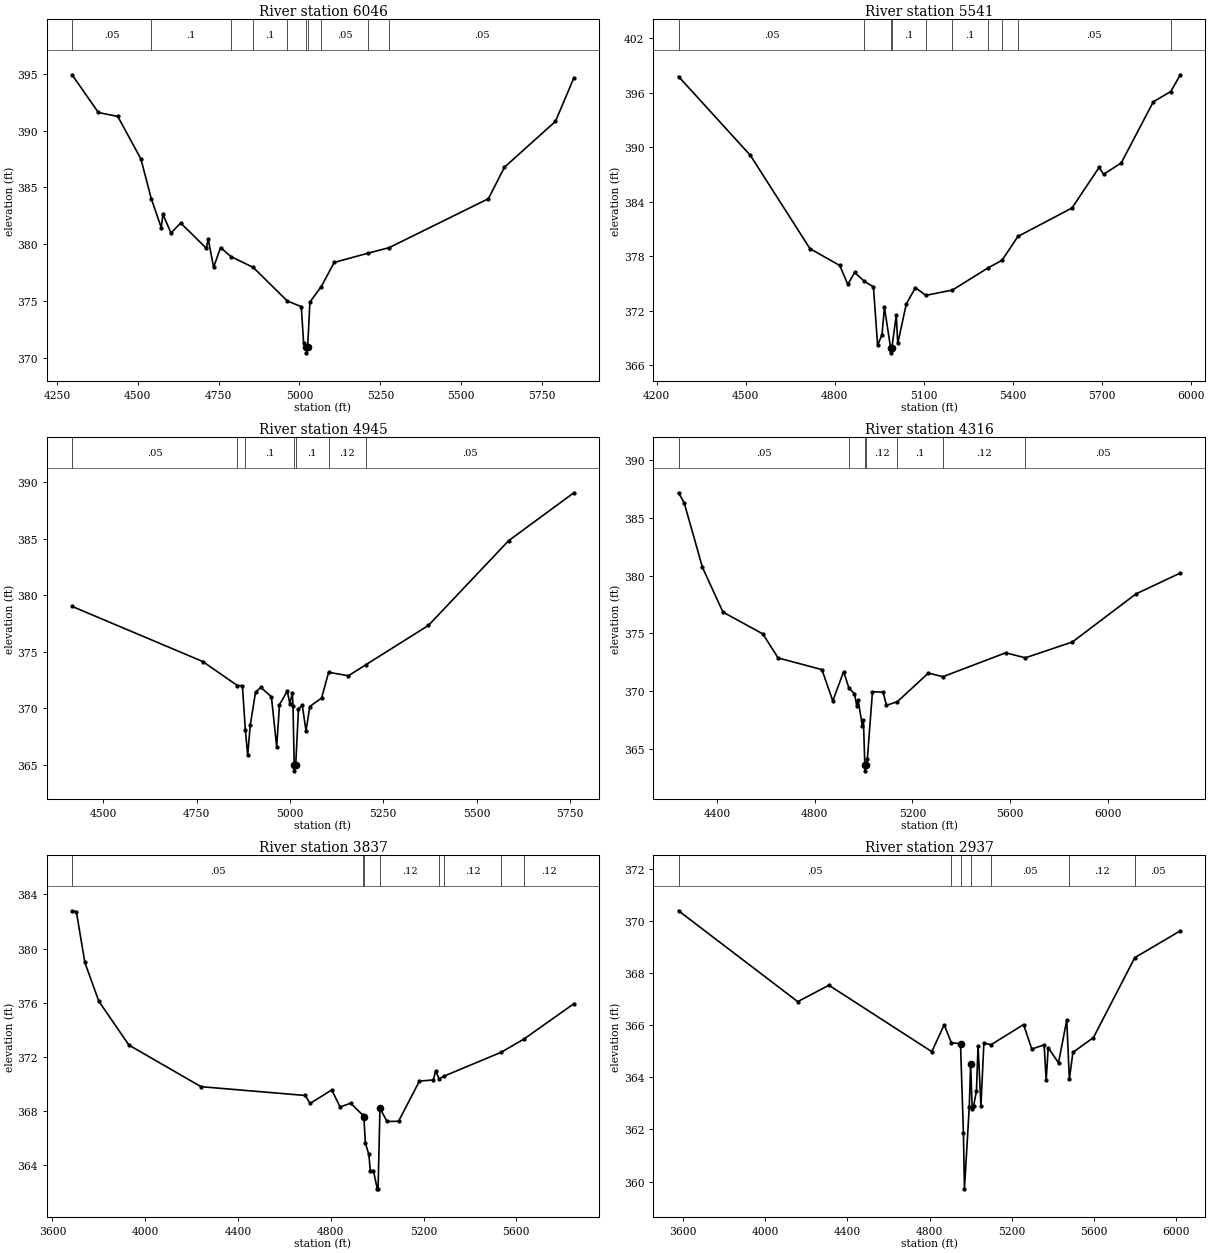
Type RM Length L Ch R = 1 ,6046    ,505,505,505
BEGIN DESCRIPTION:
CCT8_1 10.0
END DESCRIPTION:
XS GIS Cut Line= 3
      2711327.24      6875766.15       2711983.9      6876017.17
      2712789.96      6875753.15
#Sta/Elev= 30
    4297  394.91  4378.3  391.59  4438.4  391.24  4509.8   387.5    4542  383.99
  4572.6  381.46    4578  382.62  4602.7  380.98  4632.8  381.86  4712.3  379.63
  4717.6  380.47  4734.6  377.96    4756   379.7  4787.8  378.91  4857.1  377.95
  4962.1     375  5005.6   374.5  5012.7  371.33  5021.3  370.93  5021.5  370.43
  5025.3  370.93  5032.2   374.9  5067.1  376.25  5107.4  378.39  5212.7  379.21
  5277.1  379.69  5584.1     384  5633.6  386.77  5791.4  390.81  5848.2  394.64
#Mann= 10 ,-1 , 0
    4297     .05       0    4542      .1       0  4787.8     .12       0
  4857.1      .1       0  4962.1     .12       0  5021.3     .07       0
  5025.3     .12       0  5067.1     .05       0  5212.7     .12       0
  5277.1     .05       0
Bank Sta=5021.3,5025.3
XS Rating Curve= 0 ,0
Exp/Cntr=0.3,0.1

Type RM Length L Ch R = 1 ,5541    ,596,596,596
BEGIN DESCRIPTION:
Mapping XS a34924ab
END DESCRIPTION:
XS GIS Cut Line= 3
       2711334.8      6875994.01       2711907.7      6876410.66
      2712875.63      6876241.38
#Sta/Elev= 30
  4273.5  397.76  4515.5   389.1  4716.4  378.84  4816.9  376.99  4843.9  374.91
  4867.1  376.23  4899.3  375.26  4930.3  374.64  4944.4  368.22  4959.1  369.39
  4967.4  372.38  4988.3  367.89  4988.6  367.39  4992.3  367.89  5007.2  371.51
  5012.3  368.42  5041.1  372.77  5071.8  374.55  5106.9  373.71  5196.5  374.29
  5316.3  376.72  5363.6  377.56  5417.2  380.18  5599.4  383.31  5690.8  387.77
  5705.8  387.01  5765.2  388.25  5873.5  394.98  5932.3  396.11  5964.5  397.95
#Mann= 10 ,-1 , 0
  4273.5     .05       0  4899.3      .1       0  4988.3     .07       0
  4992.3      .1       0  5106.9     .05       0  5196.5      .1       0
  5316.3     .05       0  5363.6     .12       0  5417.2     .05       0
  5932.3     .12       0
Bank Sta=4988.3,4992.3
XS Rating Curve= 0 ,0
Exp/Cntr=0.3,0.1

Type RM Length L Ch R = 1 ,4945    ,629,629,629
BEGIN DESCRIPTION:
Mapping XS c81159ec
END DESCRIPTION:
XS GIS Cut Line= 3
      2711530.43      6876482.34      2711929.71      6876916.34
      2712676.25      6876812.18
#Sta/Elev= 30
  4416.7  379.02  4766.7  374.14  4859.5  372.01  4872.7     372  4880.8  368.04
  4886.9  365.86  4893.7   368.5  4907.9  371.43  4922.1  371.85  4950.4  371.02
  4964.6   366.6    4972  370.32    4993  371.52  4999.8   370.4  5006.2  371.33
  5008.3  370.24  5011.4  364.97  5011.6  364.47  5015.4  364.97  5022.9  369.93
    5033  370.29  5043.1     368  5053.2  370.16  5084.9  370.92  5103.6  373.19
  5156.4  372.88  5203.9  373.87    5371  377.34  5585.5  384.83  5760.2  389.07
#Mann= 7 ,-1 , 0
  4416.7     .05       0  4859.5     .12       0  4880.8      .1       0
  5011.4     .07       0  5015.4      .1       0  5103.6     .12       0
  5203.9     .05       0
Bank Sta=5011.4,5015.4
XS Rating Curve= 0 ,0
Exp/Cntr=0.3,0.1

Type RM Length L Ch R = 1 ,4316    ,479,479,479
BEGIN DESCRIPTION:
Mapping XS 3019f7e8
END DESCRIPTION:
XS GIS Cut Line= 4
      2711221.69        6876503.      2711551.57      6877184.45
      2711824.14      6877391.91      2712777.21      6877368.47
#Sta/Elev= 30
  4243.2  387.15  4266.7  386.26    4341  380.71  4424.8  376.85  4588.4  374.96
  4650.6  372.89  4829.8  371.88  4874.3  369.18  4918.7   371.7  4940.6  370.27
  4963.1   369.8  4972.4  368.76  4977.9  369.27    4995  367.05  4999.6  367.53
  5005.4  363.64  5005.7  363.14  5009.6  363.64  5015.8  364.19  5036.6  369.97
  5080.2  369.93  5093.8   368.8  5138.4  369.11  5265.3  371.58    5325  371.27
  5581.5  373.33  5662.2   372.9  5854.9  374.27  6114.9  378.42  6296.2  380.22
#Mann= 7 ,-1 , 0
  4243.2     .05       0  4940.6     .12       0  5005.4     .07       0
  5009.6     .12       0  5138.4      .1       0    5325     .12       0
  5662.2     .05       0
Bank Sta=5005.4,5009.6
XS Rating Curve= 0 ,0
Exp/Cntr=0.3,0.1

Type RM Length L Ch R = 1 ,3837    ,900,900,900
BEGIN DESCRIPTION:
Mapping XS c9d77283
END DESCRIPTION:
XS GIS Cut Line= 4
      2711039.94      6876506.06      2711093.52       6877368.8
       2711454.6      6877605.36      2712321.83      6877592.35
#Sta/Elev= 30
  3684.8  382.79  3703.4  382.72  3739.8  378.98    3800  376.11  3930.2  372.86
  4240.8  369.79  4689.9  369.14  4710.9  368.55  4804.4  369.55  4840.6  368.29
  4885.9  368.57  4939.5  367.67  4943.1  367.52  4949.1  365.63  4964.2  364.79
  4970.6  363.58  4984.1  363.59  5000.5  362.24  5004.1  362.24  5012.3  368.21
  5042.3  367.22  5092.3  367.23  5182.3   370.2  5242.3  370.29  5252.3  370.95
  5267.4  370.37  5289.8  370.58  5535.7  372.34  5634.8  373.33  5848.2  375.92
#Mann= 8 ,-1 , 0
  3684.8     .05       0  4939.5     .12       0  4943.1     .07       0
  5012.3     .12       0  5267.4     .05       0  5289.8     .12       0
  5535.7     .05       0  5634.8     .12       0
Bank Sta=4943.1,5012.3
XS Rating Curve= 0 ,0
Exp/Cntr=0.3,0.1

Type RM Length L Ch R = 1 ,2937    ,421,421,421
BEGIN DESCRIPTION:
Mapping XS c877ef0b
END DESCRIPTION:
XS GIS Cut Line= 4
      2710854.91      6876859.04      2711030.07      6878179.19
      2711153.73      6878289.39      2712098.92      6878279.92
#Sta/Elev= 30
  3577.9   370.4  4158.2  366.91  4309.8  367.54  4810.6  364.99  4871.1  366.02
  4905.4  365.34  4950.5  365.29  4964.7  361.85  4969.6  359.72  4993.1  362.86
  4999.8  364.52  5007.3  362.77    5014  362.89  5028.2  363.49  5035.8  365.21
    5050  362.92  5064.2  365.31  5099.9  365.26  5257.5  366.03  5297.5  365.09
  5357.5  365.25  5367.5  363.89  5377.5  365.14  5427.5  364.56  5467.6   366.2
  5480.4  363.93  5497.6  364.96  5597.6  365.53  5798.8   368.6  6020.5  369.63
#Mann= 7 ,-1 , 0
  3577.9     .05       0  4905.4     .07       0  4950.5     .05       0
  4999.8     .07       0  5099.9     .05       0  5480.4     .12       0
  5798.8     .05       0
Bank Sta=4950.5,4999.8
XS Rating Curve= 0 ,0
Exp/Cntr=0.3,0.1

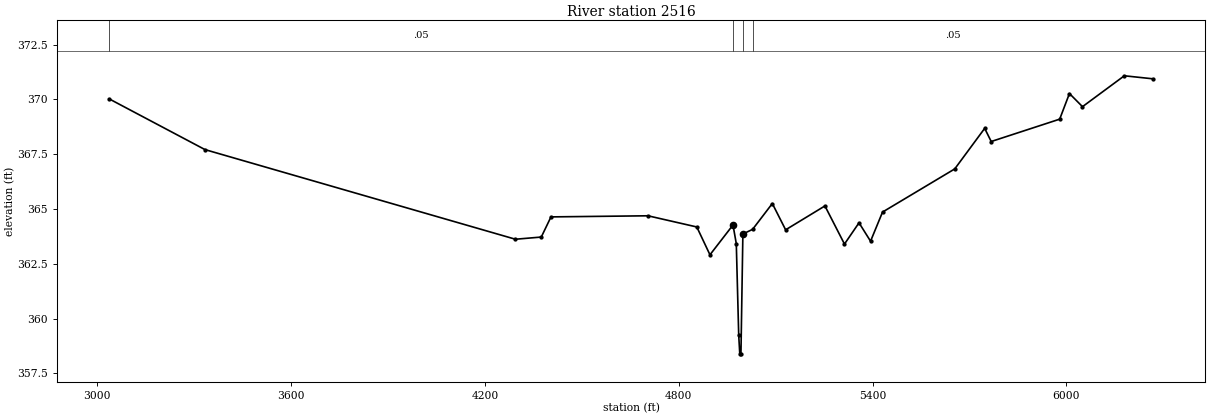
Type RM Length L Ch R = 1 ,2516    ,0,0,0
BEGIN DESCRIPTION:
Mapping XS 4477a845
END DESCRIPTION:
XS GIS Cut Line= 4
      2710657.04      6876785.25      2710718.52       6878584.2
      2711057.49      6878519.24      2712132.95      6878374.52
#Sta/Elev= 30
  3038.1  370.02    3334  367.71  4294.6  363.62  4374.6  363.72  4404.6  364.64
  4704.8  364.69  4855.9  364.18  4896.6  362.91  4967.9  364.27  4978.1  363.42
  4985.6  359.24  4988.9  358.39  4992.5  358.39  4998.5  363.86  5028.5  364.07
  5089.6  365.25  5130.8  364.05  5252.4  365.14  5312.9   363.4  5357.9  364.37
  5393.6  363.53  5430.7  364.86  5654.2  366.83  5746.8  368.68    5767  368.08
  5978.9   369.1  6009.1  370.27  6049.5  369.67    6179  371.08  6268.4  370.94
#Mann= 4 ,-1 , 0
  3038.1     .05       0  4967.9    .035       0  4998.5     .07       0
  5028.5     .05       0
Bank Sta=4967.9,4998.5
XS Rating Curve= 0 ,0
Exp/Cntr=0.3,0.1

Chan Stop Cuts=-1
Use User Specified Reach Order=0
Composite Channel Slope=5