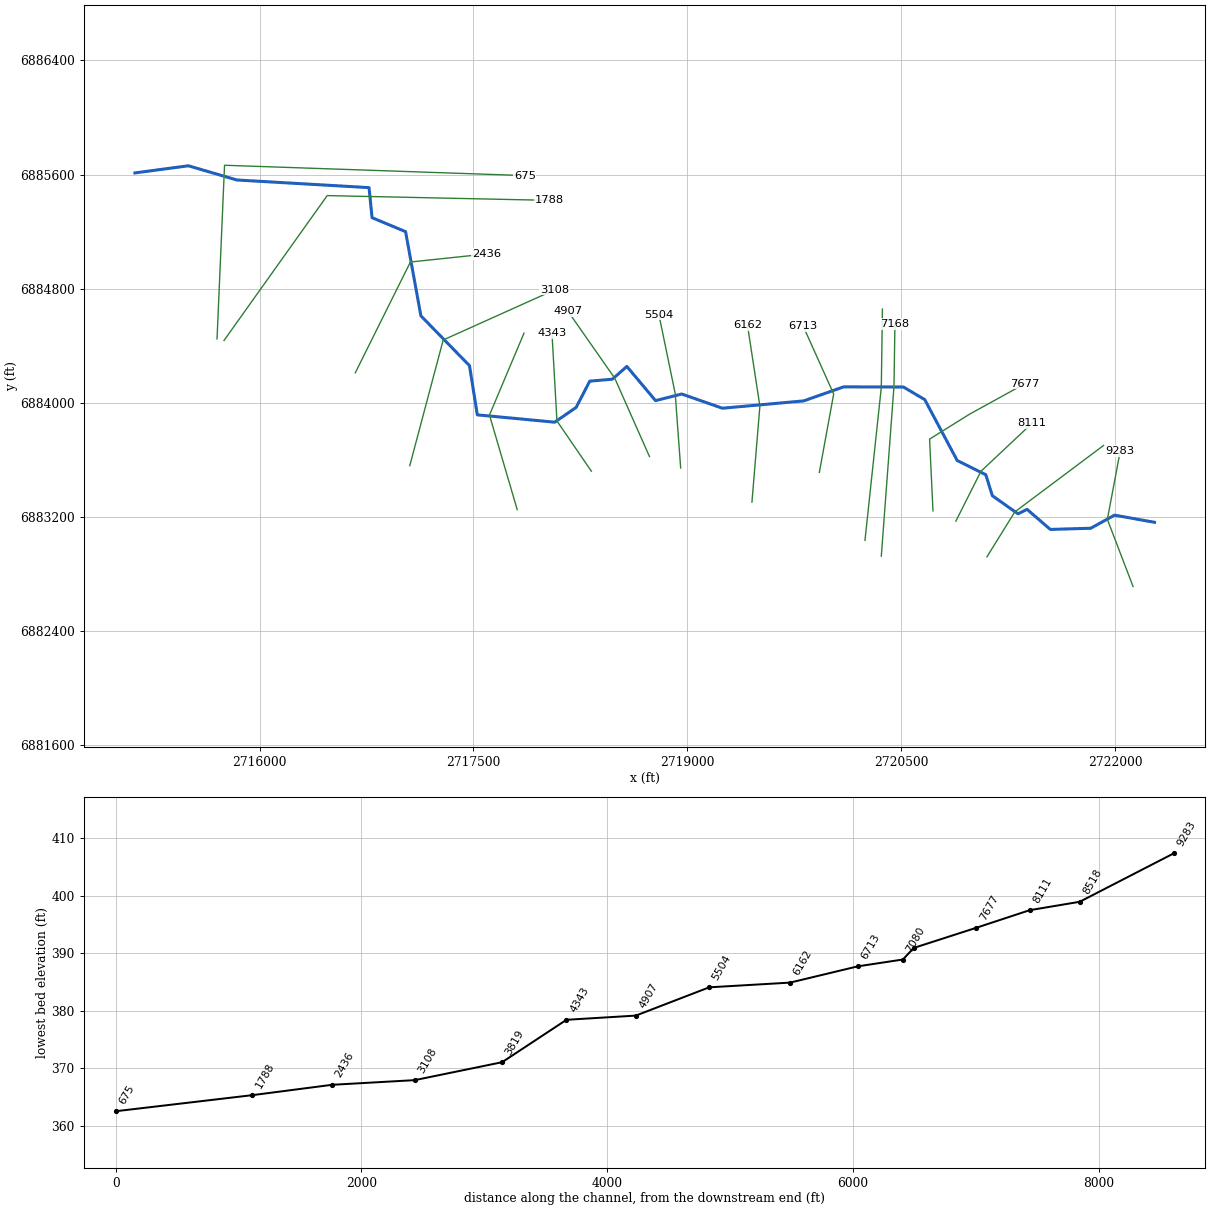
--- CCT8_2.prj (project) ---

Proj Title=CCT8_2 Base Level Engineering
Current Plan=p01
Default Exp/Contr=0.3,0.1
English Units
Geom File=g01
Flow File=f01
Plan File=p01
BEGIN DESCRIPTION:
CCT8_2
END DESCRIPTION:

--- CCT8_2.p01 (plan) ---

Plan Title=Multiple Run
Short Identifier=Multiple
Geom File=g01
Flow File=f01
Subcritical Flow
K Sum by GR= 0
Std Step Tol= 0.01
Critical Tol= 0.01
Num of Std Step Trials= 20
Max Error Tol= 0.3
Flow Tol Ratio= 0.001
Split Flow NTrial= 30
Split Flow Tol= 0.02
Split Flow Ratio= 0.02
Log Output Level= 0
Friction Slope Method= 1
Unsteady Friction Slope Method= 2
Unsteady Bridges Friction Slope Method= 1
Parabolic Critical Depth
Global Vel Dist=  1 , 1 , 1
Global Log Level= 0
CheckData=True
Encroach Param= -1, 0, 0, 0
BEGIN DESCRIPTION:
Multiple Run
END DESCRIPTION:

--- CCT8_2.f01 (steady flow) ---

Flow Title=Multiple
Number of Profiles=7
Profile Names=10-year,25-year,50-year,1pct_min,100-year,1pct_plu,500-year
River Rch & RM= CCT8_2,Reach-1,9283
     604     813     983     591    1179    2352    1693
River Rch & RM= CCT8_2,Reach-1,7677
     852    1168    1430     868    1732    3456    2539
River Rch & RM= CCT8_2,Reach-1,3108
    1299    1818    2256    1386    2766    5519    4156
Boundary for River Rch & Prof#=CCT8_2,Reach-1,1
Up Type=0
Dn Type=3
Dn Slope=0.005
Boundary for River Rch & Prof#=CCT8_2,Reach-1,2
Up Type=0
Dn Type=3
Dn Slope=0.005
Boundary for River Rch & Prof#=CCT8_2,Reach-1,3
Up Type=0
Dn Type=3
Dn Slope=0.005
Boundary for River Rch & Prof#=CCT8_2,Reach-1,4
Up Type=0
Dn Type=3
Dn Slope=0.005
Boundary for River Rch & Prof#=CCT8_2,Reach-1,5
Up Type=0
Dn Type=3
Dn Slope=0.005
Boundary for River Rch & Prof#=CCT8_2,Reach-1,6
Up Type=0
Dn Type=3
Dn Slope=0.005
Boundary for River Rch & Prof#=CCT8_2,Reach-1,7
Up Type=0
Dn Type=3
Dn Slope=0.005

--- CCT8_2.g01 (geometry) ---

Geom Title=Existing Conditions

River Reach=CCT8_2,Reach-1
Reach XY= 30
      2722276.00      6883161.00      2721996.03      6883210.96
      2721829.23      6883119.24      2721545.98      6883110.96
      2721382.67      6883251.70      2721319.34      6883220.32
      2721139.26      6883347.35      2721093.21      6883494.73
      2720892.64      6883594.29      2720665.37      6884021.00
      2720515.50      6884109.80      2720096.30      6884110.70
      2719815.50      6884012.22      2719246.10      6883960.91
      2718960.73      6884060.62      2718777.42      6884014.04
      2718576.01      6884253.92      2718474.53      6884164.57
      2718315.88      6884150.65      2718220.41      6883966.61
      2718070.15      6883863.06      2717527.40      6883914.39
      2717472.46      6884259.54      2717131.80      6884608.70
      2717024.37      6885199.19      2716789.20      6885297.27
      2716768.05      6885508.00      2715841.22      6885561.52
      2715501.11      6885661.15      2715126.00      6885611.00

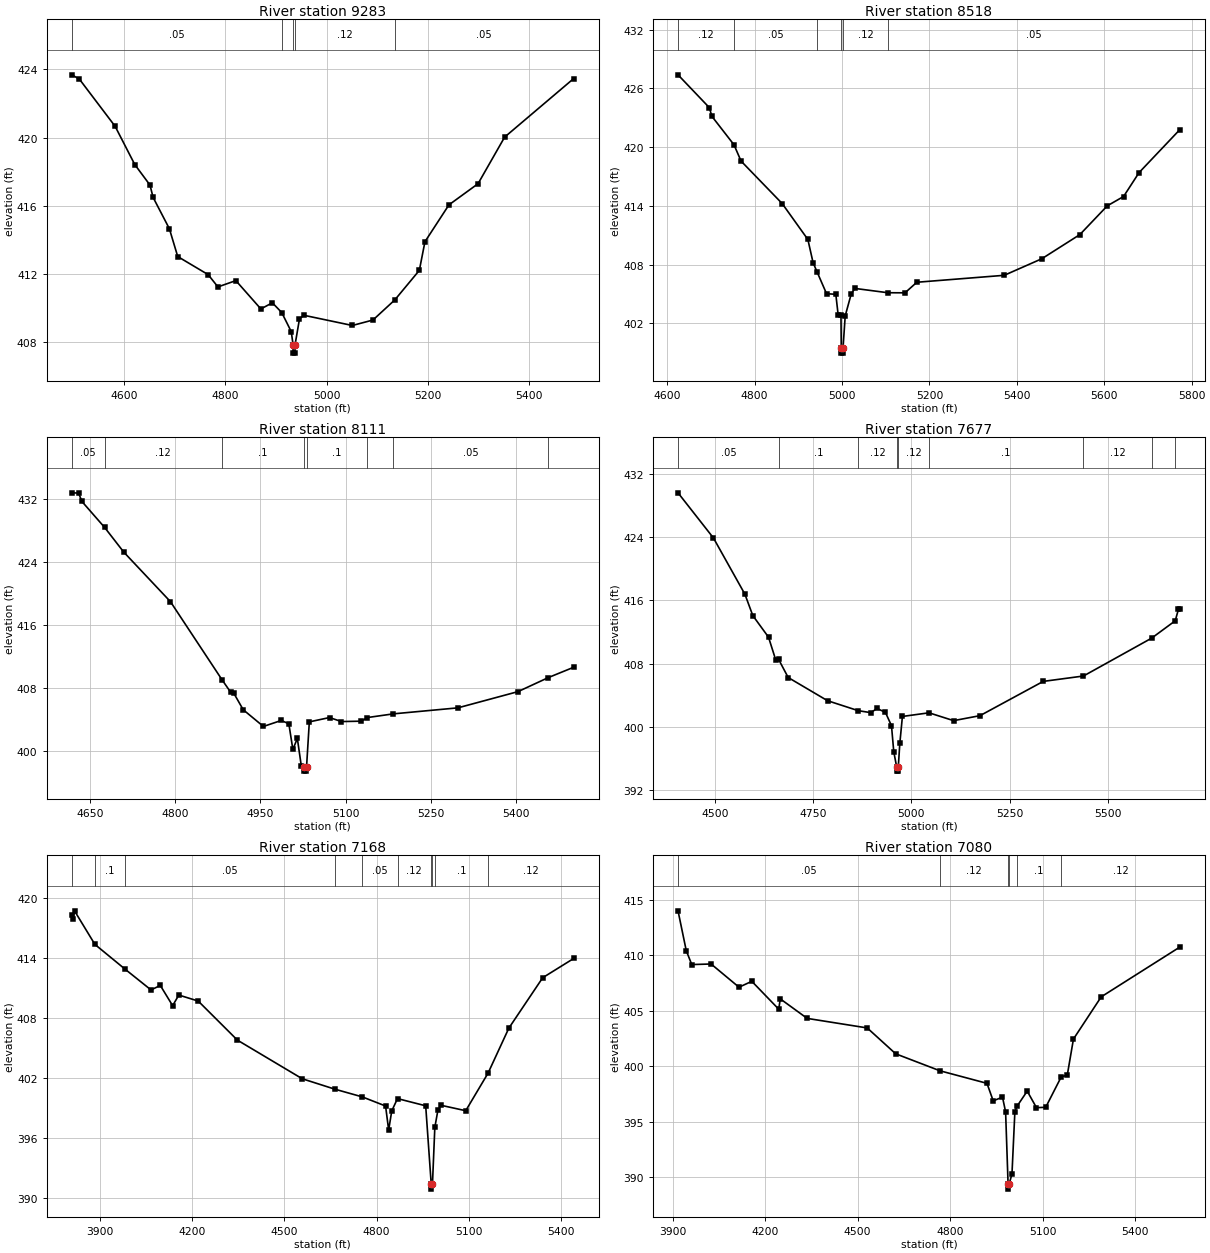
Type RM Length L Ch R = 1,9283,765,765,765
BEGIN DESCRIPTION:
CCT8_2 16.0
END DESCRIPTION:
XS GIS Cut Line= 3
      2722126.01      6882710.98      2721945.88      6883181.27
      2722036.11      6883660.55
#Sta/Elev= 30
  4496.4  423.68  4511.4  423.43  4582.1  420.66  4620.9  418.42  4650.9  417.22
  4657.0  416.50  4689.2  414.66  4705.7  413.03  4765.8  411.97  4785.1  411.25
  4820.5  411.62  4869.9  409.96  4892.6  410.32  4911.1  409.75  4929.9  408.63
  4933.5  407.87  4933.7  407.37  4937.2  407.37  4937.5  407.87  4946.2  409.38
  4954.6  409.59  5050.6  408.99  5091.3  409.31  5134.5  410.49  5182.9  412.22
  5194.0  413.90  5241.4  416.06  5298.9  417.30  5351.4  420.03  5487.7  423.46
#Mann=5,-1,0
  4496.4    0.05       0  4911.1    0.12       0  4933.5    0.07       0
  4937.5    0.12       0  5134.5    0.05       0
Bank Sta=4933.5,4937.5
Exp/Cntr=0.3,0.1

Type RM Length L Ch R = 1,8518,407,407,407
BEGIN DESCRIPTION:
Mapping XS a4040143
END DESCRIPTION:
XS GIS Cut Line= 3
      2721101.25      6882918.45      2721296.53      6883233.51
      2721918.94      6883699.67
#Sta/Elev= 30
  4624.9  427.38  4696.5  424.03  4702.4  423.14  4753.0  420.23  4769.1  418.57
  4863.2  414.23  4922.0  410.56  4933.9  408.19  4943.1  407.24  4964.7  405.02
  4985.9  404.96  4991.2  402.89  4997.7  402.89  4998.4  399.45  4998.7  398.95
  5002.2  398.95  5002.4  399.45  5007.4  402.75  5021.3  405.02  5029.6  405.56
  5104.9  405.12  5144.2  405.11  5171.3  406.19  5371.3  406.90  5457.2  408.59
  5544.3  411.06  5607.1  414.00  5644.3  414.95  5679.7  417.39  5773.2  421.79
#Mann=6,-1,0
  4624.9    0.12       0  4753.0    0.05       0  4943.1    0.12       0
  4998.4    0.07       0  5002.4    0.12       0  5104.9    0.05       0
Bank Sta=4998.4,5002.4
Exp/Cntr=0.3,0.1

Type RM Length L Ch R = 1,8111,434,434,434
BEGIN DESCRIPTION:
Mapping XS b3da7c8f
END DESCRIPTION:
XS GIS Cut Line= 3
      2720883.54      6883169.25      2721059.34      6883518.67
      2721418.92      6883856.59
#Sta/Elev= 30
  4617.5  432.81  4629.6  432.78  4635.2  431.73  4675.5  428.41  4709.0  425.30
  4791.4  419.00  4882.2  409.10  4897.4  407.52  4903.0  407.39  4919.7  405.28
  4955.3  403.16  4986.7  403.92  5000.1  403.50  5007.2  400.24  5015.1  401.64
  5022.0  398.18  5027.3  397.99  5027.6  397.49  5031.1  397.49  5031.3  397.99
  5036.2  403.74  5071.8  404.29  5092.8  403.78  5128.0  403.83  5138.6  404.29
  5184.5  404.76  5298.0  405.52  5404.0  407.58  5457.7  409.37  5502.1  410.67
#Mann=8,-1,0
  4617.5    0.05       0  4675.5    0.12       0  4882.2     0.1       0
  5027.3    0.07       0  5031.3     0.1       0  5138.6    0.12       0
  5184.5    0.05       0  5457.7    0.12       0
Bank Sta=5027.3,5031.3
Exp/Cntr=0.3,0.1

Type RM Length L Ch R = 1,7677,509,509,509
BEGIN DESCRIPTION:
Mapping XS 0b37761c
END DESCRIPTION:
XS GIS Cut Line= 4
      2720722.96      6883240.93      2720699.09      6883744.37
      2720981.21      6883920.15      2721367.53      6884132.84
#Sta/Elev= 30
  4406.1  429.60  4496.3  423.89  4576.4  416.78  4596.4  414.09  4636.4  411.36
  4655.1  408.43  4662.1  408.55  4686.5  406.26  4786.6  403.33  4864.8  402.07
  4896.7  401.82  4912.8  402.35  4934.0  401.85  4949.4  400.17  4955.2  396.88
  4962.7  394.93  4963.0  394.43  4966.5  394.43  4966.7  394.93  4970.6  397.93
  4977.2  401.34  5044.9  401.80  5107.5  400.81  5174.7  401.44  5335.6  405.77
  5438.0  406.45  5611.7  411.24  5671.6  413.43  5679.8  414.89  5683.5  414.89
#Mann=9,-1,0
  4406.1    0.05       0  4662.1     0.1       0  4864.8    0.12       0
  4962.7    0.07       0  4966.7    0.12       0  5044.9     0.1       0
  5438.0    0.12       0  5611.7    0.05       0  5671.6    0.12       0
Bank Sta=4962.7,4966.7
Exp/Cntr=0.3,0.1

Type RM Length L Ch R = 1,7168,88,88,88
BEGIN DESCRIPTION:
Mapping XS 5a507798
END DESCRIPTION:
XS GIS Cut Line= 3
      2720360.56      6882924.10      2720449.53      6884115.46
      2720456.04      6884551.64
#Sta/Elev= 30
  3809.6  418.32  3813.5  417.91  3818.5  418.71  3884.7  415.36  3983.0  412.88
  4067.2  410.81  4097.3  411.26  4137.4  409.24  4157.5  410.30  4220.5  409.70
  4347.8  405.80  4558.6  401.94  4664.6  400.90  4753.7  400.13  4829.3  399.22
  4839.4  396.82  4849.4  398.73  4868.1  399.96  4959.7  399.24  4977.7  391.42
  4978.0  390.92  4981.7  391.42  4989.4  397.09  4999.5  398.82  5009.8  399.29
  5089.8  398.75  5162.5  402.51  5229.8  406.99  5339.9  412.03  5440.5  413.95
#Mann=10,-1,0
  3809.6    0.12       0  3884.7     0.1       0  3983.0    0.05       0
  4664.6    0.12       0  4753.7    0.05       0  4868.1    0.12       0
  4977.7    0.07       0  4981.7    0.12       0  4989.4     0.1       0
  5162.5    0.12       0
Bank Sta=4977.7,4981.7
Exp/Cntr=0.3,0.1

Type RM Length L Ch R = 1,7080,367,367,367
BEGIN DESCRIPTION:
Mapping XS 4e0928db
END DESCRIPTION:
XS GIS Cut Line= 3
      2720245.97      6883034.33      2720360.55      6884107.21
      2720368.36      6884656.37
#Sta/Elev= 30
  3917.2  413.98  3944.0  410.38  3961.8  409.14  4024.5  409.19  4115.0  407.10
  4156.6  407.63  4243.9  405.12  4248.9  406.05  4336.2  404.29  4531.0  403.43
  4623.3  401.10  4767.0  399.57  4919.5  398.44  4939.7  396.86  4969.8  397.20
  4979.9  395.87  4987.9  389.41  4988.2  388.91  4991.9  389.41  5000.6  390.29
  5010.0  395.89  5016.8  396.37  5050.0  397.74  5080.0  396.25  5110.0  396.28
  5160.5  399.03  5180.0  399.18  5200.0  402.43  5290.0  406.23  5545.4  410.72
#Mann=6,-1,0
  3917.2    0.05       0  4767.0    0.12       0  4987.9    0.07       0
  4991.9    0.12       0  5016.8     0.1       0  5160.5    0.12       0
Bank Sta=4987.9,4991.9
Exp/Cntr=0.3,0.1

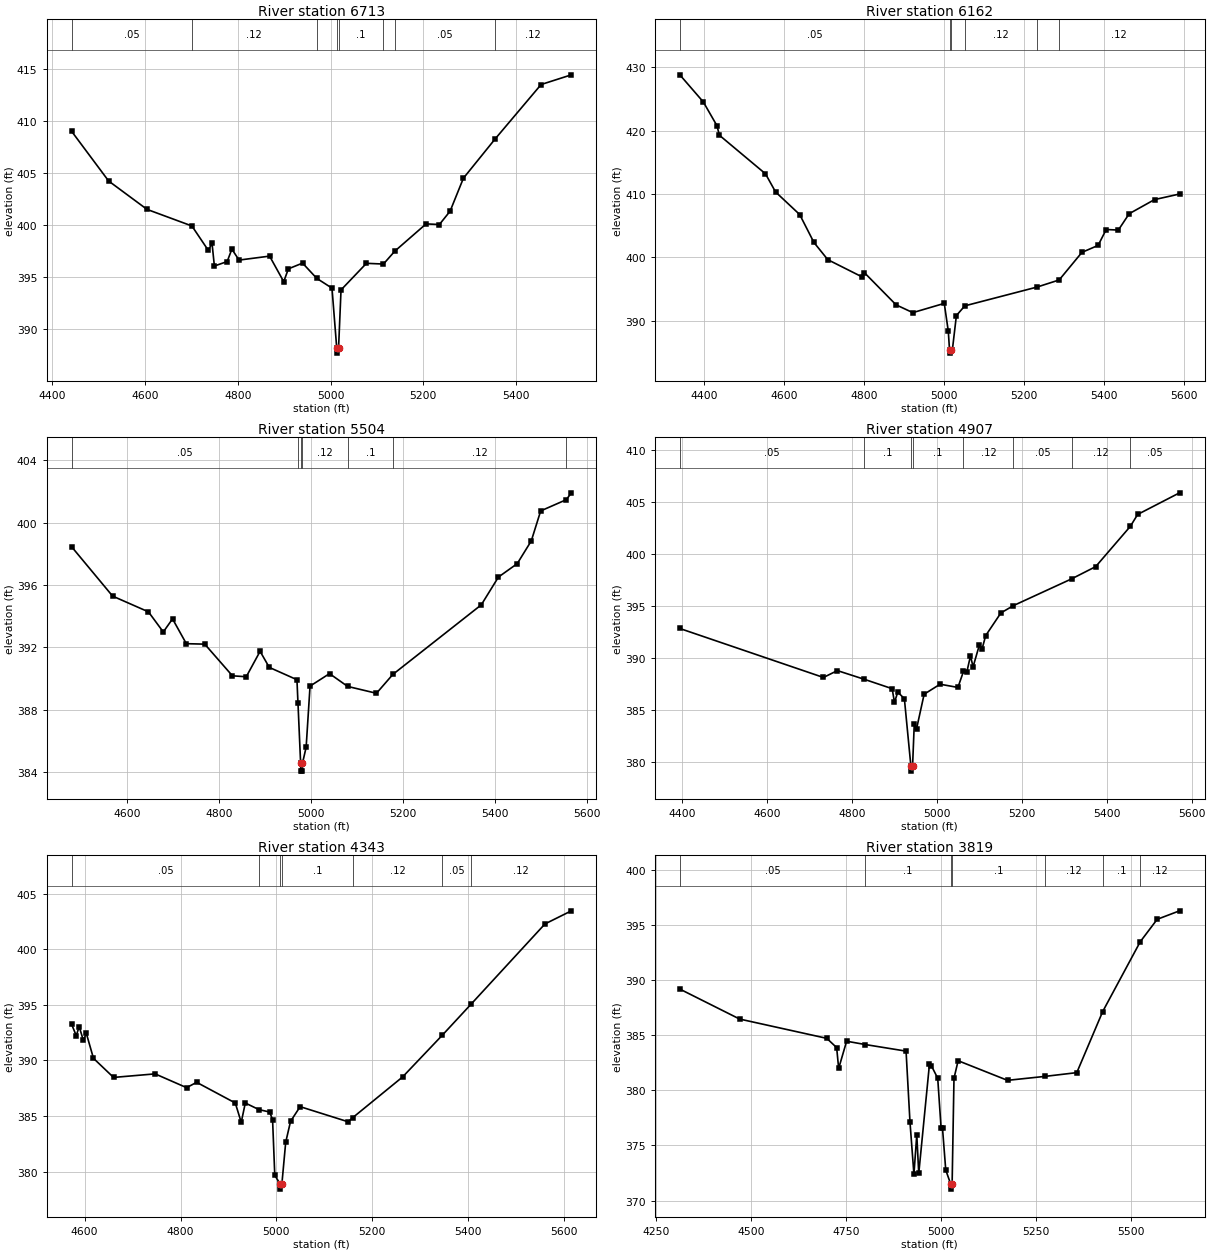
Type RM Length L Ch R = 1,6713,551,551,551
BEGIN DESCRIPTION:
CCT8_2 10.0
END DESCRIPTION:
XS GIS Cut Line= 3
      2719926.00      6883511.01      2720026.51      6884060.50
      2719813.68      6884534.29
#Sta/Elev= 30
  4441.4  408.98  4521.2  404.22  4604.0  401.50  4700.8  399.91  4736.2  397.57
  4744.2  398.26  4749.3  396.07  4776.9  396.50  4787.0  397.69  4802.5  396.64
  4868.4  397.02  4898.9  394.57  4908.9  395.80  4939.5  396.35  4970.1  394.89
  5003.0  393.95  5013.2  388.22  5013.5  387.72  5017.2  388.22  5022.5  393.78
  5077.3  396.33  5114.0  396.26  5138.6  397.50  5206.0  400.11  5234.7  400.05
  5257.8  401.33  5286.5  404.49  5354.5  408.23  5454.1  413.47  5519.4  414.40
#Mann=8,-1,0
  4441.4    0.05       0  4700.8    0.12       0  4970.1     0.1       0
  5013.2    0.07       0  5017.2     0.1       0  5114.0    0.12       0
  5138.6    0.05       0  5354.5    0.12       0
Bank Sta=5013.2,5017.2
Exp/Cntr=0.3,0.1

Type RM Length L Ch R = 1,6162,658,658,658
BEGIN DESCRIPTION:
Mapping XS 6eee4639
END DESCRIPTION:
XS GIS Cut Line= 3
      2719453.43      6883302.51      2719508.99      6883976.14
      2719422.18      6884542.10
#Sta/Elev= 30
  4339.4  428.81  4398.1  424.53  4432.3  420.77  4438.2  419.28  4553.4  413.19
  4578.7  410.32  4638.9  406.76  4674.4  402.36  4709.1  399.64  4795.4  396.90
  4800.5  397.59  4879.7  392.51  4921.5  391.28  5000.1  392.74  5010.2  388.33
  5013.2  385.39  5013.5  384.89  5017.2  385.39  5020.3  385.39  5030.4  390.82
  5051.4  392.35  5232.1  395.32  5287.2  396.44  5344.0  400.79  5384.4  401.89
  5404.7  404.40  5435.0  404.31  5462.1  406.89  5525.4  409.12  5587.9  410.00
#Mann=6,-1,0
  4339.4    0.05       0  5013.2    0.04       0  5017.2    0.05       0
  5051.4    0.12       0  5232.1    0.05       0  5287.2    0.12       0
Bank Sta=5013.2,5017.2
Exp/Cntr=0.3,0.1

Type RM Length L Ch R = 1,5504,597,597,597
BEGIN DESCRIPTION:
Mapping XS 8e88eecd
END DESCRIPTION:
XS GIS Cut Line= 3
      2718953.43      6883542.13      2718915.24      6884062.94
      2718801.09      6884616.38
#Sta/Elev= 30
  4479.0  398.45  4568.1  395.29  4646.1  394.28  4678.4  392.99  4698.5  393.83
  4728.5  392.24  4768.6  392.21  4828.8  390.18  4858.9  390.12  4889.0  391.75
  4909.0  390.72  4969.2  389.93  4971.4  388.46  4977.2  384.57  4977.5  384.07
  4981.0  384.07  4981.2  384.57  4989.2  385.60  4997.7  389.52  5040.1  390.32
  5079.5  389.50  5142.2  389.06  5177.9  390.27  5370.3  394.73  5407.6  396.51
  5448.5  397.37  5479.1  398.83  5499.5  400.75  5555.2  401.47  5566.3  401.91
#Mann=7,-1,0
  4479.0    0.05       0  4971.4    0.12       0  4977.2    0.07       0
  4981.2    0.12       0  5079.5     0.1       0  5177.9    0.12       0
  5555.2    0.05       0
Bank Sta=4977.2,4981.2
Exp/Cntr=0.3,0.1

Type RM Length L Ch R = 1,4907,564,564,564
BEGIN DESCRIPTION:
Mapping XS 5e54e333
END DESCRIPTION:
XS GIS Cut Line= 3
      2718734.68      6883621.97      2718491.63      6884170.58
      2718161.75      6884642.83
#Sta/Elev= 30
  4395.5  392.87  4733.5  388.16  4766.3  388.82  4829.2  387.99  4895.2  387.08
  4900.7  385.77  4908.5  386.75  4924.0  386.12  4939.3  379.65  4939.6  379.15
  4943.3  379.65  4947.3  383.73  4952.7  383.23  4970.5  386.55  5008.1  387.51
  5050.0  387.20  5063.1  388.74  5070.9  388.68  5079.6  390.23  5085.7  389.18
  5100.6  391.30  5106.7  390.88  5115.4  392.19  5151.2  394.37  5180.6  395.07
  5317.4  397.64  5374.2  398.82  5455.7  402.69  5473.0  403.84  5571.6  405.92
#Mann=8,-1,0
  4395.5    0.05       0  4829.2     0.1       0  4939.3    0.07       0
  4943.3     0.1       0  5063.1    0.12       0  5180.6    0.05       0
  5317.4    0.12       0  5455.7    0.05       0
Bank Sta=4939.3,4943.3
Exp/Cntr=0.3,0.1

Type RM Length L Ch R = 1,4343,524,524,524
BEGIN DESCRIPTION:
Mapping XS a30a92aa
END DESCRIPTION:
XS GIS Cut Line= 3
      2718327.21      6883519.17      2718085.80      6883871.50
      2718051.00      6884486.01
#Sta/Elev= 30
  4572.9  393.24  4582.5  392.23  4588.6  393.04  4597.4  391.80  4603.5  392.44
  4618.4  390.19  4660.3  388.47  4747.0  388.79  4812.7  387.55  4833.7  388.03
  4914.3  386.17  4926.7  384.43  4935.2  386.17  4963.9  385.57  4986.0  385.36
  4992.1  384.67  4996.7  379.66  5007.4  378.92  5007.8  378.42  5011.6  378.92
  5019.5  382.64  5029.6  384.52  5049.6  385.84  5149.7  384.48  5159.6  384.86
  5263.3  388.51  5345.8  392.25  5406.0  395.05  5560.4  402.28  5615.5  403.46
#Mann=7,-1,0
  4572.9    0.05       0  4963.9     0.1       0  5007.4    0.07       0
  5011.6     0.1       0  5159.6    0.12       0  5345.8    0.05       0
  5406.0    0.12       0
Bank Sta=5007.4,5011.6
Exp/Cntr=0.3,0.1

Type RM Length L Ch R = 1,3819,711,711,711
BEGIN DESCRIPTION:
Mapping XS b3788e9f
END DESCRIPTION:
XS GIS Cut Line= 3
      2717807.04      6883249.95      2717612.61      6883913.12
      2717854.92      6884487.74
#Sta/Elev= 30
  4312.2  389.19  4469.6  386.47  4698.9  384.72  4724.8  383.88  4730.1  381.99
  4751.0  384.46  4799.8  384.16  4907.4  383.56  4917.7  377.14  4928.1  372.38
  4935.6  375.98  4940.8  372.46  4969.0  382.39  4974.2  382.22  4990.7  381.10
  4999.6  376.56  5003.3  376.56  5011.8  372.78  5024.4  371.54  5024.7  371.04
  5028.6  371.54  5033.5  381.10  5044.4  382.69  5174.3  380.91  5273.2  381.27
  5356.6  381.61  5424.7  387.15  5523.6  393.49  5568.1  395.52  5626.9  396.29
#Mann=7,-1,0
  4312.2    0.05       0  4799.8     0.1       0  5024.4    0.07       0
  5028.6     0.1       0  5273.2    0.12       0  5424.7     0.1       0
  5523.6    0.12       0
Bank Sta=5024.4,5028.6
Exp/Cntr=0.3,0.1

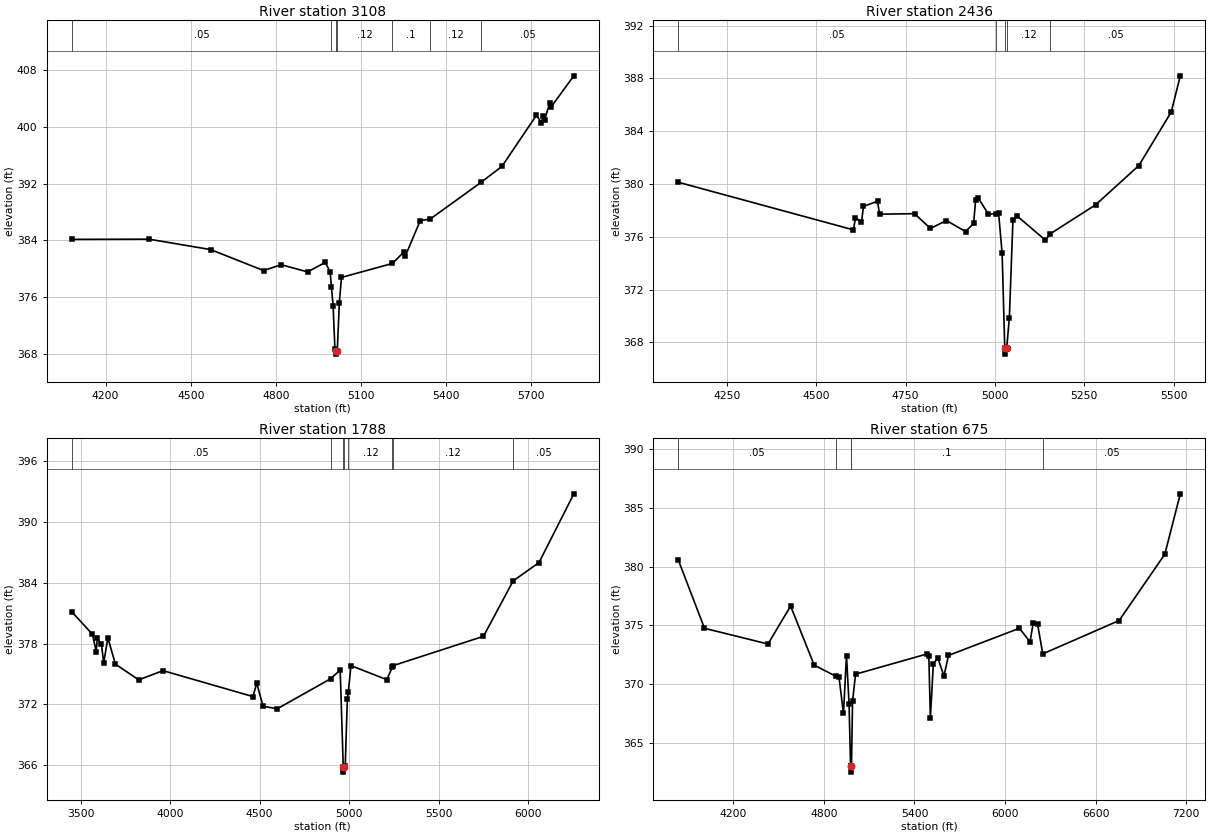
Type RM Length L Ch R = 1,3108,672,672,672
BEGIN DESCRIPTION:
Mapping XS 0a4d3f03
END DESCRIPTION:
XS GIS Cut Line= 3
      2717053.76      6883558.27      2717288.07      6884439.39
      2718069.28      6884790.93
#Sta/Elev= 30
  4081.0  384.12  4352.9  384.15  4570.2  382.68  4756.4  379.72  4818.5  380.54
  4911.6  379.53  4973.7  380.86  4991.0  379.55  4995.6  377.44  5001.4  374.77
  5007.9  368.59  5010.6  368.42  5011.4  367.92  5016.2  368.42  5023.4  375.16
  5031.0  378.75  5210.4  380.72  5250.4  382.33  5255.8  381.76  5308.5  386.78
  5342.7  386.97  5523.3  392.19  5596.4  394.44  5717.6  401.64  5735.3  400.60
  5740.8  401.48  5747.1  401.03  5763.9  403.34  5769.4  402.83  5849.4  407.21
#Mann=7,-1,0
  4081.0    0.05       0  4995.6    0.12       0  5010.6    0.07       0
  5016.2    0.12       0  5210.4     0.1       0  5342.7    0.12       0
  5523.3    0.05       0
Bank Sta=5010.6,5016.2
Exp/Cntr=0.3,0.1

Type RM Length L Ch R = 1,2436,648,648,648
BEGIN DESCRIPTION:
Mapping XS 8ff8cf54
END DESCRIPTION:
XS GIS Cut Line= 3
      2716671.74      6884209.33      2717058.03      6884986.26
      2717591.49      6885042.64
#Sta/Elev= 30
  4114.2  380.13  4604.3  376.52  4609.9  377.45  4626.7  377.11  4632.3  378.30
  4671.5  378.69  4677.1  377.71  4775.0  377.75  4819.6  376.63  4864.3  377.23
  4917.9  376.39  4940.3  377.02  4945.8  378.77  4953.7  378.92  4981.7  377.70
  5003.6  377.76  5010.0  377.83  5020.0  374.74  5027.3  367.61  5028.2  367.11
  5032.9  367.61  5040.2  369.86  5050.2  377.25  5060.3  377.61  5140.7  375.75
  5155.0  376.23  5281.5  378.42  5402.2  381.39  5492.7  385.44  5518.3  388.19
#Mann=5,-1,0
  4114.2    0.05       0  5003.6    0.12       0  5027.3    0.05       0
  5032.9    0.12       0  5155.0    0.05       0
Bank Sta=5027.3,5032.9
Exp/Cntr=0.3,0.1

Type RM Length L Ch R = 1,1788,1113,1113,1113
BEGIN DESCRIPTION:
Mapping XS 37474810
END DESCRIPTION:
XS GIS Cut Line= 3
      2715750.99      6884435.99      2716474.75      6885452.05
      2718030.52      6885418.77
#Sta/Elev= 30
  3450.8  381.14  3566.4  378.92  3587.3  377.22  3593.4  378.52  3616.6  377.94
  3629.1  376.09  3652.4  378.57  3694.2  375.98  3824.6  374.42  3960.3  375.33
  4462.7  372.77  4483.6  374.10  4519.2  371.81  4598.8  371.57  4896.2  374.53
  4949.6  375.39  4966.8  365.81  4967.6  365.31  4972.4  365.81  4977.8  365.92
  4989.6  372.52  4995.3  373.23  5009.6  375.83  5209.6  374.44  5241.6  375.69
  5244.3  375.82  5749.8  378.72  5915.4  384.19  6059.8  386.00  6254.4  392.79
#Mann=8,-1,0
  3450.8    0.05       0  4896.2     0.1       0  4966.8    0.07       0
  4972.4     0.1       0  4995.3    0.12       0  5241.6     0.1       0
  5244.3    0.12       0  5915.4    0.05       0
Bank Sta=4966.8,4972.4
Exp/Cntr=0.3,0.1

Type RM Length L Ch R = 1,675,0,0,0
BEGIN DESCRIPTION:
CCT8_2 2.0
END DESCRIPTION:
XS GIS Cut Line= 3
      2715702.09      6884447.11      2715754.67      6885664.87
      2717861.23      6885592.37
#Sta/Elev= 30
  3834.9  380.59  4008.9  374.76  4429.3  373.42  4579.5  376.65  4735.8  371.62
  4879.8  370.67  4899.8  370.63  4929.8  367.51  4949.8  372.44  4966.8  368.31
  4976.8  363.01  4977.8  362.51  4982.9  363.01  4989.9  368.58  5009.9  370.85
  5485.4  372.58  5495.4  372.37  5505.4  367.11  5525.4  371.75  5555.4  372.23
  5595.4  370.69  5625.5  372.45  6095.7  374.76  6165.8  373.60  6187.3  375.24
  6215.8  375.12  6250.3  372.58  6756.1  375.42  7058.7  381.06  7161.6  386.21
#Mann=5,-1,0
  3834.9    0.05       0  4879.8     0.1       0  4976.8    0.07       0
  4982.9     0.1       0  6250.3    0.05       0
Bank Sta=4976.8,4982.9
Exp/Cntr=0.3,0.1

Chan Stop Cuts=-1