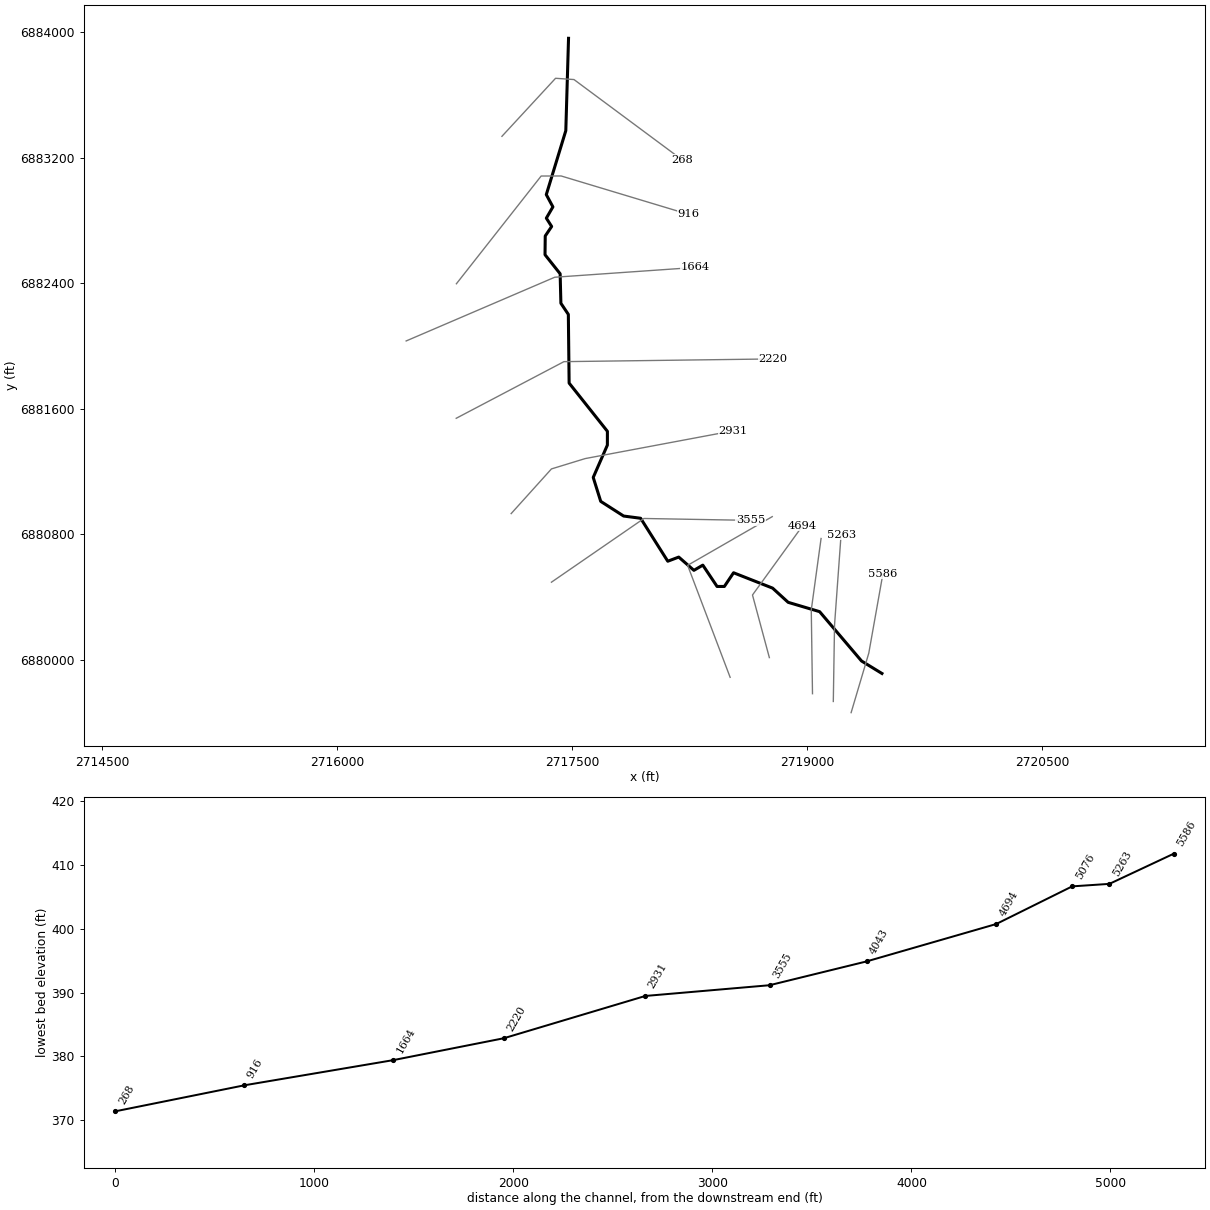
--- CCT8_2_1.prj (project) ---

Proj Title=CCT8_2_1 Base Level Engineering
Current Plan=p01
Default Exp/Contr=0.3,0.1
English Units
Geom File=g01
Flow File=f01
Plan File=p01
Y Axis Title=Elevation
X Axis Title(PF)=Main Channel Distance
X Axis Title(XS)=Station
BEGIN DESCRIPTION:
CCT8_2_1
END DESCRIPTION:
DSS Export Rating Curves= 0
DSS Export Rating Curve Sorted= 0
DSS Export Volume Flow Curves= 0
DXF OffsetX= 0
DXF OffsetY= 0
DXF ScaleX= 1
DXF ScaleY= 10

--- CCT8_2_1.p01 (plan) ---

Plan Title=Multiple Run
Short Identifier=Multiple
Geom File=g01
Flow File=f01
Subcritical Flow
K Sum by GR= 0
Std Step Tol= 0.01
Critical Tol= 0.01
Num of Std Step Trials= 20
Max Error Tol= 0.3
Flow Tol Ratio= 0.001
Split Flow NTrial= 30
Split Flow Tol= 0.02
Split Flow Ratio= 0.02
Log Output Level= 0
Friction Slope Method= 1
Unsteady Friction Slope Method= 2
Unsteady Bridges Friction Slope Method= 1
Parabolic Critical Depth
Global Vel Dist=  1 , 1 , 1
Global Log Level= 0
CheckData=True
Encroach Param= -1, 0, 0, 0
BEGIN DESCRIPTION:
Multiple Run
END DESCRIPTION:

--- CCT8_2_1.f01 (steady flow) ---

Flow Title=Multiple
Program Version=4.10
Number of Profiles= 7
Profile Names=10-year,25-year,50-year,1pct_min,100-year,1pct_plu,500-year
River Rch & RM=CCT8_2_1,Reach-1         ,5586
     336     435     512     301     600    1197     820
River Rch & RM=CCT8_2_1,Reach-1         ,3555
     606     815     984     591    1178    2351    1686
Boundary for River Rch & Prof#=CCT8_2_1,Reach-1         , 1
Up Type= 0
Dn Type= 3
Dn Slope=0.00615
Boundary for River Rch & Prof#=CCT8_2_1,Reach-1         , 2
Up Type= 0
Dn Type= 3
Dn Slope=0.00615
Boundary for River Rch & Prof#=CCT8_2_1,Reach-1         , 3
Up Type= 0
Dn Type= 3
Dn Slope=0.00615
Boundary for River Rch & Prof#=CCT8_2_1,Reach-1         , 4
Up Type= 0
Dn Type= 3
Dn Slope=0.00615
Boundary for River Rch & Prof#=CCT8_2_1,Reach-1         , 5
Up Type= 0
Dn Type= 3
Dn Slope=0.00615
Boundary for River Rch & Prof#=CCT8_2_1,Reach-1         , 6
Up Type= 0
Dn Type= 3
Dn Slope=0.00615
Boundary for River Rch & Prof#=CCT8_2_1,Reach-1         , 7
Up Type= 0
Dn Type= 3
Dn Slope=0.00615
DSS Import GetInterval= 0
DSS Import GetPeak= 0
DSS Import FillOption= 0

--- CCT8_2_1.g01 (geometry) ---

Geom Title=Existing Conditions
Program Version=4.10

River Reach=CCT8_2_1        ,Reach-1
Reach XY= 30
        2719476.        6879911.      2719345.76      6879990.58
       2719078.3      6880305.17       2718877.5      6880364.62
      2718778.29      6880455.15      2718529.04      6880553.18
      2718470.35      6880465.79       2718423.8      6880465.83
      2718332.95      6880601.81      2718276.01      6880568.59
      2718179.33      6880653.11      2718109.22      6880626.69
       2717936.1      6880900.61      2717827.59      6880914.83
      2717681.42      6881008.33      2717633.56        6881161.
      2717723.84      6881366.98      2717724.04      6881455.11
      2717479.75      6881762.55      2717474.78       6882200.5
      2717427.22      6882271.51      2717422.45      6882459.53
      2717325.94      6882580.99      2717327.36      6882700.56
      2717368.21       6882761.1      2717334.32      6882814.23
      2717376.22        6882886.       2717334.1      6882964.29
      2717458.56      6883372.06        2717476.        6883961.

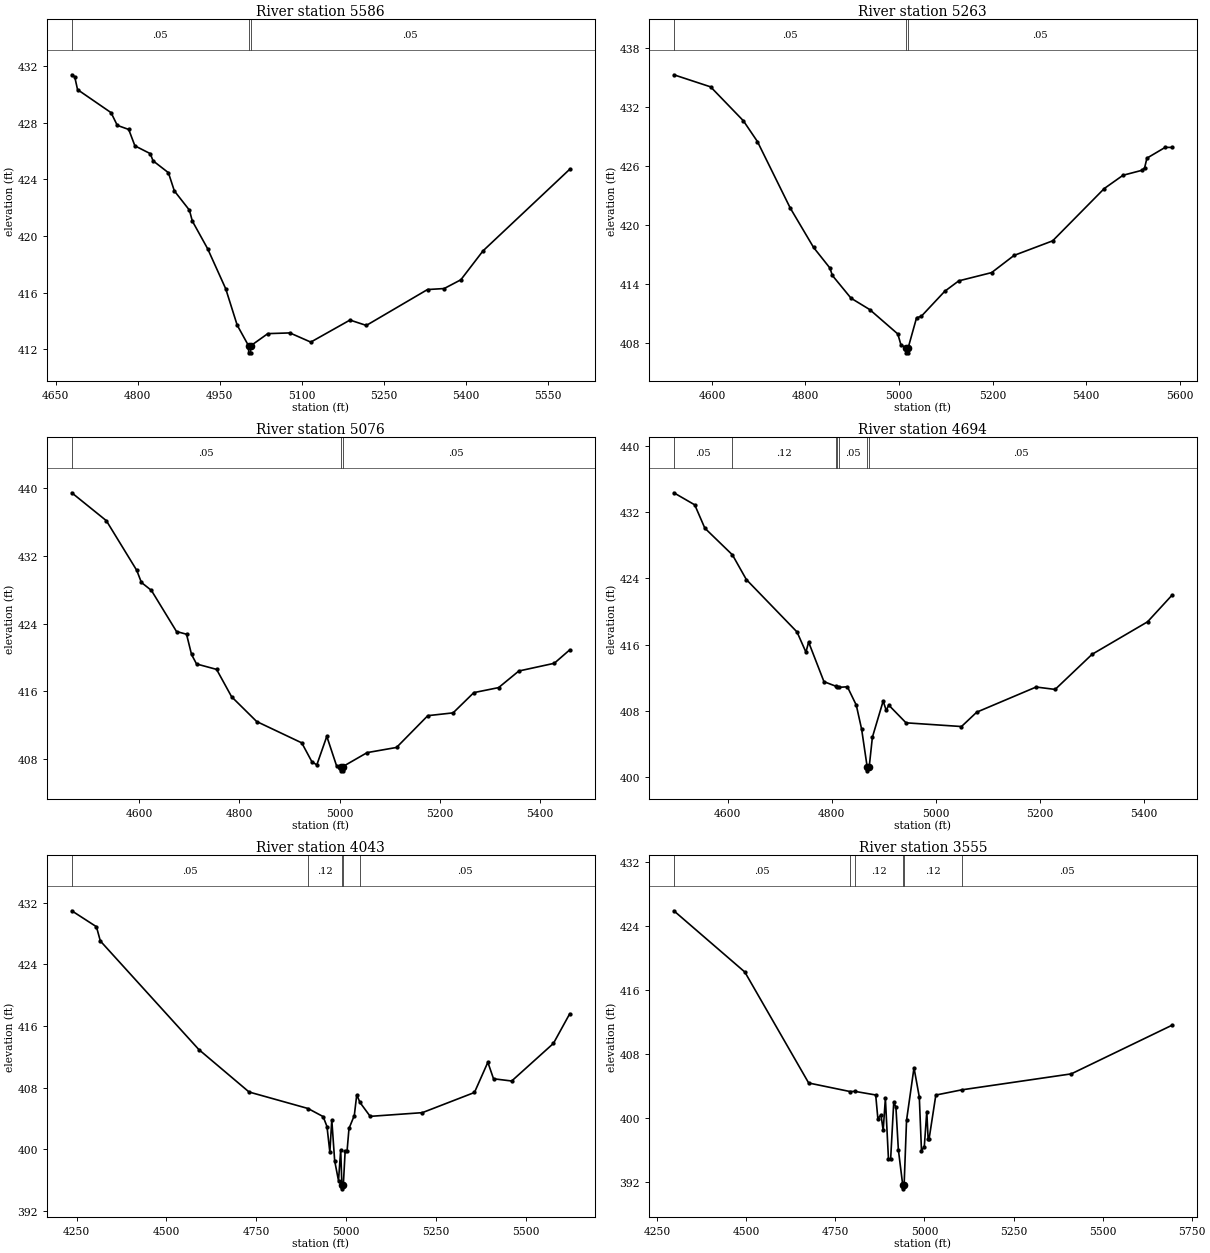
Type RM Length L Ch R = 1 ,5586    ,323,323,323
BEGIN DESCRIPTION:
Mapping XS b7b927ad
END DESCRIPTION:
XS GIS Cut Line= 3
      2719279.35      6879661.25      2719392.08      6880040.75
       2719482.2       6880546.8
#Sta/Elev= 30
  4679.4  431.41  4684.8  431.27    4690  430.36  4751.2  428.73  4762.6  427.83
  4783.5  427.54  4794.8  426.38  4822.8  425.83    4828  425.32    4856  424.48
  4866.9  423.19  4894.4  421.83  4899.7  421.06  4927.7   419.1  4960.8  416.26
  4981.7  413.69  5002.5  412.23  5002.7  411.73  5006.2  411.73  5006.5  412.23
  5037.7  413.09    5078  413.14  5116.2  412.49  5187.8  414.05  5217.7  413.67
  5329.5  416.21  5359.9  416.28  5390.4   416.9    5431  418.95  5589.3  424.72
#Mann= 3 ,-1 , 0
  4679.4     .05       0  5002.5     .04       0  5006.5     .05       0
Bank Sta=5002.5,5006.5
XS Rating Curve= 0 ,0
Exp/Cntr=0.3,0.1

Type RM Length L Ch R = 1 ,5263    ,187,187,187
BEGIN DESCRIPTION:
Mapping XS 5e75c5b8
END DESCRIPTION:
XS GIS Cut Line= 3
      2719165.65      6879732.43      2719173.46      6880219.46
      2719215.13      6880794.96
#Sta/Elev= 30
  4518.7  435.29  4597.3  434.06  4667.3  430.61  4697.3   428.5  4767.3  421.75
  4817.3  417.73  4852.3  415.63  4857.3  414.89  4897.3  412.57  4937.3  411.41
  4997.3  408.93  5004.1  407.81  5015.4  407.51  5015.6  407.01  5019.1  407.01
  5019.4  407.51  5037.4  410.58  5047.4  410.72  5097.6  413.27  5127.6  414.33
  5197.8  415.17  5245.8  416.92  5328.2   418.4  5438.5  423.72  5478.6  425.07
  5518.7  425.57  5524.7  425.82  5529.7  426.81  5568.8  427.91  5582.8   427.9
#Mann= 3 ,-1 , 0
  4518.7     .05       0  5015.4     .05       0  5019.4     .05       0
Bank Sta=5015.4,5019.4
XS Rating Curve= 0 ,0
Exp/Cntr=0.3,0.1

Type RM Length L Ch R = 1 ,5076    ,382,382,382
BEGIN DESCRIPTION:
Mapping XS 9e78e8de
END DESCRIPTION:
XS GIS Cut Line= 3
      2719032.84      6879781.97      2719025.03      6880315.81
      2719087.53      6880771.55
#Sta/Elev= 30
  4465.4  439.43  4534.4  436.14  4595.2  430.27  4604.4  428.85  4624.4  427.91
  4674.5  423.06  4694.5  422.74  4704.5  420.35  4714.5  419.23  4754.5  418.59
  4784.5  415.36  4834.5  412.44  4924.5  409.92  4944.5  407.72  4954.5  407.31
  4974.5  410.69  4994.4  407.14  5002.5  407.12  5002.8  406.62  5006.3  406.62
  5006.5  407.12    5055  408.77  5113.7  409.38  5176.1  413.13  5226.6  413.46
    5268  415.85  5317.4  416.44  5357.8   418.4  5428.5  419.31  5459.3  420.89
#Mann= 3 ,-1 , 0
  4465.4     .05       0  5002.5     .05       0  5006.5     .05       0
Bank Sta=5002.5,5006.5
XS Rating Curve= 0 ,0
Exp/Cntr=0.3,0.1

Type RM Length L Ch R = 1 ,4694    ,651,651,651
BEGIN DESCRIPTION:
Mapping XS f48398c8
END DESCRIPTION:
XS GIS Cut Line= 3
      2718757.53      6880012.14       2718649.9      6880411.41
      2718969.31      6880852.35
#Sta/Elev= 30
  4496.3  434.36  4536.5   432.9  4555.9  430.08    4609  426.85  4635.8  423.86
  4733.3  417.52  4750.4  415.08  4755.6  416.29  4785.1  411.51  4808.7  410.94
  4810.5  410.89  4813.2  410.82  4830.2  410.89  4847.3  408.67  4857.6  405.75
  4868.2  401.22  4868.4  400.72  4872.2  401.22  4878.3  404.79    4899  409.16
  4904.9  408.04  4909.8  408.67    4943  406.53  5049.7  406.08  5079.1  407.82
  5193.3  410.86  5229.9  410.57    5301  414.82  5407.7  418.75  5454.3  421.94
#Mann= 7 ,-1 , 0
  4496.3     .05       0    4609     .12       0  4808.7     .05       0
  4810.5     .12       0  4813.2     .05       0  4868.2     .05       0
  4872.2     .05       0
Bank Sta=4868.2,4872.2
XS Rating Curve= 0 ,0
Exp/Cntr=0.3,0.1

Type RM Length L Ch R = 1 ,4043    ,488,488,488
BEGIN DESCRIPTION:
CCT8_2_1 8.0
END DESCRIPTION:
XS GIS Cut Line= 3
      2718507.24      6879886.55        2718236.      6880600.57
      2718776.03      6880911.02
#Sta/Elev= 30
  4236.2  430.97  4304.9   428.9  4315.8  427.05  4590.2  412.95  4730.1  407.44
  4894.2   405.3  4936.3  404.25    4947  402.96    4955  399.63  4960.4  403.82
  4968.4  398.51  4979.1  395.93  4985.2  399.93  4988.5  395.37  4988.8  394.87
  4992.5  395.37  4997.6  399.77  5002.9  399.77  5008.3  402.71  5023.1  404.39
  5029.9  407.08  5038.8  406.09  5067.3  404.28  5212.5  404.76  5357.7  407.38
    5395   411.3  5410.8  409.16  5461.4  408.87  5577.6  413.75  5622.9  417.59
#Mann= 5 ,-1 , 0
  4236.2     .05       0  4894.2     .12       0  4988.5     .07       0
  4992.5     .12       0  5038.8     .05       0
Bank Sta=4988.5,4992.5
XS Rating Curve= 0 ,0
Exp/Cntr=0.3,0.1

Type RM Length L Ch R = 1 ,3555    ,624,624,624
BEGIN DESCRIPTION:
Mapping XS 9912929b
END DESCRIPTION:
XS GIS Cut Line= 3
      2717366.94      6880493.03      2717957.19      6880899.26
      2718638.06      6880887.17
#Sta/Elev= 30
  4296.7  425.92  4495.9  418.26  4675.1  404.38  4791.2  403.31  4805.1  403.33
  4863.2  402.88  4869.3  399.93  4878.1  400.38  4884.2  398.45  4890.4  402.47
  4899.1  394.83  4905.1  394.81  4913.9  402.02    4920  401.32  4926.8  396.06
    4939  391.64  4939.2  391.14    4943  391.64  4949.8  399.71  4970.7  406.28
  4985.6  402.63  4991.7  395.92  4999.6   396.4  5006.6  400.81  5010.3  397.43
  5013.2  397.43    5032  402.87  5104.5  403.52  5412.1  405.52  5694.2  411.59
#Mann= 6 ,-1 , 0
  4296.7     .05       0  4791.2      .1       0  4805.1     .12       0
    4939     .07       0    4943     .12       0  5104.5     .05       0
Bank Sta=4939,4943
XS Rating Curve= 0 ,0
Exp/Cntr=0.3,0.1

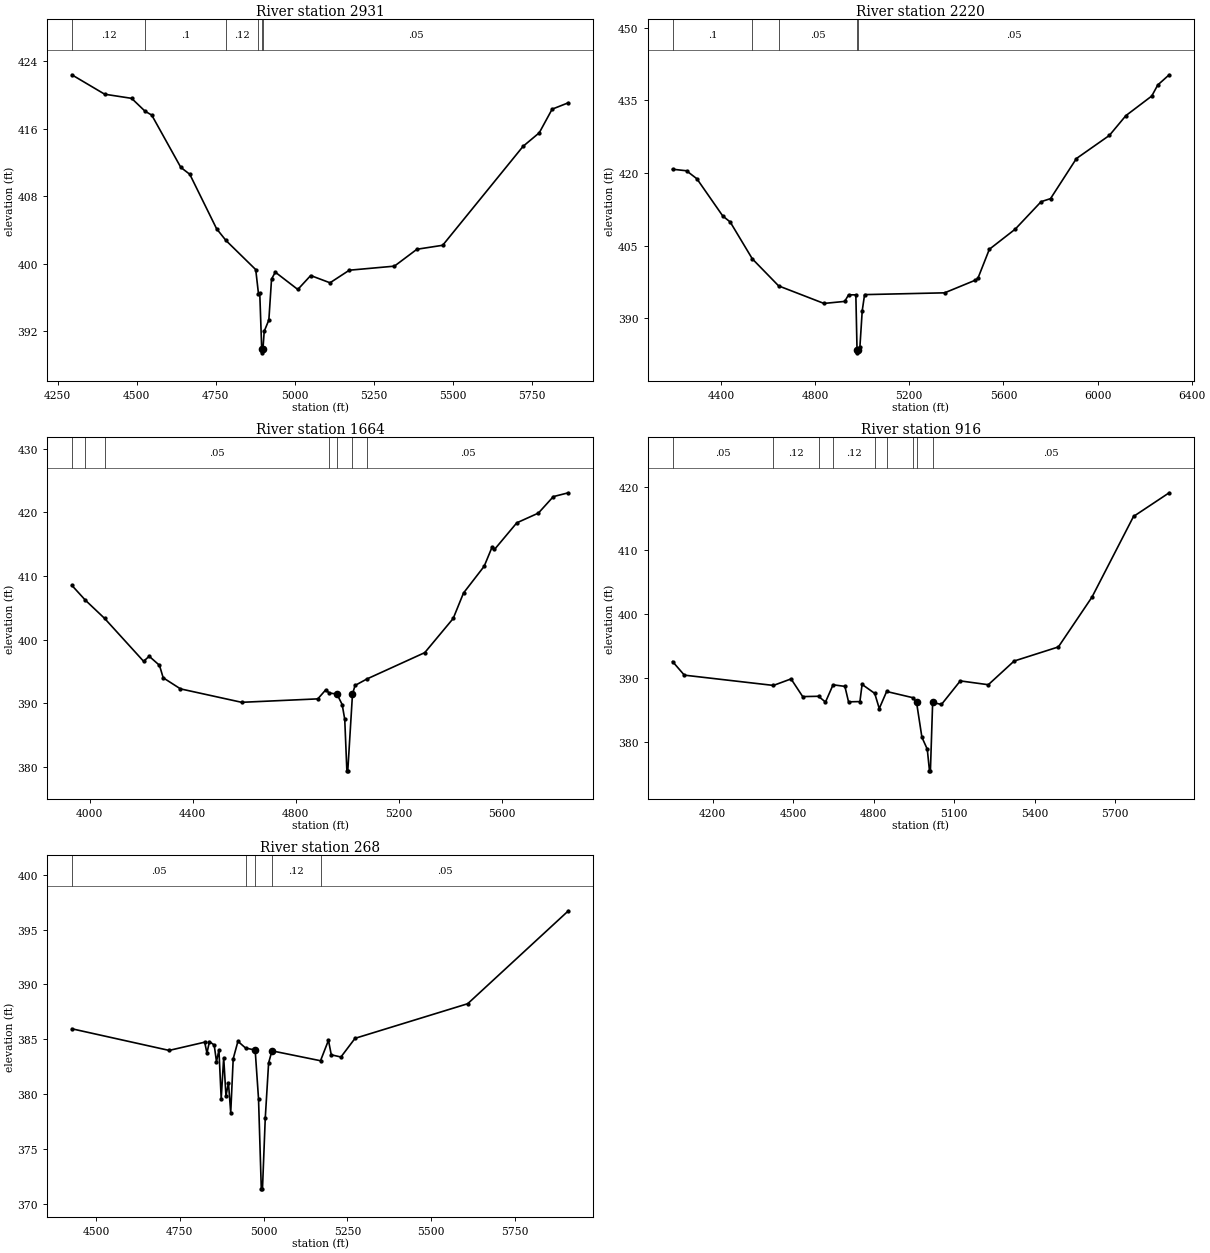
Type RM Length L Ch R = 1 ,2931    ,711,711,711
BEGIN DESCRIPTION:
Mapping XS 24e13c30
END DESCRIPTION:
XS GIS Cut Line= 4
      2717109.95      6880930.49      2717366.91      6881215.23
      2717582.19       6881281.2      2718526.62      6881458.29
#Sta/Elev= 30
  4294.7  422.37  4398.6  420.07  4483.8  419.58  4526.4  418.05  4547.3   417.6
  4639.2  411.41  4667.6  410.59  4752.4  404.14  4781.9  402.76    4876  399.31
  4884.7  396.45  4888.7  396.57  4894.9  389.96  4895.2  389.46  4898.9  389.96
  4902.8  392.01  4917.5  393.35    4926  398.19  4937.8  399.01    5009  396.96
  5049.7  398.61  5110.8  397.75  5171.8  399.24  5314.3  399.72  5385.5  401.72
  5466.9  402.19  5721.2  413.91  5772.1   415.5  5812.8   418.3  5864.3  419.06
#Mann= 6 ,-1 , 0
  4294.7     .12       0  4526.4      .1       0  4781.9     .12       0
  4884.7     .05       0  4894.9     .04       0  4898.9     .05       0
Bank Sta=4894.9,4898.9
XS Rating Curve= 0 ,0
Exp/Cntr=0.3,0.1

Type RM Length L Ch R = 1 ,2220    ,556,556,556
BEGIN DESCRIPTION:
Mapping XS 7e339b05
END DESCRIPTION:
XS GIS Cut Line= 3
      2716759.25      6881538.14      2717446.77      6881899.26
      2718780.06      6881916.62
#Sta/Elev= 30
  4194.2  420.75  4253.4  420.43  4297.5  418.78  4407.7  411.08    4439  409.86
  4533.1  402.24  4644.9  396.66  4837.4  393.04  4925.6  393.46    4942  394.82
  4972.9  394.81    4978  383.34  4978.3  382.84    4982  383.34    4990  383.95
    5000  391.53    5010  394.86  5350.1  395.23  5480.1  397.83  5491.8  398.26
  5540.1  404.22  5650.1  408.38  5760.1  414.05  5800.1  414.68  5910.1  422.96
  6050.1  427.73  6120.1  431.81  6230.1  435.86  6255.8  438.15  6304.2  440.25
#Mann= 5 ,-1 , 0
  4194.2      .1       0  4533.1     .12       0  4644.9     .05       0
    4978     .04       0    4982     .05       0
Bank Sta=4978,4982
XS Rating Curve= 0 ,0
Exp/Cntr=0.3,0.1

Type RM Length L Ch R = 1 ,1664    ,748,748,748
BEGIN DESCRIPTION:
Mapping XS 483ea65d
END DESCRIPTION:
XS GIS Cut Line= 3
      2716439.86      6882031.22      2717387.74      6882437.45
       2718282.3      6882499.87
#Sta/Elev= 30
  3930.3  408.54  3983.3  406.19  4057.5  403.35    4209  396.61  4230.7   397.4
  4270.6  395.98  4285.1  394.02  4352.2  392.28  4589.8  390.17  4885.3  390.71
  4916.2  392.13  4929.3  391.64  4959.7  391.46  4979.9  389.82  4989.9  387.51
  4998.2  379.41  5001.7  379.41    5020  391.47    5030  392.82  5075.8  393.83
  5300.6  397.97  5410.9  403.33    5451  407.33  5531.2  411.53  5561.3  414.48
  5571.3  414.17  5657.8  418.35  5741.7  419.88  5799.8  422.47  5858.3  423.07
#Mann= 7 ,-1 , 0
  3930.3     .05       0  3983.3     .12       0  4057.5     .05       0
  4929.3     .12       0  4959.7     .04       0    5020     .12       0
  5075.8     .05       0
Bank Sta=4959.7,5020
XS Rating Curve= 0 ,0
Exp/Cntr=0.3,0.1

Type RM Length L Ch R = 1 ,916     ,648,648,648
BEGIN DESCRIPTION:
Mapping XS 8e3f5dd3
END DESCRIPTION:
XS GIS Cut Line= 4
      2716760.41      6882395.84      2717301.27      6883082.83
       2717428.9      6883083.18      2718241.42      6882838.64
#Sta/Elev= 30
  4050.9  392.59  4094.8  390.46  4426.7  388.85  4492.4  389.87  4535.8   387.1
  4594.7  387.15  4620.7  386.24  4648.9  388.95    4693   388.7  4706.6  386.28
    4749  386.32  4757.1  389.01  4804.2   387.6  4821.1  385.23  4848.6   387.9
  4947.1  386.92    4960  386.21    4980  380.73    5000  378.86  5008.2  375.47
  5011.7  375.47    5020  386.18  5052.9  385.87    5123  389.56  5227.4  388.96
  5323.6  392.67  5488.5  394.88  5613.8  402.69  5768.5  415.32  5901.4  419.03
#Mann= 9 ,-1 , 0
  4050.9     .05       0  4426.7     .12       0  4594.7      .1       0
  4648.9     .12       0  4804.2      .1       0  4848.6     .12       0
  4947.1     .05       0    4960     .04       0    5020     .05       0
Bank Sta=4960,5020
XS Rating Curve= 0 ,0
Exp/Cntr=0.3,0.1

Type RM Length L Ch R = 1 ,268     ,0,0,0
BEGIN DESCRIPTION:
CCT8_2_1 4.0
END DESCRIPTION:
XS GIS Cut Line= 4
      2717051.02      6883336.02      2717393.22      6883706.08
      2717510.77      6883697.97      2718200.96      6883186.03
#Sta/Elev= 30
    4428  385.97  4718.3     384  4824.3  384.75  4831.1  383.76  4838.5   384.8
  4852.7  384.49  4859.5  382.98  4866.8  384.04  4873.6  379.61    4881  383.34
  4887.8  379.86  4895.2  381.05    4902  378.34  4909.4  383.24  4923.5  384.83
  4946.1  384.22  4974.9  384.03  4984.9   379.6  4993.2   371.4  4996.7   371.4
    5005  377.83    5015  382.86    5025  383.96  5169.8  383.06  5193.5  384.92
  5201.9   383.6  5230.7   383.4  5272.8   385.1  5608.8  388.25  5909.2  396.71
#Mann= 5 ,-1 , 0
    4428     .05       0  4946.1     .12       0  4974.9     .04       0
    5025     .12       0  5169.8     .05       0
Bank Sta=4974.9,5025
XS Rating Curve= 0 ,0
Exp/Cntr=0.3,0.1

Chan Stop Cuts=-1
Use User Specified Reach Order=0
Composite Channel Slope=5