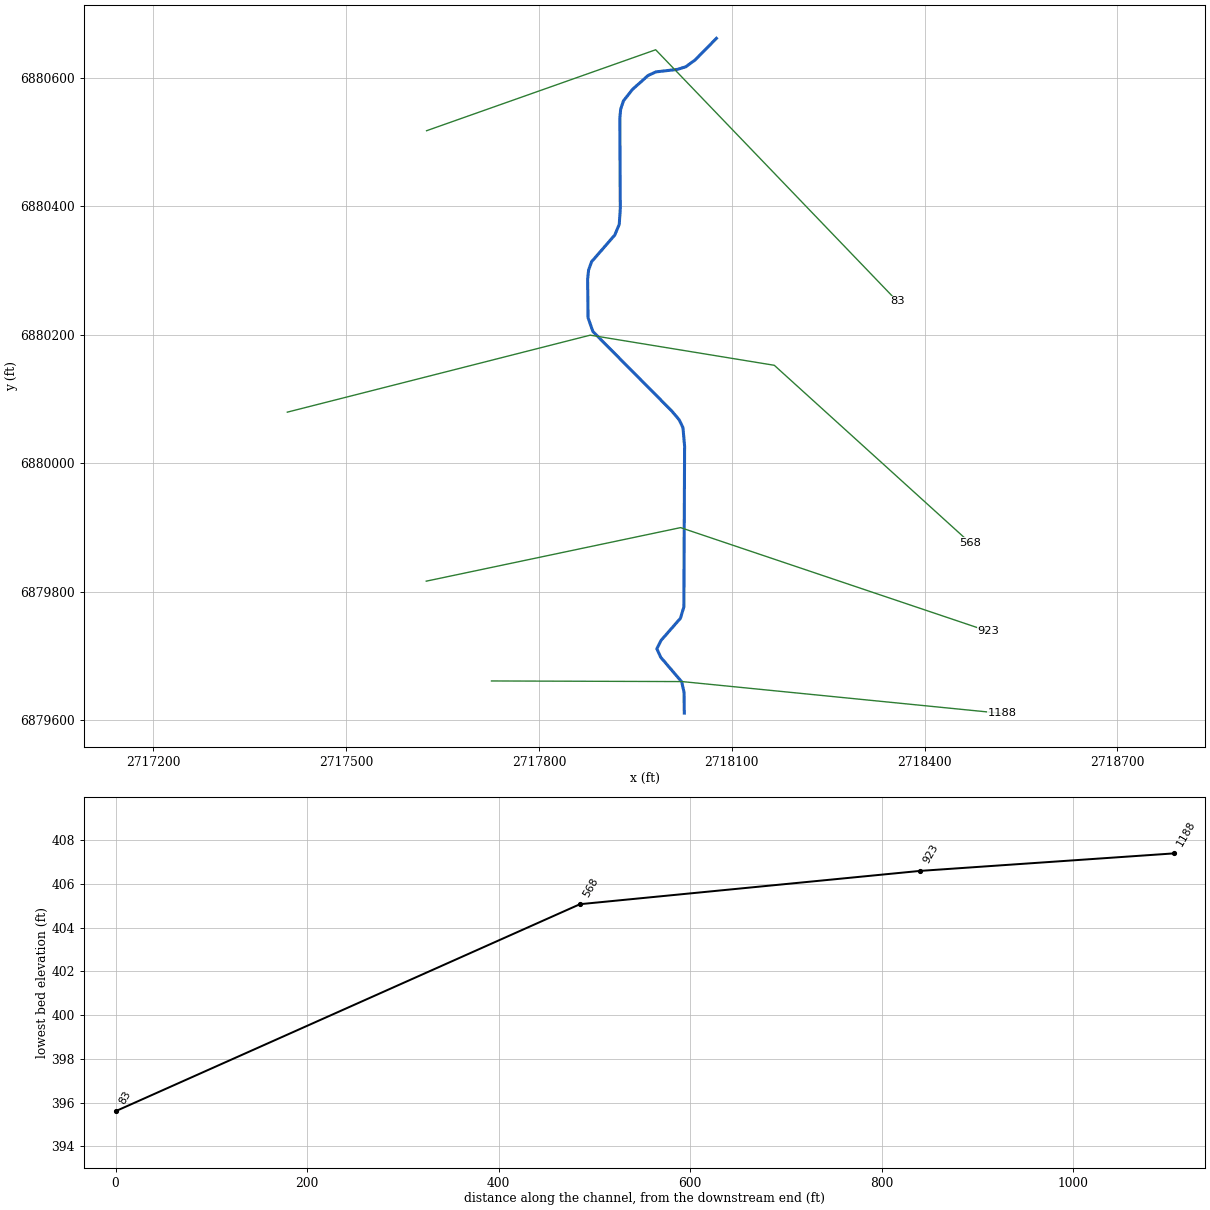
--- CCT8_2_1_1.prj (project) ---

Proj Title=CCT8_2_1_1 Base Level Engineering
Current Plan=p01
Default Exp/Contr=0.3,0.1
English Units
Geom File=g01
Flow File=f01
Plan File=p01
Y Axis Title=Elevation
X Axis Title(PF)=Main Channel Distance
X Axis Title(XS)=Station
BEGIN DESCRIPTION:
CCT8_2_1_1
END DESCRIPTION:
DSS Export Rating Curves= 0
DSS Export Rating Curve Sorted= 0
DSS Export Volume Flow Curves= 0
DXF OffsetX= 0
DXF OffsetY= 0
DXF ScaleX= 1
DXF ScaleY= 10

--- CCT8_2_1_1.p01 (plan) ---

Plan Title=Multiple Run
Short Identifier=Multiple
Geom File=g01
Flow File=f01
Subcritical Flow
K Sum by GR= 0
Std Step Tol= 0.01
Critical Tol= 0.01
Num of Std Step Trials= 20
Max Error Tol= 0.3
Flow Tol Ratio= 0.001
Split Flow NTrial= 30
Split Flow Tol= 0.02
Split Flow Ratio= 0.02
Log Output Level= 0
Friction Slope Method= 1
Unsteady Friction Slope Method= 2
Unsteady Bridges Friction Slope Method= 1
Parabolic Critical Depth
Global Vel Dist=  1 , 1 , 1
Global Log Level= 0
CheckData=True
Encroach Param= -1, 0, 0, 0
BEGIN DESCRIPTION:
Multiple Run
END DESCRIPTION:

--- CCT8_2_1_1.f01 (steady flow) ---

Flow Title=Multiple
Program Version=4.10
Number of Profiles= 7
Profile Names=10-year,25-year,50-year,1pct_min,100-year,1pct_plu,500-year
River Rch & RM=CCT8_2_1_1,Reach-1         ,1188
     230     289     334     193     384     767     506
Boundary for River Rch & Prof#=CCT8_2_1_1,Reach-1         , 1
Up Type= 0
Dn Type= 3
Dn Slope=0.02
Boundary for River Rch & Prof#=CCT8_2_1_1,Reach-1         , 2
Up Type= 0
Dn Type= 3
Dn Slope=0.02
Boundary for River Rch & Prof#=CCT8_2_1_1,Reach-1         , 3
Up Type= 0
Dn Type= 3
Dn Slope=0.02
Boundary for River Rch & Prof#=CCT8_2_1_1,Reach-1         , 4
Up Type= 0
Dn Type= 3
Dn Slope=0.02
Boundary for River Rch & Prof#=CCT8_2_1_1,Reach-1         , 5
Up Type= 0
Dn Type= 3
Dn Slope=0.02
Boundary for River Rch & Prof#=CCT8_2_1_1,Reach-1         , 6
Up Type= 0
Dn Type= 3
Dn Slope=0.02
Boundary for River Rch & Prof#=CCT8_2_1_1,Reach-1         , 7
Up Type= 0
Dn Type= 3
Dn Slope=0.02
DSS Import GetInterval= 0
DSS Import GetPeak= 0
DSS Import FillOption= 0

--- CCT8_2_1_1.g01 (geometry) ---

Geom Title=Existing Conditions

River Reach=CCT8_2_1_1,Reach-1
Reach XY= 30
      2718026.00      6879611.00      2718025.69      6879642.88
      2718022.00      6879659.64      2717989.48      6879697.72
      2717983.31      6879710.96      2717989.91      6879724.18
      2718020.00      6879758.55      2718025.35      6879776.16
      2718026.49      6880026.20      2718023.94      6880055.15
      2718018.19      6880067.19      2718006.39      6880081.16
      2717883.76      6880204.83      2717876.24      6880226.22
      2717875.59      6880286.00      2717877.10      6880300.45
      2717881.68      6880313.31      2717917.85      6880354.94
      2717924.78      6880371.50      2717926.43      6880395.82
      2717925.67      6880536.21      2717926.98      6880550.72
      2717931.35      6880563.70      2717945.42      6880581.56
      2717969.55      6880603.09      2717981.74      6880608.76
      2718015.25      6880612.68      2718028.32      6880616.72
      2718042.91      6880627.43      2718076.00      6880661.00

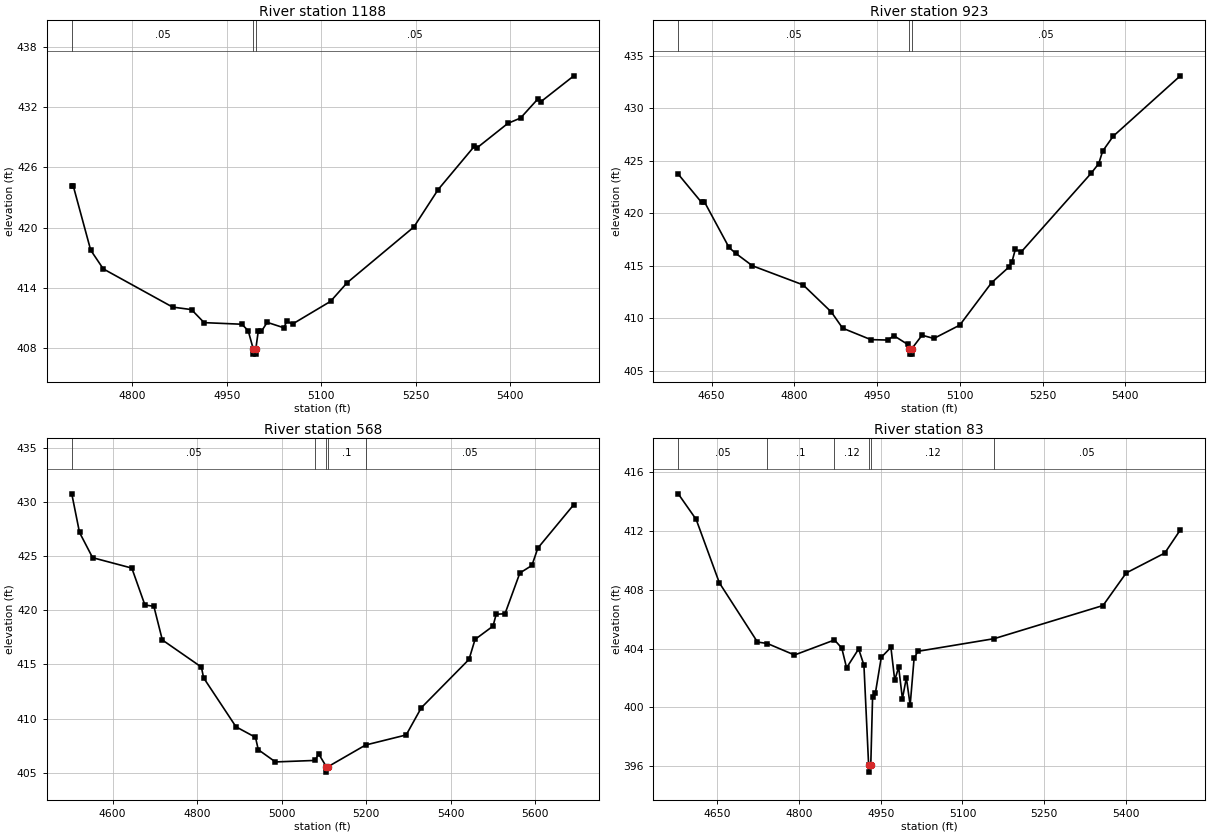
Type RM Length L Ch R = 1,1188,265,265,265
BEGIN DESCRIPTION:
CCT8_2_1_1 2.0
END DESCRIPTION:
XS GIS Cut Line= 3
      2717725.98      6879661.00      2718022.85      6879660.02
      2718520.23      6879610.55
#Sta/Elev= 30
  4704.2  424.13  4706.7  424.13  4734.2  417.76  4754.2  415.89  4864.2  412.08
  4894.2  411.83  4914.2  410.53  4974.2  410.37  4984.2  409.72  4992.2  407.89
  4992.5  407.39  4996.0  407.39  4996.2  407.89  5000.1  409.67  5005.2  409.67
  5014.3  410.56  5040.6  410.02  5045.6  410.67  5054.5  410.39  5114.8  412.65
  5141.3  414.52  5247.1  420.07  5285.6  423.80  5342.8  428.10  5347.9  427.99
  5396.2  430.40  5416.3  430.93  5443.6  432.82  5448.6  432.56  5500.9  435.14
#Mann=3,-1,0
  4704.2    0.05       0  4992.2    0.04       0  4996.2    0.05       0
Bank Sta=4992.2,4996.2
Exp/Cntr=0.3,0.1

Type RM Length L Ch R = 1,923,355,355,355
BEGIN DESCRIPTION:
Mapping XS 7394eb32
END DESCRIPTION:
XS GIS Cut Line= 3
      2717624.44      6879816.28      2718020.25      6879899.61
      2718499.39      6879738.16
#Sta/Elev= 30
  4589.4  423.72  4631.7  421.03  4636.8  421.09  4681.5  416.74  4693.2  416.20
  4723.8  415.00  4815.8  413.18  4866.9  410.60  4887.4  409.06  4938.5  407.97
  4969.1  407.93  4980.4  408.34  5005.2  407.52  5008.5  407.09  5008.8  406.59
  5012.3  406.59  5012.5  407.09  5031.4  408.39  5052.7  408.08  5099.7  409.35
  5157.4  413.39  5188.9  414.88  5194.1  415.33  5200.5  416.57  5211.0  416.31
  5337.6  423.79  5351.6  424.72  5358.7  425.91  5377.8  427.33  5499.5  433.08
#Mann=3,-1,0
  4589.4    0.05       0  5008.5    0.04       0  5012.5    0.05       0
Bank Sta=5008.5,5012.5
Exp/Cntr=0.3,0.1

Type RM Length L Ch R = 1,568,485,485,485
BEGIN DESCRIPTION:
Mapping XS 623cddad
END DESCRIPTION:
XS GIS Cut Line= 4
      2717408.26      6880079.29      2717879.62      6880199.09
      2718166.08      6880152.21      2718470.83      6879875.87
#Sta/Elev= 30
  4503.6  430.74  4521.9  427.18  4552.9  424.85  4645.7  423.89  4676.7  420.48
  4697.8  420.37  4717.9  417.26  4810.3  414.76  4815.5  413.77  4892.2  409.25
  4938.3  408.28  4944.9  407.14  4985.5  406.01  5079.5  406.15  5087.6  406.76
  5105.9  405.57  5106.1  405.07  5109.9  405.57  5198.8  407.57  5294.9  408.50
  5330.7  411.01  5443.6  415.47  5457.8  417.31  5500.4  418.54  5507.8  419.63
  5528.7  419.68  5563.9  423.44  5592.3  424.13  5606.5  425.74  5691.6  429.75
#Mann=5,-1,0
  4503.6    0.05       0  5079.5     0.1       0  5105.9    0.04       0
  5109.9     0.1       0  5198.8    0.05       0
Bank Sta=5105.9,5109.9
Exp/Cntr=0.3,0.1

Type RM Length L Ch R = 1,83,0,0,0
BEGIN DESCRIPTION:
CCT8_2_1_1 1.0
END DESCRIPTION:
XS GIS Cut Line= 3
      2717624.95      6880517.23      2717981.48      6880643.23
      2718357.32      6880251.93
#Sta/Elev= 30
  4578.8  414.50  4611.7  412.76  4654.2  408.46  4724.1  404.44  4742.3  404.34
  4792.0  403.56  4865.3  404.58  4878.7  404.03  4887.5  402.69  4909.6  403.97
  4919.3  402.88  4927.9  396.11  4928.2  395.61  4931.9  396.11  4935.2  400.72
  4940.5  401.01  4951.1  403.40  4968.8  404.08  4975.8  401.85  4983.0  402.73
  4989.9  400.59  4997.1  402.01  5004.1  400.16  5011.3  403.33  5018.2  403.81
  5158.3  404.67  5357.8  406.92  5400.3  409.13  5471.0  410.48  5499.5  412.05
#Mann=6,-1,0
  4578.8    0.05       0  4742.3     0.1       0  4865.3    0.12       0
  4927.9    0.07       0  4931.9    0.12       0  5158.3    0.05       0
Bank Sta=4927.9,4931.9
Exp/Cntr=0.3,0.1

Chan Stop Cuts=-1