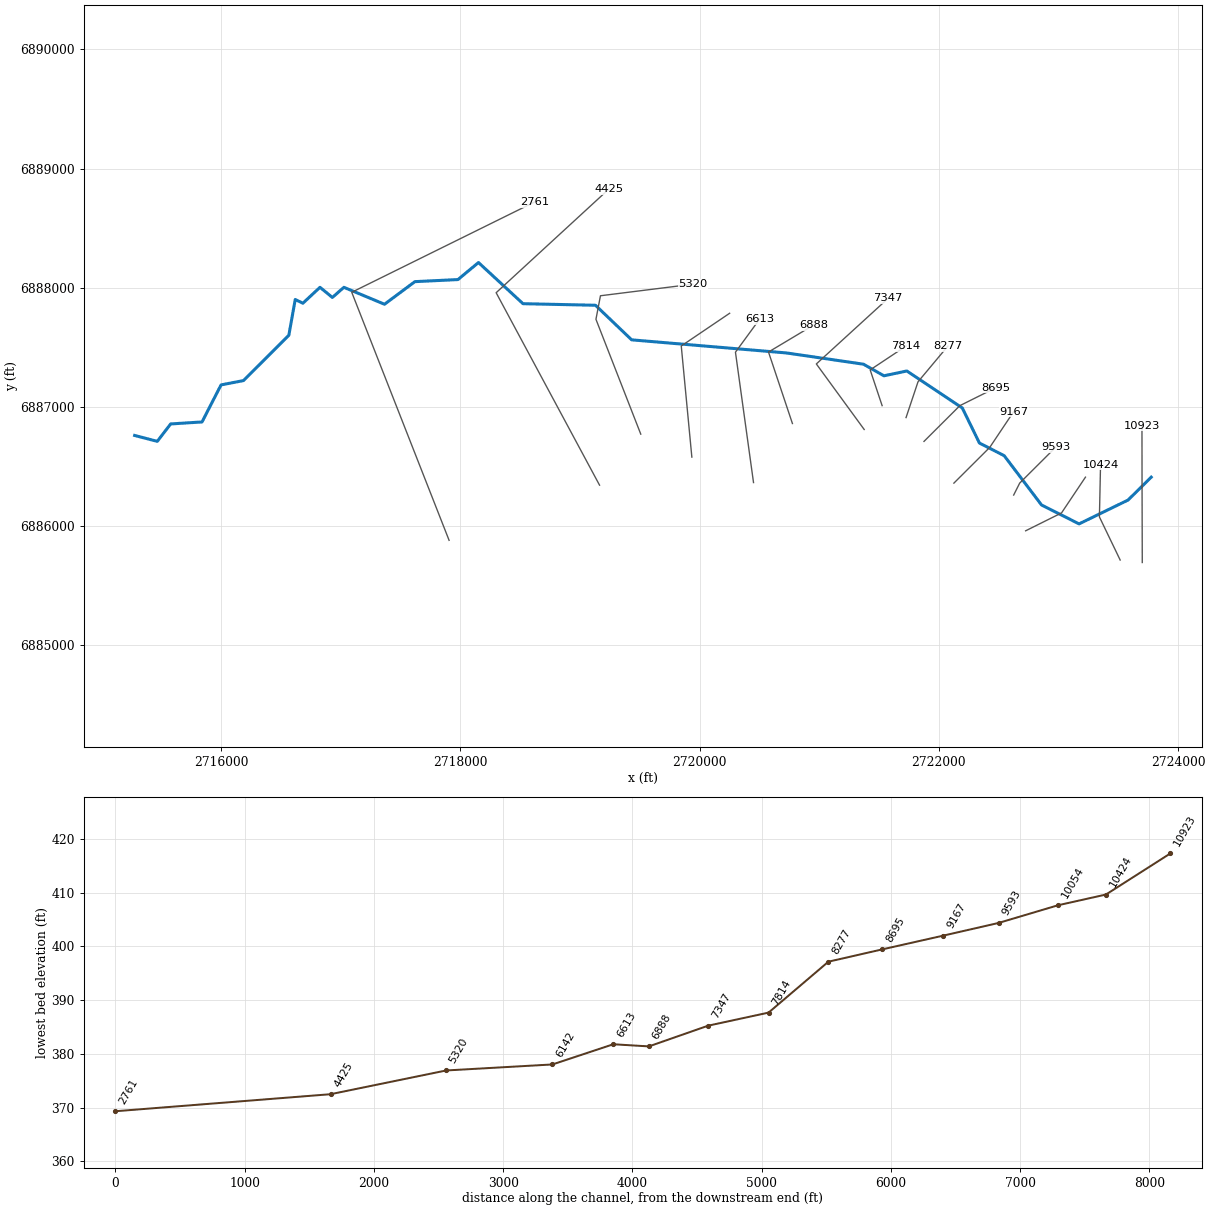
--- CCT8_3.prj (project) ---

Proj Title=CCT8_3 Base Level Engineering
Current Plan=p01
Default Exp/Contr=0.3,0.1
English Units
Geom File=g01
Flow File=f01
Plan File=p01
BEGIN DESCRIPTION:
CCT8_3
END DESCRIPTION:

--- CCT8_3.p01 (plan) ---

Plan Title=Multiple Run
Short Identifier=Multiple
Geom File=g01
Flow File=f01
Subcritical Flow
K Sum by GR= 0
Std Step Tol= 0.01
Critical Tol= 0.01
Num of Std Step Trials= 20
Max Error Tol= 0.3
Flow Tol Ratio= 0.001
Split Flow NTrial= 30
Split Flow Tol= 0.02
Split Flow Ratio= 0.02
Log Output Level= 0
Friction Slope Method= 1
Unsteady Friction Slope Method= 2
Unsteady Bridges Friction Slope Method= 1
Parabolic Critical Depth
Global Vel Dist=  1 , 1 , 1
Global Log Level= 0
CheckData=True
Encroach Param= -1, 0, 0, 0
BEGIN DESCRIPTION:
Multiple Run
END DESCRIPTION:

--- CCT8_3.f01 (steady flow) ---

Flow Title=Multiple
Number of Profiles=7
Profile Names=10-year,25-year,50-year,1pct_min,100-year,1pct_plu,500-year
River Rch & RM= CCT8_3,Reach-1,10923
     516     685     821     489     975    1946    1373
River Rch & RM= CCT8_3,Reach-1,4425
     905    1240    1517     920    1835    3661    2684
Boundary for River Rch & Prof#=CCT8_3,Reach-1,1
Up Type=0
Dn Type=3
Dn Slope=0.005
Boundary for River Rch & Prof#=CCT8_3,Reach-1,2
Up Type=0
Dn Type=3
Dn Slope=0.005
Boundary for River Rch & Prof#=CCT8_3,Reach-1,3
Up Type=0
Dn Type=3
Dn Slope=0.005
Boundary for River Rch & Prof#=CCT8_3,Reach-1,4
Up Type=0
Dn Type=3
Dn Slope=0.005
Boundary for River Rch & Prof#=CCT8_3,Reach-1,5
Up Type=0
Dn Type=3
Dn Slope=0.005
Boundary for River Rch & Prof#=CCT8_3,Reach-1,6
Up Type=0
Dn Type=3
Dn Slope=0.005
Boundary for River Rch & Prof#=CCT8_3,Reach-1,7
Up Type=0
Dn Type=3
Dn Slope=0.005

--- CCT8_3.g01 (geometry) ---

Geom Title=Existing Conditions

River Reach=CCT8_3,Reach-1
Reach XY= 30
      2723776.00      6886411.00      2723582.34      6886219.02
      2723172.68      6886019.04      2722858.95      6886177.49
      2722546.51      6886591.28      2722339.46      6886697.37
      2722196.51      6886991.27      2721732.73      6887301.85
      2721541.22      6887261.49      2721370.07      6887358.76
      2720725.90      6887453.21      2719431.85      6887563.06
      2719129.42      6887853.21      2718523.30      6887866.36
      2718151.08      6888211.61      2717979.42      6888068.80
      2717619.45      6888051.41      2717365.36      6887861.64
      2717025.91      6888003.69      2716929.33      6887918.64
      2716826.00      6888003.90      2716682.66      6887870.31
      2716618.96      6887901.81      2716565.37      6887601.00
      2716186.12      6887221.35      2715998.67      6887185.02
      2715839.67      6886874.23      2715577.25      6886857.55
      2715465.53      6886711.53      2715276.00      6886761.00

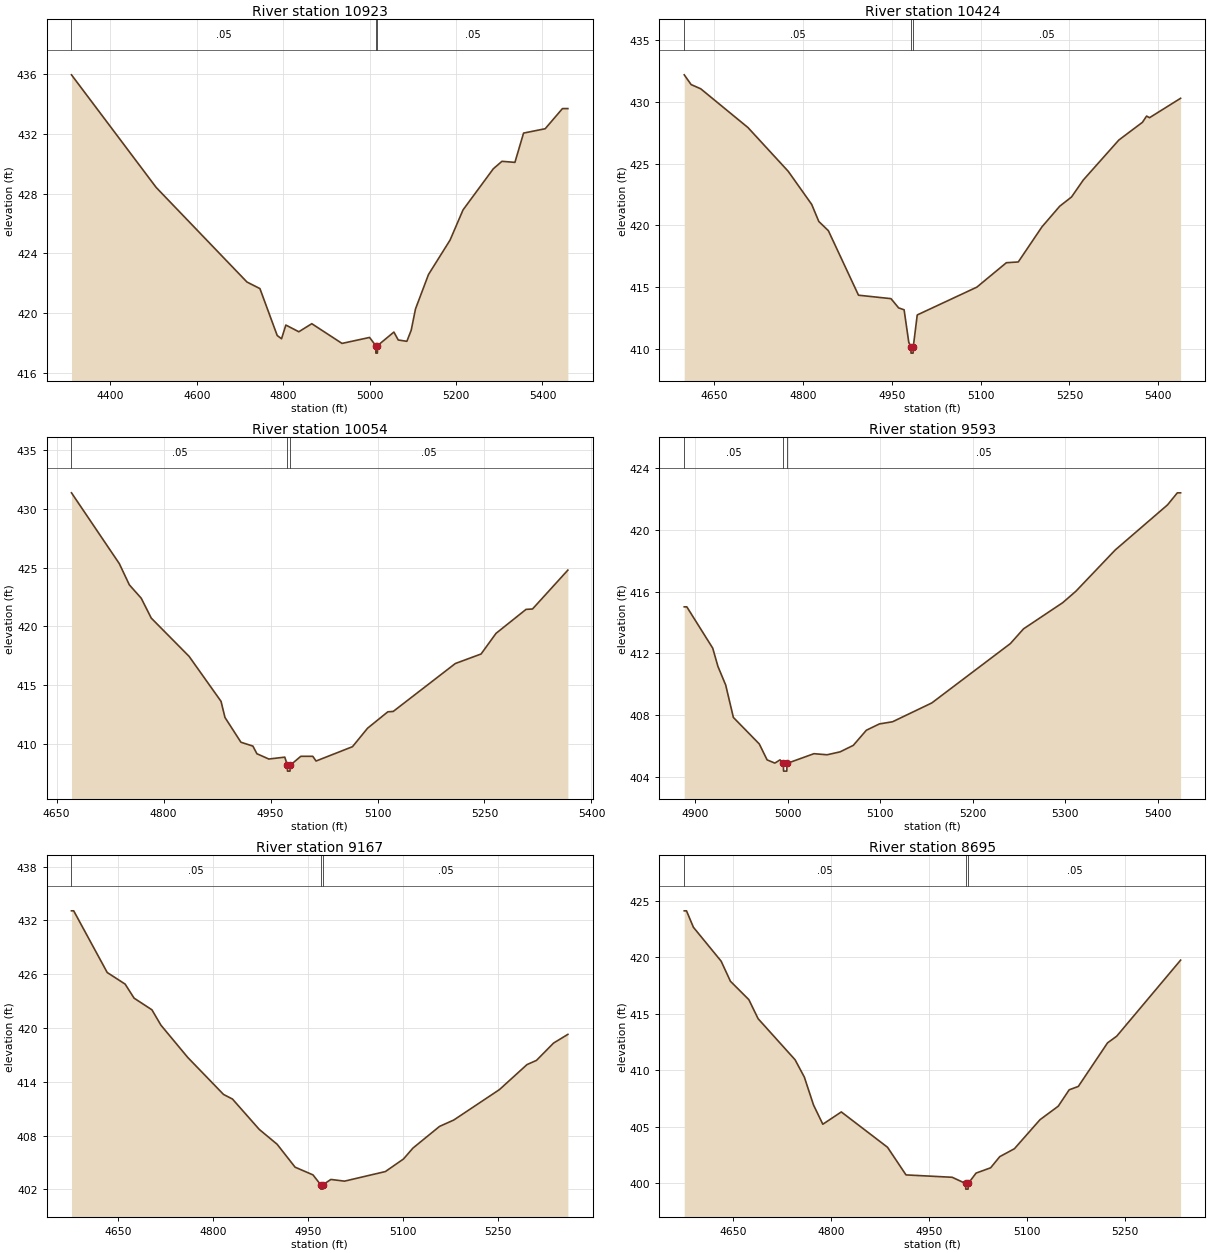
Type RM Length L Ch R = 1,10923,499,499,499
BEGIN DESCRIPTION:
CCT8_3 12.0
END DESCRIPTION:
XS GIS Cut Line= 3
      2723701.16      6885694.98      2723699.13      6886384.68
      2723698.56      6886843.48
#Sta/Elev= 30
  4310.3  435.95  4506.3  428.41  4716.3  422.08  4746.3  421.64  4786.3  418.50
  4796.3  418.28  4806.3  419.20  4836.3  418.75  4866.3  419.29  4936.3  417.97
  5000.0  418.37  5014.3  417.82  5014.6  417.32  5018.1  417.32  5018.3  417.82
  5056.3  418.73  5066.3  418.20  5086.3  418.11  5096.3  418.85  5106.3  420.28
  5136.3  422.58  5186.3  424.89  5216.3  426.91  5286.3  429.66  5306.3  430.16
  5336.3  430.09  5356.3  432.05  5406.3  432.34  5446.3  433.69  5458.8  433.69
#Mann=3,-1,0
  4310.3    0.05       0  5014.3    0.05       0  5018.3    0.05       0
Bank Sta=5014.3,5018.3
Exp/Cntr=0.3,0.1

Type RM Length L Ch R = 1,10424,370,370,370
BEGIN DESCRIPTION:
CCT8_3 11.0
END DESCRIPTION:
XS GIS Cut Line= 3
      2723516.26      6885715.87      2723342.74      6886077.49
      2723352.20      6886515.39
#Sta/Elev= 30
  4598.9  432.19  4610.6  431.40  4626.8  431.06  4706.7  427.92  4774.7  424.38
  4814.4  421.70  4826.4  420.32  4842.6  419.57  4893.5  414.35  4948.4  414.07
  4961.4  413.32  4970.6  413.17  4978.5  410.54  4982.1  410.16  4982.3  409.66
  4985.8  409.66  4986.1  410.16  4992.8  412.75  5093.5  415.00  5143.5  416.98
  5163.6  417.04  5203.6  419.88  5233.6  421.55  5253.6  422.30  5273.6  423.68
  5333.6  426.91  5373.6  428.35  5380.5  428.85  5385.5  428.72  5438.0  430.29
#Mann=3,-1,0
  4598.9    0.05       0  4982.1    0.04       0  4986.1    0.05       0
Bank Sta=4982.1,4986.1
Exp/Cntr=0.3,0.1

Type RM Length L Ch R = 1,10054,461,461,461
BEGIN DESCRIPTION:
CCT8_3 10.0
END DESCRIPTION:
XS GIS Cut Line= 3
      2722725.98      6885960.99      2723026.00      6886111.00
      2723226.01      6886411.01
#Sta/Elev= 30
  4670.9  431.36  4738.0  425.33  4752.0  423.53  4768.7  422.39  4782.7  420.70
  4835.8  417.44  4880.6  413.61  4886.1  412.24  4908.5  410.13  4925.3  409.80
  4930.9  409.15  4947.6  408.70  4970.0  408.86  4973.6  408.17  4973.8  407.67
  4977.3  407.67  4977.6  408.17  4992.4  408.93  5009.3  408.93  5013.8  408.53
  5064.9  409.75  5086.0  411.32  5114.5  412.72  5122.0  412.75  5209.1  416.83
  5245.2  417.64  5266.2  419.40  5308.3  421.44  5317.3  421.47  5366.9  424.78
#Mann=3,-1,0
  4670.9    0.05       0  4973.6    0.04       0  4977.6    0.05       0
Bank Sta=4973.6,4977.6
Exp/Cntr=0.3,0.1

Type RM Length L Ch R = 1,9593,426,426,426
BEGIN DESCRIPTION:
CCT8_3 9.0
END DESCRIPTION:
XS GIS Cut Line= 3
      2722625.98      6886260.97      2722676.00      6886361.00
      2722976.00      6886661.00
#Sta/Elev= 30
  4888.4  415.02  4891.2  415.02  4919.2  412.34  4924.8  411.16  4933.2  409.95
  4941.5  407.85  4969.5  406.13  4977.9  405.10  4986.3  404.89  4991.9  405.10
  4995.4  404.87  4995.7  404.37  4999.2  404.37  4999.4  404.87  5028.5  405.50
  5042.7  405.43  5056.8  405.62  5071.0  406.04  5085.1  407.02  5099.2  407.43
  5113.4  407.57  5155.8  408.79  5240.7  412.64  5254.8  413.59  5297.2  415.29
  5311.4  416.03  5353.8  418.70  5410.4  421.63  5421.0  422.41  5424.5  422.41
#Mann=3,-1,0
  4888.4    0.05       0  4995.4    0.04       0  4999.4    0.05       0
Bank Sta=4995.4,4999.4
Exp/Cntr=0.3,0.1

Type RM Length L Ch R = 1,9167,472,472,472
BEGIN DESCRIPTION:
CCT8_3 8.0
END DESCRIPTION:
XS GIS Cut Line= 3
      2722126.03      6886361.03      2722426.00      6886661.00
      2722626.01      6886961.02
#Sta/Elev= 30
  4575.8  433.06  4579.3  433.06  4632.3  426.18  4660.6  424.89  4674.8  423.32
  4703.0  422.02  4717.2  420.31  4759.6  416.71  4816.2  412.58  4830.3  412.07
  4872.7  408.68  4901.0  407.02  4929.3  404.47  4957.6  403.61  4969.7  402.52
  4970.0  402.02  4973.5  402.02  4973.7  402.52  4985.9  403.10  5007.5  402.91
  5072.1  403.98  5100.7  405.38  5115.7  406.60  5157.8  409.02  5180.3  409.73
  5252.4  413.12  5296.0  415.91  5311.0  416.38  5338.0  418.31  5360.6  419.28
#Mann=3,-1,0
  4575.8    0.05       0  4969.7    0.04       0  4973.7    0.05       0
Bank Sta=4969.7,4973.7
Exp/Cntr=0.3,0.1

Type RM Length L Ch R = 1,8695,418,418,418
BEGIN DESCRIPTION:
CCT8_3 7.0
END DESCRIPTION:
XS GIS Cut Line= 3
      2721876.03      6886711.03      2722176.00      6887011.00
      2722475.97      6887160.99
#Sta/Elev= 30
  4575.3  424.12  4578.8  424.12  4589.4  422.66  4631.8  419.66  4646.0  417.88
  4674.2  416.25  4688.4  414.56  4745.0  410.92  4759.1  409.39  4773.2  406.91
  4787.4  405.21  4815.7  406.30  4886.4  403.17  4914.7  400.72  4985.4  400.51
  5005.9  399.96  5006.2  399.46  5009.7  399.46  5009.9  399.96  5021.9  400.88
  5044.2  401.35  5058.2  402.34  5080.6  403.04  5119.7  405.61  5147.7  406.81
  5164.4  408.26  5178.4  408.56  5223.1  412.42  5237.1  413.01  5334.9  419.75
#Mann=3,-1,0
  4575.3    0.05       0  5005.9    0.04       0  5009.9    0.05       0
Bank Sta=5005.9,5009.9
Exp/Cntr=0.3,0.1

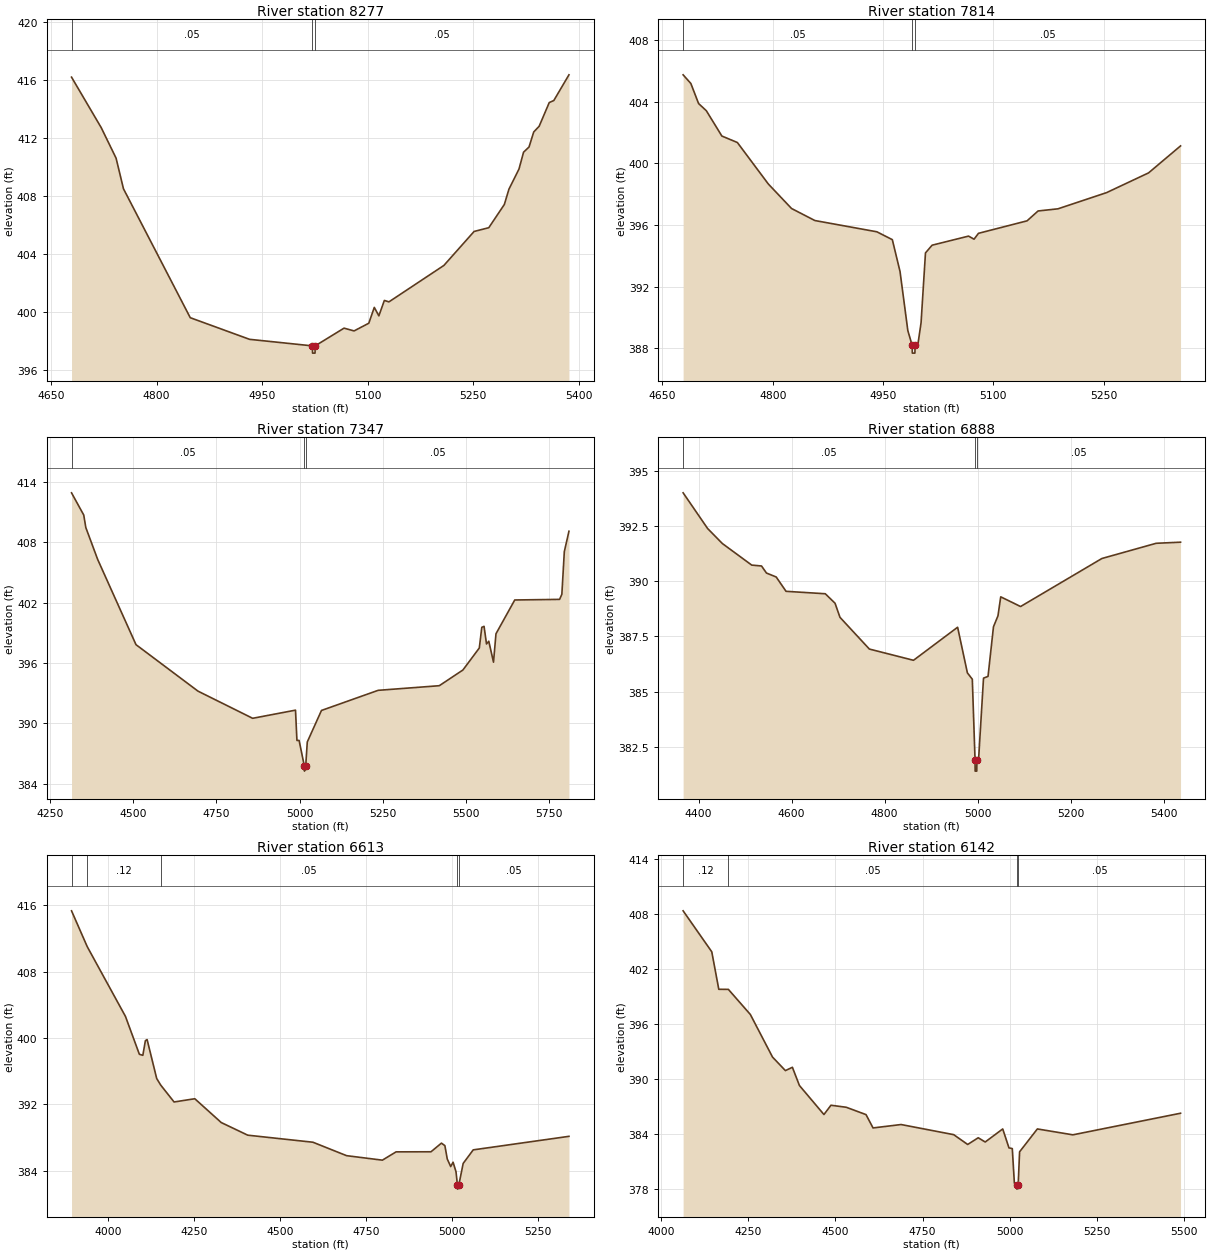
Type RM Length L Ch R = 1,8277,463,463,463
BEGIN DESCRIPTION:
CCT8_3 6.0
END DESCRIPTION:
XS GIS Cut Line= 3
      2721725.99      6886910.97      2721826.00      6887211.00
      2722076.02      6887511.02
#Sta/Elev= 30
  4679.1  416.17  4721.3  412.69  4742.4  410.59  4752.9  408.48  4847.8  399.60
  4932.1  398.11  5021.3  397.66  5021.6  397.16  5025.1  397.16  5025.3  397.66
  5066.3  398.88  5080.6  398.69  5101.5  399.22  5109.3  400.31  5115.8  399.73
  5123.6  400.79  5130.1  400.69  5208.2  403.20  5251.1  405.54  5272.0  405.80
  5294.1  407.40  5300.6  408.45  5314.9  409.84  5321.4  411.00  5329.2  411.36
  5335.8  412.39  5343.6  412.79  5357.9  414.42  5364.4  414.56  5385.9  416.33
#Mann=3,-1,0
  4679.1    0.05       0  5021.3    0.04       0  5025.3    0.05       0
Bank Sta=5021.3,5025.3
Exp/Cntr=0.3,0.1

Type RM Length L Ch R = 1,7814,467,467,467
BEGIN DESCRIPTION:
CCT8_3 5.0
END DESCRIPTION:
XS GIS Cut Line= 3
      2721525.99      6887011.03      2721426.00      6887311.00
      2721725.96      6887510.97
#Sta/Elev= 30
  4678.1  405.73  4688.6  405.17  4699.1  403.87  4709.7  403.40  4730.8  401.76
  4751.9  401.34  4794.0  398.65  4825.6  397.06  4857.3  396.28  4941.6  395.55
  4962.7  395.04  4973.2  392.97  4983.8  389.14  4989.7  388.18  4989.9  387.68
  4993.4  387.68  4993.7  388.18  4997.3  388.18  5001.8  389.65  5007.8  394.18
  5016.8  394.68  5066.4  395.27  5073.9  395.07  5079.9  395.45  5146.0  396.26
  5161.0  396.90  5188.1  397.04  5254.2  398.09  5311.3  399.37  5354.8  401.12
#Mann=3,-1,0
  4678.1    0.05       0  4989.7    0.04       0  4993.7    0.05       0
Bank Sta=4989.7,4993.7
Exp/Cntr=0.3,0.1

Type RM Length L Ch R = 1,7347,459,459,459
BEGIN DESCRIPTION:
CCT8_3 4.0
END DESCRIPTION:
XS GIS Cut Line= 3
      2721375.99      6886811.01      2720976.00      6887361.00
      2721576.00      6887911.00
#Sta/Elev= 30
  4315.3  412.91  4352.0  410.70  4358.2  409.46  4393.7  406.30  4508.9  397.82
  4695.1  393.20  4859.3  390.50  4988.0  391.31  4992.3  388.30  4998.8  388.30
  5014.6  385.75  5014.9  385.25  5018.6  385.75  5023.4  388.15  5066.0  391.28
  5236.2  393.28  5419.9  393.74  5490.8  395.30  5540.1  397.49  5547.5  399.54
  5554.3  399.64  5561.7  397.89  5568.5  398.16  5582.7  396.08  5590.1  398.90
  5646.5  402.26  5781.2  402.32  5788.0  402.83  5795.4  407.07  5809.3  409.09
#Mann=3,-1,0
  4315.3    0.05       0  5014.6    0.04       0  5018.6    0.05       0
Bank Sta=5014.6,5018.6
Exp/Cntr=0.3,0.1

Type RM Length L Ch R = 1,6888,275,275,275
BEGIN DESCRIPTION:
CCT8_3 3.0
END DESCRIPTION:
XS GIS Cut Line= 3
      2720775.99      6886861.03      2720576.00      6887461.00
      2720950.96      6887685.98
#Sta/Elev= 30
  4366.9  394.02  4419.6  392.40  4451.2  391.72  4514.4  390.74  4535.5  390.70
  4546.1  390.38  4567.1  390.20  4588.2  389.55  4672.6  389.44  4693.6  389.01
  4704.2  388.37  4767.4  386.93  4862.3  386.42  4957.2  387.92  4978.2  385.85
  4988.8  385.56  4994.7  381.89  4994.9  381.39  4998.4  381.39  4998.7  381.89
  5002.2  381.89  5012.9  385.61  5022.6  385.69  5034.3  387.94  5044.0  388.44
  5049.9  389.30  5092.6  388.86  5267.5  391.04  5384.2  391.73  5436.6  391.78
#Mann=3,-1,0
  4366.9    0.05       0  4994.7    0.04       0  4998.7    0.05       0
Bank Sta=4994.7,4998.7
Exp/Cntr=0.3,0.1

Type RM Length L Ch R = 1,6613,471,471,471
BEGIN DESCRIPTION:
Mapping XS eb11b844
END DESCRIPTION:
XS GIS Cut Line= 3
      2720450.69      6886365.70      2720299.65      6887459.44
      2720500.99      6887735.98
#Sta/Elev= 30
  3894.0  415.32  3939.7  411.00  4050.8  402.60  4091.2  398.04  4101.3  397.91
  4108.7  399.67  4113.7  399.81  4141.6  395.12  4153.0  394.34  4192.1  392.29
  4252.4  392.68  4329.3  389.81  4406.3  388.29  4595.9  387.44  4693.8  385.82
  4797.8  385.28  4837.6  386.28  4939.1  386.29  4969.4  387.33  4979.5  387.03
  4986.4  385.42  4996.4  384.51  5003.3  385.03  5011.8  383.89  5016.0  382.29
  5016.3  381.79  5020.0  382.29  5032.7  384.89  5061.9  386.52  5340.2  388.15
#Mann=5,-1,0
  3894.0    0.05       0  3939.7    0.12       0  4153.0    0.05       0
  5016.0    0.04       0  5020.0    0.05       0
Bank Sta=5016,5020
Exp/Cntr=0.3,0.1

Type RM Length L Ch R = 1,6142,822,822,822
BEGIN DESCRIPTION:
Mapping XS e7bc7a54
END DESCRIPTION:
XS GIS Cut Line= 3
      2719935.06      6886579.26      2719846.52      6887511.52
      2720251.02      6887786.02
#Sta/Elev= 30
  4064.1  408.32  4146.2  403.86  4166.3  399.78  4193.8  399.77  4256.7  397.04
  4320.3  392.40  4357.2  390.93  4377.2  391.29  4397.3  389.31  4467.6  386.15
  4487.7  387.16  4531.5  386.94  4588.2  386.14  4608.3  384.69  4688.6  385.06
  4839.3  383.96  4879.5  382.89  4909.6  383.62  4929.7  383.16  4979.9  384.58
  4997.8  382.52  5007.3  382.44  5013.3  378.67  5020.2  378.53  5020.4  378.03
  5024.2  378.53  5028.2  382.09  5079.1  384.58  5180.9  383.94  5489.4  386.29
#Mann=4,-1,0
  4064.1    0.12       0  4193.8    0.05       0  5020.2    0.04       0
  5024.2    0.05       0
Bank Sta=5020.2,5024.2
Exp/Cntr=0.3,0.1

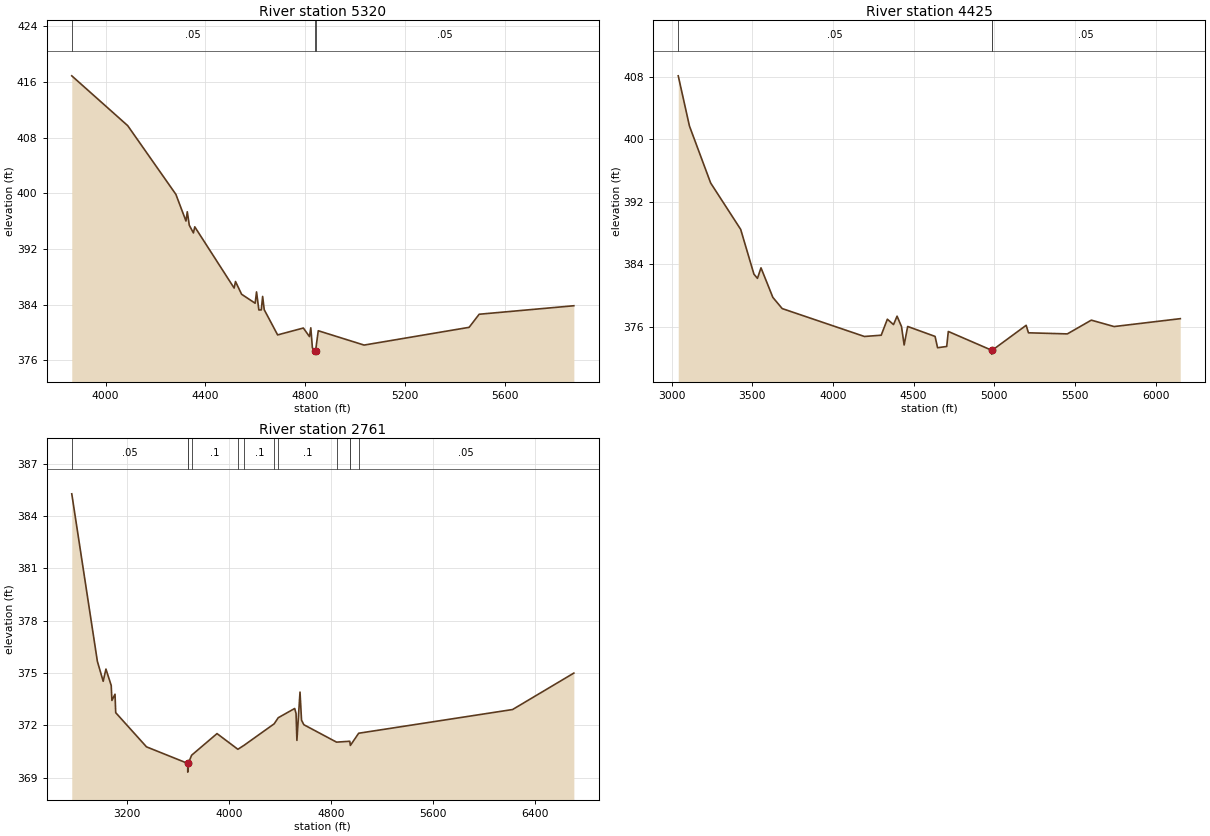
Type RM Length L Ch R = 1,5320,895,895,895
BEGIN DESCRIPTION:
Mapping XS 537e5f2f
END DESCRIPTION:
XS GIS Cut Line= 4
      2719507.96      6886771.97      2719133.20      6887735.49
      2719170.87      6887932.96      2719942.53      6888029.94
#Sta/Elev= 30
  3864.2  416.89  4088.5  409.73  4281.6  399.86  4322.0  396.03  4327.3  397.36
  4335.3  395.42  4351.9  394.32  4357.2  395.20  4515.1  386.40  4520.5  387.34
  4545.0  385.51  4599.4  384.22  4604.8  385.85  4614.2  383.26  4623.9  383.26
  4629.3  385.20  4635.7  383.29  4689.4  379.67  4792.5  380.66  4817.0  379.43
  4822.4  380.69  4828.8  377.82  4837.6  377.41  4837.8  376.91  4841.6  377.41
  4852.3  380.27  5036.0  378.21  5457.0  380.76  5497.3  382.64  5876.8  383.86
#Mann=3,-1,0
  3864.2    0.05       0  4837.6    0.04       0  4841.6    0.05       0
Bank Sta=4837.6,4841.6
Exp/Cntr=0.3,0.1

Type RM Length L Ch R = 1,4425,1664,1664,1664
BEGIN DESCRIPTION:
Mapping XS da377161
END DESCRIPTION:
XS GIS Cut Line= 3
      2719163.28      6886343.92      2718298.70      6887958.50
      2719239.96      6888826.96
#Sta/Elev= 30
  3041.2  408.12  3110.6  401.70  3242.2  394.40  3428.3  388.46  3510.4  382.73
  3532.3  382.19  3554.2  383.54  3627.8  379.75  3685.8  378.32  4195.3  374.75
  4299.3  374.91  4337.5  376.96  4375.7  376.27  4397.6  377.35  4425.2  376.02
  4441.5  373.66  4463.4  376.03  4633.2  374.76  4648.7  373.31  4705.4  373.47
  4715.3  375.39  4983.8  372.99  4984.1  372.49  4987.8  372.99  5197.9  376.18
  5212.1  375.22  5453.1  375.08  5601.7  376.84  5742.9  376.02  6153.4  377.03
#Mann=3,-1,0
  3041.2    0.05       0  4983.8    0.04       0  4987.8    0.05       0
Bank Sta=4983.8,4987.8
Exp/Cntr=0.3,0.1

Type RM Length L Ch R = 1,2761,0,0,0
BEGIN DESCRIPTION:
CCT8_3 1.0
END DESCRIPTION:
XS GIS Cut Line= 3
      2717905.25      6885881.25      2717091.36      6887962.15
      2718620.93      6888719.96
#Sta/Elev= 30
  2765.6  385.28  2966.7  375.67  3012.3  374.53  3033.8  375.23  3075.3  374.29
  3080.7  373.43  3105.1  373.79  3110.5  372.73  3352.2  370.77  3675.9  369.82
  3676.2  369.32  3679.9  369.82  3706.6  370.29  3905.9  371.53  4069.7  370.63
  4120.4  370.87  4354.5  372.09  4386.5  372.44  4515.6  372.97  4526.3  372.68
  4533.0  371.14  4557.4  373.91  4569.3  372.30  4587.3  372.04  4844.1  371.04
  4948.2  371.09  4952.5  370.85  5017.9  371.55  6226.1  372.91  6707.0  375.00
#Mann=12,-1,0
  2765.6    0.05       0  3675.9    0.07       0  3679.9    0.05       0
  3706.6     0.1       0  4069.7    0.12       0  4120.4     0.1       0
  4354.5    0.12       0  4386.5     0.1       0  4844.1    0.12       0
  4948.2    0.05       0  4952.5    0.12       0  5017.9    0.05       0
Bank Sta=3675.9,3679.9
Exp/Cntr=0.3,0.1

Chan Stop Cuts=-1