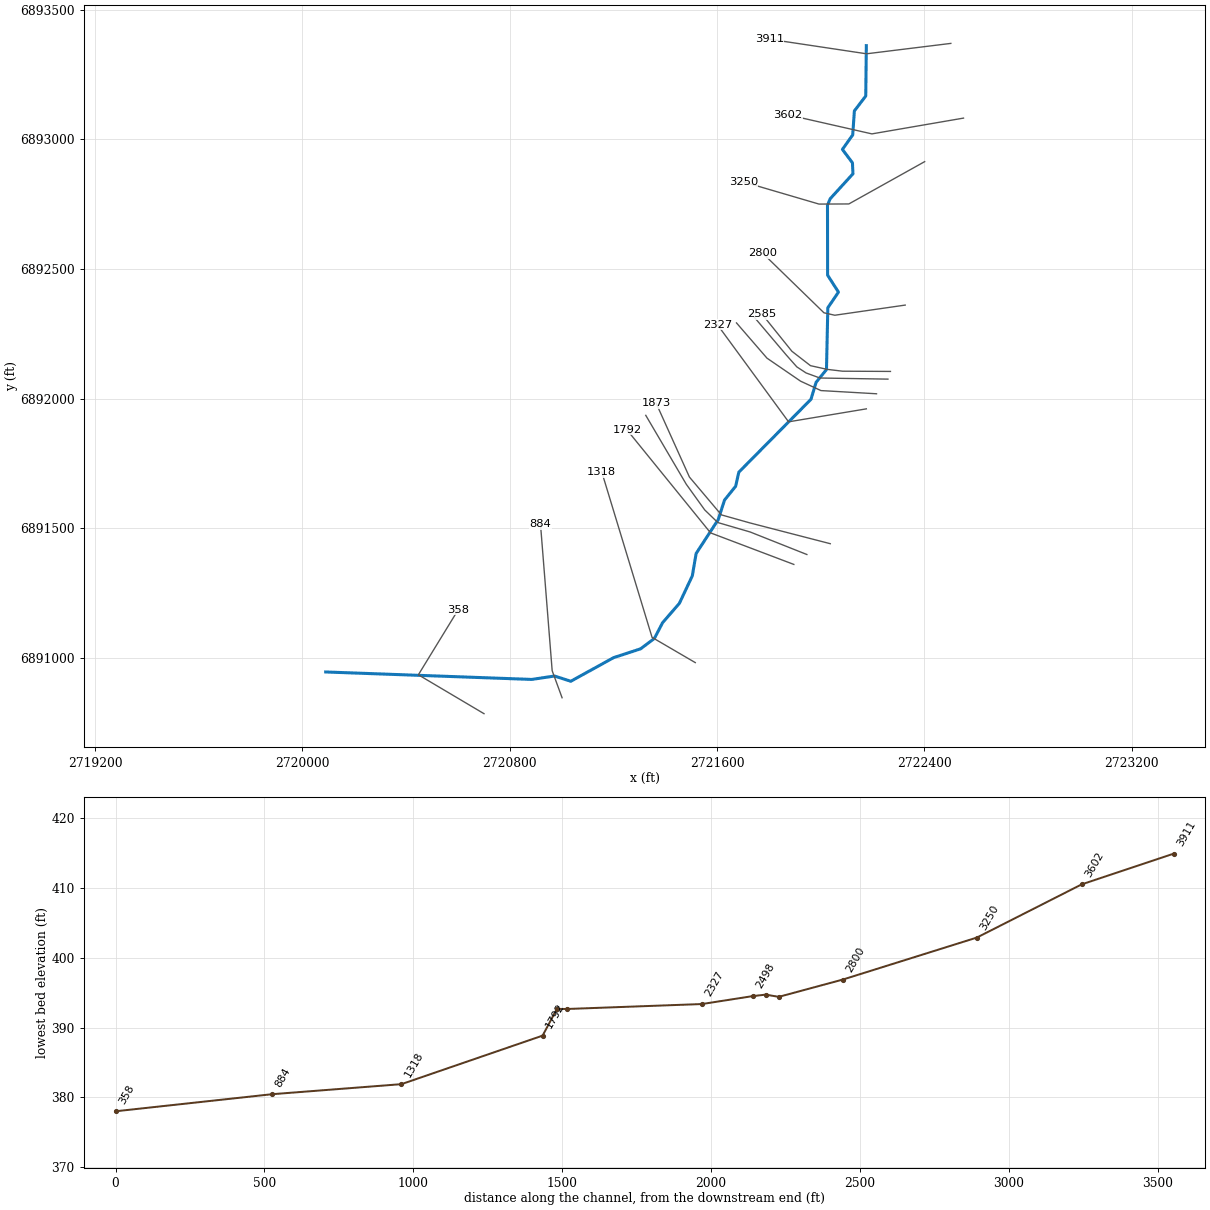
--- CCT8_4.prj (project) ---

Proj Title=CCT8_4 Base Level Engineering
Current Plan=p01
Default Exp/Contr=0.3,0.1
English Units
Geom File=g01
Flow File=f01
Plan File=p01
Y Axis Title=Elevation
X Axis Title(PF)=Main Channel Distance
X Axis Title(XS)=Station
BEGIN DESCRIPTION:
CCT8_4
END DESCRIPTION:
DSS Export Rating Curves= 0
DSS Export Rating Curve Sorted= 0
DSS Export Volume Flow Curves= 0
DXF OffsetX= 0
DXF OffsetY= 0
DXF ScaleX= 1
DXF ScaleY= 10

--- CCT8_4.p01 (plan) ---

Plan Title=Multiple Run
Short Identifier=Multiple
Geom File=g01
Flow File=f01
Subcritical Flow
K Sum by GR= 0
Std Step Tol= 0.01
Critical Tol= 0.01
Num of Std Step Trials= 20
Max Error Tol= 0.3
Flow Tol Ratio= 0.001
Split Flow NTrial= 30
Split Flow Tol= 0.02
Split Flow Ratio= 0.02
Log Output Level= 0
Friction Slope Method= 1
Unsteady Friction Slope Method= 2
Unsteady Bridges Friction Slope Method= 1
Parabolic Critical Depth
Global Vel Dist=  1 , 1 , 1
Global Log Level= 0
CheckData=True
Encroach Param= -1, 0, 0, 0
BEGIN DESCRIPTION:
Multiple Run
END DESCRIPTION:

--- CCT8_4.f01 (steady flow) ---

Flow Title=Multiple
Number of Profiles=7
Profile Names=10-year,25-year,50-year,1pct_min,100-year,1pct_plu,500-year
River Rch & RM= CCT8_4,Reach-1,3911
      44      48      51      27      54     107      59
River Rch & RM= CCT8_4,Reach-1,2800
     225     283     327     189     377     751     496
Boundary for River Rch & Prof#=CCT8_4,Reach-1,1
Up Type=0
Dn Type=3
Dn Slope=0.005
Boundary for River Rch & Prof#=CCT8_4,Reach-1,2
Up Type=0
Dn Type=3
Dn Slope=0.005
Boundary for River Rch & Prof#=CCT8_4,Reach-1,3
Up Type=0
Dn Type=3
Dn Slope=0.005
Boundary for River Rch & Prof#=CCT8_4,Reach-1,4
Up Type=0
Dn Type=3
Dn Slope=0.005
Boundary for River Rch & Prof#=CCT8_4,Reach-1,5
Up Type=0
Dn Type=3
Dn Slope=0.005
Boundary for River Rch & Prof#=CCT8_4,Reach-1,6
Up Type=0
Dn Type=3
Dn Slope=0.005
Boundary for River Rch & Prof#=CCT8_4,Reach-1,7
Up Type=0
Dn Type=3
Dn Slope=0.005

--- CCT8_4.g01 (geometry) ---

Geom Title=Existing Conditions
Program Version=4.10

River Reach=CCT8_4          ,Reach-1
Reach XY= 30
        2722176.        6893361.      2722173.75      6893166.93
      2722129.85       6893109.4      2722123.45      6893016.89
      2722083.59      6892960.99      2722122.43      6892909.35
      2722124.34      6892867.05      2722036.46      6892770.81
      2722026.12      6892745.95      2722026.65      6892476.16
      2722068.44        6892411.      2722027.38      6892350.56
      2722022.25      6892112.55      2721982.14      6892063.17
      2721962.38      6891997.78      2721684.15      6891717.06
      2721671.85      6891662.74      2721628.94      6891609.48
      2721604.49      6891533.92       2721519.3      6891403.44
      2721504.67      6891317.43      2721454.75      6891211.37
      2721389.88      6891136.68      2721358.22      6891075.84
      2721305.38      6891036.17      2721200.91      6891001.97
      2721035.75      6890910.98      2720973.07      6890931.19
      2720885.26      6890918.05      2720090.19      6890946.81

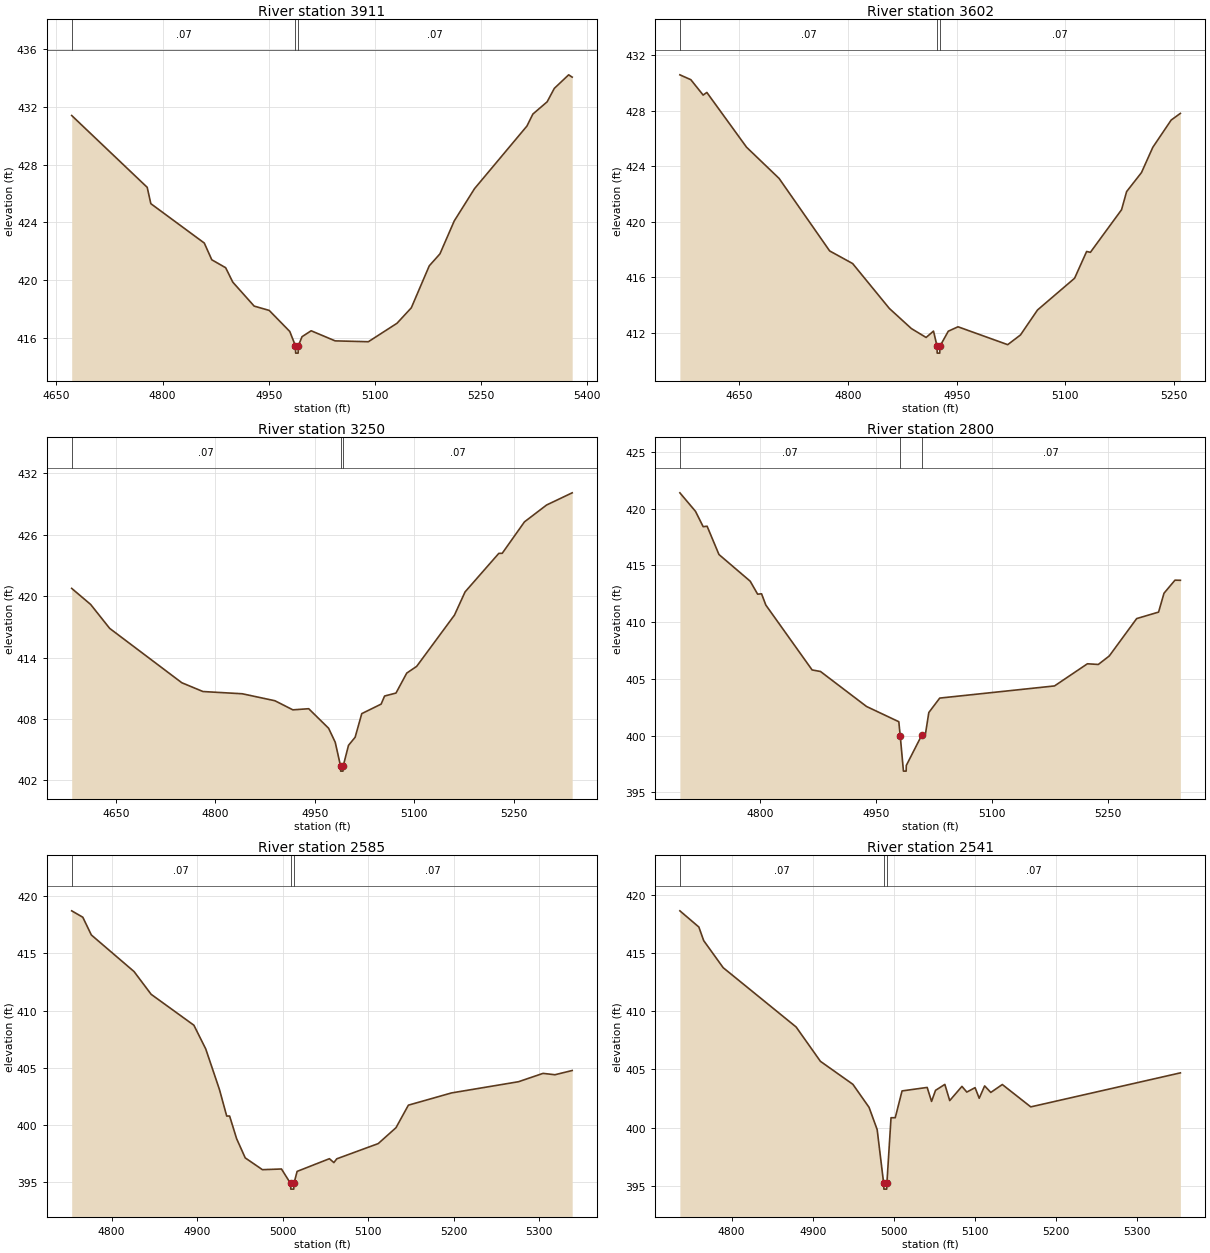
Type RM Length L Ch R = 1 ,3911    ,309,309,309
BEGIN DESCRIPTION:
CCT8_4 6.0
END DESCRIPTION:
XS GIS Cut Line= 3
      2722502.06      6893369.67      2722176.68      6893329.61
      2721801.03        6893386.
#Sta/Elev= 30
  4671.5  431.41  4778.3  426.43  4783.4   425.3    4859  422.57  4869.6  421.41
  4889.2  420.86  4899.3  419.86  4929.5   418.2  4950.8   417.9  4979.9  416.44
  4987.9  415.44  4988.2  414.94  4991.7  414.94  4991.9  415.44  4997.2  416.08
  5010.1  416.49    5044  415.79    5091  415.73  5131.5  417.01  5151.7  418.08
  5177.1  420.99  5192.2  421.82  5212.4   424.1  5241.1  426.34  5315.2  430.68
  5323.6  431.51  5343.8  432.36  5353.9  433.29  5374.2  434.23  5379.2  434.07
#Mann= 3 ,-1 , 0
  4671.5     .07       0  4987.9     .04       0  4991.9     .07       0
Bank Sta=4987.9,4991.9
XS Rating Curve= 0 ,0
Exp/Cntr=0.3,0.1

Type RM Length L Ch R = 1 ,3602    ,352,352,352
BEGIN DESCRIPTION:
Mapping XS a0adb9c3
END DESCRIPTION:
XS GIS Cut Line= 3
      2722550.91      6893081.74      2722197.43      6893020.87
      2721873.65      6893094.37
#Sta/Elev= 30
    4568   430.6  4583.1  430.25  4600.1  429.14  4605.2  429.33    4660  425.38
  4704.9  423.13  4774.7   417.9  4806.4  416.99  4857.1  413.75  4887.5   412.3
  4907.8  411.66    4918  412.12  4922.9  411.03  4923.1  410.53  4926.6  410.53
  4926.9  411.03  4938.4  412.11  4951.8  412.43  5020.4  411.14    5038  411.84
  5061.5  413.64  5112.7  415.93  5129.3  417.86  5134.5   417.8  5177.5  420.87
  5184.5  422.18    5205  423.55  5220.6  425.37    5246  427.34  5258.7  427.82
#Mann= 3 ,-1 , 0
    4568     .07       0  4922.9     .04       0  4926.9     .07       0
Bank Sta=4922.9,4926.9
XS Rating Curve= 0 ,0
Exp/Cntr=0.3,0.1

Type RM Length L Ch R = 1 ,3250    ,450,450,450
BEGIN DESCRIPTION:
CCT8_4 5.0
END DESCRIPTION:
XS GIS Cut Line= 4
      2722401.02      6892913.89      2722108.52      6892750.84
      2721993.39      6892750.32      2721700.99        6892836.
#Sta/Elev= 30
  4583.4  420.76    4612  419.19  4640.7  416.85  4749.4  411.54  4781.3  410.68
  4840.7  410.46  4889.8  409.78  4916.9  408.89  4940.8     409  4970.8  407.09
  4980.8  405.72  4988.8   403.4    4989   402.9  4992.5   402.9  4992.8   403.4
  5000.8  405.42  5010.8  406.21  5020.8  408.52    5050  409.45  5055.2  410.24
  5072.4  410.53  5088.6  412.48  5103.6  413.14  5160.6  418.15  5176.6  420.42
  5227.4  424.18  5232.6  424.19  5266.1  427.26  5299.5  428.91  5338.1   430.1
#Mann= 3 ,-1 , 0
  4583.4     .07       0  4988.8     .04       0  4992.8     .07       0
Bank Sta=4988.8,4992.8
XS Rating Curve= 0 ,0
Exp/Cntr=0.3,0.1

Type RM Length L Ch R = 1 ,2800    ,215,215,215
BEGIN DESCRIPTION:
CCT8_4 4.0
END DESCRIPTION:
XS GIS Cut Line= 4
      2722325.96      6892360.99      2722054.38      6892321.85
       2722012.5      6892331.26      2721776.02      6892560.98
#Sta/Elev= 30
  4696.2  421.38  4716.4  419.75  4726.3   418.4  4731.4  418.44  4746.7  415.95
  4787.1   413.6  4796.7  412.46  4801.8  412.49  4807.3   411.5  4867.1  405.79
    4878  405.65  4937.5  402.57  4979.2  401.23 4981.01 400.008  4985.2  396.88
  4988.7  396.88  4988.9  397.38  5009.2  400.09  5013.5  400.09    5018  402.04
  5032.1  403.31  5180.5  404.38    5223  406.33  5237.1  406.27  5251.3  407.02
  5286.7  410.31    5315  410.88    5322  412.54  5336.2  413.69  5343.2  413.68
#Mann= 3 ,-1 , 0
  4696.2     .07       0 4981.01     .03       0  5009.2     .07       0
Bank Sta=4981.01,5009.2
XS Rating Curve= 0 ,0
Exp/Cntr=0.3,0.1

Type RM Length L Ch R = 1 ,2585    ,44,44,44
BEGIN DESCRIPTION:
Mapping XS 40625ceb
END DESCRIPTION:
XS GIS Cut Line= 6
      2722268.97      6892105.25      2722084.18      6892106.14
      2722023.87      6892113.39      2721960.48       6892127.5
      2721888.78      6892182.98      2721773.06      6892326.76
#Sta/Elev= 30
  4753.2  418.73  4766.2  418.17  4776.2  416.62  4826.2  413.42  4846.2  411.43
  4896.2  408.73  4910.1  406.65  4926.2  403.09  4934.6  400.79    4938  400.79
  4946.2  398.81  4956.3  397.13  4976.4   396.1  4998.7  396.16  5009.3   394.9
  5009.6   394.4  5013.1   394.4  5013.3   394.9    5017  395.95  5054.8  397.06
    5060  396.72  5063.4  397.05  5111.9  398.38  5132.7  399.77  5147.2  401.74
  5197.7  402.81  5276.1  403.79  5304.8  404.52  5318.7   404.4  5338.9  404.77
#Mann= 3 ,-1 , 0
  4753.2     .07       0  5009.3     .04       0  5013.3     .07       0
Bank Sta=5009.3,5013.3
XS Rating Curve= 0 ,0
Exp/Cntr=0.3,0.1

Type RM Length L Ch R = 1 ,2541    ,43,43,43
BEGIN DESCRIPTION:
Mapping XS 07cdf0eb
END DESCRIPTION:
XS GIS Cut Line= 6
      2722259.39      6892075.59      2721996.79      6892079.86
      2721943.53       6892099.4      2721907.78      6892122.81
      2721867.12      6892168.62      2721741.58      6892316.71
#Sta/Elev= 30
  4736.2  418.61  4759.6  417.22  4765.6  416.05  4789.6  413.73  4879.6  408.64
  4909.6  405.69  4949.6  403.72  4969.6  401.74  4979.6  399.83  4987.6  395.22
  4987.9  394.72  4991.4  394.72  4991.6  395.22  4996.7  400.85  5001.9  400.85
  5010.3  403.15  5041.3  403.45  5046.7  402.25  5051.6   403.2  5063.1  403.71
  5069.1  402.32  5084.2  403.54  5090.2  403.05  5100.4  403.43  5105.5  402.52
  5112.2  403.58  5119.8  403.02    5134   403.7  5169.1  401.78  5353.7   404.7
#Mann= 3 ,-1 , 0
  4736.2     .07       0  4987.6     .04       0  4991.6     .07       0
Bank Sta=4987.6,4991.6
XS Rating Curve= 0 ,0
Exp/Cntr=0.3,0.1

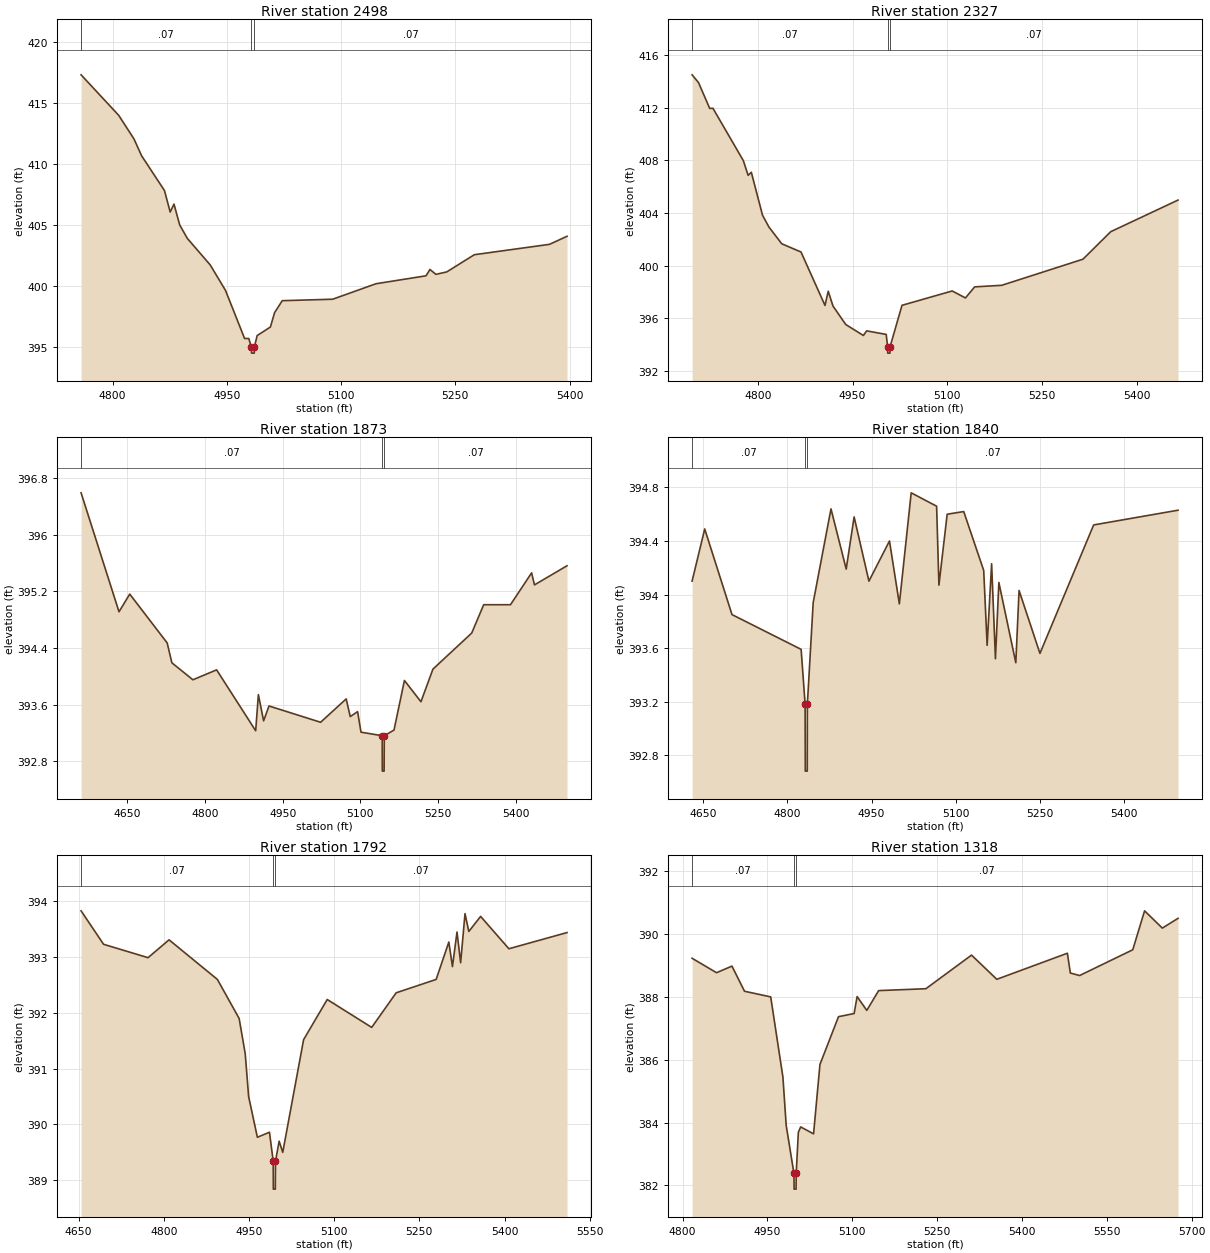
Type RM Length L Ch R = 1 ,2498    ,171,171,171
BEGIN DESCRIPTION:
Mapping XS c1e6d727
END DESCRIPTION:
XS GIS Cut Line= 5
       2722215.3      6892019.14      2722000.85      6892031.46
      2721922.27      6892067.73       2721792.6       6892156.5
      2721675.04      6892292.29
#Sta/Elev= 30
  4758.6  417.33    4808  414.01    4828  412.08    4838   410.7  4868.1  407.84
  4875.6  406.08  4880.6  406.73  4888.1  405.02  4898.1  403.92  4928.2  401.74
  4948.2  399.66  4973.3  395.71  4978.8  395.71  4982.2  395.01  4982.5  394.51
    4986  394.51  4986.2  395.01  4989.8  395.95  5007.2  396.65  5012.7  397.83
  5022.8  398.81    5089  398.93  5145.9   400.2  5211.6  400.85  5216.7  401.37
  5224.6  400.97  5238.8  401.17    5275  402.58  5373.7  403.43  5396.7  404.09
#Mann= 3 ,-1 , 0
  4758.6     .07       0  4982.2     .04       0  4986.2     .07       0
Bank Sta=4982.2,4986.2
XS Rating Curve= 0 ,0
Exp/Cntr=0.3,0.1

Type RM Length L Ch R = 1 ,2327    ,454,454,454
BEGIN DESCRIPTION:
CCT8_4 3.0
END DESCRIPTION:
XS GIS Cut Line= 3
      2722176.02        6891961.        2721876.        6891911.
      2721600.99      6892286.01
#Sta/Elev= 30
  4695.9   414.5  4706.1  413.91  4723.8  411.95  4728.9  411.96    4777  407.99
  4784.6  406.87  4789.7   407.1  4807.4  403.84  4817.6  402.94  4837.9  401.67
  4868.3  401.05  4906.3  396.99  4911.4  398.07    4919  396.94  4939.2  395.54
  4967.1  394.71  4972.2  395.06  5003.2  394.79  5005.4  393.87  5005.6  393.37
  5009.1  393.37  5009.4  393.87  5028.2     397  5107.7  398.09  5128.6  397.56
  5143.2   398.4  5186.1  398.52  5314.6   400.5  5358.6  402.59  5465.1  404.99
#Mann= 3 ,-1 , 0
  4695.9     .07       0  5005.4     .04       0  5009.4     .07       0
Bank Sta=5005.4,5009.4
XS Rating Curve= 0 ,0
Exp/Cntr=0.3,0.1

Type RM Length L Ch R = 1 ,1873    ,33,33,33
BEGIN DESCRIPTION:
Mapping XS 83c95ca3
END DESCRIPTION:
XS GIS Cut Line= 5
      2722036.88      6891441.22      2721727.84      6891521.08
      2721616.72      6891552.33      2721493.46      6891698.17
        2721365.      6891982.86
#Sta/Elev= 30
    4561  396.59  4634.2  394.91  4654.9  395.16  4727.2  394.47  4736.2  394.19
  4776.8  393.95  4822.6  394.09    4898  393.23  4903.2  393.74  4913.3  393.37
  4923.7  393.58  5023.3  393.35  5072.7  393.68  5080.5  393.43  5094.7   393.5
  5101.3  393.21  5142.2  393.16  5142.4  392.66  5145.9  392.66  5146.2  393.16
    5165  393.24  5185.1  393.94    5217  393.64  5240.1   394.1    5315  394.61
  5338.1  395.01  5389.8  395.01  5430.6  395.46  5436.1  395.29  5498.9  395.56
#Mann= 3 ,-1 , 0
    4561     .07       0  5142.2     .04       0  5146.2     .07       0
Bank Sta=5142.2,5146.2
XS Rating Curve= 0 ,0
Exp/Cntr=0.3,0.1

Type RM Length L Ch R = 1 ,1840    ,48,48,48
BEGIN DESCRIPTION:
Mapping XS 78c78f08
END DESCRIPTION:
XS GIS Cut Line= 6
      2721946.56      6891399.56      2721727.84      6891486.36
      2721602.84      6891522.82      2721552.49      6891571.43
      2721481.31      6891670.39      2721325.05      6891936.02
#Sta/Elev= 30
  4630.3   394.1  4652.8  394.49  4701.4  393.85  4824.6  393.59  4831.7  393.18
    4832  392.68  4835.5  392.68  4835.7  393.18  4846.1  393.94  4877.8  394.64
  4904.9  394.19    4919  394.58  4945.4   394.1    4982   394.4  4999.6  393.93
  5020.7  394.76    5066  394.66  5070.1  394.07  5084.8   394.6  5114.3  394.62
  5149.9  394.18    5156  393.62    5164  394.23  5170.8  393.52  5176.9  394.09
  5207.1  393.49  5212.9  394.03  5250.1  393.56  5345.8  394.52  5496.1  394.63
#Mann= 3 ,-1 , 0
  4630.3     .07       0  4831.7     .04       0  4835.7     .07       0
Bank Sta=4831.7,4835.7
XS Rating Curve= 0 ,0
Exp/Cntr=0.3,0.1

Type RM Length L Ch R = 1 ,1792    ,474,474,474
BEGIN DESCRIPTION:
Mapping XS 5c0e7d16
END DESCRIPTION:
XS GIS Cut Line= 3
      2721896.27      6891361.35      2721575.06      6891482.89
      2721252.16      6891880.43
#Sta/Elev= 30
  4654.4  393.83    4694  393.23  4772.3  392.99  4809.3  393.31  4894.4   392.6
  4932.7   391.9  4943.4  391.27  4949.4   390.5  4964.8  389.77  4986.1  389.86
  4992.7  389.34  4992.9  388.84  4996.4  388.84  4996.7  389.34  5003.1   389.7
  5009.5   389.5  5046.2  391.52  5087.8  392.24  5166.1  391.74  5209.2  392.36
  5279.6   392.6  5301.9  393.27  5308.3  392.83  5316.3  393.45  5322.7   392.9
  5330.4  393.78  5337.1  393.46  5357.9  393.73  5407.7  393.15    5510  393.44
#Mann= 3 ,-1 , 0
  4654.4     .07       0  4992.7     .04       0  4996.7     .07       0
Bank Sta=4992.7,4996.7
XS Rating Curve= 0 ,0
Exp/Cntr=0.3,0.1

Type RM Length L Ch R = 1 ,1318    ,434,434,434
BEGIN DESCRIPTION:
Mapping XS c04304ef
END DESCRIPTION:
XS GIS Cut Line= 3
      2721516.03      6890982.89      2721349.36      6891080.11
      2721155.38      6891717.49
#Sta/Elev= 30
  4816.7  389.23  4859.9  388.77  4887.2  388.98  4909.4  388.18  4955.7     388
  4977.3  385.45  4983.1  383.91  4996.8  382.38  4997.1  381.88  5000.6  381.88
  5000.8  382.38  5004.6  383.69  5008.7  383.86  5031.5  383.64  5042.8  385.85
  5075.6  387.37  5103.2  387.47  5108.5  388.01  5125.6  387.57  5146.6   388.2
  5230.1  388.26  5310.8  389.33  5355.5  388.56  5480.3  389.39  5485.5  388.76
  5501.9  388.68  5595.9   389.5  5616.8  390.74  5648.2  390.19  5675.9   390.5
#Mann= 3 ,-1 , 0
  4816.7     .07       0  4996.8     .04       0  5000.8     .07       0
Bank Sta=4996.8,5000.8
XS Rating Curve= 0 ,0
Exp/Cntr=0.3,0.1

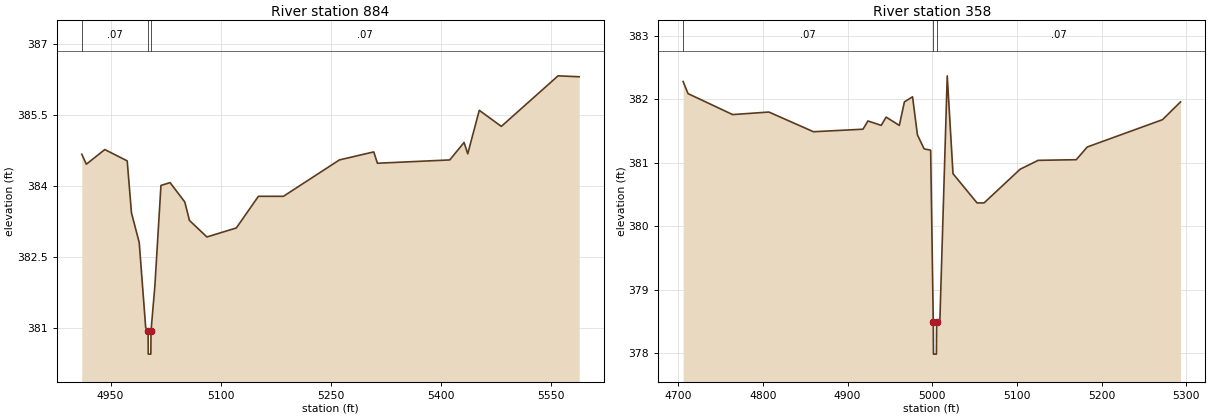
Type RM Length L Ch R = 1 ,884     ,526,526,526
BEGIN DESCRIPTION:
Mapping XS 0ef1152f
END DESCRIPTION:
XS GIS Cut Line= 3
      2721002.14      6890847.47      2720963.95      6890951.64
      2720918.87      6891516.79
#Sta/Elev= 30
  4910.8  384.67    4917  384.46  4942.2  384.77  4972.7  384.53  4978.5  383.43
  4989.1   382.8  4997.9     381  5001.2  380.94  5001.4  380.44  5004.9  380.44
  5005.2  380.94  5010.4  381.88  5018.7  384.01  5031.1  384.07  5051.2  383.66
  5057.5  383.27  5081.3  382.92  5121.4  383.11  5151.5  383.78  5185.6  383.78
  5261.9  384.55  5308.7  384.72  5313.7  384.48  5412.3  384.55  5431.8  384.92
  5436.8  384.68  5452.5   385.6  5482.6  385.26  5559.9  386.33  5588.7  386.31
#Mann= 3 ,-1 , 0
  4910.8     .07       0  5001.2     .04       0  5005.2     .07       0
Bank Sta=5001.2,5005.2
XS Rating Curve= 0 ,0
Exp/Cntr=0.3,0.1

Type RM Length L Ch R = 1 ,358     ,0,0,0
BEGIN DESCRIPTION:
CCT8_4 1.0
END DESCRIPTION:
XS GIS Cut Line= 3
      2720700.98      6890786.01      2720447.73      6890935.93
        2720601.        6891186.
#Sta/Elev= 30
  4705.7  382.28  4711.5  382.09  4764.2  381.76    4807   381.8  4859.7  381.49
  4918.2  381.53    4924  381.66  4939.7  381.59  4945.5  381.72  4961.1  381.59
  4967.1  381.96  4976.7  382.04  4982.5  381.44  4990.4  381.22  4998.1   381.2
  5001.2  378.49  5001.4  377.99  5004.9  377.99  5005.2  378.49    5009  378.52
  5017.7  382.37  5024.5  380.83  5052.9  380.37  5061.2  380.37  5103.8   380.9
  5125.1  381.04  5170.1  381.05  5183.1  381.25    5272  381.68  5293.3  381.96
#Mann= 3 ,-1 , 0
  4705.7     .07       0  5001.2     .04       0  5005.2     .07       0
Bank Sta=5001.2,5005.2
XS Rating Curve= 0 ,0
Exp/Cntr=0.3,0.1

Chan Stop Cuts=-1
Use User Specified Reach Order=0
Composite Channel Slope=5