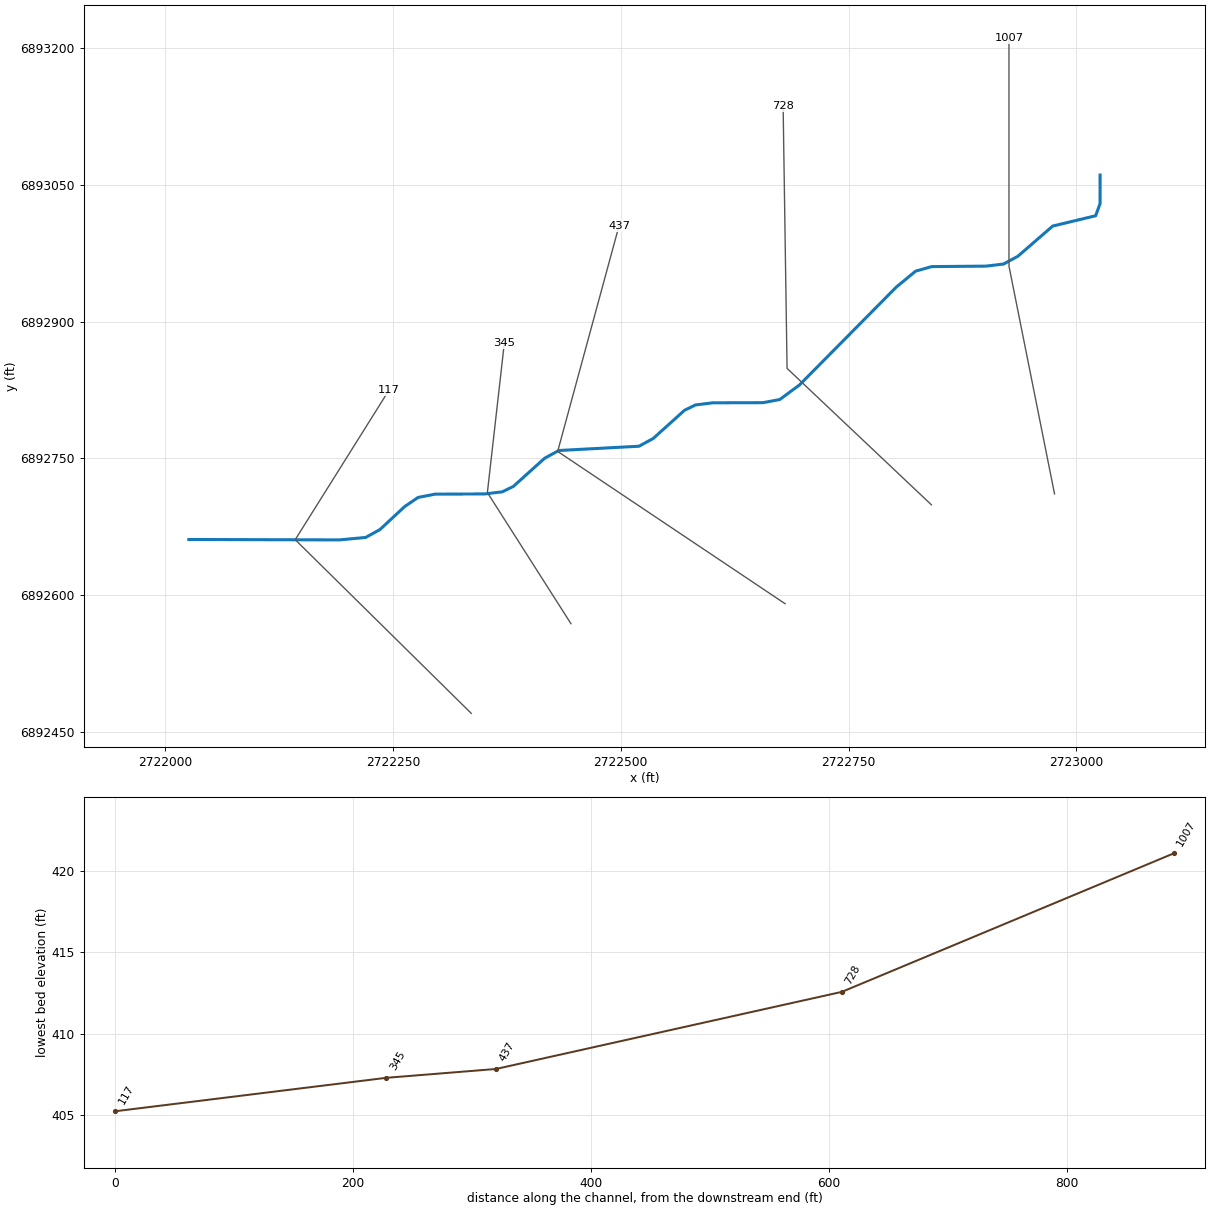
--- CCT8_4_1.prj (project) ---

Proj Title=CCT8_4_1 Base Level Engineering
Current Plan=p01
Default Exp/Contr=0.3,0.1
English Units
Geom File=g01
Flow File=f01
Plan File=p01
Y Axis Title=Elevation
X Axis Title(PF)=Main Channel Distance
X Axis Title(XS)=Station
BEGIN DESCRIPTION:
CCT8_4_1
END DESCRIPTION:
DSS Export Rating Curves= 0
DSS Export Rating Curve Sorted= 0
DSS Export Volume Flow Curves= 0
DXF OffsetX= 0
DXF OffsetY= 0
DXF ScaleX= 1
DXF ScaleY= 10

--- CCT8_4_1.p01 (plan) ---

Plan Title=Multiple Run
Short Identifier=Multiple
Geom File=g01
Flow File=f01
Subcritical Flow
K Sum by GR= 0
Std Step Tol= 0.01
Critical Tol= 0.01
Num of Std Step Trials= 20
Max Error Tol= 0.3
Flow Tol Ratio= 0.001
Split Flow NTrial= 30
Split Flow Tol= 0.02
Split Flow Ratio= 0.02
Log Output Level= 0
Friction Slope Method= 1
Unsteady Friction Slope Method= 2
Unsteady Bridges Friction Slope Method= 1
Parabolic Critical Depth
Global Vel Dist=  1 , 1 , 1
Global Log Level= 0
CheckData=True
Encroach Param= -1, 0, 0, 0
BEGIN DESCRIPTION:
Multiple Run
END DESCRIPTION:

--- CCT8_4_1.f01 (steady flow) ---

Flow Title=Multiple
Program Version=4.10
Number of Profiles= 7
Profile Names=10-year,25-year,50-year,1pct_min,100-year,1pct_plu,500-year
River Rch & RM=CCT8_4_1,Reach-1         ,1007
     105     124     138      77     153     305     187
Boundary for River Rch & Prof#=CCT8_4_1,Reach-1         , 1
Up Type= 0
Dn Type= 3
Dn Slope=0.009
Boundary for River Rch & Prof#=CCT8_4_1,Reach-1         , 2
Up Type= 0
Dn Type= 3
Dn Slope=0.009
Boundary for River Rch & Prof#=CCT8_4_1,Reach-1         , 3
Up Type= 0
Dn Type= 3
Dn Slope=0.009
Boundary for River Rch & Prof#=CCT8_4_1,Reach-1         , 4
Up Type= 0
Dn Type= 3
Dn Slope=0.009
Boundary for River Rch & Prof#=CCT8_4_1,Reach-1         , 5
Up Type= 0
Dn Type= 3
Dn Slope=0.009
Boundary for River Rch & Prof#=CCT8_4_1,Reach-1         , 6
Up Type= 0
Dn Type= 3
Dn Slope=0.009
Boundary for River Rch & Prof#=CCT8_4_1,Reach-1         , 7
Up Type= 0
Dn Type= 3
Dn Slope=0.009
DSS Import GetInterval= 0
DSS Import GetPeak= 0
DSS Import FillOption= 0

--- CCT8_4_1.g01 (geometry) ---

Geom Title=Existing Conditions
Program Version=4.10

River Reach=CCT8_4_1        ,Reach-1
Reach XY= 30
        2723026.        6893061.      2723025.94      6893029.44
       2723021.1      6893016.28        2722974.      6893004.96
      2722935.71      6892971.79      2722920.06      6892963.31
      2722901.01      6892960.99      2722841.22      6892960.48
      2722823.57      6892955.48      2722802.48      6892938.12
      2722696.15      6892830.63       2722674.5      6892814.61
      2722655.95      6892811.13        2722601.      6892810.99
      2722581.98      6892808.64      2722569.96      6892802.81
      2722535.63      6892771.89      2722520.03      6892763.35
      2722431.97      6892758.65      2722416.37      6892750.11
      2722382.04      6892719.19      2722370.03      6892713.35
        2722351.        6892711.       2722296.1      6892710.76
       2722277.6      6892707.14      2722262.87      6892697.17
      2722235.65      6892671.85      2722220.07      6892663.25
      2722191.18      6892660.55        2722026.        6892661.

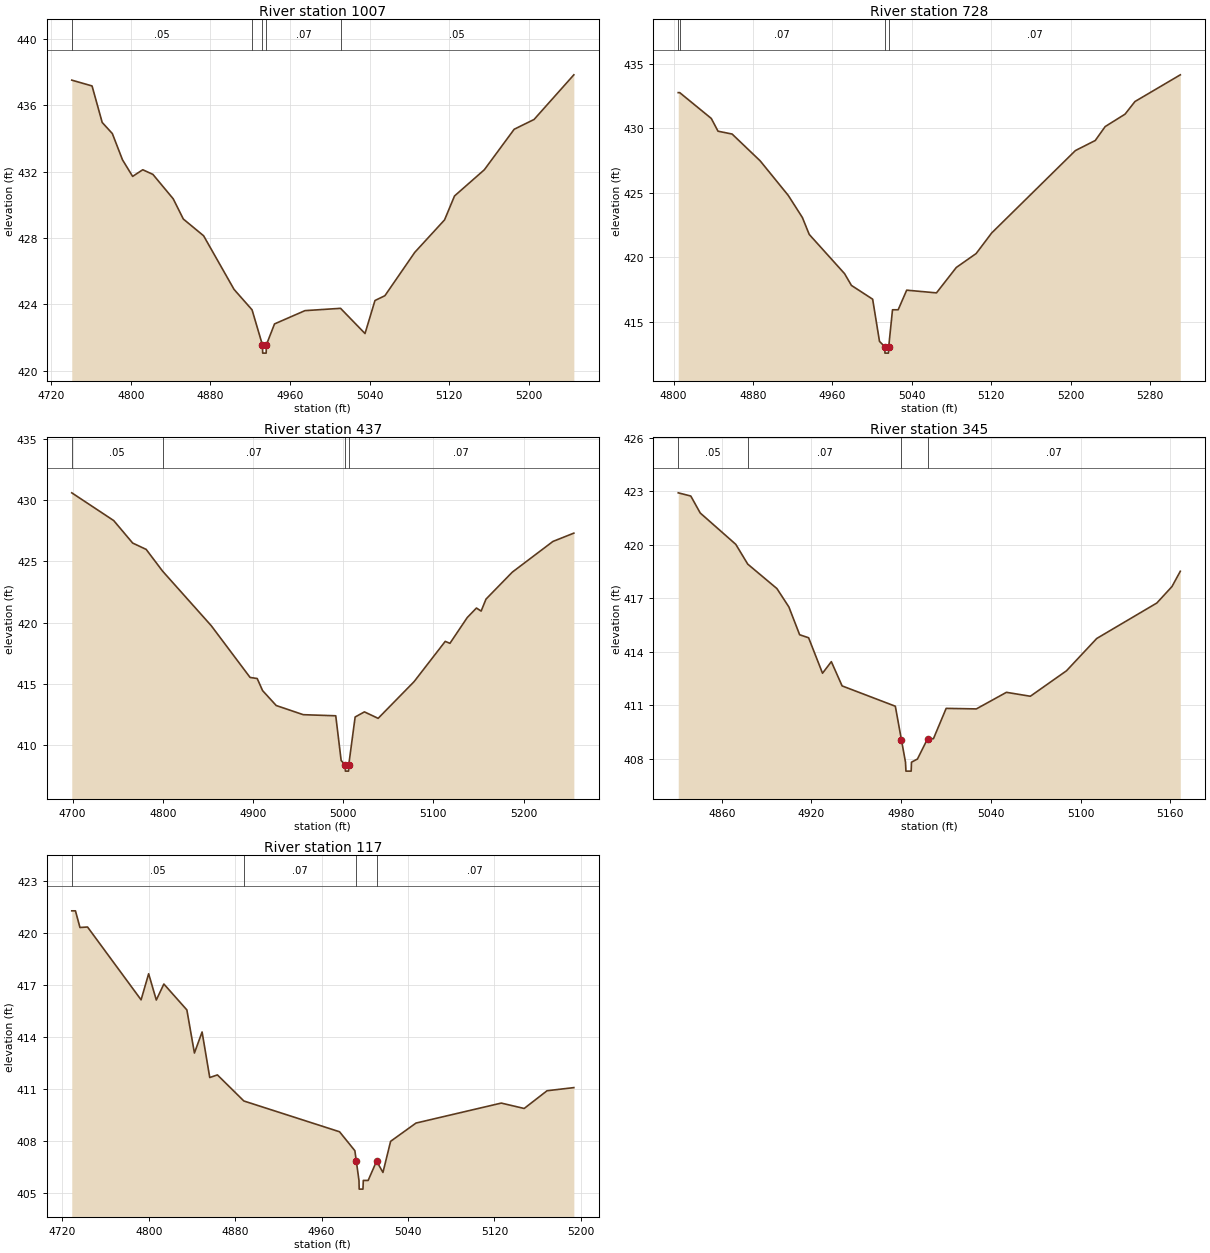
Type RM Length L Ch R = 1 ,1007    ,279,279,279
BEGIN DESCRIPTION:
CCT8_4_1 2.0
END DESCRIPTION:
XS GIS Cut Line= 3
        2722976.      6892711.02        2722926.        6892961.
        2722926.      6893210.97
#Sta/Elev= 30
  4740.5  437.51  4760.9  437.16  4771.1  434.96  4781.3  434.29  4791.5  432.71
  4801.7  431.71  4811.9  432.11  4822.1  431.83  4842.5  430.36  4852.7  429.14
  4873.1  428.13  4903.7   424.9  4921.8  423.67  4932.2  421.56  4932.5  421.06
    4936  421.06  4936.2  421.56  4944.4  422.82    4975  423.62  5010.8  423.76
  5035.4  422.24  5045.4  424.23  5055.4  424.52  5085.4  427.13  5115.4  429.09
  5125.4  430.53  5155.4  432.11  5185.4  434.55  5205.4  435.14  5245.4  437.83
#Mann= 5 ,-1 , 0
  4740.5     .05       0  4921.8     .07       0  4932.2     .04       0
  4936.2     .07       0  5010.8     .05       0
Bank Sta=4932.2,4936.2
XS Rating Curve= 0 ,0
Exp/Cntr=0.3,0.1

Type RM Length L Ch R = 1 ,728     ,291,291,291
BEGIN DESCRIPTION:
Mapping XS f8914ac9
END DESCRIPTION:
XS GIS Cut Line= 3
      2722840.87      6892699.07      2722682.48      6892848.78
      2722678.15       6893136.7
#Sta/Elev= 30
  4804.6  432.76  4806.1  432.76  4837.9  430.76  4844.7  429.77  4858.9  429.55
  4887.2  427.47  4915.5  424.79  4929.7  423.08  4936.6  421.77  4972.2  418.73
  4979.1  417.82  5000.5  416.75  5007.4  413.48  5012.7  413.07  5012.9  412.57
  5016.4  412.57  5016.7  413.07  5020.5  415.93  5026.2  415.93  5034.8  417.45
  5064.8  417.24  5084.8  419.21  5104.8  420.29  5120.4  421.88  5204.8  428.27
  5224.8  429.05  5234.8  430.13  5254.8  431.09  5264.8  432.07  5310.5  434.14
#Mann= 4 ,-1 , 0
  4804.6     .05       0  4806.1     .07       0  5012.7     .04       0
  5016.7     .07       0
Bank Sta=5012.7,5016.7
XS Rating Curve= 0 ,0
Exp/Cntr=0.3,0.1

Type RM Length L Ch R = 1 ,437     ,92,92,92
BEGIN DESCRIPTION:
Mapping XS af51e15d
END DESCRIPTION:
XS GIS Cut Line= 3
      2722680.29      6892590.54      2722430.74      6892757.63
      2722498.02      6893005.03
#Sta/Elev= 30
    4699  430.62  4745.5  428.35  4766.5  426.51  4781.5  425.99  4799.7  424.21
  4853.6  419.75  4896.7  415.51  4904.6  415.42  4910.6  414.43  4925.7  413.21
  4955.7  412.46  4991.7  412.37  4997.7  408.71  5002.1  408.34  5002.4  407.84
  5005.9  407.84  5006.1  408.34  5013.2  412.27  5023.5  412.69  5038.7  412.16
  5078.5  415.16  5113.1  418.46  5118.3   418.3  5137.5  420.41  5147.7  421.19
  5152.9  420.94  5158.3  421.92  5187.5  424.13  5232.5  426.64  5255.7  427.32
#Mann= 4 ,-1 , 0
    4699     .05       0  4799.7     .07       0  5002.1     .04       0
  5006.1     .07       0
Bank Sta=5002.1,5006.1
XS Rating Curve= 0 ,0
Exp/Cntr=0.3,0.1

Type RM Length L Ch R = 1 ,345     ,228,228,228
BEGIN DESCRIPTION:
Mapping XS f35013f9
END DESCRIPTION:
XS GIS Cut Line= 3
      2722445.34      6892568.56       2722353.6      6892712.51
      2722372.21      6892876.57
#Sta/Elev= 30
  4830.9  422.91  4839.3  422.73  4845.6  421.78  4869.4  420.02  4877.4  418.91
  4896.9  417.54  4904.9  416.51  4912.1  414.95  4918.1  414.78  4927.4  412.79
  4933.3  413.44  4940.5  412.08  4976.1  410.94 4980.22 409.037  4982.9   407.8
  4983.2   407.3  4986.7   407.3  4986.9   407.8  4990.9  407.98  4997.7  409.12
  5001.6  409.12  5010.1  410.82  5030.3  410.79  5050.4  411.72  5066.4   411.5
  5090.6  412.93  5110.8  414.74    5151  416.73  5161.1  417.65  5166.7  418.51
#Mann= 4 ,-1 , 0
  4830.9     .05       0  4877.4     .07       0 4980.22     .04       0
  4997.7     .07       0
Bank Sta=4980.22,4997.7
XS Rating Curve= 0 ,0
Exp/Cntr=0.3,0.1

Type RM Length L Ch R = 1 ,117     ,0,0,0
BEGIN DESCRIPTION:
CCT8_4_1 1.0
END DESCRIPTION:
XS GIS Cut Line= 3
      2722335.92      6892470.18      2722142.72      6892660.79
      2722245.58      6892824.81
#Sta/Elev= 30
  4728.6  421.26    4732  421.26  4736.2   420.3  4743.2  420.33  4792.8  416.14
  4799.8  417.64  4806.9  416.13  4813.9  417.05  4835.2  415.56  4842.2  413.08
  4849.3  414.29  4856.4  411.67  4863.5  411.82    4888  410.32  4976.6  408.55
  4990.8  407.46 4992.17 406.844  4994.6  405.75  4994.8  405.25  4998.3  405.25
  4998.6  405.75  5003.1  405.75  5010.9  406.86  5016.8  406.21  5023.9     408
  5047.4  409.05  5126.4   410.2  5147.6  409.89  5168.8  410.91  5193.6  411.09
#Mann= 4 ,-1 , 0
  4728.6     .05       0    4888     .07       0 4992.17     .04       0
  5010.9     .07       0
Bank Sta=4992.17,5010.9
XS Rating Curve= 0 ,0
Exp/Cntr=0.3,0.1

Chan Stop Cuts=-1
Use User Specified Reach Order=0
Composite Channel Slope=5