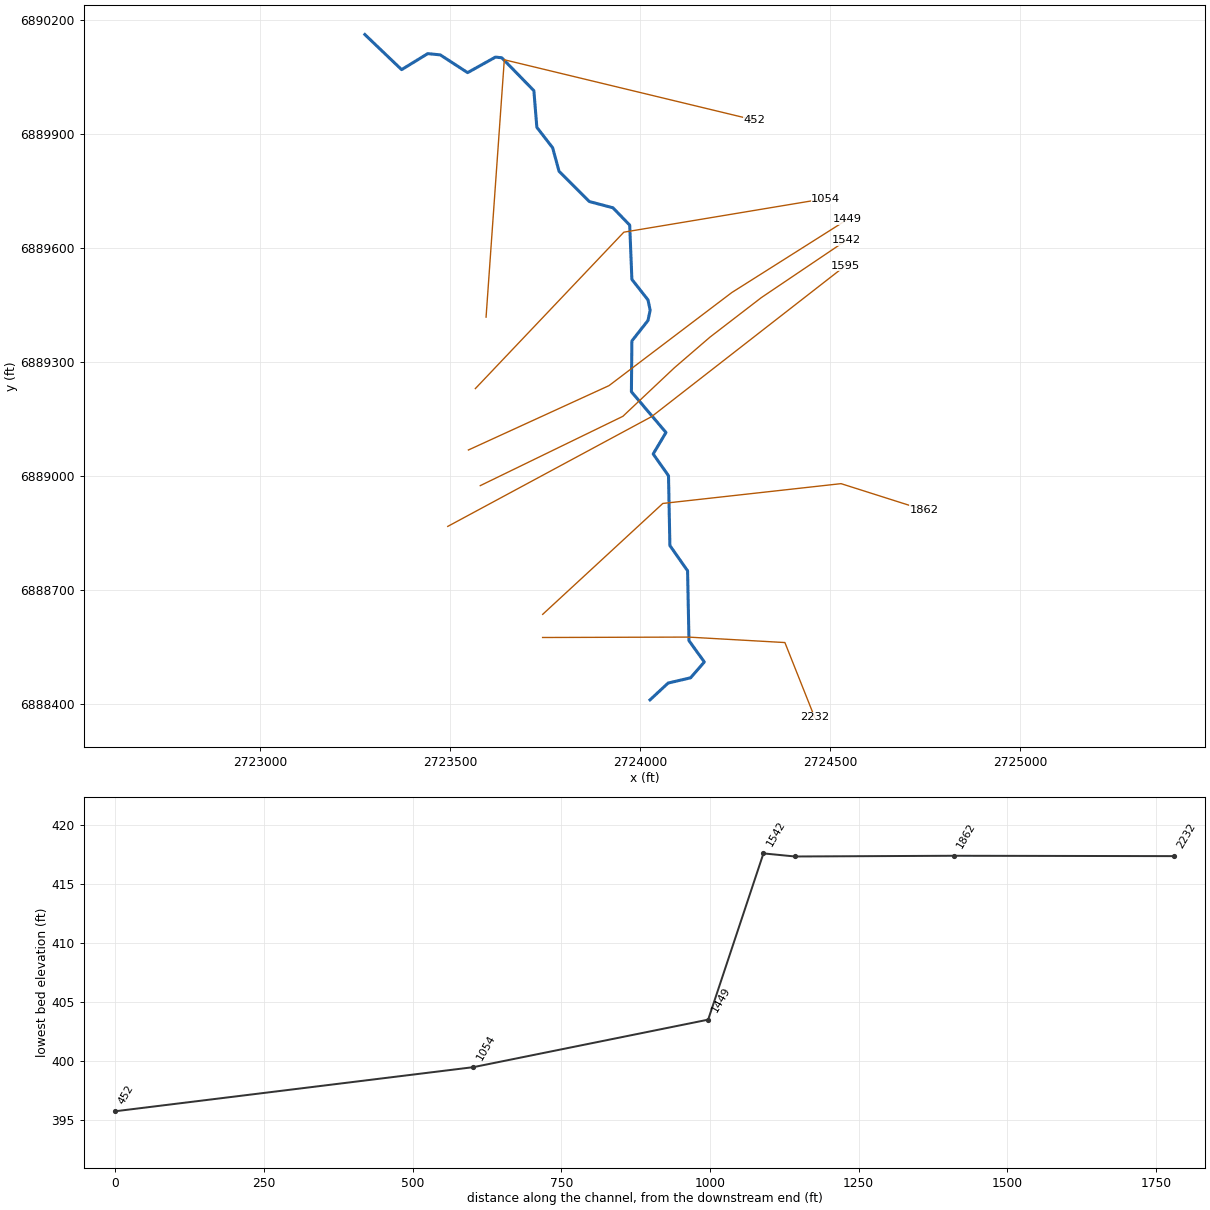
--- CCT8_5.prj (project) ---

Proj Title=CCT8_5 Base Level Engineering
Current Plan=p01
Default Exp/Contr=0.3,0.1
English Units
Geom File=g01
Flow File=f01
Plan File=p01
BEGIN DESCRIPTION:
CCT8_5
END DESCRIPTION:

--- CCT8_5.p01 (plan) ---

Plan Title=Multiple Run
Short Identifier=Multiple
Geom File=g01
Flow File=f01
Subcritical Flow
K Sum by GR= 0
Std Step Tol= 0.01
Critical Tol= 0.01
Num of Std Step Trials= 20
Max Error Tol= 0.3
Flow Tol Ratio= 0.001
Split Flow NTrial= 30
Split Flow Tol= 0.02
Split Flow Ratio= 0.02
Log Output Level= 0
Friction Slope Method= 1
Unsteady Friction Slope Method= 2
Unsteady Bridges Friction Slope Method= 1
Parabolic Critical Depth
Global Vel Dist=  1 , 1 , 1
Global Log Level= 0
CheckData=True
Encroach Param= -1, 0, 0, 0
BEGIN DESCRIPTION:
Multiple Run
END DESCRIPTION:

--- CCT8_5.f01 (steady flow) ---

Flow Title=Multiple
Number of Profiles=7
Profile Names=10-year,25-year,50-year,1pct_min,100-year,1pct_plu,500-year
River Rch & RM= CCT8_5,Reach-1,2232
     193     241     276     158     316     631     411
Boundary for River Rch & Prof#=CCT8_5,Reach-1,1
Up Type=0
Dn Type=3
Dn Slope=0.005
Boundary for River Rch & Prof#=CCT8_5,Reach-1,2
Up Type=0
Dn Type=3
Dn Slope=0.005
Boundary for River Rch & Prof#=CCT8_5,Reach-1,3
Up Type=0
Dn Type=3
Dn Slope=0.005
Boundary for River Rch & Prof#=CCT8_5,Reach-1,4
Up Type=0
Dn Type=3
Dn Slope=0.005
Boundary for River Rch & Prof#=CCT8_5,Reach-1,5
Up Type=0
Dn Type=3
Dn Slope=0.005
Boundary for River Rch & Prof#=CCT8_5,Reach-1,6
Up Type=0
Dn Type=3
Dn Slope=0.005
Boundary for River Rch & Prof#=CCT8_5,Reach-1,7
Up Type=0
Dn Type=3
Dn Slope=0.005

--- CCT8_5.g01 (geometry) ---

Geom Title=Existing Conditions

River Reach=CCT8_5,Reach-1
Reach XY= 30
      2724026.00      6888411.00      2724073.72      6888455.29
      2724132.78      6888469.05      2724168.79      6888510.68
      2724128.47      6888566.84      2724124.78      6888750.49
      2724078.26      6888816.94      2724074.62      6889000.57
      2724034.29      6889057.79      2724067.99      6889114.33
      2723977.05      6889221.44      2723978.28      6889355.07
      2724020.62      6889408.82      2724026.40      6889436.00
      2724020.62      6889463.18      2723978.30      6889516.93
      2723972.55      6889659.75      2723928.57      6889705.26
      2723866.32      6889721.78      2723786.75      6889801.29
      2723769.86      6889863.17      2723728.33      6889916.97
      2723720.48      6890013.46      2723636.08      6890099.90
      2723619.46      6890101.67      2723546.20      6890060.81
      2723474.27      6890107.57      2723441.34      6890110.77
      2723372.59      6890068.70      2723276.00      6890161.00

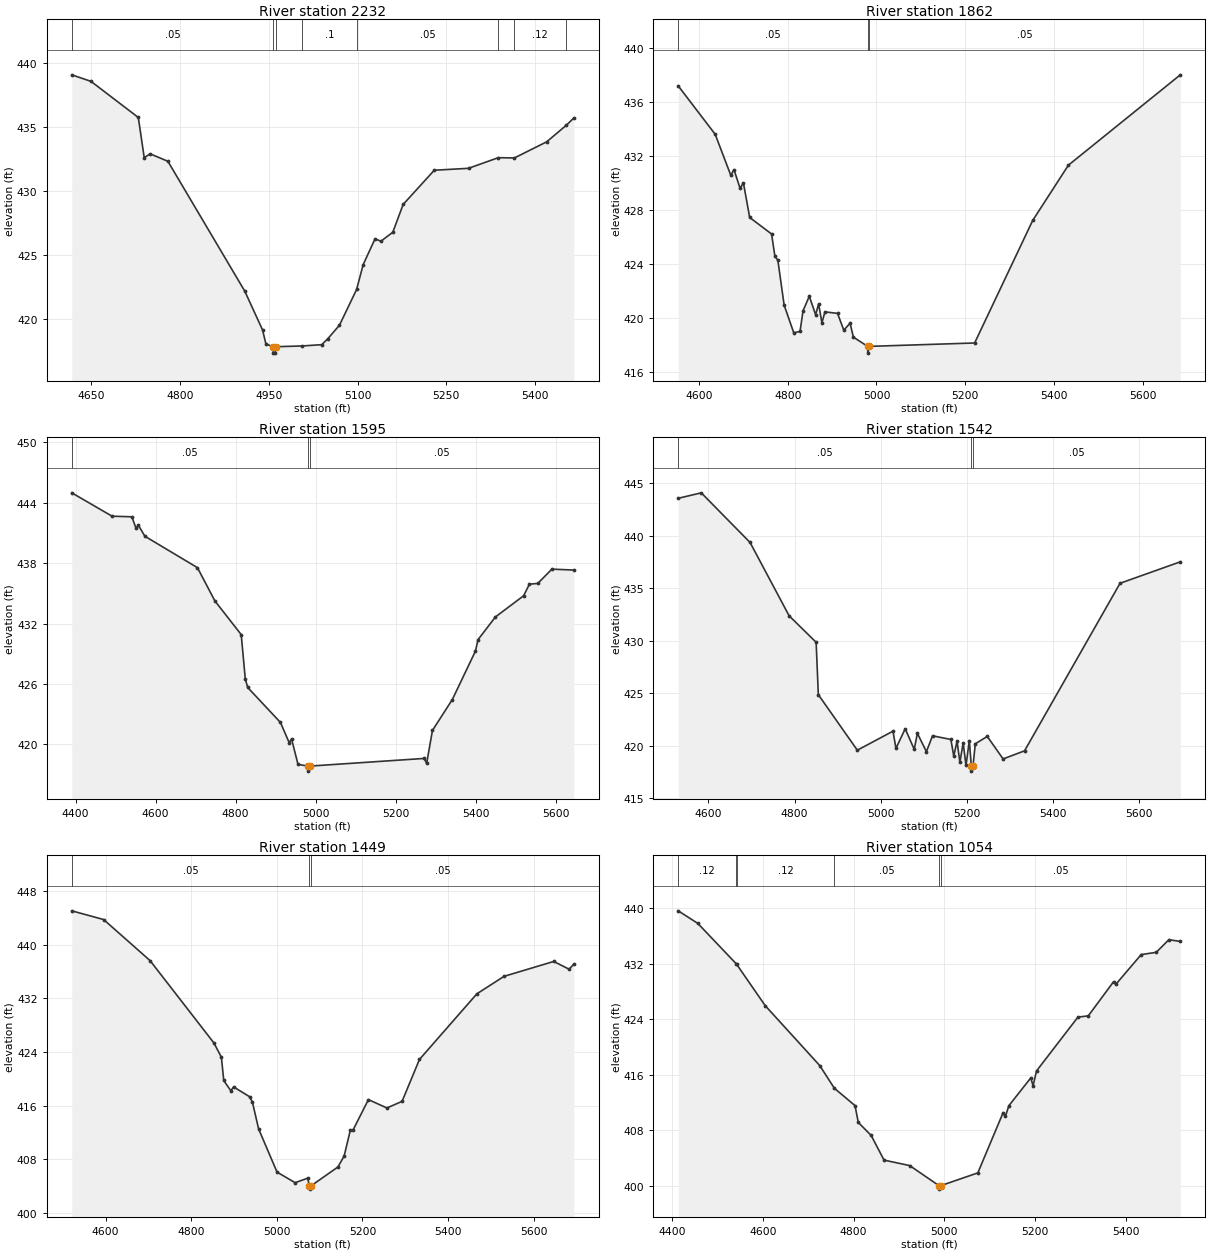
Type RM Length L Ch R = 1,2232,370,370,370
BEGIN DESCRIPTION:
Mapping XS 0a7b0749
END DESCRIPTION:
XS GIS Cut Line= 4
      2723743.47      6888575.07      2724126.67      6888576.15
      2724380.78      6888561.76      2724458.82      6888365.53
#Sta/Elev= 30
  4616.8  439.10  4649.3  438.59  4729.3  435.77  4739.3  432.63  4749.3  432.93
  4779.3  432.35  4909.3  422.21  4939.3  419.19  4945.1  418.08  4957.3  417.87
  4957.6  417.37  4961.1  417.37  4961.3  417.87  5006.4  417.93  5039.4  418.03
  5049.4  418.48  5069.4  419.55  5098.4  422.34  5109.5  424.28  5129.5  426.29
  5139.6  426.11  5159.6  426.81  5177.1  428.98  5229.7  431.65  5287.6  431.80
  5337.9  432.63  5365.2  432.61  5419.8  433.87  5452.9  435.16  5465.7  435.73
#Mann=8,-1,0
  4616.8    0.05       0  4957.3    0.05       0  4961.3    0.05       0
  5006.4     0.1       0  5098.4    0.05       0  5337.9     0.1       0
  5365.2    0.12       0  5452.9     0.1       0
Bank Sta=4957.3,4961.3
Exp/Cntr=0.3,0.1

Type RM Length L Ch R = 1,1862,267,267,267
BEGIN DESCRIPTION:
Mapping XS e6a6e299
END DESCRIPTION:
XS GIS Cut Line= 4
      2723743.68      6888635.96      2724059.67      6888927.64
      2724528.42      6888979.73      2724747.19      6888910.28
#Sta/Elev= 30
  4553.4  437.16  4636.7  433.58  4671.8  430.55  4679.0  430.97  4692.8  429.58
  4700.2  430.00  4714.4  427.43  4763.7  426.21  4771.1  424.58  4777.9  424.26
  4792.0  420.95  4813.6  418.91  4827.8  419.00  4834.6  420.53  4848.7  421.61
  4862.9  420.24  4869.7  421.04  4877.1  419.64  4883.9  420.45  4912.3  420.34
  4926.4  419.10  4940.6  419.61  4948.0  418.58  4980.2  417.90  4980.5  417.40
  4984.2  417.90  5221.2  418.15  5352.0  427.21  5432.5  431.30  5684.6  437.98
#Mann=3,-1,0
  4553.4    0.05       0  4980.2   0.035       0  4984.2    0.05       0
Bank Sta=4980.2,4984.2
Exp/Cntr=0.3,0.1

Type RM Length L Ch R = 1,1595,53,53,53
BEGIN DESCRIPTION:
Mapping XS 372d1712
END DESCRIPTION:
XS GIS Cut Line= 3
      2723494.04      6888867.31      2724030.08      6889155.94
      2724540.08      6889553.09
#Sta/Elev= 30
  4390.3  444.98  4491.0  442.66  4540.5  442.60  4551.1  441.44  4556.7  441.77
  4573.0  440.67  4704.4  437.55  4748.2  434.24  4813.9  430.90  4824.1  426.50
  4830.1  425.65  4912.1  422.17  4934.0  420.15  4939.7  420.55  4955.9  418.01
  4981.5  417.84  4981.7  417.34  4985.5  417.84  5271.2  418.60  5277.5  418.11
  5292.0  421.38  5341.7  424.45  5399.5  429.26  5406.0  430.40  5449.4  432.65
  5520.0  434.76  5534.5  435.91  5555.3  435.98  5590.6  437.40  5645.5  437.31
#Mann=3,-1,0
  4390.3    0.05       0  4981.5   0.035       0  4985.5    0.05       0
Bank Sta=4981.5,4985.5
Exp/Cntr=0.3,0.1

Type RM Length L Ch R = 1,1542,93,93,93
BEGIN DESCRIPTION:
Mapping XS 9a14a150
END DESCRIPTION:
XS GIS Cut Line= 6
      2723579.53      6888974.50      2723954.56      6889156.81
      2724089.98      6889284.41      2724183.73      6889365.14
      2724319.15      6889469.31      2724542.04      6889619.63
#Sta/Elev= 30
  4529.7  443.54  4583.2  444.06  4696.6  439.34  4787.3  432.37  4850.1  429.85
  4855.2  424.87  4945.8  419.59  5028.7  421.40  5035.5  419.76  5057.0  421.63
  5078.0  419.67  5085.3  421.20  5106.3  419.45  5120.5  420.96  5163.2  420.61
  5169.8  419.03  5177.5  420.44  5184.1  418.45  5191.7  420.28  5198.3  418.14
  5206.0  420.50  5210.6  418.10  5210.8  417.60  5214.6  418.10  5219.9  420.20
  5247.7  420.90  5284.5  418.76  5334.3  419.53  5556.2  435.46  5696.2  437.50
#Mann=3,-1,0
  4529.7    0.05       0  5210.6   0.035       0  5214.6    0.05       0
Bank Sta=5210.6,5214.6
Exp/Cntr=0.3,0.1

Type RM Length L Ch R = 1,1449,395,395,395
BEGIN DESCRIPTION:
Mapping XS 5e8b4427
END DESCRIPTION:
XS GIS Cut Line= 4
      2723548.32      6889068.27      2723918.10      6889237.54
      2724241.02      6889482.33      2724545.69      6889675.03
#Sta/Elev= 30
  4521.2  445.03  4595.6  443.73  4704.0  437.61  4853.1  425.33  4870.6  423.20
  4876.1  419.73  4892.6  418.20  4899.1  418.77  4936.7  417.30  4943.0  416.51
  4957.5  412.51  5000.5  406.07  5042.8  404.49  5071.9  405.16  5076.2  404.03
  5076.5  403.53  5080.2  404.03  5142.7  406.83  5157.2  408.46  5171.8  412.36
  5178.1  412.36  5213.9  416.88  5257.1  415.63  5292.5  416.62  5333.1  422.87
  5467.1  432.65  5530.6  435.26  5646.6  437.48  5682.4  436.33  5693.6  437.07
#Mann=3,-1,0
  4521.2    0.05       0  5076.2   0.035       0  5080.2    0.05       0
Bank Sta=5076.2,5080.2
Exp/Cntr=0.3,0.1

Type RM Length L Ch R = 1,1054,602,602,602
BEGIN DESCRIPTION:
Mapping XS 43907657
END DESCRIPTION:
XS GIS Cut Line= 3
      2723566.57      6889229.75      2723957.17      6889641.19
      2724488.43      6889729.73
#Sta/Elev= 30
  4413.8  439.60  4456.9  437.79  4541.6  431.97  4542.2  431.92  4605.4  425.94
  4725.5  417.31  4757.7  414.04  4803.2  411.54  4810.4  409.12  4838.8  407.24
  4867.1  403.69  4923.7  402.90  4988.1  400.01  4988.3  399.51  4992.1  400.01
  5073.7  401.85  5129.5  410.54  5134.6  410.02  5142.1  411.53  5190.3  415.53
  5195.4  414.40  5203.0  416.54  5294.2  424.29  5317.0  424.47  5372.8  429.40
  5377.9  429.03  5433.6  433.30  5466.6  433.62  5494.5  435.44  5519.7  435.19
#Mann=6,-1,0
  4413.8    0.12       0  4541.6    0.05       0  4542.2    0.12       0
  4757.7    0.05       0  4988.1    0.05       0  4992.1    0.05       0
Bank Sta=4988.1,4992.1
Exp/Cntr=0.3,0.1

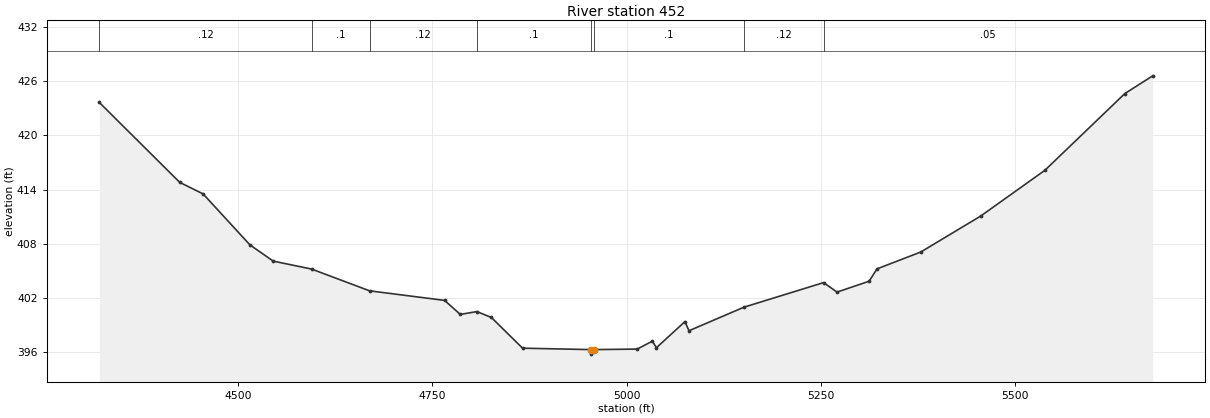
Type RM Length L Ch R = 1,452,0,0,0
BEGIN DESCRIPTION:
CCT8_5 1.0
END DESCRIPTION:
XS GIS Cut Line= 3
      2723594.76      6889417.71      2723642.74      6890094.71
      2724300.98      6889936.01
#Sta/Elev= 30
  4321.3  423.65  4424.8  414.80  4454.9  413.52  4515.1  407.88  4545.1  406.08
  4594.5  405.20  4669.1  402.79  4765.7  401.73  4785.8  400.18  4807.3  400.49
  4825.9  399.84  4866.0  396.44  4954.2  396.28  4954.4  395.78  4958.2  396.28
  5013.6  396.34  5033.1  397.22  5038.3  396.49  5075.0  399.38  5080.2  398.37
  5151.0  400.98  5253.4  403.70  5270.8  402.65  5312.0  403.85  5322.2  405.22
  5378.6  407.09  5456.0  411.09  5538.3  416.14  5641.1  424.63  5677.1  426.60
#Mann=8,-1,0
  4321.3    0.12       0  4594.5     0.1       0  4669.1    0.12       0
  4807.3     0.1       0  4954.2    0.07       0  4958.2     0.1       0
  5151.0    0.12       0  5253.4    0.05       0
Bank Sta=4954.2,4958.2
Exp/Cntr=0.3,0.1

Chan Stop Cuts=-1