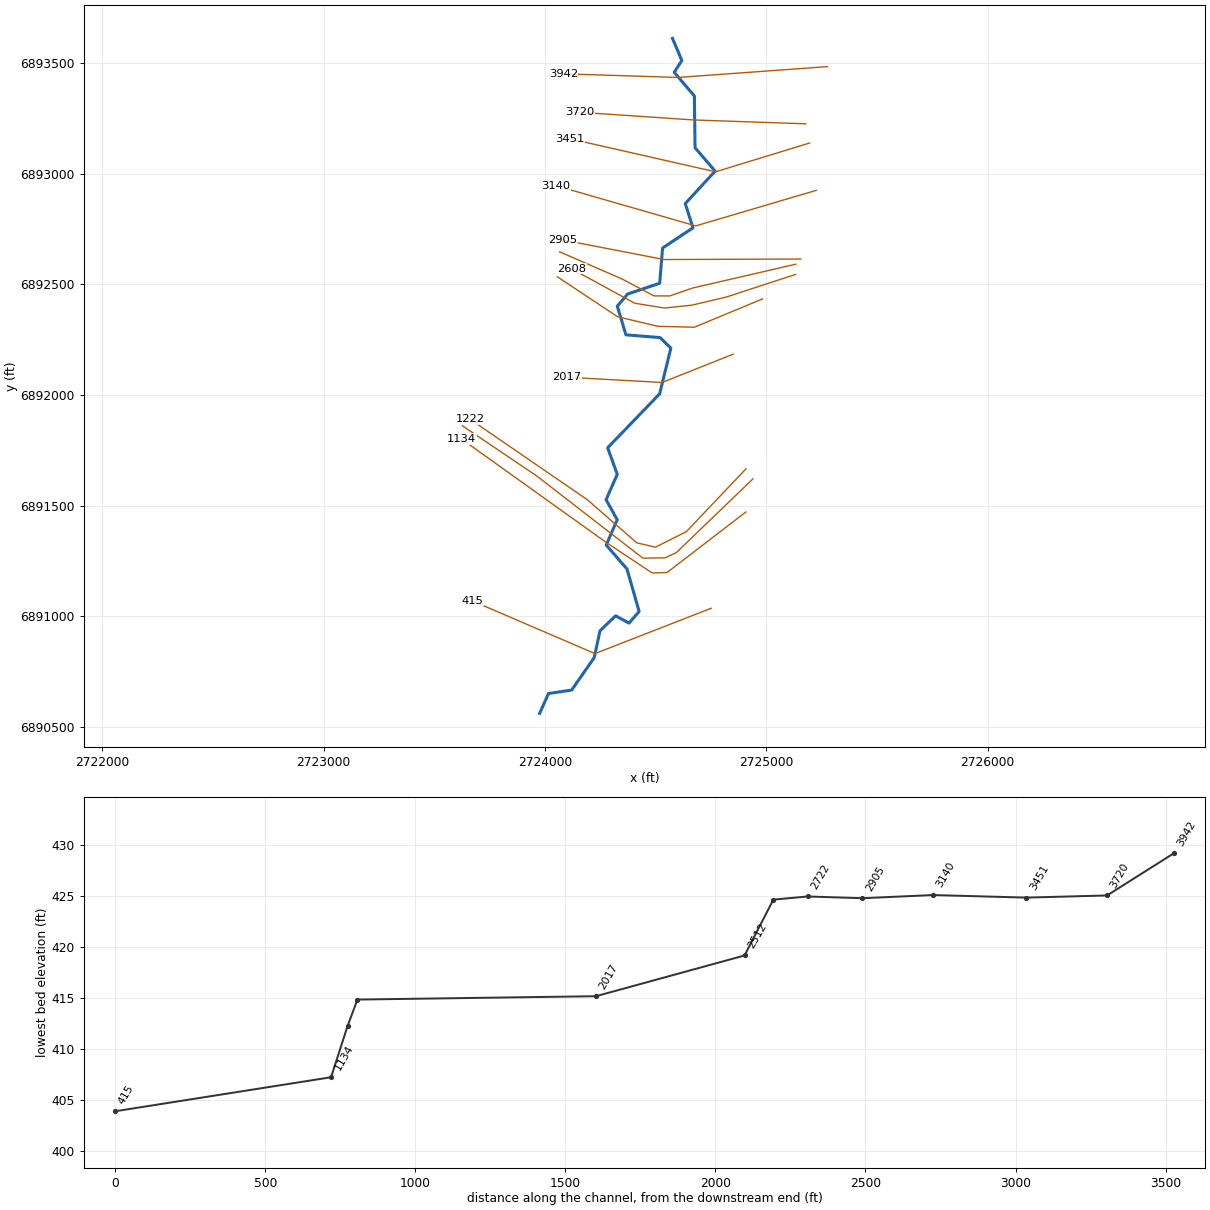
--- CCT8_6.prj (project) ---

Proj Title=CCT8_6 Base Level Engineering
Current Plan=p01
Default Exp/Contr=0.3,0.1
English Units
Geom File=g01
Flow File=f01
Plan File=p01
BEGIN DESCRIPTION:
CCT8_6
END DESCRIPTION:

--- CCT8_6.p01 (plan) ---

Plan Title=Multiple Run
Short Identifier=Multiple
Geom File=g01
Flow File=f01
Subcritical Flow
K Sum by GR= 0
Std Step Tol= 0.01
Critical Tol= 0.01
Num of Std Step Trials= 20
Max Error Tol= 0.3
Flow Tol Ratio= 0.001
Split Flow NTrial= 30
Split Flow Tol= 0.02
Split Flow Ratio= 0.02
Log Output Level= 0
Friction Slope Method= 1
Unsteady Friction Slope Method= 2
Unsteady Bridges Friction Slope Method= 1
Parabolic Critical Depth
Global Vel Dist=  1 , 1 , 1
Global Log Level= 0
CheckData=True
Encroach Param= -1, 0, 0, 0
BEGIN DESCRIPTION:
Multiple Run
END DESCRIPTION:

--- CCT8_6.f01 (steady flow) ---

Flow Title=Multiple
Number of Profiles=7
Profile Names=10-year,25-year,50-year,1pct_min,100-year,1pct_plu,500-year
River Rch & RM= CCT8_6,Reach-1,3942
     330     423     496     289     577    1151     778
Boundary for River Rch & Prof#=CCT8_6,Reach-1,1
Up Type=0
Dn Type=3
Dn Slope=0.005
Boundary for River Rch & Prof#=CCT8_6,Reach-1,2
Up Type=0
Dn Type=3
Dn Slope=0.005
Boundary for River Rch & Prof#=CCT8_6,Reach-1,3
Up Type=0
Dn Type=3
Dn Slope=0.005
Boundary for River Rch & Prof#=CCT8_6,Reach-1,4
Up Type=0
Dn Type=3
Dn Slope=0.005
Boundary for River Rch & Prof#=CCT8_6,Reach-1,5
Up Type=0
Dn Type=3
Dn Slope=0.005
Boundary for River Rch & Prof#=CCT8_6,Reach-1,6
Up Type=0
Dn Type=3
Dn Slope=0.005
Boundary for River Rch & Prof#=CCT8_6,Reach-1,7
Up Type=0
Dn Type=3
Dn Slope=0.005

--- CCT8_6.g01 (geometry) ---

Geom Title=Existing Conditions

River Reach=CCT8_6,Reach-1
Reach XY= 30
      2724576.00      6893611.00      2724618.42      6893510.93
      2724583.99      6893457.67      2724674.94      6893350.57
      2724678.08      6893116.85      2724768.92      6893010.99
      2724633.82      6892864.41      2724668.61      6892754.67
      2724531.37      6892663.70      2724518.32      6892504.48
      2724373.29      6892455.59      2724326.86      6892400.68
      2724365.82      6892271.33      2724520.55      6892258.94
      2724568.79      6892211.35      2724518.18      6892004.81
      2724283.32      6891761.10      2724326.57      6891640.95
      2724276.11      6891526.39      2724326.38      6891436.00
      2724276.61      6891321.63      2724370.46      6891213.42
      2724425.40      6891021.29      2724379.66      6890968.90
      2724319.32      6891001.70      2724248.88      6890934.63
      2724222.37      6890812.50      2724120.53      6890666.26
      2724015.95      6890650.72      2723976.00      6890561.00

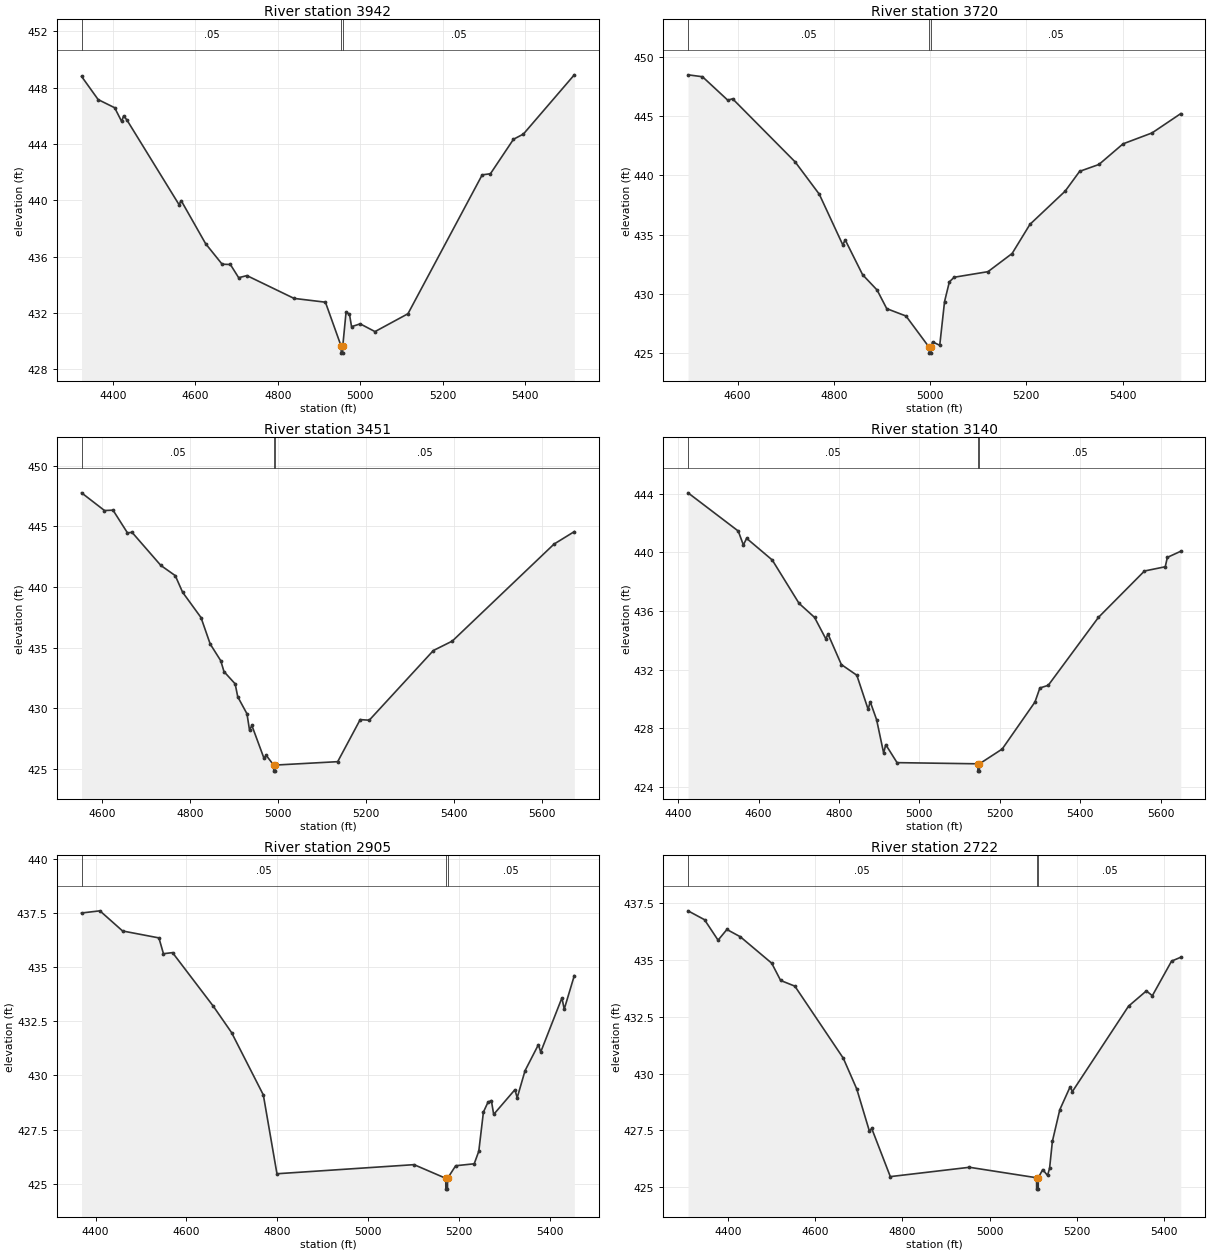
Type RM Length L Ch R = 1,3942,222,222,222
BEGIN DESCRIPTION:
CCT8_6 8.0
END DESCRIPTION:
XS GIS Cut Line= 3
      2725276.18      6893483.13      2724601.84      6893434.36
      2724082.59      6893450.58
#Sta/Elev= 30
  4323.9  448.81  4364.2  447.16  4404.3  446.58  4421.1  445.61  4426.1  446.01
  4434.4  445.69  4560.5  439.69  4565.6  439.98  4624.9  436.92  4665.0  435.46
  4685.0  435.44  4705.1  434.50  4725.1  434.65  4839.5  433.03  4915.6  432.76
  4953.7  429.64  4954.0  429.14  4957.5  429.14  4957.7  429.64  4965.7  432.06
  4974.0  431.90  4979.0  431.02  5000.0  431.22  5035.9  430.67  5115.9  431.94
  5296.0  441.81  5316.0  441.89  5371.9  444.34  5396.0  444.71  5519.5  448.92
#Mann=3,-1,0
  4323.9    0.05       0  4953.7    0.05       0  4957.7    0.05       0
Bank Sta=4953.7,4957.7
Exp/Cntr=0.3,0.1

Type RM Length L Ch R = 1,3720,269,269,269
BEGIN DESCRIPTION:
CCT8_6 7.0
END DESCRIPTION:
XS GIS Cut Line= 3
      2725178.52      6893224.89      2724670.73      6893242.25
      2724156.39      6893276.97
#Sta/Elev= 30
  4497.2  448.49  4527.2  448.33  4579.8  446.35  4589.8  446.47  4719.9  441.14
  4769.9  438.42  4818.7  434.15  4823.7  434.57  4859.9  431.63  4890.0  430.34
  4910.0  428.77  4950.0  428.15  4998.0  425.52  4998.3  425.02  5001.8  425.02
  5002.0  425.52  5005.2  425.97  5020.1  425.68  5030.1  429.37  5040.1  431.03
  5050.1  431.42  5120.3  431.89  5170.4  433.42  5207.5  435.88  5280.6  438.68
  5310.7  440.35  5350.8  440.93  5400.9  442.67  5461.1  443.59  5520.8  445.22
#Mann=3,-1,0
  4497.2    0.05       0  4998.0    0.04       0  5002.0    0.05       0
Bank Sta=4998,5002
Exp/Cntr=0.3,0.1

Type RM Length L Ch R = 1,3451,311,311,311
BEGIN DESCRIPTION:
Mapping XS df9b0441
END DESCRIPTION:
XS GIS Cut Line= 3
      2725195.87      6893138.07      2724770.56      6893007.87
      2724110.93      6893157.59
#Sta/Elev= 30
  4553.1  447.77  4605.3  446.31  4624.7  446.34  4657.5  444.47  4668.0  444.51
  4733.5  441.78  4766.3  440.94  4783.0  439.57  4824.9  437.48  4845.8  435.30
  4869.8  433.92  4877.2  433.02  4902.6  432.01  4908.5  430.94  4929.5  429.54
  4935.3  428.19  4940.6  428.58  4968.1  425.88  4973.3  426.11  4990.2  425.31
  4990.5  424.81  4994.0  424.81  4994.2  425.31  5135.9  425.59  5187.1  429.06
  5207.7  429.01  5353.6  434.76  5396.7  435.54  5628.1  443.54  5674.3  444.57
#Mann=3,-1,0
  4553.1    0.05       0  4990.2    0.03       0  4994.2    0.05       0
Bank Sta=4990.2,4994.2
Exp/Cntr=0.3,0.1

Type RM Length L Ch R = 1,3140,235,235,235
BEGIN DESCRIPTION:
Mapping XS d3e8690b
END DESCRIPTION:
XS GIS Cut Line= 3
      2725225.82      6892924.10      2724681.15      6892763.52
      2724049.22      6892945.30
#Sta/Elev= 30
  4424.7  444.07  4549.6  441.46  4562.3  440.51  4570.5  440.96  4634.2  439.48
  4700.8  436.52  4739.4  435.56  4767.5  434.09  4772.7  434.43  4806.0  432.34
  4844.5  431.61  4872.6  429.28  4877.8  429.80  4893.7  428.57  4911.2  426.29
  4916.4  426.87  4944.5  425.64  5145.5  425.56  5145.7  425.06  5149.2  425.06
  5149.5  425.56  5206.0  426.57  5287.5  429.78  5299.7  430.74  5320.5  430.92
  5445.3  435.56  5559.8  438.73  5611.5  439.02  5616.7  439.66  5650.1  440.08
#Mann=3,-1,0
  4424.7    0.05       0  5145.5    0.03       0  5149.5    0.05       0
Bank Sta=5145.5,5149.5
Exp/Cntr=0.3,0.1

Type RM Length L Ch R = 1,2905,183,183,183
BEGIN DESCRIPTION:
Mapping XS 7c7d6986
END DESCRIPTION:
XS GIS Cut Line= 3
      2725156.37      6892613.78      2724537.92      6892611.61
      2724079.47      6892700.27
#Sta/Elev= 30
  4369.0  437.50  4409.4  437.60  4459.4  436.67  4539.4  436.35  4549.4  435.62
  4569.4  435.67  4659.4  433.19  4699.4  431.98  4769.4  429.10  4799.4  425.46
  5101.4  425.88  5171.2  425.25  5171.5  424.75  5175.0  424.75  5175.2  425.25
  5193.1  425.83  5233.9  425.92  5244.0  426.50  5254.2  428.31  5264.4  428.77
  5271.7  428.84  5276.8  428.20  5323.5  429.34  5328.6  428.97  5345.9  430.22
  5375.3  431.42  5380.4  431.08  5427.1  433.58  5432.2  433.06  5454.4  434.61
#Mann=3,-1,0
  4369.0    0.05       0  5171.2    0.03       0  5175.2    0.05       0
Bank Sta=5171.2,5175.2
Exp/Cntr=0.3,0.1

Type RM Length L Ch R = 1,2722,114,114,114
BEGIN DESCRIPTION:
Mapping XS 9b2b8cd4
END DESCRIPTION:
XS GIS Cut Line= 6
      2725132.84      6892590.42      2724665.99      6892482.52
      2724564.14      6892447.24      2724492.27      6892447.29
      2724349.63      6892523.03      2724066.20      6892646.43
#Sta/Elev= 30
  4308.6  437.15  4346.4  436.76  4377.5  435.86  4397.7  436.33  4428.5  436.01
  4500.4  434.85  4520.9  434.09  4553.5  433.84  4664.6  430.67  4695.4  429.32
  4724.5  427.46  4729.6  427.59  4772.3  425.47  4953.7  425.88  5107.5  425.42
  5107.8  424.92  5111.3  424.92  5111.5  425.42  5121.7  425.78  5132.7  425.52
  5137.4  425.84  5143.8  427.02  5160.8  428.41  5184.3  429.41  5189.7  429.21
  5318.3  432.96  5359.2  433.63  5372.9  433.42  5417.0  434.94  5438.1  435.11
#Mann=3,-1,0
  4308.6    0.05       0  5107.5    0.04       0  5111.5    0.05       0
Bank Sta=5107.5,5111.5
Exp/Cntr=0.3,0.1

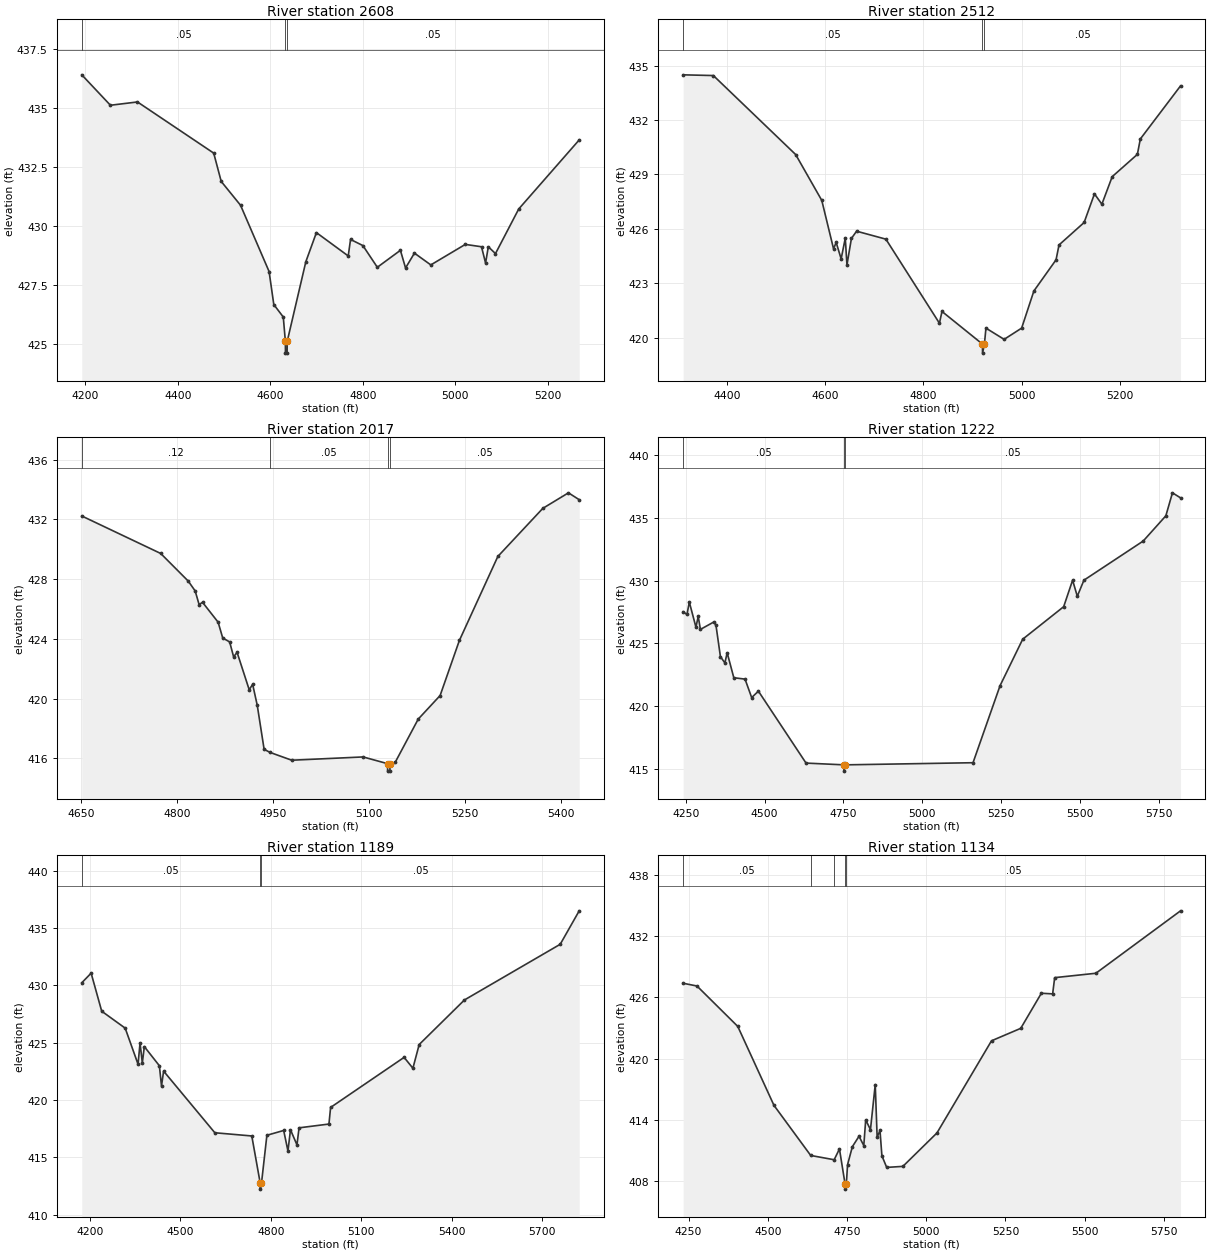
Type RM Length L Ch R = 1,2608,96,96,96
BEGIN DESCRIPTION:
Mapping XS 64f07500
END DESCRIPTION:
XS GIS Cut Line= 6
      2725132.55      6892544.34      2724820.04      6892442.34
      2724663.79      6892405.44      2724540.09      6892392.42
      2724405.54      6892414.12      2724120.04      6892569.87
#Sta/Elev= 30
  4192.5  436.41  4254.4  435.12  4312.9  435.26  4477.7  433.09  4493.9  431.89
  4535.7  430.88  4597.4  428.07  4607.6  426.67  4628.1  426.14  4632.6  425.11
  4632.8  424.61  4636.3  424.61  4636.6  425.11  4676.9  428.49  4699.7  429.72
  4768.5  428.73  4773.5  429.43  4800.2  429.17  4831.4  428.25  4881.3  428.97
  4892.4  428.22  4911.6  428.85  4947.0  428.35  5021.6  429.22  5056.6  429.12
  5065.4  428.43  5071.3  429.12  5086.8  428.83  5137.0  430.72  5267.8  433.65
#Mann=3,-1,0
  4192.5    0.05       0  4632.6    0.04       0  4636.6    0.05       0
Bank Sta=4632.6,4636.6
Exp/Cntr=0.3,0.1

Type RM Length L Ch R = 1,2512,495,495,495
BEGIN DESCRIPTION:
Mapping XS 4157a01c
END DESCRIPTION:
XS GIS Cut Line= 5
      2724982.80      6892433.66      2724674.64      6892305.62
      2724509.71      6892309.96      2724327.42      6892353.36
      2724056.15      6892533.48
#Sta/Elev= 30
  4311.2  434.50  4372.7  434.46  4540.1  430.10  4593.2  427.57  4617.1  424.90
  4622.5  425.25  4632.6  424.34  4641.0  425.49  4644.4  424.01  4653.5  425.47
  4664.0  425.87  4723.6  425.43  4832.5  420.79  4837.7  421.44  4920.0  419.64
  4920.2  419.14  4924.0  419.64  4927.1  420.52  4964.1  419.90  4999.7  420.52
  5024.6  422.57  5069.7  424.29  5075.7  425.11  5126.8  426.35  5147.8  427.93
  5162.9  427.36  5183.9  428.88  5235.1  430.11  5241.1  430.96  5322.9  433.89
#Mann=3,-1,0
  4311.2    0.05       0  4920.0    0.04       0  4924.0    0.05       0
Bank Sta=4920,4924
Exp/Cntr=0.3,0.1

Type RM Length L Ch R = 1,2017,795,795,795
BEGIN DESCRIPTION:
Mapping XS 69481bb8
END DESCRIPTION:
XS GIS Cut Line= 3
      2724850.40      6892184.08      2724529.24      6892056.05
      2724099.24      6892079.82
#Sta/Elev= 30
  4651.4  432.23  4774.6  429.72  4817.6  427.87  4828.4  427.21  4834.5  426.30
  4839.9  426.45  4864.2  425.12  4871.4  424.06  4882.2  423.80  4888.4  422.80
  4893.8  423.10  4912.7  420.60  4918.1  420.96  4925.3  419.55  4936.0  416.61
  4945.4  416.40  4979.1  415.88  5090.5  416.10  5128.6  415.65  5128.8  415.15
  5132.3  415.15  5132.6  415.65  5140.6  415.74  5176.5  418.63  5210.7  420.21
  5240.8  423.90  5300.8  429.52  5371.0  432.74  5411.0  433.78  5427.8  433.32
#Mann=4,-1,0
  4651.4    0.12       0  4945.4    0.05       0  5128.6    0.03       0
  5132.6    0.05       0
Bank Sta=5128.6,5132.6
Exp/Cntr=0.3,0.1

Type RM Length L Ch R = 1,1222,33,33,33
BEGIN DESCRIPTION:
Mapping XS 16cea059
END DESCRIPTION:
XS GIS Cut Line= 6
      2724908.38      6891666.10      2724638.83      6891382.22
      2724499.51      6891311.91      2724414.87      6891331.44
      2724190.91      6891526.75      2723660.35      6891890.87
#Sta/Elev= 30
  4241.3  427.51  4253.6  427.30  4260.9  428.29  4281.9  426.29  4289.2  427.14
  4296.1  426.11  4338.6  426.70  4345.5  426.44  4359.6  423.94  4373.8  423.44
  4381.0  424.25  4402.1  422.26  4437.7  422.15  4458.7  420.68  4480.1  421.19
  4631.2  415.46  4751.5  415.32  4751.8  414.82  4755.5  415.32  5160.9  415.49
  5246.7  421.63  5318.5  425.33  5448.5  427.92  5476.8  430.03  5491.7  428.75
  5512.7  430.03  5700.8  433.15  5772.6  435.16  5793.5  436.99  5819.2  436.59
#Mann=3,-1,0
  4241.3    0.05       0  4751.5    0.04       0  4755.5    0.05       0
Bank Sta=4751.5,4755.5
Exp/Cntr=0.3,0.1

Type RM Length L Ch R = 1,1189,55,55,55
BEGIN DESCRIPTION:
Mapping XS e7ce455a
END DESCRIPTION:
XS GIS Cut Line= 6
      2724939.64      6891620.53      2724593.26      6891287.17
      2724542.48      6891263.73      2724442.22      6891262.43
      2723963.05      6891633.53      2723627.07      6891860.11
#Sta/Elev= 30
  4172.9  430.23  4203.9  431.07  4239.0  427.75  4316.9  426.27  4359.6  423.12
  4366.2  424.98  4373.8  423.23  4380.4  424.66  4430.3  422.99  4437.4  421.22
  4444.4  422.52  4614.4  417.14  4737.0  416.86  4765.1  412.72  4765.4  412.22
  4769.1  412.72  4787.1  416.92  4842.8  417.34  4857.0  415.55  4865.4  417.40
  4886.9  416.08  4893.8  417.57  4993.0  417.90  4998.5  419.35  5242.4  423.72
  5271.6  422.77  5292.4  424.84  5442.6  428.73  5760.4  433.59  5823.4  436.51
#Mann=3,-1,0
  4172.9    0.05       0  4765.1    0.04       0  4769.1    0.05       0
Bank Sta=4765.1,4769.1
Exp/Cntr=0.3,0.1

Type RM Length L Ch R = 1,1134,719,719,719
BEGIN DESCRIPTION:
Mapping XS ffdbcbac
END DESCRIPTION:
XS GIS Cut Line= 5
      2724907.74      6891471.00      2724551.81      6891197.54
      2724484.53      6891195.37      2724278.37      6891332.09
      2723622.99      6891800.84
#Sta/Elev= 30
  4233.0  427.39  4276.7  427.12  4405.4  423.16  4519.6  415.42  4635.5  410.51
  4709.5  410.09  4726.2  411.15  4743.9  407.71  4744.2  407.21  4747.9  407.71
  4751.8  409.61  4766.9  411.37  4787.9  412.39  4803.0  411.48  4809.0  414.00
  4824.0  413.04  4839.1  417.46  4845.1  412.30  4854.1  412.96  4860.1  410.48
  4875.2  409.34  4926.3  409.44  5033.9  412.72  5205.9  421.75  5298.1  422.97
  5363.2  426.41  5398.8  426.35  5405.2  427.94  5535.2  428.37  5802.3  434.49
#Mann=5,-1,0
  4233.0    0.05       0  4635.5    0.12       0  4709.5    0.05       0
  4743.9    0.04       0  4747.9    0.05       0
Bank Sta=4743.9,4747.9
Exp/Cntr=0.3,0.1

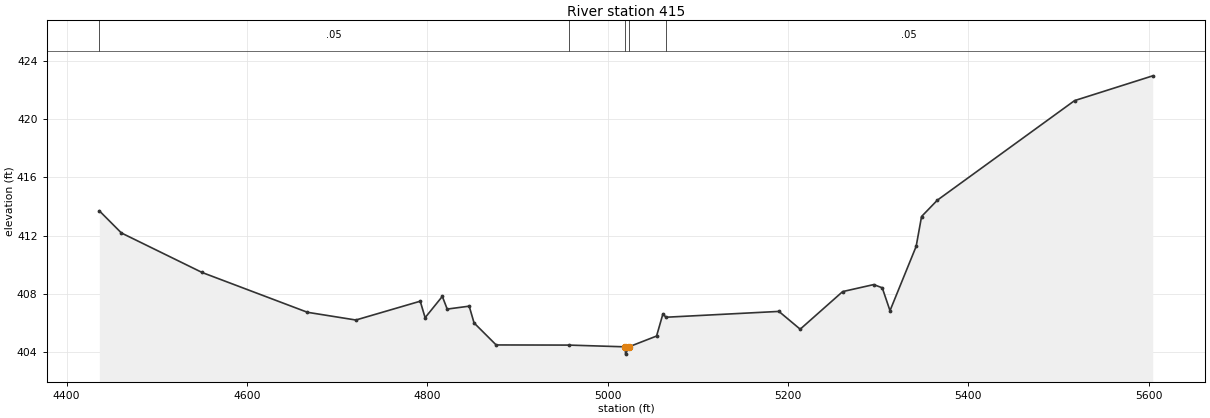
Type RM Length L Ch R = 1,415,0,0,0
BEGIN DESCRIPTION:
CCT8_6 1.0
END DESCRIPTION:
XS GIS Cut Line= 3
      2724750.99      6891036.00      2724225.86      6890831.06
      2723670.43      6891069.87
#Sta/Elev= 30
  4436.3  413.71  4460.8  412.19  4550.3  409.48  4667.1  406.75  4720.8  406.22
  4792.2  407.51  4797.6  406.38  4816.7  407.84  4822.1  406.97  4846.5  407.17
  4851.9  406.02  4876.4  404.51  4957.2  404.50  5019.6  404.38  5019.9  403.88
  5023.6  404.38  5054.3  405.12  5061.4  406.65  5064.6  406.41  5190.0  406.81
  5213.6  405.59  5260.7  408.17  5295.1  408.65  5304.6  408.43  5313.2  406.86
  5342.2  411.27  5348.2  413.32  5365.7  414.44  5517.9  421.27  5604.6  422.97
#Mann=5,-1,0
  4436.3    0.05       0  4957.2    0.12       0  5019.6    0.07       0
  5023.6    0.12       0  5064.6    0.05       0
Bank Sta=5019.6,5023.6
Exp/Cntr=0.3,0.1

Chan Stop Cuts=-1