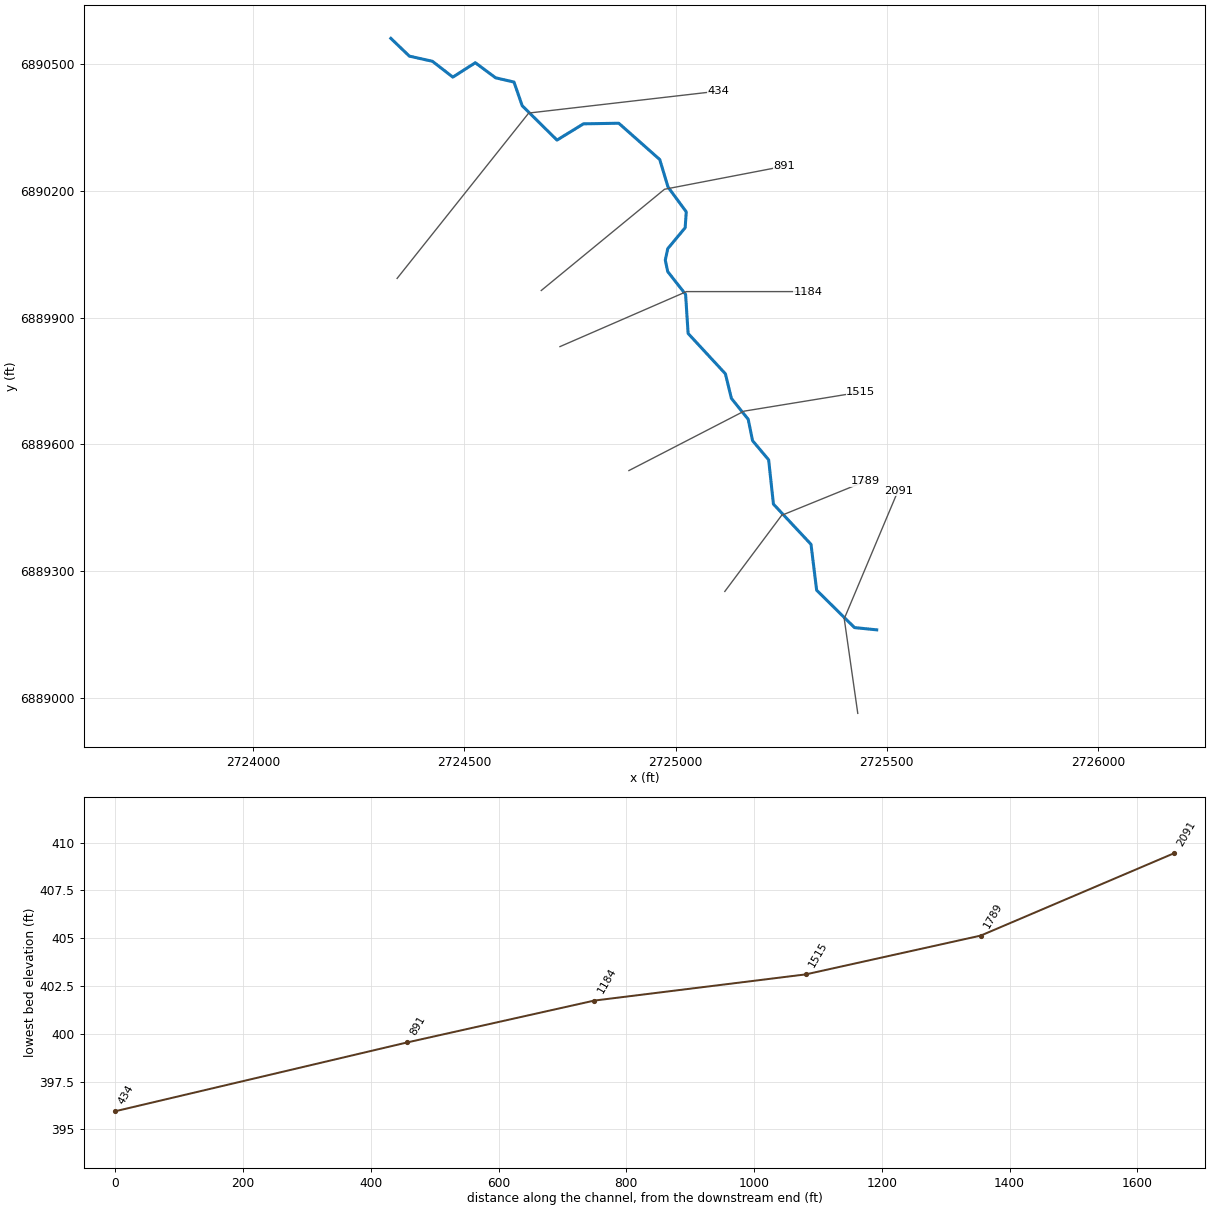
--- CCT8_7.prj (project) ---

Proj Title=CCT8_7 Base Level Engineering
Current Plan=p01
Default Exp/Contr=0.3,0.1
English Units
Geom File=g01
Flow File=f01
Plan File=p01
BEGIN DESCRIPTION:
CCT8_7
END DESCRIPTION:

--- CCT8_7.p01 (plan) ---

Plan Title=Multiple Run
Short Identifier=Multiple
Geom File=g01
Flow File=f01
Subcritical Flow
K Sum by GR= 0
Std Step Tol= 0.01
Critical Tol= 0.01
Num of Std Step Trials= 20
Max Error Tol= 0.3
Flow Tol Ratio= 0.001
Split Flow NTrial= 30
Split Flow Tol= 0.02
Split Flow Ratio= 0.02
Log Output Level= 0
Friction Slope Method= 1
Unsteady Friction Slope Method= 2
Unsteady Bridges Friction Slope Method= 1
Parabolic Critical Depth
Global Vel Dist=  1 , 1 , 1
Global Log Level= 0
CheckData=True
Encroach Param= -1, 0, 0, 0
BEGIN DESCRIPTION:
Multiple Run
END DESCRIPTION:

--- CCT8_7.f01 (steady flow) ---

Flow Title=Multiple
Number of Profiles=7
Profile Names=10-year,25-year,50-year,1pct_min,100-year,1pct_plu,500-year
River Rch & RM= CCT8_7,Reach-1,2091
     509     674     806     479     957    1909    1344
Boundary for River Rch & Prof#=CCT8_7,Reach-1,1
Up Type=0
Dn Type=3
Dn Slope=0.005
Boundary for River Rch & Prof#=CCT8_7,Reach-1,2
Up Type=0
Dn Type=3
Dn Slope=0.005
Boundary for River Rch & Prof#=CCT8_7,Reach-1,3
Up Type=0
Dn Type=3
Dn Slope=0.005
Boundary for River Rch & Prof#=CCT8_7,Reach-1,4
Up Type=0
Dn Type=3
Dn Slope=0.005
Boundary for River Rch & Prof#=CCT8_7,Reach-1,5
Up Type=0
Dn Type=3
Dn Slope=0.005
Boundary for River Rch & Prof#=CCT8_7,Reach-1,6
Up Type=0
Dn Type=3
Dn Slope=0.005
Boundary for River Rch & Prof#=CCT8_7,Reach-1,7
Up Type=0
Dn Type=3
Dn Slope=0.005

--- CCT8_7.g01 (geometry) ---

Geom Title=Existing Conditions

River Reach=CCT8_7,Reach-1
Reach XY= 30
      2725476.00      6889161.00      2725423.46      6889166.30
      2725333.84      6889254.81      2725320.46      6889363.42
      2725231.54      6889458.58      2725220.23      6889563.32
      2725182.12      6889608.82      2725171.84      6889659.28
      2725132.10      6889708.81      2725117.84      6889767.05
      2725029.62      6889862.50      2725023.62      6889955.03
      2724981.37      6890008.82      2724975.61      6890036.00
      2724981.41      6890063.20      2725022.60      6890112.72
      2725025.25      6890150.31      2724982.18      6890208.82
      2724962.39      6890274.24      2724865.52      6890360.06
      2724781.89      6890358.63      2724719.25      6890320.13
      2724636.89      6890401.54      2724617.50      6890457.53
      2724574.04      6890467.54      2724525.94      6890503.25
      2724472.77      6890469.22      2724424.42      6890506.68
      2724369.86      6890518.88      2724326.00      6890561.00

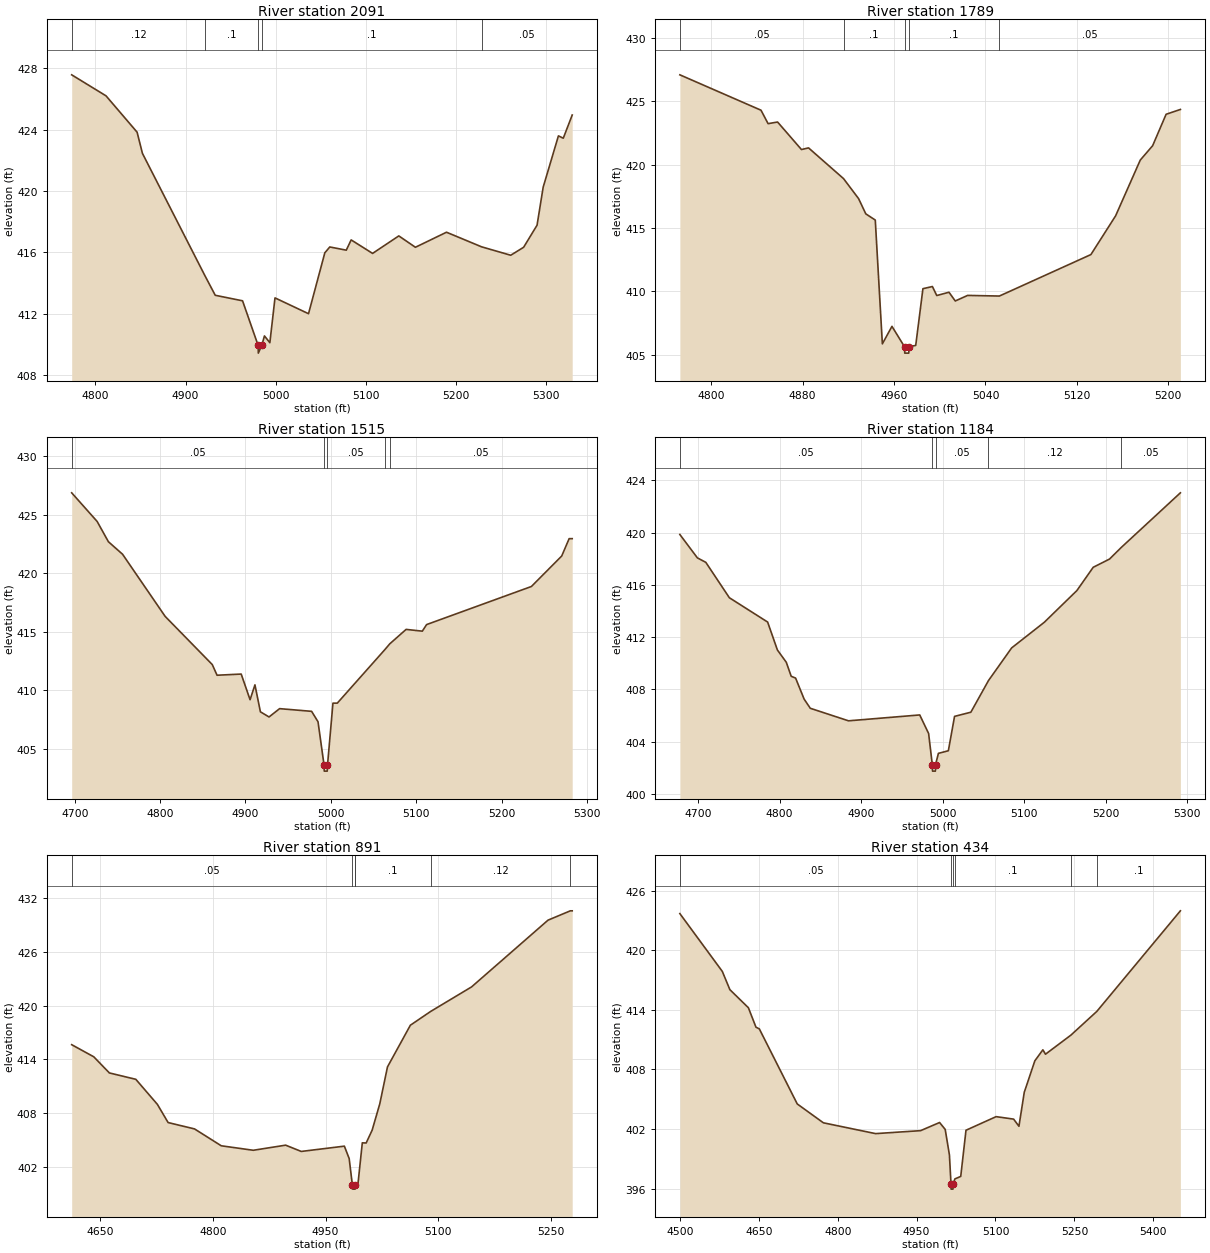
Type RM Length L Ch R = 1,2091,302,302,302
BEGIN DESCRIPTION:
CCT8_7 4.0
END DESCRIPTION:
XS GIS Cut Line= 3
      2725431.17      6888963.30      2725399.12      6889187.32
      2725526.67      6889490.69
#Sta/Elev= 30
  4773.7  427.58  4811.8  426.21  4846.3  423.84  4852.2  422.46  4921.7  414.47
  4933.0  413.21  4963.3  412.85  4980.6  409.94  4980.8  409.44  4984.6  409.94
  4987.6  410.56  4993.6  410.12  4999.3  413.04  5036.5  412.01  5054.6  415.98
  5060.1  416.36  5078.4  416.15  5083.8  416.82  5107.6  415.94  5136.7  417.08
  5155.1  416.34  5189.6  417.32  5228.5  416.37  5260.9  415.82  5275.2  416.34
  5290.1  417.78  5296.9  420.26  5313.8  423.60  5319.2  423.45  5329.1  424.96
#Mann=5,-1,0
  4773.7    0.12       0  4921.7     0.1       0  4980.6    0.07       0
  4984.6     0.1       0  5228.5    0.05       0
Bank Sta=4980.6,4984.6
Exp/Cntr=0.3,0.1

Type RM Length L Ch R = 1,1789,274,274,274
BEGIN DESCRIPTION:
Mapping XS ec35409d
END DESCRIPTION:
XS GIS Cut Line= 3
      2725116.48      6889251.92      2725251.04      6889432.06
      2725448.49      6889512.34
#Sta/Elev= 30
  4772.6  427.08  4843.6  424.29  4849.8  423.23  4858.1  423.36  4879.0  421.19
  4885.2  421.32  4915.8  418.90  4929.0  417.32  4935.3  416.12  4943.6  415.63
  4949.8  405.87  4958.2  407.25  4969.2  405.64  4969.4  405.14  4972.9  405.14
  4973.2  405.64  4979.0  405.75  4985.3  410.22  4993.6  410.39  4997.4  409.68
  5008.1  409.94  5013.6  409.25  5024.4  409.69  5052.2  409.64  5132.3  412.91
  5153.9  415.96  5175.5  420.36  5186.3  421.49  5198.1  423.97  5210.6  424.35
#Mann=5,-1,0
  4772.6    0.05       0  4915.8     0.1       0  4969.2    0.07       0
  4973.2     0.1       0  5052.2    0.05       0
Bank Sta=4969.2,4973.2
Exp/Cntr=0.3,0.1

Type RM Length L Ch R = 1,1515,331,331,331
BEGIN DESCRIPTION:
Mapping XS 11357178
END DESCRIPTION:
XS GIS Cut Line= 3
      2724889.49      6889537.96      2725162.07      6889678.59
      2725438.09      6889723.72
#Sta/Elev= 30
  4696.4  426.85  4726.2  424.41  4739.4  422.68  4756.0  421.61  4805.9  416.31
  4861.1  412.20  4866.7  411.29  4895.0  411.39  4905.4  409.20  4911.1  410.47
  4917.5  408.17  4927.6  407.73  4940.0  408.44  4977.5  408.21  4985.0  407.32
  4992.1  403.61  4992.3  403.11  4995.8  403.11  4996.1  403.61  5002.5  408.91
  5007.6  408.91  5063.0  413.45  5069.1  413.97  5088.2  415.20  5107.2  415.05
  5112.2  415.61  5235.0  418.86  5270.5  421.46  5279.2  422.94  5282.8  422.94
#Mann=5,-1,0
  4696.4    0.05       0  4992.1    0.04       0  4996.1    0.05       0
  5063.0    0.12       0  5069.1    0.05       0
Bank Sta=4992.1,4996.1
Exp/Cntr=0.3,0.1

Type RM Length L Ch R = 1,1184,293,293,293
BEGIN DESCRIPTION:
Mapping XS c2f68dd6
END DESCRIPTION:
XS GIS Cut Line= 3
      2724726.31      6889831.37      2725025.78      6889961.57
      2725312.92      6889961.57
#Sta/Elev= 30
  4677.7  419.85  4699.2  418.06  4709.5  417.72  4738.4  415.01  4785.3  413.15
  4797.3  411.01  4808.2  410.07  4814.2  409.00  4819.6  408.86  4830.0  407.26
  4837.6  406.55  4884.5  405.59  4971.8  406.04  4982.7  404.62  4987.2  402.24
  4987.5  401.74  4991.0  401.74  4991.2  402.24  4994.7  403.10  5006.9  403.30
  5014.5  405.93  5034.5  406.25  5056.1  408.67  5084.5  411.17  5124.5  413.13
  5164.5  415.56  5184.5  417.34  5204.5  417.97  5219.1  418.87  5291.4  423.04
#Mann=5,-1,0
  4677.7    0.05       0  4987.2   0.035       0  4991.2    0.05       0
  5056.1    0.12       0  5219.1    0.05       0
Bank Sta=4987.2,4991.2
Exp/Cntr=0.3,0.1

Type RM Length L Ch R = 1,891,457,457,457
BEGIN DESCRIPTION:
Mapping XS b479df2c
END DESCRIPTION:
XS GIS Cut Line= 3
      2724682.07      6889964.21      2724973.70      6890203.76
      2725257.57      6890258.45
#Sta/Elev= 30
  4612.0  415.65  4641.4  414.30  4662.2  412.50  4697.4  411.79  4726.1  409.00
  4740.4  406.97  4775.6  406.26  4811.2  404.38  4853.8  403.88  4896.9  404.45
  4917.7  403.75  4975.1  404.34  4981.5  402.96  4985.7  400.05  4985.9  399.55
  4989.4  399.55  4989.7  400.05  4989.8  400.05  4993.1  400.05  4999.0  404.71
  5004.1  404.69  5012.1  406.12  5022.3  409.07  5032.5  413.17  5063.0  417.82
  5090.1  419.36  5144.5  422.09  5246.3  429.53  5276.0  430.57  5278.5  430.57
#Mann=6,-1,0
  4612.0    0.05       0  4985.7    0.07       0  4989.7    0.05       0
  4989.8     0.1       0  5090.1    0.12       0  5276.0    0.05       0
Bank Sta=4985.7,4989.7
Exp/Cntr=0.3,0.1

Type RM Length L Ch R = 1,434,0,0,0
BEGIN DESCRIPTION:
CCT8_7 1.0
END DESCRIPTION:
XS GIS Cut Line= 3
      2724340.86      6889992.79      2724652.34      6890384.16
      2725100.96      6890436.00
#Sta/Elev= 30
  4499.8  423.70  4580.5  417.88  4594.9  416.04  4630.1  414.22  4644.5  412.26
  4650.9  412.09  4723.0  404.53  4772.7  402.63  4872.0  401.54  4957.6  401.84
  4993.7  402.66  5004.4  401.96  5012.4  399.39  5015.4  396.45  5015.6  395.95
  5019.1  395.95  5019.4  396.45  5022.8  396.98  5033.9  397.23  5043.9  401.88
  5101.2  403.25  5134.5  403.00  5144.6  402.28  5154.7  405.70  5174.8  408.87
  5190.1  409.98  5195.1  409.54  5243.4  411.46  5292.7  413.85  5451.6  423.98
#Mann=6,-1,0
  4499.8    0.05       0  5015.4   0.035       0  5019.4    0.05       0
  5022.8     0.1       0  5243.4    0.12       0  5292.7     0.1       0
Bank Sta=5015.4,5019.4
Exp/Cntr=0.3,0.1

Chan Stop Cuts=-1