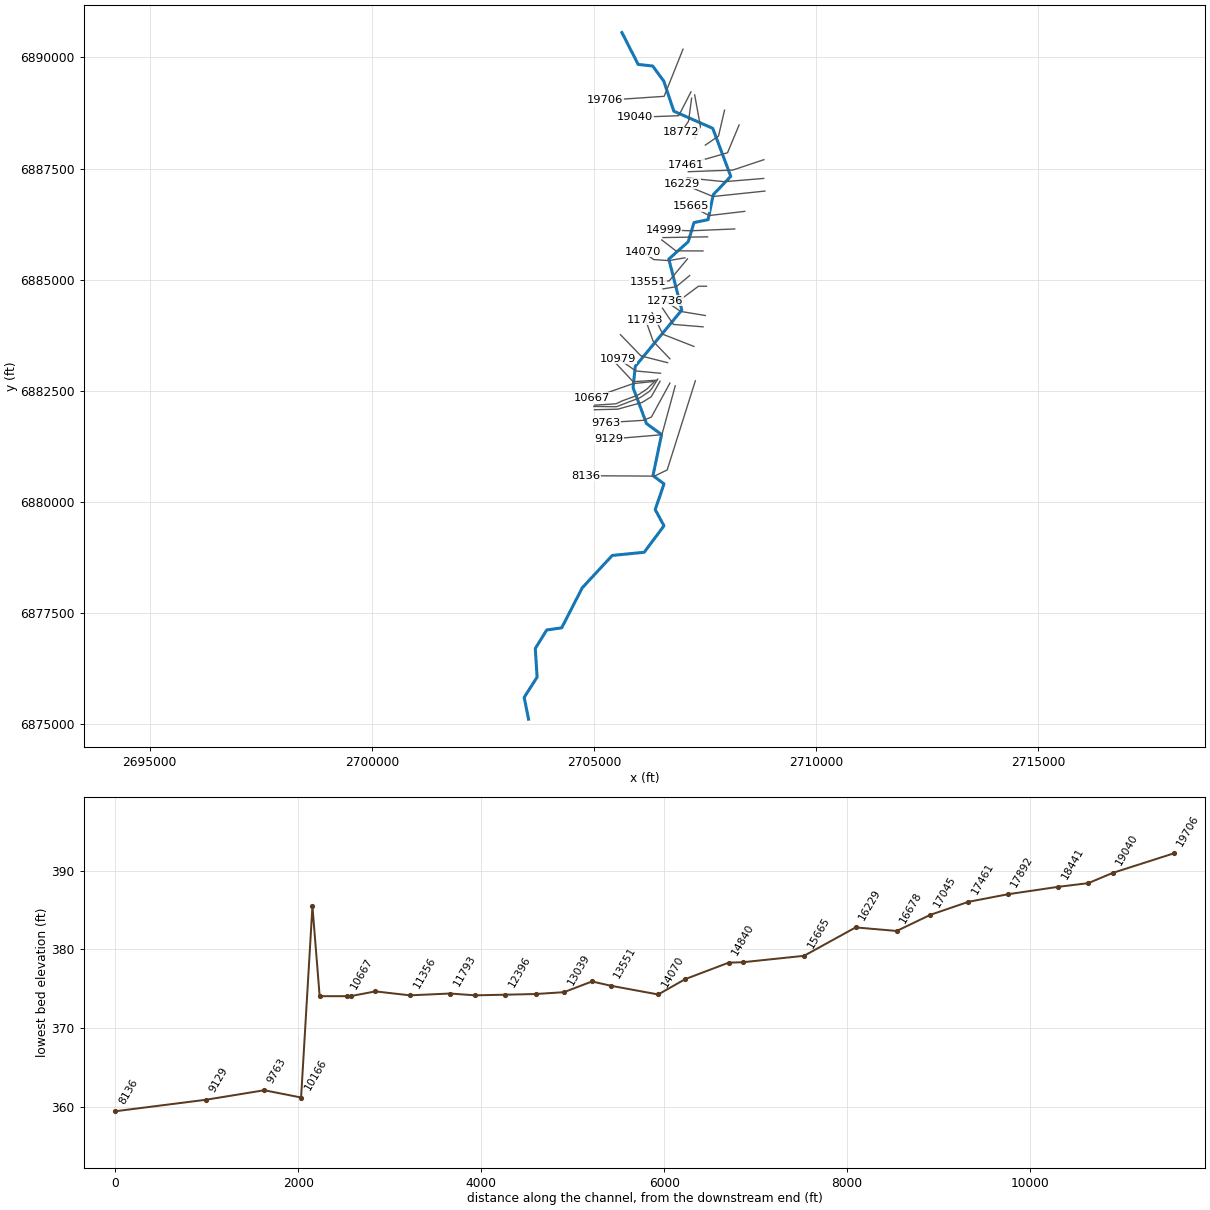
--- CCT9.prj (project) ---

Proj Title=CCT9 Base Level Engineering
Current Plan=p01
Default Exp/Contr=0.3,0.1
English Units
Geom File=g01
Flow File=f01
Plan File=p01
Y Axis Title=Elevation
X Axis Title(PF)=Main Channel Distance
X Axis Title(XS)=Station
BEGIN DESCRIPTION:
CCT9
END DESCRIPTION:
DSS Export Rating Curves= 0
DSS Export Rating Curve Sorted= 0
DSS Export Volume Flow Curves= 0
DXF OffsetX= 0
DXF OffsetY= 0
DXF ScaleX= 1
DXF ScaleY= 10

--- CCT9.p01 (plan) ---

Plan Title=Multiple Run
Short Identifier=Multiple
Geom File=g01
Flow File=f01
Subcritical Flow
K Sum by GR= 0
Std Step Tol= 0.01
Critical Tol= 0.01
Num of Std Step Trials= 20
Max Error Tol= 0.3
Flow Tol Ratio= 0.001
Split Flow NTrial= 30
Split Flow Tol= 0.02
Split Flow Ratio= 0.02
Log Output Level= 0
Friction Slope Method= 1
Unsteady Friction Slope Method= 2
Unsteady Bridges Friction Slope Method= 1
Parabolic Critical Depth
Global Vel Dist=  1 , 1 , 1
Global Log Level= 0
CheckData=True
Encroach Param= -1, 0, 0, 0
BEGIN DESCRIPTION:
Multiple Run
END DESCRIPTION:

--- CCT9.f01 (steady flow) ---

Flow Title=Multiple
Program Version=4.10
Number of Profiles= 7
Profile Names=10-year,25-year,50-year,1pct_min,100-year,1pct_plu,500-year
River Rch & RM=CCT9,Reach-1         ,19706
     553     726     862     508    1013    2020    1396
River Rch & RM=CCT9,Reach-1         ,17045
     892    1201    1450     866    1728    3447    2454
River Rch & RM=CCT9,Reach-1         ,14999
     996    1346    1630     975    1945    3881    2773
River Rch & RM=CCT9,Reach-1         ,11356
    1006    1359    1644     983    1962    3914    2793
River Rch & RM=CCT9,Reach-1         ,10667
    1084    1470    1783    1069    2132    4254    3050
River Rch & RM=CCT9,Reach-1         ,10166
    1148    1565    1905    1146    2286    4562    3295
Boundary for River Rch & Prof#=CCT9,Reach-1         , 1
Up Type= 0
Dn Type= 3
Dn Slope=0.005
Boundary for River Rch & Prof#=CCT9,Reach-1         , 2
Up Type= 0
Dn Type= 3
Dn Slope=0.005
Boundary for River Rch & Prof#=CCT9,Reach-1         , 3
Up Type= 0
Dn Type= 3
Dn Slope=0.005
Boundary for River Rch & Prof#=CCT9,Reach-1         , 4
Up Type= 0
Dn Type= 3
Dn Slope=0.005
Boundary for River Rch & Prof#=CCT9,Reach-1         , 5
Up Type= 0
Dn Type= 3
Dn Slope=0.005
Boundary for River Rch & Prof#=CCT9,Reach-1         , 6
Up Type= 0
Dn Type= 3
Dn Slope=0.005
Boundary for River Rch & Prof#=CCT9,Reach-1         , 7
Up Type= 0
Dn Type= 3
Dn Slope=0.005
DSS Import GetInterval= 0
DSS Import GetPeak= 0
DSS Import FillOption= 0

--- CCT9.g01 (geometry) ---

Geom Title=Existing Conditions
Program Version=4.10

River Reach=CCT9            ,Reach-1
Reach XY= 30
        2705626.        6890561.      2705992.49      6889843.78
      2706317.68      6889807.85      2706568.63      6889467.34
       2706795.6      6888790.83      2707670.38      6888405.44
      2708075.68      6887326.02      2707681.46      6886913.46
      2707565.64      6886350.84      2707248.67      6886285.01
      2707118.27       6885854.5      2706681.48      6885463.45
      2706973.76      6884316.93      2705927.22       6883050.5
      2705877.04      6882571.44      2706179.16      6881762.65
      2706518.33      6881514.73       2706325.3      6880590.85
      2706574.03      6880405.33      2706375.37      6879826.55
      2706572.66      6879462.73       2706128.7      6878866.36
      2705408.87      6878794.75      2704734.16      6878067.05
        2704271.        6877166.        2703934.      6877117.39
      2703676.99      6876700.72      2703718.01      6876057.66
      2703426.65      6875600.36        2703526.        6875111.

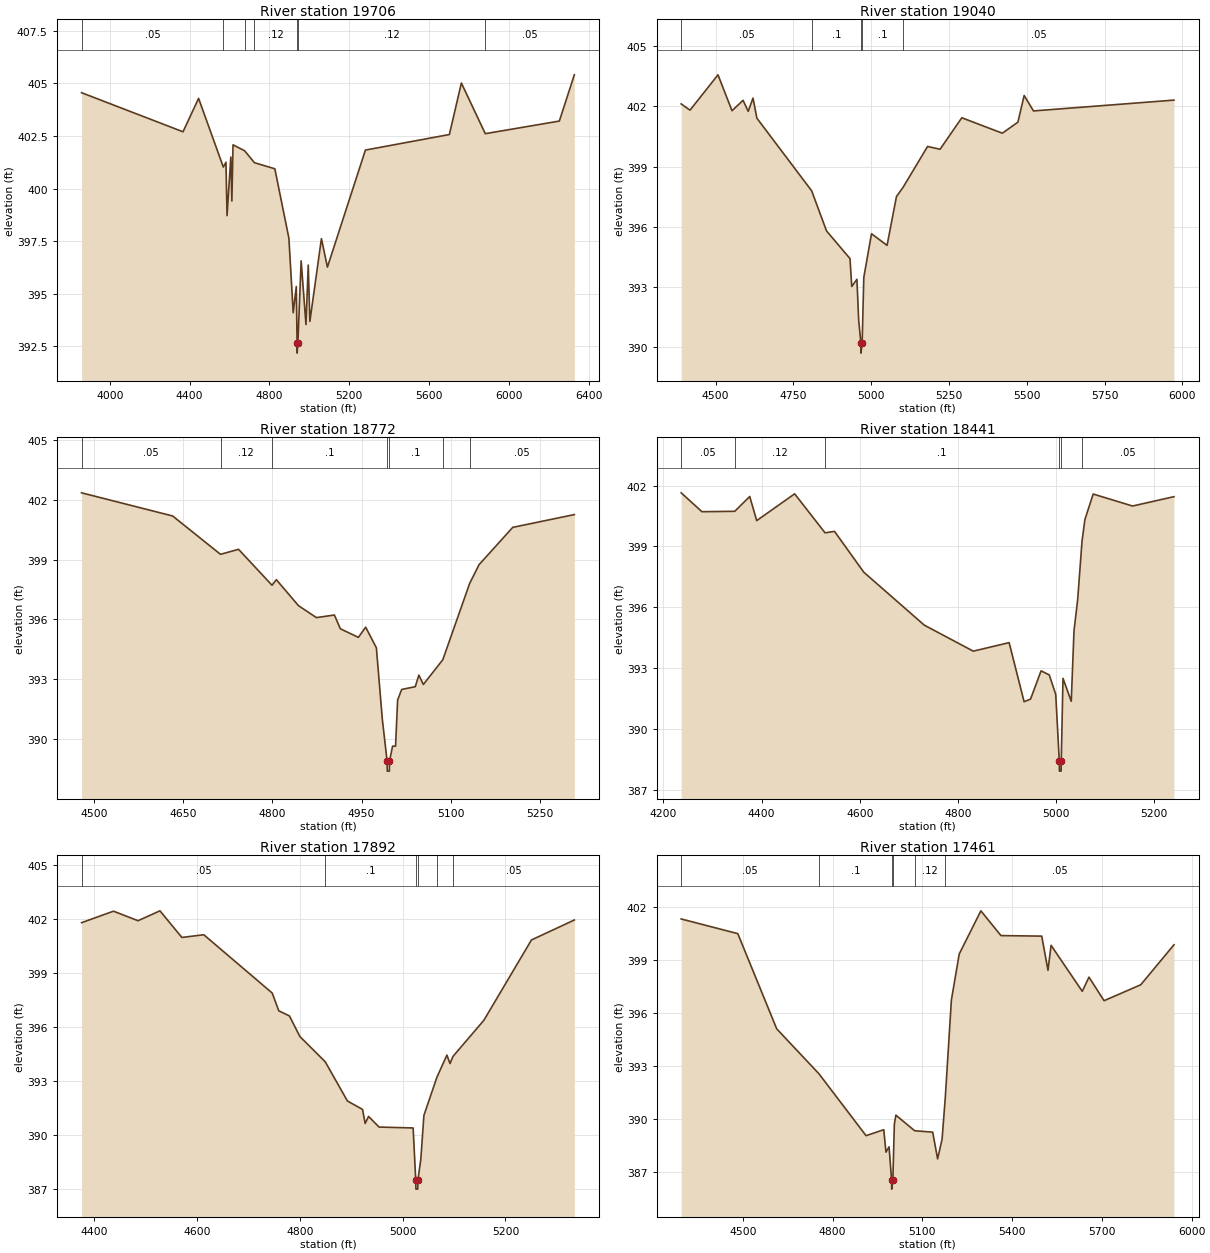
Type RM Length L Ch R = 1 ,19706   ,666,666,666
BEGIN DESCRIPTION:
CCT9 31.0
END DESCRIPTION:
XS GIS Cut Line= 3
      2707001.01      6890186.01      2706576.52      6889125.94
      2705250.97        6889036.
#Sta/Elev= 30
  3858.1  404.56  4366.8   402.7  4444.9  404.29  4568.9  401.02  4582.1  401.25
  4587.5  398.71  4606.4   401.5  4611.7  399.41  4617.5  402.08  4675.4   401.8
  4724.9  401.23  4827.1  400.94  4897.6  397.64  4919.2  394.09  4934.7  395.34
  4938.7  392.67  4938.9  392.17  4942.7  392.67    4959  396.56  4983.2  393.53
  4994.6  396.36  5002.8  393.68  5060.7  397.62  5090.7  396.26  5281.2  401.83
  5702.1  402.57  5762.3  405.02  5882.2  402.61  6253.4  403.21  6328.6  405.41
#Mann= 7 ,-1 , 0
  3858.1     .05       0  4568.9     .12       0  4675.4      .1       0
  4724.9     .12       0  4938.7     .07       0  4942.7     .12       0
  5882.2     .05       0
Bank Sta=4938.7,4942.7
XS Rating Curve= 0 ,0
Exp/Cntr=0.3,0.1

Type RM Length L Ch R = 1 ,19040   ,268,268,268
BEGIN DESCRIPTION:
Mapping XS a37c1517
END DESCRIPTION:
XS GIS Cut Line= 3
      2707180.23      6889226.23      2706904.17      6888689.75
      2705924.99      6888653.29
#Sta/Elev= 30
  4389.5  402.12  4417.9  401.81  4507.8  403.57  4552.8  401.78  4588.3   402.3
  4604.9  401.75  4620.3  402.41  4632.7  401.41  4808.7  397.79  4856.5  395.79
  4931.9  394.41  4937.5  393.02  4954.1  393.38  4959.7  391.36  4966.9   390.2
  4967.2   389.7  4970.9   390.2  4976.2  393.47    5001  395.65    5051  395.07
  5081.1   397.5  5102.7  397.97  5181.1     400  5221.2  399.86  5291.2  401.43
  5421.3  400.66  5471.3  401.21  5491.4  402.54  5521.4  401.77  5972.7  402.31
#Mann= 5 ,-1 , 0
  4389.5     .05       0  4808.7      .1       0  4966.9     .07       0
  4970.9      .1       0  5102.7     .05       0
Bank Sta=4966.9,4970.9
XS Rating Curve= 0 ,0
Exp/Cntr=0.3,0.1

Type RM Length L Ch R = 1 ,18772   ,331,331,331
BEGIN DESCRIPTION:
Mapping XS 92faacc2
END DESCRIPTION:
XS GIS Cut Line= 3
      2707194.55        6889083.      2707124.29      6888561.85
      2706951.05        6888312.
#Sta/Elev= 30
  4478.5  402.34  4631.9  401.18  4712.5  399.26  4742.9  399.51  4799.3  397.71
  4806.5  397.99  4843.8  396.69    4874  396.09  4904.3  396.22  4914.4  395.53
  4944.7   395.1    4957  395.61    4975  394.58    4985  391.01  4993.1   388.9
  4993.4   388.4  4996.9   388.4  4997.1   388.9  5002.3  389.65  5007.3  389.65
  5010.8  391.96  5017.6  392.49  5040.5  392.63  5046.6  393.21  5054.1  392.74
  5086.9  393.98  5132.1   397.8  5147.9  398.74  5204.7  400.61  5308.4  401.25
#Mann= 7 ,-1 , 0
  4478.5     .05       0  4712.5     .12       0  4799.3      .1       0
  4993.1     .07       0  4997.1      .1       0  5086.9     .12       0
  5132.1     .05       0
Bank Sta=4993.1,4997.1
XS Rating Curve= 0 ,0
Exp/Cntr=0.3,0.1

Type RM Length L Ch R = 1 ,18441   ,549,549,549
BEGIN DESCRIPTION:
Mapping XS a160528c
END DESCRIPTION:
XS GIS Cut Line= 3
      2707263.55      6889158.46      2707393.76      6888444.96
      2707269.02      6888195.49
#Sta/Elev= 30
  4236.1  401.64  4278.4  400.71  4345.3  400.73  4375.8  401.46    4390  400.27
  4467.3  401.59  4529.3  399.67  4548.6  399.74  4608.2  397.73  4731.6  395.12
  4831.4  393.84  4904.4  394.26  4934.9  391.35  4948.1  391.48  4969.5  392.87
  4986.2  392.67  4999.4  391.71  5006.6  388.43  5006.9  387.93  5010.4  387.93
  5010.6  388.43  5014.2   392.5    5031  391.37  5036.6  394.84  5044.1  396.38
    5053  399.27  5058.9  400.33  5075.7  401.58  5155.9  400.99  5240.3  401.45
#Mann= 6 ,-1 , 0
  4236.1     .05       0  4345.3     .12       0  4529.3      .1       0
  5006.6     .07       0  5010.6      .1       0    5053     .05       0
Bank Sta=5006.6,5010.6
XS Rating Curve= 0 ,0
Exp/Cntr=0.3,0.1

Type RM Length L Ch R = 1 ,17892   ,431,431,431
BEGIN DESCRIPTION:
Mapping XS 860ffe8f
END DESCRIPTION:
XS GIS Cut Line= 3
      2707935.43       6888814.8      2707800.01      6888231.41
      2707503.14      6888028.29
#Sta/Elev= 30
  4375.4   401.8  4437.5  402.44  4485.3  401.91  4527.9  402.46  4570.6  400.98
  4613.2  401.13  4746.3  397.89  4759.1   396.9  4779.7  396.62  4800.2  395.47
  4849.4  394.07  4892.6  391.89    4922  391.42  4927.1  390.64  4933.7  391.03
  4954.2  390.44  5020.4  390.39  5025.5  387.49  5025.8  386.99  5029.4  386.99
  5029.7  387.49  5035.3  388.63  5041.4  391.09  5066.7  393.21  5086.1  394.44
  5092.2  393.97    5098  394.37  5157.9  396.37  5250.6  400.84    5334  401.95
#Mann= 6 ,-1 , 0
  4375.4     .05       0  4849.4      .1       0  5025.5     .07       0
  5029.7      .1       0  5066.7     .12       0    5098     .05       0
Bank Sta=5025.5,5029.7
XS Rating Curve= 0 ,0
Exp/Cntr=0.3,0.1

Type RM Length L Ch R = 1 ,17461   ,416,416,416
BEGIN DESCRIPTION:
Mapping XS b7bd4282
END DESCRIPTION:
XS GIS Cut Line= 3
      2708263.55      6888481.43      2708003.13      6887856.41
      2707071.64      6887585.81
#Sta/Elev= 30
  4293.8   401.3  4483.1  400.47  4613.1  395.09  4754.3  392.55  4911.8  389.05
  4970.9  389.39  4978.3  388.12  4988.7  388.42  4997.1  386.53  4997.4  386.03
  5001.3  386.53  5006.3   389.7  5011.5  390.21  5074.2  389.33  5134.5  389.25
  5150.9  387.74  5165.8  388.85  5176.6  391.21    5197  396.72  5223.2  399.32
  5295.5  401.76  5362.6  400.36    5499  400.33  5519.8   398.4  5530.2  399.81
  5634.4  397.21  5656.9  398.01  5707.3  396.68  5829.9  397.58  5940.9  399.84
#Mann= 6 ,-1 , 0
  4293.8     .05       0  4754.3      .1       0  4997.1     .07       0
  5001.3      .1       0  5074.2     .12       0  5176.6     .05       0
Bank Sta=4997.1,5001.3
XS Rating Curve= 0 ,0
Exp/Cntr=0.3,0.1

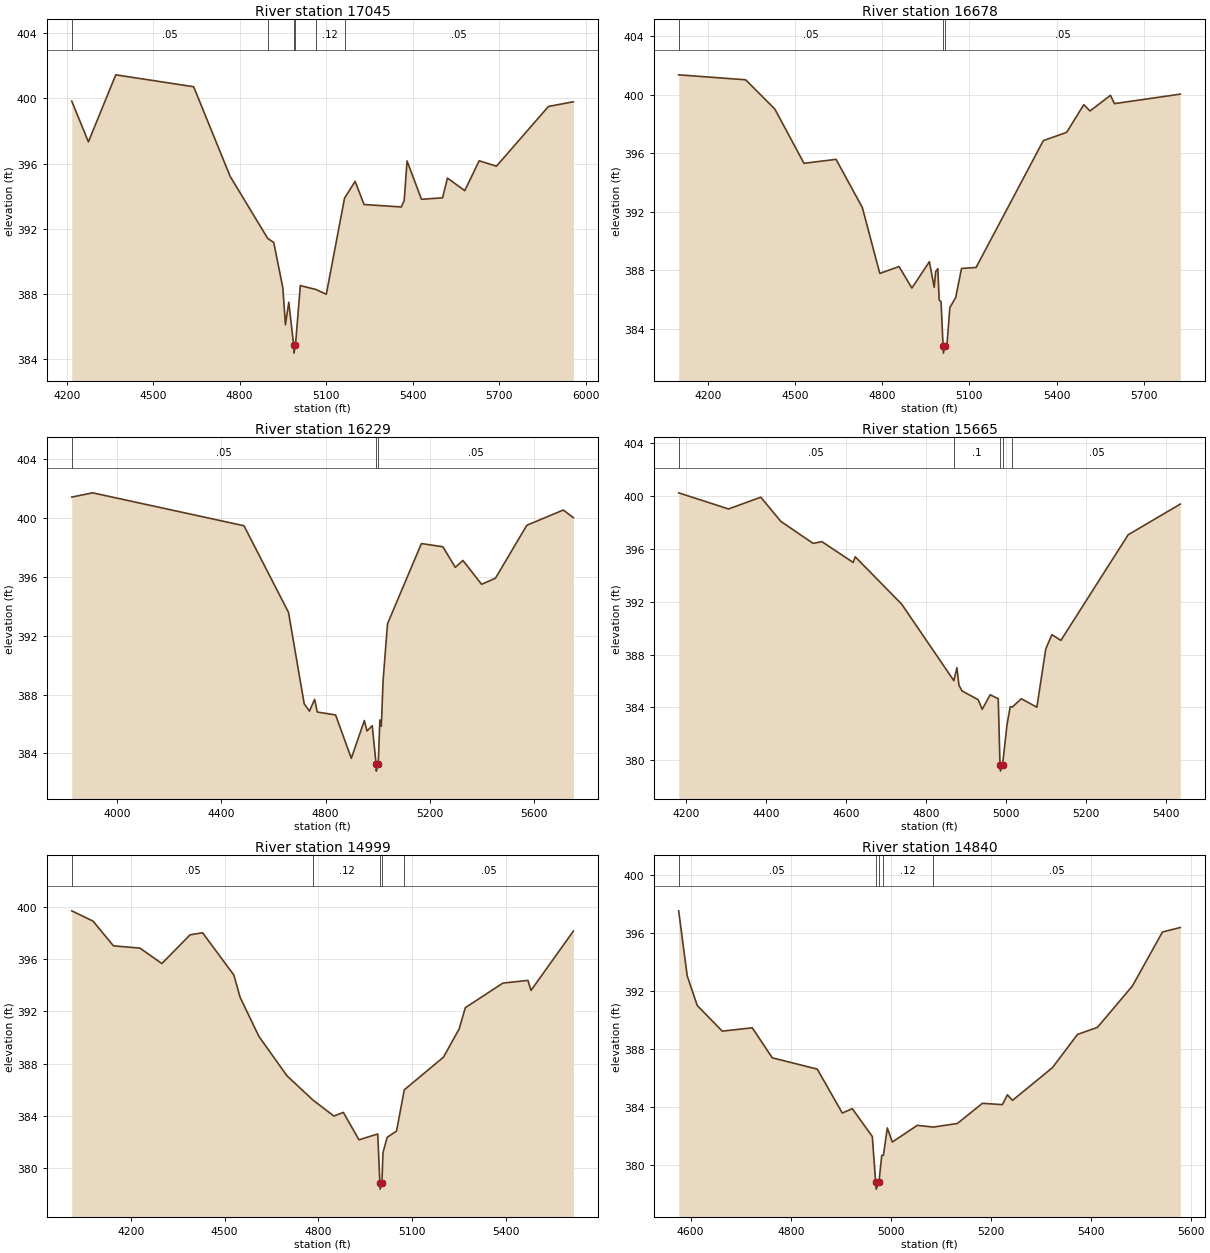
Type RM Length L Ch R = 1 ,17045   ,367,367,367
BEGIN DESCRIPTION:
Mapping XS 95fe9ecd
END DESCRIPTION:
XS GIS Cut Line= 3
      2708820.85      6887700.17      2708117.71      6887465.79
      2707119.35      6887429.39
#Sta/Elev= 30
  4217.5  399.83  4275.3  397.33  4370.2  401.44  4640.4  400.71  4766.9  395.22
  4897.4  391.41  4918.3  391.16  4949.9  388.37  4958.7  386.12  4970.4   387.5
  4987.3  384.88  4988.3  384.38  4993.6  384.88  5010.4  388.52  5064.8  388.28
  5100.5  387.99  5163.8  393.88  5200.5  394.91  5231.5  393.49  5360.7  393.34
  5370.7  393.74  5380.7  396.16  5430.7  393.81  5503.8   393.9  5520.8  395.11
  5580.8  394.34  5630.8  396.17  5690.9  395.84    5871   399.5  5957.7  399.79
#Mann= 6 ,-1 , 0
  4217.5     .05       0  4897.4      .1       0  4987.3     .07       0
  4993.6      .1       0  5064.8     .12       0  5163.8     .05       0
Bank Sta=4987.3,4993.6
XS Rating Curve= 0 ,0
Exp/Cntr=0.3,0.1

Type RM Length L Ch R = 1 ,16678   ,449,449,449
BEGIN DESCRIPTION:
Mapping XS abf62b3f
END DESCRIPTION:
XS GIS Cut Line= 3
      2708815.67      6887278.29      2707930.21      6887205.37
      2707096.93       6887288.7
#Sta/Elev= 30
  4099.7  401.37  4330.2  401.03  4430.5  399.03  4530.8  395.32  4641.2  395.59
  4731.5   392.3  4791.7  387.79  4857.8  388.26  4902.1  386.79  4962.3  388.59
  4978.9  386.84  4983.9  387.91  4991.3  388.12  4995.9  385.98  5002.4  385.84
  5009.3  382.84  5010.4  382.34  5015.6  382.84  5022.5  382.85  5032.6  385.45
  5052.7  386.14  5072.8  388.13    5123   388.2  5354.2  396.87  5434.6  397.44
  5493.4  399.33    5515   398.9  5585.3  399.97  5598.9   399.4  5825.6  400.05
#Mann= 3 ,-1 , 0
  4099.7     .05       0  5009.3     .04       0  5015.6     .05       0
Bank Sta=5009.3,5015.6
XS Rating Curve= 0 ,0
Exp/Cntr=0.3,0.1

Type RM Length L Ch R = 1 ,16229   ,564,564,564
BEGIN DESCRIPTION:
Mapping XS 678283b9
END DESCRIPTION:
XS GIS Cut Line= 3
       2708844.1      6886994.08      2707675.55      6886871.19
      2706980.65      6887159.15
#Sta/Elev= 30
    3825  401.43  3905.4  401.72  4486.7  399.48  4657.7  393.59    4718  387.37
  4738.1  386.87    4758  387.67  4768.3  386.81  4838.7  386.61    4899  383.66
  4949.1  386.23  4959.3  385.52  4979.4  385.88  4994.1  383.29  4995.1  382.79
  5000.5  383.29  5002.5  383.29  5008.7  386.27  5014.2  385.84  5021.2  388.97
    5038  392.81  5168.3  398.27  5250.8  398.05  5298.5  396.65  5327.8  397.12
  5399.5   395.5  5452.7  395.91  5573.2  399.51  5713.2  400.55  5752.2  400.03
#Mann= 3 ,-1 , 0
    3825     .05       0  4994.1     .04       0  5000.5     .05       0
Bank Sta=4994.1,5000.5
XS Rating Curve= 0 ,0
Exp/Cntr=0.3,0.1

Type RM Length L Ch R = 1 ,15665   ,666,666,666
BEGIN DESCRIPTION:
Mapping XS 80a0eb78
END DESCRIPTION:
XS GIS Cut Line= 3
      2708389.88      6886537.41      2707591.24      6886443.65
      2707189.72      6886647.88
#Sta/Elev= 30
  4180.5  400.22  4305.2     399  4385.8  399.89  4436.1  398.06  4516.7   396.4
  4538.8  396.53  4616.9  394.96  4621.9  395.39  4738.2  391.81  4868.6  386.03
  4876.4     387  4881.5  385.68  4889.2  385.25  4929.5  384.59  4939.6  383.86
  4959.6  384.96  4979.7  384.66  4984.1  379.69  4985.1  379.19  4990.6  379.69
  5001.7  382.71  5009.6  384.05  5015.2  384.04  5037.5  384.66  5076.3  384.02
  5098.6  388.43  5113.9   389.5  5136.4  389.07  5304.6  397.05  5435.1  399.37
#Mann= 5 ,-1 , 0
  4180.5     .05       0  4868.6      .1       0  4984.1     .07       0
  4990.6      .1       0  5015.2     .05       0
Bank Sta=4984.1,4990.6
XS Rating Curve= 0 ,0
Exp/Cntr=0.3,0.1

Type RM Length L Ch R = 1 ,14999   ,159,159,159
BEGIN DESCRIPTION:
Mapping XS 56dc8fe2
END DESCRIPTION:
XS GIS Cut Line= 3
      2708164.19      6886141.57      2707167.63       6886099.9
      2706560.54      6886124.19
#Sta/Elev= 30
  4010.7  399.71  4078.9  398.92    4144  397.03  4229.1  396.85  4299.1  395.67
  4389.2  397.87  4429.3  398.03  4529.3  394.79  4549.4  393.08  4609.4  390.09
  4699.5  387.06  4783.3  385.19  4849.6  383.98  4879.6  384.26  4929.7  382.16
  4989.7  382.61  4996.5  378.88  4997.5  378.38  5003.1  378.88  5006.4  381.17
  5019.8  382.35  5049.8  382.83  5074.6  385.99  5199.9  388.49    5250  390.65
    5270  392.29  5390.1  394.17  5470.1  394.38  5480.1  393.61  5615.7  398.16
#Mann= 5 ,-1 , 0
  4010.7     .05       0  4783.3     .12       0  4996.5     .07       0
  5003.1     .12       0  5074.6     .05       0
Bank Sta=4996.5,5003.1
XS Rating Curve= 0 ,0
Exp/Cntr=0.3,0.1

Type RM Length L Ch R = 1 ,14840   ,473,473,473
BEGIN DESCRIPTION:
Mapping XS cd6da0fd
END DESCRIPTION:
XS GIS Cut Line= 3
      2707553.08      6885964.49      2707143.32      6885957.54
      2706550.33      6885947.14
#Sta/Elev= 30
    4576  397.52  4593.1  393.03  4613.1  390.99  4663.1  389.22  4723.1  389.45
  4763.1  387.38  4853.1   386.6  4903.1  383.57  4923.1  383.87  4963.1  381.95
  4969.8  378.82  4970.9  378.32  4976.4  378.82    4982  380.65  4985.3  380.65
  4993.1  382.54  5003.1  381.57  5053.1  382.72  5085.1   382.6  5133.2  382.85
  5183.2  384.24  5223.2  384.15  5233.2  384.83  5243.2  384.44  5323.2   386.7
  5373.2  388.99  5413.2  389.48  5483.2  392.34  5543.2  396.06  5578.9  396.37
#Mann= 5 ,-1 , 0
    4576     .05       0  4969.8     .07       0  4976.4     .05       0
  4985.3     .12       0  5085.1     .05       0
Bank Sta=4969.8,4976.4
XS Rating Curve= 0 ,0
Exp/Cntr=0.3,0.1

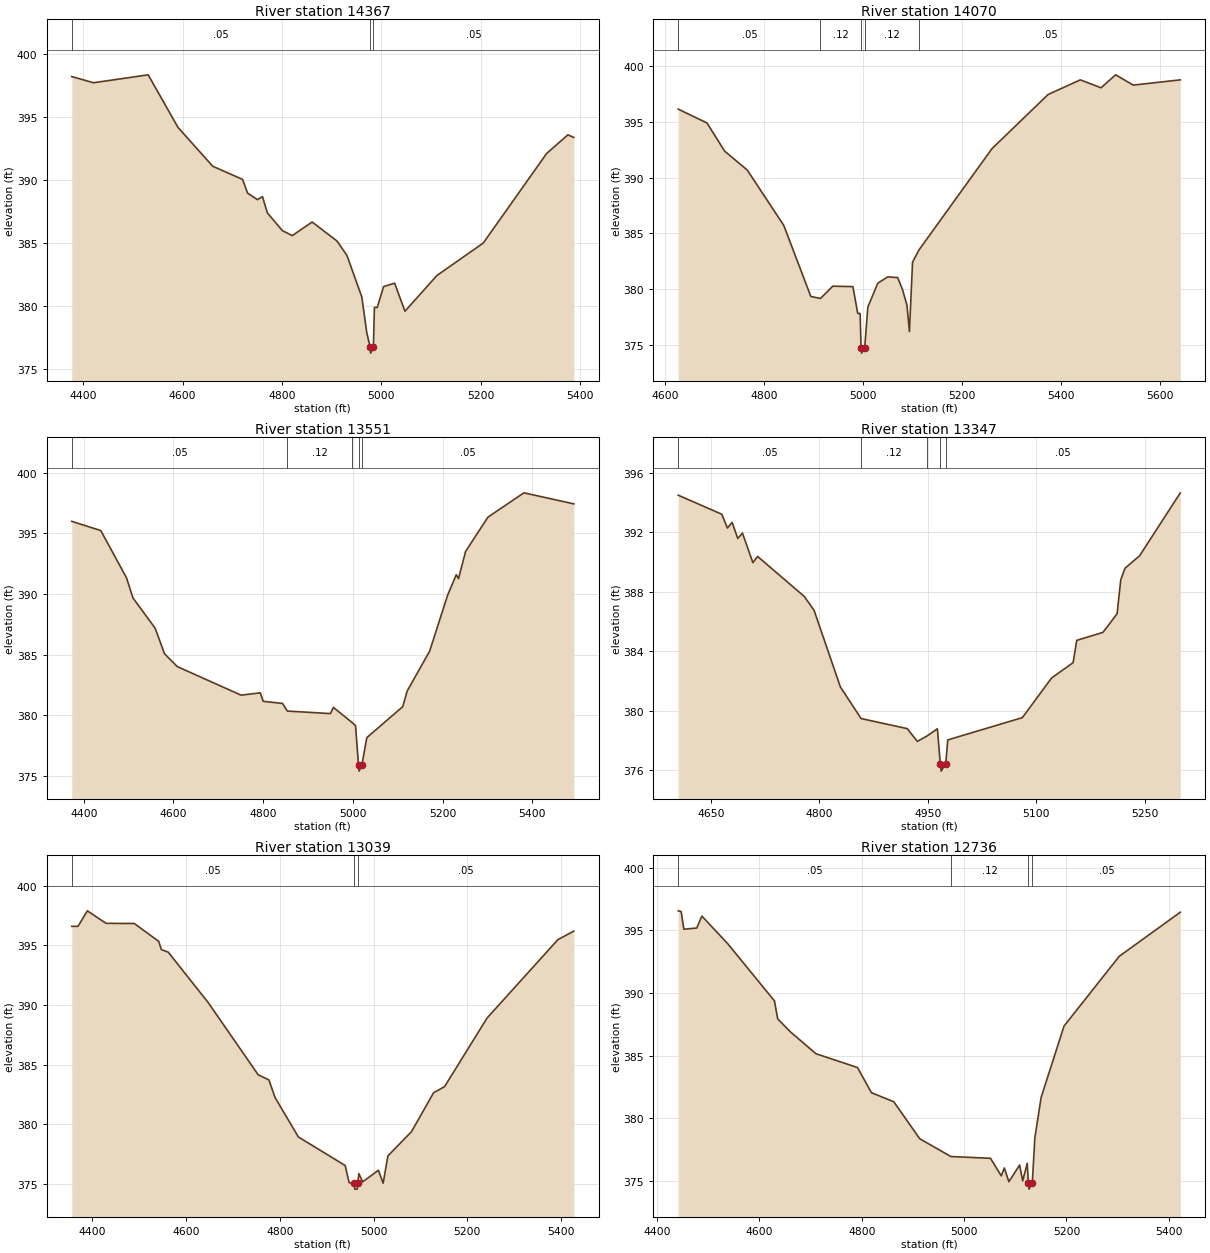
Type RM Length L Ch R = 1 ,14367   ,297,297,297
BEGIN DESCRIPTION:
Mapping XS 56449437
END DESCRIPTION:
XS GIS Cut Line= 3
      2707449.78      6885646.78      2706840.37      6885649.38
      2706522.66      6885894.18
#Sta/Elev= 30
    4377  398.22  4420.8  397.73  4530.8  398.36  4590.8  394.18  4660.8  391.09
  4720.8  390.05  4730.8  388.96  4750.8  388.44  4760.8  388.68  4770.8  387.38
  4800.8  385.98  4820.8  385.58  4860.8  386.66  4910.8  385.15  4930.8  384.01
  4960.8   380.7  4970.8  377.85  4977.4  376.74  4978.5  376.24  4984.1  376.74
  4986.1  379.87  4991.8  379.87  5004.6  381.53  5026.8   381.8  5047.6  379.57
  5111.9  382.41  5205.2  384.99  5332.8  392.11  5375.5  393.59  5387.5  393.38
#Mann= 3 ,-1 , 0
    4377     .05       0  4977.4     .04       0  4984.1     .05       0
Bank Sta=4977.4,4984.1
XS Rating Curve= 0 ,0
Exp/Cntr=0.3,0.1

Type RM Length L Ch R = 1 ,14070   ,519,519,519
BEGIN DESCRIPTION:
Mapping XS 343ba237
END DESCRIPTION:
XS GIS Cut Line= 4
      2707043.27      6885492.04      2706681.61      6885429.23
       2706342.2      6885452.67      2706093.85      6885631.45
#Sta/Elev= 30
  4626.9  396.12    4685  394.88  4720.6  392.36  4766.2  390.67  4839.9  385.72
  4894.5  379.36    4914  379.18  4938.8  380.28  4979.4  380.24  4989.2  377.84
    4994  377.84  4995.9  374.79  4997.1  374.29  5003.2  374.79  5009.6  378.41
  5029.7  380.55  5049.7  381.11  5069.8  381.05  5079.8  379.94  5088.5  378.58
  5093.5  376.22  5099.8  382.43  5112.9  383.53  5260.2  392.59  5373.4  397.43
  5438.4  398.74  5480.2  398.03  5509.6  399.19  5545.2  398.27  5640.2  398.74
#Mann= 5 ,-1 , 0
  4626.9     .05       0    4914     .12       0  4995.9     .07       0
  5003.2     .12       0  5112.9     .05       0
Bank Sta=4995.9,5003.2
XS Rating Curve= 0 ,0
Exp/Cntr=0.3,0.1

Type RM Length L Ch R = 1 ,13551   ,204,204,204
BEGIN DESCRIPTION:
Mapping XS 65254ee6
END DESCRIPTION:
XS GIS Cut Line= 3
      2707101.04      6885467.39      2706689.83      6884972.07
      2706214.78      6884958.81
#Sta/Elev= 30
  4373.4  395.98  4438.1  395.22  4495.4  391.33  4509.8  389.67  4559.2  387.18
  4580.1  385.07  4608.7  384.01  4750.7  381.66  4793.6  381.85  4800.1  381.15
  4843.1  380.98  4853.8  380.35  4949.9  380.14  4956.4  380.65  4998.8  379.39
  5005.9  379.15  5012.5   375.9  5013.7   375.4    5020   375.9    5031  378.16
    5111  380.71    5121     382  5171.1  385.29  5211.1   389.9  5230.4  391.58
  5235.4  391.26  5251.1   393.5  5301.1  396.33  5381.1  398.33  5492.4  397.42
#Mann= 5 ,-1 , 0
  4373.4     .05       0  4853.8     .12       0  4998.8     .05       0
  5012.5     .04       0    5020     .05       0
Bank Sta=5012.5,5020
XS Rating Curve= 0 ,0
Exp/Cntr=0.3,0.1

Type RM Length L Ch R = 1 ,13347   ,308,308,308
BEGIN DESCRIPTION:
CCT9 19.0
END DESCRIPTION:
XS GIS Cut Line= 3
      2707149.97      6885092.26      2706849.96      6884842.25
      2706550.52      6884792.34
#Sta/Elev= 30
    4605  394.51  4665.2  393.23    4673   392.3  4679.5  392.68  4687.3   391.6
  4693.8  391.96  4708.2  389.97  4714.7  390.39  4779.4  387.69  4792.8  386.76
  4829.2   381.6  4857.8  379.48  4921.6   378.8  4935.6  377.94  4949.1  378.31
  4963.3  378.79  4967.3  376.44  4968.5  375.94  4974.8  376.44  4977.6  378.04
  5080.7  379.54  5121.2  382.21  5150.9  383.24  5155.9  384.74  5192.2  385.28
  5211.7  386.53  5216.8  388.82  5222.6  389.59  5242.9  390.44  5299.1  394.67
#Mann= 5 ,-1 , 0
    4605     .05       0  4857.8     .12       0  4949.1     .05       0
  4967.3     .04       0  4974.8     .05       0
Bank Sta=4967.3,4974.8
XS Rating Curve= 0 ,0
Exp/Cntr=0.3,0.1

Type RM Length L Ch R = 1 ,13039   ,303,303,303
BEGIN DESCRIPTION:
Mapping XS 6b11d0ad
END DESCRIPTION:
XS GIS Cut Line= 4
      2707529.32      6884852.47      2707348.77      6884852.84
      2706981.92      6884579.56      2706552.33      6884632.11
#Sta/Elev= 30
  4356.4   396.6  4369.7   396.6  4389.7   397.9  4429.7  396.85  4489.7  396.84
  4541.8  395.34  4547.5  394.65  4562.1  394.44  4647.6   390.2    4754  384.16
  4776.9  383.73  4789.8  382.27  4839.7  378.95  4939.5  376.56  4947.9  375.12
  4958.7  375.08  4959.9  374.58  4965.2  374.58  4966.3  375.08  4968.7  375.88
  4976.8  375.19  5010.4  376.16  5020.5  375.08  5030.6  377.36    5081   379.4
    5128  382.65  5151.5  383.17  5242.2  388.92  5393.3  395.49  5427.2   396.2
#Mann= 3 ,-1 , 0
  4356.4     .05       0  4958.7     .04       0  4966.3     .05       0
Bank Sta=4958.7,4966.3
XS Rating Curve= 0 ,0
Exp/Cntr=0.3,0.1

Type RM Length L Ch R = 1 ,12736   ,340,340,340
BEGIN DESCRIPTION:
Mapping XS 75a7a5b3
END DESCRIPTION:
XS GIS Cut Line= 3
      2707501.62      6884194.17      2706949.49      6884285.32
      2706600.79      6884522.12
#Sta/Elev= 30
  4441.3  396.55    4447  396.49  4452.3  395.08  4477.4  395.18  4487.5  396.13
  4538.2  393.92  4629.4  389.36  4635.6  387.94  4659.8  386.92  4710.5  385.15
  4791.6  384.05  4818.9  382.04  4862.5  381.32  4913.2  378.37  4974.1  376.95
  5051.5  376.81  5072.5  375.41  5078.5  376.04  5087.4  374.94  5108.4  376.27
  5114.4  375.01  5123.3  376.41  5125.6  374.85  5126.7  374.35  5133.2  374.85
  5138.1  378.42  5150.4  381.66  5195.2  387.36    5303  392.92  5422.4  396.44
#Mann= 4 ,-1 , 0
  4441.3     .05       0  4974.1     .12       0  5125.6     .07       0
  5133.2     .05       0
Bank Sta=5125.6,5133.2
XS Rating Curve= 0 ,0
Exp/Cntr=0.3,0.1

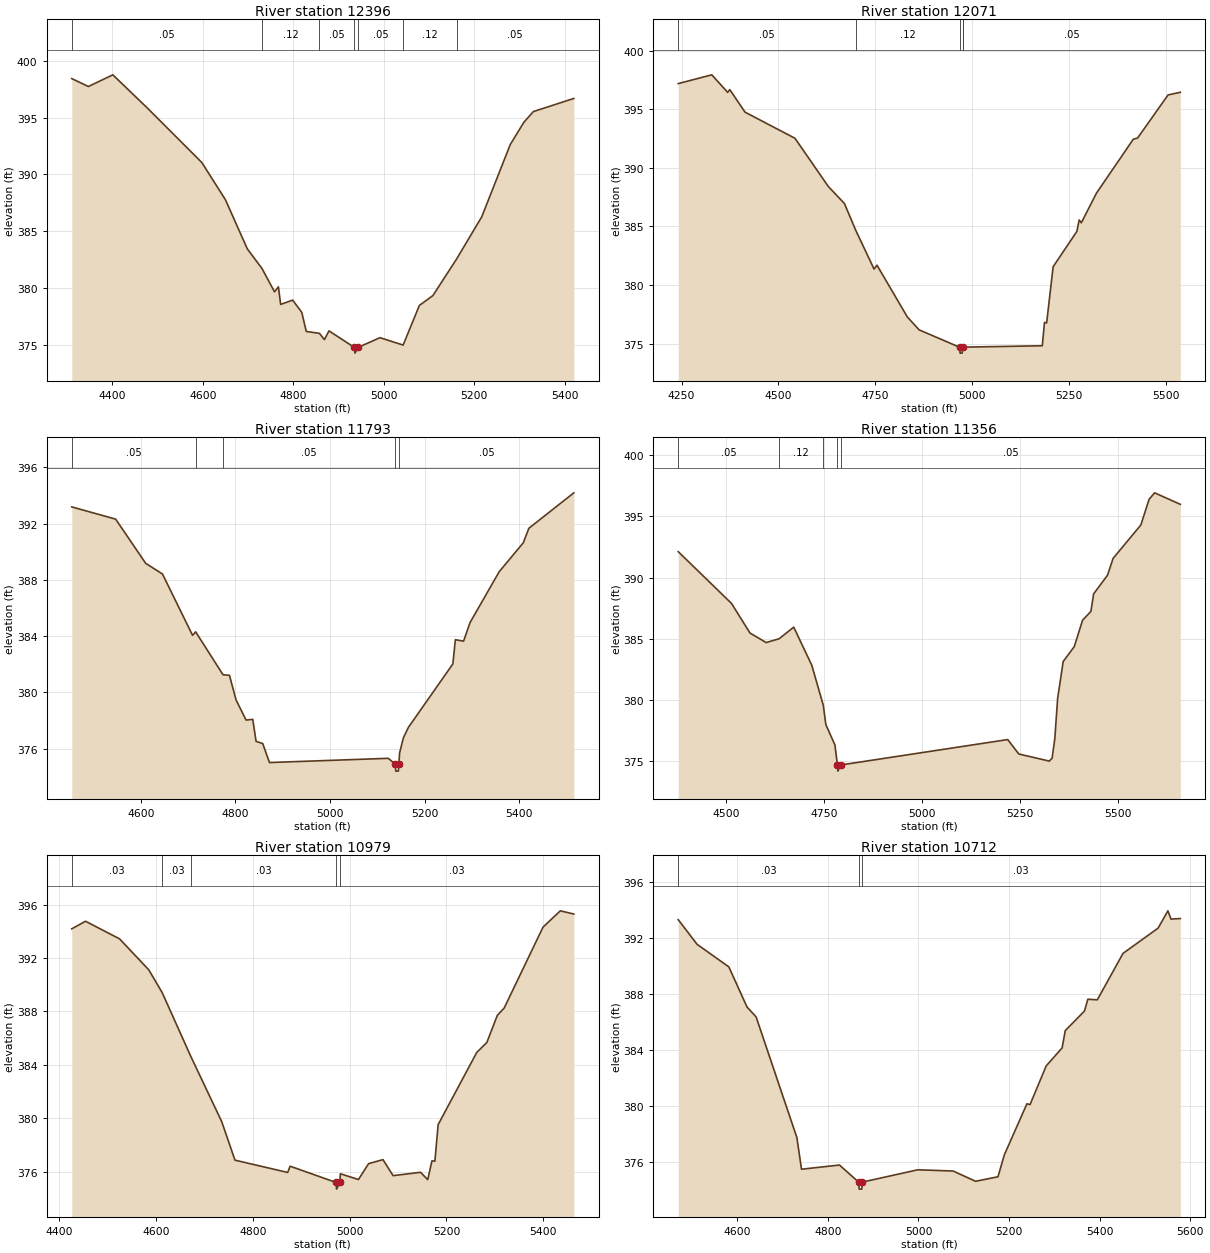
Type RM Length L Ch R = 1 ,12396   ,325,325,325
BEGIN DESCRIPTION:
Mapping XS d03edf87
END DESCRIPTION:
XS GIS Cut Line= 3
       2707452.7      6883938.75      2706784.34        6883993.
      2706539.13      6884357.55
#Sta/Elev= 30
  4310.5  398.45  4347.3  397.75  4401.3  398.78  4477.7  395.85  4598.1  391.05
  4650.3  387.77  4698.5  383.45    4731  381.72  4758.7  379.66  4767.3   380.1
  4772.3  378.55  4798.8  378.93  4818.9  377.86  4828.9  376.17  4858.1     376
    4869  375.45  4879.1  376.22  4935.4  374.76  4936.6  374.26  4943.1  374.76
  4991.9  375.62    5043  374.97  5078.9  378.46  5108.8  379.33  5161.2  382.55
  5216.8  386.27  5279.9  392.64  5309.8  394.59  5330.8  395.54  5420.4   396.7
#Mann= 7 ,-1 , 0
  4310.5     .05       0    4731     .12       0  4858.1     .05       0
  4935.4     .04       0  4943.1     .05       0    5043     .12       0
  5161.2     .05       0
Bank Sta=4935.4,4943.1
XS Rating Curve= 0 ,0
Exp/Cntr=0.3,0.1

Type RM Length L Ch R = 1 ,12071   ,278,278,278
BEGIN DESCRIPTION:
Mapping XS da1587f7
END DESCRIPTION:
XS GIS Cut Line= 3
       2707246.6       6883498.2      2706547.79      6883771.65
      2706304.75      6884259.89
#Sta/Elev= 30
  4241.3   397.2  4327.9  397.95    4369  396.45  4374.3  396.69  4413.8  394.76
  4542.6  392.53  4628.5  388.42  4670.2  386.96  4699.6  384.66  4746.7  381.36
  4754.3  381.69  4832.6  377.27  4862.9  376.17  4967.6  374.68  4968.8  374.18
  4974.1  374.18  4975.3  374.68    4977  374.69  5180.9  374.81  5186.5   376.8
  5192.1  376.76  5208.9  381.56  5270.2  384.58    5276  385.55  5281.6  385.31
  5320.8  387.85    5416  392.46  5426.6  392.54  5505.5  396.23  5537.1  396.46
#Mann= 5 ,-1 , 0
  4241.3     .05       0  4699.6     .12       0  4967.6     .03       0
  4975.3     .12       0    4977     .05       0
Bank Sta=4967.6,4975.3
XS Rating Curve= 0 ,0
Exp/Cntr=0.3,0.1

Type RM Length L Ch R = 1 ,11793   ,437,437,437
BEGIN DESCRIPTION:
Mapping XS dcaaa546
END DESCRIPTION:
XS GIS Cut Line= 3
      2706705.67      6883219.53       2706330.2      6883612.36
       2706156.6      6884100.61
#Sta/Elev= 30
  4454.1  393.19  4546.9  392.32  4610.4  389.18  4645.9  388.42  4709.5  384.06
  4716.1  384.31  4773.9  381.26  4787.5  381.22  4801.6  379.46  4822.7  378.04
  4836.8  378.09  4843.8  376.53  4857.9  376.37  4872.1  375.02  5123.4  375.32
    5138  374.91  5139.2  374.41  5144.6  374.41  5145.8  374.91  5147.2  375.69
  5155.3  376.78  5165.9  377.52  5259.9  382.03  5265.2  383.75  5282.6  383.65
  5296.1  384.96  5357.8  388.58  5408.8  390.64  5420.6  391.67  5515.7  394.19
#Mann= 5 ,-1 , 0
  4454.1     .05       0  4716.1     .12       0  4773.9     .05       0
    5138     .03       0  5145.8     .05       0
Bank Sta=5138,5145.8
XS Rating Curve= 0 ,0
Exp/Cntr=0.3,0.1

Type RM Length L Ch R = 1 ,11356   ,377,377,377
BEGIN DESCRIPTION:
Mapping XS 2c00e4a2
END DESCRIPTION:
XS GIS Cut Line= 3
      2706653.52      6883132.77      2706054.59      6883284.67
      2705594.53      6883762.09
#Sta/Elev= 30
  4378.9  392.12  4514.8  387.89    4562  385.47  4603.3  384.69  4636.2     385
  4673.6  385.95  4719.7  382.83    4749  379.56  4755.5  377.98  4778.7  376.32
    4785  374.68  4786.2  374.18    4793  374.68  5219.5  376.76  5247.8  375.58
  5325.5     375  5332.7  375.24  5339.6  376.82  5346.8  380.12    5361  383.14
  5389.3  384.36  5410.4  386.51  5431.7  387.24  5438.7  388.67  5474.2   390.2
  5488.3  391.57  5559.1   394.3  5580.2   396.4  5594.3  396.93  5659.8  395.99
#Mann= 5 ,-1 , 0
  4378.9     .05       0  4636.2     .12       0    4749     .05       0
    4785     .03       0    4793     .05       0
Bank Sta=4785,4793
XS Rating Curve= 0 ,0
Exp/Cntr=0.3,0.1

Type RM Length L Ch R = 1 ,10979   ,267,267,267
BEGIN DESCRIPTION:
Mapping XS b2dc8b10
END DESCRIPTION:
XS GIS Cut Line= 3
      2706494.28      6882894.34      2705938.74      6882946.42
      2705546.39      6883220.72
#Sta/Elev= 30
  4426.4  394.18  4454.8  394.75  4525.1  393.43  4585.4  391.11    4613  389.41
  4672.1  384.63    4736  379.74  4763.4  376.85  4872.2  375.93  4877.2   376.4
    4972  375.18  4973.2  374.68    4980  375.18    4981  375.83  5018.4   375.4
  5039.3  376.59    5069  376.89  5089.9  375.69  5146.6  375.94  5161.4  375.39
  5170.1   376.8  5176.2  376.77  5182.9  379.51  5262.6  384.92  5283.5  385.67
    5305  387.69  5319.3  388.25  5399.5  394.31  5435.2  395.53  5463.1  395.29
#Mann= 5 ,-1 , 0
  4426.4     .03       0    4613     .03       0  4672.1     .03       0
    4972     .03       0    4980     .03       0
Bank Sta=4972,4980
XS Rating Curve= 0 ,0
Exp/Cntr=0.3,0.1

Type RM Length L Ch R = 1 ,10712   ,45,45,45
BEGIN DESCRIPTION:
Mapping XS 23316773
END DESCRIPTION:
XS GIS Cut Line= 3
      2706407.52      6882738.09      2705878.25      6882705.06
      2705483.27      6883127.04
#Sta/Elev= 30
  4469.7  393.32  4511.3  391.56  4581.4  389.95  4621.5  387.09  4641.6  386.38
  4731.7  377.76  4741.8  375.51  4825.6  375.81    4868  374.59  4869.2  374.09
  4874.8  374.09    4876  374.59  4998.6  375.47  5076.6  375.38  5126.1  374.65
  5175.5  374.97  5189.6  376.54  5239.4  380.18  5246.3  380.12  5281.9  382.88
  5317.1  384.17    5324   385.4  5366.5   386.8  5373.8  387.64  5394.8   387.6
  5451.5  390.91  5529.1  392.72  5550.6  393.95  5557.5  393.36    5578   393.4
#Mann= 3 ,-1 , 0
  4469.7     .03       0    4868     .03       0    4876     .03       0
Bank Sta=4868,4876
XS Rating Curve= 0 ,0
Exp/Cntr=0.3,0.1

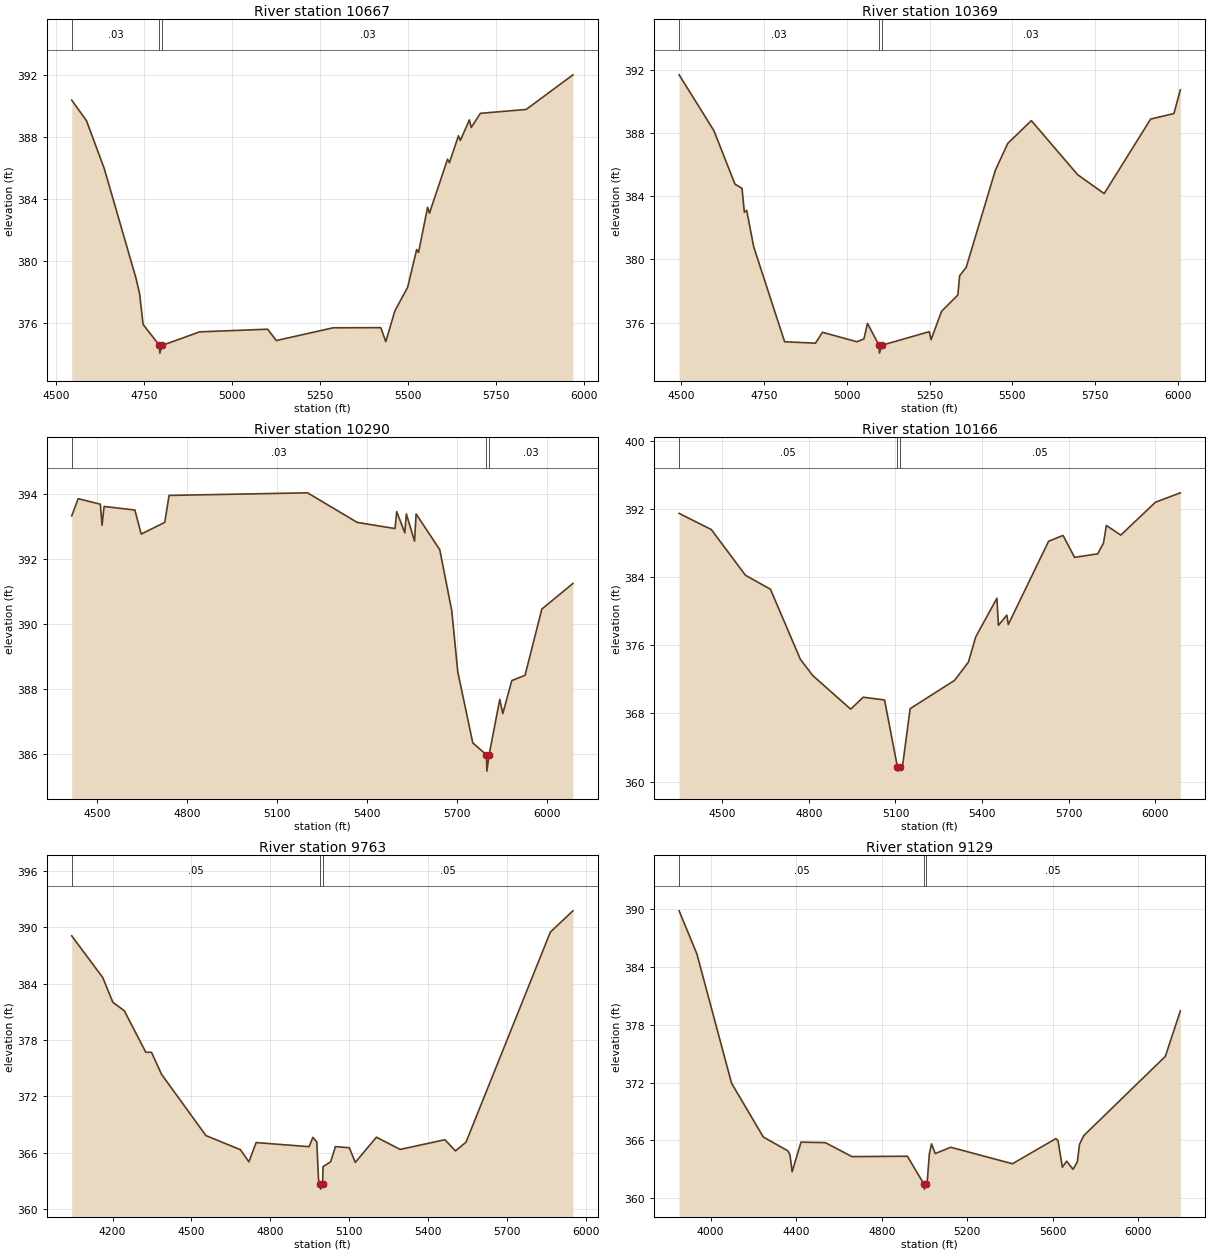
Type RM Length L Ch R = 1 ,10667   ,298,298,298
BEGIN DESCRIPTION:
Mapping XS 4485359a
END DESCRIPTION:
XS GIS Cut Line= 3
      2706327.75      6882708.28      2705879.92      6882661.71
      2704960.55      6882339.63
#Sta/Elev= 30
  4545.1  390.36  4587.1  389.03  4637.3  385.97  4727.8  378.89  4737.9   377.9
  4747.9  375.92  4794.2  374.57  4795.4  374.07  4802.2  374.57  4908.8  375.44
  5101.8  375.61  5126.6  374.88  5287.9   375.7  5423.3  375.71  5437.6  374.81
  5463.4  376.79  5499.7  378.31  5525.4  380.74  5530.7  380.55  5556.4  383.46
  5561.7  383.08  5613.1  386.56  5618.4  386.33  5644.2  388.07  5649.5  387.76
  5675.2  389.09  5680.5   388.6  5706.2  389.51  5836.6  389.76  5969.5  391.99
#Mann= 3 ,-1 , 0
  4545.1     .03       0  4794.2     .03       0  4802.2     .03       0
Bank Sta=4794.2,4802.2
XS Rating Curve= 0 ,0
Exp/Cntr=0.3,0.1

Type RM Length L Ch R = 1 ,10369   ,79,79,79
BEGIN DESCRIPTION:
Mapping XS d165dd21
END DESCRIPTION:
XS GIS Cut Line= 6
      2706373.77      6882721.61      2706191.46      6882541.04
      2705981.39      6882400.41      2705625.48       6882270.2
      2705495.28       6882207.7      2705016.61      6882176.22
#Sta/Elev= 30
  4494.4  391.69  4599.3  388.16  4662.9  384.77  4684.2   384.5  4691.2  382.99
  4698.3  383.11  4719.5   380.8  4812.8  374.79  4905.9   374.7  4926.9  375.39
  5030.8  374.79  5052.1  374.97  5062.8  375.95  5097.6  374.57  5098.9  374.07
  5106.4  374.57  5249.3  375.43  5254.6  374.92  5286.4  376.72  5335.5  377.75
  5340.9  378.97  5360.7   379.5  5448.7  385.65  5486.2  387.35  5557.3  388.79
  5696.8  385.37    5777  384.17  5917.3  388.89  5987.5  389.24  6006.9  390.74
#Mann= 3 ,-1 , 0
  4494.4     .03       0  5097.6     .03       0  5106.4     .03       0
Bank Sta=5097.6,5106.4
XS Rating Curve= 0 ,0
Exp/Cntr=0.3,0.1

Type RM Length L Ch R = 1 ,10290   ,124,124,124
BEGIN DESCRIPTION:
Mapping XS 1ea643b3
END DESCRIPTION:
XS GIS Cut Line= 6
       2706432.8      6882763.29      2706302.57      6882554.92
      2706243.54      6882485.48      2706038.68      6882346.59
      2705503.96      6882141.73      2704992.27      6882147.95
#Sta/Elev= 30
  4416.6  393.33  4438.1  393.86  4511.9  393.69  4517.7  393.04  4524.4  393.62
  4627.1  393.51  4648.1  392.77  4726.6  393.13  4740.9  393.96  5202.5  394.04
  5367.5  393.13  5493.8  392.94  5499.4  393.46  5526.3  392.81  5531.5  393.39
  5558.8  392.55    5564  393.39  5642.8  392.29  5682.8  390.41  5702.8  388.53
  5752.8  386.34  5798.4  385.97  5799.7  385.47  5807.2  385.97  5842.8  387.68
  5852.8  387.24  5882.9  388.26  5926.9  388.42  5982.9  390.46  6086.6  391.25
#Mann= 3 ,-1 , 0
  4416.6     .03       0  5798.4     .03       0  5807.2     .03       0
Bank Sta=5798.4,5807.2
XS Rating Curve= 0 ,0
Exp/Cntr=0.3,0.1

Type RM Length L Ch R = 1 ,10166   ,403,403,403
BEGIN DESCRIPTION:
Mapping XS 7b8982ae
END DESCRIPTION:
XS GIS Cut Line= 6
      2706484.63      6882715.35      2706285.75      6882364.44
      2706076.01        6882236.       2705763.5      6882150.41
      2705533.42        6882086.       2705009.8      6882073.89
#Sta/Elev= 30
  4350.7  391.47  4462.2  389.57  4580.5  384.21    4667  382.57  4770.8  374.34
  4813.4  372.45  4944.9   368.5  4988.3   369.9  5062.2  369.58  5106.8  361.73
  5108.1  361.23  5115.6  361.73  5124.4  361.81  5150.9  368.56  5304.4  371.87
  5352.6  374.01    5378  376.98  5451.4  381.51  5456.6  378.33  5485.6  379.53
  5490.8  378.43  5630.4   388.2  5680.4  388.88  5720.4  386.31  5800.4  386.72
  5820.4  387.97  5830.4  390.05  5880.4  388.92  6000.5  392.78  6086.7  393.88
#Mann= 3 ,-1 , 0
  4350.7     .05       0  5106.8     .04       0  5115.6     .05       0
Bank Sta=5106.8,5115.6
XS Rating Curve= 0 ,0
Exp/Cntr=0.3,0.1

Type RM Length L Ch R = 1 ,9763    ,634,634,634
BEGIN DESCRIPTION:
Mapping XS 1c407dc4
END DESCRIPTION:
XS GIS Cut Line= 4
      2706706.01      6882672.73      2706289.87      6881909.95
       2706115.5      6881835.84      2705270.23      6881782.85
#Sta/Elev= 30
  4044.8  389.07    4163  384.63    4201  382.01  4244.6  381.11  4326.3   376.7
  4348.1  376.69  4386.1  374.36    4555  367.84    4686  366.34  4718.3  365.05
  4745.8   367.1  4947.2  366.66  4961.4  367.65  4976.3  367.17  4983.1  363.09
  4989.6  362.65  4990.9  362.15  4998.4  362.65    5000  364.53    5029  365.06
  5047.3  366.67    5100  366.55  5122.7  364.99  5202.9  367.67    5293  366.37
  5463.4   367.4  5503.5  366.21  5543.5  367.14  5864.2  389.47  5950.1  391.73
#Mann= 3 ,-1 , 0
  4044.8     .05       0  4989.6     .04       0  4998.4     .05       0
Bank Sta=4989.6,4998.4
XS Rating Curve= 0 ,0
Exp/Cntr=0.3,0.1

Type RM Length L Ch R = 1 ,9129    ,993,993,993
BEGIN DESCRIPTION:
CCT9 10.0
END DESCRIPTION:
XS GIS Cut Line= 3
      2706826.01      6882611.04        2706526.        6881511.
      2705325.97        6881411.
#Sta/Elev= 30
  3852.4   389.8  3935.4  385.34  4097.7  371.93  4246.3  366.35  4360.3  364.93
  4370.7  364.53  4381.1  362.76  4422.5  365.82  4536.5  365.77  4660.9  364.32
  4920.1  364.36  4998.2  361.45  4999.5  360.95    5007  361.45  5012.7  361.66
  5022.7  364.58  5032.8  365.64  5050.3  364.64  5123.1  365.29  5411.6  363.58
  5614.8  366.19  5624.8  365.95  5644.9  363.22  5664.9  363.85    5695     363
  5715.1  363.79  5725.1  365.59  5745.2   366.5  6126.5  374.71  6196.8  379.42
#Mann= 3 ,-1 , 0
  3852.4     .05       0  4998.2     .04       0    5007     .05       0
Bank Sta=4998.2,5007
XS Rating Curve= 0 ,0
Exp/Cntr=0.3,0.1

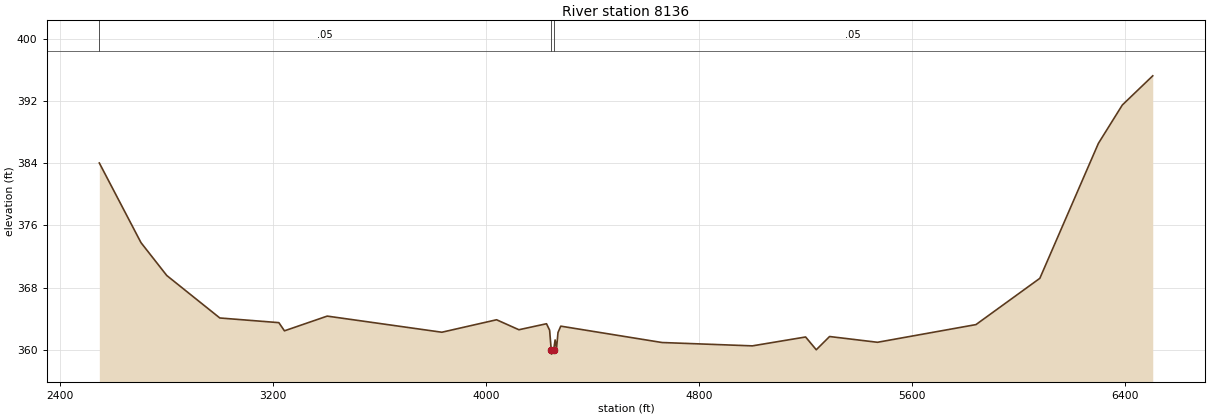
Type RM Length L Ch R = 1 ,8136    ,0,0,0
BEGIN DESCRIPTION:
Mapping XS ca965eef
END DESCRIPTION:
XS GIS Cut Line= 4
      2707278.47      6882724.16       2706644.8      6880718.99
      2706358.34       6880580.1      2704821.83      6880588.78
#Sta/Elev= 30
  2546.2  384.02  2702.7   373.8  2799.6  369.58  2998.8  364.13  3220.7  363.53
  3241.7  362.48  3402.4  364.37  3833.1   362.3  4038.7   363.9  4122.6  362.62
  4226.3  363.39    4238  362.56  4244.1  359.99  4245.3  359.49  4252.9  359.99
  4258.6  361.31  4263.8  360.18  4269.5  362.27  4279.9  363.08  4660.2  360.98
  4999.8  360.55  5199.8  361.69  5239.8  360.05  5289.8  361.75  5469.8  361.01
  5839.8  363.28  6079.8  369.22  6299.8  386.54  6389.8  391.47    6504  395.21
#Mann= 3 ,-1 , 0
  2546.2     .05       0  4244.1     .04       0  4252.9     .05       0
Bank Sta=4244.1,4252.9
XS Rating Curve= 0 ,0
Exp/Cntr=0.3,0.1

Chan Stop Cuts=-1
Use User Specified Reach Order=0
Composite Channel Slope=5