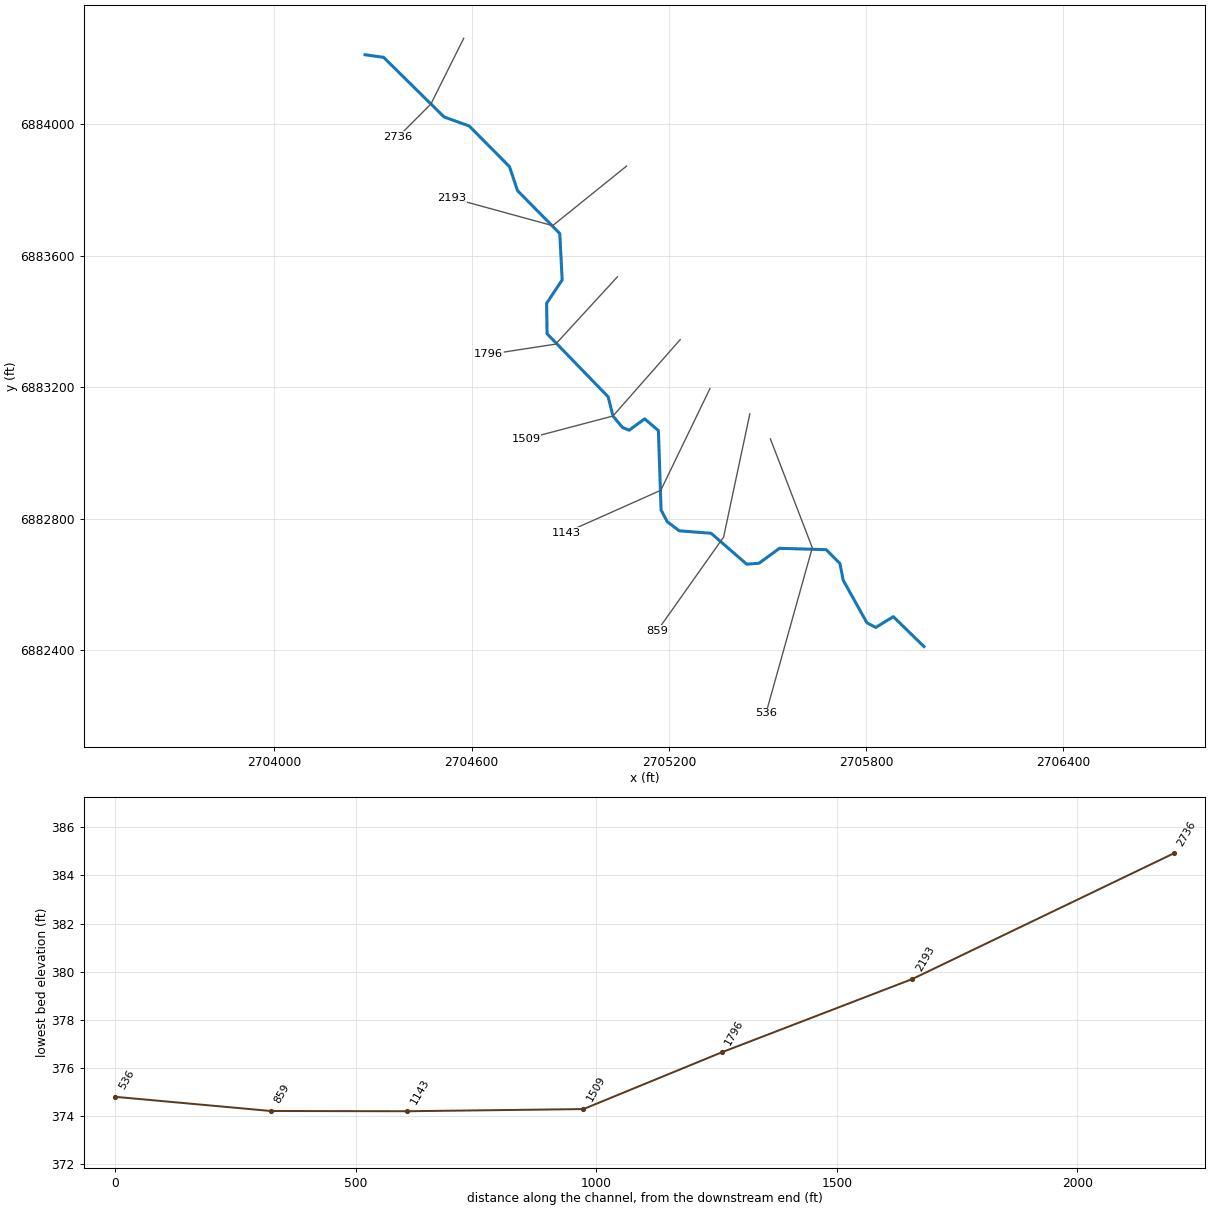
--- CCT9_1.prj (project) ---

Proj Title=CCT9_1 Base Level Engineering
Current Plan=p01
Default Exp/Contr=0.3,0.1
English Units
Geom File=g01
Flow File=f01
Plan File=p01
Y Axis Title=Elevation
X Axis Title(PF)=Main Channel Distance
X Axis Title(XS)=Station
BEGIN DESCRIPTION:
CCT9_1
END DESCRIPTION:
DSS Export Rating Curves= 0
DSS Export Rating Curve Sorted= 0
DSS Export Volume Flow Curves= 0
DXF OffsetX= 0
DXF OffsetY= 0
DXF ScaleX= 1
DXF ScaleY= 10

--- CCT9_1.p01 (plan) ---

Plan Title=Multiple Run
Short Identifier=Multiple
Geom File=g01
Flow File=f01
Subcritical Flow
K Sum by GR= 0
Std Step Tol= 0.01
Critical Tol= 0.01
Num of Std Step Trials= 20
Max Error Tol= 0.3
Flow Tol Ratio= 0.001
Split Flow NTrial= 30
Split Flow Tol= 0.02
Split Flow Ratio= 0.02
Log Output Level= 0
Friction Slope Method= 1
Unsteady Friction Slope Method= 2
Unsteady Bridges Friction Slope Method= 1
Parabolic Critical Depth
Global Vel Dist=  1 , 1 , 1
Global Log Level= 0
CheckData=True
Encroach Param= -1, 0, 0, 0
BEGIN DESCRIPTION:
Multiple Run
END DESCRIPTION:

--- CCT9_1.f01 (steady flow) ---

Flow Title=Multiple
Number of Profiles=7
Profile Names=10-year,25-year,50-year,1pct_min,100-year,1pct_plu,500-year
River Rch & RM= CCT9_1,Reach-1,2736
     208     257     293     166     332     662     425
Boundary for River Rch & Prof#=CCT9_1,Reach-1,1
Up Type=0
Dn Type=3
Dn Slope=0.005
Boundary for River Rch & Prof#=CCT9_1,Reach-1,2
Up Type=0
Dn Type=3
Dn Slope=0.005
Boundary for River Rch & Prof#=CCT9_1,Reach-1,3
Up Type=0
Dn Type=3
Dn Slope=0.005
Boundary for River Rch & Prof#=CCT9_1,Reach-1,4
Up Type=0
Dn Type=3
Dn Slope=0.005
Boundary for River Rch & Prof#=CCT9_1,Reach-1,5
Up Type=0
Dn Type=3
Dn Slope=0.005
Boundary for River Rch & Prof#=CCT9_1,Reach-1,6
Up Type=0
Dn Type=3
Dn Slope=0.005
Boundary for River Rch & Prof#=CCT9_1,Reach-1,7
Up Type=0
Dn Type=3
Dn Slope=0.005

--- CCT9_1.g01 (geometry) ---

Geom Title=Existing Conditions
Program Version=4.10

River Reach=CCT9_1          ,Reach-1
Reach XY= 30
        2704276.        6884211.      2704332.21      6884203.24
      2704516.32      6884021.78      2704592.67      6883994.35
      2704715.22      6883870.68      2704739.63      6883797.79
      2704868.19      6883667.19      2704875.49      6883526.22
      2704828.16      6883455.02      2704829.46       6883362.5
      2705015.22      6883170.64      2705029.98      6883112.18
      2705058.96      6883077.24      2705079.17      6883069.09
      2705126.23      6883103.54      2705168.19      6883067.82
      2705176.32      6882826.02       2705195.4      6882790.35
      2705231.69      6882763.07      2705328.42      6882755.46
      2705436.62       6882661.6      2705474.25      6882664.34
       2705536.5      6882709.77       2705678.7      6882705.65
      2705720.29      6882663.59       2705730.2      6882612.76
      2705802.29      6882483.36      2705829.15      6882469.07
      2705882.66      6882501.82        2705976.        6882411.

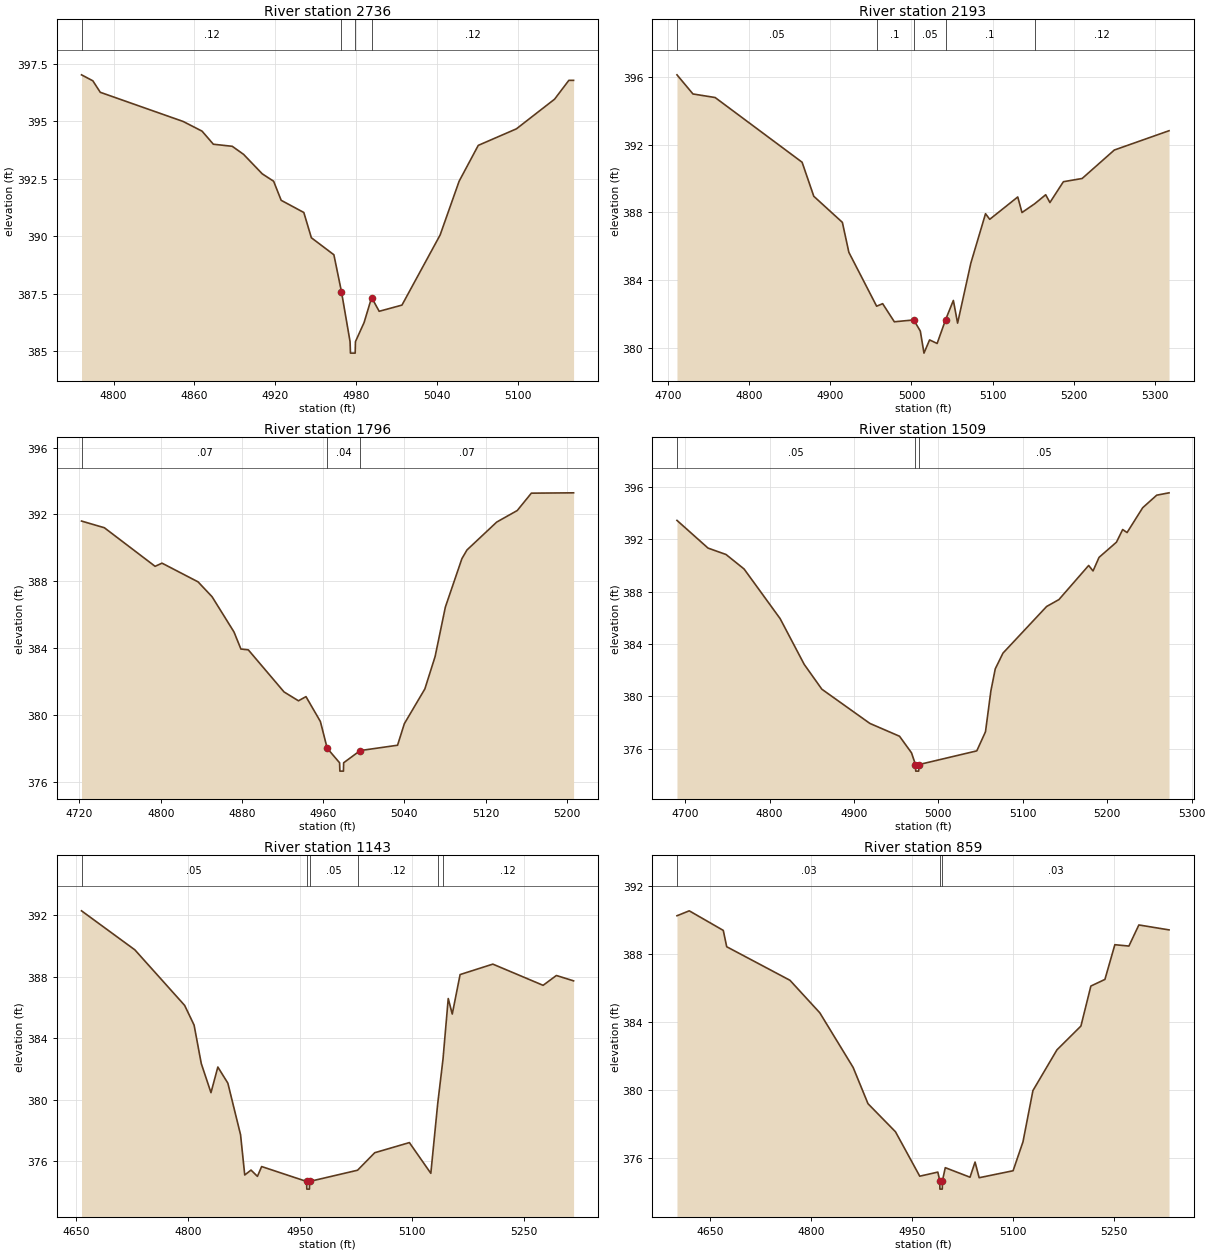
Type RM Length L Ch R = 1 ,2736    ,543,543,543
BEGIN DESCRIPTION:
CCT9_1 6.0
END DESCRIPTION:
XS GIS Cut Line= 3
      2704575.98      6884260.97        2704476.        6884061.
        2704376.        6883961.
#Sta/Elev= 30
  4776.2  397.03  4784.6  396.77  4790.1  396.27  4851.6     395  4865.6  394.58
    4874  394.01    4888  393.92  4896.4  393.57  4910.3  392.72  4918.7   392.4
  4924.3  391.57  4941.1  391.04  4946.7  389.94  4963.4   389.2    4969   387.6
  4975.4  385.42  4975.7  384.92  4979.2  384.92  4979.4  385.42  4985.8  386.25
  4991.4  387.34    4997  386.74  5013.9  387.01  5042.2  390.06  5056.3   392.4
  5070.5  393.96  5098.8  394.68  5127.1  395.97  5137.7  396.79  5141.2  396.79
#Mann= 4 ,-1 , 0
  4776.2     .12       0    4969     .07       0  4979.4     .12       0
  4991.4     .12       0
Bank Sta=4969,4991.4
XS Rating Curve= 0 ,0
Exp/Cntr=0.3,0.1

Type RM Length L Ch R = 1 ,2193    ,397,397,397
BEGIN DESCRIPTION:
CCT9_1 5.0
END DESCRIPTION:
XS GIS Cut Line= 3
      2705071.35      6883872.44      2704846.49       6883691.2
      2704540.57      6883775.05
#Sta/Elev= 30
  4711.2  396.12  4730.9  394.99  4758.2  394.78  4865.3  390.96  4879.7  388.95
  4914.9  387.41  4922.9  385.64  4957.1  382.46  4964.5  382.61  4978.9  381.54
  5002.8  381.65  5010.9  380.99  5015.4  379.69  5022.3  380.47  5031.6  380.26
    5042  381.66  5051.6   382.8  5056.8  381.46  5073.1     385  5091.2  387.92
  5096.4  387.59  5130.9  388.91  5136.1  387.99  5151.8  388.51  5165.3  389.04
  5170.5  388.58  5187.1  389.81  5210.2     390  5249.8  391.68  5317.2  392.82
#Mann= 5 ,-1 , 0
  4711.2     .05       0  4957.1      .1       0  5002.8     .05       0
    5042      .1       0  5151.8     .12       0
Bank Sta=5002.8,5042
XS Rating Curve= 0 ,0
Exp/Cntr=0.3,0.1

Type RM Length L Ch R = 1 ,1796    ,287,287,287
BEGIN DESCRIPTION:
CCT9_1 4.0
END DESCRIPTION:
XS GIS Cut Line= 3
      2705043.51      6883535.58       2704855.5       6883330.8
      2704651.18       6883299.5
#Sta/Elev= 30
    4722   391.6  4744.5   391.2  4794.5  388.89  4801.3  389.08  4836.8  387.96
  4850.6  387.07  4872.2  384.96    4879  383.94  4886.3  383.89  4921.5  381.37
  4935.7  380.84  4943.1  381.09  4957.3   379.6    4964     378  4976.2  377.13
  4976.5  376.63    4980  376.63  4980.2  377.13  4996.5  377.86  5033.3  378.18
    5040  379.47  5060.2  381.55  5070.3  383.49  5080.4  386.45  5096.7  389.35
  5101.7  389.87    5131  391.54  5151.2  392.23  5165.1  393.27  5206.7  393.29
#Mann= 3 ,-1 , 0
    4722     .07       0    4964     .04       0  4996.5     .07       0
Bank Sta=4964,4996.5
XS Rating Curve= 0 ,0
Exp/Cntr=0.3,0.1

Type RM Length L Ch R = 1 ,1509    ,366,366,366
BEGIN DESCRIPTION:
CCT9_1 3.0
END DESCRIPTION:
XS GIS Cut Line= 3
      2705234.49      6883344.61      2705029.98      6883112.18
       2704765.8      6883042.56
#Sta/Elev= 30
  4690.4  393.46  4727.2  391.34  4748.5  390.85  4769.9  389.74  4812.6  385.94
  4841.1  382.44    4862  380.54  4918.9  377.92    4954  376.94  4968.2  375.67
  4972.9  374.77  4973.2  374.27  4976.7  374.27  4976.9  374.77  5045.5  375.82
  5055.8  377.28  5062.2  380.41  5067.4   382.1  5076.5   383.3  5128.2  386.87
  5142.8   387.4    5178  390.01  5183.2  389.59  5190.3  390.63  5210.9  391.79
  5218.3  392.76  5223.5  392.53    5242  394.43  5258.6  395.39  5273.2  395.57
#Mann= 3 ,-1 , 0
  4690.4     .05       0  4972.9     .04       0  4976.9     .05       0
Bank Sta=4972.9,4976.9
XS Rating Curve= 0 ,0
Exp/Cntr=0.3,0.1

Type RM Length L Ch R = 1 ,1143    ,284,284,284
BEGIN DESCRIPTION:
Mapping XS dad7598b
END DESCRIPTION:
XS GIS Cut Line= 3
      2705324.78      6883195.31      2705175.48       6882886.3
      2704887.31      6882757.84
#Sta/Elev= 30
  4657.5   392.3  4728.9  389.76  4795.6  386.14  4808.2  384.86  4817.8  382.36
  4830.8  380.46    4840  382.13  4853.4  381.08  4870.4  377.72    4876   375.1
  4884.4  375.42    4893  375.01  4898.6  375.65  4958.8  374.68  4959.1  374.18
  4962.6  374.18  4962.8  374.68    5027  375.41    5050  376.55  5096.4  377.21
  5125.1  375.21  5134.3  379.74  5141.4  382.64  5148.4  386.59  5153.8  385.58
  5164.3  388.15  5208.1  388.83  5275.4  387.45  5293.2  388.09  5316.2  387.74
#Mann= 6 ,-1 , 0
  4657.5     .05       0  4958.8     .03       0  4962.8     .05       0
    5027     .12       0  5134.3      .1       0  5141.4     .12       0
Bank Sta=4958.8,4962.8
XS Rating Curve= 0 ,0
Exp/Cntr=0.3,0.1

Type RM Length L Ch R = 1 ,859     ,323,323,323
BEGIN DESCRIPTION:
Mapping XS 19b29328
END DESCRIPTION:
XS GIS Cut Line= 3
      2705446.31      6883118.93      2705366.46      6882743.94
      2705165.09      6882459.25
#Sta/Elev= 30
  4600.2  390.25  4618.5  390.54  4669.1  389.39  4674.2  388.43  4768.3  386.46
  4812.7  384.55  4862.3  381.34  4884.4  379.21  4925.3  377.56  4961.4  374.95
  4988.3  375.19  4991.2  374.69  4991.4  374.19  4994.9  374.19  4995.2  374.69
  4999.4  375.45  5036.2  374.89  5043.7  375.78  5049.8  374.86  5100.3  375.27
    5115  376.97  5129.8  379.98  5165.5  382.37  5201.2  383.77    5216  386.12
  5236.9  386.51  5251.7  388.55  5272.6  388.47  5287.4  389.71  5332.3  389.42
#Mann= 3 ,-1 , 0
  4600.2     .03       0  4991.2     .03       0  4995.2     .03       0
Bank Sta=4991.2,4995.2
XS Rating Curve= 0 ,0
Exp/Cntr=0.3,0.1

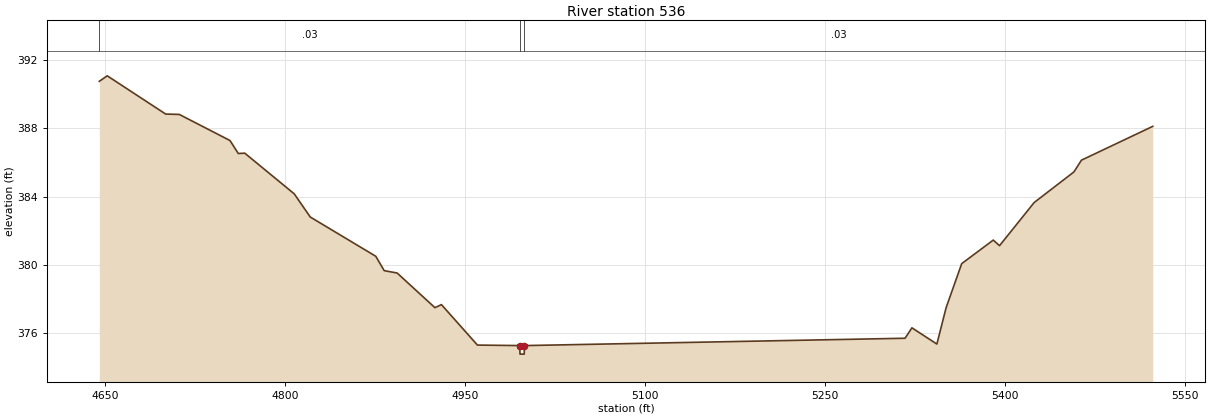
Type RM Length L Ch R = 1 ,536     ,0,0,0
BEGIN DESCRIPTION:
CCT9_1 2.0
END DESCRIPTION:
XS GIS Cut Line= 3
       2705508.8      6883042.59      2705636.23      6882711.57
      2705495.28      6882207.71
#Sta/Elev= 30
  4645.3  390.76  4651.9  391.08  4700.6  388.84  4711.9  388.82  4754.2  387.29
  4761.1  386.53  4766.5  386.55  4807.7  384.17  4821.1  382.81  4875.7  380.51
  4882.7  379.67  4893.5  379.53    4925   377.5  4930.4  377.68  4960.4  375.31
  4995.6  375.28  4995.9  374.78  4999.4  374.78  4999.6  375.28  5316.8  375.71
  5322.5  376.32  5343.3  375.37    5351   377.5    5364  380.08  5390.3  381.46
  5395.5  381.13  5424.4  383.66  5457.5  385.45  5463.8  386.14  5523.2  388.12
#Mann= 3 ,-1 , 0
  4645.3     .03       0  4995.6     .03       0  4999.6     .03       0
Bank Sta=4995.6,4999.6
XS Rating Curve= 0 ,0
Exp/Cntr=0.3,0.1

Chan Stop Cuts=-1
Use User Specified Reach Order=0
Composite Channel Slope=5