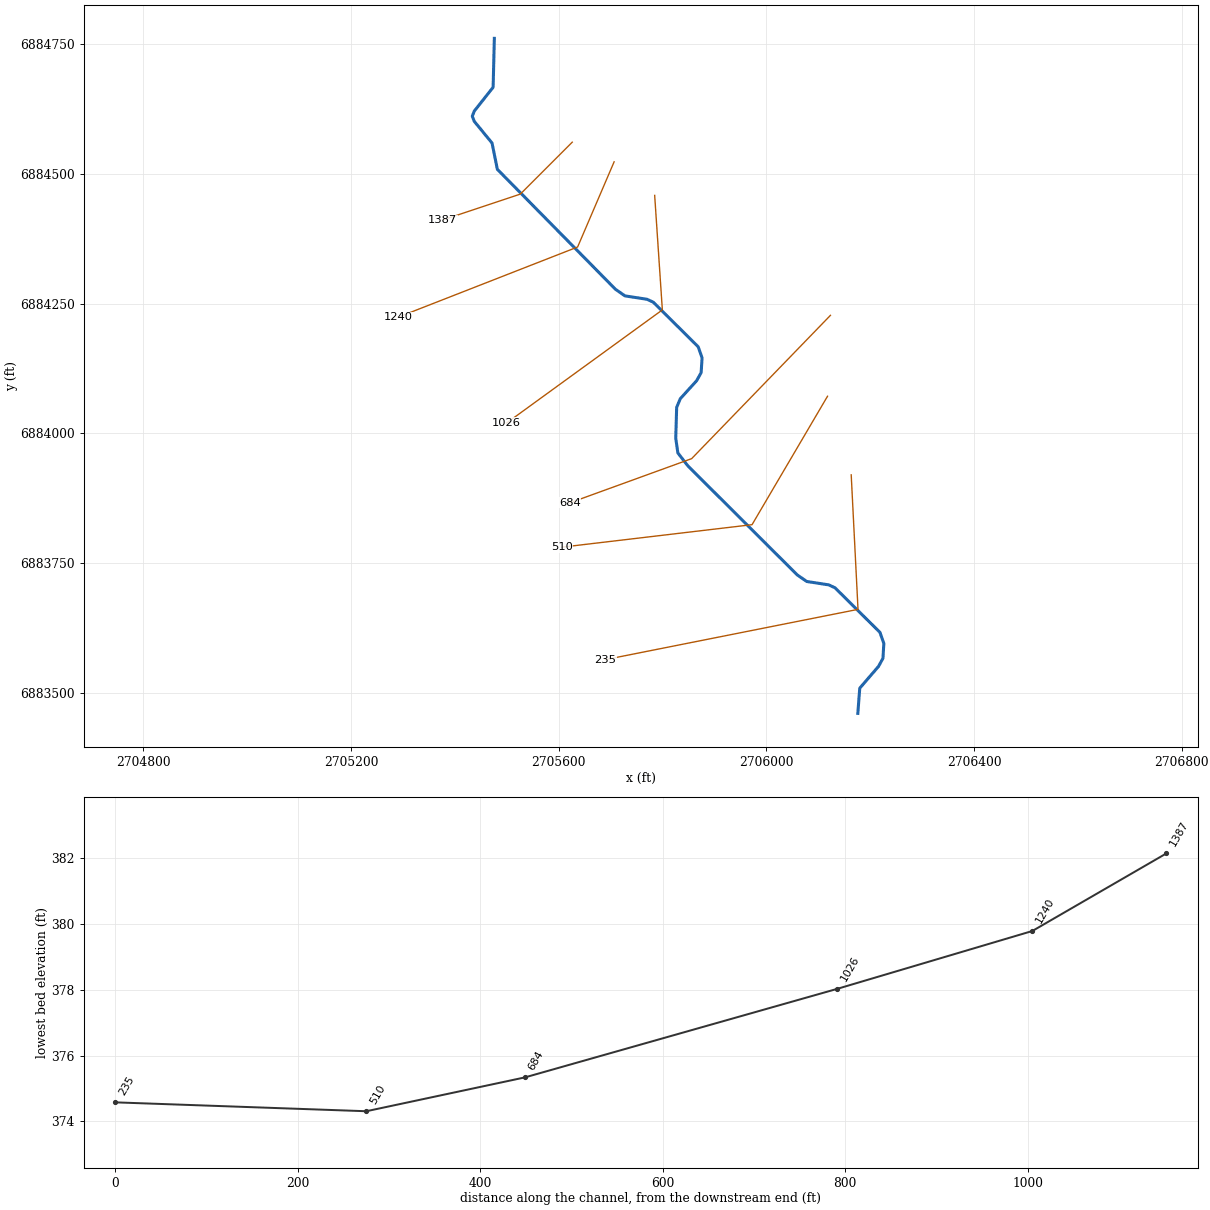
--- CCT9_2.prj (project) ---

Proj Title=CCT9_2 Base Level Engineering
Current Plan=p01
Default Exp/Contr=0.3,0.1
English Units
Geom File=g01
Flow File=f01
Plan File=p01
BEGIN DESCRIPTION:
CCT9_2
END DESCRIPTION:

--- CCT9_2.p01 (plan) ---

Plan Title=Multiple Run
Short Identifier=Multiple
Geom File=g01
Flow File=f01
Subcritical Flow
K Sum by GR= 0
Std Step Tol= 0.01
Critical Tol= 0.01
Num of Std Step Trials= 20
Max Error Tol= 0.3
Flow Tol Ratio= 0.001
Split Flow NTrial= 30
Split Flow Tol= 0.02
Split Flow Ratio= 0.02
Log Output Level= 0
Friction Slope Method= 1
Unsteady Friction Slope Method= 2
Unsteady Bridges Friction Slope Method= 1
Parabolic Critical Depth
Global Vel Dist=  1 , 1 , 1
Global Log Level= 0
CheckData=True
Encroach Param= -1, 0, 0, 0
BEGIN DESCRIPTION:
Multiple Run
END DESCRIPTION:

--- CCT9_2.f01 (steady flow) ---

Flow Title=Multiple
Number of Profiles=7
Profile Names=10-year,25-year,50-year,1pct_min,100-year,1pct_plu,500-year
River Rch & RM= CCT9_2,Reach-1,1387
     101     119     132      73     146     291     176
Boundary for River Rch & Prof#=CCT9_2,Reach-1,1
Up Type=0
Dn Type=3
Dn Slope=0.005
Boundary for River Rch & Prof#=CCT9_2,Reach-1,2
Up Type=0
Dn Type=3
Dn Slope=0.005
Boundary for River Rch & Prof#=CCT9_2,Reach-1,3
Up Type=0
Dn Type=3
Dn Slope=0.005
Boundary for River Rch & Prof#=CCT9_2,Reach-1,4
Up Type=0
Dn Type=3
Dn Slope=0.005
Boundary for River Rch & Prof#=CCT9_2,Reach-1,5
Up Type=0
Dn Type=3
Dn Slope=0.005
Boundary for River Rch & Prof#=CCT9_2,Reach-1,6
Up Type=0
Dn Type=3
Dn Slope=0.005
Boundary for River Rch & Prof#=CCT9_2,Reach-1,7
Up Type=0
Dn Type=3
Dn Slope=0.005

--- CCT9_2.g01 (geometry) ---

Geom Title=Existing Conditions

River Reach=CCT9_2,Reach-1
Reach XY= 30
      2705476.00      6884761.00      2705473.66      6884666.77
      2705437.38      6884620.91      2705433.48      6884610.99
      2705437.40      6884601.08      2705471.55      6884559.35
      2705481.81      6884508.71      2705709.33      6884277.65
      2705727.65      6884264.98      2705769.96      6884258.47
      2705782.07      6884252.85      2705868.53      6884167.07
      2705876.05      6884145.67      2705874.22      6884117.14
      2705865.44      6884101.48      2705834.14      6884067.05
      2705827.12      6884050.45      2705825.33      6883990.92
      2705829.46      6883962.50      2705848.84      6883937.48
      2706059.33      6883727.65      2706077.65      6883714.98
      2706119.96      6883708.47      2706132.07      6883702.85
      2706218.53      6883617.08      2706226.10      6883595.68
      2706224.40      6883567.10      2706215.78      6883551.38
      2706179.69      6883509.51      2706176.00      6883461.00

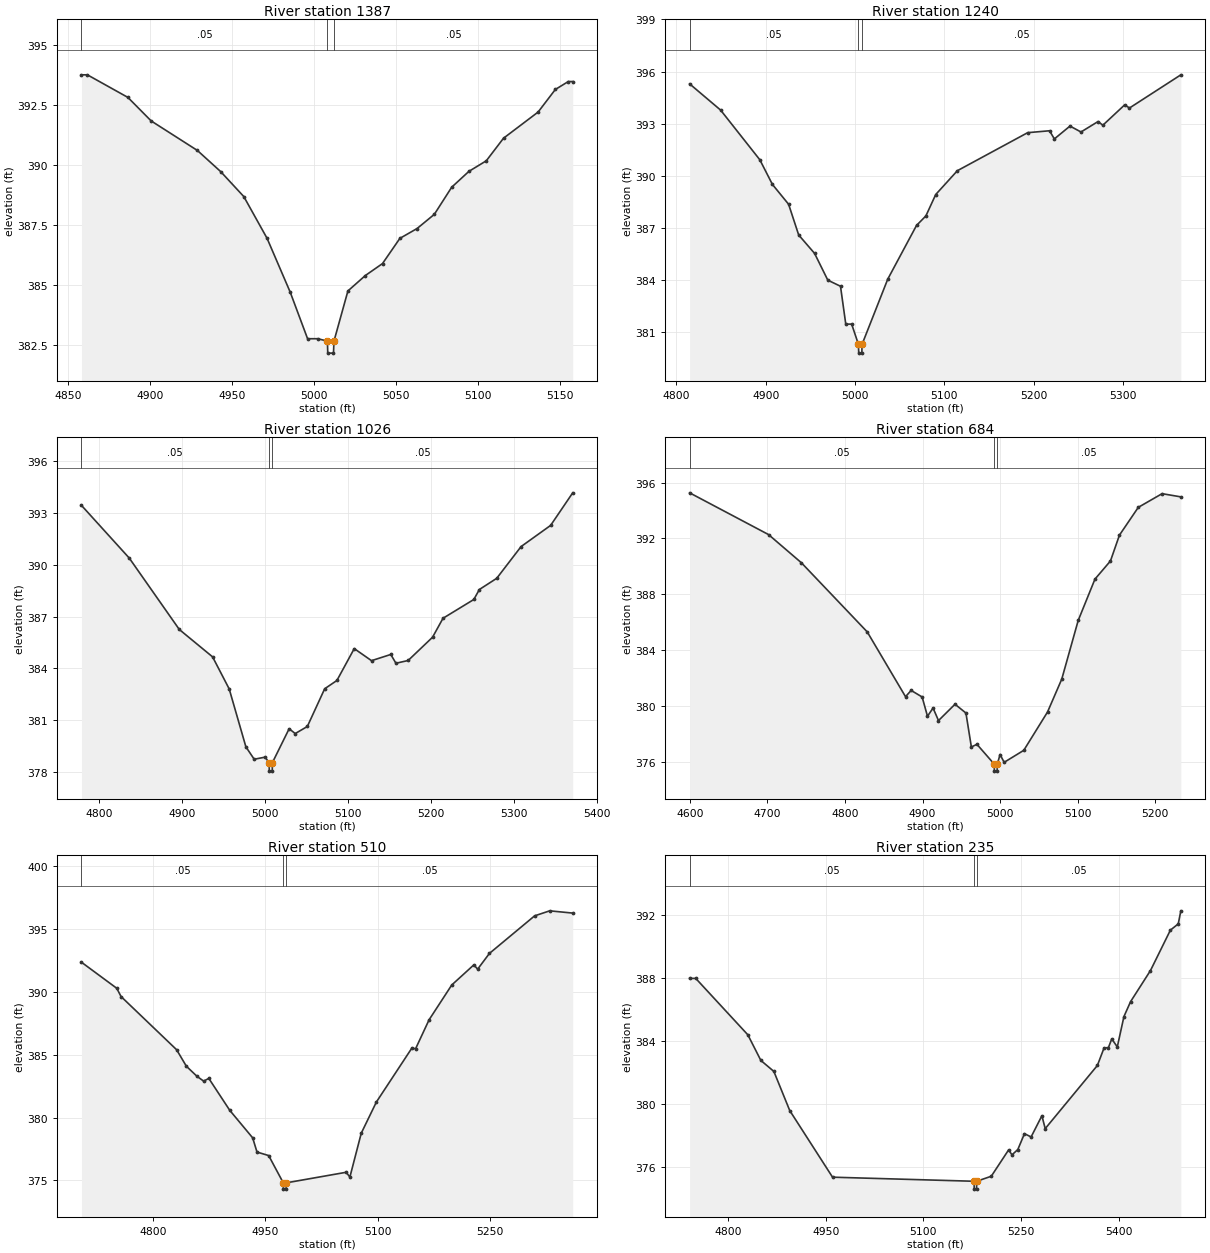
Type RM Length L Ch R = 1,1387,147,147,147
BEGIN DESCRIPTION:
CCT9_2 3.0
END DESCRIPTION:
XS GIS Cut Line= 3
      2705626.02      6884561.02      2705526.00      6884461.00
      2705375.97      6884410.99
#Sta/Elev= 29
  4858.3  393.74  4861.9  393.74  4886.6  392.80  4900.8  391.82  4929.0  390.59
  4943.2  389.71  4957.3  388.67  4971.5  386.93  4985.6  384.69  4996.2  382.75
  5002.4  382.75  5008.3  382.65  5008.5  382.15  5012.0  382.15  5012.3  382.65
  5020.8  384.74  5031.4  385.38  5041.9  385.88  5052.5  386.93  5063.0  387.34
  5073.5  387.93  5084.1  389.06  5094.6  389.72  5105.2  390.16  5115.7  391.10
  5136.8  392.19  5147.3  393.13  5155.2  393.46  5157.9  393.46
#Mann=3,-1,0
  4858.3    0.05       0  5008.3    0.04       0  5012.3    0.05       0
Bank Sta=5008.3,5012.3
Exp/Cntr=0.3,0.1

Type RM Length L Ch R = 1,1240,214,214,214
BEGIN DESCRIPTION:
Mapping XS e457ae68
END DESCRIPTION:
XS GIS Cut Line= 3
      2705706.66      6884523.21      2705636.34      6884359.13
      2705290.46      6884223.89
#Sta/Elev= 30
  4814.9  395.29  4849.6  393.78  4893.5  390.92  4907.6  389.50  4925.7  388.36
  4937.0  386.59  4954.8  385.53  4969.6  383.99  4983.8  383.64  4989.7  381.46
  4996.3  381.46  5003.9  380.29  5004.2  379.79  5007.7  379.79  5007.9  380.29
  5036.7  384.05  5068.9  387.14  5079.4  387.69  5090.4  388.92  5114.6  390.29
  5193.3  392.48  5217.8  392.59  5223.2  392.12  5240.7  392.86  5253.0  392.52
  5272.1  393.12  5277.5  392.91  5301.9  394.08  5307.3  393.90  5364.8  395.81
#Mann=3,-1,0
  4814.9    0.05       0  5003.9    0.04       0  5007.9    0.05       0
Bank Sta=5003.9,5007.9
Exp/Cntr=0.3,0.1

Type RM Length L Ch R = 1,1026,342,342,342
BEGIN DESCRIPTION:
CCT9_2 2.0
END DESCRIPTION:
XS GIS Cut Line= 3
      2705784.78      6884458.51      2705799.53      6884238.01
      2705499.65      6884020.25
#Sta/Elev= 30
  4779.0  393.45  4836.6  390.39  4896.8  386.25  4936.9  384.66  4956.9  382.80
  4977.0  379.44  4987.0  378.72  5000.0  378.84  5005.0  378.53  5005.2  378.03
  5008.7  378.03  5009.0  378.53  5029.1  380.49  5036.4  380.21  5051.0  380.62
  5071.9  382.81  5086.6  383.29  5107.5  385.14  5128.3  384.44  5151.5  384.80
  5157.7  384.29  5172.4  384.45  5201.8  385.80  5214.4  386.90  5251.5  387.99
  5258.2  388.57  5279.1  389.22  5308.4  391.06  5344.0  392.29  5370.6  394.18
#Mann=3,-1,0
  4779.0    0.05       0  5005.0    0.04       0  5009.0    0.05       0
Bank Sta=5005,5009
Exp/Cntr=0.3,0.1

Type RM Length L Ch R = 1,684,174,174,174
BEGIN DESCRIPTION:
Mapping XS 24faaf23
END DESCRIPTION:
XS GIS Cut Line= 3
      2706123.30      6884227.59      2705855.96      6883951.57
      2705621.58      6883866.50
#Sta/Elev= 30
  4599.6  395.27  4701.4  392.28  4743.8  390.26  4828.7  385.31  4878.1  380.67
  4885.3  381.12  4899.5  380.65  4906.4  379.27  4913.6  379.86  4920.6  378.96
  4941.9  380.13  4956.0  379.50  4963.0  377.07  4970.2  377.26  4992.5  375.84
  4992.7  375.34  4996.2  375.34  4996.5  375.84  5000.0  376.53  5005.3  375.97
  5030.6  376.83  5061.2  379.57  5079.6  381.93  5100.8  386.13  5122.4  389.09
  5142.4  390.39  5154.0  392.24  5178.3  394.23  5209.0  395.21  5233.2  394.98
#Mann=3,-1,0
  4599.6    0.05       0  4992.5    0.05       0  4996.5    0.05       0
Bank Sta=4992.5,4996.5
Exp/Cntr=0.3,0.1

Type RM Length L Ch R = 1,510,275,275,275
BEGIN DESCRIPTION:
Mapping XS 81856939
END DESCRIPTION:
XS GIS Cut Line= 3
      2706117.67      6884071.78      2705972.28      6883824.40
      2705605.48      6883781.00
#Sta/Elev= 30
  4704.3  392.36  4751.4  390.29  4757.2  389.63  4831.4  385.40  4844.4  384.09
  4858.7  383.28  4867.6  382.90  4874.4  383.12  4902.4  380.58  4933.0  378.39
  4938.8  377.26  4954.4  376.98  4973.9  374.81  4974.2  374.31  4977.7  374.31
  4977.9  374.81  5057.9  375.65  5062.9  375.27  5078.1  378.76  5098.3  381.24
  5145.7  385.53  5150.7  385.48  5168.7  387.78  5199.0  390.55  5228.5  392.15
  5233.6  391.81  5249.3  393.06  5309.7  396.05  5329.9  396.45  5360.6  396.27
#Mann=3,-1,0
  4704.3    0.05       0  4973.9    0.04       0  4977.9    0.05       0
Bank Sta=4973.9,4977.9
Exp/Cntr=0.3,0.1

Type RM Length L Ch R = 1,235,0,0,0
BEGIN DESCRIPTION:
CCT9_2 1.0
END DESCRIPTION:
XS GIS Cut Line= 3
      2706163.25      6883920.37      2706176.36      6883661.30
      2705690.19      6883564.60
#Sta/Elev= 30
  4740.6  387.99  4750.0  387.99  4830.1  384.40  4850.1  382.77  4870.1  382.07
  4894.5  379.58  4960.3  375.34  5177.9  375.08  5178.1  374.58  5181.6  374.58
  5181.9  375.08  5204.3  375.40  5231.0  377.08  5236.1  376.76  5245.1  377.10
  5255.3  378.11  5265.5  377.90  5282.1  379.25  5287.2  378.43  5367.4  382.45
  5377.6  383.56  5384.4  383.59  5389.5  384.14  5398.0  383.63  5408.2  385.56
  5418.4  386.51  5449.0  388.49  5479.6  391.06  5491.7  391.46  5495.7  392.29
#Mann=3,-1,0
  4740.6    0.05       0  5177.9    0.03       0  5181.9    0.05       0
Bank Sta=5177.9,5181.9
Exp/Cntr=0.3,0.1

Chan Stop Cuts=-1