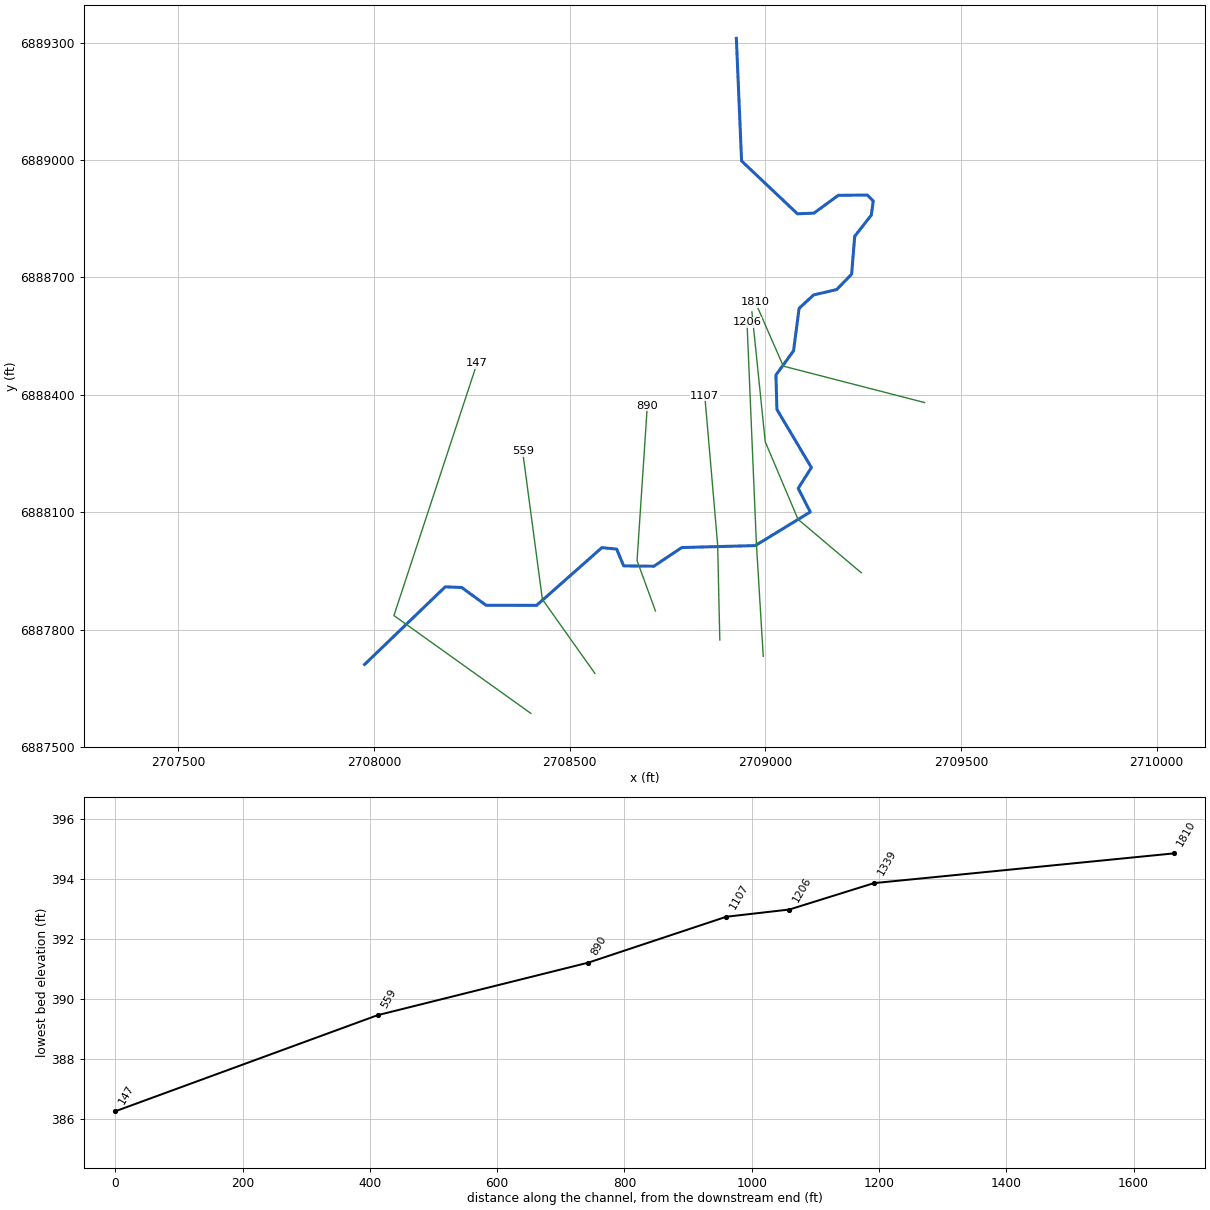
--- CCT9_3.prj (project) ---

Proj Title=CCT9_3 Base Level Engineering
Current Plan=p01
Default Exp/Contr=0.3,0.1
English Units
Geom File=g01
Flow File=f01
Plan File=p01
BEGIN DESCRIPTION:
CCT9_3
END DESCRIPTION:

--- CCT9_3.p01 (plan) ---

Plan Title=Multiple Run
Short Identifier=Multiple
Geom File=g01
Flow File=f01
Subcritical Flow
K Sum by GR= 0
Std Step Tol= 0.01
Critical Tol= 0.01
Num of Std Step Trials= 20
Max Error Tol= 0.3
Flow Tol Ratio= 0.001
Split Flow NTrial= 30
Split Flow Tol= 0.02
Split Flow Ratio= 0.02
Log Output Level= 0
Friction Slope Method= 1
Unsteady Friction Slope Method= 2
Unsteady Bridges Friction Slope Method= 1
Parabolic Critical Depth
Global Vel Dist=  1 , 1 , 1
Global Log Level= 0
CheckData=True
Encroach Param= -1, 0, 0, 0
BEGIN DESCRIPTION:
Multiple Run
END DESCRIPTION:

--- CCT9_3.f01 (steady flow) ---

Flow Title=Multiple
Number of Profiles=7
Profile Names=10-year,25-year,50-year,1pct_min,100-year,1pct_plu,500-year
River Rch & RM= CCT9_3,Reach-1,1810
     483     626     736     430     857    1710    1160
Boundary for River Rch & Prof#=CCT9_3,Reach-1,1
Up Type=0
Dn Type=3
Dn Slope=0.005
Boundary for River Rch & Prof#=CCT9_3,Reach-1,2
Up Type=0
Dn Type=3
Dn Slope=0.005
Boundary for River Rch & Prof#=CCT9_3,Reach-1,3
Up Type=0
Dn Type=3
Dn Slope=0.005
Boundary for River Rch & Prof#=CCT9_3,Reach-1,4
Up Type=0
Dn Type=3
Dn Slope=0.005
Boundary for River Rch & Prof#=CCT9_3,Reach-1,5
Up Type=0
Dn Type=3
Dn Slope=0.005
Boundary for River Rch & Prof#=CCT9_3,Reach-1,6
Up Type=0
Dn Type=3
Dn Slope=0.005
Boundary for River Rch & Prof#=CCT9_3,Reach-1,7
Up Type=0
Dn Type=3
Dn Slope=0.005

--- CCT9_3.g01 (geometry) ---

Geom Title=Existing Conditions

River Reach=CCT9_3,Reach-1
Reach XY= 30
      2708926.00      6889311.00      2708939.37      6888997.68
      2709082.03      6888862.62      2709124.26      6888864.34
      2709186.68      6888909.92      2709260.68      6888910.48
      2709275.87      6888895.32      2709270.81      6888859.23
      2709228.40      6888805.06      2709220.58      6888708.33
      2709182.35      6888669.03      2709123.45      6888655.25
      2709086.39      6888621.10      2709072.14      6888512.60
      2709027.10      6888450.45      2709029.68      6888362.58
      2709117.77      6888214.23      2709084.05      6888160.98
      2709114.90      6888100.68      2708974.45      6888014.75
      2708786.50      6888009.78      2708715.34      6887962.07
      2708637.99      6887962.91      2708620.20      6888005.81
      2708582.39      6888009.48      2708415.56      6887862.04
      2708286.50      6887862.23      2708224.25      6887907.66
      2708182.03      6887909.38      2707976.00      6887711.00

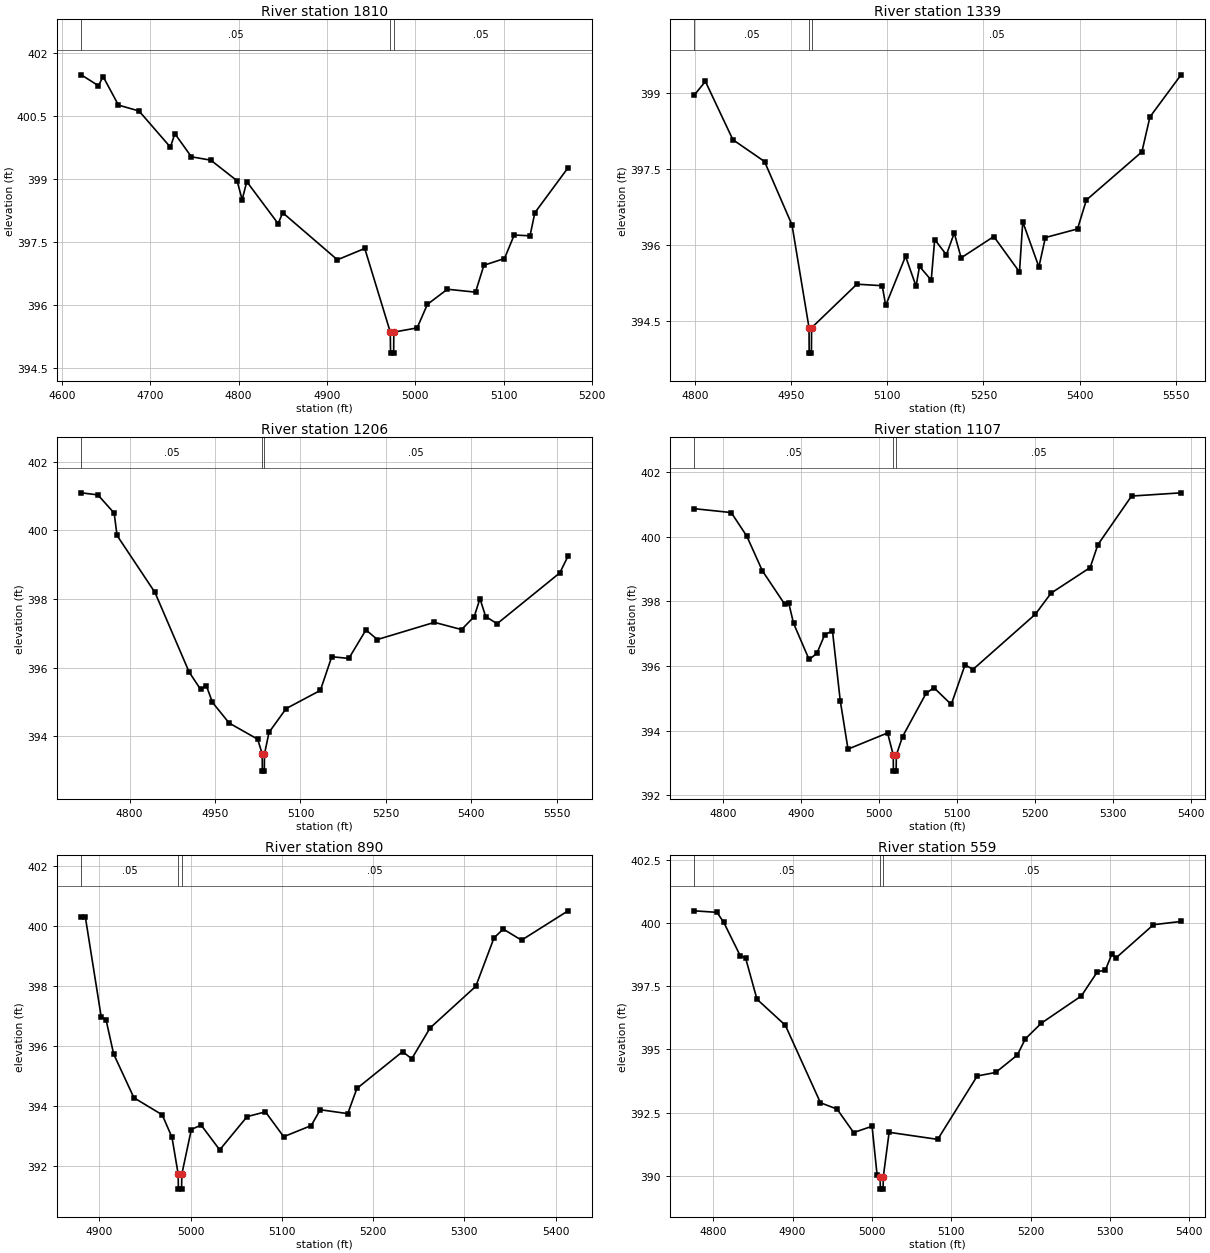
Type RM Length L Ch R = 1,1810,471,471,471
BEGIN DESCRIPTION:
Mapping XS 5bda2842
END DESCRIPTION:
XS GIS Cut Line= 3
      2709406.78      6888380.32      2709045.97      6888473.38
      2708974.42      6888637.00
#Sta/Elev= 30
  4621.8  401.48  4641.3  401.22  4646.5  401.44  4663.9  400.76  4687.2  400.62
  4722.7  399.76  4727.8  400.08  4746.5  399.53  4768.5  399.45  4798.2  398.96
  4804.0  398.51  4809.2  398.94  4844.7  397.94  4849.9  398.20  4911.8  397.08
  4942.8  397.35  4971.7  395.36  4972.0  394.86  4975.5  394.86  4975.7  395.36
  5002.1  395.46  5013.7  396.02  5036.4  396.38  5068.2  396.31  5077.7  396.95
  5101.0  397.11  5112.0  397.67  5129.9  397.65  5135.4  398.20  5173.0  399.27
#Mann=3,-1,0
  4621.8    0.05       0  4971.7    0.03       0  4975.7    0.05       0
Bank Sta=4971.7,4975.7
Exp/Cntr=0.3,0.1

Type RM Length L Ch R = 1,1339,133,133,133
BEGIN DESCRIPTION:
Mapping XS 52d60f88
END DESCRIPTION:
XS GIS Cut Line= 4
      2709245.08      6887945.42      2709083.53      6888082.00
      2708999.78      6888280.10      2708965.79      6888611.84
#Sta/Elev= 30
  4798.4  398.96  4815.8  399.23  4858.7  398.08  4908.1  397.65  4951.0  396.40
  4977.6  394.37  4977.8  393.87  4981.3  393.87  4981.6  394.37  5052.3  395.23
  5091.9  395.20  5097.3  394.81  5128.3  395.78  5144.7  395.19  5150.1  395.58
  5168.4  395.31  5173.8  396.11  5192.1  395.81  5204.3  396.24  5215.1  395.75
  5266.1  396.17  5306.2  395.47  5311.3  396.46  5336.5  395.57  5346.6  396.15
  5396.8  396.32  5410.6  396.89  5497.3  397.84  5509.9  398.53  5558.5  399.36
#Mann=3,-1,0
  4798.4    0.05       0  4977.6    0.04       0  4981.6    0.05       0
Bank Sta=4977.6,4981.6
Exp/Cntr=0.3,0.1

Type RM Length L Ch R = 1,1206,99,99,99
BEGIN DESCRIPTION:
Mapping XS 5efd5a47
END DESCRIPTION:
XS GIS Cut Line= 3
      2708994.72      6887731.88      2708977.07      6888022.41
      2708953.19      6888585.54
#Sta/Elev= 30
  4715.1  401.09  4744.3  401.03  4772.9  400.50  4777.9  399.85  4844.5  398.19
  4904.6  395.87  4924.6  395.37  4934.6  395.48  4945.5  394.99  4974.7  394.39
  5024.8  393.92  5032.8  393.49  5033.0  392.99  5036.5  392.99  5036.8  393.49
  5044.8  394.12  5074.8  394.81  5134.9  395.34  5154.9  396.32  5184.9  396.27
  5214.9  397.10  5235.0  396.82  5335.1  397.32  5382.8  397.11  5405.1  397.49
  5415.1  398.01  5425.1  397.49  5445.2  397.28  5555.3  398.76  5569.8  399.25
#Mann=3,-1,0
  4715.1    0.05       0  5032.8    0.04       0  5036.8    0.05       0
Bank Sta=5032.8,5036.8
Exp/Cntr=0.3,0.1

Type RM Length L Ch R = 1,1107,217,217,217
BEGIN DESCRIPTION:
Mapping XS ca94a6a9
END DESCRIPTION:
XS GIS Cut Line= 3
      2708883.75      6887773.55      2708878.17      6888017.55
      2708845.36      6888397.37
#Sta/Elev= 30
  4762.5  400.86  4810.0  400.74  4830.0  400.01  4850.0  398.94  4878.9  397.90
  4883.9  397.94  4890.0  397.32  4910.0  396.20  4920.0  396.39  4930.0  396.96
  4940.0  397.09  4950.0  394.93  4960.0  393.43  5010.8  393.93  5018.1  393.25
  5018.3  392.75  5021.8  392.75  5022.1  393.25  5030.1  393.82  5060.2  395.15
  5070.3  395.33  5092.6  394.81  5110.4  396.04  5120.4  395.89  5200.7  397.60
  5220.8  398.25  5271.0  399.04  5281.0  399.75  5324.2  401.25  5387.8  401.35
#Mann=3,-1,0
  4762.5    0.05       0  5018.1    0.04       0  5022.1    0.05       0
Bank Sta=5018.1,5022.1
Exp/Cntr=0.3,0.1

Type RM Length L Ch R = 1,890,331,331,331
BEGIN DESCRIPTION:
Mapping XS 6f9b6d7b
END DESCRIPTION:
XS GIS Cut Line= 3
      2708719.24      6887847.65      2708672.28      6887976.48
      2708698.44      6888371.89
#Sta/Elev= 30
  4880.3  400.30  4884.8  400.30  4902.1  396.98  4907.4  396.88  4915.8  395.73
  4938.0  394.27  4969.0  393.70  4979.7  392.95  4986.5  391.72  4986.7  391.22
  4990.2  391.22  4990.5  391.72  5000.9  393.21  5011.6  393.36  5032.0  392.53
  5062.0  393.64  5082.1  393.80  5102.1  392.97  5132.2  393.34  5142.2  393.87
  5172.3  393.74  5182.3  394.58  5232.4  395.81  5242.4  395.57  5262.5  396.60
  5312.6  397.99  5332.6  399.61  5342.7  399.90  5362.7  399.53  5413.7  400.51
#Mann=3,-1,0
  4880.3    0.05       0  4986.5    0.04       0  4990.5    0.05       0
Bank Sta=4986.5,4990.5
Exp/Cntr=0.3,0.1

Type RM Length L Ch R = 1,559,412,412,412
BEGIN DESCRIPTION:
Mapping XS 7ebc845f
END DESCRIPTION:
XS GIS Cut Line= 3
      2708564.43      6887688.30      2708430.31      6887877.43
      2708379.86      6888255.52
#Sta/Elev= 30
  4776.2  400.49  4804.8  400.43  4813.4  400.03  4834.3  398.70  4840.8  398.63
  4855.2  396.99  4890.9  395.96  4935.2  392.89  4956.1  392.64  4977.0  391.71
  5000.2  391.96  5006.6  390.01  5010.4  389.97  5010.6  389.47  5014.1  389.47
  5014.4  389.97  5021.7  391.72  5082.9  391.44  5132.7  393.95  5156.0  394.09
  5183.2  394.78  5193.3  395.42  5213.4  396.04  5263.9  397.12  5284.1  398.08
  5294.1  398.14  5302.2  398.77  5307.3  398.62  5354.7  399.94  5389.5  400.07
#Mann=3,-1,0
  4776.2    0.05       0  5010.4    0.04       0  5014.4    0.05       0
Bank Sta=5010.4,5014.4
Exp/Cntr=0.3,0.1

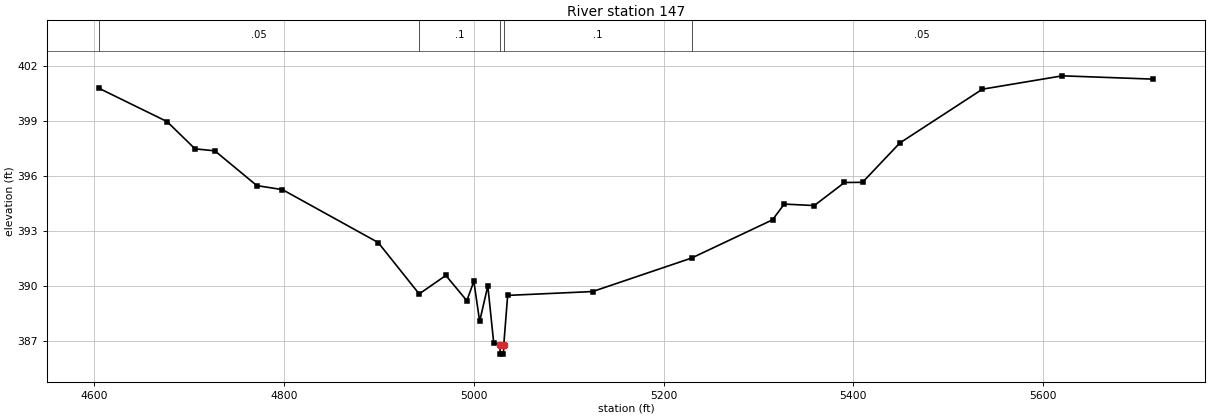
Type RM Length L Ch R = 1,147,0,0,0
BEGIN DESCRIPTION:
CCT9_3 1.0
END DESCRIPTION:
XS GIS Cut Line= 3
      2708400.99      6887586.00      2708051.00      6887836.00
      2708263.54      6888481.40
#Sta/Elev= 30
  4605.7  400.79  4677.0  398.98  4706.5  397.49  4727.4  397.38  4771.6  395.48
  4798.6  395.26  4899.4  392.37  4942.6  389.56  4970.7  390.57  4992.8  389.19
  5000.2  390.25  5006.3  388.06  5014.9  390.00  5021.1  386.89  5027.7  386.77
  5027.9  386.27  5031.4  386.27  5031.7  386.77  5035.8  389.48  5125.3  389.69
  5229.5  391.52  5314.8  393.61  5327.1  394.47  5358.8  394.39  5390.6  395.65
  5409.6  395.66  5448.9  397.81  5535.9  400.75  5620.1  401.48  5715.3  401.30
#Mann=5,-1,0
  4605.7    0.05       0  4942.6     0.1       0  5027.7    0.07       0
  5031.7     0.1       0  5229.5    0.05       0
Bank Sta=5027.7,5031.7
Exp/Cntr=0.3,0.1

Chan Stop Cuts=-1