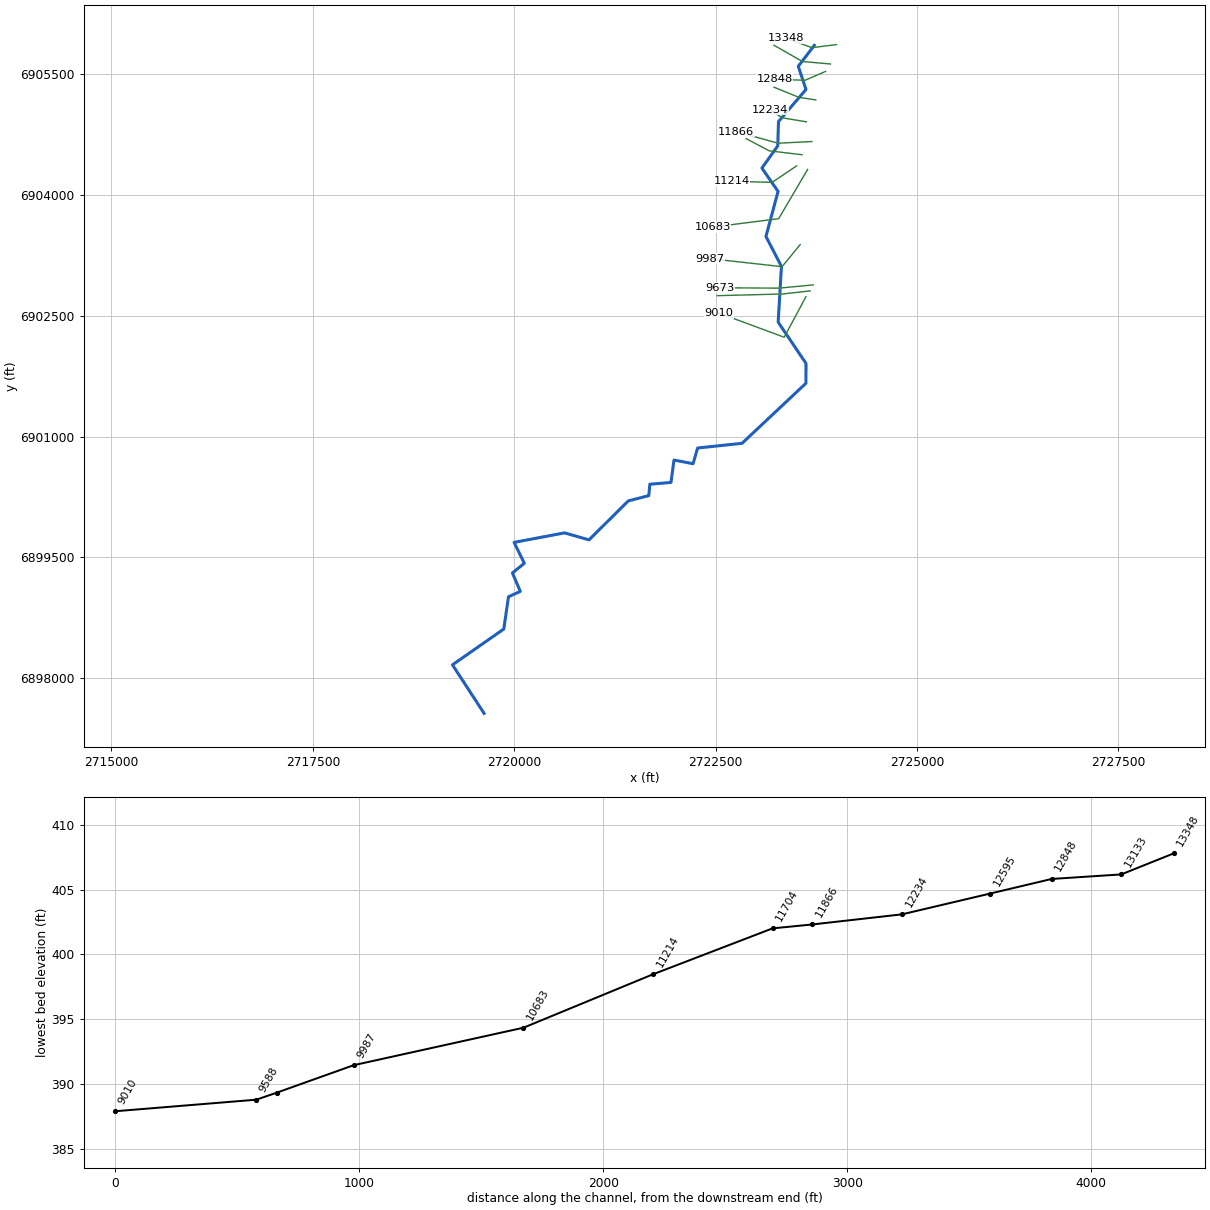
--- Caney T1.prj (project) ---

Proj Title=Caney T1 Base Level Engineering
Current Plan=p01
Default Exp/Contr=0.3,0.1
English Units
Geom File=g01
Flow File=f01
Plan File=p01
Y Axis Title=Elevation
X Axis Title(PF)=Main Channel Distance
X Axis Title(XS)=Station
BEGIN DESCRIPTION:
Caney T1
END DESCRIPTION:
DSS Export Rating Curves= 0
DSS Export Rating Curve Sorted= 0
DSS Export Volume Flow Curves= 0
DXF OffsetX= 0
DXF OffsetY= 0
DXF ScaleX= 1
DXF ScaleY= 10

--- Caney T1.p01 (plan) ---

Plan Title=Multiple Run
Short Identifier=Multiple
Geom File=g01
Flow File=f01
Subcritical Flow
K Sum by GR= 0
Std Step Tol= 0.01
Critical Tol= 0.01
Num of Std Step Trials= 20
Max Error Tol= 0.3
Flow Tol Ratio= 0.001
Split Flow NTrial= 30
Split Flow Tol= 0.02
Split Flow Ratio= 0.02
Log Output Level= 0
Friction Slope Method= 1
Unsteady Friction Slope Method= 2
Unsteady Bridges Friction Slope Method= 1
Parabolic Critical Depth
Global Vel Dist=  1 , 1 , 1
Global Log Level= 0
CheckData=True
Encroach Param= -1, 0, 0, 0
BEGIN DESCRIPTION:
Multiple Run
END DESCRIPTION:

--- Caney T1.f01 (steady flow) ---

Flow Title=Multiple
Number of Profiles=7
Profile Names=10-year,25-year,50-year,1pct_min,100-year,1pct_plu,500-year
River Rch & RM= Caney T1,Reach-1,13348
     512     671     796     469     935    1865    1288
Boundary for River Rch & Prof#=Caney T1,Reach-1,1
Up Type=0
Dn Type=3
Dn Slope=0.005
Boundary for River Rch & Prof#=Caney T1,Reach-1,2
Up Type=0
Dn Type=3
Dn Slope=0.005
Boundary for River Rch & Prof#=Caney T1,Reach-1,3
Up Type=0
Dn Type=3
Dn Slope=0.005
Boundary for River Rch & Prof#=Caney T1,Reach-1,4
Up Type=0
Dn Type=3
Dn Slope=0.005
Boundary for River Rch & Prof#=Caney T1,Reach-1,5
Up Type=0
Dn Type=3
Dn Slope=0.005
Boundary for River Rch & Prof#=Caney T1,Reach-1,6
Up Type=0
Dn Type=3
Dn Slope=0.005
Boundary for River Rch & Prof#=Caney T1,Reach-1,7
Up Type=0
Dn Type=3
Dn Slope=0.005

--- Caney T1.g01 (geometry) ---

Geom Title=Existing Conditions
Program Version=4.10

River Reach=Caney T1        ,Reach-1
Reach XY= 30
        2723726.        6905861.      2723526.94      6905600.51
      2723622.53       6905312.5      2723281.09       6904913.3
      2723272.48      6904612.28      2723075.59        6904336.
      2723275.75      6904045.78       2723125.5      6903485.97
      2723317.99      6903114.33      2723277.22       6902421.5
       2723622.4      6901909.51      2723622.26      6901662.52
      2722828.67       6900916.3      2722277.37      6900857.93
      2722220.51      6900662.96      2721983.95      6900708.19
      2721946.66       6900430.4      2721683.92      6900408.08
      2721670.82      6900266.42      2721416.18      6900200.53
      2720928.44      6899716.47      2720625.91      6899803.69
      2719998.68      6899685.41      2720125.69      6899426.06
      2719977.89      6899305.29      2720075.93      6899076.78
      2719929.03      6899009.61      2719870.54      6898608.55
      2719233.58      6898164.32        2719626.        6897561.

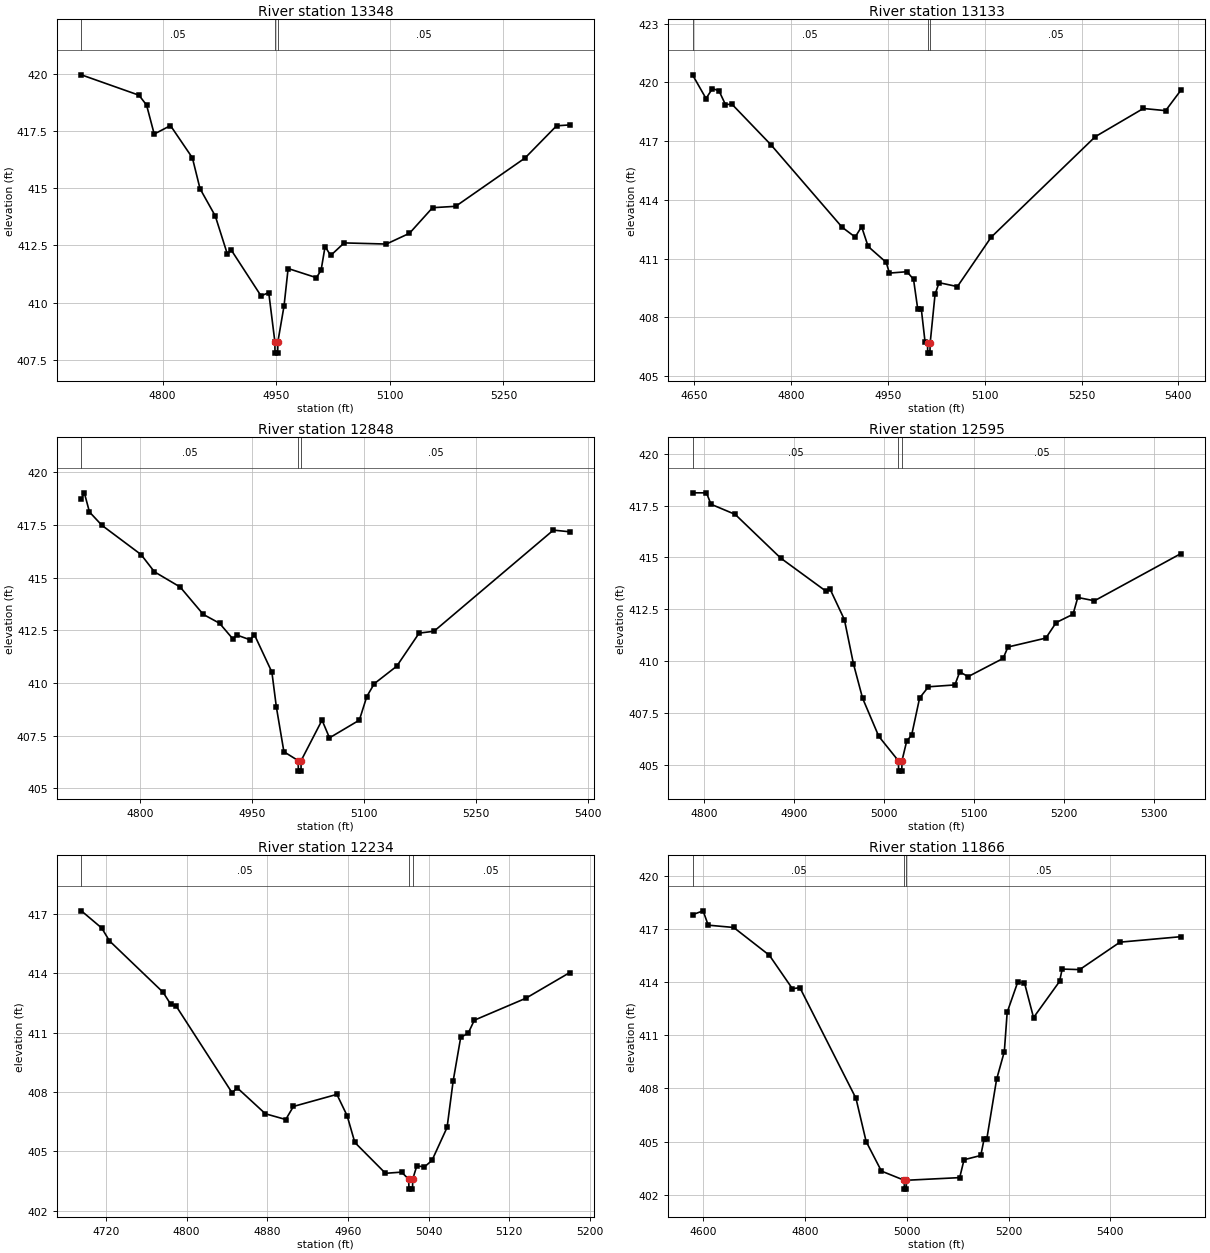
Type RM Length L Ch R = 1 ,13348   ,215,215,215
BEGIN DESCRIPTION:
Caney T1 8.0
END DESCRIPTION:
XS GIS Cut Line= 3
      2724001.44      6905870.33      2723696.58      6905831.73
       2723379.6      6905947.91
#Sta/Elev= 30
  4692.7  419.96  4768.7  419.07  4778.8  418.64  4788.9  417.37  4810.4  417.74
  4839.3  416.33  4849.4  414.98  4869.5  413.79  4885.5  412.12  4890.6   412.3
    4930  410.29  4940.1  410.44  4948.2  408.29  4948.4  407.79  4951.9  407.79
  4952.2  408.29  4960.3  409.85  4965.7  411.49    5003  411.09  5009.2  411.41
  5014.5  412.45  5021.9  412.06  5039.7  412.61  5095.4  412.56  5125.9  413.03
  5156.4  414.15  5186.9  414.21  5278.4  416.32  5320.1  417.73  5337.6  417.77
#Mann= 3 ,-1 , 0
  4692.7     .05       0  4948.2     .04       0  4952.2     .05       0
Bank Sta=4948.2,4952.2
XS Rating Curve= 0 ,0
Exp/Cntr=0.3,0.1

Type RM Length L Ch R = 1 ,13133   ,285,285,285
BEGIN DESCRIPTION:
Mapping XS e455cab1
END DESCRIPTION:
XS GIS Cut Line= 3
      2723926.79        6905629.       2723577.8      6905660.25
      2723225.37      6905861.64
#Sta/Elev= 30
  4647.7  420.39  4668.6  419.18  4678.6  419.69  4688.7  419.57  4698.7  418.87
  4708.7  418.89    4769  416.82  4879.4   412.6  4899.5   412.1  4909.5  412.63
  4919.6  411.62  4947.5  410.81  4952.6  410.26  4979.8  410.33  4989.9  409.94
  4996.5   408.4    5002   408.4  5007.8  406.72  5011.6  406.67  5011.8  406.17
  5015.3  406.17  5015.6  406.67  5023.2  409.17  5029.4  409.77  5057.8  409.57
    5110  412.09  5271.3  417.23  5345.7  418.67  5380.2  418.56    5404  419.61
#Mann= 3 ,-1 , 0
  4647.7     .05       0  5011.6     .04       0  5015.6     .05       0
Bank Sta=5011.6,5015.6
XS Rating Curve= 0 ,0
Exp/Cntr=0.3,0.1

Type RM Length L Ch R = 1 ,12848   ,253,253,253
BEGIN DESCRIPTION:
Mapping XS 1c5e496b
END DESCRIPTION:
XS GIS Cut Line= 3
      2723866.01      6905536.99      2723612.52      6905427.61
      2723234.04      6905438.03
#Sta/Elev= 30
    4721  418.74    4725  419.03  4731.9  418.12  4748.5  417.49    4801   416.1
    4819  415.28  4853.4  414.56  4884.4  413.26  4906.2  412.84    4924   412.1
  4929.4  412.28  4947.5  412.05  4952.9   412.3  4976.4  410.52  4982.4  408.86
  4992.5  406.74  5011.6  406.32  5011.9  405.82  5015.4  405.82  5015.6  406.32
  5043.6  408.24  5053.6   407.4  5093.6  408.24  5103.6  409.36  5113.6  409.97
  5143.7   410.8  5173.7  412.37  5193.7  412.46  5353.7  417.26  5375.7  417.18
#Mann= 3 ,-1 , 0
    4721     .05       0  5011.6     .04       0  5015.6     .05       0
Bank Sta=5011.6,5015.6
XS Rating Curve= 0 ,0
Exp/Cntr=0.3,0.1

Type RM Length L Ch R = 1 ,12595   ,361,361,361
BEGIN DESCRIPTION:
Mapping XS 4f809cdc
END DESCRIPTION:
XS GIS Cut Line= 3
      2723742.88      6905183.16      2723535.43      6905214.68
      2723226.82      6905339.96
#Sta/Elev= 30
  4787.5  418.12    4803  418.12    4808  417.57  4834.9  417.08  4885.5  414.97
  4935.3  413.39  4940.3  413.48  4956.3     412  4966.4  409.86  4976.5  408.21
  4994.5  406.37  5016.3  405.19  5016.6  404.69  5020.1  404.69  5020.3  405.19
  5025.6  406.15    5031  406.42  5039.9  408.22  5049.7  408.76  5079.1  408.85
  5084.5  409.48  5093.8  409.25  5132.7  410.13  5138.1  410.68  5180.2  411.11
  5191.7  411.86  5210.4  412.26  5215.7  413.07  5234.2  412.91  5330.4  415.19
#Mann= 3 ,-1 , 0
  4787.5     .05       0  5016.3     .04       0  5020.3     .05       0
Bank Sta=5016.3,5020.3
XS Rating Curve= 0 ,0
Exp/Cntr=0.3,0.1

Type RM Length L Ch R = 1 ,12234   ,368,368,368
BEGIN DESCRIPTION:
Caney T1 6.0
END DESCRIPTION:
XS GIS Cut Line= 3
      2723625.97        6904911.        2723326.        6904961.
      2723175.99      6905061.01
#Sta/Elev= 30
  4695.6  417.16  4715.8  416.29  4723.5  415.64  4776.7  413.04  4784.3  412.43
  4789.3  412.37  4845.1  407.96  4850.2  408.21  4878.1   406.9  4898.3  406.61
  4905.9  407.27    4949  407.88  4959.2   406.8  4966.8  405.45  4997.2  403.89
  5013.2  403.95  5020.2  403.59  5020.5  403.09    5024  403.09  5024.2  403.59
  5028.3  404.27  5035.8  404.21  5043.3  404.54  5058.3  406.21  5064.3  408.55
  5071.8  410.76  5079.3  410.98  5085.3  411.63  5136.4  412.74    5180  414.04
#Mann= 3 ,-1 , 0
  4695.6     .05       0  5020.2     .04       0  5024.2     .05       0
Bank Sta=5020.2,5024.2
XS Rating Curve= 0 ,0
Exp/Cntr=0.3,0.1

Type RM Length L Ch R = 1 ,11866   ,162,162,162
BEGIN DESCRIPTION:
Mapping XS eed13c1f
END DESCRIPTION:
XS GIS Cut Line= 3
      2723696.77      6904665.75      2723277.45      6904644.92
      2722756.62      6904788.15
#Sta/Elev= 30
  4578.9  417.81  4599.7  418.03  4609.7  417.22  4659.8  417.09  4729.9  415.52
  4775.2  413.63  4789.9  413.69  4900.1  407.44  4920.1     405  4950.1  403.33
    4995  402.81  4995.2  402.31  4998.7  402.31    4999  402.81    5104  402.96
  5112.5  403.97  5145.4  404.21  5152.1  405.16  5157.3  405.15  5176.5  408.51
  5191.7  410.08  5197.3   412.3    5218     414  5231.3  413.96  5249.1     412
  5300.2  414.04  5305.4  414.74  5339.8  414.71    5419  416.26  5538.9  416.57
#Mann= 3 ,-1 , 0
  4578.9     .05       0    4995     .04       0    4999     .05       0
Bank Sta=4995,4999
XS Rating Curve= 0 ,0
Exp/Cntr=0.3,0.1

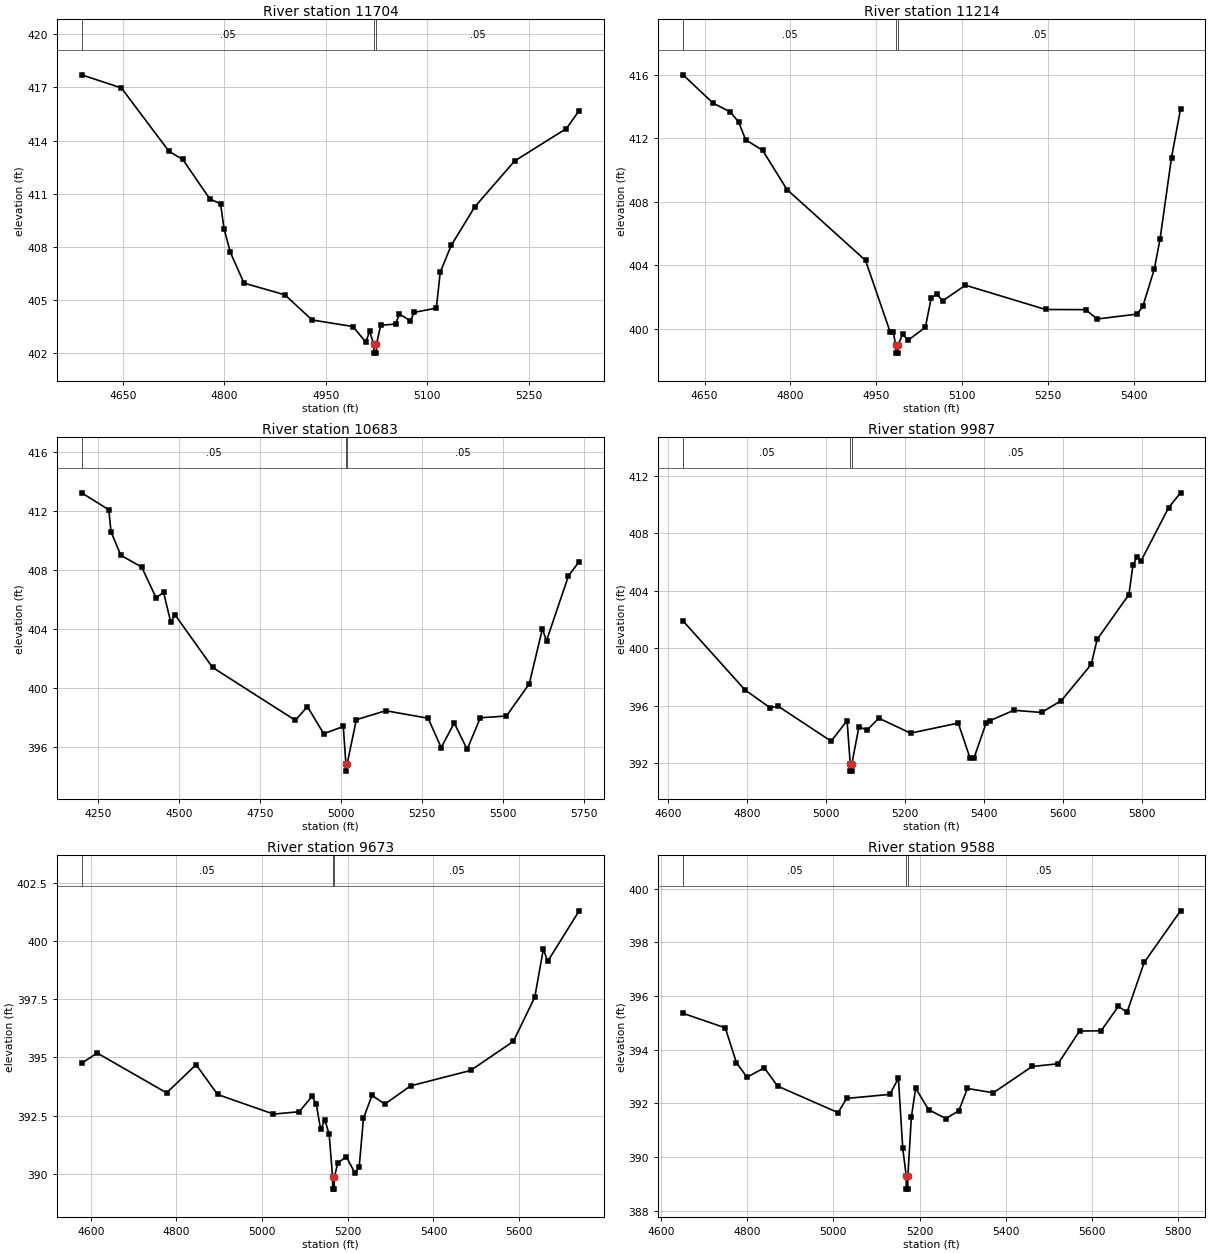
Type RM Length L Ch R = 1 ,11704   ,490,490,490
BEGIN DESCRIPTION:
Mapping XS ae103b2f
END DESCRIPTION:
XS GIS Cut Line= 3
      2723574.32      6904501.67      2723166.29      6904550.21
      2722879.42      6904702.11
#Sta/Elev= 30
  4589.1  417.71  4647.8  416.97  4718.3  413.39  4738.5  412.94  4778.7   410.7
  4794.5  410.44  4799.5  409.04    4809  407.69  4829.1  405.96  4889.5   405.3
  4929.8  403.88  4990.2  403.51  5009.2  402.63  5014.8  403.24    5021  402.51
  5021.2  402.01  5024.7  402.01    5025  402.51  5031.2  403.58  5053.2  403.65
  5058.8  404.22  5075.2  403.83  5080.8  404.31  5113.5  404.55  5119.2  406.57
  5135.5  408.09  5170.1  410.25  5229.2  412.85  5305.8  414.68  5324.6  415.69
#Mann= 3 ,-1 , 0
  4589.1     .05       0    5021     .04       0    5025     .05       0
Bank Sta=5021,5025
XS Rating Curve= 0 ,0
Exp/Cntr=0.3,0.1

Type RM Length L Ch R = 1 ,11214   ,531,531,531
BEGIN DESCRIPTION:
Mapping XS 2603b8f4
END DESCRIPTION:
XS GIS Cut Line= 3
      2723506.61      6904363.66      2723201.93      6904157.94
       2722700.2      6904173.53
#Sta/Elev= 30
  4612.4  416.01  4664.6  414.23  4694.6  413.68  4709.5  413.04  4721.7  411.92
  4751.5  411.25  4794.1  408.78  4931.4  404.31  4974.6  399.78    4980  399.78
    4984  398.97  4984.2  398.47  4987.7  398.47    4988  398.97    4996  399.65
    5006  399.29    5036   400.1    5046  401.92    5056   402.2    5066  401.76
    5106  402.75  5246.1  401.22  5316.1  401.21  5336.1  400.62  5406.2  400.93
  5416.2  401.43  5436.2  403.77  5446.2  405.67  5466.2  410.79    5482  413.86
#Mann= 3 ,-1 , 0
  4612.4     .05       0    4984     .04       0    4988     .05       0
Bank Sta=4984,4988
XS Rating Curve= 0 ,0
Exp/Cntr=0.3,0.1

Type RM Length L Ch R = 1 ,10683   ,696,696,696
BEGIN DESCRIPTION:
Mapping XS 7dcabce6
END DESCRIPTION:
XS GIS Cut Line= 3
      2723642.93       6904319.2      2723283.53      6903707.18
      2722463.26      6903603.02
#Sta/Elev= 30
  4198.1  413.24  4281.9  412.09  4288.8  410.59  4319.1     409  4383.5   408.2
  4427.9  406.12  4451.1  406.48  4473.5  404.44  4485.9  404.98  4602.3  401.39
  4858.2   397.8  4895.4  398.73  4945.7  396.89  5006.2  397.38  5014.2  394.85
  5014.5  394.35  5018.2  394.85  5046.5  397.84  5137.2  398.45  5268.2  397.94
  5308.6  395.95  5348.9  397.62  5388.8  395.83  5429.5  397.97  5510.2  398.09
  5580.7  400.28  5621.1     404  5633.9   403.2  5701.7   407.6  5734.7  408.57
#Mann= 3 ,-1 , 0
  4198.1     .05       0  5014.2     .04       0  5018.2     .05       0
Bank Sta=5014.2,5018.2
XS Rating Curve= 0 ,0
Exp/Cntr=0.3,0.1

Type RM Length L Ch R = 1 ,9987    ,314,314,314
BEGIN DESCRIPTION:
Caney T1 2.0
END DESCRIPTION:
XS GIS Cut Line= 3
      2723550.98      6903385.97        2723326.        6903111.
      2722426.02        6903211.
#Sta/Elev= 30
    4637   401.9  4793.4  397.12  4857.3  395.87  4878.1  395.97  5012.4  393.54
  5052.6  394.97  5060.7  391.96    5061  391.46  5064.5  391.46  5064.7  391.96
  5082.8  394.56    5103   394.3  5133.1  395.14  5213.6   394.1  5334.4   394.8
  5364.6  392.34  5374.6  392.39  5404.8  394.78  5414.9  394.97  5475.2  395.69
  5545.7  395.54    5596  396.37  5671.4  398.88  5686.5  400.62    5767  403.74
  5777.1  405.76  5787.1  406.34  5797.2  406.05  5867.6  409.78  5897.8  410.81
#Mann= 3 ,-1 , 0
    4637     .05       0  5060.7     .04       0  5064.7     .05       0
Bank Sta=5060.7,5064.7
XS Rating Curve= 0 ,0
Exp/Cntr=0.3,0.1

Type RM Length L Ch R = 1 ,9673    ,85,85,85
BEGIN DESCRIPTION:
Mapping XS d0a8d697
END DESCRIPTION:
XS GIS Cut Line= 3
       2723711.9      6902884.37      2723287.62      6902844.16
      2722552.52      6902848.67
#Sta/Elev= 30
  4578.8  394.75  4614.9  395.19  4777.1  393.48  4845.9  394.69  4896.1  393.41
  5026.6  392.57  5086.6  392.67  5116.6  393.33  5126.6  392.99  5136.6  391.91
  5146.6  392.31  5156.6   391.7  5164.6  389.85  5164.9  389.35  5168.4  389.35
  5168.6  389.85  5176.6  390.47  5196.6  390.74  5216.6  390.04  5226.6  390.28
  5236.6  392.39  5256.6  393.37  5286.6     393  5346.6  393.78  5486.6  394.44
  5586.6  395.69  5636.6  397.59  5656.6  399.65  5666.6  399.12  5740.1  401.29
#Mann= 3 ,-1 , 0
  4578.8     .05       0  5164.6     .04       0  5168.6     .05       0
Bank Sta=5164.6,5168.6
XS Rating Curve= 0 ,0
Exp/Cntr=0.3,0.1

Type RM Length L Ch R = 1 ,9588    ,578,578,578
BEGIN DESCRIPTION:
Mapping XS 44500b79
END DESCRIPTION:
XS GIS Cut Line= 3
      2723673.31      6902809.87      2723331.47      6902771.59
      2722521.82      6902750.54
#Sta/Elev= 30
  4651.3  395.35  4749.2  394.81  4775.1  393.51  4799.5  392.97  4839.8  393.32
  4870.4  392.64  5010.8  391.65  5030.8  392.18  5130.8  392.33  5150.8  392.93
  5160.8  390.33  5168.8   389.3  5169.1   388.8  5172.6   388.8  5172.8   389.3
  5180.8  391.48  5190.8  392.56  5220.8  391.76  5260.8  391.43  5290.8  391.72
  5310.9  392.55  5370.9  392.39  5460.9  393.37  5520.9  393.47  5570.9  394.69
    5621   394.7    5661  395.61    5681  395.39    5721  397.25  5805.2  399.17
#Mann= 3 ,-1 , 0
  4651.3     .05       0  5168.8     .04       0  5172.8     .05       0
Bank Sta=5168.8,5172.8
XS Rating Curve= 0 ,0
Exp/Cntr=0.3,0.1

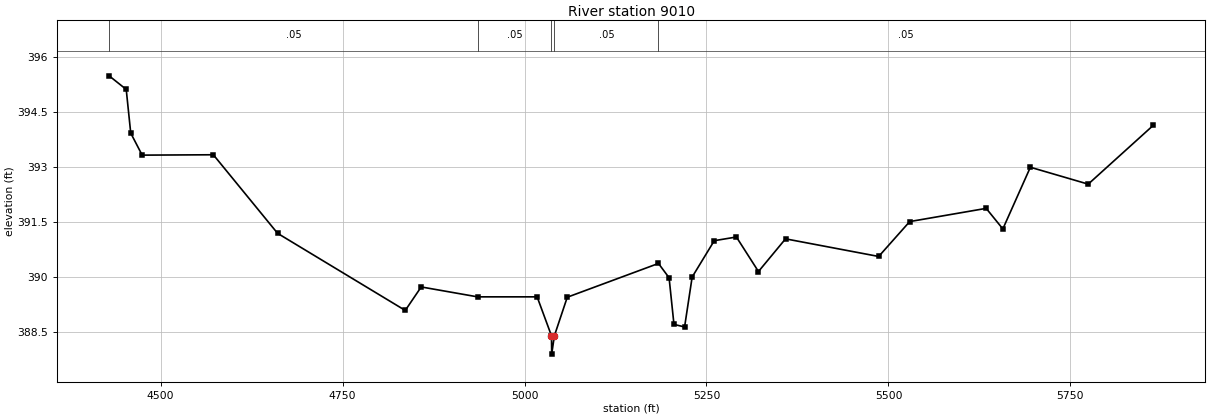
Type RM Length L Ch R = 1 ,9010    ,0,0,0
BEGIN DESCRIPTION:
Caney T1 1.0
END DESCRIPTION:
XS GIS Cut Line= 3
      2723621.84      6902737.22      2723352.18      6902234.13
       2722542.3      6902534.54
#Sta/Elev= 30
  4429.2  395.49  4452.7  395.12  4458.9  393.93  4474.6  393.33  4572.4  393.34
  4660.7   391.2  4836.1   389.1    4858  389.74  4935.4  389.47  5017.3  389.47
    5037  388.41  5037.3  387.91    5041  388.41  5058.7  389.46    5184  390.38
  5198.6  389.99  5205.3  388.72  5219.9  388.65  5230.3  390.01  5260.7     391
  5291.1   391.1  5321.4  390.16  5358.6  391.05  5486.6  390.57  5529.2  391.52
  5634.3  391.88  5657.2  391.32    5695     393  5774.5  392.54  5863.8  394.14
#Mann= 5 ,-1 , 0
  4429.2     .05       0  4935.4     .05       0    5037     .04       0
    5041     .05       0    5184     .05       0
Bank Sta=5037,5041
XS Rating Curve= 0 ,0
Exp/Cntr=0.3,0.1

Chan Stop Cuts=-1
Use User Specified Reach Order=0
Composite Channel Slope=5