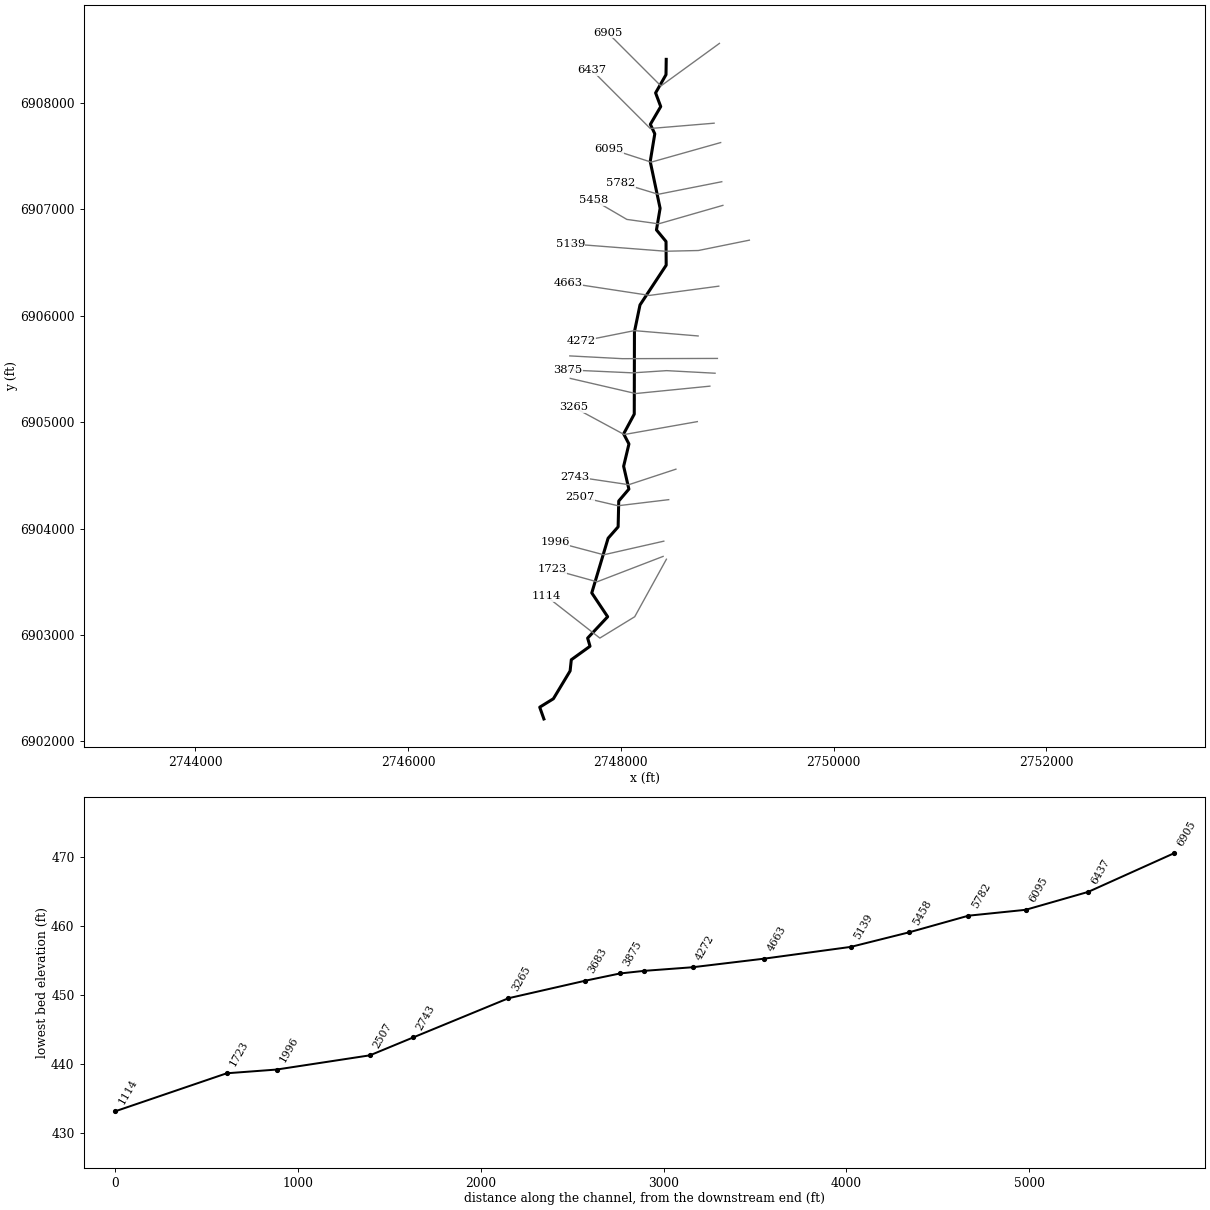
--- Caney T10.prj (project) ---

Proj Title=Caney T10 Base Level Engineering
Current Plan=p01
Default Exp/Contr=0.3,0.1
English Units
Geom File=g01
Flow File=f01
Plan File=p01
BEGIN DESCRIPTION:
Caney T10
END DESCRIPTION:

--- Caney T10.p01 (plan) ---

Plan Title=Multiple Run
Short Identifier=Multiple
Geom File=g01
Flow File=f01
Subcritical Flow
K Sum by GR= 0
Std Step Tol= 0.01
Critical Tol= 0.01
Num of Std Step Trials= 20
Max Error Tol= 0.3
Flow Tol Ratio= 0.001
Split Flow NTrial= 30
Split Flow Tol= 0.02
Split Flow Ratio= 0.02
Log Output Level= 0
Friction Slope Method= 1
Unsteady Friction Slope Method= 2
Unsteady Bridges Friction Slope Method= 1
Parabolic Critical Depth
Global Vel Dist=  1 , 1 , 1
Global Log Level= 0
CheckData=True
Encroach Param= -1, 0, 0, 0
BEGIN DESCRIPTION:
Multiple Run
END DESCRIPTION:

--- Caney T10.f01 (steady flow) ---

Flow Title=Multiple
Number of Profiles=7
Profile Names=10-year,25-year,50-year,1pct_min,100-year,1pct_plu,500-year
River Rch & RM= Caney T10,Reach-1,6905
     525     700     841     503    1003    2001    1427
Boundary for River Rch & Prof#=Caney T10,Reach-1,1
Up Type=0
Dn Type=3
Dn Slope=0.005
Boundary for River Rch & Prof#=Caney T10,Reach-1,2
Up Type=0
Dn Type=3
Dn Slope=0.005
Boundary for River Rch & Prof#=Caney T10,Reach-1,3
Up Type=0
Dn Type=3
Dn Slope=0.005
Boundary for River Rch & Prof#=Caney T10,Reach-1,4
Up Type=0
Dn Type=3
Dn Slope=0.005
Boundary for River Rch & Prof#=Caney T10,Reach-1,5
Up Type=0
Dn Type=3
Dn Slope=0.005
Boundary for River Rch & Prof#=Caney T10,Reach-1,6
Up Type=0
Dn Type=3
Dn Slope=0.005
Boundary for River Rch & Prof#=Caney T10,Reach-1,7
Up Type=0
Dn Type=3
Dn Slope=0.005

--- Caney T10.g01 (geometry) ---

Geom Title=Existing Conditions

River Reach=Caney T10,Reach-1
Reach XY= 30
      2748426.00      6908411.00      2748423.80      6908266.91
      2748326.08      6908095.61      2748374.20      6907967.11
      2748276.80      6907800.30      2748318.41      6907711.01
      2748275.55      6907450.81      2748368.41      6907010.99
      2748334.23      6906807.73      2748424.08      6906699.05
      2748425.61      6906476.16      2748179.40      6906102.56
      2748127.22      6905850.50      2748125.49      6905076.21
      2748025.71      6904890.83      2748075.48      6904795.78
      2748025.60      6904586.00      2748074.96      6904371.44
      2747979.55      6904259.53      2747973.93      6904016.86
      2747879.62      6903909.50      2747726.03      6903395.58
      2747875.45      6903171.64      2747687.24      6902971.00
      2747709.62      6902894.30      2747533.75      6902767.45
      2747522.44      6902662.30      2747365.36      6902401.00
      2747236.85      6902321.38      2747276.00      6902211.00

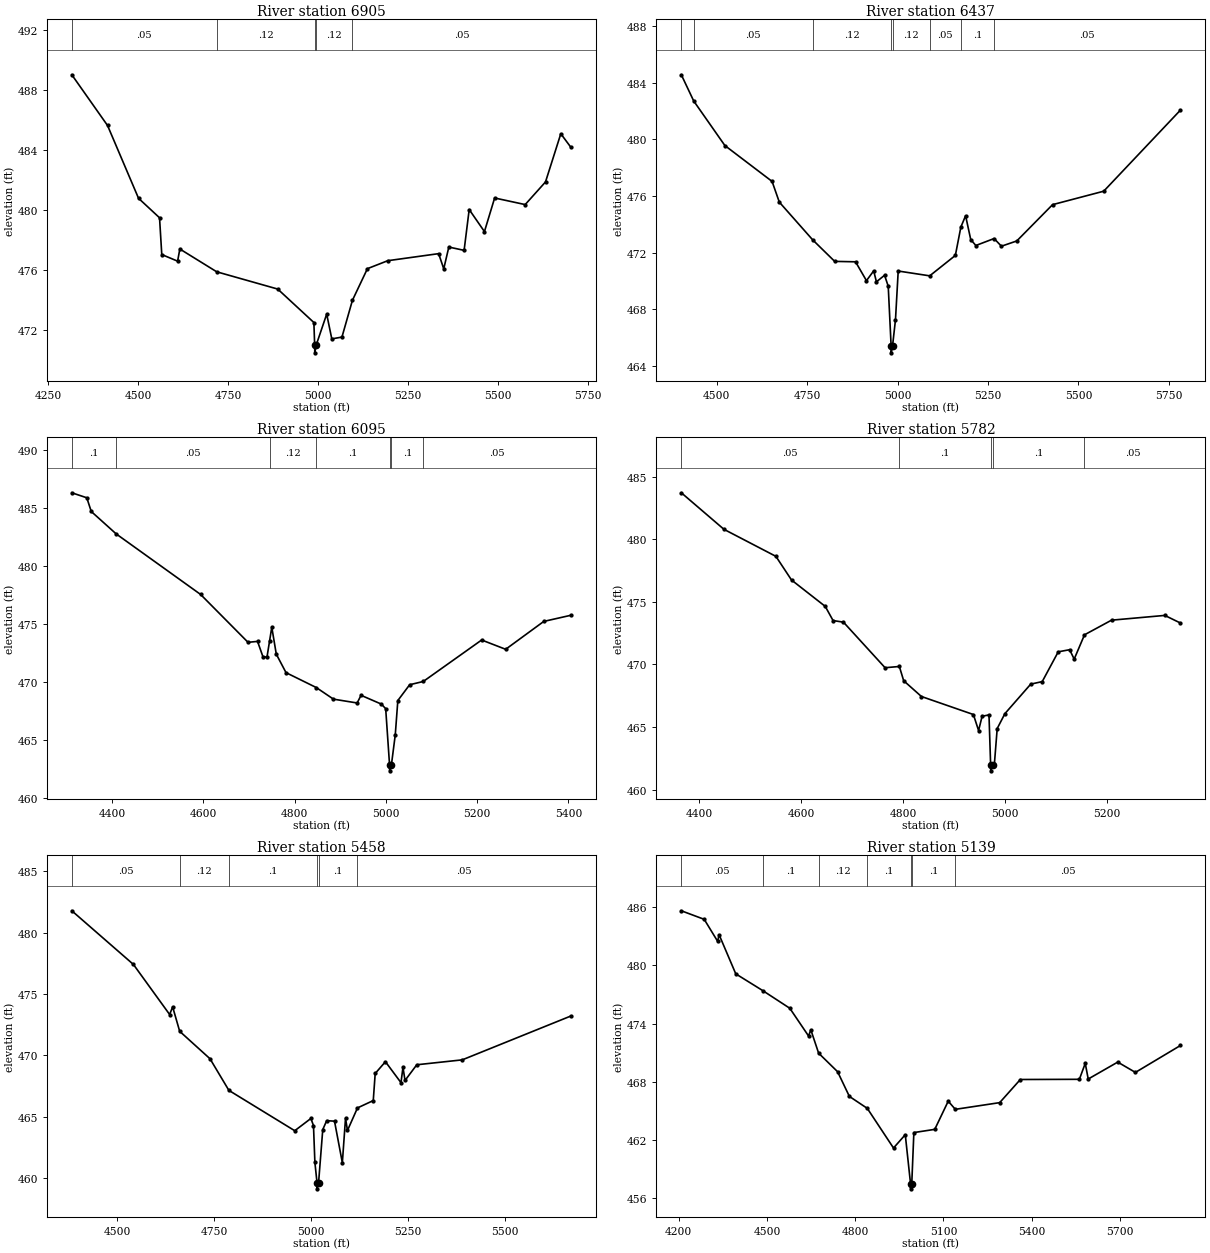
Type RM Length L Ch R = 1,6905,468,468,468
BEGIN DESCRIPTION:
Caney T10 10.0
END DESCRIPTION:
XS GIS Cut Line= 3
      2748925.96      6908560.97      2748376.00      6908161.00
      2747876.03      6908660.97
#Sta/Elev= 30
  4314.9  489.04  4414.2  485.66  4500.3  480.81  4558.7  479.51  4564.9  477.06
  4608.9  476.62  4615.1  477.43  4717.6  475.91  4887.1  474.76  4987.6  472.53
  4989.8  471.01  4990.1  470.51  4993.8  471.01  5023.2  473.09  5037.4  471.44
  5065.6  471.56  5094.7  474.01  5136.4  476.12  5192.9  476.65  5334.3  477.12
  5348.5  476.11  5362.6  477.56  5405.1  477.34  5419.2  480.06  5461.6  478.59
  5489.9  480.83  5574.8  480.39  5631.3  481.90  5673.8  485.11  5702.0  484.20
#Mann=5,-1,0
  4314.9    0.05       0  4717.6    0.12       0  4989.8    0.07       0
  4993.8    0.12       0  5094.7    0.05       0
Bank Sta=4989.8,4993.8
Exp/Cntr=0.3,0.1

Type RM Length L Ch R = 1,6437,342,342,342
BEGIN DESCRIPTION:
Caney T10 9.0
END DESCRIPTION:
XS GIS Cut Line= 3
      2748876.01      6907811.00      2748276.00      6907761.00
      2747726.00      6908311.00
#Sta/Elev= 30
  4402.2  484.55  4436.5  482.70  4522.6  479.56  4653.1  477.03  4673.1  475.57
  4765.3  472.91  4826.2  471.39  4883.9  471.36  4914.0  470.03  4934.0  470.72
  4941.6  469.95  4964.1  470.41  4974.2  469.64  4982.2  465.44  4982.5  464.94
  4986.2  465.44  4994.3  467.28  5001.8  470.71  5088.9  470.37  5159.8  471.81
  5175.0  473.81  5188.1  474.61  5202.3  472.93  5216.4  472.51  5266.9  473.00
  5287.1  472.46  5329.6  472.83  5428.5  475.39  5570.0  476.34  5782.1  482.06
#Mann=8,-1,0
  4402.2     0.1       0  4436.5    0.05       0  4765.3    0.12       0
  4982.2    0.07       0  4986.2    0.12       0  5088.9    0.05       0
  5175.0     0.1       0  5266.9    0.05       0
Bank Sta=4982.2,4986.2
Exp/Cntr=0.3,0.1

Type RM Length L Ch R = 1,6095,313,313,313
BEGIN DESCRIPTION:
Mapping XS e2a9cada
END DESCRIPTION:
XS GIS Cut Line= 3
      2748937.56      6907628.80      2748284.82      6907444.78
      2747889.98      6907572.93
#Sta/Elev= 30
  4312.1  486.28  4344.9  485.85  4354.7  484.67  4409.3  482.74  4594.2  477.53
  4698.1  473.41  4718.9  473.49  4731.2  472.12  4739.7  472.16  4745.3  473.53
  4750.1  474.71  4760.0  472.39  4781.3  470.80  4847.5  469.52  4885.2  468.52
  4937.1  468.19  4945.6  468.85  4990.3  468.09  4999.6  467.70  5008.1  462.85
  5008.3  462.35  5012.1  462.85  5020.6  465.45  5026.2  468.40  5052.1  469.76
  5081.9  470.04  5209.8  473.61  5262.4  472.81  5345.9  475.21  5405.4  475.74
#Mann=7,-1,0
  4312.1     0.1       0  4409.3    0.05       0  4745.3    0.12       0
  4847.5     0.1       0  5008.1    0.07       0  5012.1     0.1       0
  5081.9    0.05       0
Bank Sta=5008.1,5012.1
Exp/Cntr=0.3,0.1

Type RM Length L Ch R = 1,5782,324,324,324
BEGIN DESCRIPTION:
Mapping XS 32a90b40
END DESCRIPTION:
XS GIS Cut Line= 3
      2748947.97      6907260.75      2748350.79      6907142.70
      2747996.62      6907250.34
#Sta/Elev= 30
  4365.2  483.72  4448.8  480.80  4550.7  478.64  4581.3  476.75  4647.5  474.64
  4662.8  473.51  4683.2  473.38  4764.8  469.74  4792.8  469.84  4801.3  468.70
  4836.1  467.44  4938.0  466.00  4948.2  464.72  4955.1  465.86  4968.6  465.97
  4971.8  462.00  4972.1  461.50  4975.8  462.00  4979.1  462.00  4984.7  464.88
  4999.8  466.07  5050.5  468.43  5073.0  468.63  5104.4  471.01  5126.7  471.18
  5135.7  470.43  5155.9  472.37  5208.9  473.54  5313.4  473.92  5344.1  473.31
#Mann=5,-1,0
  4365.2    0.05       0  4792.8     0.1       0  4971.8    0.07       0
  4975.8     0.1       0  5155.9    0.05       0
Bank Sta=4971.8,4975.8
Exp/Cntr=0.3,0.1

Type RM Length L Ch R = 1,5458,319,319,319
BEGIN DESCRIPTION:
Mapping XS 3b50249b
END DESCRIPTION:
XS GIS Cut Line= 4
      2748958.42      6907038.53      2748354.26      6906864.92
      2748055.65      6906906.59      2747747.59      6907086.58
#Sta/Elev= 30
  4383.5  481.78  4542.4  477.40  4635.7  473.32  4643.5  473.94  4661.6  471.95
  4739.8  469.71  4788.5  467.13  4958.3  463.84  4999.9  464.84  5006.6  464.26
  5010.2  461.26  5015.7  459.60  5015.9  459.10  5019.7  459.60  5030.5  463.93
  5040.6  464.66  5060.8  464.62  5081.0  461.23  5089.2  464.86  5094.2  463.86
  5120.0  465.70  5160.7  466.30  5165.7  468.51  5192.1  469.47  5232.2  467.76
  5237.3  469.01  5242.6  467.94  5272.9  469.22  5390.1  469.62  5670.4  473.20
#Mann=6,-1,0
  4383.5    0.05       0  4661.6    0.12       0  4788.5     0.1       0
  5015.7    0.07       0  5019.7     0.1       0  5120.0    0.05       0
Bank Sta=5015.7,5019.7
Exp/Cntr=0.3,0.1

Type RM Length L Ch R = 1,5139,476,476,476
BEGIN DESCRIPTION:
Mapping XS 6143d348
END DESCRIPTION:
XS GIS Cut Line= 4
      2749207.38      6906711.45      2748728.22      6906614.23
      2748422.67      6906607.28      2747523.40      6906676.73
#Sta/Elev= 30
  4208.9  485.60  4286.7  484.72  4332.3  482.46  4337.4  483.13  4394.0  479.11
  4485.5  477.39  4577.6  475.57  4641.3  472.72  4649.1  473.35  4675.6  470.95
  4740.1  469.04  4780.1  466.50  4841.0  465.27  4930.1  461.19  4970.1  462.56
  4988.1  457.49  4988.4  456.99  4992.1  457.49  4999.3  462.78  5070.3  463.11
  5116.1  466.01  5140.2  465.17  5291.0  465.86  5361.2  468.24  5561.8  468.26
  5581.8  469.90  5591.9  468.29  5692.2  470.03  5752.3  468.97  5905.4  471.74
#Mann=7,-1,0
  4208.9    0.05       0  4485.5     0.1       0  4675.6    0.12       0
  4841.0     0.1       0  4988.1    0.07       0  4992.1     0.1       0
  5140.2    0.05       0
Bank Sta=4988.1,4992.1
Exp/Cntr=0.3,0.1

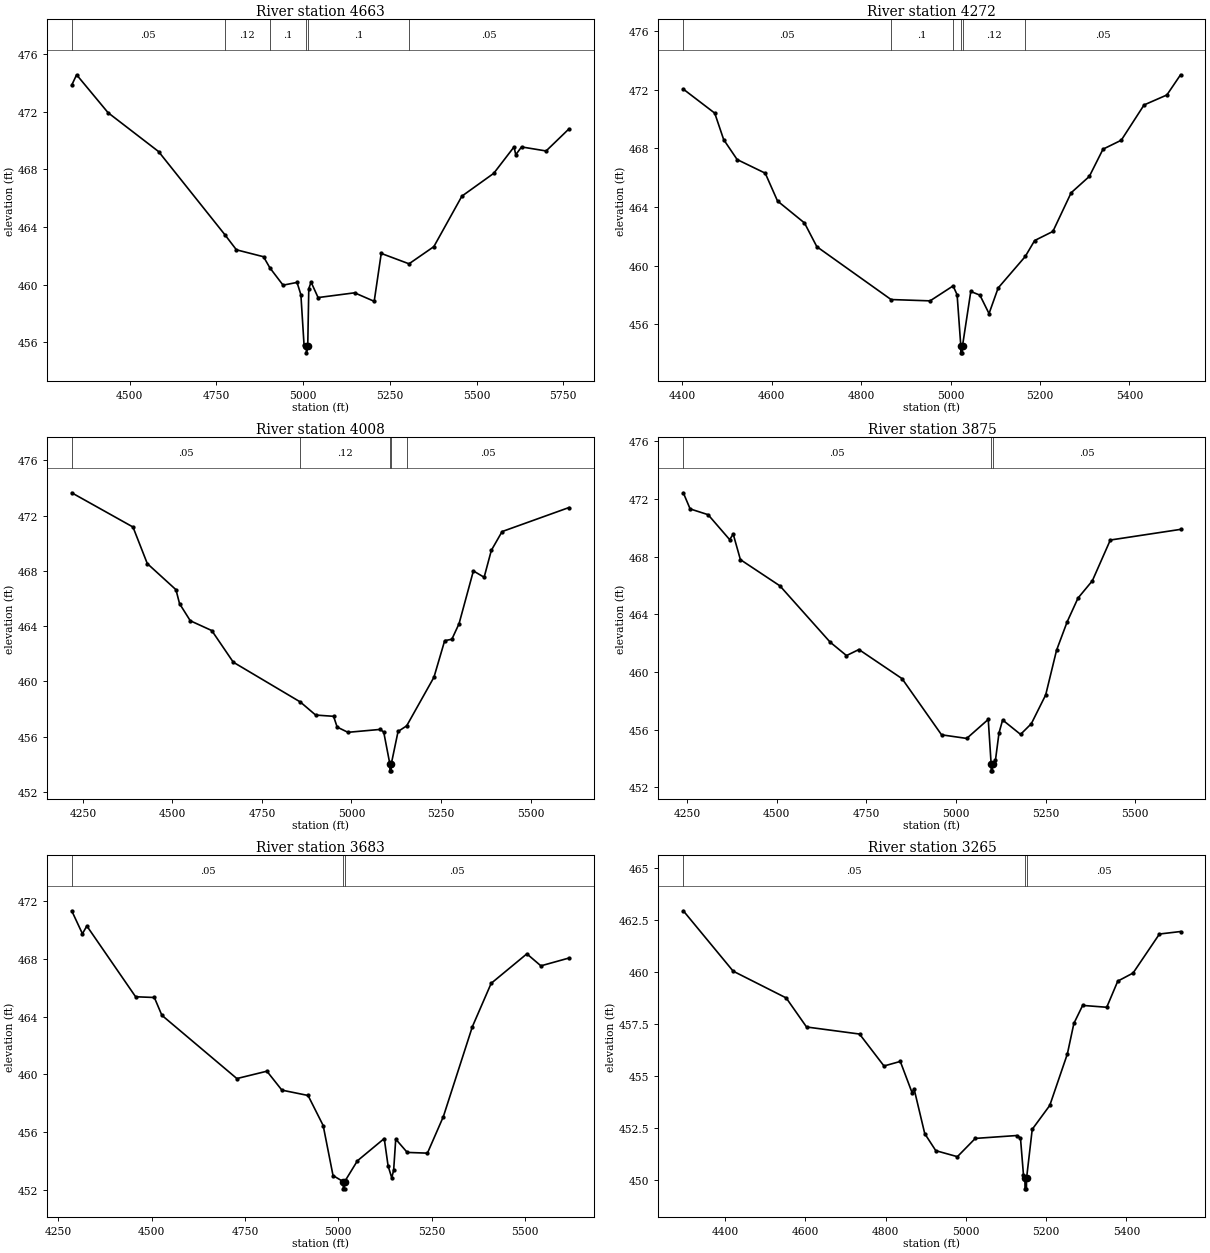
Type RM Length L Ch R = 1,4663,391,391,391
BEGIN DESCRIPTION:
Mapping XS 99895de4
END DESCRIPTION:
XS GIS Cut Line= 3
      2748920.01      6906278.99      2748268.96      6906192.18
      2747500.86      6906309.35
#Sta/Elev= 30
  4332.6  473.83  4346.7  474.55  4437.5  471.92  4583.0  469.23  4773.8  463.48
  4807.5  462.42  4885.7  461.94  4904.0  461.17  4942.0  459.97  4982.3  460.16
  4993.4  459.31  5002.5  455.83  5009.2  455.78  5009.4  455.28  5013.2  455.78
  5016.2  459.73  5022.8  460.18  5043.0  459.11  5148.3  459.44  5204.8  458.85
  5225.1  462.17  5305.2  461.45  5376.8  462.64  5457.7  466.14  5549.5  467.72
  5608.0  469.55  5613.0  469.01  5629.7  469.55  5700.5  469.27  5766.4  470.80
#Mann=6,-1,0
  4332.6    0.05       0  4773.8    0.12       0  4904.0     0.1       0
  5009.2    0.07       0  5013.2     0.1       0  5305.2    0.05       0
Bank Sta=5009.2,5013.2
Exp/Cntr=0.3,0.1

Type RM Length L Ch R = 1,4272,264,264,264
BEGIN DESCRIPTION:
Caney T10 4.0
END DESCRIPTION:
XS GIS Cut Line= 3
      2748726.02      6905811.00      2748126.00      6905861.00
      2747626.00      6905761.00
#Sta/Elev= 30
  4402.3  472.05  4472.6  470.41  4492.6  468.60  4522.7  467.24  4585.5  466.31
  4613.0  464.41  4673.3  462.91  4700.9  461.29  4866.9  457.68  4954.2  457.59
  5005.6  458.61  5014.6  458.01  5022.8  454.54  5023.0  454.04  5026.5  454.04
  5026.8  454.54  5045.2  458.23  5065.6  457.98  5086.0  456.72  5106.4  458.47
  5167.0  460.62  5188.0  461.71  5228.8  462.33  5269.6  464.97  5310.3  466.09
  5340.9  467.95  5381.7  468.56  5432.7  470.97  5483.7  471.65  5514.3  473.03
#Mann=6,-1,0
  4402.3    0.05       0  4866.9     0.1       0  5005.6    0.12       0
  5022.8    0.07       0  5026.8    0.12       0  5167.0    0.05       0
Bank Sta=5022.8,5026.8
Exp/Cntr=0.3,0.1

Type RM Length L Ch R = 1,4008,133,133,133
BEGIN DESCRIPTION:
Mapping XS 1bdb79e1
END DESCRIPTION:
XS GIS Cut Line= 3
      2748906.99      6905599.73      2748012.89      6905597.56
      2747519.58      6905623.52
#Sta/Elev= 30
  4219.0  473.66  4390.0  471.18  4430.0  468.53  4510.0  466.64  4520.0  465.63
  4550.0  464.39  4610.0  463.68  4670.0  461.39  4857.0  458.51  4900.0  457.56
  4950.0  457.47  4960.0  456.69  4990.0  456.31  5080.0  456.52  5090.0  456.33
  5107.1  454.02  5107.3  453.52  5110.8  453.52  5111.1  454.02  5130.0  456.37
  5154.1  456.78  5230.2  460.30  5260.2  462.95  5280.2  463.05  5300.3  464.18
  5340.3  468.00  5370.3  467.54  5390.4  469.49  5420.4  470.85  5607.1  472.59
#Mann=5,-1,0
  4219.0    0.05       0  4857.0    0.12       0  5107.1    0.07       0
  5111.1    0.12       0  5154.1    0.05       0
Bank Sta=5107.1,5111.1
Exp/Cntr=0.3,0.1

Type RM Length L Ch R = 1,3875,192,192,192
BEGIN DESCRIPTION:
Mapping XS db3ab581
END DESCRIPTION:
XS GIS Cut Line= 4
      2748885.01      6905460.70      2748430.13      6905485.00
      2748110.69      6905464.17      2747500.27      6905491.92
#Sta/Elev= 30
  4239.7  472.44  4258.7  471.32  4308.8  470.92  4368.9  469.19  4378.9  469.57
  4398.9  467.80  4509.1  465.98  4649.3  462.07  4694.8  461.14  4729.4  461.56
  4849.7  459.54  4959.9  455.64  5030.1  455.39  5090.1  456.71  5098.1  453.64
  5098.4  453.14  5101.9  453.14  5102.1  453.64  5110.1  453.86  5120.1  455.77
  5130.2  456.67  5180.2  455.67  5210.2  456.41  5250.3  458.41  5280.6  461.51
  5310.3  463.49  5340.4  465.13  5380.4  466.33  5430.5  469.16  5626.4  469.90
#Mann=3,-1,0
  4239.7    0.05       0  5098.1    0.04       0  5102.1    0.05       0
Bank Sta=5098.1,5102.1
Exp/Cntr=0.3,0.1

Type RM Length L Ch R = 1,3683,418,418,418
BEGIN DESCRIPTION:
Mapping XS 7a9e483f
END DESCRIPTION:
XS GIS Cut Line= 3
      2748836.34      6905339.17      2748138.46      6905269.73
      2747523.86      6905412.09
#Sta/Elev= 30
  4285.9  471.32  4314.6  469.73  4326.4  470.27  4457.1  465.37  4507.3  465.32
  4527.4  464.09  4728.4  459.71  4808.8  460.22  4849.0  458.91  4919.1  458.54
  4959.6  456.46  4986.0  453.00  5013.2  452.58  5013.5  452.08  5017.0  452.08
  5017.2  452.58  5051.3  454.02  5123.2  455.56  5133.5  453.67  5143.3  452.84
  5148.4  453.37  5154.0  455.52  5184.8  454.60  5238.9  454.55  5281.6  457.08
  5359.3  463.30  5409.7  466.30  5505.3  468.34  5542.9  467.51  5618.1  468.05
#Mann=3,-1,0
  4285.9    0.05       0  5013.2    0.04       0  5017.2    0.05       0
Bank Sta=5013.2,5017.2
Exp/Cntr=0.3,0.1

Type RM Length L Ch R = 1,3265,522,522,522
BEGIN DESCRIPTION:
Mapping XS 4946fc23
END DESCRIPTION:
XS GIS Cut Line= 3
      2748718.34      6905005.84      2748030.83      6904884.31
      2747555.16      6905141.24
#Sta/Elev= 30
  4295.9  462.96  4420.1  460.05  4552.2  458.76  4602.9  457.36  4734.9  457.02
  4795.9  455.48  4836.5  455.70  4865.7  454.20  4870.8  454.38  4897.4  452.22
  4924.9  451.40  4978.7  451.11  5023.3  451.99  5127.1  452.13  5135.9  452.01
  5143.3  450.24  5147.0  450.06  5147.2  449.56  5150.7  449.56  5151.0  450.06
  5165.2  452.43  5208.9  453.58  5252.7  456.06  5268.9  457.53  5290.8  458.40
  5350.8  458.31  5378.3  459.57  5416.4  459.96  5482.1  461.84  5534.7  461.96
#Mann=3,-1,0
  4295.9    0.05       0  5147.0    0.04       0  5151.0    0.05       0
Bank Sta=5147,5151
Exp/Cntr=0.3,0.1

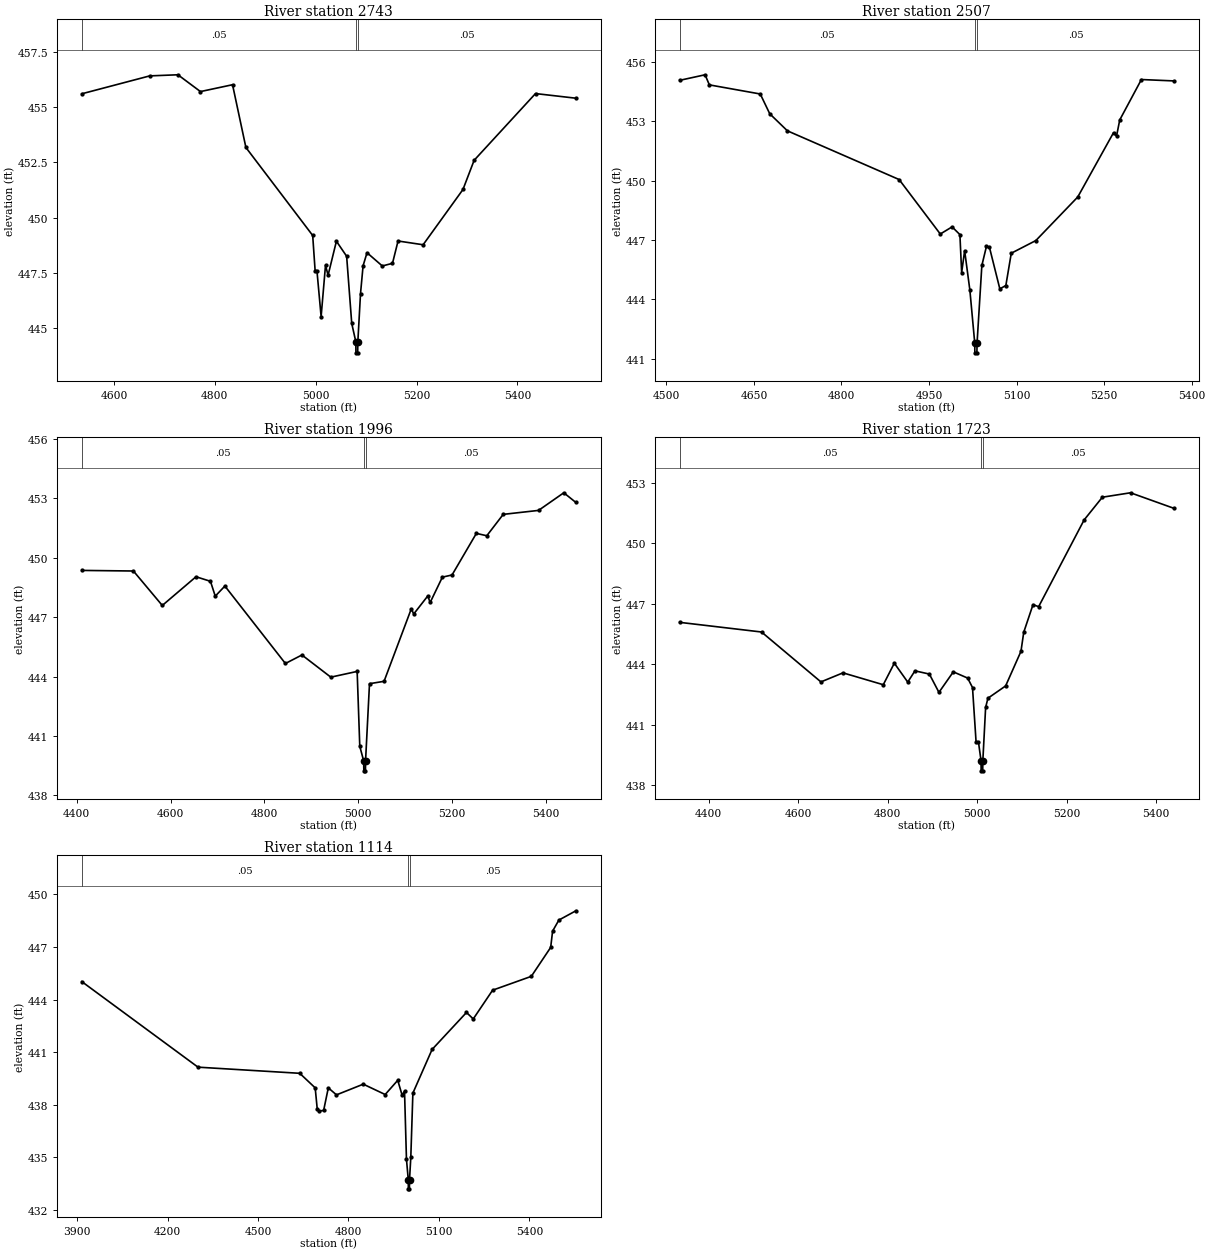
Type RM Length L Ch R = 1,2743,236,236,236
BEGIN DESCRIPTION:
Mapping XS 5e7d82e5
END DESCRIPTION:
XS GIS Cut Line= 3
      2748516.92      6904558.78      2748074.23      6904412.95
      2747566.40      6904488.48
#Sta/Elev= 30
  4536.3  455.60  4671.0  456.41  4726.8  456.46  4771.5  455.70  4835.1  456.01
  4861.6  453.17  4994.0  449.19  4998.8  447.60  5002.4  447.60  5010.7  445.52
  5019.4  447.84  5024.5  447.39  5041.0  448.93  5061.3  448.25  5071.4  445.21
  5079.5  444.38  5079.7  443.88  5083.2  443.88  5083.5  444.38  5088.8  446.56
  5093.9  447.82  5101.7  448.41  5132.0  447.81  5152.2  447.93  5163.2  448.94
  5212.9  448.77  5291.9  451.27  5314.0  452.59  5435.7  455.61  5515.8  455.40
#Mann=3,-1,0
  4536.3    0.05       0  5079.5    0.04       0  5083.5    0.05       0
Bank Sta=5079.5,5083.5
Exp/Cntr=0.3,0.1

Type RM Length L Ch R = 1,2507,511,511,511
BEGIN DESCRIPTION:
Mapping XS 93f9b745
END DESCRIPTION:
XS GIS Cut Line= 3
      2748449.22      6904272.33      2747972.67      6904215.04
      2747615.85      6904298.38
#Sta/Elev= 30
  4522.9  455.06  4566.4  455.34  4573.7  454.83  4660.9  454.37  4677.2  453.37
  4707.4  452.51  4898.8  450.05  4969.3  447.30  4989.5  447.66  5002.9  447.27
  5005.9  445.35  5011.0  446.46  5020.0  444.46  5028.3  441.80  5028.5  441.30
  5032.0  441.30  5032.3  441.80  5040.5  445.71  5048.4  446.68  5053.5  446.63
  5071.3  444.53  5081.6  444.70  5090.9  446.33  5133.0  446.97  5204.8  449.17
  5266.1  452.42  5271.2  452.24  5276.7  453.06  5313.8  455.10  5369.3  455.03
#Mann=3,-1,0
  4522.9    0.05       0  5028.3    0.04       0  5032.3    0.05       0
Bank Sta=5028.3,5032.3
Exp/Cntr=0.3,0.1

Type RM Length L Ch R = 1,1996,273,273,273
BEGIN DESCRIPTION:
Mapping XS eabe0768
END DESCRIPTION:
XS GIS Cut Line= 3
      2748403.17      6903882.13      2747838.99      6903754.10
      2747381.07      6903875.63
#Sta/Elev= 30
  4411.0  449.36  4520.9  449.33  4582.4  447.59  4654.2  449.04  4685.0  448.81
  4695.2  448.06  4715.7  448.57  4844.6  444.66  4879.8  445.09  4941.3  443.97
  4997.4  444.26  5003.0  440.48  5011.3  439.74  5011.6  439.24  5015.1  439.24
  5015.3  439.74  5023.7  443.64  5054.7  443.76  5112.7  447.42  5117.9  447.16
  5147.8  448.07  5152.9  447.74  5178.9  449.02  5199.5  449.13  5251.3  451.23
  5273.5  451.11  5308.5  452.19  5383.7  452.39  5437.5  453.28  5463.3  452.79
#Mann=3,-1,0
  4411.0    0.05       0  5011.3    0.04       0  5015.3    0.05       0
Bank Sta=5011.3,5015.3
Exp/Cntr=0.3,0.1

Type RM Length L Ch R = 1,1723,609,609,609
BEGIN DESCRIPTION:
Mapping XS 4219072d
END DESCRIPTION:
XS GIS Cut Line= 3
      2748396.68      6903738.90      2747776.05      6903500.19
      2747352.83      6903617.39
#Sta/Elev= 30
  4335.1  446.08  4518.0  445.60  4650.7  443.12  4700.0  443.57  4790.0  442.98
  4814.7  444.05  4844.7  443.11  4860.8  443.67  4893.0  443.51  4914.4  442.60
  4946.5  443.62  4978.6  443.31  4989.4  442.84  4997.4  440.13  5002.7  440.13
  5008.5  439.20  5008.7  438.70  5012.2  438.70  5012.5  439.20  5018.7  441.85
  5023.9  442.31  5063.4  442.92  5097.7  444.64  5103.9  445.59  5124.6  446.96
  5137.2  446.86  5238.8  451.17  5279.6  452.30  5342.5  452.52  5439.2  451.75
#Mann=3,-1,0
  4335.1    0.05       0  5008.5    0.04       0  5012.5    0.05       0
Bank Sta=5008.5,5012.5
Exp/Cntr=0.3,0.1

Type RM Length L Ch R = 1,1114,0,0,0
BEGIN DESCRIPTION:
Mapping XS d24ab77b
END DESCRIPTION:
XS GIS Cut Line= 4
      2748427.61      6903712.37      2748129.78      6903171.79
      2747801.95      6902971.11      2747300.15      6903363.71
#Sta/Elev= 30
  3915.7  445.03  4301.1  440.15  4638.4  439.80  4689.7  438.97  4696.4  437.78
  4702.3  437.65  4717.7  437.68  4733.2  438.97  4760.3  438.57  4849.2  439.18
  4921.8  438.59  4963.5  439.40  4977.9  438.56  4986.0  438.78  4992.4  434.91
  4998.5  433.71  4998.7  433.21  5002.2  433.21  5002.5  433.71  5006.8  435.00
  5013.7  438.67  5077.4  441.16  5191.5  443.27  5213.9  442.90  5278.1  444.54
  5406.5  445.33  5470.7  446.98  5477.1  447.91  5497.9  448.54  5554.4  449.07
#Mann=3,-1,0
  3915.7    0.05       0  4998.5    0.04       0  5002.5    0.05       0
Bank Sta=4998.5,5002.5
Exp/Cntr=0.3,0.1

Chan Stop Cuts=-1