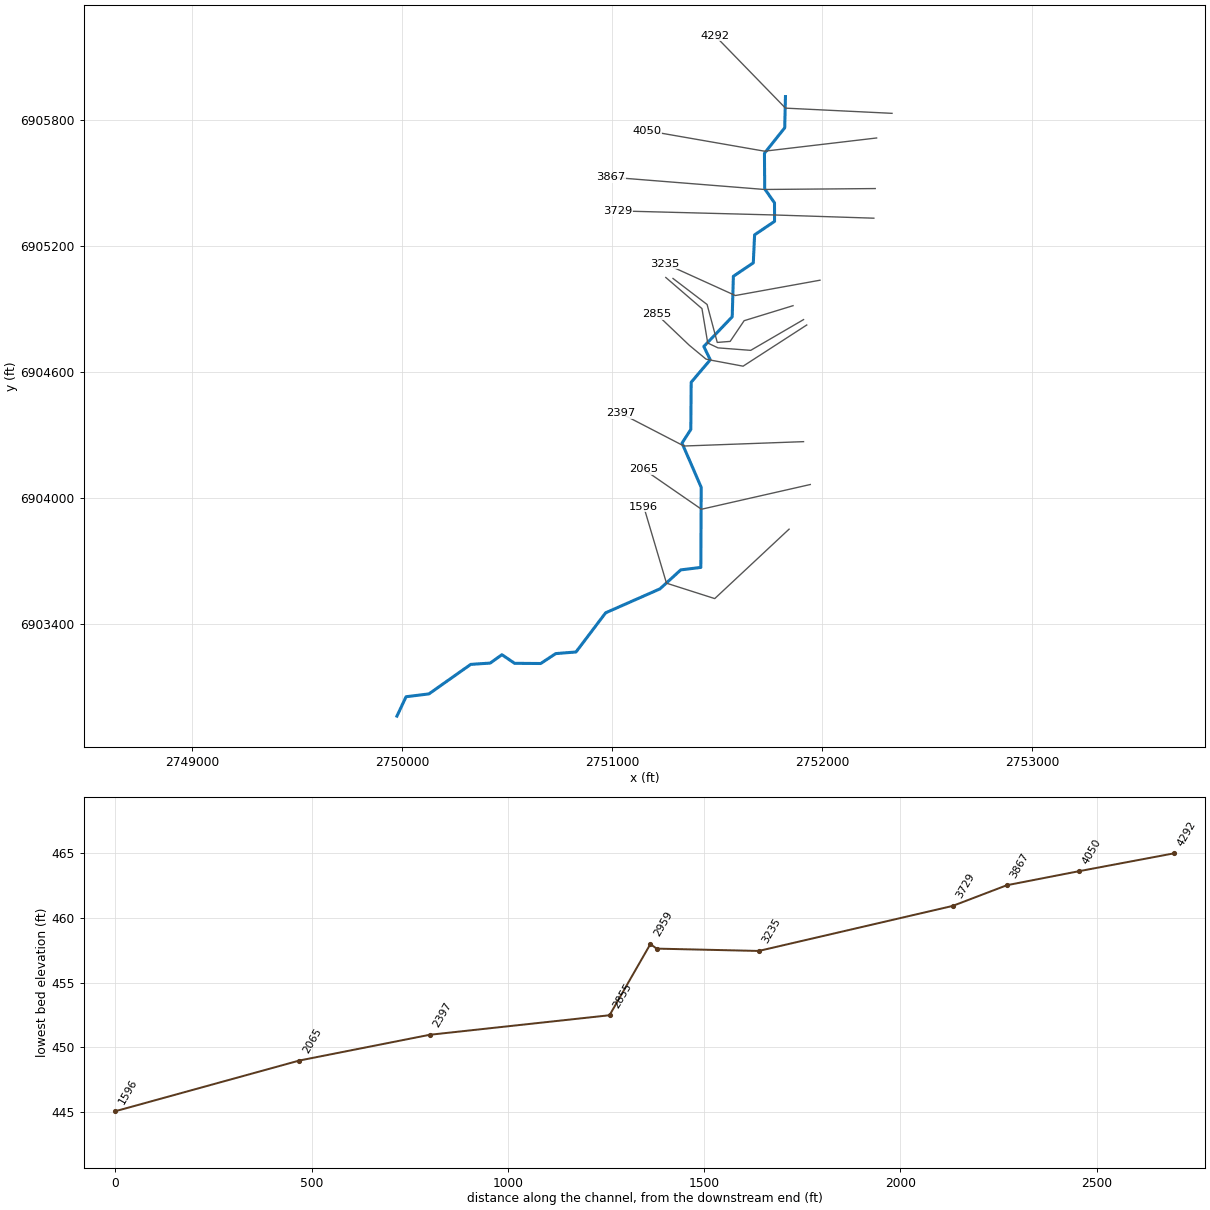
--- Caney T11.prj (project) ---

Proj Title=Caney T11 Base Level Engineering
Current Plan=p01
Default Exp/Contr=0.3,0.1
English Units
Geom File=g01
Flow File=f01
Plan File=p01
BEGIN DESCRIPTION:
Caney T11
END DESCRIPTION:

--- Caney T11.p01 (plan) ---

Plan Title=Multiple Run
Short Identifier=Multiple
Geom File=g01
Flow File=f01
Subcritical Flow
K Sum by GR= 0
Std Step Tol= 0.01
Critical Tol= 0.01
Num of Std Step Trials= 20
Max Error Tol= 0.3
Flow Tol Ratio= 0.001
Split Flow NTrial= 30
Split Flow Tol= 0.02
Split Flow Ratio= 0.02
Log Output Level= 0
Friction Slope Method= 1
Unsteady Friction Slope Method= 2
Unsteady Bridges Friction Slope Method= 1
Parabolic Critical Depth
Global Vel Dist=  1 , 1 , 1
Global Log Level= 0
CheckData=True
Encroach Param= -1, 0, 0, 0
BEGIN DESCRIPTION:
Multiple Run
END DESCRIPTION:

--- Caney T11.f01 (steady flow) ---

Flow Title=Multiple
Number of Profiles=7
Profile Names=10-year,25-year,50-year,1pct_min,100-year,1pct_plu,500-year
River Rch & RM= Caney T11,Reach-1,4292
     207     261     302     175     349     696     464
Boundary for River Rch & Prof#=Caney T11,Reach-1,1
Up Type=0
Dn Type=3
Dn Slope=0.005
Boundary for River Rch & Prof#=Caney T11,Reach-1,2
Up Type=0
Dn Type=3
Dn Slope=0.005
Boundary for River Rch & Prof#=Caney T11,Reach-1,3
Up Type=0
Dn Type=3
Dn Slope=0.005
Boundary for River Rch & Prof#=Caney T11,Reach-1,4
Up Type=0
Dn Type=3
Dn Slope=0.005
Boundary for River Rch & Prof#=Caney T11,Reach-1,5
Up Type=0
Dn Type=3
Dn Slope=0.005
Boundary for River Rch & Prof#=Caney T11,Reach-1,6
Up Type=0
Dn Type=3
Dn Slope=0.005
Boundary for River Rch & Prof#=Caney T11,Reach-1,7
Up Type=0
Dn Type=3
Dn Slope=0.005

--- Caney T11.g01 (geometry) ---

Geom Title=Existing Conditions

River Reach=Caney T11,Reach-1
Reach XY= 30
      2751826.00      6905911.00      2751822.49      6905762.45
      2751725.96      6905641.01      2751727.22      6905471.50
      2751773.84      6905405.02      2751774.09      6905316.72
      2751679.11      6905252.68      2751672.89      6905119.32
      2751578.01      6905055.32      2751572.46      6904862.46
      2751437.24      6904721.00      2751467.98      6904657.67
      2751377.06      6904550.57      2751375.34      6904326.16
      2751333.56      6904261.00      2751424.78      6904050.50
      2751423.07      6903668.97      2751327.58      6903657.34
      2751228.30      6903566.83      2750969.89      6903452.95
      2750828.67      6903266.42      2750731.98      6903258.64
      2750660.78      6903211.51      2750536.44      6903212.37
      2750476.00      6903253.44      2750420.10      6903213.56
      2750327.50      6903207.38      2750128.32      6903066.77
      2750019.55      6903053.36      2749976.00      6902961.00

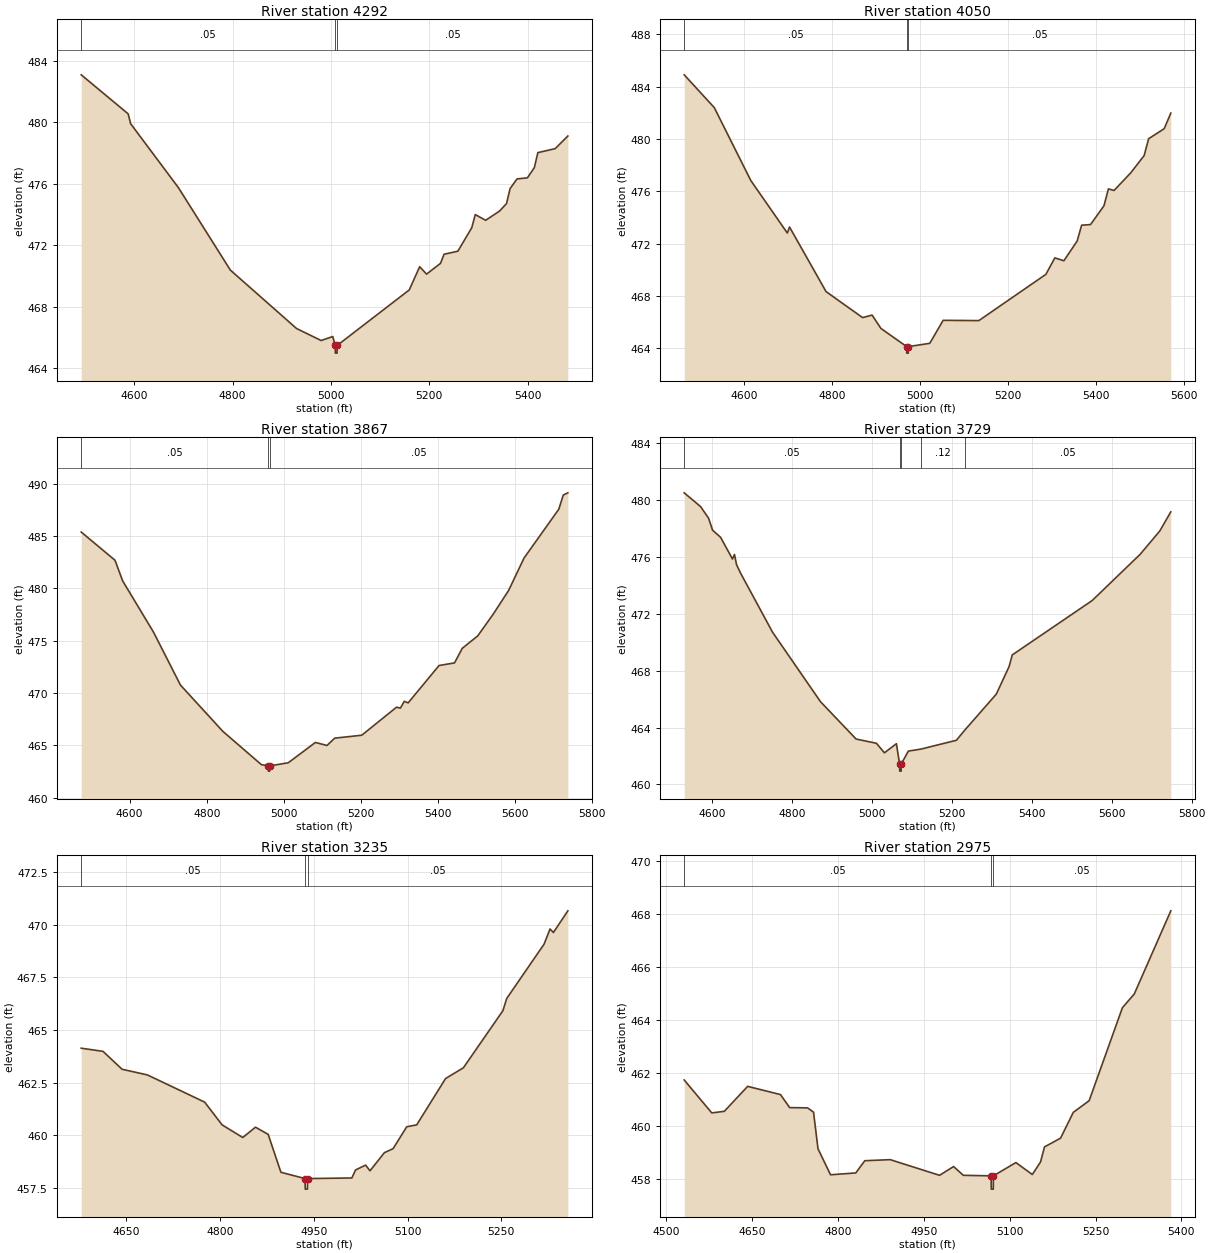
Type RM Length L Ch R = 1,4292,242,242,242
BEGIN DESCRIPTION:
Caney T11 2.0
END DESCRIPTION:
XS GIS Cut Line= 3
      2752333.44      6905831.21      2751826.14      6905855.94
      2751490.13      6906201.38
#Sta/Elev= 30
  4492.1  483.09  4587.6  480.55  4592.6  479.91  4689.8  475.75  4795.4  470.39
  4930.1  466.59  4980.1  465.81  5003.7  466.07  5008.7  465.49  5009.0  464.99
  5012.5  464.99  5012.7  465.49  5159.3  469.10  5180.5  470.61  5194.6  470.13
  5222.9  470.83  5230.1  471.42  5258.2  471.62  5286.5  473.15  5293.6  474.00
  5314.7  473.63  5343.0  474.23  5357.2  474.72  5364.4  475.69  5378.5  476.32
  5399.6  476.39  5413.8  477.06  5420.9  478.03  5456.2  478.29  5481.9  479.11
#Mann=3,-1,0
  4492.1    0.05       0  5008.7    0.04       0  5012.7    0.05       0
Bank Sta=5008.7,5012.7
Exp/Cntr=0.3,0.1

Type RM Length L Ch R = 1,4050,183,183,183
BEGIN DESCRIPTION:
Mapping XS 1df83bd2
END DESCRIPTION:
XS GIS Cut Line= 3
      2752260.07      6905713.88      2751726.18      6905650.94
      2751166.32      6905748.59
#Sta/Elev= 30
  4463.4  484.91  4531.8  482.40  4614.8  476.82  4697.8  472.80  4702.8  473.26
  4785.8  468.32  4868.8  466.33  4890.4  466.52  4910.5  465.50  4969.0  464.11
  4969.2  463.61  4972.7  463.61  4973.0  464.11  5021.5  464.36  5051.9  466.12
  5133.1  466.10  5285.4  469.64  5305.7  470.90  5326.3  470.68  5356.5  472.19
  5366.6  473.40  5386.9  473.45  5417.4  474.89  5427.5  476.18  5440.3  476.06
  5478.3  477.41  5508.7  478.73  5518.9  480.02  5554.3  480.79  5569.3  481.98
#Mann=3,-1,0
  4463.4    0.05       0  4969.0    0.04       0  4973.0    0.05       0
Bank Sta=4969,4973
Exp/Cntr=0.3,0.1

Type RM Length L Ch R = 1,3867,138,138,138
BEGIN DESCRIPTION:
Mapping XS 12172a96
END DESCRIPTION:
XS GIS Cut Line= 3
      2752253.55      6905472.99      2751726.18      6905468.65
      2750992.71      6905527.24
#Sta/Elev= 30
  4474.3  485.37  4561.9  482.68  4581.9  480.70  4661.9  475.81  4731.9  470.75
  4841.9  466.33  4941.9  463.15  4959.9  463.03  4960.1  462.53  4963.6  462.53
  4963.9  463.03  5011.9  463.33  5082.1  465.27  5112.2  464.98  5132.3  465.68
  5202.5  465.96  5292.8  468.64  5302.8  468.55  5312.9  469.20  5322.9  469.05
  5403.1  472.62  5443.3  472.87  5463.3  474.26  5503.5  475.45  5543.6  477.52
  5583.7  479.79  5623.8  482.89  5714.1  487.56  5725.6  488.91  5737.5  489.12
#Mann=3,-1,0
  4474.3    0.05       0  4959.9    0.05       0  4963.9    0.05       0
Bank Sta=4959.9,4963.9
Exp/Cntr=0.3,0.1

Type RM Length L Ch R = 1,3729,494,494,494
BEGIN DESCRIPTION:
Mapping XS 0b558b95
END DESCRIPTION:
XS GIS Cut Line= 3
      2752247.04      6905331.93      2751778.26      6905347.12
      2751029.24      6905366.60
#Sta/Elev= 30
  4529.5  480.52  4570.6  479.55  4590.6  478.73  4600.6  477.89  4620.6  477.39
  4650.4  475.86  4655.4  476.18  4660.6  475.46  4670.6  474.87  4750.7  470.71
  4870.7  465.82  4959.8  463.19  5010.8  462.89  5030.8  462.22  5060.8  462.86
  5068.8  461.43  5069.1  460.93  5072.6  460.93  5072.8  461.43  5090.8  462.34
  5122.0  462.48  5210.9  463.10  5232.1  463.82  5310.9  466.35  5342.9  468.29
  5350.9  469.11  5551.0  472.94  5671.0  476.19  5720.3  477.84  5747.8  479.18
#Mann=5,-1,0
  4529.5    0.05       0  5068.8    0.04       0  5072.8    0.05       0
  5122.0    0.12       0  5232.1    0.05       0
Bank Sta=5068.8,5072.8
Exp/Cntr=0.3,0.1

Type RM Length L Ch R = 1,3235,260,260,260
BEGIN DESCRIPTION:
Mapping XS 2b4acbb9
END DESCRIPTION:
XS GIS Cut Line= 3
      2751990.24      6905036.57      2751587.50      6904963.66
      2751251.36      6905116.14
#Sta/Elev= 30
  4578.0  464.14  4612.8  463.99  4643.3  463.14  4683.9  462.87  4775.4  461.58
  4803.3  460.50  4836.4  459.90  4856.7  460.39  4877.0  460.05  4897.4  458.25
  4936.0  457.95  4936.3  457.45  4939.8  457.45  4940.0  457.95  5010.9  457.98
  5016.8  458.36  5032.9  458.59  5039.9  458.32  5062.9  459.18  5076.8  459.37
  5098.7  460.41  5114.6  460.50  5160.8  462.70  5189.3  463.21  5252.5  465.92
  5258.6  466.50  5318.4  469.08  5327.9  469.80  5333.3  469.63  5356.4  470.66
#Mann=3,-1,0
  4578.0    0.05       0  4936.0    0.04       0  4940.0    0.05       0
Bank Sta=4936,4940
Exp/Cntr=0.3,0.1

Type RM Length L Ch R = 1,2975,16,16,16
BEGIN DESCRIPTION:
Mapping XS 401f087e
END DESCRIPTION:
XS GIS Cut Line= 6
      2751862.07      6904915.31      2751629.24      6904843.87
      2751562.71      6904745.28      2751501.25      6904740.33
      2751452.89      6904921.00      2751290.55      6905044.85
#Sta/Elev= 30
  4531.3  461.74  4579.5  460.50  4601.4  460.56  4642.2  461.50  4699.6  461.19
  4715.5  460.70  4746.8  460.69  4757.3  460.53  4765.1  459.15  4787.0  458.17
  4831.1  458.24  4846.9  458.70  4891.3  458.74  4977.5  458.15  5002.0  458.48
  5019.1  458.15  5067.6  458.13  5067.9  457.63  5071.4  457.63  5071.6  458.13
  5110.9  458.63  5139.6  458.18  5153.9  458.65  5160.9  459.22  5189.0  459.55
  5211.2  460.52  5238.9  460.96  5297.0  464.46  5317.8  464.98  5381.6  468.11
#Mann=3,-1,0
  4531.3    0.05       0  5067.6    0.04       0  5071.6    0.05       0
Bank Sta=5067.6,5071.6
Exp/Cntr=0.3,0.1

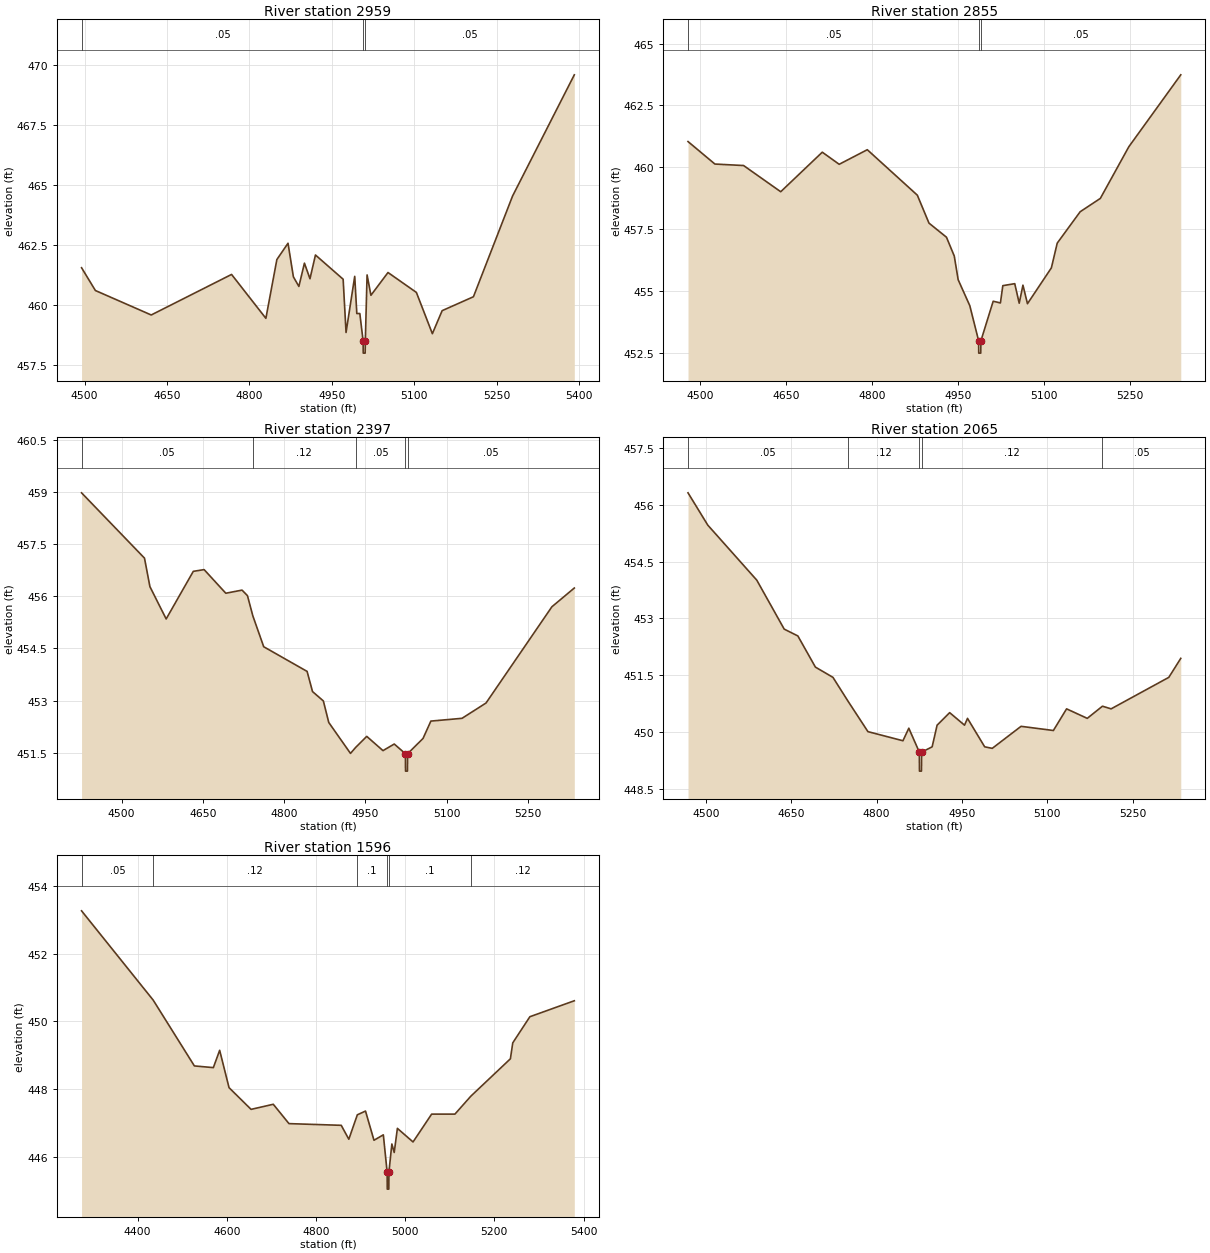
Type RM Length L Ch R = 1,2959,104,104,104
BEGIN DESCRIPTION:
Mapping XS 7fbaa87d
END DESCRIPTION:
XS GIS Cut Line= 6
      2751912.14      6904849.01      2751660.52      6904702.62
      2751504.81      6904714.44      2751455.87      6904737.50
      2751428.44      6904901.36      2751256.21      6905049.61
#Sta/Elev= 30
  4494.3  461.54  4519.5  460.59  4621.2  459.57  4767.5  461.26  4830.0  459.43
  4850.0  461.88  4870.3  462.56  4880.1  461.16  4890.1  460.76  4900.2  461.73
  4910.3  461.08  4920.3  462.07  4970.7  461.06  4976.0  458.84  4991.8  461.18
  4995.6  459.63  5001.1  459.63  5007.1  458.48  5007.3  457.98  5010.8  457.98
  5011.1  458.48  5014.3  461.24  5021.3  460.39  5052.4  461.34  5104.1  460.51
  5133.2  458.79  5151.0  459.75  5208.0  460.33  5279.3  464.53  5391.7  469.58
#Mann=3,-1,0
  4494.3    0.05       0  5007.1    0.04       0  5011.1    0.05       0
Bank Sta=5007.1,5011.1
Exp/Cntr=0.3,0.1

Type RM Length L Ch R = 1,2855,458,458,458
BEGIN DESCRIPTION:
Mapping XS 77b5a124
END DESCRIPTION:
XS GIS Cut Line= 6
      2751927.38      6904823.39      2751624.22      6904627.28
      2751476.93      6904654.88      2751447.46      6904661.10
      2751368.16      6904726.72      2751212.07      6904875.34
#Sta/Elev= 30
  4479.6  461.04  4526.5  460.13  4576.5  460.07  4641.3  459.01  4713.8  460.61
  4743.3  460.12  4792.3  460.71  4879.6  458.87  4899.9  457.74  4930.4  457.17
  4944.0  456.41  4950.8  455.45  4971.1  454.40  4986.5  452.98  4986.7  452.48
  4990.2  452.48  4990.5  452.98  5011.9  454.58  5024.5  454.51  5028.7  455.21
  5049.5  455.29  5057.3  454.50  5063.8  455.23  5071.7  454.48  5113.4  455.93
  5123.6  456.93  5163.6  458.20  5198.8  458.74  5248.5  460.83  5339.1  463.74
#Mann=3,-1,0
  4479.6    0.05       0  4986.5    0.04       0  4990.5    0.05       0
Bank Sta=4986.5,4990.5
Exp/Cntr=0.3,0.1

Type RM Length L Ch R = 1,2397,332,332,332
BEGIN DESCRIPTION:
Mapping XS 7964d25c
END DESCRIPTION:
XS GIS Cut Line= 3
      2751912.12      6904267.91      2751342.71      6904247.08
      2751040.80      6904403.24
#Sta/Elev= 30
  4426.1  458.98  4542.3  457.10  4552.3  456.28  4582.3  455.35  4632.4  456.72
  4652.4  456.77  4692.4  456.09  4722.4  456.18  4732.4  456.02  4742.3  455.44
  4762.4  454.55  4842.5  453.84  4852.5  453.26  4872.5  452.99  4882.5  452.37
  4922.6  451.48  4932.0  451.65  4952.6  451.97  4982.6  451.56  5003.4  451.75
  5024.0  451.47  5024.2  450.97  5027.7  450.97  5028.0  451.47  5056.5  451.91
  5071.0  452.41  5128.5  452.49  5172.8  452.93  5294.4  455.70  5335.8  456.24
#Mann=5,-1,0
  4426.1    0.05       0  4742.3    0.12       0  4932.0    0.05       0
  5024.0    0.04       0  5028.0    0.05       0
Bank Sta=5024,5028
Exp/Cntr=0.3,0.1

Type RM Length L Ch R = 1,2065,469,469,469
BEGIN DESCRIPTION:
Mapping XS c3a65c0e
END DESCRIPTION:
XS GIS Cut Line= 3
      2751944.22      6904063.82      2751426.04      6903946.02
      2751150.98      6904136.01
#Sta/Elev= 30
  4468.6  456.31  4503.3  455.46  4589.4  454.01  4637.6  452.72  4661.6  452.54
  4692.4  451.72  4723.2  451.45  4749.8  450.82  4784.7  450.02  4846.2  449.78
  4856.5  450.11  4875.0  449.48  4875.2  448.98  4878.7  448.98  4879.0  449.48
  4897.5  449.62  4906.2  450.19  4928.3  450.52  4954.4  450.19  4959.6  450.37
  4989.8  449.62  5003.1  449.58  5053.7  450.16  5110.5  450.05  5133.7  450.62
  5170.0  450.37  5196.7  450.69  5211.9  450.62  5313.3  451.45  5334.3  451.95
#Mann=5,-1,0
  4468.6    0.05       0  4749.8    0.12       0  4875.0    0.07       0
  4879.0    0.12       0  5196.7    0.05       0
Bank Sta=4875,4879
Exp/Cntr=0.3,0.1

Type RM Length L Ch R = 1,1596,0,0,0
BEGIN DESCRIPTION:
Mapping XS 245e2a84
END DESCRIPTION:
XS GIS Cut Line= 4
      2751843.21      6903851.26      2751489.26      6903520.64
      2751259.45      6903594.05      2751151.52      6903957.68
#Sta/Elev= 30
  4274.4  453.26  4435.0  450.63  4527.4  448.69  4569.9  448.64  4584.1  449.15
  4605.1  448.05  4654.5  447.41  4704.3  447.56  4739.5  446.99  4856.7  446.94
  4873.7  446.53  4892.8  447.25  4911.1  447.36  4930.1  446.50  4951.1  446.66
  4959.6  445.56  4959.9  445.06  4963.4  445.06  4963.6  445.56  4970.2  446.39
  4975.5  446.14  4982.6  446.85  5017.7  446.45  5059.4  447.27  5111.6  447.27
  5147.4  447.80  5236.0  448.90  5241.3  449.37  5279.7  450.14  5379.3  450.61
#Mann=6,-1,0
  4274.4    0.05       0  4435.0    0.12       0  4892.8     0.1       0
  4959.6    0.07       0  4963.6     0.1       0  5147.4    0.12       0
Bank Sta=4959.6,4963.6
Exp/Cntr=0.3,0.1

Chan Stop Cuts=-1