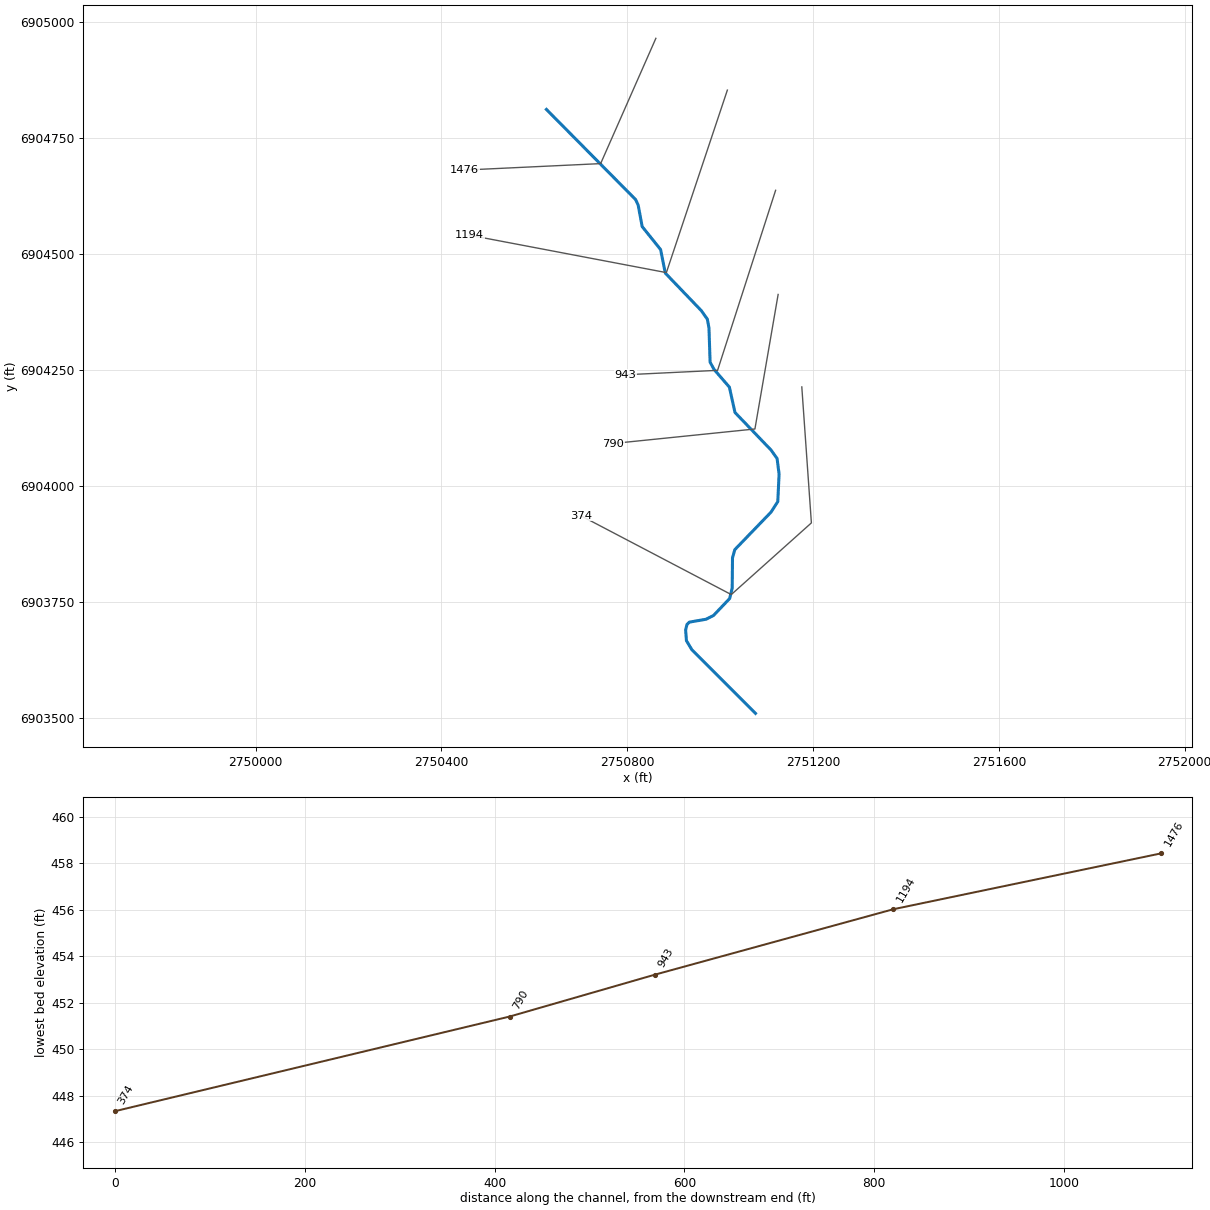
--- Caney T11_1.prj (project) ---

Proj Title=Caney T11_1 Base Level Engineering
Current Plan=p01
Default Exp/Contr=0.3,0.1
English Units
Geom File=g01
Flow File=f01
Plan File=p01
Y Axis Title=Elevation
X Axis Title(PF)=Main Channel Distance
X Axis Title(XS)=Station
BEGIN DESCRIPTION:
Caney T11_1
END DESCRIPTION:
DSS Export Rating Curves= 0
DSS Export Rating Curve Sorted= 0
DSS Export Volume Flow Curves= 0
DXF OffsetX= 0
DXF OffsetY= 0
DXF ScaleX= 1
DXF ScaleY= 10

--- Caney T11_1.p01 (plan) ---

Plan Title=Multiple Run
Short Identifier=Multiple
Geom File=g01
Flow File=f01
Subcritical Flow
K Sum by GR= 0
Std Step Tol= 0.01
Critical Tol= 0.01
Num of Std Step Trials= 20
Max Error Tol= 0.3
Flow Tol Ratio= 0.001
Split Flow NTrial= 30
Split Flow Tol= 0.02
Split Flow Ratio= 0.02
Log Output Level= 0
Friction Slope Method= 1
Unsteady Friction Slope Method= 2
Unsteady Bridges Friction Slope Method= 1
Parabolic Critical Depth
Global Vel Dist=  1 , 1 , 1
Global Log Level= 0
CheckData=True
Encroach Param= -1, 0, 0, 0
BEGIN DESCRIPTION:
Multiple Run
END DESCRIPTION:

--- Caney T11_1.f01 (steady flow) ---

Flow Title=Multiple
Program Version=4.10
Number of Profiles= 7
Profile Names=10-year,25-year,50-year,1pct_min,100-year,1pct_plu,500-year
River Rch & RM=Caney T11_1,Reach-1         ,1476
     119     144     163      92     183     366     231
Boundary for River Rch & Prof#=Caney T11_1,Reach-1         , 1
Up Type= 0
Dn Type= 3
Dn Slope=0.01
Boundary for River Rch & Prof#=Caney T11_1,Reach-1         , 2
Up Type= 0
Dn Type= 3
Dn Slope=0.01
Boundary for River Rch & Prof#=Caney T11_1,Reach-1         , 3
Up Type= 0
Dn Type= 3
Dn Slope=0.01
Boundary for River Rch & Prof#=Caney T11_1,Reach-1         , 4
Up Type= 0
Dn Type= 3
Dn Slope=0.01
Boundary for River Rch & Prof#=Caney T11_1,Reach-1         , 5
Up Type= 0
Dn Type= 3
Dn Slope=0.01
Boundary for River Rch & Prof#=Caney T11_1,Reach-1         , 6
Up Type= 0
Dn Type= 3
Dn Slope=0.01
Boundary for River Rch & Prof#=Caney T11_1,Reach-1         , 7
Up Type= 0
Dn Type= 3
Dn Slope=0.01
DSS Import GetInterval= 0
DSS Import GetPeak= 0
DSS Import FillOption= 0

--- Caney T11_1.g01 (geometry) ---

Geom Title=Existing Conditions
Program Version=4.10

River Reach=Caney T11_1     ,Reach-1
Reach XY= 30
        2750626.        6904811.      2750817.86      6904617.06
       2750823.5      6904604.97       2750832.1      6904558.81
      2750871.81      6904509.27      2750881.85      6904458.71
      2750959.51      6904377.74      2750972.38       6904359.5
      2750975.87      6904340.95      2750978.33      6904266.97
      2750986.84      6904251.35      2751019.86      6904213.17
      2751031.85      6904158.71      2751109.57      6904077.74
      2751122.53       6904059.5      2751126.78      6904026.08
      2751124.03       6903966.9      2751109.56      6903944.26
      2751031.54      6903863.42      2751026.53      6903845.77
       2751025.9      6903780.96      2751020.54      6903758.34
       2750985.7      6903721.73      2750969.58      6903713.61
      2750933.75      6903707.43      2750928.62      6903702.49
      2750925.62      6903690.63      2750927.42      6903667.43
      2750939.01      6903648.02        2751076.        6903511.

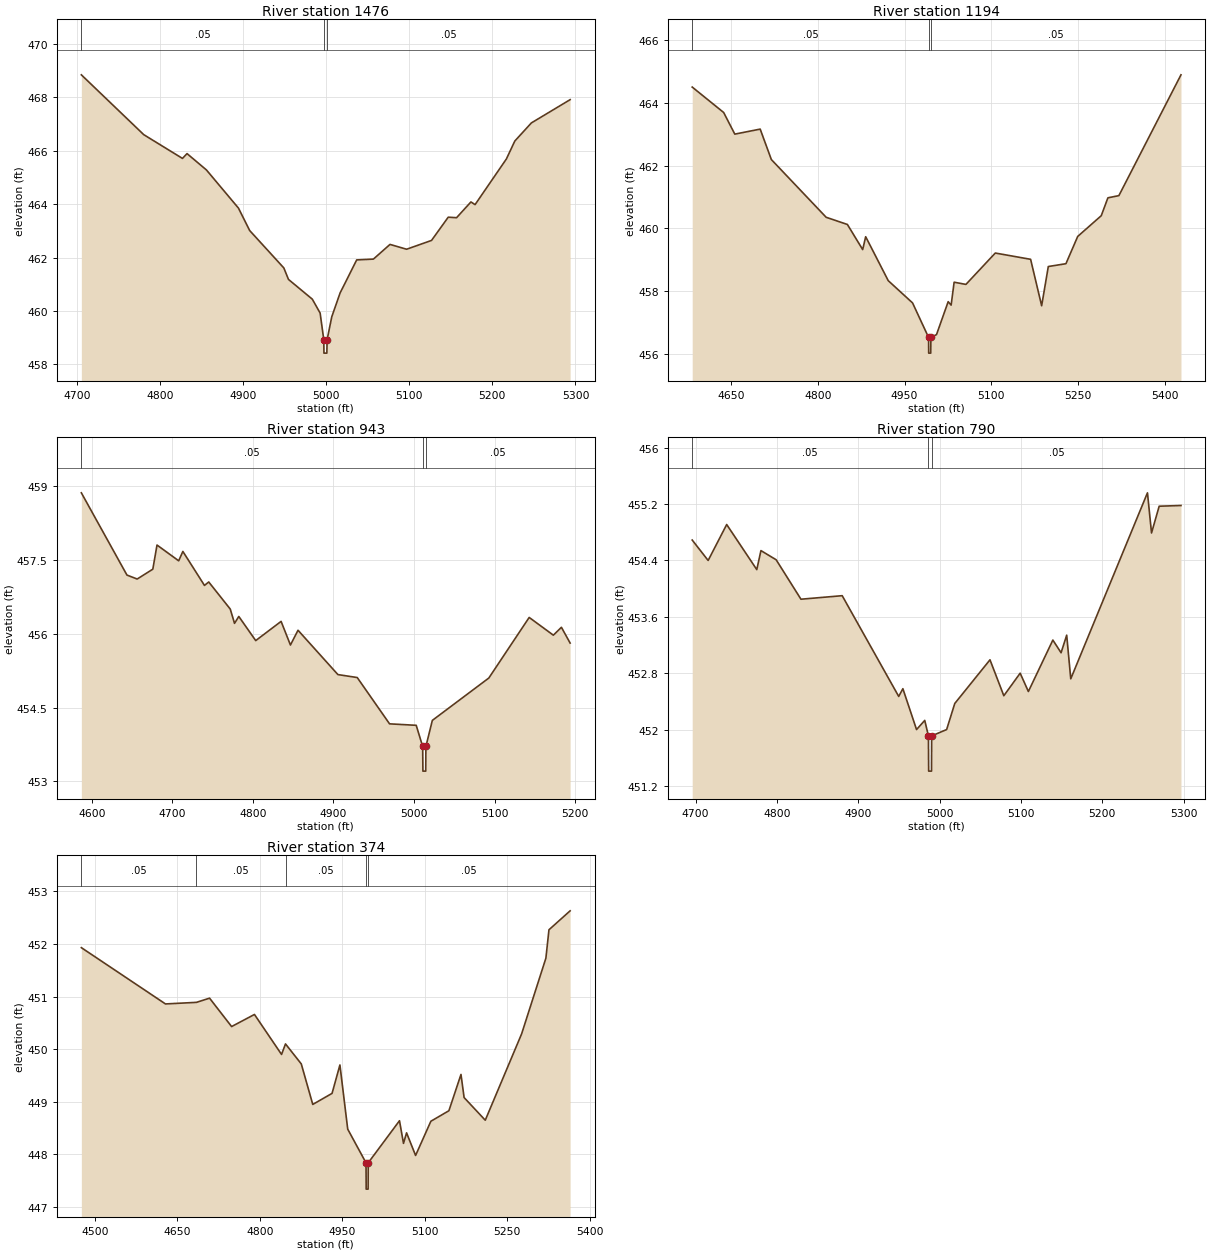
Type RM Length L Ch R = 1 ,1476    ,282,282,282
BEGIN DESCRIPTION:
Caney T11_1 1.0
END DESCRIPTION:
XS GIS Cut Line= 3
      2750861.57      6904964.01       2750742.7      6904694.35
      2750449.43      6904680.46
#Sta/Elev= 30
  4705.3  468.84  4780.4   466.6    4827  465.71  4832.5  465.89  4855.8  465.28
  4894.4  463.85  4907.9  463.01    4949  461.61  4954.6  461.18  4983.3  460.44
  4992.7  459.92  4997.1  458.92  4997.3  458.42  5000.8  458.42  5001.1  458.92
  5006.7  459.78  5016.7  460.67  5036.7  461.91  5056.8  461.94  5076.8  462.49
  5096.8  462.31  5126.8  462.64  5146.9  463.51  5156.9  463.49  5174.2  464.08
  5179.2  463.98  5216.9  465.69    5227  466.36    5247  467.04  5293.6  467.91
#Mann= 3 ,-1 , 0
  4705.3     .05       0  4997.1     .04       0  5001.1     .05       0
Bank Sta=4997.1,5001.1
XS Rating Curve= 0 ,0
Exp/Cntr=0.3,0.1

Type RM Length L Ch R = 1 ,1194    ,251,251,251
BEGIN DESCRIPTION:
Mapping XS 9fe59469
END DESCRIPTION:
XS GIS Cut Line= 3
      2751015.48      6904852.58      2750884.22      6904459.74
       2750460.5       6904540.3
#Sta/Elev= 30
  4582.6   464.5    4637  463.69  4656.3     463  4700.2  463.16  4719.5  462.19
  4814.3  460.35  4851.1  460.12  4877.5  459.32  4882.7  459.73  4921.7  458.33
  4963.8  457.62  4991.5  456.52  4991.7  456.02  4995.2  456.02  4995.5  456.52
  5005.2  456.61  5025.4  457.66  5030.5  457.55  5035.7  458.28  5056.1  458.21
  5106.9  459.21    5168  459.01  5187.1  457.53  5198.6  458.78  5229.1  458.87
  5249.5  459.74  5290.2   460.4  5301.7  460.97  5320.7  461.04  5428.1  464.89
#Mann= 3 ,-1 , 0
  4582.6     .05       0  4991.5     .04       0  4995.5     .05       0
Bank Sta=4991.5,4995.5
XS Rating Curve= 0 ,0
Exp/Cntr=0.3,0.1

Type RM Length L Ch R = 1 ,943     ,153,153,153
BEGIN DESCRIPTION:
Mapping XS 3ebe45d5
END DESCRIPTION:
XS GIS Cut Line= 3
      2751119.34      6904636.92      2750994.43      6904249.38
      2750795.23      6904239.76
#Sta/Elev= 30
  4587.1  458.86  4643.7  457.19  4656.4  457.11  4675.8  457.31    4681   457.8
  4707.9  457.48  4713.1  457.67  4739.9  456.98  4745.2  457.05  4771.9   456.5
  4777.2  456.21  4782.5  456.35  4803.5  455.86    4835  456.25  4846.6  455.77
    4856  456.07  4905.5  455.17  4929.5  455.11  4969.6  454.17  5002.7  454.14
  5010.7  453.71    5011  453.21  5014.5  453.21  5014.7  453.71  5022.7  454.24
  5092.8   455.1  5142.9  456.33  5172.9  455.97  5182.9  456.13  5193.7  455.81
#Mann= 3 ,-1 , 0
  4587.1     .05       0  5010.7     .04       0  5014.7     .05       0
Bank Sta=5010.7,5014.7
XS Rating Curve= 0 ,0
Exp/Cntr=0.3,0.1

Type RM Length L Ch R = 1 ,790     ,416,416,416
BEGIN DESCRIPTION:
Mapping XS f13e8b93
END DESCRIPTION:
XS GIS Cut Line= 3
      2751124.76      6904412.74       2751074.8      6904123.15
      2750769.37      6904091.87
#Sta/Elev= 30
  4695.9  454.69  4715.5   454.4  4738.3  454.91  4775.3  454.27  4780.4  454.54
  4799.1  454.41  4829.6  453.85  4880.3   453.9  4949.8  452.47  4954.9  452.58
  4971.7     452  4981.8  452.13  4986.3  451.91  4986.6  451.41  4990.1  451.41
  4990.3  451.91  5008.7     452  5018.7  452.37    5062  452.99    5079  452.48
  5099.1   452.8  5109.2  452.54  5139.3  453.27  5149.4  453.09  5156.3  453.34
  5161.3  452.72  5255.6  455.36  5260.6  454.79    5270  455.17  5296.8  455.18
#Mann= 3 ,-1 , 0
  4695.9     .05       0  4986.3     .04       0  4990.3     .05       0
Bank Sta=4986.3,4990.3
XS Rating Curve= 0 ,0
Exp/Cntr=0.3,0.1

Type RM Length L Ch R = 1 ,374     ,0,0,0
BEGIN DESCRIPTION:
Caney T11_1 0.0
END DESCRIPTION:
XS GIS Cut Line= 4
      2751175.71      6904213.68      2751196.35      6903921.01
      2751023.89      6903766.72      2750700.98      6903936.01
#Sta/Elev= 30
  4475.2  451.93  4628.3  450.86  4684.6  450.89  4708.5  450.97  4748.6  450.43
  4790.2  450.66  4839.5   449.9  4846.7   450.1  4875.4  449.72  4896.3  448.95
  4931.4  449.16  4945.7   449.7  4959.9  448.48  4993.2  447.84  4993.5  447.34
    4997  447.34  4997.2  447.84  5054.1  448.64  5061.4  448.21    5067  448.41
  5083.4  447.98  5111.2  448.63    5144  448.83    5166  449.52  5171.7  449.08
  5210.2  448.65  5276.3  450.29  5320.5  451.73  5326.1  452.27  5364.6  452.63
#Mann= 5 ,-1 , 0
  4475.2     .05       0  4684.6     .05       0  4846.7     .05       0
  4993.2     .04       0  4997.2     .05       0
Bank Sta=4993.2,4997.2
XS Rating Curve= 0 ,0
Exp/Cntr=0.3,0.1

Chan Stop Cuts=-1
Use User Specified Reach Order=0
Composite Channel Slope=5