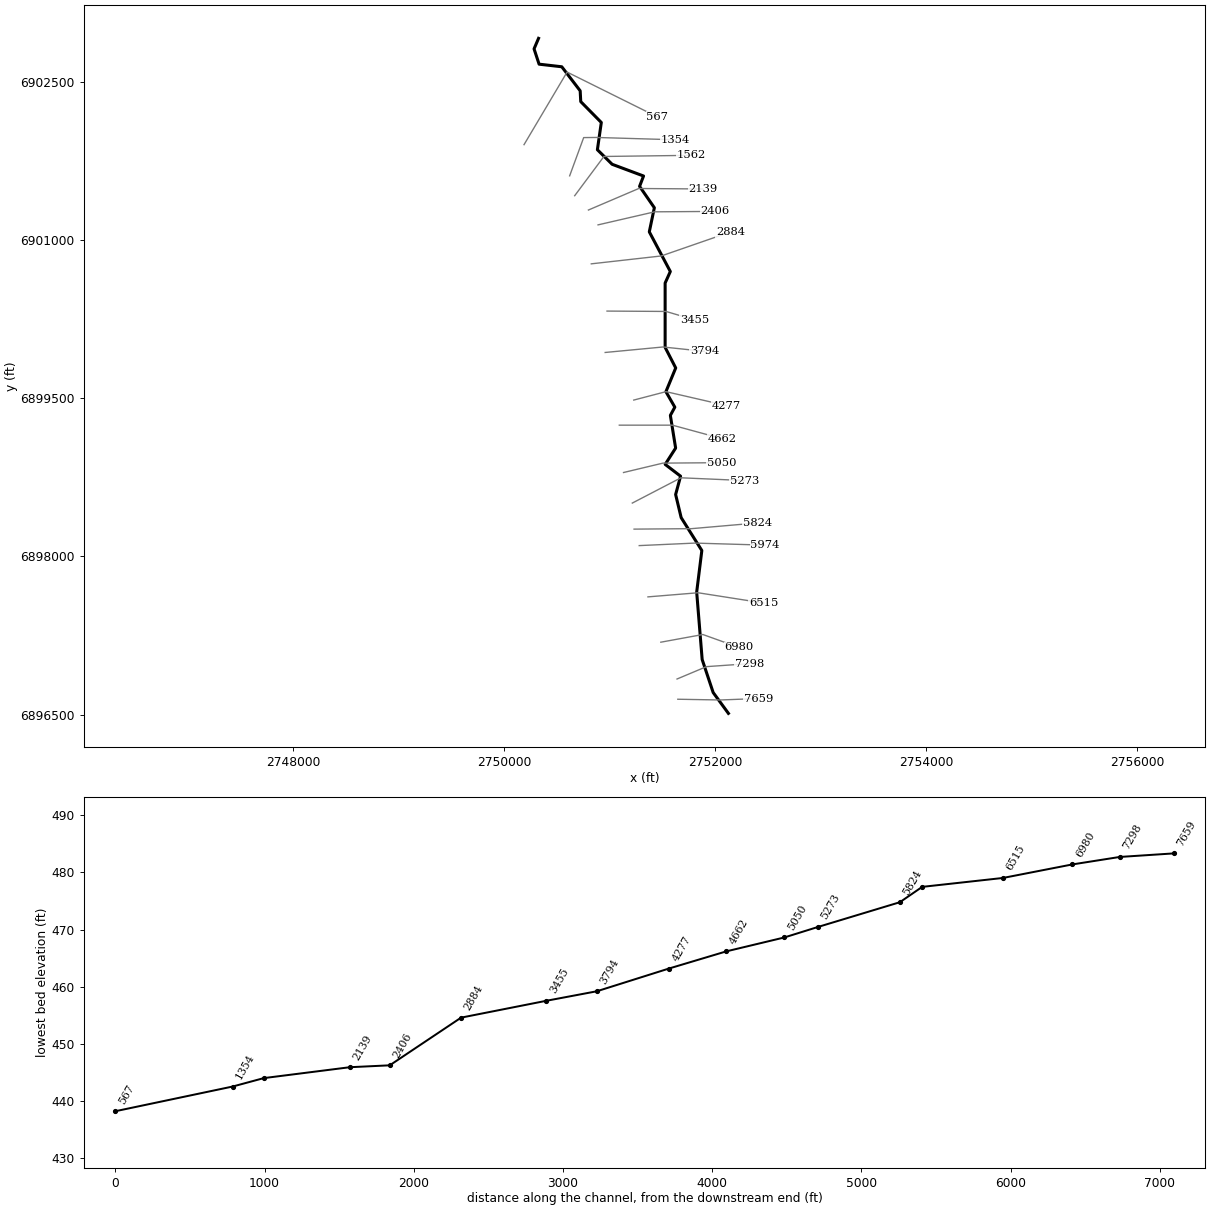
--- Caney T12.prj (project) ---

Proj Title=Caney T12 Base Level Engineering
Current Plan=p01
Default Exp/Contr=0.3,0.1
English Units
Geom File=g01
Flow File=f01
Plan File=p01
Y Axis Title=Elevation
X Axis Title(PF)=Main Channel Distance
X Axis Title(XS)=Station
BEGIN DESCRIPTION:
Caney T12
END DESCRIPTION:
DSS Export Rating Curves= 0
DSS Export Rating Curve Sorted= 0
DSS Export Volume Flow Curves= 0
DXF OffsetX= 0
DXF OffsetY= 0
DXF ScaleX= 1
DXF ScaleY= 10

--- Caney T12.p01 (plan) ---

Plan Title=Multiple Run
Short Identifier=Multiple
Geom File=g01
Flow File=f01
Subcritical Flow
K Sum by GR= 0
Std Step Tol= 0.01
Critical Tol= 0.01
Num of Std Step Trials= 20
Max Error Tol= 0.3
Flow Tol Ratio= 0.001
Split Flow NTrial= 30
Split Flow Tol= 0.02
Split Flow Ratio= 0.02
Log Output Level= 0
Friction Slope Method= 1
Unsteady Friction Slope Method= 2
Unsteady Bridges Friction Slope Method= 1
Parabolic Critical Depth
Global Vel Dist=  1 , 1 , 1
Global Log Level= 0
CheckData=True
Encroach Param= -1, 0, 0, 0
BEGIN DESCRIPTION:
Multiple Run
END DESCRIPTION:

--- Caney T12.f01 (steady flow) ---

Flow Title=Multiple
Program Version=4.10
Number of Profiles= 7
Profile Names=10-year,25-year,50-year,1pct_min,100-year,1pct_plu,500-year
River Rch & RM=Caney T12,Reach-1         ,7659
     387     507     604     358     714    1425    1000
River Rch & RM=Caney T12,Reach-1         ,2884
     592     798     966     581    1160    2315    1677
River Rch & RM=Caney T12,Reach-1         ,567
     631     853    1034     624    1245    2483    1805
Boundary for River Rch & Prof#=Caney T12,Reach-1         , 1
Up Type= 0
Dn Type= 3
Dn Slope=0.005
Boundary for River Rch & Prof#=Caney T12,Reach-1         , 2
Up Type= 0
Dn Type= 3
Dn Slope=0.005
Boundary for River Rch & Prof#=Caney T12,Reach-1         , 3
Up Type= 0
Dn Type= 3
Dn Slope=0.005
Boundary for River Rch & Prof#=Caney T12,Reach-1         , 4
Up Type= 0
Dn Type= 3
Dn Slope=0.005
Boundary for River Rch & Prof#=Caney T12,Reach-1         , 5
Up Type= 0
Dn Type= 3
Dn Slope=0.005
Boundary for River Rch & Prof#=Caney T12,Reach-1         , 6
Up Type= 0
Dn Type= 3
Dn Slope=0.005
Boundary for River Rch & Prof#=Caney T12,Reach-1         , 7
Up Type= 0
Dn Type= 3
Dn Slope=0.005
DSS Import GetInterval= 0
DSS Import GetPeak= 0
DSS Import FillOption= 0

--- Caney T12.g01 (geometry) ---

Geom Title=Existing Conditions
Program Version=4.10

River Reach=Caney T12       ,Reach-1
Reach XY= 30
        2752126.        6896511.      2751981.52      6896708.57
      2751877.22       6897021.5      2751825.21      6897660.99
      2751874.02       6898055.1      2751678.08      6898366.86
       2751625.6        6898586.      2751672.63      6898759.72
      2751526.49      6898871.49      2751625.61      6899026.16
      2751575.69      6899336.04      2751617.93      6899414.31
       2751533.5        6899561.      2751626.41        6899786.
      2751526.06      6899981.03      2751526.09      6900590.97
      2751575.25      6900700.32      2751375.97      6901076.33
      2751423.81      6901305.09      2751283.84      6901507.62
      2751321.34      6901605.74       2751023.7      6901716.83
      2750883.81      6901854.81       2750920.9      6902113.29
        2750726.        6902311.      2750720.64      6902413.49
       2750546.2      6902641.41      2750331.07      6902666.03
      2750283.31      6902811.04        2750326.        6902911.

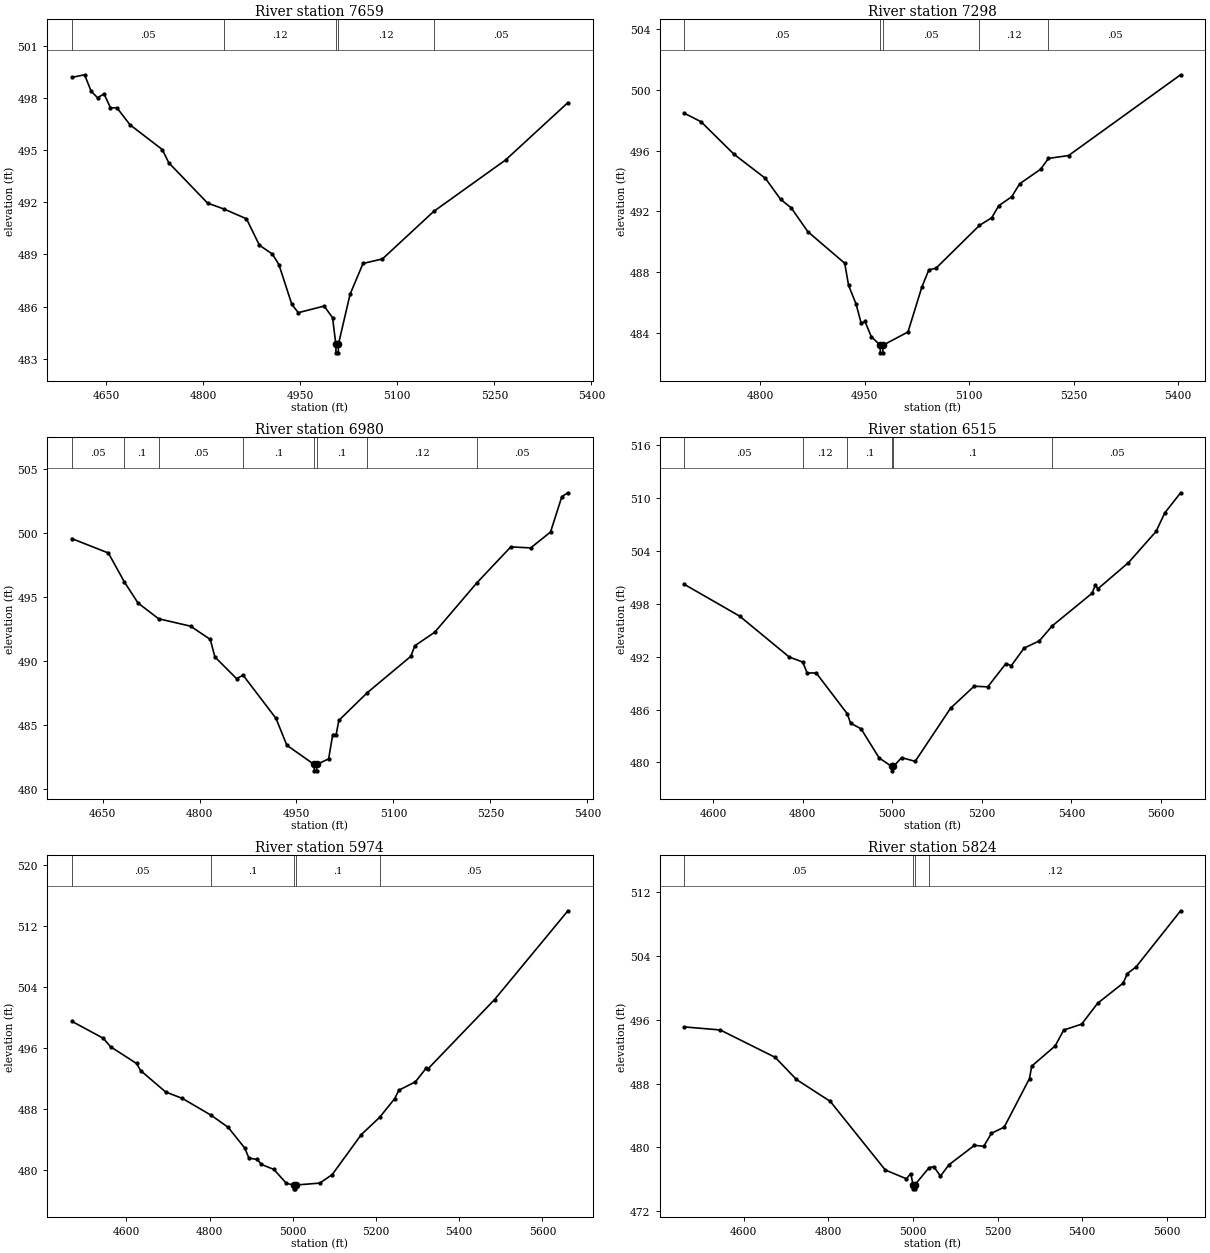
Type RM Length L Ch R = 1 ,7659    ,361,361,361
BEGIN DESCRIPTION:
Caney T12 14.0
END DESCRIPTION:
XS GIS Cut Line= 3
       2751646.2      6896645.04      2752048.93      6896638.01
      2752412.27      6896651.94
#Sta/Elev= 30
  4597.2  499.18    4617  499.33    4627  498.39    4637  498.01    4647  498.23
    4657  497.43    4667  497.43    4687  496.46    4737  495.03    4747  494.27
    4807  491.95  4832.3  491.61    4867  491.05    4887  489.53  4907.1  489.02
  4917.1  488.42  4937.1  486.13  4947.1  485.65  4987.1  486.03    5000  485.36
  5005.1  483.84  5005.3  483.34  5008.8  483.34  5009.1  483.84  5027.1  486.71
  5047.1  488.48  5077.1  488.74  5156.2  491.47  5267.3  494.43  5363.6  497.73
#Mann= 5 ,-1 , 0
  4597.2     .05       0  4832.3     .12       0  5005.1     .07       0
  5009.1     .12       0  5156.2     .05       0
Bank Sta=5005.1,5009.1
XS Rating Curve= 0 ,0
Exp/Cntr=0.3,0.1

Type RM Length L Ch R = 1 ,7298    ,318,318,318
BEGIN DESCRIPTION:
Mapping XS be3032a3
END DESCRIPTION:
XS GIS Cut Line= 3
      2751638.92      6896836.88      2751917.56      6896954.07
      2752326.37      6896982.71
#Sta/Elev= 30
  4691.5  498.44  4715.2  497.89  4762.7  495.75  4807.7  494.17  4829.4   492.8
  4844.8  492.23  4868.6  490.67  4921.5   488.6    4927  487.16  4937.8  485.92
  4945.2  484.65  4950.6  484.78  4959.5  483.79  4972.4  483.22  4972.6  482.72
  4976.1  482.72  4976.4  483.22  5012.3  484.09  5032.3  487.05  5042.3  488.17
  5052.4  488.27  5114.8  491.08  5132.6  491.59  5142.6  492.38  5161.1  492.96
  5172.7  493.82  5202.7  494.77  5213.9  495.48  5242.8  495.67  5403.6  500.97
#Mann= 5 ,-1 , 0
  4691.5     .05       0  4972.4     .05       0  4976.4     .05       0
  5114.8     .12       0  5213.9     .05       0
Bank Sta=4972.4,4976.4
XS Rating Curve= 0 ,0
Exp/Cntr=0.3,0.1

Type RM Length L Ch R = 1 ,6980    ,465,465,465
BEGIN DESCRIPTION:
Mapping XS 32d9aa94
END DESCRIPTION:
XS GIS Cut Line= 3
      2751485.22      6897185.83      2751883.71      6897258.76
      2752224.81      6897136.37
#Sta/Elev= 30
  4602.4  499.57    4659  498.44  4683.6  496.19  4704.9  494.53  4736.7   493.3
  4786.2  492.72  4816.7  491.68  4823.7  490.32  4857.3  488.62  4867.4  488.89
  4918.3  485.51  4935.1  483.41  4977.3  481.91  4977.6  481.41  4981.1  481.41
  4981.3  481.91  4999.7  482.34  5006.1  484.25  5011.4  484.25  5015.5  485.35
  5059.5  487.52  5126.8  490.36  5133.1  491.19  5163.9  492.25  5228.7  496.09
  5281.5  498.92  5312.3  498.84    5343  500.08  5360.5  502.85  5369.9  503.15
#Mann= 8 ,-1 , 0
  4602.4     .05       0  4683.6      .1       0  4736.7     .05       0
  4867.4      .1       0  4977.3     .07       0  4981.3      .1       0
  5059.5     .12       0  5228.7     .05       0
Bank Sta=4977.3,4981.3
XS Rating Curve= 0 ,0
Exp/Cntr=0.3,0.1

Type RM Length L Ch R = 1 ,6515    ,541,541,541
BEGIN DESCRIPTION:
Mapping XS 1df431e2
END DESCRIPTION:
XS GIS Cut Line= 3
      2751363.12      6897615.53      2751838.35      6897654.59
       2752461.1      6897556.95
#Sta/Elev= 30
  4536.3  500.21  4659.4  496.61    4770  491.97  4800.3  491.39  4810.1  490.15
  4830.2  490.16  4899.5  485.53  4906.9  484.46  4930.5  483.81  4970.6  480.51
  4998.7  479.54    4999  479.04  5002.7  479.54  5020.9  480.54  5051.2  480.12
  5130.2  486.16  5182.8  488.65  5213.2  488.58  5253.7  491.23  5265.6  490.98
  5294.2  492.98  5328.2   493.8  5356.9   495.5    5446  499.21  5453.5  500.17
  5458.6   499.7    5527  502.68  5588.9  506.24    5608  508.32  5643.5  510.62
#Mann= 6 ,-1 , 0
  4536.3     .05       0  4800.3     .12       0  4899.5      .1       0
  4998.7     .07       0  5002.7      .1       0  5356.9     .05       0
Bank Sta=4998.7,5002.7
XS Rating Curve= 0 ,0
Exp/Cntr=0.3,0.1

Type RM Length L Ch R = 1 ,5974    ,150,150,150
BEGIN DESCRIPTION:
Mapping XS fc294869
END DESCRIPTION:
XS GIS Cut Line= 3
      2751280.59      6898101.64      2751807.97      6898125.51
      2752472.26      6898106.04
#Sta/Elev= 30
  4468.9  499.45  4544.4  497.23  4562.4   496.1  4624.5  493.92  4634.5  492.98
  4694.5  490.18  4734.6  489.34  4803.5  487.14  4844.7  485.55  4884.7  482.82
  4894.7  481.51  4914.8  481.33  4924.8  480.68  4954.8  480.02  4984.8  478.19
  5002.9  477.98  5003.1  477.48  5006.6  477.48  5006.9  477.98  5064.9  478.23
  5094.9  479.35  5164.9   484.6  5209.1  486.87    5245  489.31    5255  490.41
    5295  491.52  5320.7  493.31  5325.7  493.25  5485.1   502.3  5661.4  513.94
#Mann= 5 ,-1 , 0
  4468.9     .05       0  4803.5      .1       0  5002.9     .07       0
  5006.9      .1       0  5209.1     .05       0
Bank Sta=5002.9,5006.9
XS Rating Curve= 0 ,0
Exp/Cntr=0.3,0.1

Type RM Length L Ch R = 1 ,5824    ,551,551,551
BEGIN DESCRIPTION:
Mapping XS df0f42af
END DESCRIPTION:
XS GIS Cut Line= 3
      2751231.58      6898257.89      2751776.32      6898262.23
      2752401.11      6898316.46
#Sta/Elev= 30
  4460.5   495.1  4544.9  494.72  4674.9  491.28  4724.9  488.51  4804.9  485.76
  4934.9  477.15  4984.9  476.05  4994.9  476.71  5000.6  475.29  5000.8  474.79
  5004.3  474.79  5004.6  475.29  5038.4  477.45  5049.5  477.57  5065.2  476.39
  5085.2  477.81  5145.5  480.25  5167.5  480.13  5185.6  481.76  5215.7  482.53
  5275.5  488.63  5280.6  490.18  5336.2  492.72  5356.3  494.71  5398.6  495.45
  5436.6  498.08  5496.8   500.6  5506.6   501.8  5526.9  502.61  5632.4  509.67
#Mann= 4 ,-1 , 0
  4460.5     .05       0  5000.6     .05       0  5004.6     .05       0
  5038.4     .12       0
Bank Sta=5000.6,5004.6
XS Rating Curve= 0 ,0
Exp/Cntr=0.3,0.1

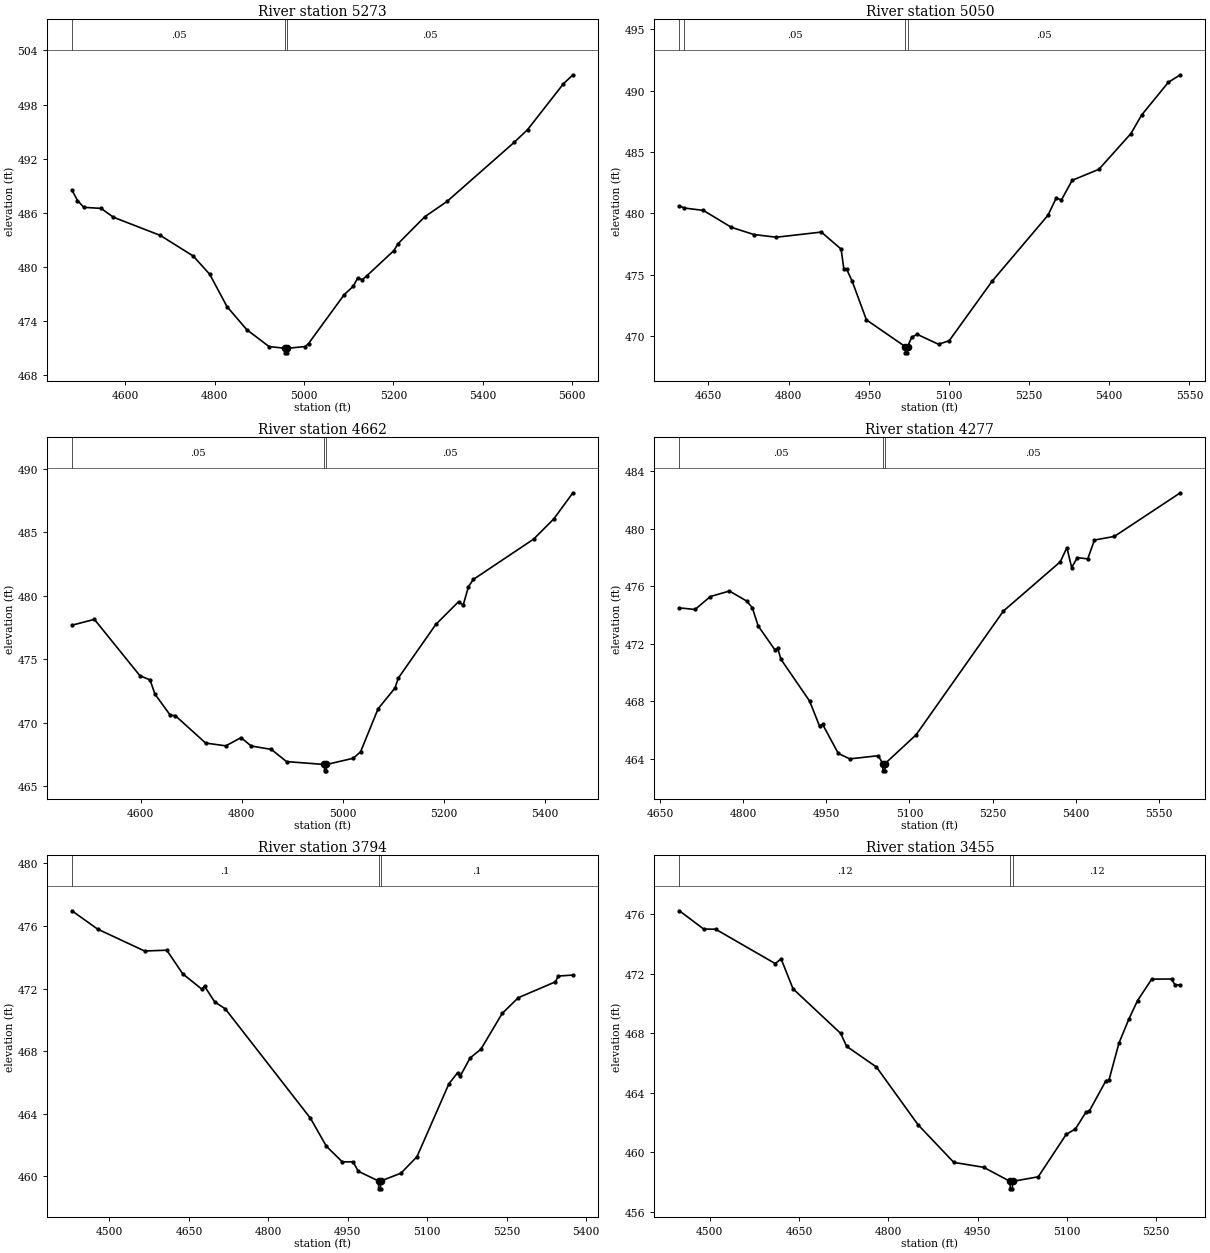
Type RM Length L Ch R = 1 ,5273    ,223,223,223
BEGIN DESCRIPTION:
Mapping XS e4892aef
END DESCRIPTION:
XS GIS Cut Line= 3
      2751214.88      6898504.95      2751675.84      6898744.54
      2752277.37       6898718.5
#Sta/Elev= 30
  4480.4  488.52  4492.9  487.34  4507.1  486.59  4545.7  486.47  4573.4  485.49
  4678.4  483.47  4752.1  481.18  4788.9  479.16  4827.5  475.58  4871.7  473.02
  4921.6  471.14  4958.2  470.94  4958.4  470.44  4961.9  470.44  4962.2  470.94
  5002.5  471.14  5010.1  471.47  5090.2  476.91  5110.2  477.82  5120.2  478.75
  5130.2  478.55  5140.2  478.97  5201.3  481.79  5210.3  482.54  5270.3  485.54
  5320.4  487.25  5470.5   493.8  5500.5  495.21  5580.6  500.29    5602   501.3
#Mann= 3 ,-1 , 0
  4480.4     .05       0  4958.2     .04       0  4962.2     .05       0
Bank Sta=4958.2,4962.2
XS Rating Curve= 0 ,0
Exp/Cntr=0.3,0.1

Type RM Length L Ch R = 1 ,5050    ,388,388,388
BEGIN DESCRIPTION:
Mapping XS 9e04ff3a
END DESCRIPTION:
XS GIS Cut Line= 3
      2751131.69      6898794.62      2751504.99       6898883.6
      2752058.41      6898887.94
#Sta/Elev= 30
  4595.8  480.61    4605  480.43  4640.6  480.24    4693  478.86  4735.1  478.27
  4777.2  478.05  4861.4  478.47  4898.4  477.08  4903.6  475.42  4908.7  475.44
  4918.9  474.48  4945.7  471.31  5018.6  469.12  5018.8  468.62  5022.3  468.62
  5022.6  469.12  5030.6   469.9  5040.6  470.13  5080.6  469.32  5100.6  469.61
  5180.6  474.45  5285.3  479.84  5300.6  481.23  5310.6   481.1  5330.6  482.69
  5380.6  483.59  5440.6  486.51  5460.6  488.02  5510.6  490.69    5533   491.3
#Mann= 4 ,-1 , 0
  4595.8     .12       0    4605     .05       0  5018.6     .04       0
  5022.6     .05       0
Bank Sta=5018.6,5022.6
XS Rating Curve= 0 ,0
Exp/Cntr=0.3,0.1

Type RM Length L Ch R = 1 ,4662    ,385,385,385
BEGIN DESCRIPTION:
Mapping XS 4a389262
END DESCRIPTION:
XS GIS Cut Line= 3
      2751091.47       6899243.5      2751594.92       6899243.5
      2752065.37      6899115.51
#Sta/Elev= 30
  4464.1  477.67  4508.6  478.13  4598.6  473.69  4618.6  473.36  4628.6  472.22
  4658.6  470.58  4668.6  470.54  4728.6  468.38  4768.6  468.16  4798.6  468.81
  4818.6  468.15  4858.6  467.88  4888.6  466.92  4963.6  466.69  4963.8  466.19
  4967.3  466.19  4967.6  466.69  5020.5  467.18  5035.1  467.69  5069.7  471.08
  5103.4  472.73  5109.5  473.49  5183.9  477.73  5228.8  479.52  5238.1  479.26
  5248.5  480.71  5258.2  481.28  5377.5  484.46  5417.3  486.05  5455.1  488.11
#Mann= 3 ,-1 , 0
  4464.1     .05       0  4963.6     .04       0  4967.6     .05       0
Bank Sta=4963.6,4967.6
XS Rating Curve= 0 ,0
Exp/Cntr=0.3,0.1

Type RM Length L Ch R = 1 ,4277    ,483,483,483
BEGIN DESCRIPTION:
Mapping XS 0da6e907
END DESCRIPTION:
XS GIS Cut Line= 3
      2751228.65      6899481.36      2751534.16      6899561.21
      2752107.09      6899429.26
#Sta/Elev= 30
  4684.9  474.49  4713.2  474.38  4740.9  475.28  4775.2  475.66  4806.2  474.97
  4816.5   474.5    4827  473.24  4857.1  471.59  4862.2  471.69  4868.2  470.92
  4919.9  468.02    4938  466.26  4943.1  466.42  4971.6  464.39  4992.2  464.01
  5043.6  464.23  5051.9  463.68  5052.1  463.18  5055.6  463.18  5055.9  463.68
  5111.7  465.67  5269.4  474.27    5372  477.69  5383.9  478.67  5392.5  477.29
  5402.8  477.98  5421.5  477.89  5433.6   479.2  5469.5  479.45  5588.6  482.48
#Mann= 3 ,-1 , 0
  4684.9     .05       0  5051.9     .04       0  5055.9     .05       0
Bank Sta=5051.9,5055.9
XS Rating Curve= 0 ,0
Exp/Cntr=0.3,0.1

Type RM Length L Ch R = 1 ,3794    ,339,339,339
BEGIN DESCRIPTION:
Mapping XS aabdb5f7
END DESCRIPTION:
XS GIS Cut Line= 3
      2750957.74      6899932.73      2751506.38      6899984.82
      2751898.77      6899943.15
#Sta/Elev= 30
  4429.2  476.97  4477.7   475.8  4566.3   474.4  4608.3  474.45  4638.4  472.94
  4674.5  471.96  4679.5  472.15  4698.7  471.15  4718.8   470.7  4879.5  463.71
  4909.6  461.92  4939.7  460.92  4959.8  460.93  4969.9  460.32  5008.1   459.7
  5008.3   459.2  5011.8   459.2  5012.1   459.7  5050.3   460.2  5080.5  461.25
  5140.8  465.91  5157.2  466.62  5162.2  466.41    5181  467.57  5201.2  468.12
  5241.4  470.41  5271.6  471.41  5341.9  472.43  5347.4   472.8  5374.9  472.86
#Mann= 3 ,-1 , 0
  4429.2      .1       0  5008.1     .05       0  5012.1      .1       0
Bank Sta=5008.1,5012.1
XS Rating Curve= 0 ,0
Exp/Cntr=0.3,0.1

Type RM Length L Ch R = 1 ,3455    ,571,571,571
BEGIN DESCRIPTION:
Mapping XS ba9dc23e
END DESCRIPTION:
XS GIS Cut Line= 3
       2750975.1       6900325.1      2751534.16      6900321.63
      2751804.96      6900241.77
#Sta/Elev= 30
  4449.1  476.24    4490  475.01    4510     475    4610  472.69    4620     473
    4640  470.99    4720  467.99    4730  467.12    4780  465.73    4850  461.84
    4910  459.31    4960  458.98  5004.6  458.03  5004.8  457.53  5008.3  457.53
  5008.6  458.03  5051.8  458.34  5098.7  461.19  5114.3  461.56  5132.1   462.7
  5137.3  462.74  5165.4   464.8  5170.6  464.85  5187.3  467.33  5203.9  468.94
  5218.6   470.2  5242.4  471.64  5275.7  471.65  5281.2  471.27  5290.5  471.24
#Mann= 3 ,-1 , 0
  4449.1     .12       0  5004.6     .07       0  5008.6     .12       0
Bank Sta=5004.6,5008.6
XS Rating Curve= 0 ,0
Exp/Cntr=0.3,0.1

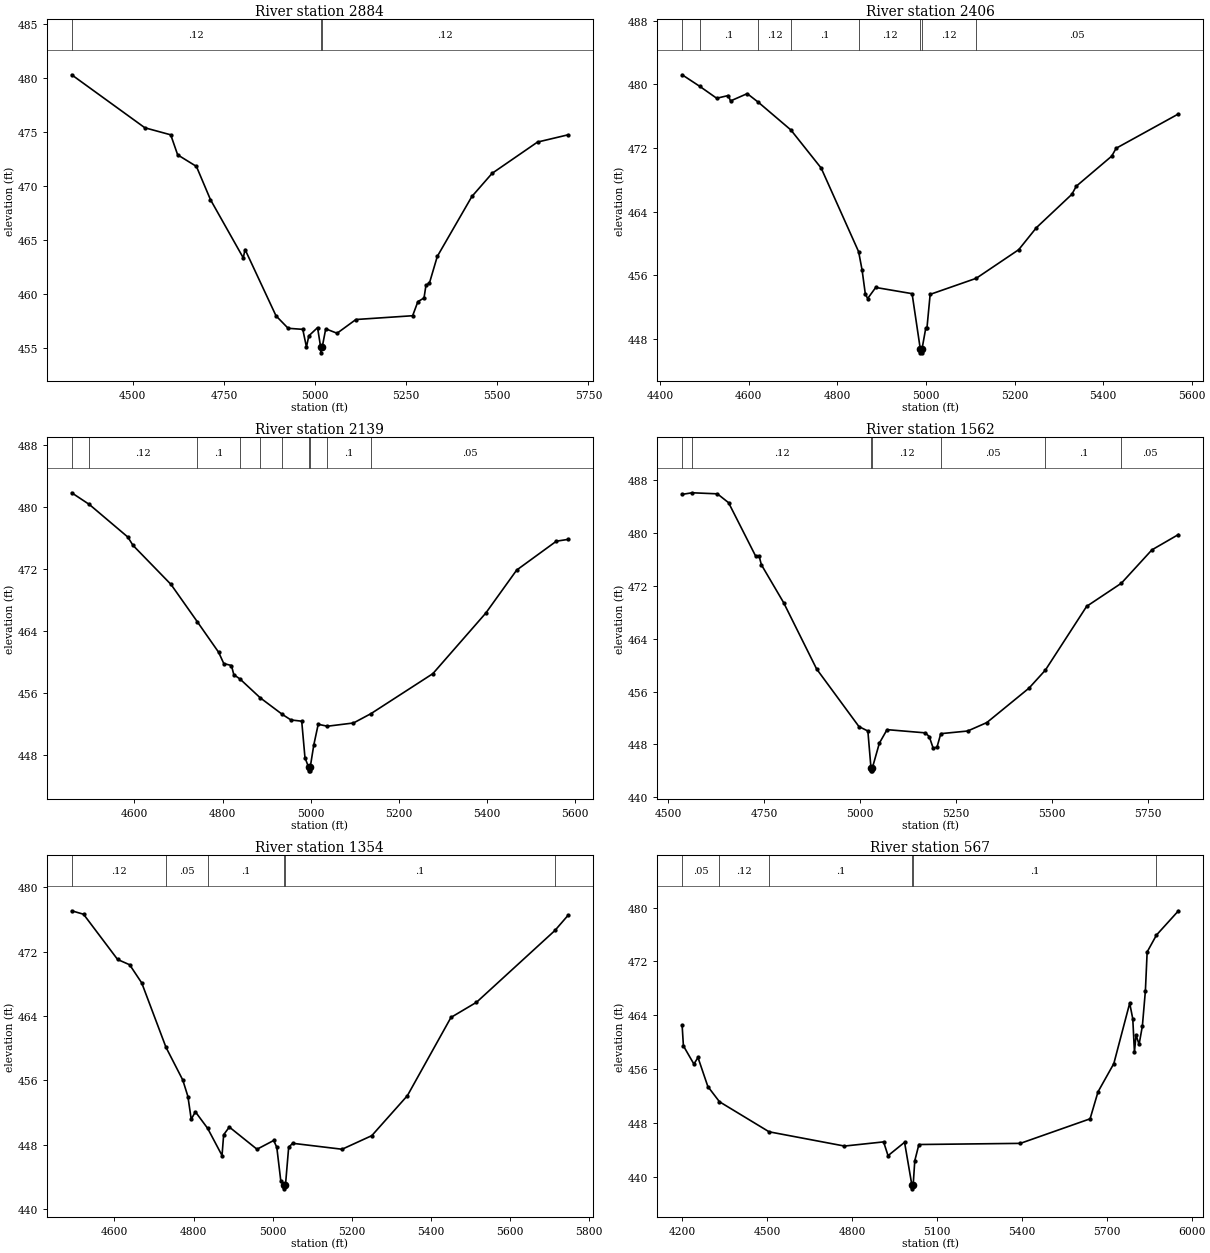
Type RM Length L Ch R = 1 ,2884    ,478,478,478
BEGIN DESCRIPTION:
Caney T12 3.0
END DESCRIPTION:
XS GIS Cut Line= 3
      2750825.86      6900773.02      2751489.57      6900847.76
      2752145.28       6901075.1
#Sta/Elev= 30
  4332.1  480.28    4533  475.38  4603.9  474.73  4622.9  472.88  4674.4  471.81
  4712.9  468.74  4802.9  463.36  4807.9  464.13  4892.8     458    4926  456.85
  4966.2  456.75  4976.3  455.12  4982.8  456.15  5006.8  456.91  5015.4  455.08
  5015.6  454.58  5019.4  455.08  5029.2   456.8  5060.3  456.39    5112  457.66
  5267.7  458.01    5282  459.31  5298.9  459.65  5304.2  460.82  5313.7  461.02
  5335.3  463.49  5430.2  469.03  5485.7  471.17  5610.3  474.06    5694  474.73
#Mann= 3 ,-1 , 0
  4332.1     .12       0  5015.4     .07       0  5019.4     .12       0
Bank Sta=5015.4,5019.4
XS Rating Curve= 0 ,0
Exp/Cntr=0.3,0.1

Type RM Length L Ch R = 1 ,2406    ,267,267,267
BEGIN DESCRIPTION:
Caney T12 2.0
END DESCRIPTION:
XS GIS Cut Line= 3
      2750890.02      6901142.45      2751426.53      6901266.22
      2751996.81      6901270.06
#Sta/Elev= 30
  4449.4  481.19  4489.1  479.74  4527.4  478.24  4553.6  478.58  4558.7   477.9
  4596.4  478.82  4621.4  477.74    4695  474.25  4763.4  469.46    4848  458.94
  4855.8  456.64  4863.2  453.59  4868.4  453.06  4886.6  454.45  4968.7  453.67
  4987.2  446.73  4987.4  446.23  4990.9  446.23  4991.2  446.73  4999.5  449.31
  5002.2  449.31  5009.5  453.58  5113.5   455.6  5209.5   459.2  5249.5  461.97
  5329.5  466.16  5339.5  467.18  5419.5  470.96  5429.5  471.95  5570.3  476.27
#Mann= 8 ,-1 , 0
  4449.4     .05       0  4489.1      .1       0  4621.4     .12       0
    4695      .1       0    4848     .12       0  4987.2     .07       0
  4991.2     .12       0  5113.5     .05       0
Bank Sta=4987.2,4991.2
XS Rating Curve= 0 ,0
Exp/Cntr=0.3,0.1

Type RM Length L Ch R = 1 ,2139    ,577,577,577
BEGIN DESCRIPTION:
Mapping XS e1e31d40
END DESCRIPTION:
XS GIS Cut Line= 3
       2750798.8       6901283.3      2751276.24      6901487.29
      2751882.43      6901482.96
#Sta/Elev= 30
    4458   481.8  4498.1  480.29  4585.4  476.08  4596.9  475.02  4683.3  469.96
  4742.6  465.17  4791.2  461.21  4802.9  459.75  4820.2   459.5  4825.7  458.31
  4839.4  457.77  4885.5  455.33  4935.8  453.18  4955.2  452.47  4979.6  452.31
    4987  447.59    4995   446.4  4995.2   445.9  4998.7   445.9    4999   446.4
    5007  449.25    5017  451.91  5037.8  451.66    5097  452.08  5136.8  453.29
    5277  458.45    5397  466.27    5467  471.82    5557  475.55  5583.4  475.78
#Mann= 10 ,-1 , 0
    4458     .05       0  4498.1     .12       0  4742.6      .1       0
  4839.4     .12       0  4885.5      .1       0  4935.8     .12       0
    4995     .07       0    4999     .12       0  5037.8      .1       0
  5136.8     .05       0
Bank Sta=4995,4999
XS Rating Curve= 0 ,0
Exp/Cntr=0.3,0.1

Type RM Length L Ch R = 1 ,1562    ,208,208,208
BEGIN DESCRIPTION:
Mapping XS 0b45aa9e
END DESCRIPTION:
XS GIS Cut Line= 3
      2750668.61      6901419.02       2750945.9      6901790.93
      2751775.33      6901801.82
#Sta/Elev= 30
  4536.1  485.86  4562.2   486.1  4627.9  485.94  4657.1   484.6    4728  476.47
  4736.4  476.57  4742.6   475.2  4800.5  469.47  4886.5  459.42  4996.9  450.69
  5020.1  450.02  5028.1  444.49  5028.4  443.99  5031.9  443.99  5032.1  444.49
  5050.1  448.19  5070.1  450.23  5170.1  449.74  5180.1  449.17  5190.1  447.45
  5200.1  447.55  5210.1  449.62  5280.1  450.02  5330.1   451.3  5440.1  456.52
  5482.6  459.24  5590.2   468.9  5680.6   472.4  5760.2  477.45  5829.5  479.78
#Mann= 7 ,-1 , 0
  4536.1     .05       0  4562.2     .12       0  5028.1     .07       0
  5032.1     .12       0  5210.1     .05       0  5482.6      .1       0
  5680.6     .05       0
Bank Sta=5028.1,5032.1
XS Rating Curve= 0 ,0
Exp/Cntr=0.3,0.1

Type RM Length L Ch R = 1 ,1354    ,787,787,787
BEGIN DESCRIPTION:
Mapping XS 386dd59f
END DESCRIPTION:
XS GIS Cut Line= 4
      2750620.87      6901607.39      2750753.81      6901969.98
       2750875.5      6901971.17      2751621.68      6901949.17
#Sta/Elev= 30
  4492.1  477.07  4522.1  476.64  4608.2  471.02  4638.7  470.36  4669.2   468.1
  4730.5   460.1  4772.9  456.04  4785.9  453.99  4794.2  451.17  4804.8  452.09
  4835.7  450.04  4872.1  446.66  4876.2  449.24  4890.5   450.2  4960.5  447.44
  5002.7  448.53  5010.5  447.68  5020.5  443.55  5028.5  443.02  5028.8  442.52
  5032.5  443.02  5040.5  447.68  5050.5  448.18  5175.5  447.44  5250.6  449.13
  5340.6   454.1  5450.7  463.82  5515.2   465.7  5713.4  474.62  5746.5   476.5
#Mann= 6 ,-1 , 0
  4492.1     .12       0  4730.5     .05       0  4835.7      .1       0
  5028.5     .07       0  5032.5      .1       0  5713.4     .05       0
Bank Sta=5028.5,5032.5
XS Rating Curve= 0 ,0
Exp/Cntr=0.3,0.1

Type RM Length L Ch R = 1 ,567     ,0,0,0
BEGIN DESCRIPTION:
Caney T12 1.0
END DESCRIPTION:
XS GIS Cut Line= 3
      2750188.25      6901902.85      2750596.42      6902591.24
      2751450.67      6902166.98
#Sta/Elev= 30
  4199.7  462.49  4204.2  459.45  4241.3  456.74  4255.7  457.72  4290.6   453.4
  4331.6  451.14    4507  446.67  4773.4  444.55  4911.7  445.17  4927.4  443.12
  4985.8  445.11  5011.9  438.69  5012.3  438.19  5016.1  438.69  5021.9  442.37
  5036.4  444.78  5394.9  444.95  5641.4   448.6  5669.5  452.62  5725.3  456.81
  5781.4  465.79  5792.3  463.46  5798.2  458.51  5803.8  461.05  5814.6  459.67
  5826.2  462.39  5836.9  467.65  5843.1  473.41    5876  475.92  5953.8  479.53
#Mann= 6 ,-1 , 0
  4199.7     .05       0  4331.6     .12       0    4507      .1       0
  5011.9     .07       0  5016.1      .1       0    5876     .12       0
Bank Sta=5011.9,5016.1
XS Rating Curve= 0 ,0
Exp/Cntr=0.3,0.1

Chan Stop Cuts=-1
Use User Specified Reach Order=0
Composite Channel Slope=5