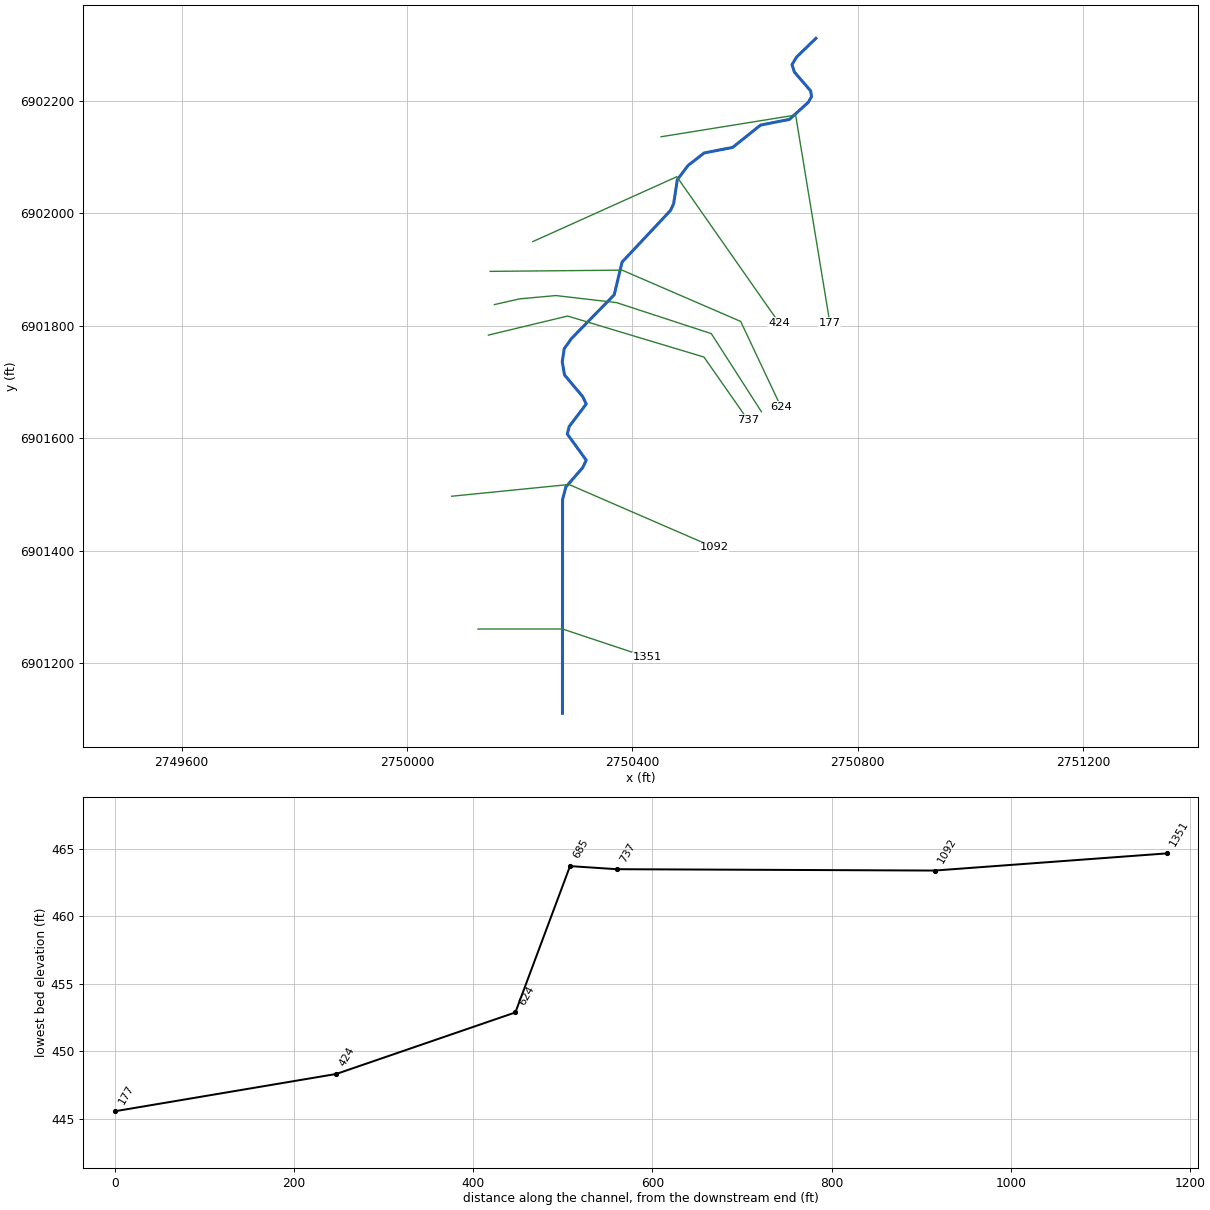
--- Caney T12_1.prj (project) ---

Proj Title=Caney T12_1 Base Level Engineering
Current Plan=p01
Default Exp/Contr=0.3,0.1
English Units
Geom File=g01
Flow File=f01
Plan File=p01
BEGIN DESCRIPTION:
Caney T12_1
END DESCRIPTION:

--- Caney T12_1.p01 (plan) ---

Plan Title=Multiple Run
Short Identifier=Multiple
Geom File=g01
Flow File=f01
Subcritical Flow
K Sum by GR= 0
Std Step Tol= 0.01
Critical Tol= 0.01
Num of Std Step Trials= 20
Max Error Tol= 0.3
Flow Tol Ratio= 0.001
Split Flow NTrial= 30
Split Flow Tol= 0.02
Split Flow Ratio= 0.02
Log Output Level= 0
Friction Slope Method= 1
Unsteady Friction Slope Method= 2
Unsteady Bridges Friction Slope Method= 1
Parabolic Critical Depth
Global Vel Dist=  1 , 1 , 1
Global Log Level= 0
CheckData=True
Encroach Param= -1, 0, 0, 0
BEGIN DESCRIPTION:
Multiple Run
END DESCRIPTION:

--- Caney T12_1.f01 (steady flow) ---

Flow Title=Multiple
Number of Profiles=7
Profile Names=10-year,25-year,50-year,1pct_min,100-year,1pct_plu,500-year
River Rch & RM= Caney T12_1,Reach-1,1351
      85      99     109      60     121     241     146
Boundary for River Rch & Prof#=Caney T12_1,Reach-1,1
Up Type=0
Dn Type=3
Dn Slope=0.005
Boundary for River Rch & Prof#=Caney T12_1,Reach-1,2
Up Type=0
Dn Type=3
Dn Slope=0.005
Boundary for River Rch & Prof#=Caney T12_1,Reach-1,3
Up Type=0
Dn Type=3
Dn Slope=0.005
Boundary for River Rch & Prof#=Caney T12_1,Reach-1,4
Up Type=0
Dn Type=3
Dn Slope=0.005
Boundary for River Rch & Prof#=Caney T12_1,Reach-1,5
Up Type=0
Dn Type=3
Dn Slope=0.005
Boundary for River Rch & Prof#=Caney T12_1,Reach-1,6
Up Type=0
Dn Type=3
Dn Slope=0.005
Boundary for River Rch & Prof#=Caney T12_1,Reach-1,7
Up Type=0
Dn Type=3
Dn Slope=0.005

--- Caney T12_1.g01 (geometry) ---

Geom Title=Existing Conditions

River Reach=Caney T12_1,Reach-1
Reach XY= 30
      2750276.00      6901111.00      2750276.18      6901491.02
      2750282.00      6901513.45      2750311.94      6901547.84
      2750318.22      6901561.10      2750284.55      6901607.67
      2750287.97      6901620.99      2750318.19      6901660.91
      2750311.86      6901674.19      2750279.56      6901712.65
      2750275.59      6901736.00      2750279.17      6901759.35
      2750292.26      6901777.66      2750367.82      6901854.96
      2750381.87      6901913.28      2750467.82      6902004.98
      2750473.44      6902017.09      2750479.89      6902059.57
      2750498.86      6902084.84      2750527.42      6902107.14
      2750578.17      6902117.11      2750627.80      6902156.81
      2750678.84      6902166.83      2750712.56      6902197.30
      2750718.25      6902207.41      2750716.71      6902217.50
      2750687.86      6902250.97      2750683.53      6902264.32
      2750691.70      6902277.77      2750726.00      6902311.00

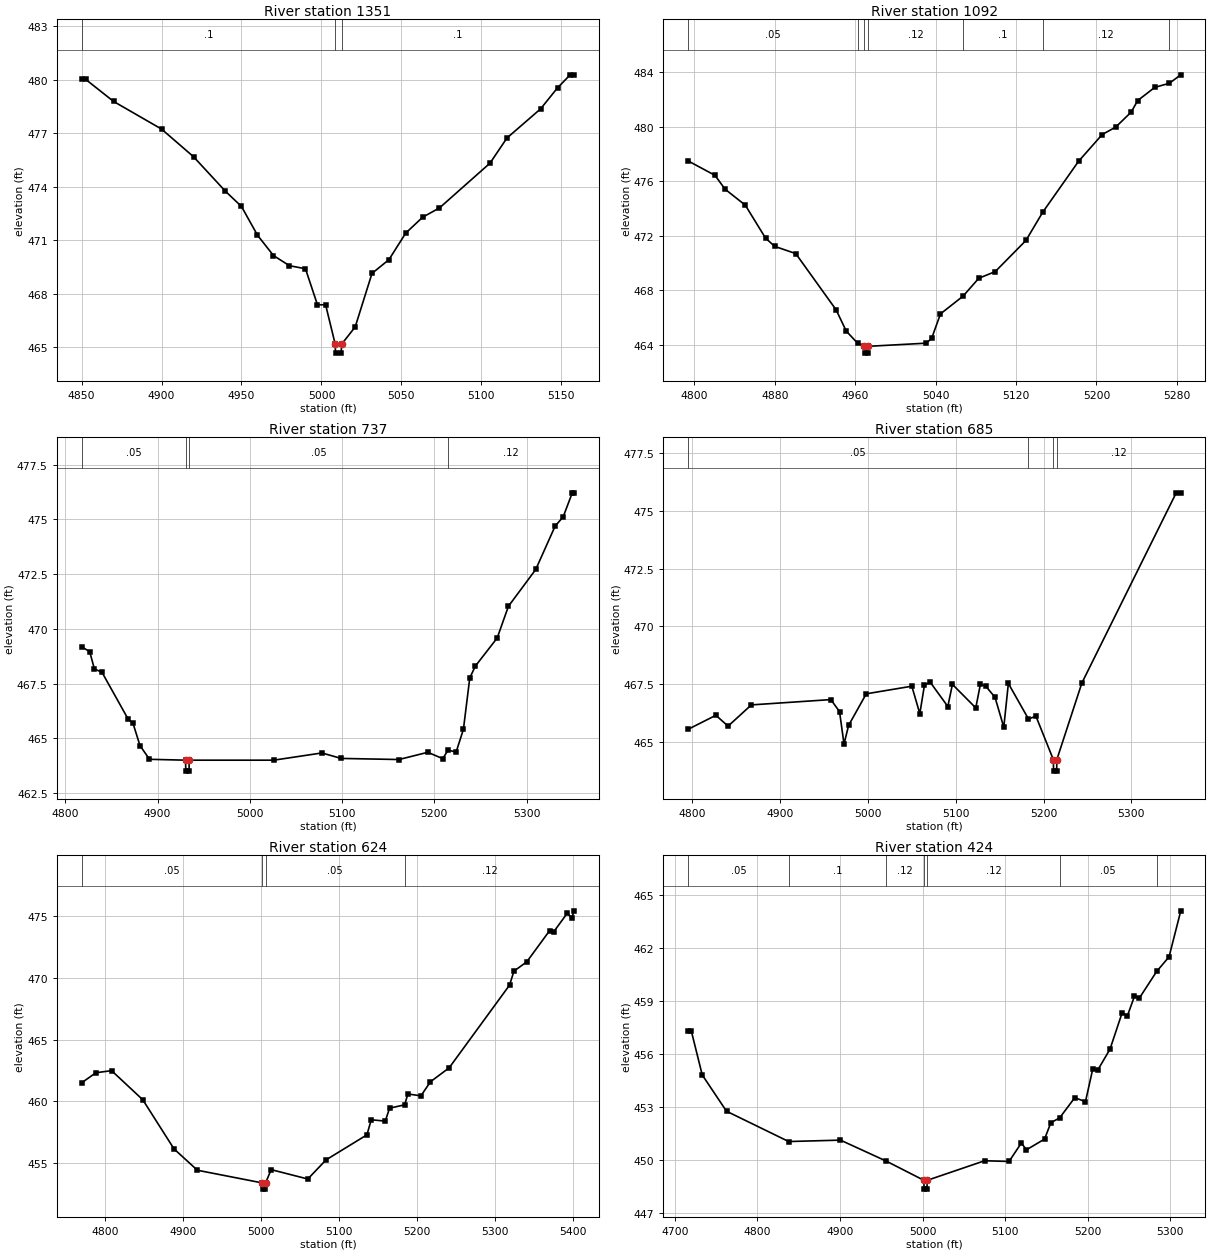
Type RM Length L Ch R = 1,1351,259,259,259
BEGIN DESCRIPTION:
Caney T12_1 2.0
END DESCRIPTION:
XS GIS Cut Line= 3
      2750125.99      6901261.00      2750276.00      6901261.00
      2750425.97      6901211.01
#Sta/Elev= 29
  4850.0  480.02  4852.5  480.02  4870.0  478.78  4900.0  477.23  4920.0  475.68
  4940.0  473.74  4950.0  472.89  4960.0  471.28  4970.0  470.14  4980.0  469.57
  4990.0  469.40  4997.5  467.38  5002.6  467.38  5008.6  465.17  5008.8  464.67
  5012.3  464.67  5012.6  465.17  5021.1  466.14  5031.6  469.14  5042.2  469.91
  5052.7  471.40  5063.3  472.29  5073.8  472.81  5105.4  475.32  5116.0  476.73
  5137.0  478.36  5147.6  479.54  5155.5  480.27  5158.1  480.27
#Mann=3,-1,0
  4850.0     0.1       0  5008.6    0.07       0  5012.6     0.1       0
Bank Sta=5008.6,5012.6
Exp/Cntr=0.3,0.1

Type RM Length L Ch R = 1,1092,355,355,355
BEGIN DESCRIPTION:
Mapping XS 1037e10a
END DESCRIPTION:
XS GIS Cut Line= 3
      2750079.33      6901497.01      2750287.70      6901517.85
      2750545.34      6901405.94
#Sta/Elev= 30
  4793.6  477.50  4820.4  476.44  4830.5  475.42  4850.6  474.25  4870.7  471.84
  4879.8  471.23  4900.8  470.70  4941.0  466.57  4951.0  465.02  4962.3  464.13
  4969.1  463.90  4969.4  463.40  4972.9  463.40  4973.1  463.90  5030.6  464.13
  5036.0  464.48  5044.8  466.28  5067.3  467.58  5082.9  468.89  5099.3  469.38
  5129.8  471.66  5146.5  473.73  5182.2  477.47  5205.7  479.43  5219.2  479.98
  5234.6  481.08  5241.0  481.92  5258.0  482.89  5272.5  483.19  5283.9  483.81
#Mann=7,-1,0
  4793.6    0.05       0  4962.3    0.12       0  4969.1    0.07       0
  4973.1    0.12       0  5067.3     0.1       0  5146.5    0.12       0
  5272.5    0.05       0
Bank Sta=4969.1,4973.1
Exp/Cntr=0.3,0.1

Type RM Length L Ch R = 1,737,52,52,52
BEGIN DESCRIPTION:
Mapping XS 01168595
END DESCRIPTION:
XS GIS Cut Line= 4
      2750144.46      6901783.47      2750285.09      6901817.33
      2750527.28      6901744.41      2750605.40      6901632.44
#Sta/Elev= 30
  4817.6  469.18  4826.4  468.96  4831.5  468.17  4839.8  468.01  4868.3  465.86
  4873.4  465.68  4880.9  464.67  4891.2  464.04  4930.3  464.00  4930.6  463.50
  4934.1  463.50  4934.3  464.00  5025.9  464.00  5078.1  464.33  5099.0  464.08
  5161.6  464.03  5192.9  464.36  5209.1  464.07  5214.9  464.46  5223.6  464.37
  5231.5  465.41  5238.4  467.76  5244.5  468.30  5268.1  469.58  5280.3  471.03
  5309.9  472.71  5330.9  474.69  5339.6  475.11  5349.5  476.21  5351.7  476.21
#Mann=4,-1,0
  4817.6    0.05       0  4930.3    0.03       0  4934.3    0.05       0
  5214.9    0.12       0
Bank Sta=4930.3,4934.3
Exp/Cntr=0.3,0.1

Type RM Length L Ch R = 1,685,61,61,61
BEGIN DESCRIPTION:
Mapping XS feb64566
END DESCRIPTION:
XS GIS Cut Line= 6
      2750155.14      6901837.69      2750199.57      6901847.84
      2750264.31      6901853.74      2750372.03      6901841.19
      2750540.30      6901786.08      2750629.25      6901647.23
#Sta/Elev= 30
  4795.2  465.54  4826.9  466.15  4840.8  465.68  4867.3  466.60  4957.8  466.83
  4967.7  466.31  4972.8  464.90  4978.0  465.71  4998.1  467.08  5050.0  467.41
  5059.1  466.22  5064.4  467.46  5071.0  467.58  5091.0  466.53  5096.2  467.49
  5122.8  466.47  5128.1  467.50  5134.2  467.41  5144.7  466.93  5154.7  465.63
  5159.9  467.53  5182.8  465.99  5191.3  466.11  5211.1  464.23  5211.4  463.73
  5214.9  463.73  5215.1  464.23  5243.6  467.55  5351.0  475.79  5356.2  475.79
#Mann=4,-1,0
  4795.2    0.05       0  5182.8    0.12       0  5211.1    0.05       0
  5215.1    0.12       0
Bank Sta=5211.1,5215.1
Exp/Cntr=0.3,0.1

Type RM Length L Ch R = 1,624,200,200,200
BEGIN DESCRIPTION:
Mapping XS 92f107e0
END DESCRIPTION:
XS GIS Cut Line= 4
      2750147.55      6901896.75      2750381.88      6901898.92
      2750592.39      6901807.78      2750663.97      6901655.94
#Sta/Elev= 30
  4770.2  461.50  4788.6  462.32  4808.7  462.49  4848.7  460.13  4888.7  456.15
  4918.7  454.42  5002.1  453.39  5002.4  452.89  5005.9  452.89  5006.1  453.39
  5013.2  454.47  5060.2  453.71  5083.6  455.26  5136.0  457.29  5141.5  458.51
  5159.5  458.40  5165.0  459.45  5184.3  459.72  5188.5  460.60  5205.2  460.45
  5217.4  461.59  5241.4  462.72  5318.8  469.42  5324.4  470.55  5340.9  471.31
  5370.0  473.82  5375.5  473.75  5392.8  475.25  5398.3  474.86  5401.8  475.44
#Mann=4,-1,0
  4770.2    0.05       0  5002.1    0.05       0  5006.1    0.05       0
  5184.3    0.12       0
Bank Sta=5002.1,5006.1
Exp/Cntr=0.3,0.1

Type RM Length L Ch R = 1,424,247,247,247
BEGIN DESCRIPTION:
Mapping XS ccce0366
END DESCRIPTION:
XS GIS Cut Line= 3
      2750223.48      6901949.73      2750479.13      6902065.01
      2750660.19      6901805.83
#Sta/Elev= 30
  4716.1  457.28  4720.2  457.28  4733.3  454.81  4762.7  452.75  4838.0  451.03
  4900.7  451.11  4956.1  449.92  5001.7  448.83  5001.9  448.33  5005.4  448.33
  5005.7  448.83  5075.2  449.94  5104.8  449.90  5119.7  450.95  5125.8  450.56
  5147.8  451.17  5155.4  452.10  5166.0  452.37  5184.4  453.52  5197.3  453.29
  5206.0  455.12  5212.1  455.08  5227.0  456.27  5241.8  458.35  5247.9  458.14
  5256.6  459.27  5262.7  459.18  5283.5  460.68  5298.5  461.51  5312.7  464.12
#Mann=7,-1,0
  4716.1    0.05       0  4838.0     0.1       0  4956.1    0.12       0
  5001.7    0.07       0  5005.7    0.12       0  5166.0    0.05       0
  5283.5    0.12       0
Bank Sta=5001.7,5005.7
Exp/Cntr=0.3,0.1

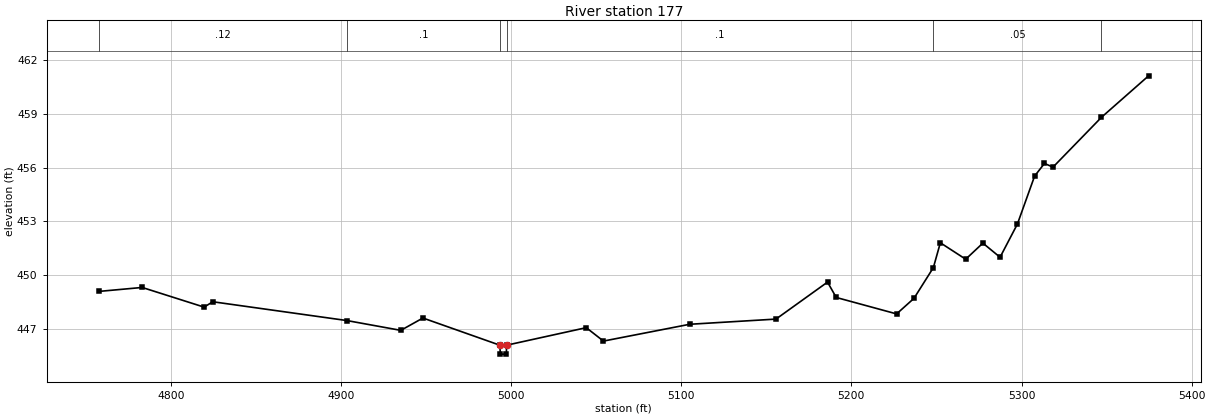
Type RM Length L Ch R = 1,177,0,0,0
BEGIN DESCRIPTION:
Caney T12_1 1.0
END DESCRIPTION:
XS GIS Cut Line= 3
      2750451.01      6902136.00      2750690.01      6902174.61
      2750750.82      6901804.88
#Sta/Elev= 30
  4757.9  449.08  4783.2  449.30  4819.6  448.20  4824.7  448.50  4903.4  447.45
  4935.2  446.90  4948.2  447.59  4993.4  446.07  4993.7  445.57  4997.2  445.57
  4997.4  446.07  5044.2  447.05  5054.3  446.30  5105.0  447.24  5155.7  447.53
  5186.0  449.60  5191.1  448.74  5226.6  447.82  5236.8  448.69  5248.2  450.41
  5252.3  451.80  5267.2  450.88  5277.3  451.78  5287.4  450.99  5297.6  452.85
  5307.7  455.53  5313.5  456.24  5318.5  456.03  5347.0  458.82  5374.7  461.14
#Mann=6,-1,0
  4757.9    0.12       0  4903.4     0.1       0  4993.4    0.07       0
  4997.4     0.1       0  5248.2    0.05       0  5347.0    0.12       0
Bank Sta=4993.4,4997.4
Exp/Cntr=0.3,0.1

Chan Stop Cuts=-1