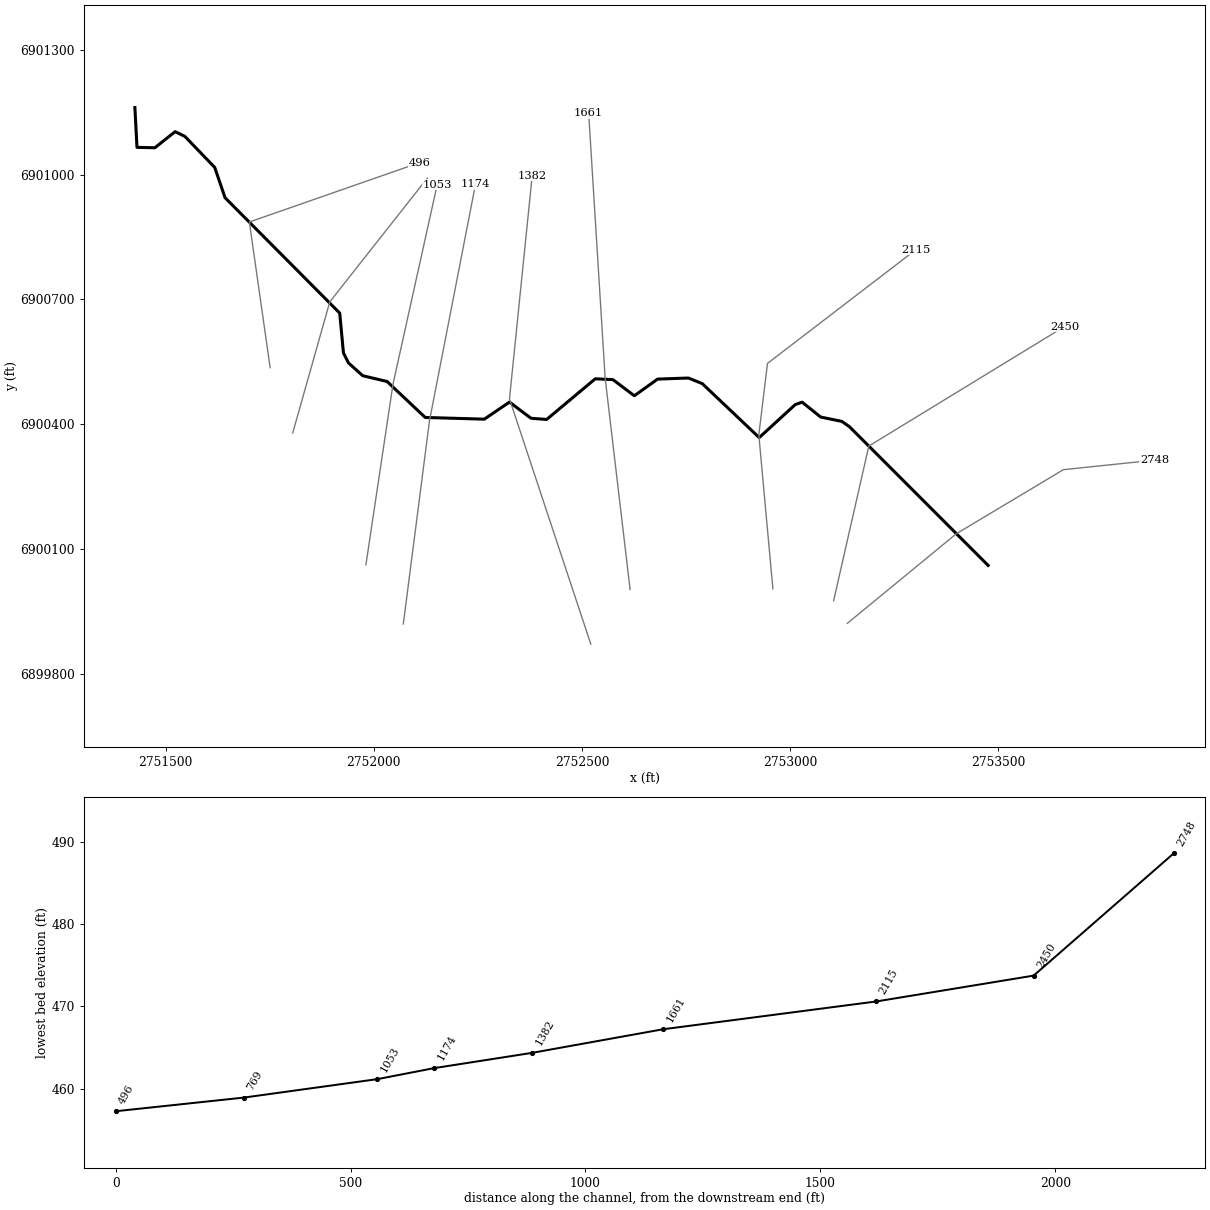
--- Caney T12_2.prj (project) ---

Proj Title=Caney T12_2 Base Level Engineering
Current Plan=p01
Default Exp/Contr=0.3,0.1
English Units
Geom File=g01
Flow File=f01
Plan File=p01
Y Axis Title=Elevation
X Axis Title(PF)=Main Channel Distance
X Axis Title(XS)=Station
BEGIN DESCRIPTION:
Caney T12_2
END DESCRIPTION:
DSS Export Rating Curves= 0
DSS Export Rating Curve Sorted= 0
DSS Export Volume Flow Curves= 0
DXF OffsetX= 0
DXF OffsetY= 0
DXF ScaleX= 1
DXF ScaleY= 10

--- Caney T12_2.p01 (plan) ---

Plan Title=Multiple Run
Short Identifier=Multiple
Geom File=g01
Flow File=f01
Subcritical Flow
K Sum by GR= 0
Std Step Tol= 0.01
Critical Tol= 0.01
Num of Std Step Trials= 20
Max Error Tol= 0.3
Flow Tol Ratio= 0.001
Split Flow NTrial= 30
Split Flow Tol= 0.02
Split Flow Ratio= 0.02
Log Output Level= 0
Friction Slope Method= 1
Unsteady Friction Slope Method= 2
Unsteady Bridges Friction Slope Method= 1
Parabolic Critical Depth
Global Vel Dist=  1 , 1 , 1
Global Log Level= 0
CheckData=True
Encroach Param= -1, 0, 0, 0
BEGIN DESCRIPTION:
Multiple Run
END DESCRIPTION:

--- Caney T12_2.f01 (steady flow) ---

Flow Title=Multiple
Program Version=4.10
Number of Profiles= 7
Profile Names=10-year,25-year,50-year,1pct_min,100-year,1pct_plu,500-year
River Rch & RM=Caney T12_2,Reach-1         ,2748
     200     251     291     168     335     669     446
River Rch & RM=Caney T12_2,Reach-1         ,2450
     324     423     501     296     591    1179     821
Boundary for River Rch & Prof#=Caney T12_2,Reach-1         , 1
Up Type= 0
Dn Type= 3
Dn Slope=0.00834
Boundary for River Rch & Prof#=Caney T12_2,Reach-1         , 2
Up Type= 0
Dn Type= 3
Dn Slope=0.00834
Boundary for River Rch & Prof#=Caney T12_2,Reach-1         , 3
Up Type= 0
Dn Type= 3
Dn Slope=0.00834
Boundary for River Rch & Prof#=Caney T12_2,Reach-1         , 4
Up Type= 0
Dn Type= 3
Dn Slope=0.00834
Boundary for River Rch & Prof#=Caney T12_2,Reach-1         , 5
Up Type= 0
Dn Type= 3
Dn Slope=0.00834
Boundary for River Rch & Prof#=Caney T12_2,Reach-1         , 6
Up Type= 0
Dn Type= 3
Dn Slope=0.00834
Boundary for River Rch & Prof#=Caney T12_2,Reach-1         , 7
Up Type= 0
Dn Type= 3
Dn Slope=0.00834
DSS Import GetInterval= 0
DSS Import GetPeak= 0
DSS Import FillOption= 0

--- Caney T12_2.g01 (geometry) ---

Geom Title=Existing Conditions
Program Version=4.10

River Reach=Caney T12_2     ,Reach-1
Reach XY= 30
        2753476.        6900061.      2753142.67      6900394.37
      2753124.35      6900407.09      2753073.71      6900417.43
      2753029.23      6900453.15      2753012.62      6900447.43
        2752926.       6900368.1       2752789.3      6900497.66
      2752755.94       6900511.2       2752681.9      6900508.64
      2752625.99       6900468.6      2752574.35      6900507.43
      2752532.05      6900509.33      2752415.36      6900411.65
      2752377.65      6900414.58      2752326.01      6900453.41
      2752265.56      6900412.37      2752123.56      6900416.47
      2752032.02      6900502.81      2751973.43      6900516.74
      2751939.26      6900547.35       2751927.1      6900571.33
      2751918.14      6900667.17      2751642.65      6900944.33
      2751617.84      6901017.09      2751546.06      6901091.72
      2751522.74      6901103.09      2751473.96      6901064.41
        2751431.      6901065.33        2751426.        6901161.

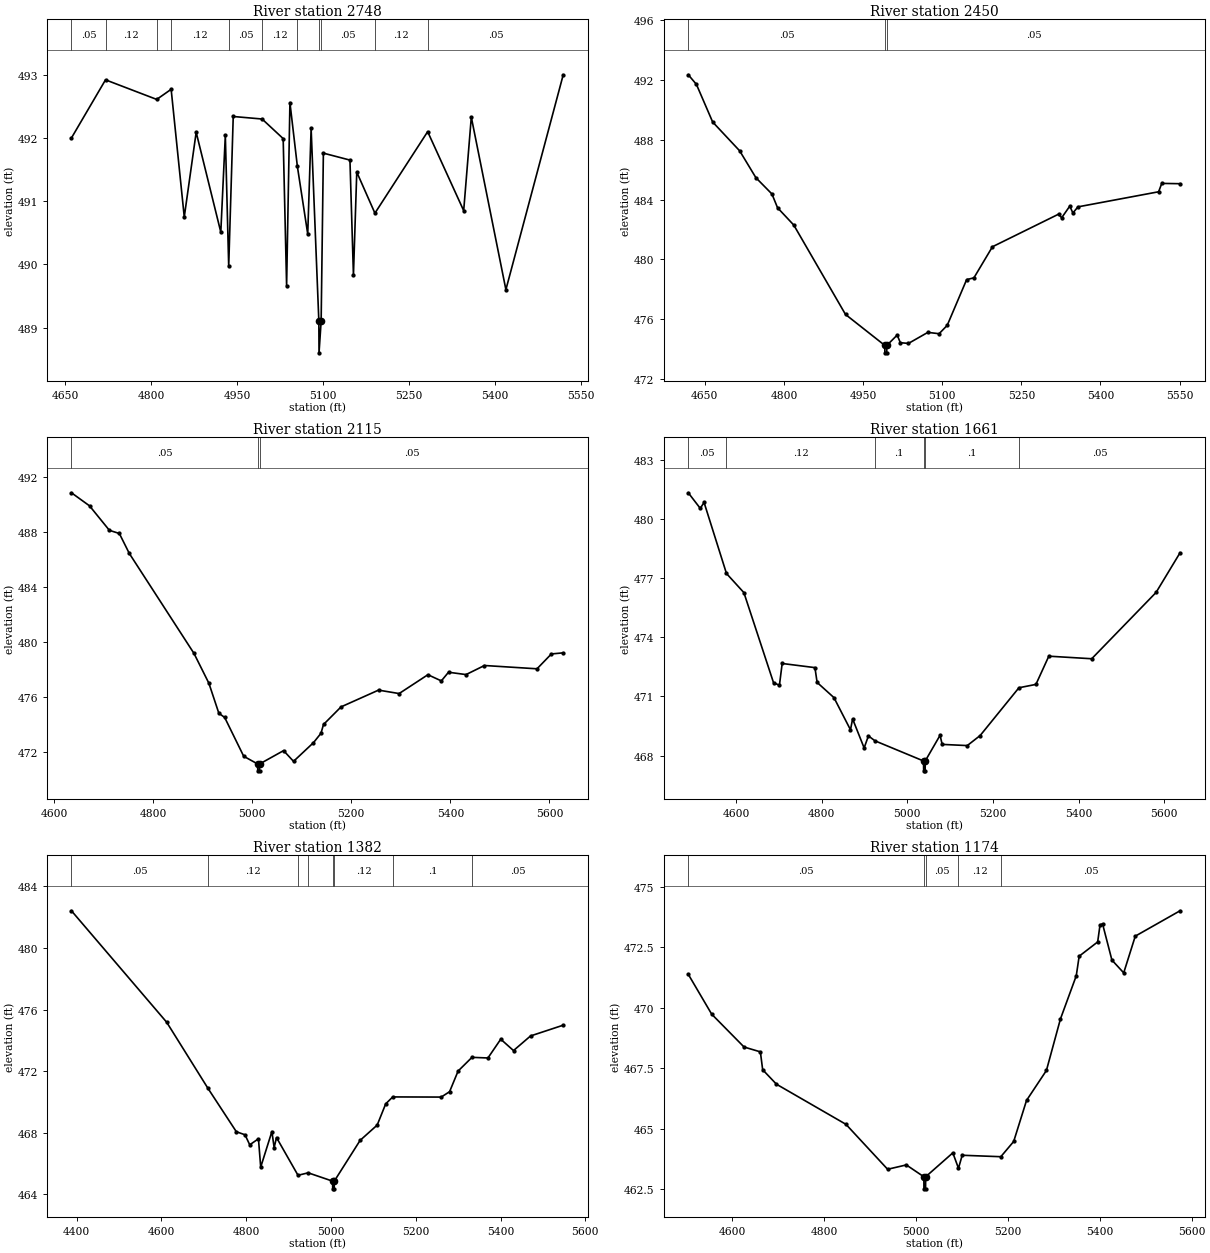
Type RM Length L Ch R = 1 ,2748    ,298,298,298
BEGIN DESCRIPTION:
Caney T12_2 5.0
END DESCRIPTION:
XS GIS Cut Line= 4
      2753137.75      6899921.83      2753399.79      6900137.21
      2753656.96      6900291.05      2753875.61      6900313.85
#Sta/Elev= 30
  4660.8     492  4720.3  492.92  4809.7  492.61  4834.9  492.77  4857.8  490.75
  4878.6  492.09  4921.6  490.51  4929.5  492.04  4935.4  489.97  4943.3  492.34
  4993.7   492.3  5030.5  491.99  5036.5  489.66  5042.3  492.56  5055.3  491.55
  5073.4  490.48  5079.3  492.15  5092.8   489.1  5093.1   488.6  5096.8   489.1
  5100.7  491.76  5147.1  491.65  5153.2  489.83    5159  491.46  5190.7  490.81
  5282.8   492.1  5345.7  490.85    5359  492.33  5419.4   489.6  5519.5     493
#Mann= 11 ,-1 , 0
  4660.8     .05       0  4720.3     .12       0  4809.7     .05       0
  4834.9     .12       0  4935.4     .05       0  4993.7     .12       0
  5055.3     .05       0  5092.8     .07       0  5096.8     .05       0
  5190.7     .12       0  5282.8     .05       0
Bank Sta=5092.8,5096.8
XS Rating Curve= 0 ,0
Exp/Cntr=0.3,0.1

Type RM Length L Ch R = 1 ,2450    ,335,335,335
BEGIN DESCRIPTION:
Caney T12_2 4.0
END DESCRIPTION:
XS GIS Cut Line= 3
      2753104.76      6899975.98      2753189.38      6900347.78
      2753659.45      6900634.85
#Sta/Elev= 30
  4618.7  492.36  4634.1  491.72  4664.9   489.2  4716.1  487.27  4746.9  485.47
  4777.3  484.38  4787.9  483.46  4818.7   482.3  4916.7  476.32  4991.1  474.25
  4991.3  473.75  4994.8  473.75  4995.1  474.25  5014.7  474.94  5020.6  474.43
    5036  474.38  5072.8  475.12  5094.1  475.03  5109.5  475.59  5146.3  478.65
  5160.1  478.77  5195.2  480.85  5320.5  483.03  5326.4  482.79  5341.8  483.57
  5347.7  483.11  5357.3  483.52  5510.2  484.53  5516.1  485.09  5550.8  485.07
#Mann= 3 ,-1 , 0
  4618.7     .05       0  4991.1     .04       0  4995.1     .05       0
Bank Sta=4991.1,4995.1
XS Rating Curve= 0 ,0
Exp/Cntr=0.3,0.1

Type RM Length L Ch R = 1 ,2115    ,454,454,454
BEGIN DESCRIPTION:
Mapping XS e6e3e62f
END DESCRIPTION:
XS GIS Cut Line= 4
      2752958.92      6900004.67      2752925.07      6900374.42
       2752945.9       6900546.3      2753301.85      6900819.11
#Sta/Elev= 30
    4635  490.83  4671.5  489.88  4711.6   488.1  4731.7  487.87  4751.8  486.42
  4882.4  479.15  4912.5  476.98  4932.6   474.8  4944.4  474.49  4982.8  471.67
  5010.9  471.11  5011.2  470.61  5014.7  470.61  5014.9  471.11  5063.3  472.08
  5083.4   471.3  5123.7  472.66  5138.8  473.34  5143.9  473.98  5179.3  475.26
    5255  476.48  5296.6  476.23  5354.7   477.6  5381.8  477.15  5396.3  477.78
  5431.7  477.61  5468.9  478.27    5575  478.03    5604  479.11  5627.9  479.19
#Mann= 3 ,-1 , 0
    4635     .05       0  5010.9     .04       0  5014.9     .05       0
Bank Sta=5010.9,5014.9
XS Rating Curve= 0 ,0
Exp/Cntr=0.3,0.1

Type RM Length L Ch R = 1 ,1661    ,279,279,279
BEGIN DESCRIPTION:
Caney T12_2 3.0
END DESCRIPTION:
XS GIS Cut Line= 3
      2752615.77      6900003.17      2752555.84      6900511.25
      2752516.28      6901146.92
#Sta/Elev= 30
  4488.4  481.32  4516.4  480.53  4525.3  480.83  4577.6  477.23  4618.3  476.26
  4687.6  471.69  4701.3  471.57  4707.7  472.67  4784.2  472.46  4789.3  471.71
  4828.6  470.94  4867.2  469.31  4872.2  469.86  4899.1  468.39  4909.1     469
  4924.5  468.75  5037.8  467.73  5038.1  467.23  5041.6  467.23  5041.8  467.73
  5076.4  469.03  5081.4  468.57    5140  468.51  5170.1  469.02  5260.6  471.44
  5300.3  471.61  5330.4  473.04  5430.6  472.91  5580.9  476.27  5636.9  478.28
#Mann= 6 ,-1 , 0
  4488.4     .05       0  4577.6     .12       0  4924.5      .1       0
  5037.8     .07       0  5041.8      .1       0  5260.6     .05       0
Bank Sta=5037.8,5041.8
XS Rating Curve= 0 ,0
Exp/Cntr=0.3,0.1

Type RM Length L Ch R = 1 ,1382    ,208,208,208
BEGIN DESCRIPTION:
Caney T12_2 2.0
END DESCRIPTION:
XS GIS Cut Line= 3
      2752521.42      6899871.82        2752326.        6900461.
      2752380.62      6900997.68
#Sta/Elev= 30
  4387.7  482.42  4612.4  475.18  4709.7  470.89  4776.7  468.07  4797.2  467.87
  4808.3  467.22  4828.9  467.61  4834.2  465.77  4860.6  468.08  4865.9  467.04
  4871.5  467.69  4922.2  465.24  4946.2   465.4  5003.8  464.86  5004.1  464.36
  5007.6  464.36  5007.8  464.86  5068.8  467.51    5109   468.5  5129.1  469.88
  5145.7  470.33  5260.1  470.32  5279.8  470.67  5299.9  472.01  5332.6   472.9
  5370.3  472.86  5400.5  474.08  5430.6  473.34  5470.8  474.29  5547.9  474.99
#Mann= 8 ,-1 , 0
  4387.7     .05       0  4709.7     .12       0  4922.2      .1       0
  4946.2     .12       0  5003.8     .07       0  5007.8     .12       0
  5145.7      .1       0  5332.6     .05       0
Bank Sta=5003.8,5007.8
XS Rating Curve= 0 ,0
Exp/Cntr=0.3,0.1

Type RM Length L Ch R = 1 ,1174    ,121,121,121
BEGIN DESCRIPTION:
Mapping XS b05634d6
END DESCRIPTION:
XS GIS Cut Line= 3
      2752070.91      6899920.47      2752133.84      6900408.71
      2752244.39      6900976.67
#Sta/Elev= 30
  4503.9  471.39  4554.9  469.74  4625.4  468.38  4660.9  468.18  4665.9  467.44
    4696  466.84  4847.3  465.18    4938  463.32  4978.7   463.5  5016.9  463.01
  5017.1  462.51  5020.6  462.51  5020.9  463.01    5080     464  5092.3  463.36
  5100.4   463.9  5184.5  463.84  5212.5  464.47  5240.5  466.17  5283.8  467.41
  5314.3  469.54  5348.8  471.33  5355.1  472.14  5395.4  472.73  5400.5  473.43
    5406  473.48  5426.4  471.98  5452.1  471.45  5477.3  472.97  5574.8  474.02
#Mann= 5 ,-1 , 0
  4503.9     .05       0  5016.9     .05       0  5020.9     .05       0
  5092.3     .12       0  5184.5     .05       0
Bank Sta=5016.9,5020.9
XS Rating Curve= 0 ,0
Exp/Cntr=0.3,0.1

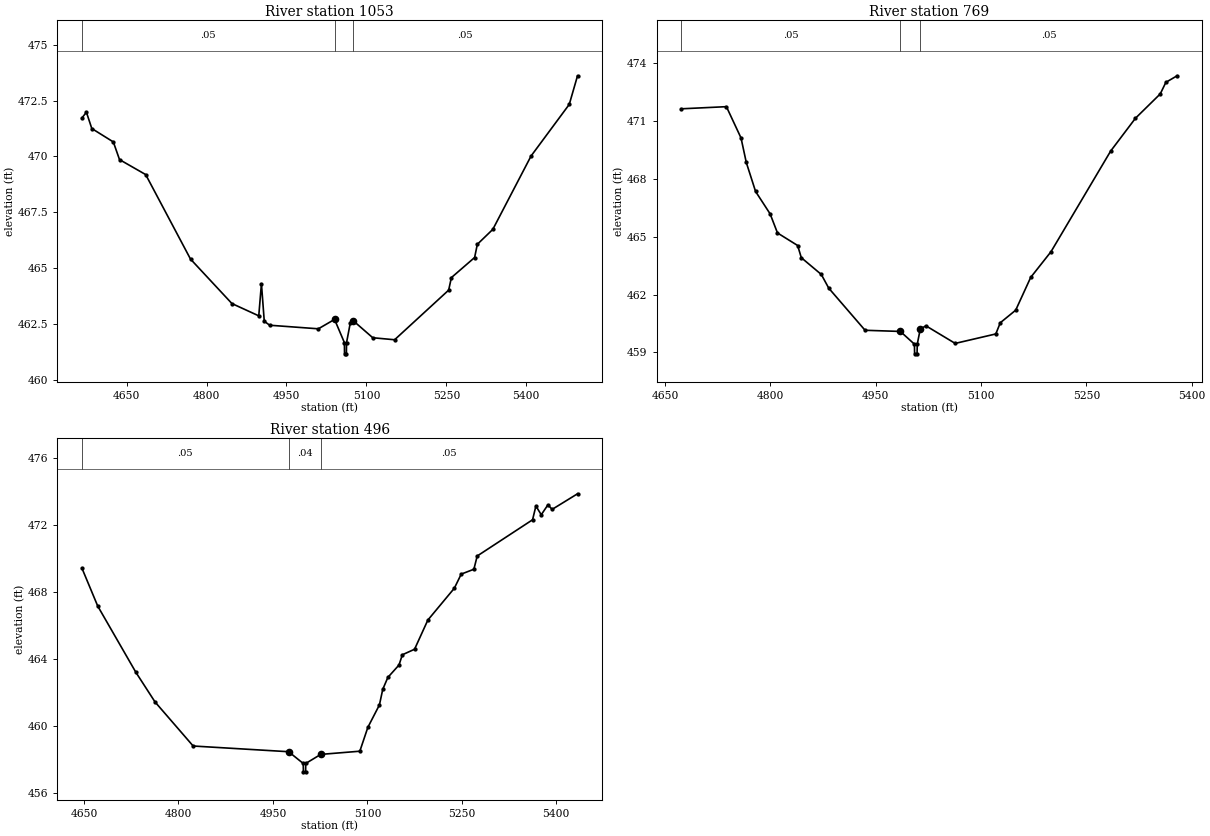
Type RM Length L Ch R = 1 ,1053    ,284,284,284
BEGIN DESCRIPTION:
Mapping XS cb0bb307
END DESCRIPTION:
XS GIS Cut Line= 3
      2751981.05       6900062.6      2752046.16      6900496.68
      2752152.46       6900976.1
#Sta/Elev= 30
  4566.1  471.72  4574.6  471.98  4584.7  471.25  4625.1  470.65  4636.7  469.86
  4685.8  469.19  4769.9  465.41  4847.6  463.42    4898  462.87    4903  464.31
  4908.3  462.63  4918.4  462.45  5009.8  462.29  5040.2  462.71  5058.7  461.67
  5058.9  461.17  5062.4  461.17  5062.7  461.67  5069.7  462.55  5074.8  462.66
  5111.9  461.89  5152.9   461.8  5254.3  464.02  5259.4  464.58    5303  465.48
  5308.1  466.07  5337.2  466.74  5408.9  470.02  5480.6  472.33  5496.1  473.61
#Mann= 3 ,-1 , 0
  4566.1     .05       0  5040.2     .04       0  5074.8     .05       0
Bank Sta=5040.2,5074.8
XS Rating Curve= 0 ,0
Exp/Cntr=0.3,0.1

Type RM Length L Ch R = 1 ,769     ,273,273,273
BEGIN DESCRIPTION:
Mapping XS 82d74bbb
END DESCRIPTION:
XS GIS Cut Line= 3
      2751805.27      6900379.44      2751894.25      6900694.16
      2752128.61      6900991.44
#Sta/Elev= 30
  4673.6  471.62  4737.6  471.73  4758.4  470.11  4765.9  468.84  4779.1  467.34
  4799.8  466.18  4810.3  465.19    4839  464.54  4844.2  463.91  4872.7  463.04
  4883.3  462.33    4935  460.15  4985.2  460.09  5005.3  459.43  5005.5  458.93
    5009  458.93  5009.3  459.43  5013.6  460.22  5021.7  460.38  5063.3  459.47
  5121.1  459.96  5127.5  460.54  5149.4  461.19  5170.8  462.89  5199.7  464.22
  5284.6  469.43  5319.9  471.13  5355.2  472.39  5363.2  472.99  5379.2  473.33
#Mann= 3 ,-1 , 0
  4673.6     .05       0  4985.2     .04       0  5013.6     .05       0
Bank Sta=4985.2,5013.6
XS Rating Curve= 0 ,0
Exp/Cntr=0.3,0.1

Type RM Length L Ch R = 1 ,496     ,0,0,0
BEGIN DESCRIPTION:
Caney T12_2 1.0
END DESCRIPTION:
XS GIS Cut Line= 3
      2751750.99      6900536.04        2751701.        6900886.
       2752110.4      6901028.79
#Sta/Elev= 30
  4646.6  469.42  4671.8  467.15  4732.4   463.2  4762.7  461.44  4823.3  458.81
  4974.9  458.47  4998.1  457.77  4998.4  457.27  5001.9  457.27  5002.1  457.77
  5025.9  458.31    5088   458.5  5100.7  459.92  5119.1  461.26  5124.4  462.19
  5132.5   462.9  5150.2  463.64  5155.5  464.25  5174.9  464.58    5196  466.32
  5238.1  468.22    5249  469.06  5269.1  469.35  5274.4  470.14  5362.3   472.3
  5367.6  473.12  5376.1   472.6  5386.7  473.19  5393.4  472.92  5433.7  473.85
#Mann= 3 ,-1 , 0
  4646.6     .05       0  4974.9     .04       0  5025.9     .05       0
Bank Sta=4974.9,5025.9
XS Rating Curve= 0 ,0
Exp/Cntr=0.3,0.1

Chan Stop Cuts=-1
Use User Specified Reach Order=0
Composite Channel Slope=5