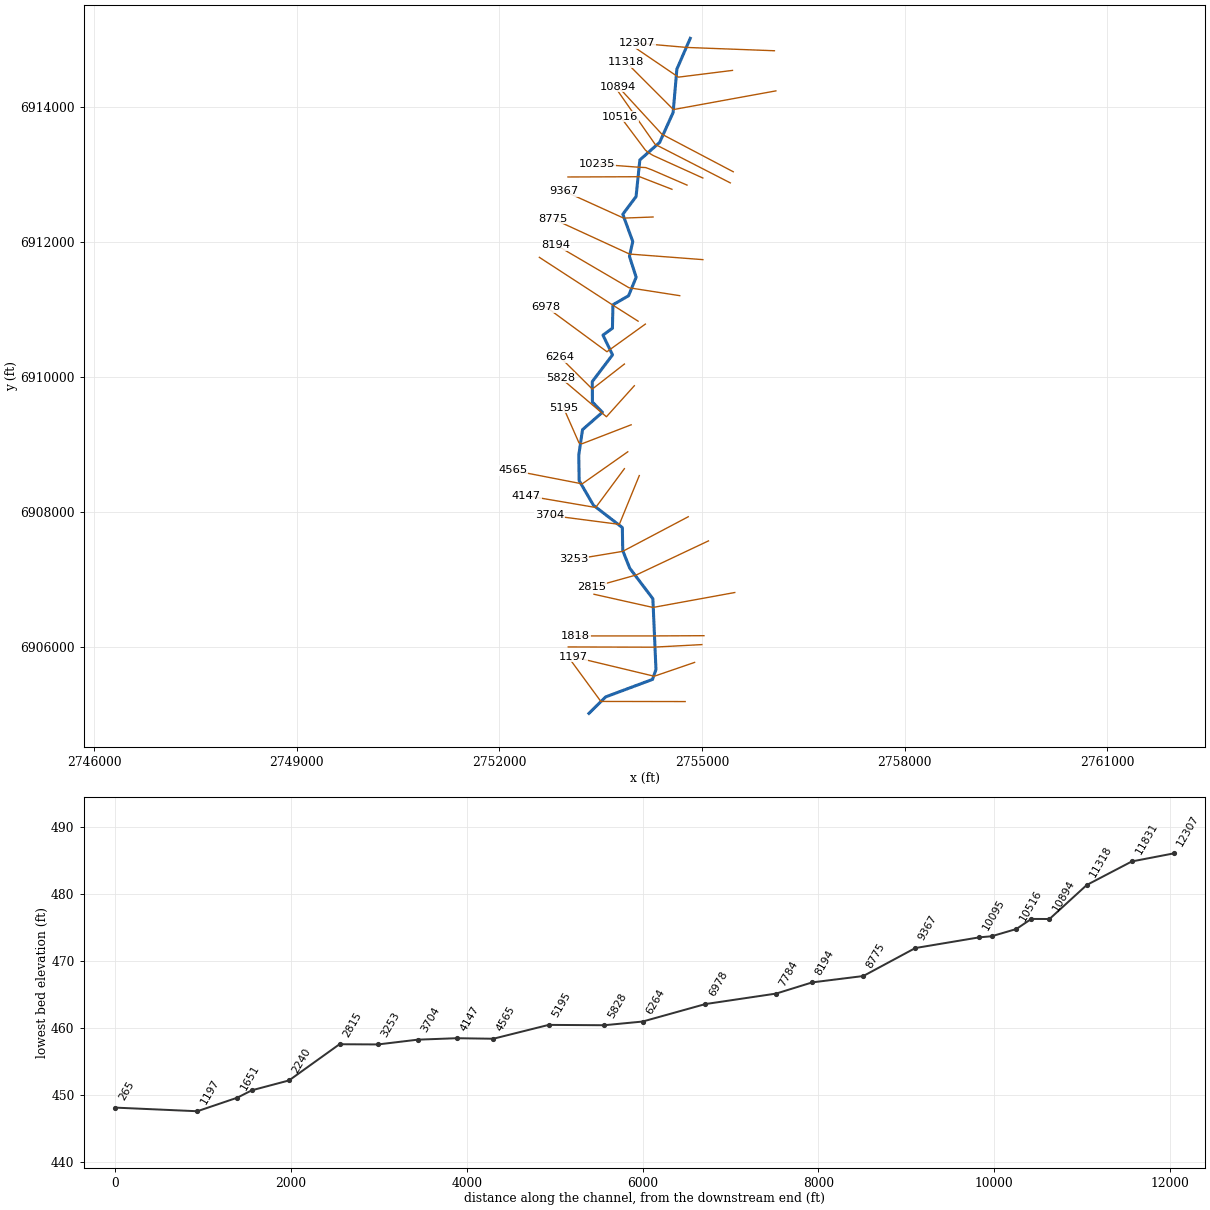
--- Caney T13.prj (project) ---

Proj Title=Caney T13 Base Level Engineering
Current Plan=p01
Default Exp/Contr=0.3,0.1
English Units
Geom File=g01
Flow File=f01
Plan File=p01
Y Axis Title=Elevation
X Axis Title(PF)=Main Channel Distance
X Axis Title(XS)=Station
BEGIN DESCRIPTION:
Caney T13
END DESCRIPTION:
DSS Export Rating Curves= 0
DSS Export Rating Curve Sorted= 0
DSS Export Volume Flow Curves= 0
DXF OffsetX= 0
DXF OffsetY= 0
DXF ScaleX= 1
DXF ScaleY= 10

--- Caney T13.p01 (plan) ---

Plan Title=Multiple Run
Short Identifier=Multiple
Geom File=g01
Flow File=f01
Subcritical Flow
K Sum by GR= 0
Std Step Tol= 0.01
Critical Tol= 0.01
Num of Std Step Trials= 20
Max Error Tol= 0.3
Flow Tol Ratio= 0.001
Split Flow NTrial= 30
Split Flow Tol= 0.02
Split Flow Ratio= 0.02
Log Output Level= 0
Friction Slope Method= 1
Unsteady Friction Slope Method= 2
Unsteady Bridges Friction Slope Method= 1
Parabolic Critical Depth
Global Vel Dist=  1 , 1 , 1
Global Log Level= 0
CheckData=True
Encroach Param= -1, 0, 0, 0
BEGIN DESCRIPTION:
Multiple Run
END DESCRIPTION:

--- Caney T13.f01 (steady flow) ---

Flow Title=Multiple
Program Version=4.10
Number of Profiles= 7
Profile Names=10-year,25-year,50-year,1pct_min,100-year,1pct_plu,500-year
River Rch & RM=Caney T13,Reach-1         ,12307
     352     456     538     316     631    1258     866
River Rch & RM=Caney T13,Reach-1         ,11318
     530     705     846     505    1007    2010    1431
River Rch & RM=Caney T13,Reach-1         ,9367
     596     795     955     570    1137    2269    1616
River Rch & RM=Caney T13,Reach-1         ,4565
     803    1086    1317     792    1581    3155    2285
River Rch & RM=Caney T13,Reach-1         ,3253
     945    1289    1572     950    1896    3784    2768
Boundary for River Rch & Prof#=Caney T13,Reach-1         , 1
Up Type= 0
Dn Type= 3
Dn Slope=0.005
Boundary for River Rch & Prof#=Caney T13,Reach-1         , 2
Up Type= 0
Dn Type= 3
Dn Slope=0.005
Boundary for River Rch & Prof#=Caney T13,Reach-1         , 3
Up Type= 0
Dn Type= 3
Dn Slope=0.005
Boundary for River Rch & Prof#=Caney T13,Reach-1         , 4
Up Type= 0
Dn Type= 3
Dn Slope=0.005
Boundary for River Rch & Prof#=Caney T13,Reach-1         , 5
Up Type= 0
Dn Type= 3
Dn Slope=0.005
Boundary for River Rch & Prof#=Caney T13,Reach-1         , 6
Up Type= 0
Dn Type= 3
Dn Slope=0.005
Boundary for River Rch & Prof#=Caney T13,Reach-1         , 7
Up Type= 0
Dn Type= 3
Dn Slope=0.005
DSS Import GetInterval= 0
DSS Import GetPeak= 0
DSS Import FillOption= 0

--- Caney T13.g01 (geometry) ---

Geom Title=Existing Conditions

River Reach=Caney T13,Reach-1
Reach XY= 30
      2754826.00      6915011.00      2754628.07      6914555.14
      2754572.25      6913912.55      2754372.84      6913469.32
      2754079.75      6913209.45      2754023.73      6912666.94
      2753827.61      6912404.97      2753974.90      6912000.45
      2753925.91      6911781.10      2754025.26      6911471.67
      2753912.64      6911197.66      2753681.28      6911063.71
      2753674.01      6910716.68      2753533.69      6910614.67
      2753675.30      6910321.70      2753375.51      6909926.20
      2753377.62      6909622.83      2753525.50      6909471.50
      2753231.35      6909213.73      2753175.53      6908836.20
      2753181.47      6908458.55      2753392.64      6908094.32
      2753820.54      6907763.46      2753826.75      6907421.67
      2753929.54      6907162.47      2754272.46      6906709.54
      2754318.44      6905661.00      2754267.85      6905514.37
      2753573.70      6905255.17      2753326.00      6905011.00

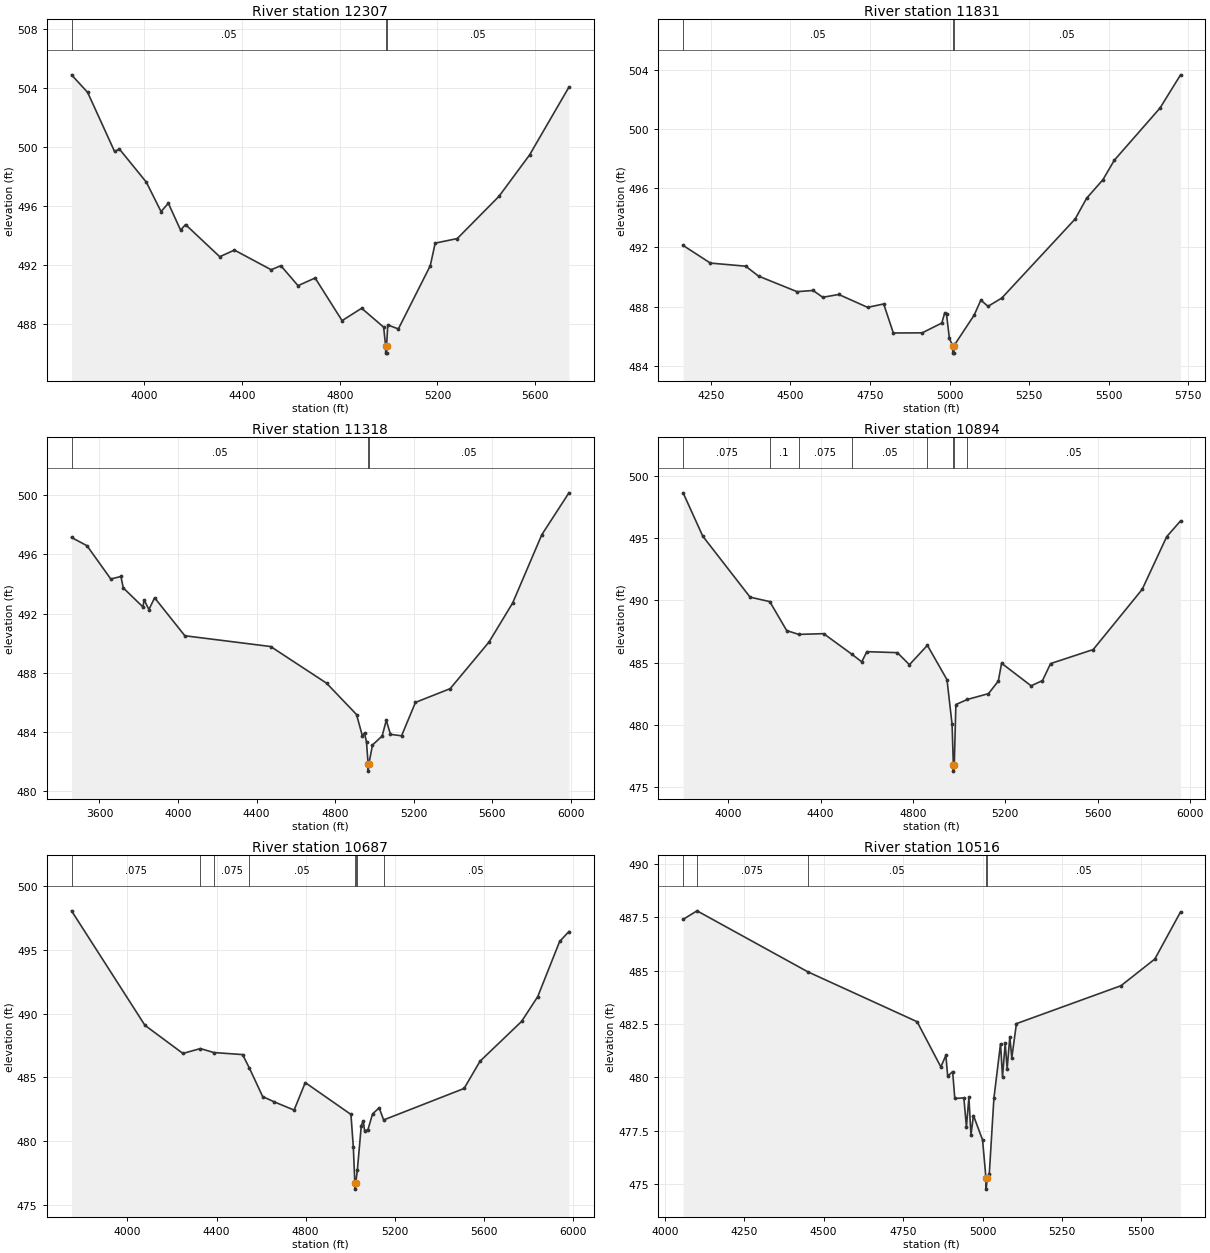
Type RM Length L Ch R = 1,12307,476,476,476
BEGIN DESCRIPTION:
Caney T13 23.0
END DESCRIPTION:
XS GIS Cut Line= 3
      2756071.83      6914827.21      2754775.85      6914876.06
      2754040.82      6914940.04
#Sta/Elev= 30
  3703.1  504.91  3769.0  503.72  3879.1  499.72  3899.1  499.88  4009.1  497.64
  4069.2  495.65  4099.2  496.21  4149.2  494.39  4169.3  494.77  4309.4  492.59
  4369.4  493.04  4519.5  491.71  4559.5  491.98  4629.6  490.63  4699.6  491.15
  4809.7  488.26  4889.8  489.10  4979.8  487.82  4987.8  486.56  4988.1  486.06
  4991.6  486.06  4991.8  486.56  4996.6  487.97  5040.0  487.70  5170.5  491.98
  5190.6  493.51  5280.9  493.82  5451.5  496.68  5576.5  499.48  5737.8  504.08
#Mann=3,-1,0
  3703.1    0.05       0  4987.8    0.05       0  4991.8    0.05       0
Bank Sta=4987.8,4991.8
Exp/Cntr=0.3,0.1

Type RM Length L Ch R = 1,11831,513,513,513
BEGIN DESCRIPTION:
Caney T13 22.0
END DESCRIPTION:
XS GIS Cut Line= 3
      2755450.97      6914536.00      2754651.00      6914436.00
      2754026.00      6914861.00
#Sta/Elev= 30
  4163.5  492.13  4249.1  490.94  4360.0  490.73  4400.3  490.06  4521.2  489.01
  4571.6  489.09  4601.9  488.63  4652.2  488.82  4742.9  487.95  4793.3  488.18
  4823.6  486.22  4914.3  486.23  4975.7  486.89  4984.6  487.55  4990.7  487.47
  4999.6  485.85  5010.0  485.36  5010.3  484.86  5013.8  484.86  5014.0  485.36
  5077.5  487.43  5098.4  488.44  5120.9  488.02  5164.2  488.58  5394.7  493.92
  5430.6  495.32  5481.5  496.56  5517.4  497.88  5661.1  501.41  5725.5  503.65
#Mann=3,-1,0
  4163.5    0.05       0  5010.0    0.04       0  5014.0    0.05       0
Bank Sta=5010,5014
Exp/Cntr=0.3,0.1

Type RM Length L Ch R = 1,11318,424,424,424
BEGIN DESCRIPTION:
Caney T13 21.0
END DESCRIPTION:
XS GIS Cut Line= 3
      2756093.50      6914232.59      2754576.44      6913955.82
      2753876.64      6914656.94
#Sta/Elev= 30
  3457.9  497.15  3536.7  496.59  3657.7  494.34  3709.5  494.51  3721.1  493.74
  3821.3  492.45  3827.6  492.93  3851.8  492.27  3880.9  493.07  4034.8  490.50
  4471.9  489.77  4756.5  487.29  4909.0  485.17  4938.8  483.72  4949.6  483.92
  4959.8  483.30  4967.9  481.84  4968.2  481.34  4971.9  481.84  4990.3  483.11
  5039.3  483.71  5060.5  484.78  5081.8  483.83  5138.3  483.73  5209.0  485.99
  5385.8  486.92  5583.8  490.08  5704.0  492.72  5852.5  497.34  5990.6  500.17
#Mann=3,-1,0
  3457.9    0.05       0  4967.9    0.04       0  4971.9    0.05       0
Bank Sta=4967.9,4971.9
Exp/Cntr=0.3,0.1

Type RM Length L Ch R = 1,10894,207,207,207
BEGIN DESCRIPTION:
Caney T13 20.0
END DESCRIPTION:
XS GIS Cut Line= 3
      2755462.42      6913034.40      2754405.60      6913591.15
      2753757.38      6914296.68
#Sta/Elev= 30
  3805.5  498.67  3890.5  495.18  4095.3  490.27  4180.5  489.91  4253.6  487.58
  4305.6  487.27  4413.6  487.33  4535.3  485.68  4578.5  485.06  4600.5  485.88
  4732.7  485.80  4784.8  484.83  4862.6  486.39  4947.4  483.62  4969.4  480.03
  4974.9  476.76  4975.2  476.26  4978.9  476.76  4985.8  481.62  5035.4  482.03
  5126.9  482.50  5169.5  483.51  5183.6  484.95  5311.3  483.13  5360.6  483.55
  5395.7  484.92  5580.1  486.05  5792.2  490.90  5898.2  495.14  5958.1  496.41
#Mann=8,-1,0
  3805.5   0.075       0  4180.5     0.1       0  4305.6   0.075       0
  4535.3    0.05       0  4862.6    0.12       0  4974.9    0.07       0
  4978.9    0.12       0  5035.4    0.05       0
Bank Sta=4974.9,4978.9
Exp/Cntr=0.3,0.1

Type RM Length L Ch R = 1,10687,171,171,171
BEGIN DESCRIPTION:
Caney T13 19.0
END DESCRIPTION:
XS GIS Cut Line= 3
      2755419.07      6912869.44      2754306.26      6913440.75
      2753743.72      6914245.29
#Sta/Elev= 30
  3749.1  498.03  4078.5  489.08  4249.0  486.88  4327.5  487.26  4387.5  486.95
  4516.9  486.79  4547.5  485.73  4606.9  483.51  4659.3  483.09  4748.1  482.45
  4798.1  484.60  5003.2  482.11  5013.9  479.56  5020.6  476.77  5020.9  476.27
  5024.6  476.77  5031.8  477.73  5049.6  481.24  5058.4  481.61  5064.5  480.84
  5079.3  480.91  5100.2  482.15  5129.9  482.63  5149.9  481.68  5511.0  484.14
  5582.5  486.27  5769.0  489.38  5841.5  491.32  5940.0  495.64  5981.7  496.41
#Mann=8,-1,0
  3749.1   0.075       0  4327.5     0.1       0  4387.5   0.075       0
  4547.5    0.05       0  5020.6    0.05       0  5024.6    0.05       0
  5031.8    0.12       0  5149.9    0.05       0
Bank Sta=5020.6,5024.6
Exp/Cntr=0.3,0.1

Type RM Length L Ch R = 1,10516,281,281,281
BEGIN DESCRIPTION:
Mapping XS 032d46b8
END DESCRIPTION:
XS GIS Cut Line= 5
      2755012.05      6912942.02      2754278.38      6913274.87
      2754211.46      6913314.37      2754160.96      6913356.44
      2753791.72      6913849.66
#Sta/Elev= 30
  4057.9  487.41  4101.6  487.81  4450.3  484.95  4794.2  482.61  4868.9  480.49
  4884.6  481.03  4890.4  480.06  4906.0  480.27  4912.8  479.01  4941.3  479.04
  4949.3  477.68  4957.1  479.06  4963.6  477.31  4971.5  478.21  5000.1  477.07
  5010.9  475.26  5011.2  474.76  5014.9  475.26  5021.3  475.48  5035.8  479.02
  5056.7  481.58  5062.9  480.02  5071.3  481.60  5077.5  480.41  5085.9  481.90
  5092.1  480.92  5106.7  482.52  5435.9  484.30  5542.2  485.55  5623.1  487.76
#Mann=5,-1,0
  4057.9    0.05       0  4101.6   0.075       0  4450.3    0.05       0
  5010.9    0.05       0  5014.9    0.05       0
Bank Sta=5010.9,5014.9
Exp/Cntr=0.3,0.1

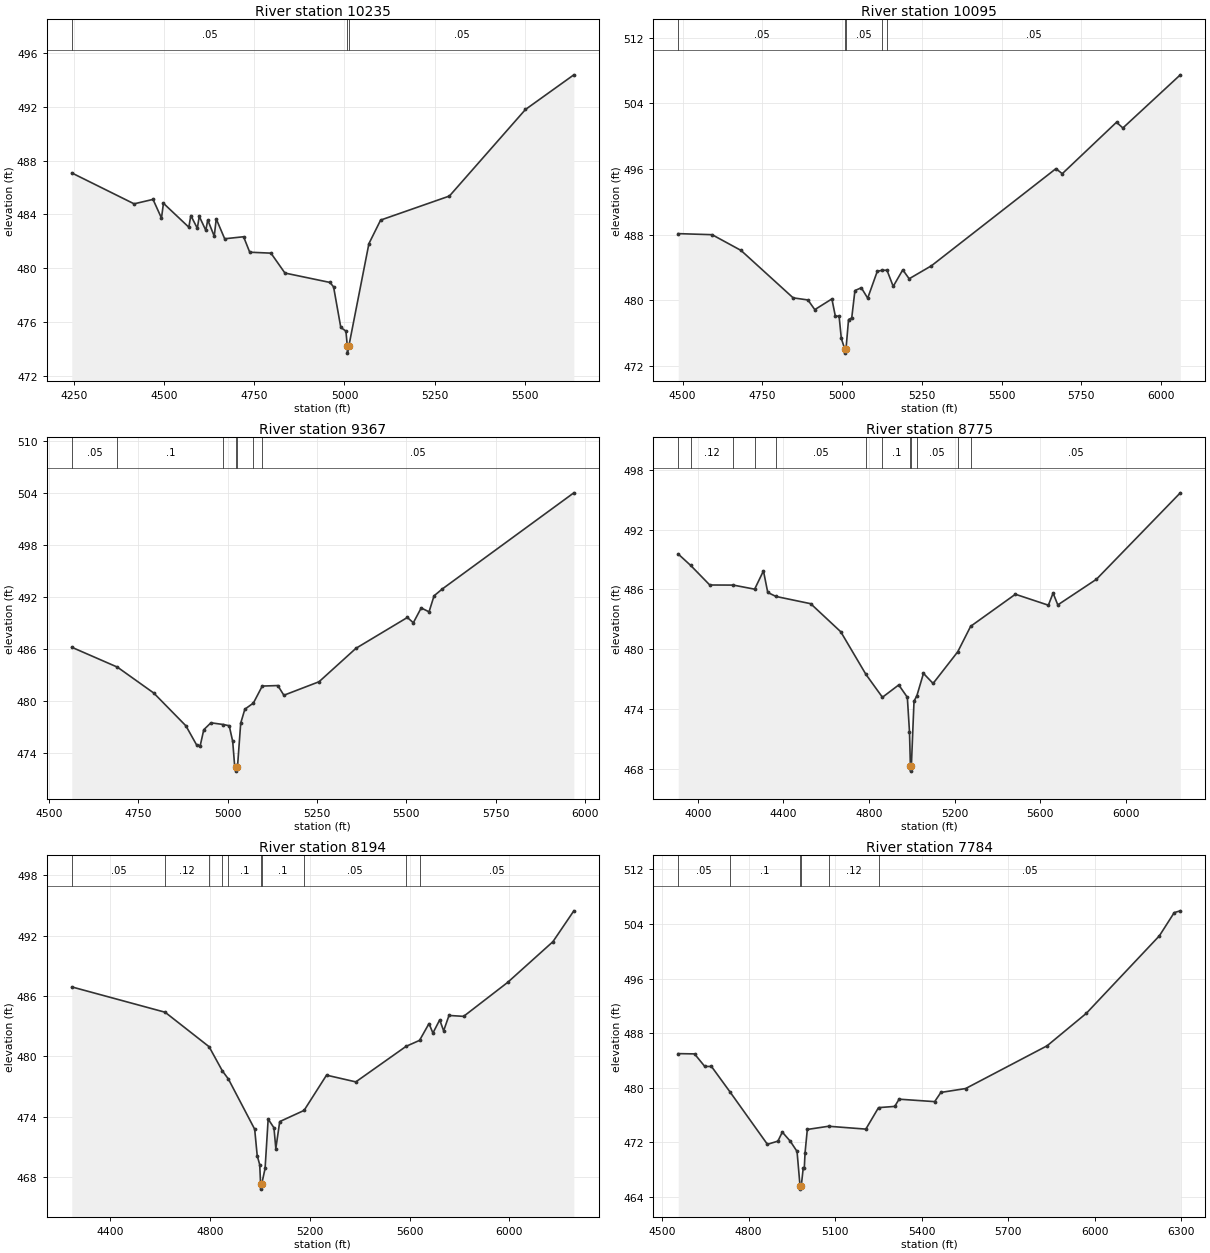
Type RM Length L Ch R = 1,10235,140,140,140
BEGIN DESCRIPTION:
Mapping XS 07848fb3
END DESCRIPTION:
XS GIS Cut Line= 5
      2754778.25      6912836.75      2754263.44      6913060.19
      2754165.44      6913096.78      2754071.89      6913101.00
      2753442.24      6913148.49
#Sta/Elev= 30
  4244.6  487.09  4417.3  484.79  4469.7  485.12  4493.1  483.73  4498.6  484.83
  4568.9  483.05  4574.4  483.92  4592.4  482.97  4597.8  483.86  4615.9  482.82
  4621.3  483.59  4639.3  482.38  4644.8  483.67  4668.2  482.19  4720.6  482.34
  4737.6  481.19  4796.4  481.12  4835.1  479.64  4959.9  478.94  4969.9  478.61
  4989.9  475.59  5004.1  475.32  5008.0  474.18  5008.2  473.68  5012.0  474.18
  5067.8  481.83  5100.2  483.58  5290.8  485.37  5501.4  491.81  5635.5  494.39
#Mann=3,-1,0
  4244.6    0.05       0  5008.0    0.05       0  5012.0    0.05       0
Bank Sta=5008,5012
Exp/Cntr=0.3,0.1

Type RM Length L Ch R = 1,10095,728,728,728
BEGIN DESCRIPTION:
Caney T13 18.0
END DESCRIPTION:
XS GIS Cut Line= 3
      2754555.01      6912774.93      2754076.08      6912960.97
      2753015.98      6912957.19
#Sta/Elev= 30
  4486.2  488.11  4592.4  487.98  4683.0  486.06  4846.4  480.27  4892.8  480.01
  4914.3  478.83  4967.9  480.14  4978.6  478.05  4990.5  478.02  4997.4  475.33
  5008.1  474.02  5008.3  473.52  5012.1  474.02  5020.1  477.62  5030.1  477.82
  5040.1  481.16  5060.1  481.50  5080.1  480.23  5110.1  483.50  5125.2  483.64
  5140.6  483.64  5160.1  481.67  5190.1  483.69  5210.1  482.60  5280.1  484.19
  5670.1  496.04  5690.1  495.43  5860.1  501.71  5880.1  501.01  6060.1  507.50
#Mann=5,-1,0
  4486.2    0.05       0  5008.1    0.05       0  5012.1    0.05       0
  5125.2     0.1       0  5140.6    0.05       0
Bank Sta=5008.1,5012.1
Exp/Cntr=0.3,0.1

Type RM Length L Ch R = 1,9367,592,592,592
BEGIN DESCRIPTION:
Caney T13 17.0
END DESCRIPTION:
XS GIS Cut Line= 3
      2754275.26      6912364.29      2753839.46      6912347.94
      2752956.96      6912748.85
#Sta/Elev= 30
  4563.9  486.22  4691.5  483.93  4793.3  480.94  4883.4  477.15  4913.4  474.94
  4923.4  474.85  4933.4  476.70  4953.4  477.50  4988.5  477.30  5004.6  477.16
  5014.4  475.35  5019.9  472.49  5023.8  472.42  5024.0  471.92  5027.8  472.42
  5036.8  477.46  5048.4  479.07  5072.3  479.78  5097.1  481.74  5140.7  481.80
  5157.6  480.68  5256.1  482.24  5359.4  486.10  5503.3  489.66  5520.0  489.05
  5542.0  490.76  5564.0  490.31  5578.0  492.16  5601.1  492.95  5969.3  504.05
#Mann=7,-1,0
  4563.9    0.05       0  4691.5     0.1       0  4988.5    0.12       0
  5023.8    0.07       0  5027.8    0.12       0  5072.3     0.1       0
  5097.1    0.05       0
Bank Sta=5023.8,5027.8
Exp/Cntr=0.3,0.1

Type RM Length L Ch R = 1,8775,581,581,581
BEGIN DESCRIPTION:
Mapping XS 709594e3
END DESCRIPTION:
XS GIS Cut Line= 3
      2755012.81      6911732.78      2753927.78      6911815.25
      2752786.26      6912340.43
#Sta/Elev= 30
  3909.0  489.55  3967.4  488.40  4056.2  486.44  4166.3  486.43  4265.8  486.02
  4307.0  487.86  4327.0  485.69  4365.3  485.29  4527.6  484.56  4668.0  481.74
  4785.8  477.45  4862.6  475.16  4938.8  476.40  4978.9  475.16  4988.9  471.71
  4993.3  468.24  4993.7  467.74  4997.7  468.24  5010.1  474.77  5023.4  475.31
  5054.2  477.56  5099.2  476.55  5214.3  479.73  5274.6  482.29  5483.5  485.51
  5637.6  484.41  5659.6  485.63  5681.6  484.44  5861.7  487.01  6253.7  495.70
#Mann=12,-1,0
  3909.0     0.1       0  3967.4    0.12       0  4166.3    0.05       0
  4265.8    0.12       0  4365.3    0.05       0  4785.8    0.12       0
  4862.6     0.1       0  4993.3    0.07       0  4997.7     0.1       0
  5023.4    0.05       0  5214.3    0.12       0  5274.6    0.05       0
Bank Sta=4993.3,4997.7
Exp/Cntr=0.3,0.1

Type RM Length L Ch R = 1,8194,410,410,410
BEGIN DESCRIPTION:
Mapping XS 1885c099
END DESCRIPTION:
XS GIS Cut Line= 3
      2754669.94      6911198.93      2753919.10      6911316.11
      2752839.70      6911949.01
#Sta/Elev= 30
  4246.6  486.91  4620.5  484.39  4796.7  480.96  4849.7  478.56  4874.1  477.74
  4979.3  472.75  4989.4  470.13  4999.5  469.21  5003.0  467.29  5003.4  466.79
  5007.4  467.29  5021.0  468.85  5033.3  473.76  5056.5  472.89  5064.0  470.83
  5079.6  473.51  5177.1  474.62  5267.1  478.13  5384.4  477.46  5586.0  481.00
  5639.7  481.59  5677.6  483.26  5693.3  482.32  5720.5  483.63  5736.2  482.54
  5757.7  484.07  5816.3  483.98  5992.2  487.35  6174.0  491.41  6257.8  494.48
#Mann=10,-1,0
  4246.6    0.05       0  4620.5    0.12       0  4796.7     0.1       0
  4849.7    0.12       0  4874.1     0.1       0  5003.0    0.07       0
  5007.4     0.1       0  5177.1    0.05       0  5586.0    0.12       0
  5639.7    0.05       0
Bank Sta=5003,5007.4
Exp/Cntr=0.3,0.1

Type RM Length L Ch R = 1,7784,806,806,806
BEGIN DESCRIPTION:
Mapping XS 9d1586c3
END DESCRIPTION:
XS GIS Cut Line= 3
      2754053.68      6910821.30      2753684.72      6911055.70
      2752592.14      6911766.74
#Sta/Elev= 30
  4556.3  484.99  4612.8  484.95  4648.3  483.11  4671.5  483.11  4735.2  479.41
  4865.5  471.69  4901.9  472.16  4917.1  473.48  4944.5  472.16  4968.2  470.65
  4978.5  465.62  4978.9  465.12  4982.9  465.62  4989.7  468.23  4993.4  468.23
  4995.9  470.41  5003.8  473.87  5077.6  474.34  5206.7  473.92  5250.7  477.07
  5306.9  477.25  5322.0  478.31  5445.3  477.95  5466.9  479.30  5552.7  479.87
  5835.2  486.14  5970.9  490.89  6224.5  502.27  6275.9  505.67  6297.0  505.93
#Mann=6,-1,0
  4556.3    0.05       0  4735.2     0.1       0  4978.5    0.07       0
  4982.9     0.1       0  5077.6    0.12       0  5250.7    0.05       0
Bank Sta=4978.5,4982.9
Exp/Cntr=0.3,0.1

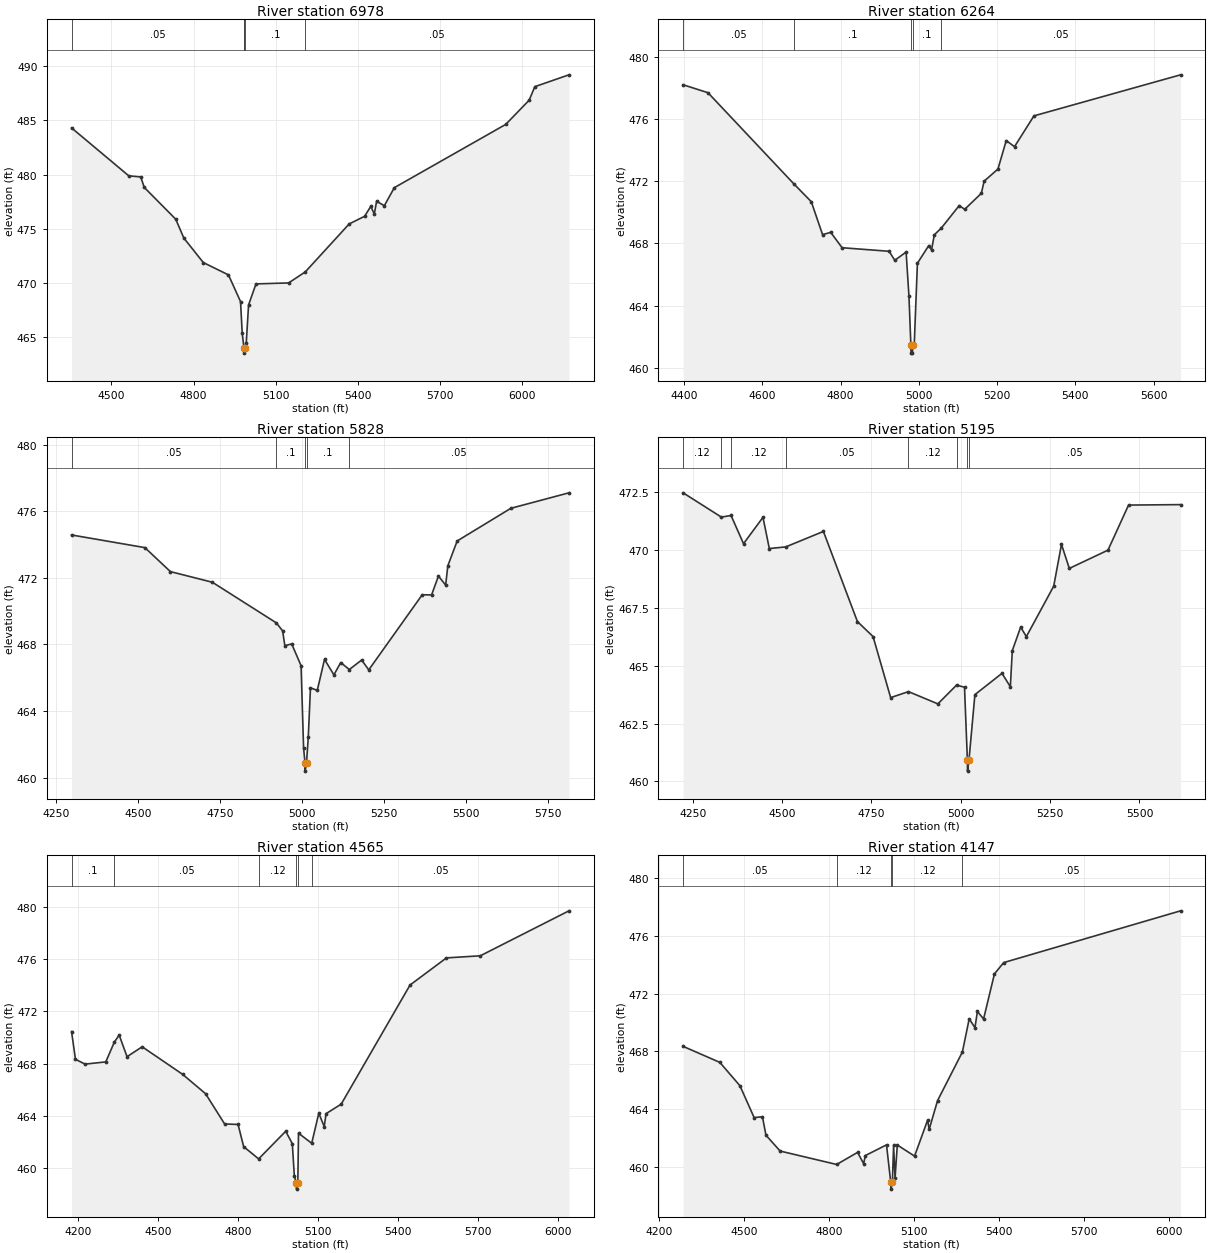
Type RM Length L Ch R = 1,6978,714,714,714
BEGIN DESCRIPTION:
Mapping XS 0a8cc8e8
END DESCRIPTION:
XS GIS Cut Line= 3
      2754161.31      6910777.94      2753592.64      6910368.41
      2752692.53      6911031.40
#Sta/Elev= 30
  4353.9  484.31  4563.2  479.89  4606.9  479.79  4619.6  478.83  4735.0  475.89
  4764.4  474.16  4835.6  471.90  4927.7  470.76  4971.8  468.30  4978.0  465.37
  4983.8  464.15  4984.3  464.05  4984.8  463.55  4988.8  464.05  4992.7  464.47
  5001.2  467.99  5028.3  469.93  5147.7  470.02  5208.7  471.04  5369.1  475.46
  5425.4  476.16  5447.9  477.07  5460.9  476.38  5469.4  477.54  5497.6  477.14
  5534.1  478.80  5941.4  484.63  6027.0  486.86  6047.9  488.11  6172.6  489.20
#Mann=5,-1,0
  4353.9    0.05       0  4983.8     0.1       0  4984.3    0.07       0
  4988.8     0.1       0  5208.7    0.05       0
Bank Sta=4984.3,4988.8
Exp/Cntr=0.3,0.1

Type RM Length L Ch R = 1,6264,436,436,436
BEGIN DESCRIPTION:
Caney T13 11.0
END DESCRIPTION:
XS GIS Cut Line= 3
      2753851.02      6910186.02      2753375.96      6909815.28
      2752901.00      6910286.00
#Sta/Elev= 30
  4397.4  478.20  4460.9  477.69  4679.9  471.84  4724.9  470.68  4753.8  468.56
  4774.6  468.71  4803.6  467.72  4923.9  467.49  4938.3  466.91  4967.3  467.44
  4974.6  464.59  4979.5  461.44  4980.0  460.94  4983.6  460.94  4984.1  461.44
  4988.1  461.49  4996.2  466.72  5025.2  467.86  5032.3  467.58  5039.4  468.55
  5057.5  468.99  5103.0  470.43  5117.1  470.19  5159.6  471.22  5166.7  472.00
  5202.0  472.78  5223.2  474.61  5244.4  474.22  5294.0  476.20  5668.7  478.84
#Mann=5,-1,0
  4397.4    0.05       0  4679.9     0.1       0  4979.5    0.07       0
  4984.1     0.1       0  5057.5    0.05       0
Bank Sta=4979.5,4984.1
Exp/Cntr=0.3,0.1

Type RM Length L Ch R = 1,5828,633,633,633
BEGIN DESCRIPTION:
Caney T13 10.0
END DESCRIPTION:
XS GIS Cut Line= 3
      2753998.14      6909864.74      2753585.27      6909405.11
      2752901.02      6909985.98
#Sta/Elev= 30
  4298.4  474.57  4521.9  473.81  4599.6  472.37  4727.5  471.73  4922.5  469.29
  4941.5  468.81  4948.3  467.92  4969.1  468.03  4997.7  466.72  5005.4  461.76
  5009.7  460.89  5010.1  460.39  5014.3  460.89  5019.7  462.45  5026.3  465.39
  5047.1  465.24  5069.1  467.10  5097.7  466.17  5118.5  466.91  5144.7  466.49
  5182.2  467.06  5203.9  466.47  5366.8  470.98  5395.3  470.97  5416.2  472.10
  5438.2  471.56  5444.8  472.72  5473.3  474.21  5636.7  476.17  5813.8  477.10
#Mann=5,-1,0
  4298.4    0.05       0  4922.5     0.1       0  5009.7    0.07       0
  5014.3     0.1       0  5144.7    0.05       0
Bank Sta=5009.7,5014.3
Exp/Cntr=0.3,0.1

Type RM Length L Ch R = 1,5195,630,630,630
BEGIN DESCRIPTION:
Caney T13 9.0
END DESCRIPTION:
XS GIS Cut Line= 4
      2753950.98      6909285.99      2753226.09      6909005.96
      2753179.07      6909017.28      2752951.00      6909535.99
#Sta/Elev= 30
  4222.9  472.48  4329.9  471.43  4357.0  471.50  4391.9  470.28  4446.4  471.42
  4464.1  470.07  4510.0  470.14  4615.5  470.81  4710.7  466.91  4754.5  466.26
  4803.7  463.62  4853.5  463.88  4935.8  463.35  4988.1  464.16  5010.4  464.07
  5018.4  460.94  5018.8  460.44  5023.0  460.94  5039.5  463.75  5115.3  464.67
  5138.7  464.09  5144.1  465.65  5167.5  466.67  5183.5  466.26  5260.0  468.44
  5281.8  470.25  5303.7  469.21  5411.9  470.00  5469.5  471.95  5615.0  471.97
#Mann=8,-1,0
  4222.9    0.12       0  4329.9     0.1       0  4357.0    0.12       0
  4510.0    0.05       0  4853.5    0.12       0  4988.1    0.05       0
  5018.4    0.04       0  5023.0    0.05       0
Bank Sta=5018.4,5023
Exp/Cntr=0.3,0.1

Type RM Length L Ch R = 1,4565,418,418,418
BEGIN DESCRIPTION:
Caney T13 8.0
END DESCRIPTION:
XS GIS Cut Line= 3
      2753901.03      6908886.02      2753226.00      6908411.00
      2752205.04      6908609.56
#Sta/Elev= 30
  4174.5  470.46  4189.3  468.33  4225.1  467.96  4302.9  468.13  4335.1  469.65
  4353.1  470.19  4382.7  468.53  4439.4  469.29  4590.9  467.18  4677.2  465.69
  4748.6  463.37  4799.1  463.33  4820.0  461.63  4876.2  460.69  4977.7  462.81
  5002.5  461.86  5010.1  459.37  5017.3  458.87  5018.3  458.37  5023.2  458.87
  5025.7  462.66  5075.2  461.89  5101.8  464.19  5122.2  463.17  5129.1  464.16
  5185.8  464.89  5444.1  474.03  5580.6  476.11  5707.5  476.27  6040.0  479.72
#Mann=6,-1,0
  4174.5     0.1       0  4335.1    0.05       0  4876.2    0.12       0
  5017.3    0.07       0  5023.2    0.12       0  5075.2    0.05       0
Bank Sta=5017.3,5023.2
Exp/Cntr=0.3,0.1

Type RM Length L Ch R = 1,4147,443,443,443
BEGIN DESCRIPTION:
Caney T13 7.0
END DESCRIPTION:
XS GIS Cut Line= 3
      2753850.99      6908635.99      2753426.00      6908061.00
      2752401.04      6908235.99
#Sta/Elev= 30
  4284.6  468.35  4414.1  467.24  4485.0  465.62  4535.1  463.41  4564.4  463.47
  4576.8  462.19  4626.9  461.09  4826.3  460.16  4900.1  461.00  4921.3  460.22
  4927.6  460.78  5002.1  461.52  5016.9  458.95  5017.9  458.45  5022.8  458.95
  5027.1  461.49  5032.2  459.22  5040.2  461.51  5101.1  460.74  5147.4  463.25
  5152.5  462.59  5182.2  464.59  5269.8  467.96  5293.8  470.26  5314.1  469.65
  5322.8  470.77  5344.5  470.25  5382.9  473.38  5415.5  474.16  6039.4  477.75
#Mann=5,-1,0
  4284.6    0.05       0  4826.3    0.12       0  5016.9    0.07       0
  5022.8    0.12       0  5269.8    0.05       0
Bank Sta=5016.9,5022.8
Exp/Cntr=0.3,0.1

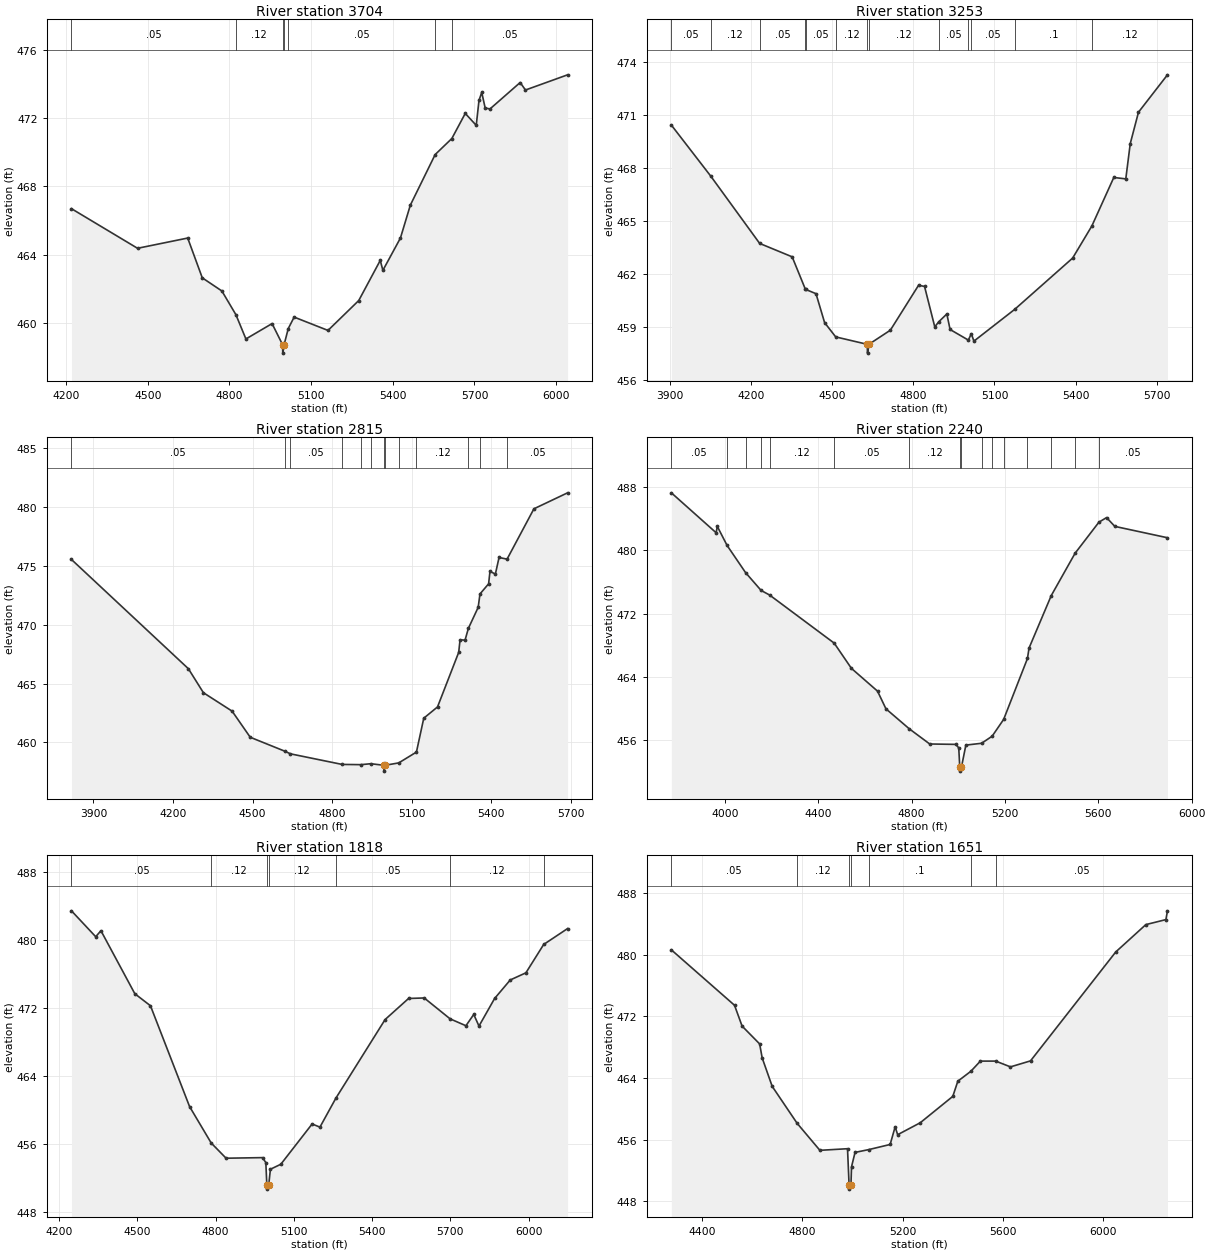
Type RM Length L Ch R = 1,3704,451,451,451
BEGIN DESCRIPTION:
Caney T13 6.0
END DESCRIPTION:
XS GIS Cut Line= 3
      2754071.48      6908533.94      2753776.00      6907811.00
      2752743.31      6907945.40
#Sta/Elev= 30
  4219.5  466.69  4462.2  464.37  4646.5  464.97  4700.0  462.64  4772.0  461.87
  4823.6  460.48  4860.3  459.06  4956.4  459.96  4994.8  458.73  4995.8  458.23
  5000.7  458.73  5015.9  459.67  5037.5  460.34  5161.8  459.56  5274.8  461.31
  5353.8  463.66  5363.5  463.08  5427.9  464.97  5464.4  466.90  5555.5  469.86
  5616.8  470.80  5666.1  472.27  5706.4  471.57  5716.5  473.03  5726.6  473.50
  5739.2  472.59  5756.8  472.53  5867.8  474.08  5887.2  473.64  6041.9  474.53
#Mann=7,-1,0
  4219.5    0.05       0  4823.6    0.12       0  4994.8    0.07       0
  5000.7    0.12       0  5015.9    0.05       0  5555.5    0.12       0
  5616.8    0.05       0
Bank Sta=4994.8,5000.7
Exp/Cntr=0.3,0.1

Type RM Length L Ch R = 1,3253,438,438,438
BEGIN DESCRIPTION:
Caney T13 5.0
END DESCRIPTION:
XS GIS Cut Line= 3
      2754796.77      6907924.14      2753826.00      6907411.00
      2753100.38      6907290.56
#Sta/Elev= 30
  3905.7  470.45  4051.1  467.56  4232.1  463.74  4352.2  462.98  4400.8  461.15
  4402.5  461.13  4440.3  460.89  4472.1  459.25  4513.1  458.44  4629.6  458.02
  4630.7  457.52  4635.8  458.02  4715.1  458.82  4819.5  461.37  4841.5  461.30
  4879.3  459.01  4894.2  459.30  4923.9  459.74  4935.9  458.86  5003.3  458.26
  5014.4  458.62  5024.0  458.20  5174.6  460.00  5388.9  462.91  5459.9  464.73
  5541.0  467.48  5585.3  467.40  5601.8  469.40  5632.2  471.18  5739.3  473.30
#Mann=13,-1,0
  3905.7    0.05       0  4051.1    0.12       0  4232.1    0.05       0
  4400.8    0.12       0  4402.5    0.05       0  4513.1    0.12       0
  4629.6    0.05       0  4635.8    0.12       0  4894.2    0.05       0
  5003.3    0.12       0  5014.4    0.05       0  5174.6     0.1       0
  5459.9    0.12       0
Bank Sta=4629.6,4635.8
Exp/Cntr=0.3,0.1

Type RM Length L Ch R = 1,2815,575,575,575
BEGIN DESCRIPTION:
Caney T13 4.0
END DESCRIPTION:
XS GIS Cut Line= 3
      2755095.54      6907566.20      2754026.00      6907061.00
      2753363.78      6906876.10
#Sta/Elev= 30
  3817.1  475.55  4257.9  466.26  4314.5  464.22  4422.8  462.65  4491.1  460.43
  4620.9  459.25  4642.8  459.02  4837.5  458.12  4908.4  458.10  4945.8  458.18
  4994.1  458.05  4995.1  457.55  5000.3  458.05  5051.0  458.25  5117.7  459.17
  5145.3  462.05  5197.2  463.01  5277.0  467.65  5282.2  468.72  5301.0  468.69
  5313.5  469.69  5350.5  471.48  5357.3  472.62  5389.8  473.48  5395.0  474.54
  5415.3  474.31  5429.2  475.72  5459.4  475.58  5560.6  479.86  5687.5  481.22
#Mann=13,-1,0
  3817.1    0.05       0  4620.9    0.12       0  4642.8    0.05       0
  4837.5    0.12       0  4908.4     0.1       0  4945.8    0.12       0
  4994.1    0.07       0  5000.3    0.12       0  5051.0     0.1       0
  5117.7    0.12       0  5313.5     0.1       0  5357.3    0.12       0
  5459.4    0.05       0
Bank Sta=4994.1,5000.3
Exp/Cntr=0.3,0.1

Type RM Length L Ch R = 1,2240,422,422,422
BEGIN DESCRIPTION:
Mapping XS 58a541fa
END DESCRIPTION:
XS GIS Cut Line= 3
      2755484.71      6906801.38      2754273.76      6906580.02
      2753401.37      6906775.34
#Sta/Elev= 30
  3771.3  487.21  3963.1  482.18  3968.1  482.98  4010.0  480.58  4089.1  477.16
  4155.7  474.91  4192.2  474.33  4468.8  468.27  4542.6  465.09  4654.4  462.22
  4690.5  459.99  4790.5  457.47  4878.0  455.56  4989.9  455.51  5002.3  455.07
  5006.7  452.64  5007.8  452.14  5013.9  452.64  5032.8  455.42  5100.2  455.65
  5145.3  456.54  5194.7  458.66  5296.7  466.34  5303.3  467.64  5398.7  474.27
  5500.7  479.60  5602.7  483.51  5635.4  484.09  5670.9  482.98  5896.3  481.55
#Mann=16,-1,0
  3771.3    0.05       0  4010.0     0.1       0  4089.1    0.12       0
  4155.7     0.1       0  4192.2    0.12       0  4468.8    0.05       0
  4790.5    0.12       0  5006.7    0.07       0  5013.9    0.12       0
  5100.2    0.05       0  5145.3    0.12       0  5194.7    0.05       0
  5296.7    0.12       0  5398.7     0.1       0  5500.7    0.12       0
  5602.7    0.05       0
Bank Sta=5006.7,5013.9
Exp/Cntr=0.3,0.1

Type RM Length L Ch R = 1,1818,167,167,167
BEGIN DESCRIPTION:
Mapping XS 47298289
END DESCRIPTION:
XS GIS Cut Line= 3
      2755028.99      6906161.80      2754285.92      6906158.32
      2753126.20      6906158.32
#Sta/Elev= 30
  4247.0  483.44  4340.0  480.39  4360.0  481.10  4490.0  473.68  4550.0  472.26
  4700.0  460.39  4783.0  456.10  4840.0  454.31  4980.0  454.38  4992.5  453.79
  4996.3  451.17  4997.5  450.67  5003.6  451.17  5010.0  453.01  5050.0  453.60
  5170.0  458.34  5200.0  457.97  5261.3  461.39  5450.0  470.64  5540.0  473.12
  5600.0  473.18  5699.3  470.72  5760.0  469.91  5790.0  471.24  5810.0  469.87
  5870.0  473.12  5930.0  475.30  5990.0  476.14  6058.2  479.48  6149.8  481.35
#Mann=7,-1,0
  4247.0    0.05       0  4783.0    0.12       0  4996.3    0.07       0
  5003.6    0.12       0  5261.3    0.05       0  5699.3    0.12       0
  6058.2    0.05       0
Bank Sta=4996.3,5003.6
Exp/Cntr=0.3,0.1

Type RM Length L Ch R = 1,1651,454,454,454
BEGIN DESCRIPTION:
Mapping XS 847dac6e
END DESCRIPTION:
XS GIS Cut Line= 3
      2754997.68      6906029.85      2754278.97      6905991.66
      2753019.80      6905995.13
#Sta/Elev= 30
  4277.3  480.64  4529.3  473.44  4559.4  470.74  4629.5  468.42  4639.5  466.61
  4679.5  462.91  4779.0  458.11  4869.8  454.60  4980.0  454.81  4986.3  450.06
  4987.5  449.56  4993.6  450.06  4996.0  452.47  5010.0  454.33  5065.4  454.70
  5150.0  455.36  5170.0  457.66  5180.0  456.63  5270.0  458.18  5400.0  461.61
  5420.0  463.58  5472.1  464.87  5510.0  466.19  5571.1  466.19  5630.0  465.44
  5710.0  466.22  6050.0  480.37  6170.0  483.92  6250.0  484.57  6256.2  485.71
#Mann=7,-1,0
  4277.3    0.05       0  4779.0    0.12       0  4986.3    0.07       0
  4993.6    0.12       0  5065.4     0.1       0  5472.1    0.12       0
  5571.1    0.05       0
Bank Sta=4986.3,4993.6
Exp/Cntr=0.3,0.1

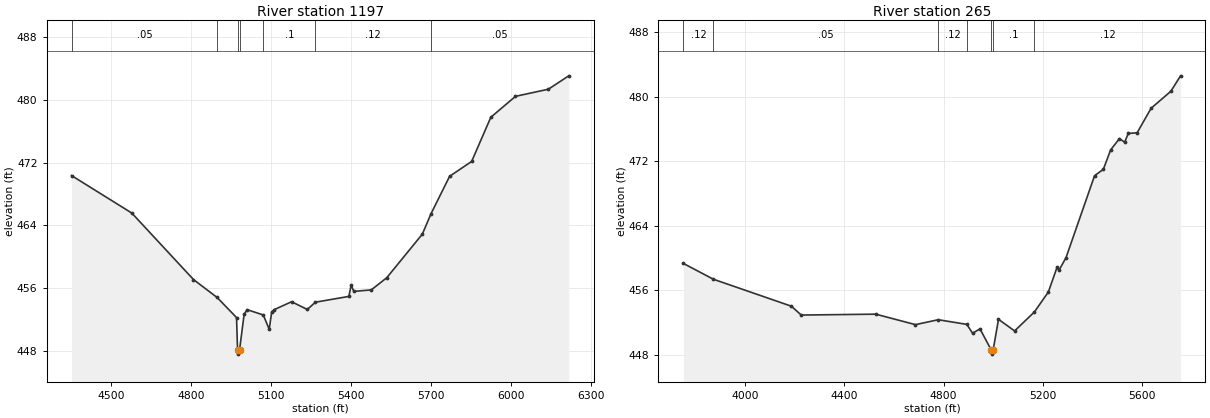
Type RM Length L Ch R = 1,1197,932,932,932
BEGIN DESCRIPTION:
Mapping XS ad65fc6e
END DESCRIPTION:
XS GIS Cut Line= 3
      2754890.04      6905765.95      2754292.86      6905561.10
      2753091.48      6905849.29
#Sta/Elev= 30
  4351.5  470.34  4577.8  465.55  4809.4  457.06  4898.2  454.77  4971.0  452.21
  4974.9  448.04  4976.0  447.54  4982.2  448.04  4999.4  452.60  5010.5  453.22
  5071.4  452.54  5093.7  450.71  5103.0  452.92  5113.3  453.23  5177.7  454.23
  5236.7  453.24  5267.1  454.17  5392.9  454.91  5401.2  456.34  5411.5  455.55
  5476.9  455.74  5534.9  457.29  5668.6  462.86  5701.1  465.46  5770.9  470.24
  5853.7  472.14  5925.7  477.78  6018.3  480.45  6141.7  481.36  6218.3  483.07
#Mann=7,-1,0
  4351.5    0.05       0  4898.2    0.12       0  4974.9    0.07       0
  4982.2    0.12       0  5071.4     0.1       0  5267.1    0.12       0
  5701.1    0.05       0
Bank Sta=4974.9,4982.2
Exp/Cntr=0.3,0.1

Type RM Length L Ch R = 1,265,0,0,0
BEGIN DESCRIPTION:
Caney T13 1.0
END DESCRIPTION:
XS GIS Cut Line= 3
      2754750.99      6905186.00      2753502.59      6905187.74
      2753057.18      6905796.62
#Sta/Elev= 30
  3751.6  459.34  3873.1  457.37  4186.6  454.03  4226.6  452.93  4526.6  453.04
  4686.6  451.74  4778.6  452.35  4893.7  451.77  4916.6  450.68  4946.6  451.21
  4992.0  448.58  4993.2  448.08  4999.5  448.58  5021.1  452.40  5086.0  450.96
  5165.6  453.31  5221.9  455.79  5257.4  458.90  5264.2  458.46  5292.9  460.04
  5408.0  470.22  5443.5  471.02  5472.8  473.43  5508.3  474.83  5529.2  474.38
  5543.8  475.47  5579.4  475.55  5635.9  478.60  5715.3  480.70  5754.4  482.62
#Mann=7,-1,0
  3751.6    0.12       0  3873.1    0.05       0  4778.6    0.12       0
  4893.7     0.1       0  4992.0    0.07       0  4999.5     0.1       0
  5165.6    0.12       0
Bank Sta=4992,4999.5
Exp/Cntr=0.3,0.1

Chan Stop Cuts=-1