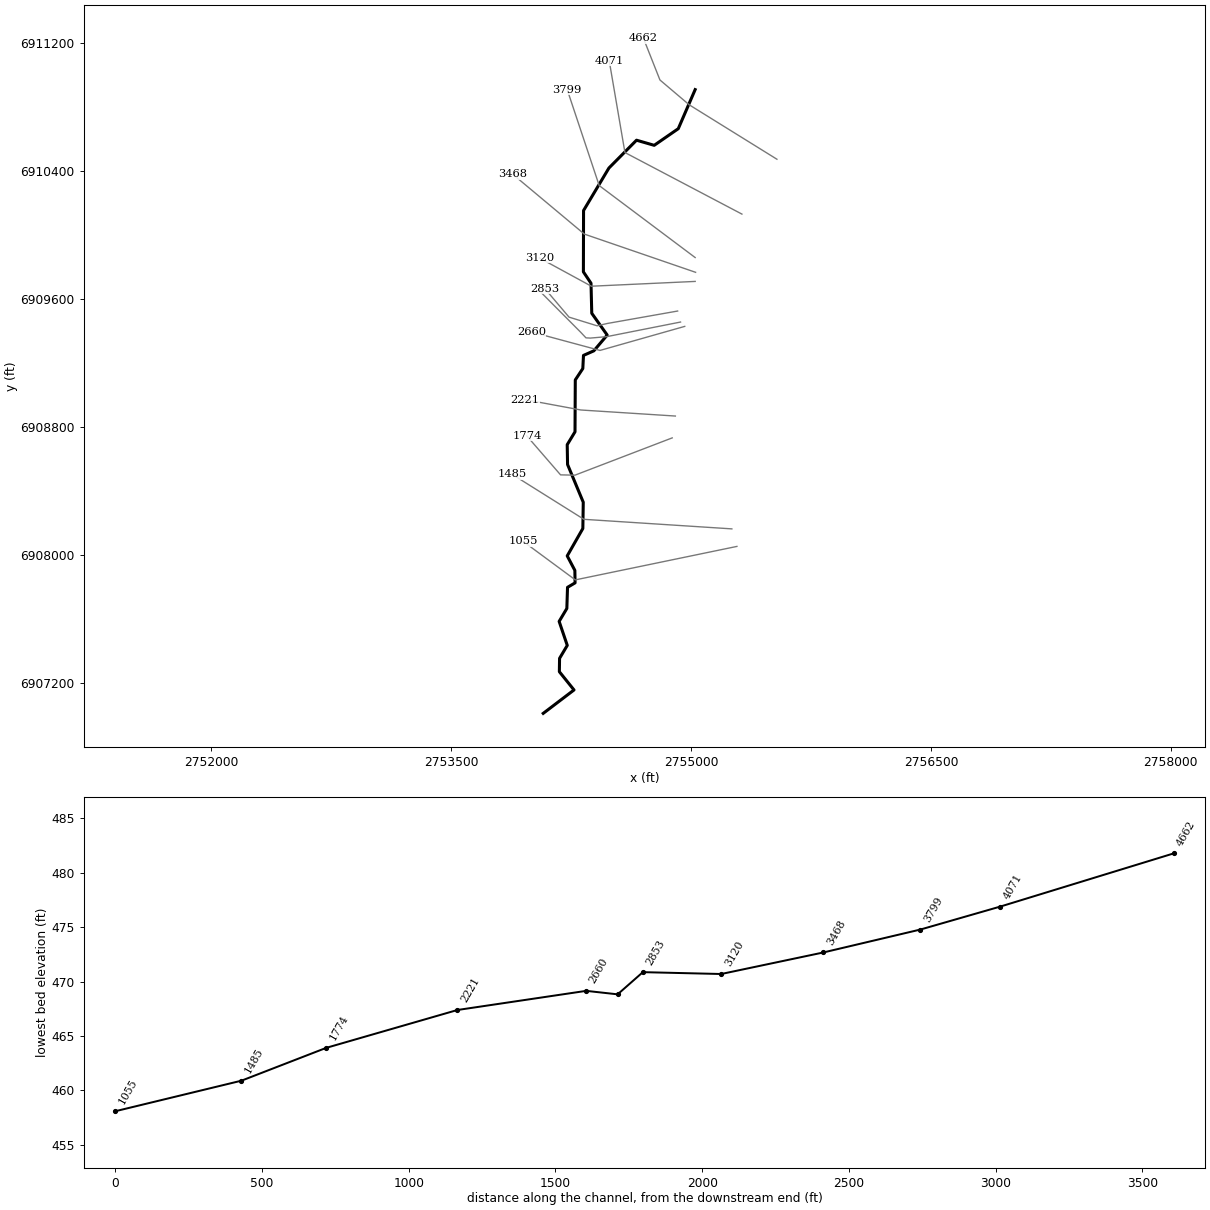
--- Caney T13_1.prj (project) ---

Proj Title=Caney T13_1 Base Level Engineering
Current Plan=p01
Default Exp/Contr=0.3,0.1
English Units
Geom File=g01
Flow File=f01
Plan File=p01
BEGIN DESCRIPTION:
Caney T13_1
END DESCRIPTION:

--- Caney T13_1.p01 (plan) ---

Plan Title=Multiple Run
Short Identifier=Multiple
Geom File=g01
Flow File=f01
Subcritical Flow
K Sum by GR= 0
Std Step Tol= 0.01
Critical Tol= 0.01
Num of Std Step Trials= 20
Max Error Tol= 0.3
Flow Tol Ratio= 0.001
Split Flow NTrial= 30
Split Flow Tol= 0.02
Split Flow Ratio= 0.02
Log Output Level= 0
Friction Slope Method= 1
Unsteady Friction Slope Method= 2
Unsteady Bridges Friction Slope Method= 1
Parabolic Critical Depth
Global Vel Dist=  1 , 1 , 1
Global Log Level= 0
CheckData=True
Encroach Param= -1, 0, 0, 0
BEGIN DESCRIPTION:
Multiple Run
END DESCRIPTION:

--- Caney T13_1.f01 (steady flow) ---

Flow Title=Multiple
Number of Profiles=7
Profile Names=10-year,25-year,50-year,1pct_min,100-year,1pct_plu,500-year
River Rch & RM= Caney T13_1,Reach-1,4662
     249     316     368     213     426     850     570
Boundary for River Rch & Prof#=Caney T13_1,Reach-1,1
Up Type=0
Dn Type=3
Dn Slope=0.005
Boundary for River Rch & Prof#=Caney T13_1,Reach-1,2
Up Type=0
Dn Type=3
Dn Slope=0.005
Boundary for River Rch & Prof#=Caney T13_1,Reach-1,3
Up Type=0
Dn Type=3
Dn Slope=0.005
Boundary for River Rch & Prof#=Caney T13_1,Reach-1,4
Up Type=0
Dn Type=3
Dn Slope=0.005
Boundary for River Rch & Prof#=Caney T13_1,Reach-1,5
Up Type=0
Dn Type=3
Dn Slope=0.005
Boundary for River Rch & Prof#=Caney T13_1,Reach-1,6
Up Type=0
Dn Type=3
Dn Slope=0.005
Boundary for River Rch & Prof#=Caney T13_1,Reach-1,7
Up Type=0
Dn Type=3
Dn Slope=0.005

--- Caney T13_1.g01 (geometry) ---

Geom Title=Existing Conditions

River Reach=Caney T13_1,Reach-1
Reach XY= 30
      2755026.00      6910911.00      2754920.41      6910666.61
      2754769.95      6910562.67      2754659.30      6910594.70
      2754486.78      6910420.68      2754328.24      6910155.07
      2754327.22      6909771.50      2754374.78      6909700.49
      2754379.55      6909512.47      2754476.11      6909376.36
      2754392.49      6909277.73      2754327.74      6909249.13
      2754323.60      6909167.06      2754276.52      6909095.79
      2754274.78      6908771.50      2754226.05      6908690.96
      2754228.25      6908566.94      2754326.36      6908331.15
      2754323.76      6908166.93      2754226.08      6907995.61
      2754273.84      6907904.95      2754275.18      6907827.01
      2754227.99      6907799.03      2754223.72      6907666.95
      2754175.60      6907586.00      2754226.40      6907436.00
      2754178.19      6907355.03      2754176.95      6907271.48
      2754268.51      6907157.42      2754076.00      6907011.00

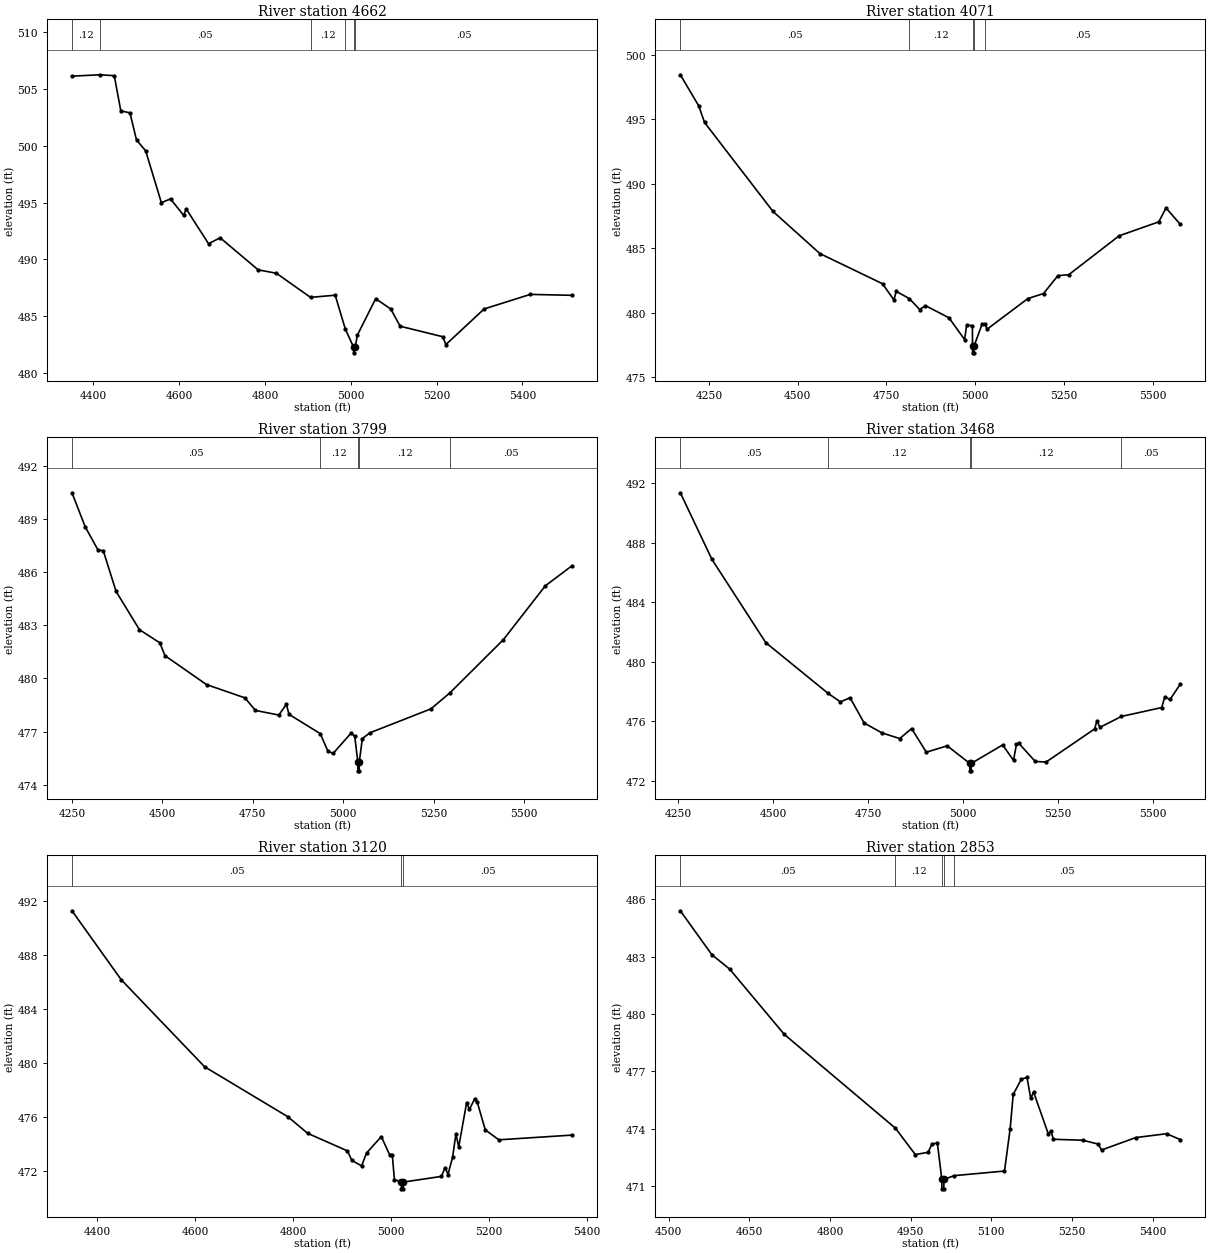
Type RM Length L Ch R = 1,4662,591,591,591
BEGIN DESCRIPTION:
Caney T13_1 3.0
END DESCRIPTION:
XS GIS Cut Line= 4
      2755537.22      6910475.68      2754988.98      6910815.85
      2754805.77      6910971.26      2754702.77      6911231.58
#Sta/Elev= 30
  4350.3  506.12  4416.0  506.24  4448.8  506.16  4464.1  503.07  4485.4  502.89
  4500.7  500.50  4522.0  499.55  4558.6  494.99  4579.9  495.32  4610.6  493.87
  4616.5  494.44  4668.5  491.38  4695.6  491.90  4784.2  489.08  4826.7  488.78
  4906.2  486.66  4963.7  486.85  4987.2  483.88  5006.6  482.28  5006.8  481.78
  5010.6  482.28  5015.1  483.32  5058.0  486.54  5093.1  485.64  5115.1  484.12
  5214.0  483.20  5221.7  482.51  5310.7  485.64  5418.3  486.92  5515.7  486.84
#Mann=6,-1,0
  4350.3    0.12       0  4416.0    0.05       0  4906.2    0.12       0
  4987.2    0.05       0  5006.6    0.04       0  5010.6    0.05       0
Bank Sta=5006.6,5010.6
Exp/Cntr=0.3,0.1

Type RM Length L Ch R = 1,4071,272,272,272
BEGIN DESCRIPTION:
Mapping XS bdad7bb1
END DESCRIPTION:
XS GIS Cut Line= 3
      2755318.37      6910132.64      2754586.98      6910517.52
      2754488.75      6911090.99
#Sta/Elev= 30
  4169.6  498.46  4221.4  496.05  4237.8  494.76  4430.5  487.86  4562.7  484.59
  4739.0  482.25  4771.2  480.99  4777.5  481.66  4814.5  481.10  4843.6  480.25
  4860.0  480.55  4926.1  479.61  4970.1  477.92  4975.8  479.02  4992.2  479.01
  4992.4  477.39  4992.7  476.89  4996.2  476.89  4996.4  477.39  5019.9  479.15
  5027.5  479.14  5033.3  478.72  5148.3  481.10  5192.4  481.49  5233.0  482.88
  5263.4  482.95  5405.4  485.97  5517.0  487.05  5537.3  488.13  5577.9  486.85
#Mann=5,-1,0
  4169.6    0.05       0  4814.5    0.12       0  4992.4    0.07       0
  4996.4    0.12       0  5027.5    0.05       0
Bank Sta=4992.4,4996.4
Exp/Cntr=0.3,0.1

Type RM Length L Ch R = 1,3799,331,331,331
BEGIN DESCRIPTION:
Caney T13_1 2.0
END DESCRIPTION:
XS GIS Cut Line= 3
      2755026.00      6909861.00      2754426.00      6910311.00
      2754225.99      6910911.04
#Sta/Elev= 30
  4250.0  490.48  4286.5  488.56  4321.9  487.25  4336.5  487.21  4371.9  484.91
  4436.5  482.75  4492.7  482.01  4507.3  481.28  4621.9  479.65  4728.1  478.90
  4757.3  478.19  4821.9  477.93  4842.7  478.54  4850.0  477.97  4936.4  476.88
  4957.3  475.90  4971.9  475.76  5021.1  476.90  5031.6  476.74  5040.2  475.28
  5040.4  474.78  5043.9  474.78  5044.2  475.28  5052.7  476.60  5073.8  476.93
  5242.4  478.28  5295.2  479.19  5442.7  482.19  5558.7  485.23  5632.5  486.36
#Mann=5,-1,0
  4250.0    0.05       0  4936.4    0.12       0  5040.2    0.07       0
  5044.2    0.12       0  5295.2    0.05       0
Bank Sta=5040.2,5044.2
Exp/Cntr=0.3,0.1

Type RM Length L Ch R = 1,3468,348,348,348
BEGIN DESCRIPTION:
Mapping XS 1521b2ac
END DESCRIPTION:
XS GIS Cut Line= 3
      2755028.81      6909768.67      2754333.09      6910007.64
      2753886.84      6910380.60
#Sta/Elev= 30
  4255.1  491.34  4338.3  486.87  4480.1  481.28  4644.4  477.87  4676.8  477.30
  4702.2  477.58  4739.3  475.88  4786.7  475.21  4833.0  474.84  4864.3  475.51
  4903.1  473.92  4958.0  474.35  5017.4  473.17  5017.7  472.67  5021.2  472.67
  5021.4  473.17  5104.2  474.41  5132.7  473.37  5140.4  474.46  5147.0  474.51
  5189.9  473.30  5218.5  473.26  5346.1  475.48  5352.6  476.02  5360.4  475.59
  5416.6  476.32  5523.1  476.92  5530.9  477.61  5545.2  477.47  5572.3  478.50
#Mann=5,-1,0
  4255.1    0.05       0  4644.4    0.12       0  5017.4    0.07       0
  5021.4    0.12       0  5416.6    0.05       0
Bank Sta=5017.4,5021.4
Exp/Cntr=0.3,0.1

Type RM Length L Ch R = 1,3120,267,267,267
BEGIN DESCRIPTION:
Mapping XS 524c8d2c
END DESCRIPTION:
XS GIS Cut Line= 3
      2755026.18      6909711.75      2754377.11      6909681.75
      2754051.88      6909858.68
#Sta/Elev= 30
  4349.3  491.28  4449.6  486.18  4619.8  479.73  4790.0  476.02  4830.0  474.80
  4911.1  473.50  4920.1  472.79  4940.1  472.39  4950.1  473.34  4980.2  474.56
  4997.1  473.22  5002.5  473.22  5007.0  471.38  5021.1  471.19  5021.3  470.69
  5024.8  470.69  5025.1  471.19  5102.8  471.61  5110.5  472.27  5116.2  471.75
  5125.6  473.03  5132.4  474.76  5138.1  473.79  5154.2  477.07  5159.9  476.57
  5170.4  477.34  5176.1  477.09  5192.2  475.06  5219.8  474.32  5369.3  474.67
#Mann=3,-1,0
  4349.3    0.05       0  5021.1    0.04       0  5025.1    0.05       0
Bank Sta=5021.1,5025.1
Exp/Cntr=0.3,0.1

Type RM Length L Ch R = 1,2853,86,86,86
BEGIN DESCRIPTION:
Mapping XS 5b72a8fd
END DESCRIPTION:
XS GIS Cut Line= 5
      2754916.41      6909526.59      2754476.65      6909448.79
      2754412.87      6909434.25      2754237.46      6909488.44
      2754085.84      6909667.34
#Sta/Elev= 30
  4521.8  485.39  4580.3  483.10  4613.6  482.34  4715.2  478.93  4921.8  474.03
  4958.9  472.65  4982.7  472.77  4989.6  473.19  4999.8  473.27  5008.1  471.36
  5008.3  470.86  5011.8  470.86  5012.1  471.36  5031.4  471.55  5124.7  471.79
  5135.2  473.99  5140.9  475.79  5156.1  476.59  5166.6  476.68  5173.5  475.59
  5178.8  475.92  5206.2  473.73  5211.4  473.89  5215.5  473.45  5270.2  473.40
  5298.8  473.20  5305.3  472.89  5369.0  473.54  5426.2  473.74  5451.9  473.43
#Mann=5,-1,0
  4521.8    0.05       0  4921.8    0.12       0  5008.1    0.07       0
  5012.1    0.12       0  5031.4    0.05       0
Bank Sta=5008.1,5012.1
Exp/Cntr=0.3,0.1

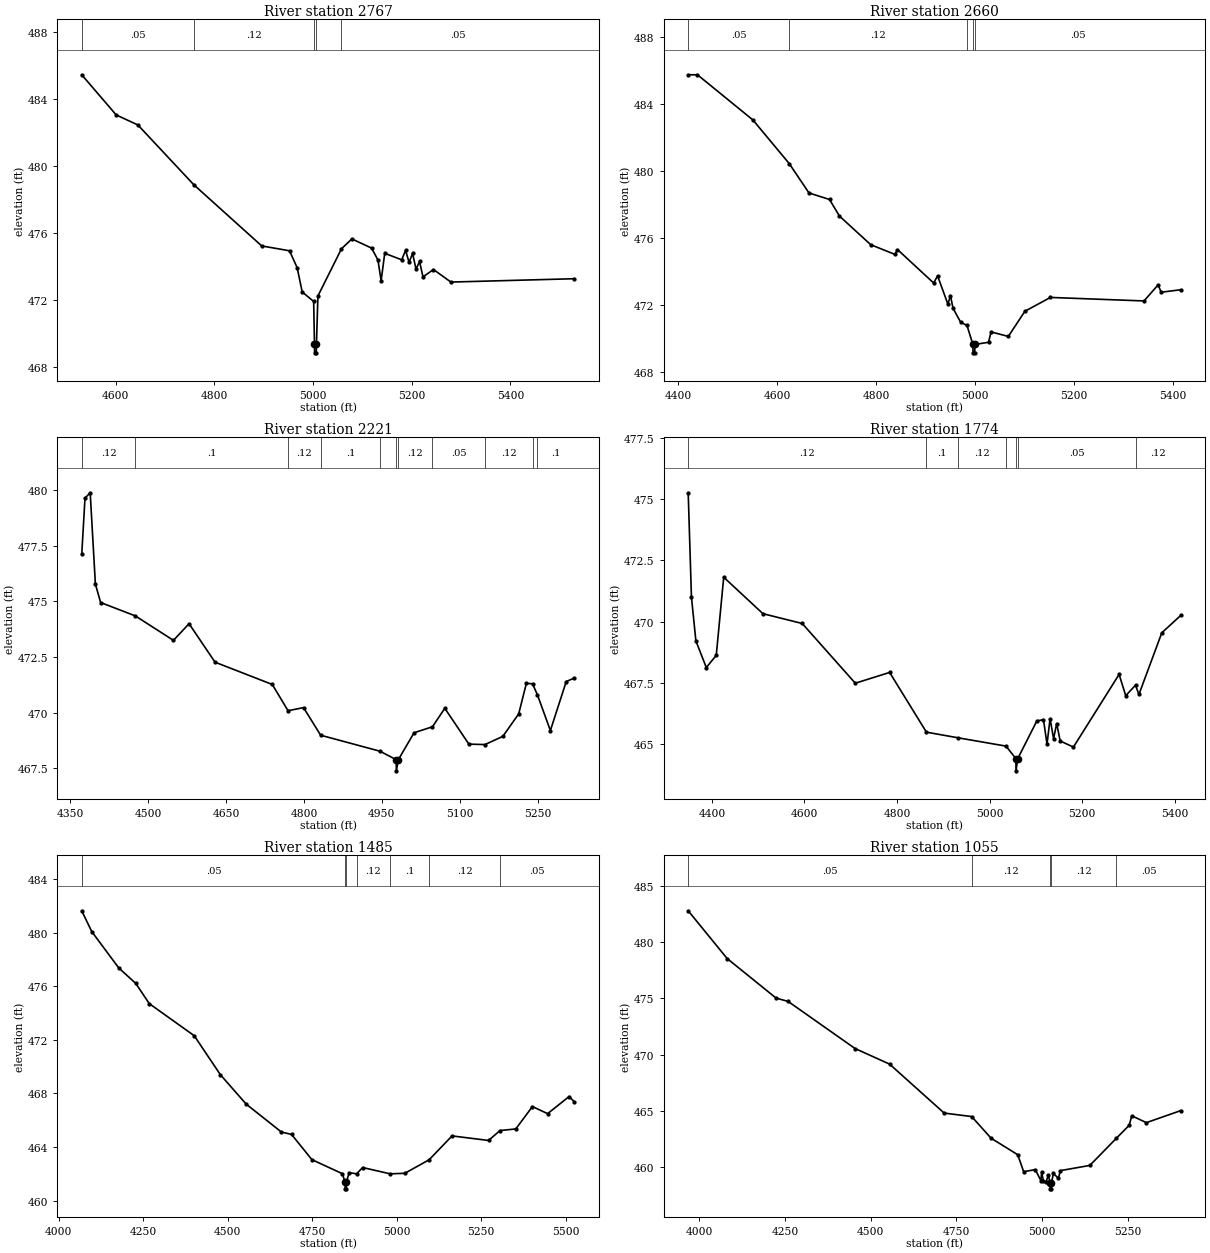
Type RM Length L Ch R = 1,2767,107,107,107
BEGIN DESCRIPTION:
Mapping XS f503a5eb
END DESCRIPTION:
XS GIS Cut Line= 6
      2754934.57      6909457.76      2754473.15      6909366.45
      2754370.75      6909357.46      2754343.23      6909358.96
      2754309.37      6909394.94      2754063.30      6909642.24
#Sta/Elev= 30
  4530.8  485.44  4600.7  483.04  4644.7  482.44  4758.0  478.87  4895.8  475.21
  4952.2  474.92  4967.7  473.91  4977.9  472.46  5001.2  471.89  5002.8  469.32
  5003.0  468.82  5006.5  468.82  5006.8  469.32  5009.8  472.22  5057.6  475.04
  5078.6  475.63  5118.7  475.08  5131.5  474.37  5138.0  473.13  5145.3  474.77
  5179.7  474.38  5187.6  474.94  5194.7  474.23  5201.8  474.76  5208.8  473.82
  5215.9  474.28  5222.9  473.36  5244.2  473.80  5279.5  473.05  5529.8  473.25
#Mann=5,-1,0
  4530.8    0.05       0  4758.0    0.12       0  5002.8    0.07       0
  5006.8    0.12       0  5057.6    0.05       0
Bank Sta=5002.8,5006.8
Exp/Cntr=0.3,0.1

Type RM Length L Ch R = 1,2660,439,439,439
BEGIN DESCRIPTION:
Mapping XS bc54d704
END DESCRIPTION:
XS GIS Cut Line= 4
      2754960.81      6909430.58      2754430.99      6909280.29
      2754221.04      6909336.79      2754001.74      6909396.05
#Sta/Elev= 30
  4420.5  485.75  4439.2  485.75  4551.3  483.05  4624.5  480.45  4664.6  478.69
  4706.1  478.30  4726.1  477.31  4789.3  475.60  4838.2  475.02  4843.4  475.31
  4916.5  473.31  4924.4  473.74  4945.2  472.05  4950.4  472.56  4955.6  471.80
  4971.2  470.96  4983.8  470.78  4995.7  469.64  4996.0  469.14  4999.5  469.14
  4999.7  469.64  5027.3  469.77  5032.5  470.39  5067.3  470.12  5100.7  471.62
  5152.4  472.45  5341.5  472.24  5370.0  473.20  5376.2  472.76  5415.8  472.91
#Mann=5,-1,0
  4420.5    0.05       0  4624.5    0.12       0  4983.8    0.05       0
  4995.7    0.04       0  4999.7    0.05       0
Bank Sta=4995.7,4999.7
Exp/Cntr=0.3,0.1

Type RM Length L Ch R = 1,2221,447,447,447
BEGIN DESCRIPTION:
Mapping XS b97055d4
END DESCRIPTION:
XS GIS Cut Line= 3
      2754902.29      6908870.02      2754311.68      6908907.80
      2753960.70      6908972.95
#Sta/Elev= 30
  4371.9  477.10  4378.2  479.63  4388.2  479.87  4398.2  475.77  4408.3  474.94
  4475.1  474.34  4548.6  473.24  4578.6  473.99  4628.7  472.26  4738.9  471.26
  4769.3  470.08  4799.1  470.22  4832.1  468.98  4946.6  468.26  4977.7  467.88
  4977.9  467.38  4981.7  467.88  5012.0  469.09  5047.5  469.36  5071.2  470.19
  5117.6  468.58  5148.6  468.56  5183.1  468.93  5213.6  469.94  5228.3  471.31
  5240.2  471.29  5249.7  470.79  5274.6  469.19  5305.1  471.39  5320.7  471.55
#Mann=11,-1,0
  4371.9    0.12       0  4475.1     0.1       0  4769.3    0.12       0
  4832.1     0.1       0  4946.6    0.12       0  4977.7    0.07       0
  4981.7    0.12       0  5047.5    0.05       0  5148.6    0.12       0
  5240.2    0.05       0  5249.7     0.1       0
Bank Sta=4977.7,4981.7
Exp/Cntr=0.3,0.1

Type RM Length L Ch R = 1,1774,289,289,289
BEGIN DESCRIPTION:
Mapping XS 59e3818d
END DESCRIPTION:
XS GIS Cut Line= 4
      2754882.54      6908733.45      2754274.67      6908500.45
      2754184.45      6908502.19      2753973.27      6908746.02
#Sta/Elev= 30
  4349.0  475.26  4356.0  471.00  4365.6  469.21  4388.1  468.12  4409.6  468.62
  4425.7  471.81  4510.4  470.32  4595.2  469.92  4709.9  467.48  4784.0  467.92
  4863.5  465.48  4931.8  465.25  5035.3  464.91  5056.7  464.40  5056.9  463.90
  5060.7  464.40  5102.0  465.94  5116.3  465.99  5123.9  464.99  5130.5  466.03
  5138.1  465.22  5144.8  465.83  5152.4  465.12  5180.9  464.87  5279.6  467.84
  5293.9  466.97  5315.0  467.40  5322.4  467.02  5371.8  469.54  5412.8  470.25
#Mann=7,-1,0
  4349.0    0.12       0  4863.5     0.1       0  4931.8    0.12       0
  5035.3    0.05       0  5056.7    0.07       0  5060.7    0.05       0
  5315.0    0.12       0
Bank Sta=5056.7,5060.7
Exp/Cntr=0.3,0.1

Type RM Length L Ch R = 1,1485,430,430,430
BEGIN DESCRIPTION:
Mapping XS 6ffc6a6c
END DESCRIPTION:
XS GIS Cut Line= 3
      2755255.52      6908164.55      2754330.48      6908224.32
      2753881.03      6908506.02
#Sta/Elev= 30
  4068.1  481.63  4097.7  480.08  4177.8  477.36  4228.0  476.21  4268.0  474.70
  4400.8  472.31  4478.5  469.39  4554.8  467.20  4658.8  465.12  4688.9  464.94
  4749.0  463.06  4839.2  462.01  4847.2  461.38  4847.5  460.88  4851.0  460.88
  4851.2  461.38  4859.3  462.09  4881.2  462.00  4899.3  462.47  4980.5  462.00
  5024.0  462.04  5096.0  463.05  5163.7  464.83  5271.8  464.49  5305.6  465.23
  5352.3  465.35  5401.6  467.02  5446.5  466.49  5510.2  467.77  5525.5  467.37
#Mann=7,-1,0
  4068.1    0.05       0  4847.2    0.07       0  4851.2    0.05       0
  4881.2    0.12       0  4980.5     0.1       0  5096.0    0.12       0
  5305.6    0.05       0
Bank Sta=4847.2,4851.2
Exp/Cntr=0.3,0.1

Type RM Length L Ch R = 1,1055,0,0,0
BEGIN DESCRIPTION:
Caney T13_1 1.0
END DESCRIPTION:
XS GIS Cut Line= 3
      2755287.12      6908054.90      2754276.77      6907845.63
      2753950.96      6908086.03
#Sta/Elev= 30
  3968.2  482.77  4081.7  478.53  4224.7  475.01  4259.5  474.72  4455.1  470.53
  4555.5  469.15  4714.8  464.80  4795.1  464.49  4851.5  462.57  4929.3  461.10
  4946.7  459.59  4980.4  459.78  4996.9  458.80  4999.1  459.56  5003.9  458.80
  5012.3  458.67  5018.5  459.33  5023.8  458.57  5024.1  458.07  5027.6  458.07
  5027.8  458.57  5033.2  459.44  5047.8  459.01  5054.0  459.69  5139.6  460.15
  5217.3  462.57  5254.5  463.72  5261.9  464.56  5304.6  463.95  5404.9  465.02
#Mann=5,-1,0
  3968.2    0.05       0  4795.1    0.12       0  5023.8    0.07       0
  5027.8    0.12       0  5217.3    0.05       0
Bank Sta=5023.8,5027.8
Exp/Cntr=0.3,0.1

Chan Stop Cuts=-1