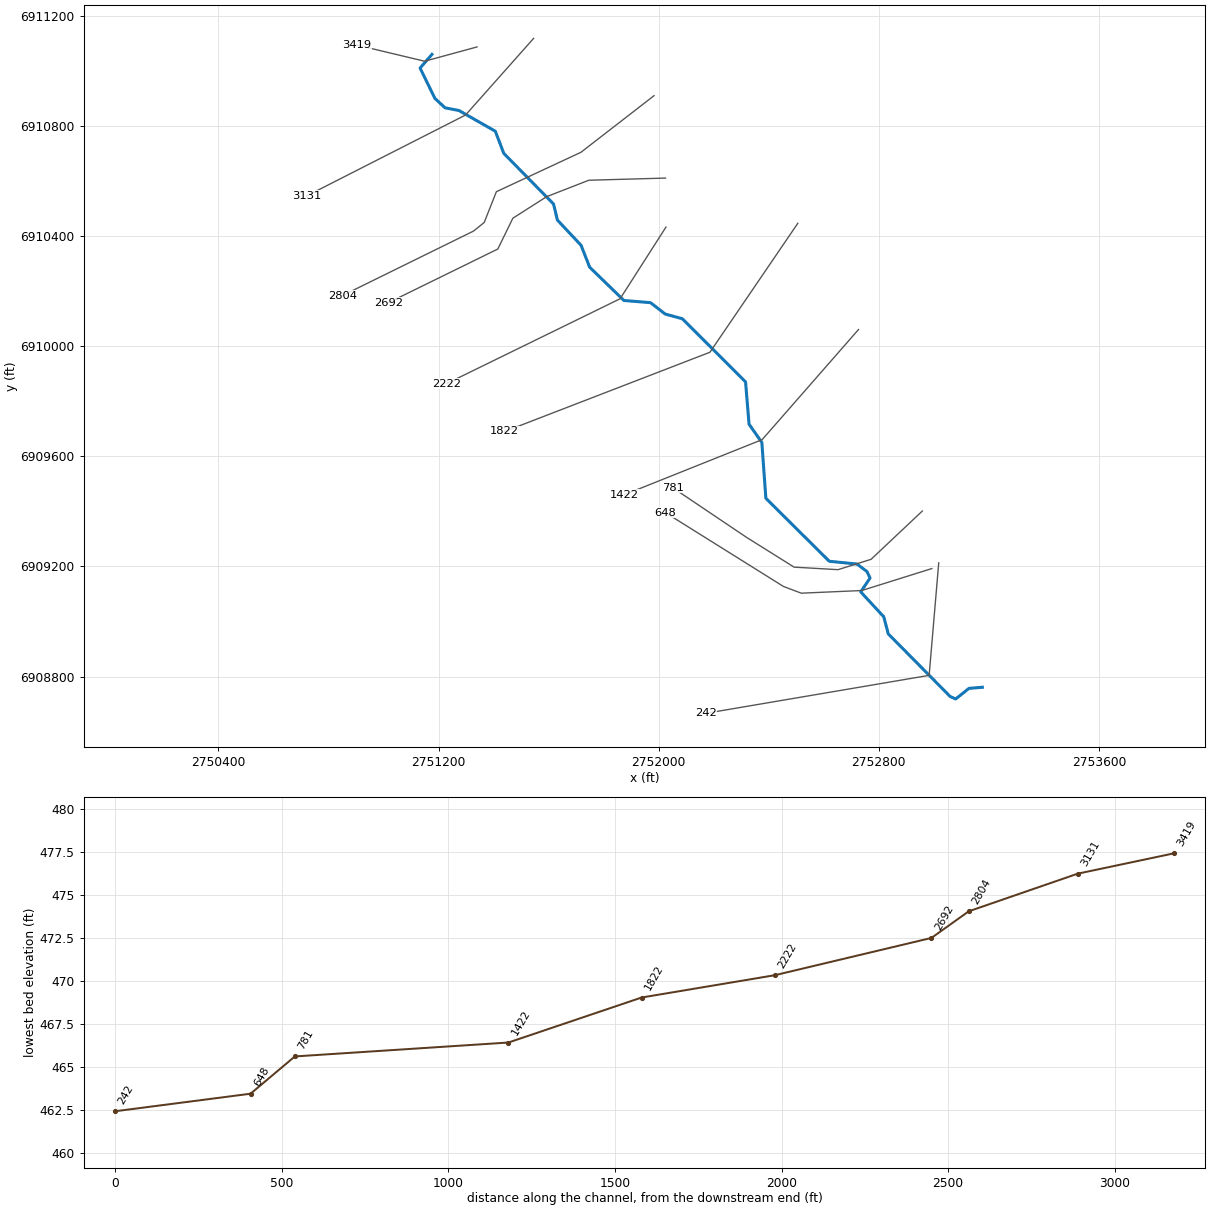
--- Caney T13_2.prj (project) ---

Proj Title=Caney T13_2 Base Level Engineering
Current Plan=p01
Default Exp/Contr=0.3,0.1
English Units
Geom File=g01
Flow File=f01
Plan File=p01
BEGIN DESCRIPTION:
Caney T13_2
END DESCRIPTION:

--- Caney T13_2.p01 (plan) ---

Plan Title=Multiple Run
Short Identifier=Multiple
Geom File=g01
Flow File=f01
Subcritical Flow
K Sum by GR= 0
Std Step Tol= 0.01
Critical Tol= 0.01
Num of Std Step Trials= 20
Max Error Tol= 0.3
Flow Tol Ratio= 0.001
Split Flow NTrial= 30
Split Flow Tol= 0.02
Split Flow Ratio= 0.02
Log Output Level= 0
Friction Slope Method= 1
Unsteady Friction Slope Method= 2
Unsteady Bridges Friction Slope Method= 1
Parabolic Critical Depth
Global Vel Dist=  1 , 1 , 1
Global Log Level= 0
CheckData=True
Encroach Param= -1, 0, 0, 0
BEGIN DESCRIPTION:
Multiple Run
END DESCRIPTION:

--- Caney T13_2.f01 (steady flow) ---

Flow Title=Multiple
Number of Profiles=7
Profile Names=10-year,25-year,50-year,1pct_min,100-year,1pct_plu,500-year
River Rch & RM= Caney T13_2,Reach-1,3419
     372     485     574     338     675    1347     934
Boundary for River Rch & Prof#=Caney T13_2,Reach-1,1
Up Type=0
Dn Type=3
Dn Slope=0.005
Boundary for River Rch & Prof#=Caney T13_2,Reach-1,2
Up Type=0
Dn Type=3
Dn Slope=0.005
Boundary for River Rch & Prof#=Caney T13_2,Reach-1,3
Up Type=0
Dn Type=3
Dn Slope=0.005
Boundary for River Rch & Prof#=Caney T13_2,Reach-1,4
Up Type=0
Dn Type=3
Dn Slope=0.005
Boundary for River Rch & Prof#=Caney T13_2,Reach-1,5
Up Type=0
Dn Type=3
Dn Slope=0.005
Boundary for River Rch & Prof#=Caney T13_2,Reach-1,6
Up Type=0
Dn Type=3
Dn Slope=0.005
Boundary for River Rch & Prof#=Caney T13_2,Reach-1,7
Up Type=0
Dn Type=3
Dn Slope=0.005

--- Caney T13_2.g01 (geometry) ---

Geom Title=Existing Conditions

River Reach=Caney T13_2,Reach-1
Reach XY= 30
      2751176.00      6911061.00      2751132.87      6911011.12
      2751186.61      6910901.00      2751223.45      6910866.73
      2751274.24      6910856.80      2751406.37      6910781.48
      2751436.79      6910701.34      2751617.84      6910517.05
      2751631.87      6910458.72      2751717.82      6910367.04
      2751749.01      6910287.53      2751873.57      6910166.52
      2751970.03      6910158.67      2752023.83      6910117.14
      2752085.68      6910100.24      2752315.52      6909870.80
      2752328.27      6909716.94      2752374.78      6909650.49
      2752389.37      6909447.68      2752619.83      6909218.86
      2752720.50      6909208.85      2752756.83      6909181.48
      2752767.93      6909157.87      2752734.02      6909107.68
      2752817.80      6909017.05      2752834.16      6908954.95
      2753059.31      6908727.25      2753079.25      6908718.54
      2753127.36      6908756.98      2753176.00      6908761.00

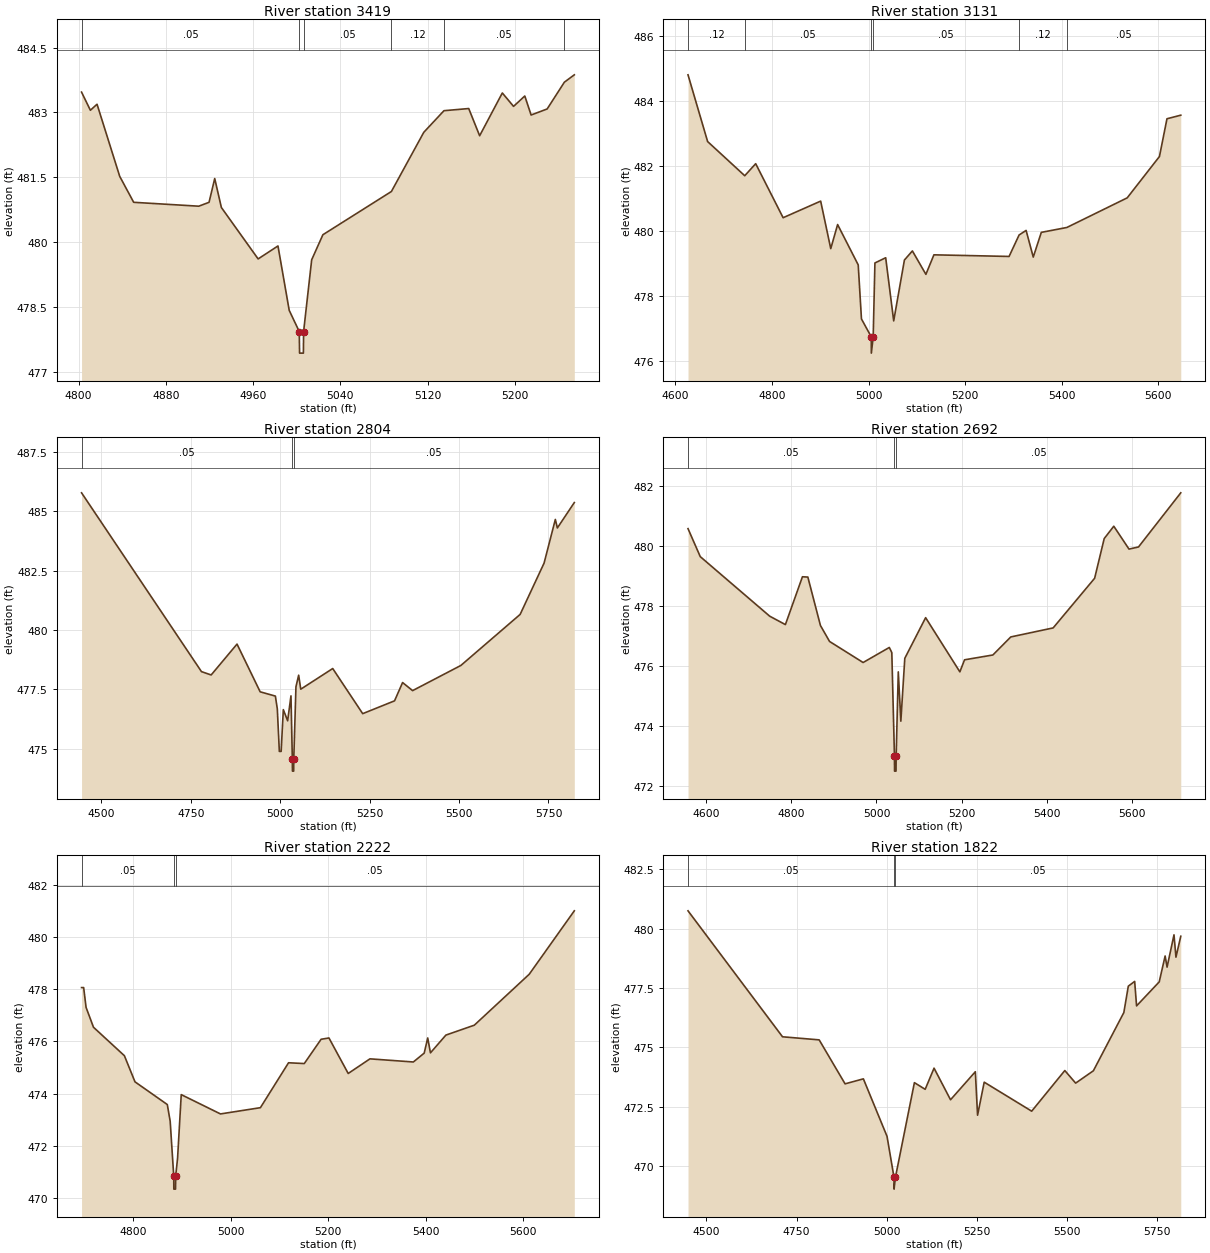
Type RM Length L Ch R = 1,3419,288,288,288
BEGIN DESCRIPTION:
Caney T13_2 6.0
END DESCRIPTION:
XS GIS Cut Line= 3
      2751339.72      6911087.87      2751149.37      6911035.98
      2750901.81      6911095.01
#Sta/Elev= 30
  4802.7  483.47  4810.8  483.05  4816.9  483.19  4837.7  481.52  4850.5  480.92
  4910.2  480.83  4919.6  480.92  4924.8  481.47  4930.9  480.80  4964.6  479.61
  4982.8  479.91  4993.1  478.42  5002.3  477.93  5002.6  477.43  5006.1  477.43
  5006.3  477.93  5013.7  479.59  5024.0  480.17  5086.8  481.17  5116.5  482.54
  5135.0  483.04  5157.7  483.09  5167.7  482.46  5188.5  483.45  5198.8  483.14
  5209.1  483.38  5214.9  482.94  5229.6  483.08  5245.4  483.70  5254.5  483.87
#Mann=6,-1,0
  4802.7    0.05       0  5002.3    0.04       0  5006.3    0.05       0
  5086.8    0.12       0  5135.0    0.05       0  5245.4    0.12       0
Bank Sta=5002.3,5006.3
Exp/Cntr=0.3,0.1

Type RM Length L Ch R = 1,3131,327,327,327
BEGIN DESCRIPTION:
Mapping XS 2127f80c
END DESCRIPTION:
XS GIS Cut Line= 3
      2751545.53      6911119.16      2751298.10      6910840.49
      2750720.49      6910546.48
#Sta/Elev= 30
  4626.0  484.80  4666.6  482.75  4743.5  481.70  4766.2  482.07  4823.0  480.41
  4900.8  480.92  4921.7  479.46  4935.9  480.20  4978.6  478.96  4985.3  477.30
  5005.6  476.75  5005.8  476.25  5009.6  476.75  5013.2  479.02  5035.5  479.18
  5052.1  477.24  5074.3  479.11  5090.8  479.39  5118.8  478.67  5135.4  479.27
  5291.1  479.22  5311.9  479.88  5326.4  480.02  5341.2  479.20  5357.9  479.96
  5410.8  480.11  5535.8  481.02  5602.6  482.29  5618.2  483.45  5646.8  483.56
#Mann=6,-1,0
  4626.0    0.12       0  4743.5    0.05       0  5005.6    0.04       0
  5009.6    0.05       0  5311.9    0.12       0  5410.8    0.05       0
Bank Sta=5005.6,5009.6
Exp/Cntr=0.3,0.1

Type RM Length L Ch R = 1,2804,112,112,112
BEGIN DESCRIPTION:
Mapping XS 35f5177d
END DESCRIPTION:
XS GIS Cut Line= 6
      2751983.00      6910910.80      2751717.37      6910705.07
      2751410.08      6910561.84      2751365.81      6910449.86
      2751326.75      6910418.61      2750850.15      6910184.22
#Sta/Elev= 30
  4444.8  485.78  4780.0  478.25  4807.1  478.11  4879.4  479.41  4944.1  477.40
  4986.6  477.22  4992.0  476.68  4997.7  474.89  5002.7  474.89  5008.8  476.65
  5020.9  476.18  5030.2  477.23  5034.0  474.56  5034.3  474.06  5037.8  474.06
  5038.0  474.56  5044.1  477.61  5051.7  478.10  5057.5  477.51  5146.9  478.38
  5230.7  476.48  5319.7  477.02  5342.2  477.79  5370.2  477.45  5505.1  478.51
  5670.8  480.66  5737.7  482.82  5769.2  484.66  5774.8  484.30  5822.2  485.37
#Mann=3,-1,0
  4444.8    0.05       0  5034.0    0.04       0  5038.0    0.05       0
Bank Sta=5034,5038
Exp/Cntr=0.3,0.1

Type RM Length L Ch R = 1,2692,470,470,470
BEGIN DESCRIPTION:
Mapping XS 187fda03
END DESCRIPTION:
XS GIS Cut Line= 6
      2752024.64      6910611.32      2751746.02      6910603.51
      2751592.37      6910543.61      2751469.98      6910465.49
      2751415.29      6910353.51      2751016.85      6910158.20
#Sta/Elev= 30
  4557.5  480.57  4586.2  479.64  4749.3  477.66  4786.2  477.38  4826.2  478.97
  4838.9  478.96  4868.5  477.35  4889.9  476.82  4968.7  476.12  5030.2  476.62
  5036.1  476.45  5042.3  473.01  5042.5  472.51  5046.0  472.51  5046.3  473.01
  5051.3  475.81  5057.3  474.17  5066.6  476.26  5115.5  477.61  5195.9  475.81
  5206.9  476.21  5273.4  476.37  5315.5  476.97  5415.0  477.27  5512.4  478.92
  5534.9  480.24  5557.4  480.65  5593.1  479.89  5615.4  479.96  5714.7  481.76
#Mann=3,-1,0
  4557.5    0.05       0  5042.3    0.04       0  5046.3    0.05       0
Bank Sta=5042.3,5046.3
Exp/Cntr=0.3,0.1

Type RM Length L Ch R = 1,2222,400,400,400
BEGIN DESCRIPTION:
Mapping XS 9cc481f5
END DESCRIPTION:
XS GIS Cut Line= 3
      2752026.36      6910433.28      2751859.68      6910172.84
      2751229.41      6909864.63
#Sta/Elev= 30
  4694.0  478.06  4698.3  478.06  4703.3  477.30  4718.5  476.54  4781.9  475.45
  4803.6  474.45  4869.9  473.58  4875.8  472.94  4883.1  470.84  4883.3  470.34
  4886.8  470.34  4887.1  470.84  4891.0  471.53  4898.5  473.96  4979.0  473.22
  5060.9  473.46  5118.6  475.18  5150.9  475.15  5185.4  476.08  5201.5  476.13
  5241.0  474.77  5285.6  475.33  5374.6  475.21  5396.9  475.55  5404.1  476.13
  5409.7  475.56  5441.4  476.24  5499.7  476.62  5612.3  478.57  5704.8  481.00
#Mann=3,-1,0
  4694.0    0.05       0  4883.1    0.04       0  4887.1    0.05       0
Bank Sta=4883.1,4887.1
Exp/Cntr=0.3,0.1

Type RM Length L Ch R = 1,1822,400,400,400
BEGIN DESCRIPTION:
Mapping XS a999815c
END DESCRIPTION:
XS GIS Cut Line= 3
      2752505.51      6910447.14      2752186.07      6909978.39
      2751440.26      6909690.48
#Sta/Elev= 30
  4449.0  480.75  4711.1  475.45  4812.8  475.32  4884.6  473.47  4935.4  473.68
  5001.0  471.26  5020.3  469.54  5020.5  469.04  5024.3  469.54  5076.9  473.52
  5106.8  473.24  5131.4  474.13  5177.1  472.80  5245.9  473.98  5252.1  472.15
  5270.5  473.54  5402.2  472.32  5494.1  474.03  5524.1  473.50  5573.3  474.02
  5657.8  476.47  5670.2  477.58  5687.8  477.78  5693.1  476.75  5755.9  477.76
  5772.3  478.85  5777.7  478.38  5796.9  479.74  5802.3  478.80  5815.7  479.68
#Mann=3,-1,0
  4449.0    0.05       0  5020.3    0.04       0  5024.3    0.05       0
Bank Sta=5020.3,5024.3
Exp/Cntr=0.3,0.1

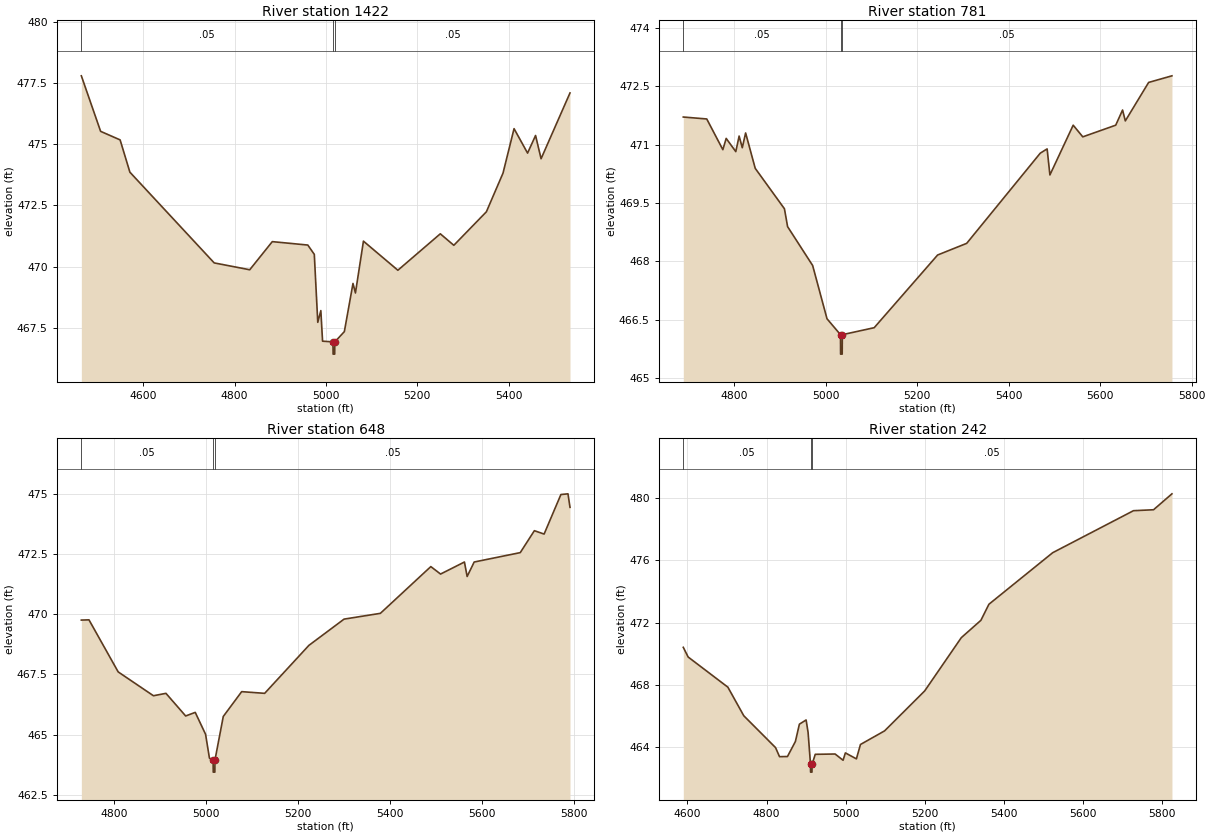
Type RM Length L Ch R = 1,1422,641,641,641
BEGIN DESCRIPTION:
Caney T13_2 2.0
END DESCRIPTION:
XS GIS Cut Line= 3
      2752726.00      6910061.00      2752376.00      6909661.00
      2751876.02      6909461.01
#Sta/Elev= 30
  4464.4  477.80  4506.6  475.53  4549.3  475.18  4570.7  473.86  4755.3  470.15
  4833.1  469.87  4882.5  471.02  4960.3  470.88  4974.5  470.50  4982.1  467.72
  4988.8  468.20  4992.6  466.95  5015.4  466.92  5015.7  466.42  5019.2  466.42
  5019.4  466.92  5040.3  467.34  5059.2  469.31  5064.6  468.92  5082.1  471.04
  5157.5  469.85  5250.4  471.34  5280.0  470.87  5351.3  472.24  5387.7  473.82
  5411.9  475.64  5441.5  474.64  5459.0  475.36  5471.1  474.41  5534.4  477.10
#Mann=3,-1,0
  4464.4    0.05       0  5015.4    0.04       0  5019.4    0.05       0
Bank Sta=5015.4,5019.4
Exp/Cntr=0.3,0.1

Type RM Length L Ch R = 1,781,133,133,133
BEGIN DESCRIPTION:
Mapping XS 92710d59
END DESCRIPTION:
XS GIS Cut Line= 6
      2752958.01      6909401.50      2752771.66      6909225.94
      2752651.63      6909188.39      2752491.98      6909197.51
      2752318.93      6909305.88      2752051.12      6909486.12
#Sta/Elev= 30
  4688.2  471.71  4739.5  471.66  4774.7  470.87  4782.0  471.16  4803.0  470.82
  4810.3  471.22  4817.2  470.92  4824.5  471.30  4845.5  470.39  4909.4  469.35
  4916.3  468.89  4971.1  467.89  5002.5  466.52  5032.0  466.11  5032.2  465.61
  5035.7  465.61  5036.0  466.11  5105.7  466.29  5244.4  468.16  5308.0  468.46
  5468.9  470.78  5483.9  470.89  5490.0  470.22  5540.9  471.50  5561.9  471.20
  5633.9  471.50  5648.9  471.89  5654.9  471.61  5705.9  472.60  5756.9  472.77
#Mann=3,-1,0
  4688.2    0.05       0  5032.0    0.04       0  5036.0    0.05       0
Bank Sta=5032,5036
Exp/Cntr=0.3,0.1

Type RM Length L Ch R = 1,648,406,406,406
BEGIN DESCRIPTION:
Mapping XS d5fb2156
END DESCRIPTION:
XS GIS Cut Line= 5
      2752992.41      6909192.34      2752737.76      6909112.55
      2752518.09      6909102.90      2752453.36      6909127.30
      2752023.61      6909396.09
#Sta/Elev= 30
  4729.2  469.75  4745.8  469.76  4809.3  467.60  4886.0  466.61  4913.2  466.71
  4956.1  465.77  4976.9  465.92  4999.4  465.01  5007.8  464.02  5015.8  463.94
  5016.1  463.44  5019.6  463.44  5019.8  463.94  5037.9  465.75  5077.9  466.78
  5127.9  466.71  5224.1  468.70  5300.6  469.79  5379.6  470.03  5489.3  471.97
  5510.5  471.66  5562.4  472.16  5568.3  471.56  5583.6  472.16  5683.8  472.55
  5714.5  473.46  5735.7  473.32  5772.2  474.96  5787.6  474.99  5792.0  474.43
#Mann=3,-1,0
  4729.2    0.05       0  5015.8    0.04       0  5019.8    0.05       0
Bank Sta=5015.8,5019.8
Exp/Cntr=0.3,0.1

Type RM Length L Ch R = 1,242,0,0,0
BEGIN DESCRIPTION:
Caney T13_2 1.0
END DESCRIPTION:
XS GIS Cut Line= 3
      2753017.53      6909213.21      2752982.67      6908804.30
      2752170.13      6908666.14
#Sta/Elev= 30
  4589.6  470.41  4601.9  469.79  4702.2  467.86  4742.4  466.03  4822.7  463.99
  4832.7  463.41  4852.8  463.42  4872.8  464.38  4882.9  465.49  4899.9  465.76
  4904.9  464.96  4911.0  462.92  4911.2  462.42  4914.7  462.42  4915.0  462.92
  4923.0  463.56  4973.2  463.58  4993.3  463.18  4999.1  463.65  5027.0  463.27
  5037.2  464.19  5098.1  465.06  5199.5  467.62  5292.0  471.03  5341.5  472.14
  5361.8  473.17  5522.9  476.47  5727.0  479.16  5777.7  479.22  5824.2  480.24
#Mann=3,-1,0
  4589.6    0.05       0  4911.0    0.04       0  4915.0    0.05       0
Bank Sta=4911,4915
Exp/Cntr=0.3,0.1

Chan Stop Cuts=-1