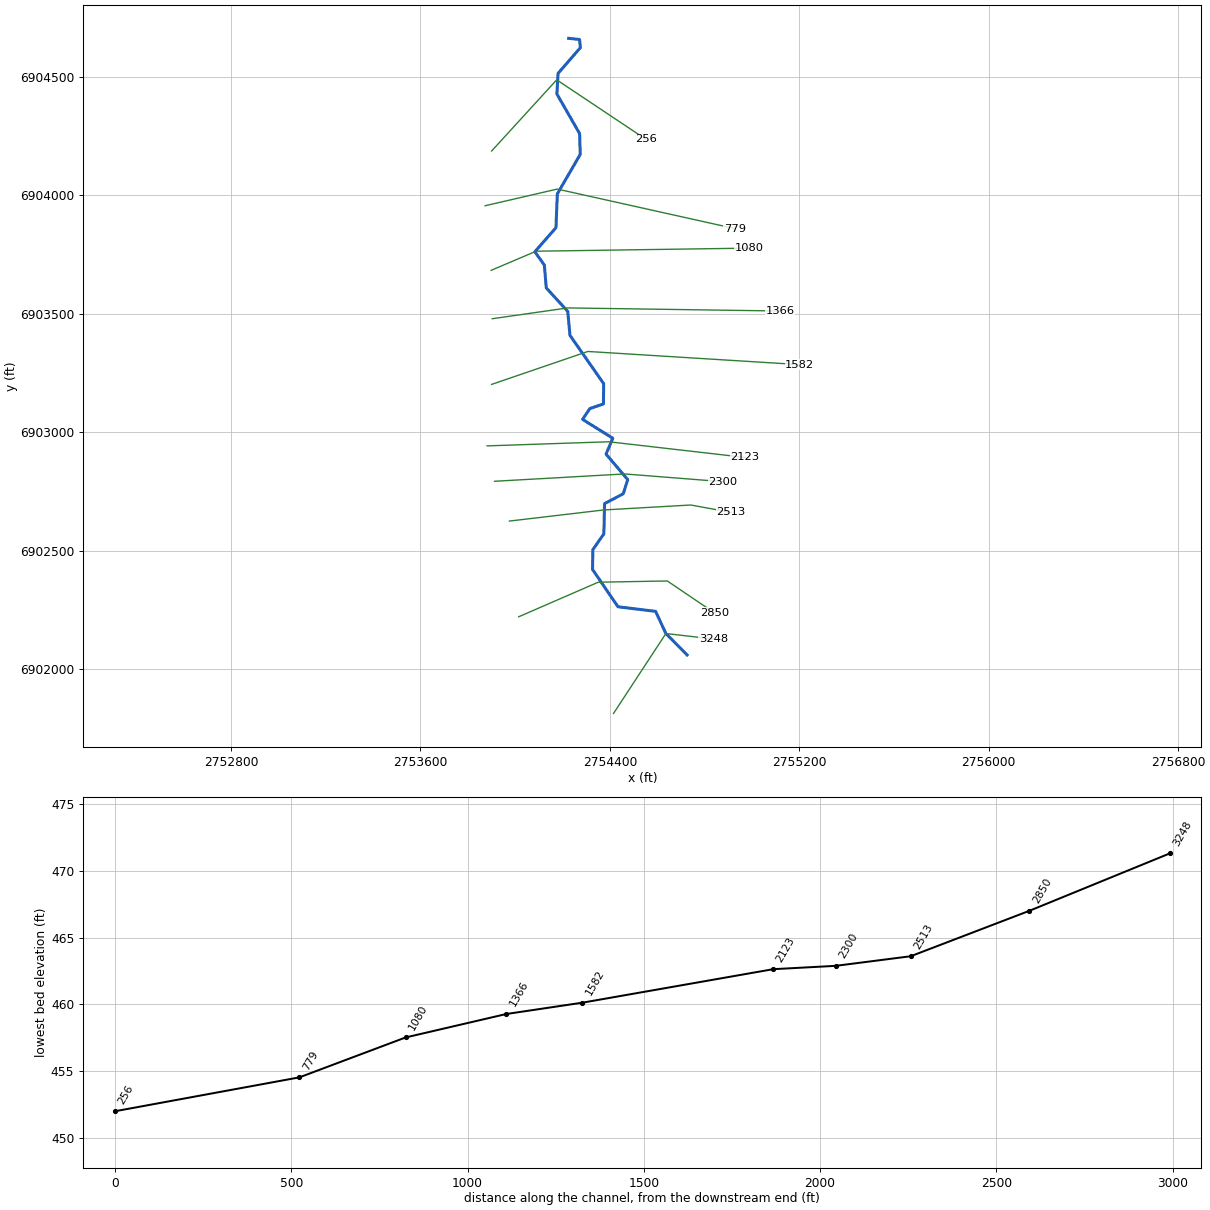
--- Caney T14.prj (project) ---

Proj Title=Caney T14 Base Level Engineering
Current Plan=p01
Default Exp/Contr=0.3,0.1
English Units
Geom File=g01
Flow File=f01
Plan File=p01
BEGIN DESCRIPTION:
Caney T14
END DESCRIPTION:

--- Caney T14.p01 (plan) ---

Plan Title=Multiple Run
Short Identifier=Multiple
Geom File=g01
Flow File=f01
Subcritical Flow
K Sum by GR= 0
Std Step Tol= 0.01
Critical Tol= 0.01
Num of Std Step Trials= 20
Max Error Tol= 0.3
Flow Tol Ratio= 0.001
Split Flow NTrial= 30
Split Flow Tol= 0.02
Split Flow Ratio= 0.02
Log Output Level= 0
Friction Slope Method= 1
Unsteady Friction Slope Method= 2
Unsteady Bridges Friction Slope Method= 1
Parabolic Critical Depth
Global Vel Dist=  1 , 1 , 1
Global Log Level= 0
CheckData=True
Encroach Param= -1, 0, 0, 0
BEGIN DESCRIPTION:
Multiple Run
END DESCRIPTION:

--- Caney T14.f01 (steady flow) ---

Flow Title=Multiple
Number of Profiles=7
Profile Names=10-year,25-year,50-year,1pct_min,100-year,1pct_plu,500-year
River Rch & RM= Caney T14,Reach-1,3248
     345     450     535     316     631    1260     880
Boundary for River Rch & Prof#=Caney T14,Reach-1,1
Up Type=0
Dn Type=3
Dn Slope=0.005
Boundary for River Rch & Prof#=Caney T14,Reach-1,2
Up Type=0
Dn Type=3
Dn Slope=0.005
Boundary for River Rch & Prof#=Caney T14,Reach-1,3
Up Type=0
Dn Type=3
Dn Slope=0.005
Boundary for River Rch & Prof#=Caney T14,Reach-1,4
Up Type=0
Dn Type=3
Dn Slope=0.005
Boundary for River Rch & Prof#=Caney T14,Reach-1,5
Up Type=0
Dn Type=3
Dn Slope=0.005
Boundary for River Rch & Prof#=Caney T14,Reach-1,6
Up Type=0
Dn Type=3
Dn Slope=0.005
Boundary for River Rch & Prof#=Caney T14,Reach-1,7
Up Type=0
Dn Type=3
Dn Slope=0.005

--- Caney T14.g01 (geometry) ---

Geom Title=Existing Conditions

River Reach=Caney T14,Reach-1
Reach XY= 30
      2754726.00      6902061.00      2754636.72      6902151.31
      2754593.14      6902244.72      2754434.30      6902264.08
      2754326.94      6902421.48      2754328.16      6902505.02
      2754374.76      6902571.52      2754377.66      6902699.16
      2754456.63      6902740.57      2754475.45      6902800.32
      2754384.02      6902907.68      2754412.49      6902974.68
      2754284.80      6903054.20      2754315.87      6903100.07
      2754372.97      6903119.34      2754373.90      6903204.95
      2754231.54      6903408.58      2754222.37      6903509.50
      2754131.53      6903608.58      2754123.44      6903705.11
      2754083.33      6903761.10      2754172.43      6903862.47
      2754178.25      6904005.07      2754274.92      6904171.54
      2754272.33      6904259.42      2754176.36      6904426.27
      2754181.41      6904513.42      2754275.63      6904621.79
      2754272.07      6904656.08      2754226.00      6904661.00

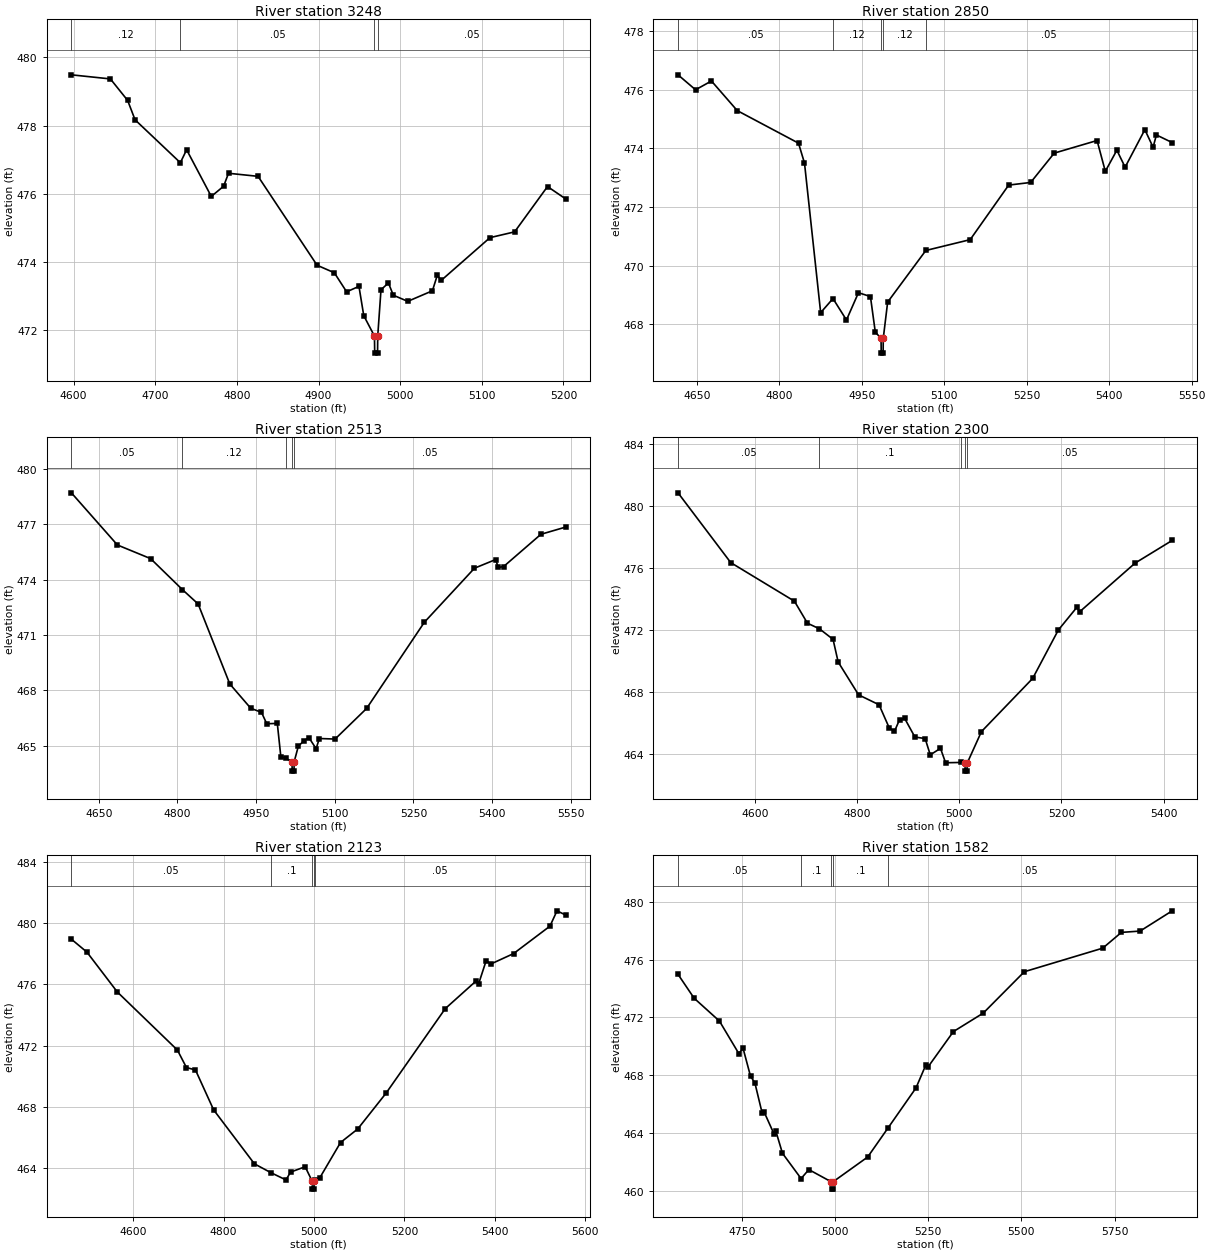
Type RM Length L Ch R = 1,3248,398,398,398
BEGIN DESCRIPTION:
Caney T14 5.0
END DESCRIPTION:
XS GIS Cut Line= 3
      2754415.73      6901814.55      2754636.72      6902151.31
      2754837.99      6902128.08
#Sta/Elev= 30
  4597.2  479.49  4645.0  479.37  4666.1  478.74  4675.2  478.17  4730.7  476.91
  4738.4  477.29  4768.6  475.92  4783.7  476.22  4789.7  476.60  4825.9  476.51
  4898.2  473.90  4919.3  473.68  4934.4  473.12  4949.5  473.28  4955.4  472.42
  4968.5  471.82  4968.8  471.32  4972.3  471.32  4972.5  471.82  4976.5  473.18
  4985.6  473.38  4991.6  473.02  5009.3  472.84  5039.5  473.15  5045.4  473.60
  5050.5  473.46  5110.0  474.71  5140.2  474.88  5180.5  476.21  5202.6  475.85
#Mann=4,-1,0
  4597.2    0.12       0  4730.7    0.05       0  4968.5    0.04       0
  4972.5    0.05       0
Bank Sta=4968.5,4972.5
Exp/Cntr=0.3,0.1

Type RM Length L Ch R = 1,2850,337,337,337
BEGIN DESCRIPTION:
Mapping XS 884268c5
END DESCRIPTION:
XS GIS Cut Line= 4
      2754015.05      6902221.84      2754350.96      6902367.66
      2754642.62      6902372.87      2754842.09      6902238.17
#Sta/Elev= 30
  4616.0  476.51  4647.9  476.00  4676.8  476.30  4723.7  475.29  4835.1  474.18
  4846.0  473.50  4875.4  468.40  4897.8  468.88  4922.3  468.15  4944.1  469.08
  4965.9  468.95  4974.7  467.74  4985.2  467.52  4985.5  467.02  4989.0  467.02
  4989.2  467.52  4997.2  468.76  5066.6  470.52  5147.3  470.89  5217.3  472.75
  5257.3  472.84  5300.1  473.84  5378.0  474.27  5393.0  473.22  5414.0  473.94
  5429.0  473.36  5464.9  474.64  5479.9  474.04  5485.9  474.46  5514.6  474.20
#Mann=5,-1,0
  4616.0    0.05       0  4897.8    0.12       0  4985.2    0.07       0
  4989.2    0.12       0  5066.6    0.05       0
Bank Sta=4985.2,4989.2
Exp/Cntr=0.3,0.1

Type RM Length L Ch R = 1,2513,213,213,213
BEGIN DESCRIPTION:
Mapping XS acbf9309
END DESCRIPTION:
XS GIS Cut Line= 4
      2753975.97      6902625.48      2754374.40      6902672.35
      2754741.58      6902693.19      2754912.23      6902662.16
#Sta/Elev= 30
  4597.8  478.71  4685.6  475.88  4748.9  475.14  4809.5  473.46  4839.5  472.68
  4899.9  468.34  4939.9  467.02  4960.3  466.80  4970.4  466.18  4990.5  466.20
  4997.3  464.38  5006.7  464.31  5018.6  464.11  5018.9  463.61  5022.4  463.61
  5022.6  464.11  5030.6  464.96  5040.6  465.24  5050.7  465.43  5064.5  464.83
  5070.7  465.38  5100.7  465.35  5160.8  467.01  5271.0  471.69  5366.5  474.62
  5406.9  475.09  5411.9  474.66  5422.1  474.71  5493.2  476.46  5540.2  476.85
#Mann=5,-1,0
  4597.8    0.05       0  4809.5    0.12       0  5006.7    0.05       0
  5018.6    0.07       0  5022.6    0.05       0
Bank Sta=5018.6,5022.6
Exp/Cntr=0.3,0.1

Type RM Length L Ch R = 1,2300,177,177,177
BEGIN DESCRIPTION:
Caney T14 3.0
END DESCRIPTION:
XS GIS Cut Line= 3
      2753913.01      6902793.19      2754462.84      6902824.20
      2754878.25      6902791.46
#Sta/Elev= 30
  4449.3  480.84  4552.5  476.34  4677.2  473.85  4702.7  472.43  4726.1  472.07
  4752.8  471.39  4762.8  469.93  4802.8  467.81  4842.9  467.17  4862.9  465.67
  4873.0  465.45  4883.0  466.21  4893.0  466.29  4913.0  465.09  4933.1  464.99
  4943.1  463.94  4963.1  464.36  4973.1  463.43  5003.2  463.45  5011.2  463.39
  5011.5  462.89  5015.0  462.89  5015.2  463.39  5043.3  465.44  5143.6  468.87
  5193.8  471.99  5230.2  473.46  5235.3  473.16  5344.2  476.31  5416.7  477.77
#Mann=5,-1,0
  4449.3    0.05       0  4726.1     0.1       0  5003.2    0.05       0
  5011.2    0.07       0  5015.2    0.05       0
Bank Sta=5011.2,5015.2
Exp/Cntr=0.3,0.1

Type RM Length L Ch R = 1,2123,541,541,541
BEGIN DESCRIPTION:
Mapping XS a4b1355e
END DESCRIPTION:
XS GIS Cut Line= 3
      2753881.72      6902942.50      2754395.63      6902959.86
      2754970.26      6902893.89
#Sta/Elev= 30
  4463.6  478.94  4497.9  478.10  4565.1  475.50  4698.0  471.71  4718.0  470.57
  4738.0  470.41  4778.1  467.81  4868.3  464.29  4904.3  463.72  4938.1  463.24
  4948.2  463.75  4980.5  464.10  4996.3  463.14  4996.6  462.64  5000.1  462.64
  5000.3  463.14  5002.2  463.26  5012.5  463.36  5058.7  465.68  5096.6  466.56
  5159.4  468.90  5290.2  474.41  5359.0  476.23  5364.0  476.03  5380.8  477.55
  5390.9  477.32  5441.2  478.00  5521.7  479.79  5537.3  480.79  5556.2  480.52
#Mann=5,-1,0
  4463.6    0.05       0  4904.3     0.1       0  4996.3    0.07       0
  5000.3     0.1       0  5002.2    0.05       0
Bank Sta=4996.3,5000.3
Exp/Cntr=0.3,0.1

Type RM Length L Ch R = 1,1582,216,216,216
BEGIN DESCRIPTION:
Mapping XS 874d9f70
END DESCRIPTION:
XS GIS Cut Line= 3
      2753900.84      6903201.76      2754307.09      6903340.65
      2755201.94      6903285.15
#Sta/Elev= 30
  4578.8  474.98  4622.0  473.33  4689.9  471.75  4742.0  469.50  4753.3  469.87
  4773.3  467.94  4785.0  467.48  4804.6  465.38  4809.9  465.46  4835.9  463.97
  4841.2  464.15  4859.0  462.61  4909.0  460.86  4929.8  461.48  4990.4  460.63
  4990.7  460.13  4994.2  460.13  4994.4  460.63  5087.7  462.35  5142.3  464.36
  5217.4  467.13  5243.6  468.71  5248.6  468.54  5317.6  471.02  5397.8  472.30
  5508.0  475.16  5718.4  476.79  5768.5  477.88  5818.6  477.97  5904.7  479.37
#Mann=5,-1,0
  4578.8    0.05       0  4909.0     0.1       0  4990.4    0.07       0
  4994.4     0.1       0  5142.3    0.05       0
Bank Sta=4990.4,4994.4
Exp/Cntr=0.3,0.1

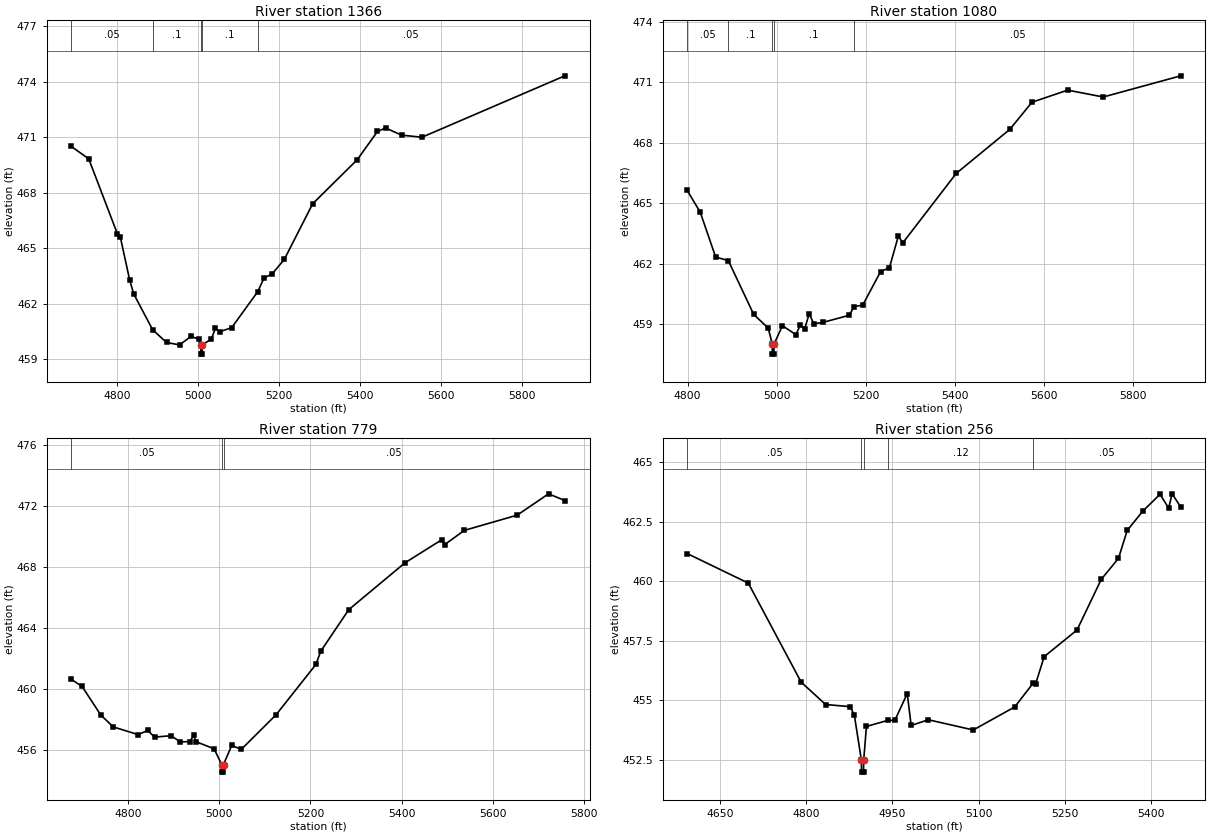
Type RM Length L Ch R = 1,1366,286,286,286
BEGIN DESCRIPTION:
Mapping XS 397668c1
END DESCRIPTION:
XS GIS Cut Line= 3
      2753903.39      6903478.66      2754222.45      6903524.24
      2755118.76      6903511.22
#Sta/Elev= 30
  4686.6  470.51  4729.6  469.84  4800.4  465.78  4807.3  465.64  4830.7  463.28
  4840.8  462.53  4887.3  460.60  4921.6  459.91  4953.8  459.78  4982.2  460.24
  5002.4  460.08  5006.2  459.78  5006.4  459.28  5009.9  459.28  5010.2  459.78
  5032.4  460.10  5042.4  460.68  5052.5  460.49  5082.5  460.71  5146.7  462.65
  5162.5  463.40  5182.5  463.62  5212.5  464.40  5282.5  467.41  5392.5  469.79
  5442.5  471.32  5462.5  471.51  5502.5  471.12  5552.5  471.01  5905.3  474.33
#Mann=5,-1,0
  4686.6    0.05       0  4887.3     0.1       0  5006.2    0.07       0
  5010.2     0.1       0  5146.7    0.05       0
Bank Sta=5006.2,5010.2
Exp/Cntr=0.3,0.1

Type RM Length L Ch R = 1,1080,301,301,301
BEGIN DESCRIPTION:
Mapping XS e427c47e
END DESCRIPTION:
XS GIS Cut Line= 3
      2753898.69      6903682.67      2754088.77      6903763.39
      2754989.76      6903776.41
#Sta/Elev= 30
  4799.4  465.64  4828.6  464.56  4863.1  462.34  4891.6  462.16  4948.6  459.49
  4981.2  458.81  4990.2  458.02  4990.5  457.52  4994.0  457.52  4994.2  458.02
  5013.1  458.93  5043.1  458.49  5053.1  458.95  5063.1  458.78  5073.1  459.53
  5083.2  459.03  5103.2  459.09  5163.2  459.45  5173.8  459.88  5193.2  459.95
  5233.2  461.61  5253.2  461.81  5273.2  463.38  5283.2  463.04  5403.2  466.49
  5523.2  468.67  5573.2  470.02  5653.2  470.62  5733.2  470.28  5907.0  471.33
#Mann=5,-1,0
  4799.4    0.05       0  4891.6     0.1       0  4990.2    0.07       0
  4994.2     0.1       0  5173.8    0.05       0
Bank Sta=4990.2,4994.2
Exp/Cntr=0.3,0.1

Type RM Length L Ch R = 1,779,523,523,523
BEGIN DESCRIPTION:
Mapping XS 4d3d52dc
END DESCRIPTION:
XS GIS Cut Line= 3
      2753873.19      6903955.04      2754177.93      6904025.36
      2754927.89      6903858.70
#Sta/Elev= 30
  4676.2  460.62  4699.6  460.16  4740.7  458.28  4767.9  457.50  4822.8  456.99
  4843.3  457.27  4858.5  456.83  4894.6  456.92  4915.1  456.51  4935.7  456.54
  4944.1  456.94  4949.2  456.53  4988.9  456.06  5005.5  455.03  5005.7  454.53
  5009.2  454.53  5009.5  455.03  5027.5  456.28  5048.4  456.02  5124.8  458.30
  5211.9  461.60  5222.6  462.47  5284.0  465.20  5407.0  468.27  5488.4  469.80
  5493.6  469.46  5537.1  470.40  5652.8  471.40  5721.5  472.80  5757.2  472.36
#Mann=3,-1,0
  4676.2    0.05       0  5005.5    0.04       0  5009.5    0.05       0
Bank Sta=5005.5,5009.5
Exp/Cntr=0.3,0.1

Type RM Length L Ch R = 1,256,0,0,0
BEGIN DESCRIPTION:
Caney T14 1.0
END DESCRIPTION:
XS GIS Cut Line= 3
      2753900.98      6904185.97      2754175.51      6904486.04
      2754550.98      6904236.01
#Sta/Elev= 30
  4593.3  461.17  4699.4  459.93  4791.3  455.77  4833.8  454.83  4876.4  454.74
  4883.8  454.38  4896.0  452.49  4896.2  451.99  4899.7  451.99  4900.0  452.49
  4904.8  453.91  4942.9  454.17  4954.1  454.16  4975.7  455.29  4982.5  453.95
  5012.4  454.19  5090.5  453.76  5162.6  454.73  5194.3  455.72  5198.7  455.68
  5213.7  456.84  5270.8  457.96  5313.0  460.09  5342.9  460.97  5358.0  462.14
  5385.0  462.95  5415.1  463.66  5430.1  463.08  5436.1  463.68  5451.1  463.13
#Mann=5,-1,0
  4593.3    0.05       0  4896.0    0.07       0  4900.0    0.05       0
  4942.9    0.12       0  5194.3    0.05       0
Bank Sta=4896,4900
Exp/Cntr=0.3,0.1

Chan Stop Cuts=-1