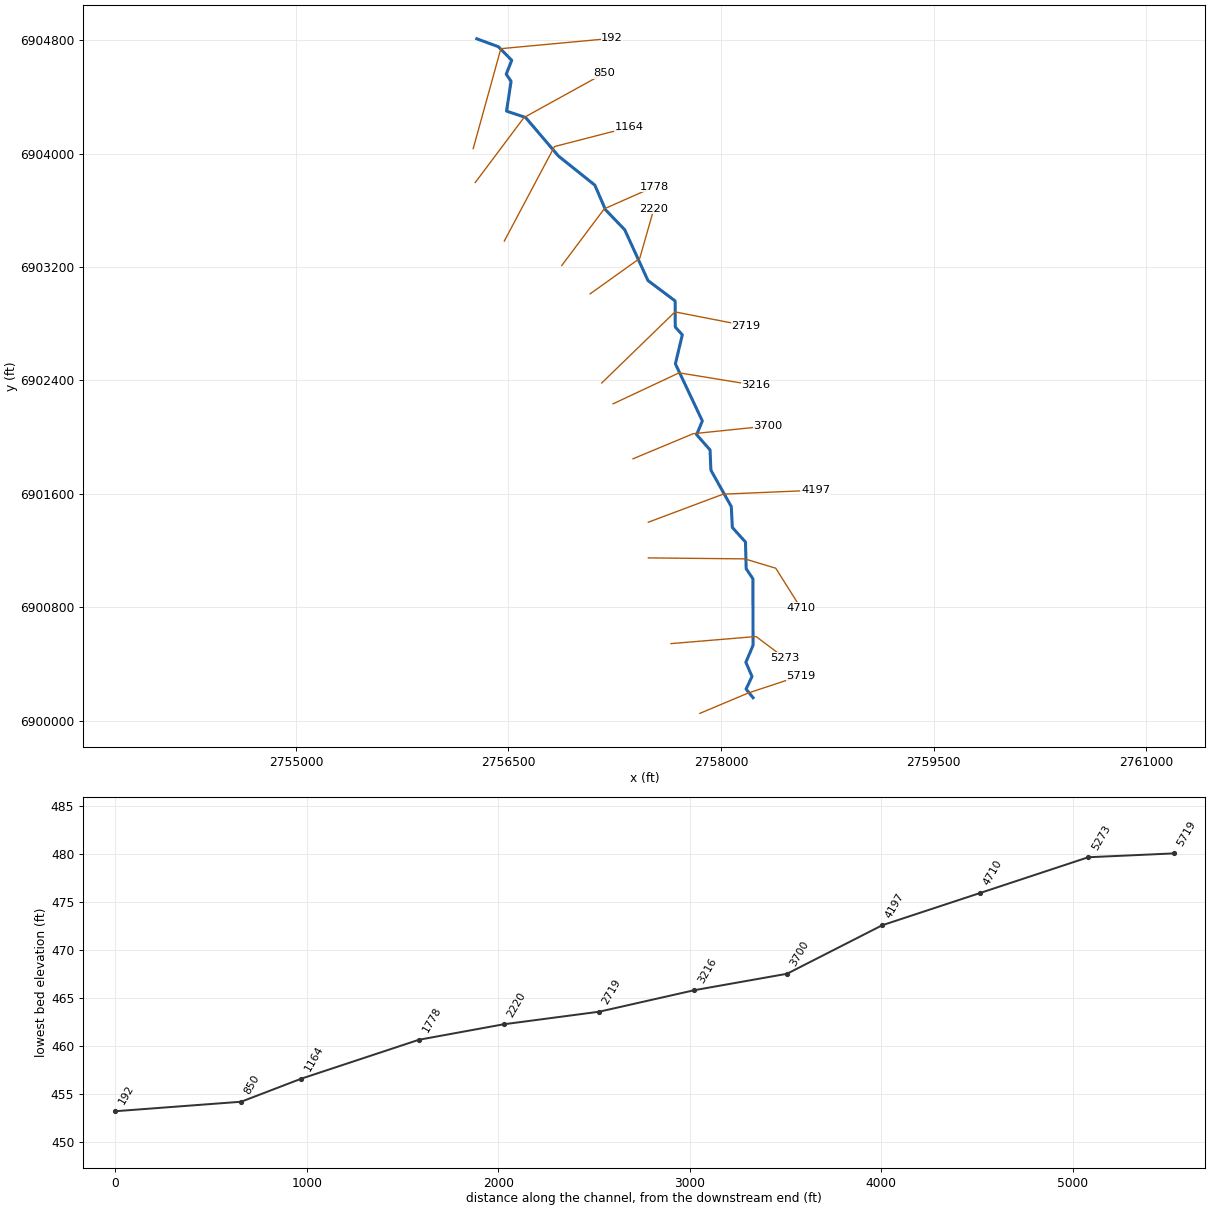
--- Caney T15.prj (project) ---

Proj Title=Caney T15 Base Level Engineering
Current Plan=p01
Default Exp/Contr=0.3,0.1
English Units
Geom File=g01
Flow File=f01
Plan File=p01
BEGIN DESCRIPTION:
Caney T15
END DESCRIPTION:

--- Caney T15.p01 (plan) ---

Plan Title=Multiple Run
Short Identifier=Multiple
Geom File=g01
Flow File=f01
Subcritical Flow
K Sum by GR= 0
Std Step Tol= 0.01
Critical Tol= 0.01
Num of Std Step Trials= 20
Max Error Tol= 0.3
Flow Tol Ratio= 0.001
Split Flow NTrial= 30
Split Flow Tol= 0.02
Split Flow Ratio= 0.02
Log Output Level= 0
Friction Slope Method= 1
Unsteady Friction Slope Method= 2
Unsteady Bridges Friction Slope Method= 1
Parabolic Critical Depth
Global Vel Dist=  1 , 1 , 1
Global Log Level= 0
CheckData=True
Encroach Param= -1, 0, 0, 0
BEGIN DESCRIPTION:
Multiple Run
END DESCRIPTION:

--- Caney T15.f01 (steady flow) ---

Flow Title=Multiple
Number of Profiles=7
Profile Names=10-year,25-year,50-year,1pct_min,100-year,1pct_plu,500-year
River Rch & RM= Caney T15,Reach-1,5719
     497     665     802     481     960    1916    1379
River Rch & RM= Caney T15,Reach-1,2220
     824    1134    1394     851    1698    3388    2526
Boundary for River Rch & Prof#=Caney T15,Reach-1,1
Up Type=0
Dn Type=3
Dn Slope=0.005
Boundary for River Rch & Prof#=Caney T15,Reach-1,2
Up Type=0
Dn Type=3
Dn Slope=0.005
Boundary for River Rch & Prof#=Caney T15,Reach-1,3
Up Type=0
Dn Type=3
Dn Slope=0.005
Boundary for River Rch & Prof#=Caney T15,Reach-1,4
Up Type=0
Dn Type=3
Dn Slope=0.005
Boundary for River Rch & Prof#=Caney T15,Reach-1,5
Up Type=0
Dn Type=3
Dn Slope=0.005
Boundary for River Rch & Prof#=Caney T15,Reach-1,6
Up Type=0
Dn Type=3
Dn Slope=0.005
Boundary for River Rch & Prof#=Caney T15,Reach-1,7
Up Type=0
Dn Type=3
Dn Slope=0.005

--- Caney T15.g01 (geometry) ---

Geom Title=Existing Conditions

River Reach=Caney T15,Reach-1
Reach XY= 30
      2758226.00      6900161.00      2758176.39      6900221.68
      2758218.43      6900310.99      2758175.21      6900410.99
      2758225.93      6900531.03      2758224.78      6901000.50
      2758177.22      6901071.51      2758172.45      6901259.53
      2758079.56      6901362.47      2758072.24      6901509.44
      2757928.25      6901766.93      2757922.44      6901909.53
      2757827.67      6902017.05      2757867.93      6902114.31
      2757677.82      6902517.12      2757726.59      6902721.52
      2757676.95      6902776.94      2757676.00      6902961.00
      2757484.14      6903104.94      2757320.17      6903463.30
      2757184.14      6903604.94      2757109.43      6903778.02
      2756852.17      6903983.87      2756620.52      6904255.74
      2756486.32      6904300.83      2756518.21      6904511.10
      2756483.83      6904560.92      2756522.85      6904659.36
      2756428.32      6904755.19      2756276.00      6904811.00

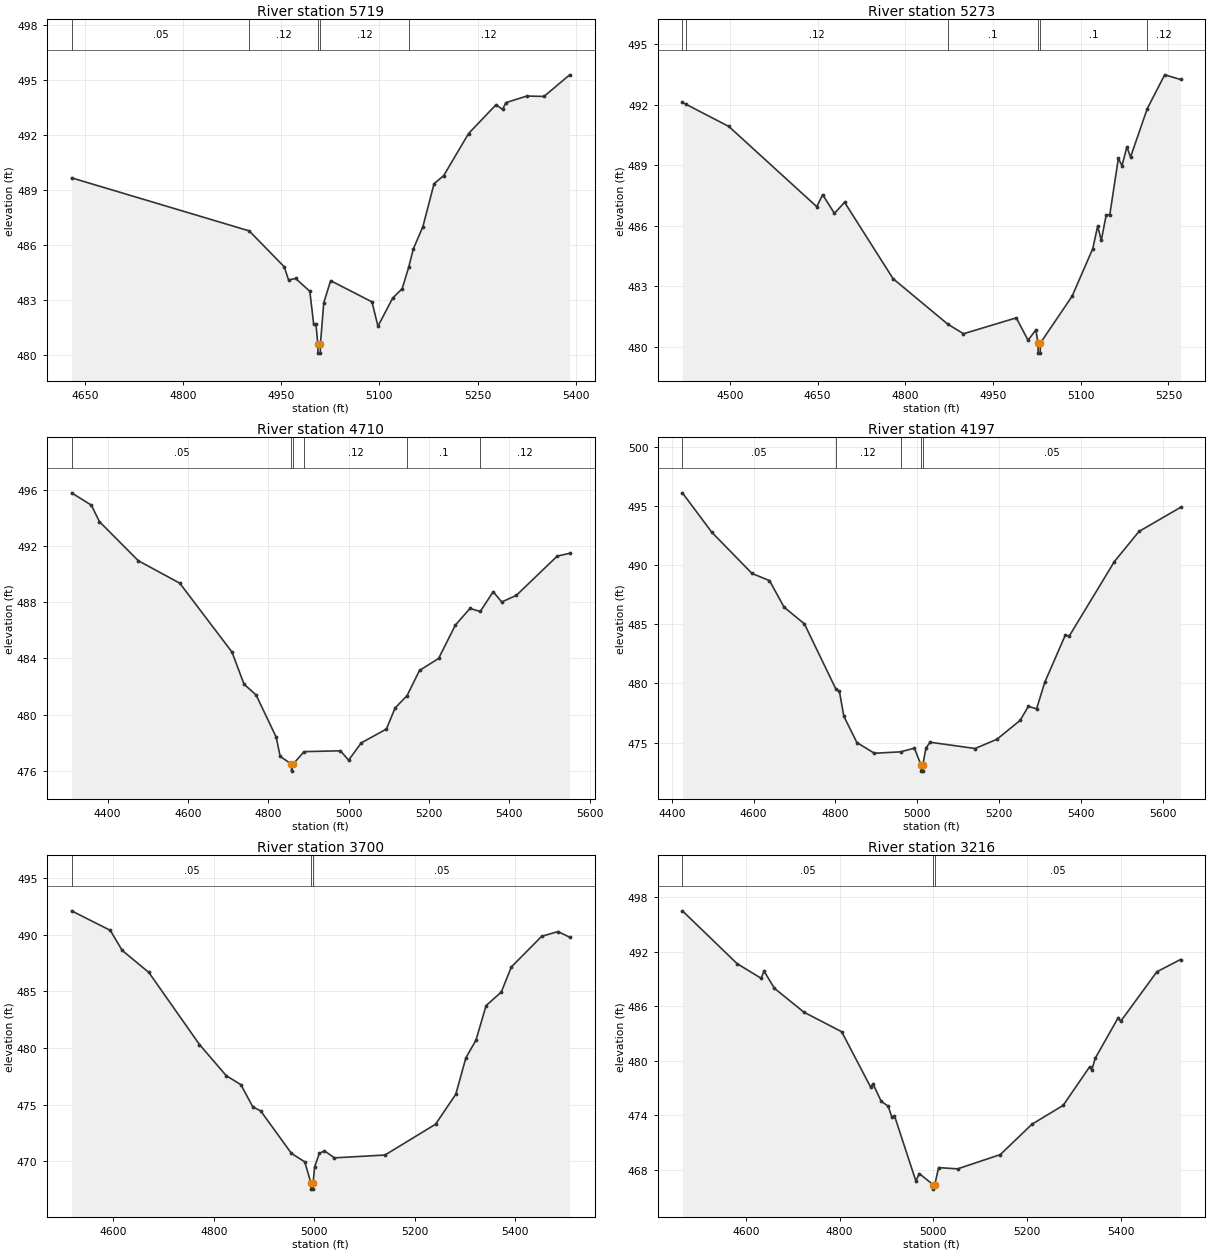
Type RM Length L Ch R = 1,5719,446,446,446
BEGIN DESCRIPTION:
Caney T15 11.0
END DESCRIPTION:
XS GIS Cut Line= 3
      2757850.45      6900050.48      2758191.77      6900194.08
      2758562.69      6900316.84
#Sta/Elev= 30
  4629.7  489.66  4901.1  486.76  4954.6  484.80  4961.2  484.08  4972.0  484.16
  4993.7  483.46  4999.6  481.66  5003.1  481.66  5005.9  480.58  5006.2  480.08
  5009.7  480.08  5009.9  480.58  5015.0  482.83  5025.5  484.04  5088.7  482.88
  5097.8  481.55  5120.3  483.09  5134.8  483.60  5144.7  484.77  5151.9  485.78
  5166.5  487.00  5183.5  489.34  5198.2  489.78  5236.2  492.08  5278.3  493.66
  5288.1  493.40  5293.3  493.77  5325.1  494.13  5351.5  494.11  5390.7  495.29
#Mann=5,-1,0
  4629.7    0.05       0  4901.1    0.12       0  5005.9    0.07       0
  5009.9    0.12       0  5144.7    0.12       0
Bank Sta=5005.9,5009.9
Exp/Cntr=0.3,0.1

Type RM Length L Ch R = 1,5273,563,563,563
BEGIN DESCRIPTION:
Caney T15 10.0
END DESCRIPTION:
XS GIS Cut Line= 3
      2757646.88      6900542.77      2758246.83      6900592.77
      2758446.81      6900442.79
#Sta/Elev= 30
  4418.7  492.12  4425.5  492.01  4498.1  490.92  4648.6  486.94  4658.6  487.54
  4678.7  486.61  4696.1  487.16  4779.1  483.37  4872.5  481.12  4899.5  480.64
  4989.8  481.43  5009.9  480.32  5023.3  480.83  5027.0  480.18  5027.2  479.68
  5030.7  479.68  5031.0  480.18  5085.2  482.50  5120.6  484.86  5129.0  485.98
  5135.2  485.27  5143.6  486.53  5149.8  486.55  5164.4  489.34  5170.6  488.97
  5179.0  489.91  5185.2  489.40  5213.8  491.80  5243.6  493.48  5270.7  493.25
#Mann=6,-1,0
  4418.7    0.05       0  4425.5    0.12       0  4872.5     0.1       0
  5027.0    0.07       0  5031.0     0.1       0  5213.8    0.12       0
Bank Sta=5027,5031
Exp/Cntr=0.3,0.1

Type RM Length L Ch R = 1,4710,513,513,513
BEGIN DESCRIPTION:
Mapping XS ab246b8c
END DESCRIPTION:
XS GIS Cut Line= 4
      2757486.74      6901147.72      2758167.31      6901140.77
      2758386.06      6901074.80      2758562.38      6900794.77
#Sta/Elev= 30
  4310.5  495.81  4359.8  494.93  4379.8  493.76  4476.7  490.97  4579.8  489.37
  4709.8  484.46  4739.8  482.17  4769.8  481.40  4819.8  478.40  4829.8  477.02
  4857.8  476.47  4858.0  475.97  4861.8  476.47  4889.4  477.36  4979.8  477.42
  5000.2  476.75  5031.5  477.98  5094.2  478.97  5115.9  480.47  5145.8  481.36
  5176.7  483.15  5224.2  484.00  5265.9  486.38  5302.4  487.57  5327.8  487.35
  5360.1  488.76  5381.3  488.03  5417.8  488.50  5519.5  491.30  5550.5  491.50
#Mann=6,-1,0
  4310.5    0.05       0  4857.8    0.07       0  4861.8    0.05       0
  4889.4    0.12       0  5145.8     0.1       0  5327.8    0.12       0
Bank Sta=4857.8,4861.8
Exp/Cntr=0.3,0.1

Type RM Length L Ch R = 1,4197,497,497,497
BEGIN DESCRIPTION:
Mapping XS c57c2a45
END DESCRIPTION:
XS GIS Cut Line= 3
      2757486.73      6901399.44      2758014.53      6901597.37
      2758667.35      6901625.15
#Sta/Elev= 30
  4426.1  496.10  4498.2  492.76  4596.2  489.29  4638.9  488.69  4674.5  486.45
  4724.3  485.03  4801.4  479.51  4809.7  479.35  4820.5  477.24  4852.5  475.01
  4895.2  474.11  4959.2  474.23  4993.0  474.54  5009.3  473.10  5009.5  472.60
  5013.0  472.60  5013.3  473.10  5021.3  474.56  5031.3  475.04  5141.4  474.51
  5194.6  475.29  5251.5  476.89  5271.5  478.07  5291.5  477.86  5311.5  480.10
  5361.6  484.08  5371.6  484.02  5481.7  490.30  5541.8  492.84  5643.2  494.87
#Mann=5,-1,0
  4426.1    0.05       0  4801.4    0.12       0  4959.2    0.05       0
  5009.3    0.04       0  5013.3    0.05       0
Bank Sta=5009.3,5013.3
Exp/Cntr=0.3,0.1

Type RM Length L Ch R = 1,3700,484,484,484
BEGIN DESCRIPTION:
Mapping XS 1f2969cc
END DESCRIPTION:
XS GIS Cut Line= 3
      2757378.69      6901846.94      2757803.16      6902024.02
      2758331.42      6902078.66
#Sta/Elev= 30
  4517.1  492.11  4594.0  490.39  4617.8  488.62  4670.9  486.67  4771.6  480.31
  4824.7  477.57  4853.9  476.77  4877.7  474.81  4893.4  474.45  4954.6  470.70
  4981.0  469.96  4993.6  468.05  4993.9  467.55  4997.4  467.55  4997.6  468.05
  5000.7  469.52  5010.0  470.70  5020.1  470.93  5040.2  470.31  5140.7  470.56
  5241.3  473.28  5281.5  475.92  5301.6  479.14  5321.7  480.70  5341.8  483.75
  5372.0  484.94  5392.1  487.16  5452.4  489.86  5484.9  490.28  5508.1  489.78
#Mann=3,-1,0
  4517.1    0.05       0  4993.6    0.04       0  4997.6    0.05       0
Bank Sta=4993.6,4997.6
Exp/Cntr=0.3,0.1

Type RM Length L Ch R = 1,3216,497,497,497
BEGIN DESCRIPTION:
Mapping XS c6dc825d
END DESCRIPTION:
XS GIS Cut Line= 3
      2757238.10      6902234.97      2757704.20      6902453.70
      2758245.84      6902365.17
#Sta/Elev= 30
  4464.4  496.48  4581.3  490.66  4632.4  489.06  4638.8  489.84  4660.9  487.95
  4723.7  485.33  4804.5  483.17  4866.1  477.10  4871.6  477.41  4888.9  475.51
  4903.9  474.97  4911.8  473.74  4917.3  473.92  4962.9  466.74  4970.2  467.56
  4999.4  466.34  4999.6  465.84  5003.4  466.34  5011.5  468.21  5052.0  468.07
  5143.2  469.64  5211.0  472.99  5277.5  475.06  5333.8  479.29  5338.9  479.00
  5345.9  480.24  5395.2  484.73  5400.3  484.31  5477.6  489.77  5528.1  491.12
#Mann=3,-1,0
  4464.4    0.05       0  4999.4    0.04       0  5003.4    0.05       0
Bank Sta=4999.4,5003.4
Exp/Cntr=0.3,0.1

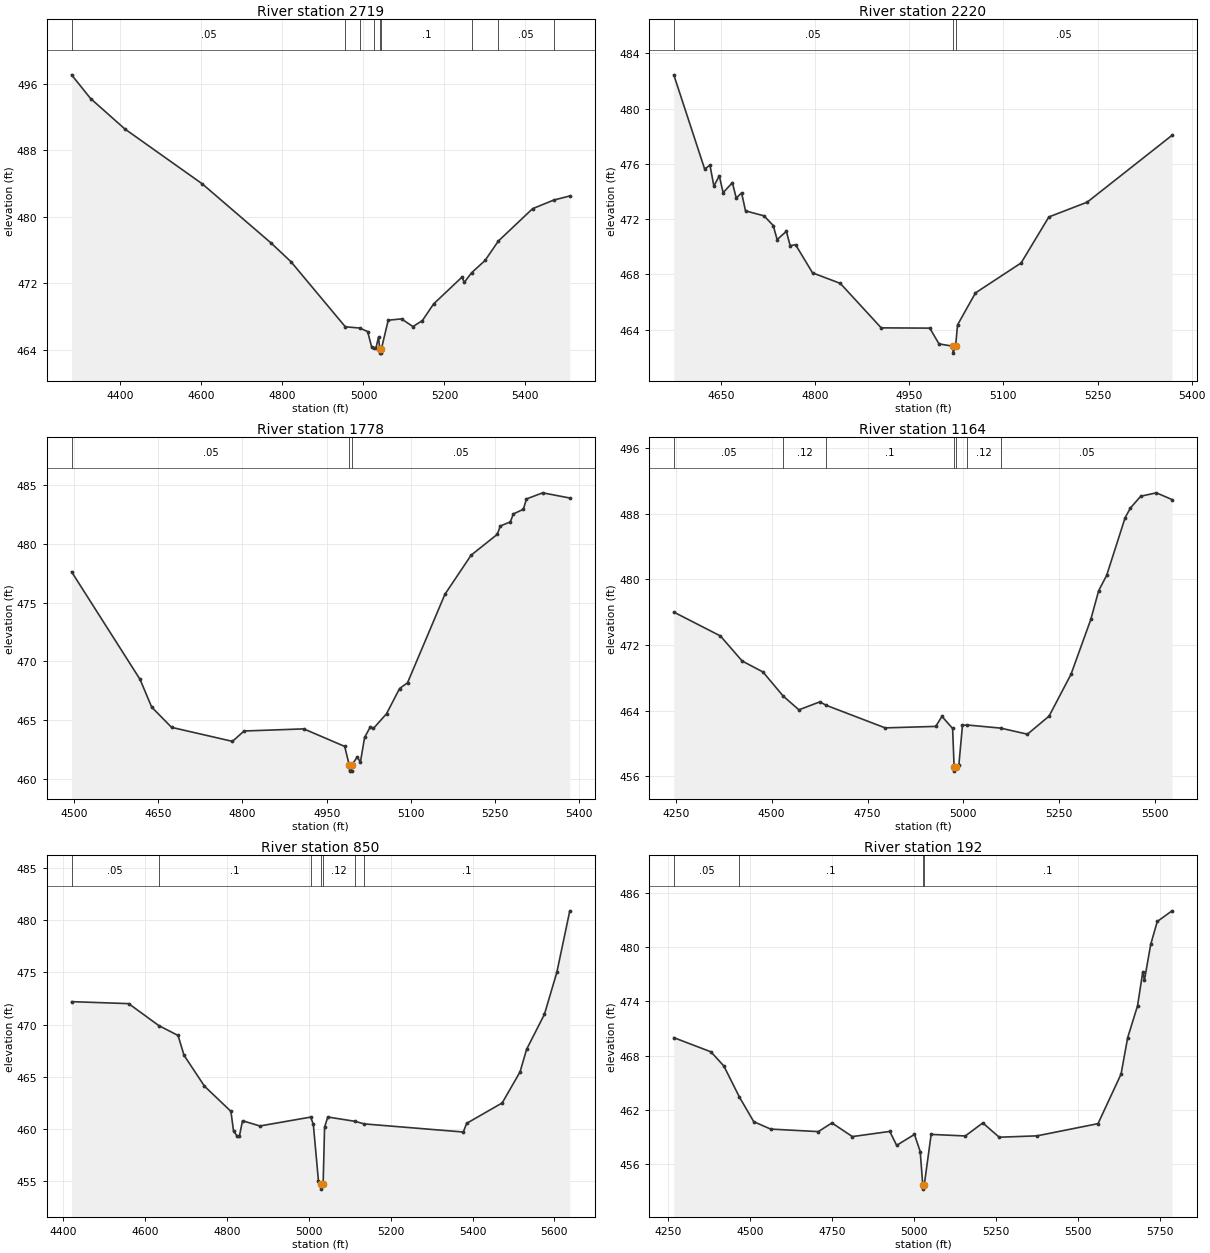
Type RM Length L Ch R = 1,2719,499,499,499
BEGIN DESCRIPTION:
Mapping XS cd2b9f07
END DESCRIPTION:
XS GIS Cut Line= 3
      2757158.42      6902382.31      2757674.91      6902883.61
      2758176.12      6902785.97
#Sta/Elev= 30
  4279.2  497.08  4326.1  494.23  4411.0  490.56  4601.8  483.97  4771.6  476.86
  4821.0  474.60  4955.2  466.77  4990.4  466.62  5010.3  466.20  5020.5  464.30
  5025.9  464.23  5030.6  464.17  5037.2  465.51  5040.3  464.10  5040.6  463.60
  5044.1  463.60  5044.3  464.10  5061.2  467.56  5094.0  467.72  5122.3  466.79
  5145.6  467.52  5173.3  469.52  5243.7  472.76  5248.8  472.10  5267.1  473.27
  5300.4  474.75  5333.3  477.09  5417.8  480.98  5469.8  482.01  5509.6  482.51
#Mann=9,-1,0
  4279.2    0.05       0  4955.2     0.1       0  4990.4    0.05       0
  5025.9     0.1       0  5040.3    0.05       0  5044.3     0.1       0
  5267.1    0.12       0  5333.3    0.05       0  5469.8     0.1       0
Bank Sta=5040.3,5044.3
Exp/Cntr=0.3,0.1

Type RM Length L Ch R = 1,2220,442,442,442
BEGIN DESCRIPTION:
Caney T15 4.0
END DESCRIPTION:
XS GIS Cut Line= 3
      2757076.02      6903011.01      2757426.00      6903261.00
      2757526.00      6903611.00
#Sta/Elev= 30
  4574.6  482.44  4623.7  475.63  4632.3  475.89  4638.5  474.38  4647.1  475.13
  4653.2  473.91  4668.0  474.63  4674.1  473.52  4682.7  473.89  4688.9  472.59
  4718.4  472.23  4733.1  471.53  4739.3  470.51  4754.0  471.11  4760.1  470.07
  4768.7  470.14  4795.8  468.10  4840.0  467.34  4905.2  464.12  4982.6  464.10
  4997.3  462.96  5019.3  462.79  5019.8  462.29  5023.8  462.79  5026.8  464.33
  5055.4  466.65  5128.2  468.82  5172.4  472.15  5233.5  473.22  5368.7  478.06
#Mann=3,-1,0
  4574.6    0.05       0  5019.3    0.04       0  5023.8    0.05       0
Bank Sta=5019.3,5023.8
Exp/Cntr=0.3,0.1

Type RM Length L Ch R = 1,1778,614,614,614
BEGIN DESCRIPTION:
Caney T15 3.0
END DESCRIPTION:
XS GIS Cut Line= 3
      2756875.99      6903210.99      2757176.00      6903611.00
      2757530.20      6903767.86
#Sta/Elev= 30
  4495.7  477.62  4617.6  468.48  4638.4  466.12  4673.8  464.40  4782.2  463.21
  4803.0  464.09  4909.3  464.27  4982.2  462.78  4990.3  461.18  4990.8  460.68
  4994.4  460.68  4994.8  461.18  5004.6  461.90  5010.1  461.43  5017.6  463.54
  5027.9  464.45  5033.4  464.31  5056.7  465.56  5079.9  467.70  5094.1  468.19
  5160.7  475.71  5207.3  479.03  5253.9  480.80  5259.3  481.51  5277.2  481.86
  5282.6  482.54  5300.4  482.93  5305.9  483.81  5334.8  484.33  5383.1  483.89
#Mann=3,-1,0
  4495.7    0.05       0  4990.3    0.04       0  4994.8    0.05       0
Bank Sta=4990.3,4994.8
Exp/Cntr=0.3,0.1

Type RM Length L Ch R = 1,1164,314,314,314
BEGIN DESCRIPTION:
Caney T15 2.0
END DESCRIPTION:
XS GIS Cut Line= 3
      2756470.40      6903383.65      2756824.50      6904050.46
      2757351.03      6904186.01
#Sta/Elev= 30
  4245.0  476.01  4366.5  473.10  4423.2  470.05  4477.5  468.71  4530.1  465.78
  4571.1  464.10  4625.7  465.07  4642.4  464.65  4795.9  461.90  4927.8  462.08
  4944.0  463.30  4971.8  461.83  4975.7  457.13  4976.2  456.63  4980.3  457.13
  4988.1  457.40  4997.5  462.21  5010.2  462.25  5097.1  461.87  5166.8  461.13
  5223.2  463.33  5280.4  468.43  5332.0  475.11  5352.6  478.63  5373.3  480.48
  5421.5  487.51  5435.2  488.69  5462.3  490.13  5503.0  490.54  5543.7  489.72
#Mann=7,-1,0
  4245.0    0.05       0  4530.1    0.12       0  4642.4     0.1       0
  4975.7    0.07       0  4980.3     0.1       0  5010.2    0.12       0
  5097.1    0.05       0
Bank Sta=4975.7,4980.3
Exp/Cntr=0.3,0.1

Type RM Length L Ch R = 1,850,658,658,658
BEGIN DESCRIPTION:
Mapping XS 68b10c0b
END DESCRIPTION:
XS GIS Cut Line= 3
      2756265.50      6903796.79      2756609.26      6904255.14
      2757173.79      6904566.84
#Sta/Elev= 30
  4419.8  472.19  4559.3  472.00  4633.3  469.89  4680.1  468.95  4694.7  467.05
  4744.7  464.09  4809.3  461.68  4815.6  459.82  4823.9  459.33  4830.1  459.33
  4837.6  460.78  4880.1  460.28  5004.2  461.13  5010.7  460.44  5023.3  454.99
  5030.1  454.73  5030.6  454.23  5034.7  454.73  5038.2  460.17  5046.1  461.14
  5113.4  460.72  5134.7  460.48  5377.4  459.70  5385.4  460.53  5472.4  462.49
  5516.0  465.46  5532.0  467.62  5575.5  470.97  5605.9  474.99  5637.6  480.89
#Mann=7,-1,0
  4419.8    0.05       0  4633.3     0.1       0  5004.2    0.12       0
  5030.1    0.07       0  5034.7    0.12       0  5113.4    0.05       0
  5134.7     0.1       0
Bank Sta=5030.1,5034.7
Exp/Cntr=0.3,0.1

Type RM Length L Ch R = 1,192,0,0,0
BEGIN DESCRIPTION:
Caney T15 1.0
END DESCRIPTION:
XS GIS Cut Line= 3
      2756251.01      6904036.03      2756446.14      6904741.24
      2757230.76      6904814.16
#Sta/Elev= 30
  4268.3  469.99  4381.6  468.42  4421.1  466.85  4468.3  463.43  4512.1  460.70
  4563.5  459.88  4709.2  459.60  4750.6  460.56  4813.0  459.05  4927.1  459.62
  4948.1  458.08  5002.4  459.29  5019.9  457.40  5027.6  453.74  5028.1  453.24
  5032.4  453.74  5053.3  459.29  5157.5  459.12  5210.8  460.56  5261.0  458.98
  5376.1  459.13  5562.3  460.48  5632.6  465.96  5652.7  469.98  5682.8  473.50
  5698.8  477.26  5703.9  476.35  5723.0  480.29  5743.0  482.83  5788.0  484.01
#Mann=4,-1,0
  4268.3    0.05       0  4468.3     0.1       0  5027.6    0.07       0
  5032.4     0.1       0
Bank Sta=5027.6,5032.4
Exp/Cntr=0.3,0.1

Chan Stop Cuts=-1