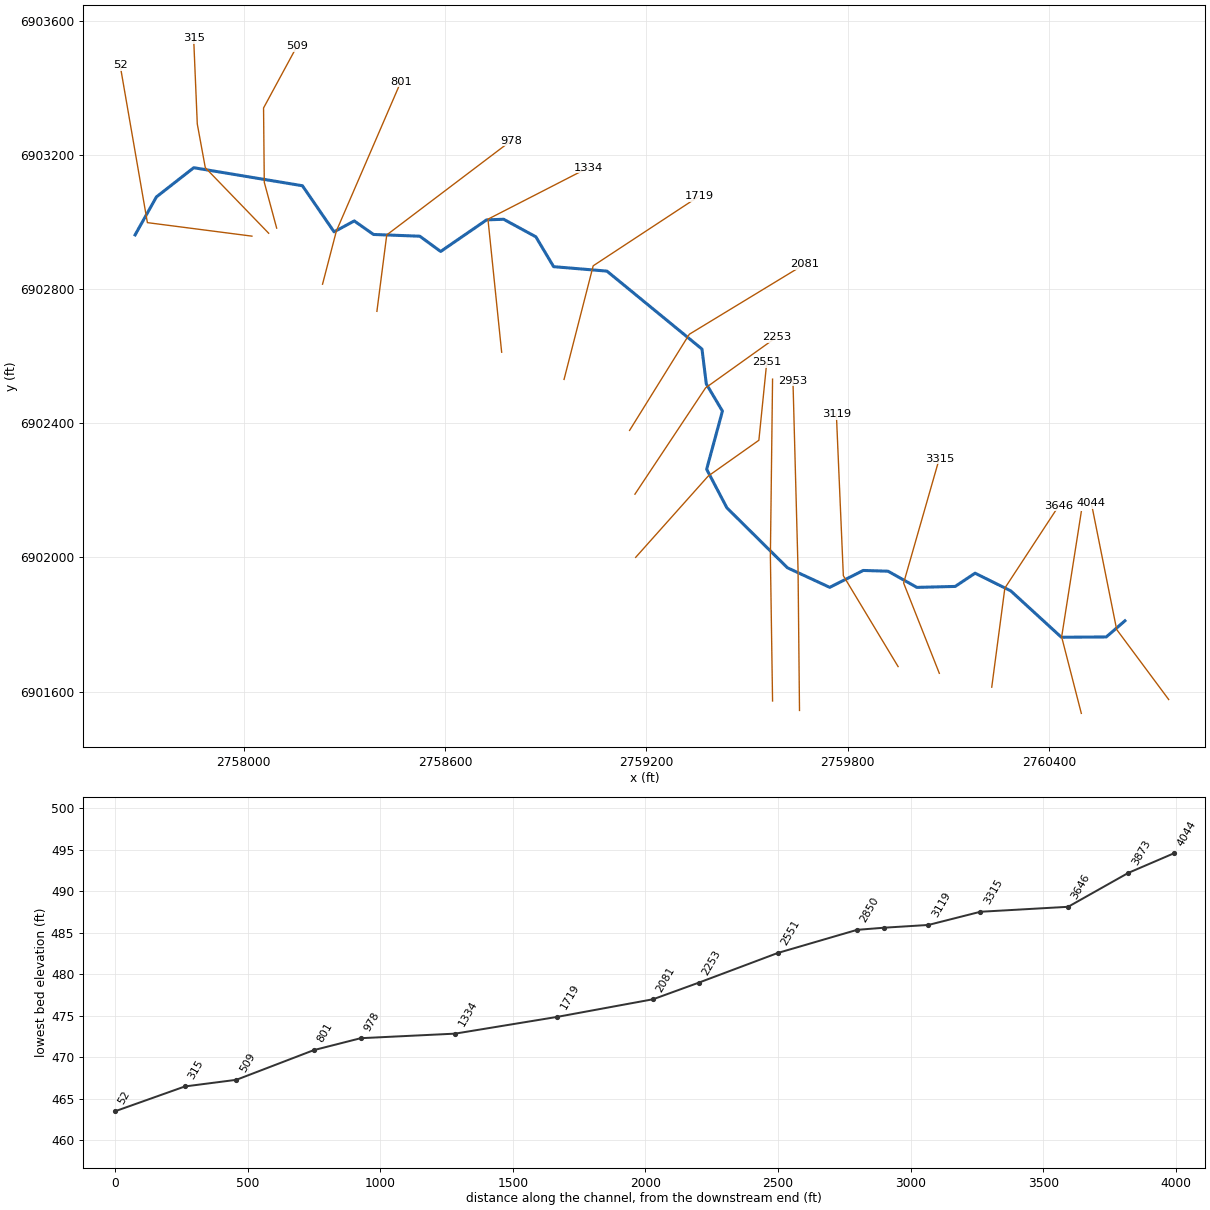
--- Caney T15_1.prj (project) ---

Proj Title=Caney T15_1 Base Level Engineering
Current Plan=p01
Default Exp/Contr=0.3,0.1
English Units
Geom File=g01
Flow File=f01
Plan File=p01
BEGIN DESCRIPTION:
Caney T15_1
END DESCRIPTION:

--- Caney T15_1.p01 (plan) ---

Plan Title=Multiple Run
Short Identifier=Multiple
Geom File=g01
Flow File=f01
Subcritical Flow
K Sum by GR= 0
Std Step Tol= 0.01
Critical Tol= 0.01
Num of Std Step Trials= 20
Max Error Tol= 0.3
Flow Tol Ratio= 0.001
Split Flow NTrial= 30
Split Flow Tol= 0.02
Split Flow Ratio= 0.02
Log Output Level= 0
Friction Slope Method= 1
Unsteady Friction Slope Method= 2
Unsteady Bridges Friction Slope Method= 1
Parabolic Critical Depth
Global Vel Dist=  1 , 1 , 1
Global Log Level= 0
CheckData=True
Encroach Param= -1, 0, 0, 0
BEGIN DESCRIPTION:
Multiple Run
END DESCRIPTION:

--- Caney T15_1.f01 (steady flow) ---

Flow Title=Multiple
Number of Profiles=7
Profile Names=10-year,25-year,50-year,1pct_min,100-year,1pct_plu,500-year
River Rch & RM= Caney T15_1,Reach-1,4044
     398     525     627     373     744    1485    1050
Boundary for River Rch & Prof#=Caney T15_1,Reach-1,1
Up Type=0
Dn Type=3
Dn Slope=0.005
Boundary for River Rch & Prof#=Caney T15_1,Reach-1,2
Up Type=0
Dn Type=3
Dn Slope=0.005
Boundary for River Rch & Prof#=Caney T15_1,Reach-1,3
Up Type=0
Dn Type=3
Dn Slope=0.005
Boundary for River Rch & Prof#=Caney T15_1,Reach-1,4
Up Type=0
Dn Type=3
Dn Slope=0.005
Boundary for River Rch & Prof#=Caney T15_1,Reach-1,5
Up Type=0
Dn Type=3
Dn Slope=0.005
Boundary for River Rch & Prof#=Caney T15_1,Reach-1,6
Up Type=0
Dn Type=3
Dn Slope=0.005
Boundary for River Rch & Prof#=Caney T15_1,Reach-1,7
Up Type=0
Dn Type=3
Dn Slope=0.005

--- Caney T15_1.g01 (geometry) ---

Geom Title=Existing Conditions

River Reach=Caney T15_1,Reach-1
Reach XY= 30
      2760626.00      6901811.00      2760570.21      6901762.88
      2760436.44      6901762.03      2760285.68      6901900.25
      2760179.32      6901952.96      2760120.14      6901913.45
      2760005.87      6901910.61      2759920.02      6901958.83
      2759846.09      6901961.08      2759746.17      6901910.71
      2759619.94      6901969.14      2759439.62      6902147.79
      2759379.34      6902262.72      2759426.40      6902436.00
      2759378.36      6902516.98      2759365.49      6902620.81
      2759082.19      6902853.18      2758923.32      6902866.40
      2758870.38      6902955.38      2758774.29      6903007.70
      2758723.71      6903005.90      2758586.71      6902911.72
      2758524.44      6902957.18      2758386.44      6902962.39
      2758329.21      6903002.71      2758269.05      6902970.18
      2758174.75      6903107.54      2757850.88      6903161.32
      2757739.56      6903074.26      2757676.00      6902961.00

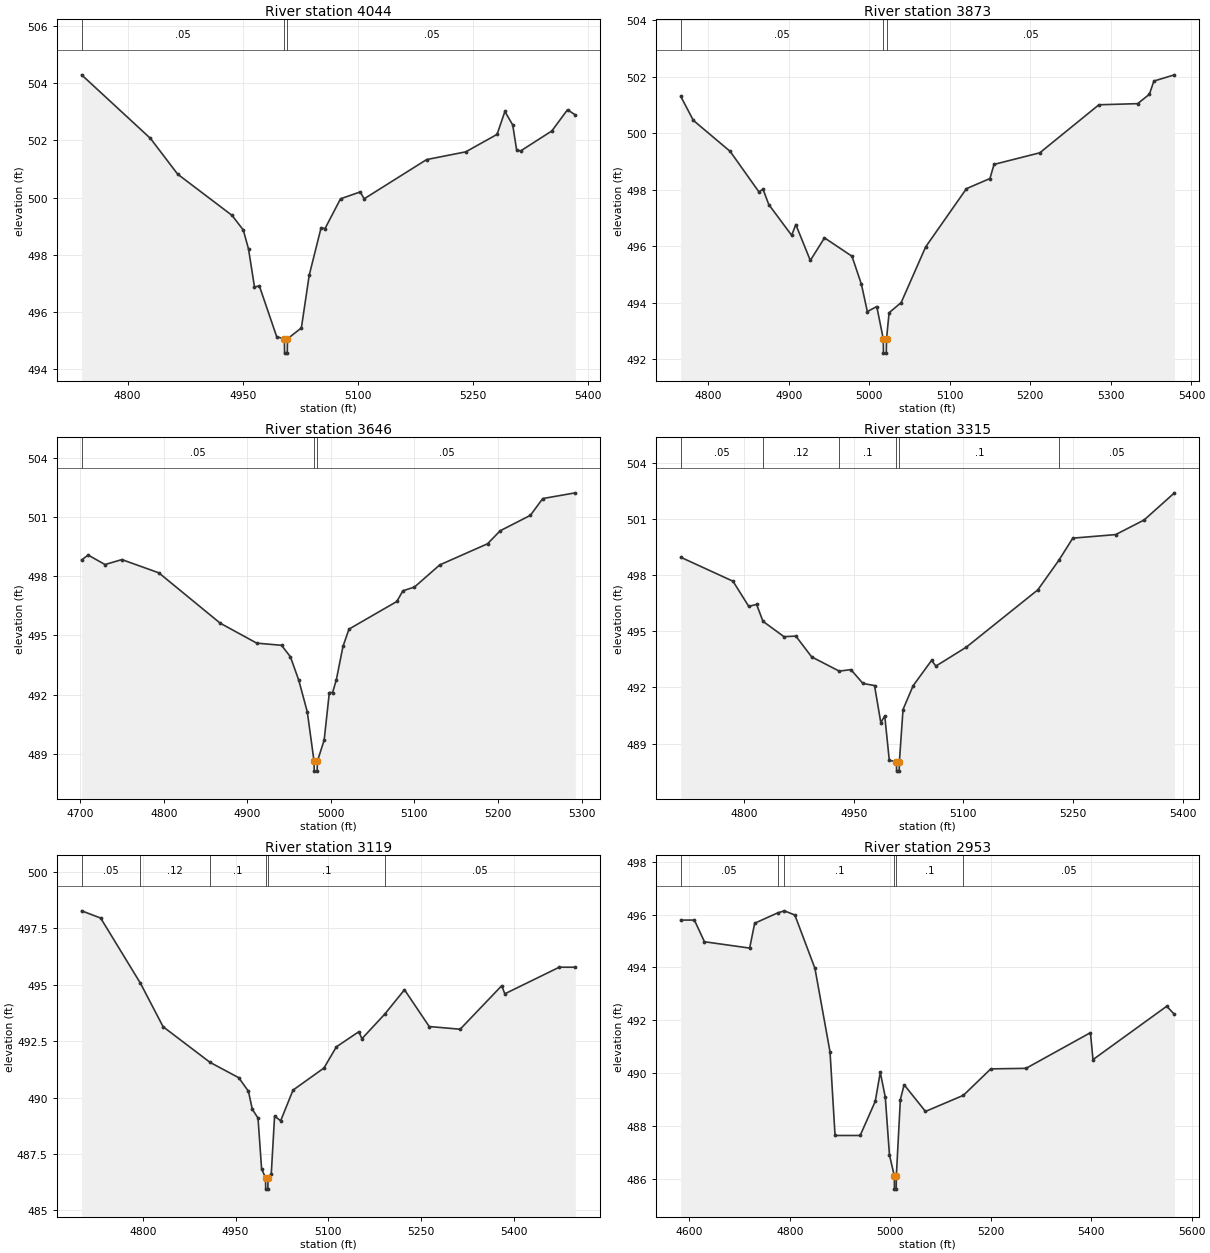
Type RM Length L Ch R = 1,4044,171,171,171
BEGIN DESCRIPTION:
Caney T15_1 8.0
END DESCRIPTION:
XS GIS Cut Line= 3
      2760756.35      6901576.41      2760601.29      6901785.11
      2760525.99      6902161.04
#Sta/Elev= 30
  4740.0  504.29  4829.7  502.07  4865.2  500.82  4936.1  499.38  4950.7  498.87
  4957.5  498.21  4965.3  496.88  4971.6  496.92  4994.3  495.14  5004.3  495.07
  5004.5  494.57  5008.0  494.57  5008.3  495.07  5026.4  495.45  5036.6  497.29
  5052.1  498.95  5057.2  498.92  5077.4  499.96  5103.1  500.20  5108.2  499.96
  5189.6  501.33  5240.6  501.60  5281.4  502.21  5291.6  503.01  5301.8  502.54
  5306.9  501.67  5312.0  501.63  5352.8  502.33  5373.2  503.07  5383.4  502.89
#Mann=3,-1,0
  4740.0    0.05       0  5004.3    0.04       0  5008.3    0.05       0
Bank Sta=5004.3,5008.3
Exp/Cntr=0.3,0.1

Type RM Length L Ch R = 1,3873,227,227,227
BEGIN DESCRIPTION:
Mapping XS 52fcc353
END DESCRIPTION:
XS GIS Cut Line= 3
      2760495.95      6901535.14      2760437.35      6901763.01
      2760495.93      6902136.15
#Sta/Elev= 30
  4765.9  501.31  4781.5  500.46  4827.3  499.36  4862.9  497.93  4868.1  498.02
  4875.2  497.48  4903.6  496.39  4908.8  496.77  4926.8  495.50  4944.4  496.30
  4978.5  495.65  4990.3  494.65  4997.6  493.69  5009.3  493.87  5017.4  492.72
  5017.6  492.22  5021.1  492.22  5021.4  492.72  5024.6  493.65  5039.6  494.01
  5070.0  495.98  5120.6  498.04  5149.8  498.40  5154.9  498.90  5211.7  499.31
  5285.1  501.01  5333.2  501.05  5347.7  501.38  5353.4  501.85  5378.9  502.07
#Mann=3,-1,0
  4765.9    0.05       0  5017.4    0.04       0  5021.4    0.05       0
Bank Sta=5017.4,5021.4
Exp/Cntr=0.3,0.1

Type RM Length L Ch R = 1,3646,331,331,331
BEGIN DESCRIPTION:
Mapping XS 87f09c2a
END DESCRIPTION:
XS GIS Cut Line= 3
      2760229.02      6901613.25      2760268.08      6901908.41
      2760428.69      6902153.67
#Sta/Elev= 30
  4701.7  498.82  4709.5  499.07  4729.7  498.59  4749.9  498.84  4794.1  498.17
  4867.6  495.62  4911.3  494.61  4941.0  494.50  4951.6  493.92  4961.7  492.72
  4971.8  491.13  4979.9  488.63  4980.1  488.13  4983.6  488.13  4983.9  488.63
  4992.0  489.70  4998.2  492.11  5002.1  492.11  5006.6  492.76  5014.5  494.44
  5021.7  495.32  5079.0  496.72  5086.2  497.26  5100.1  497.45  5130.3  498.57
  5187.5  499.64  5202.7  500.30  5238.8  501.08  5253.6  501.93  5292.6  502.22
#Mann=3,-1,0
  4701.7    0.05       0  4979.9    0.04       0  4983.9    0.05       0
Bank Sta=4979.9,4983.9
Exp/Cntr=0.3,0.1

Type RM Length L Ch R = 1,3315,196,196,196
BEGIN DESCRIPTION:
Mapping XS 34dd8690
END DESCRIPTION:
XS GIS Cut Line= 3
      2760072.78      6901654.48      2759966.43      6901923.60
      2760072.77      6902294.69
#Sta/Elev= 30
  4713.4  498.95  4784.9  497.67  4806.4  496.33  4817.2  496.43  4825.9  495.53
  4854.6  494.71  4870.9  494.74  4892.5  493.63  4930.2  492.87  4946.2  492.95
  4962.7  492.21  4978.5  492.10  4987.1  490.12  4992.5  490.48  4998.7  488.11
  5008.5  488.03  5008.7  487.53  5012.2  487.53  5012.5  488.03  5017.5  490.82
  5031.3  492.09  5056.5  493.44  5062.5  493.14  5104.1  494.15  5201.9  497.21
  5231.2  498.82  5249.7  499.97  5308.4  500.16  5347.3  500.94  5388.8  502.39
#Mann=6,-1,0
  4713.4    0.05       0  4825.9    0.12       0  4930.2     0.1       0
  5008.5    0.07       0  5012.5     0.1       0  5231.2    0.05       0
Bank Sta=5008.5,5012.5
Exp/Cntr=0.3,0.1

Type RM Length L Ch R = 1,3119,166,166,166
BEGIN DESCRIPTION:
Mapping XS 6243dfc5
END DESCRIPTION:
XS GIS Cut Line= 3
      2759949.92      6901674.60      2759786.75      6901945.39
      2759765.96      6902426.99
#Sta/Elev= 30
  4701.0  498.28  4731.8  497.96  4796.1  495.07  4832.8  493.14  4908.7  491.56
  4955.1  490.88  4970.7  490.28  4977.0  489.48  4986.2  489.09  4992.0  486.84
  4998.4  486.44  4998.6  485.94  5002.1  485.94  5002.4  486.44  5007.6  486.60
  5013.0  489.18  5022.8  488.97  5042.8  490.33  5092.8  491.31  5112.9  492.25
  5149.2  492.92  5154.2  492.61  5191.1  493.70  5223.0  494.78  5263.0  493.15
  5313.0  493.03  5380.2  494.96  5385.2  494.60  5473.2  495.78  5499.2  495.78
#Mann=6,-1,0
  4701.0    0.05       0  4796.1    0.12       0  4908.7     0.1       0
  4998.4    0.07       0  5002.4     0.1       0  5191.1    0.05       0
Bank Sta=4998.4,5002.4
Exp/Cntr=0.3,0.1

Type RM Length L Ch R = 1,2953,103,103,103
BEGIN DESCRIPTION:
Mapping XS 4822a501
END DESCRIPTION:
XS GIS Cut Line= 3
      2759656.10      6901543.85      2759651.76      6901962.67
      2759636.59      6902526.42
#Sta/Elev= 30
  4583.0  495.79  4610.2  495.79  4630.2  494.97  4720.2  494.73  4730.2  495.67
  4775.7  496.06  4789.3  496.14  4810.2  495.98  4850.2  493.96  4880.2  490.80
  4890.2  487.64  4940.2  487.64  4970.2  488.93  4980.2  490.03  4990.2  489.09
  4998.5  486.90  5008.2  486.11  5008.4  485.61  5011.9  485.61  5012.2  486.11
  5020.2  489.00  5027.7  489.56  5070.2  488.55  5145.7  489.16  5200.2  490.16
  5270.3  490.18  5398.6  491.53  5403.6  490.51  5550.4  492.53  5565.8  492.22
#Mann=6,-1,0
  4583.0    0.05       0  4775.7    0.12       0  4789.3     0.1       0
  5008.2    0.07       0  5012.2     0.1       0  5145.7    0.05       0
Bank Sta=5008.2,5012.2
Exp/Cntr=0.3,0.1

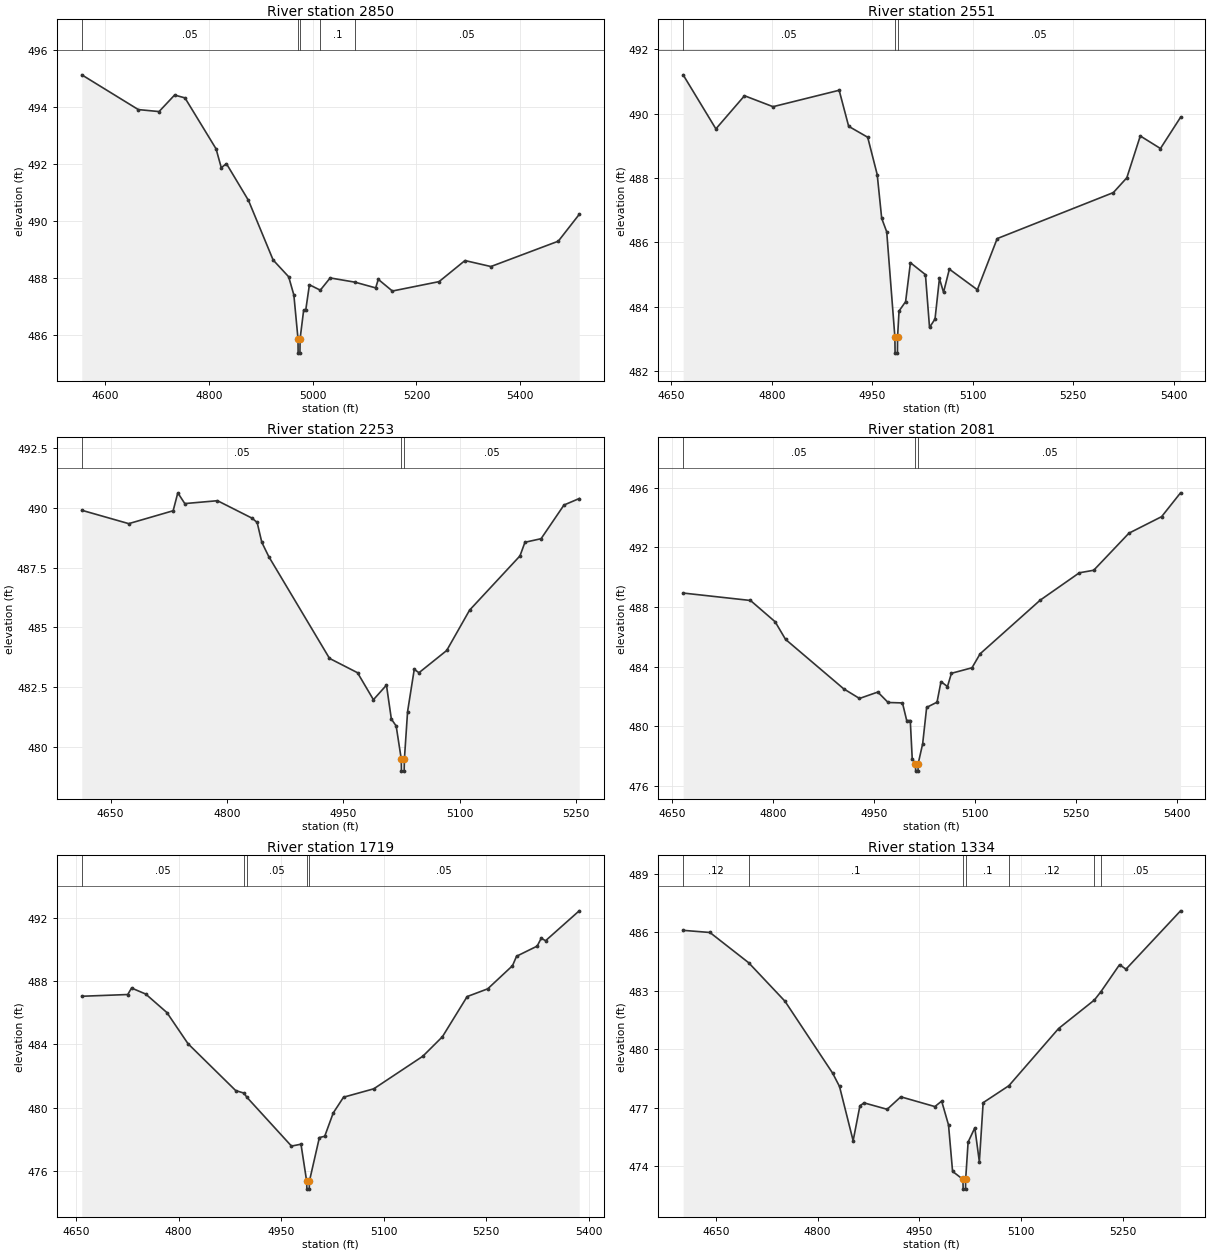
Type RM Length L Ch R = 1,2850,299,299,299
BEGIN DESCRIPTION:
Mapping XS f19e6f77
END DESCRIPTION:
XS GIS Cut Line= 3
      2759575.81      6901572.05      2759569.30      6902003.90
      2759575.81      6902531.26
#Sta/Elev= 30
  4554.7  495.12  4663.7  493.90  4703.7  493.83  4733.7  494.41  4753.7  494.31
  4813.7  492.52  4823.7  491.86  4833.7  492.00  4876.2  490.71  4923.7  488.62
  4953.7  488.03  4963.7  487.39  4971.7  485.85  4971.9  485.35  4975.4  485.35
  4975.7  485.85  4982.6  486.86  4986.6  486.86  4993.7  487.75  5014.7  487.56
  5033.7  487.99  5081.8  487.84  5121.5  487.64  5126.5  487.94  5153.7  487.53
  5243.7  487.86  5293.7  488.60  5343.7  488.39  5473.7  489.28  5514.0  490.22
#Mann=5,-1,0
  4554.7    0.05       0  4971.7    0.04       0  4975.7    0.05       0
  5014.7     0.1       0  5081.8    0.05       0
Bank Sta=4971.7,4975.7
Exp/Cntr=0.3,0.1

Type RM Length L Ch R = 1,2551,298,298,298
BEGIN DESCRIPTION:
Mapping XS 0e1f70f5
END DESCRIPTION:
XS GIS Cut Line= 4
      2759167.86      6902000.12      2759383.97      6902242.27
      2759535.01      6902349.04      2759558.45      6902580.82
#Sta/Elev= 30
  4667.5  491.21  4716.4  489.53  4759.1  490.56  4801.7  490.22  4900.4  490.73
  4914.6  489.61  4943.0  489.27  4957.2  488.11  4963.9  486.75  4971.4  486.33
  4983.6  483.06  4983.9  482.56  4987.4  482.56  4987.6  483.06  4989.8  483.87
  4999.6  484.16  5006.8  485.37  5029.2  485.00  5035.3  483.36  5043.5  483.62
  5050.1  484.88  5056.2  484.45  5064.9  485.17  5106.7  484.53  5136.3  486.12
  5309.7  487.55  5329.8  488.01  5349.9  489.31  5380.0  488.92  5410.0  489.89
#Mann=3,-1,0
  4667.5    0.05       0  4983.6    0.04       0  4987.6    0.05       0
Bank Sta=4983.6,4987.6
Exp/Cntr=0.3,0.1

Type RM Length L Ch R = 1,2253,172,172,172
BEGIN DESCRIPTION:
Mapping XS c9ce85e1
END DESCRIPTION:
XS GIS Cut Line= 3
      2759165.65      6902188.36      2759376.16      6902505.20
      2759588.06      6902656.56
#Sta/Elev= 30
  4612.9  489.90  4673.4  489.34  4730.6  489.88  4736.6  490.63  4745.6  490.18
  4787.7  490.30  4832.2  489.57  4838.8  489.39  4844.8  488.56  4853.8  487.96
  4932.0  483.70  4968.1  483.10  4988.6  481.97  5005.4  482.58  5011.7  481.16
  5017.9  480.87  5024.5  479.48  5024.7  478.98  5028.2  478.98  5028.5  479.48
  5032.6  481.47  5041.2  483.24  5047.3  483.10  5083.0  484.03  5112.5  485.72
  5177.4  487.99  5183.8  488.56  5204.6  488.71  5234.1  490.12  5253.7  490.39
#Mann=3,-1,0
  4612.9    0.05       0  5024.5    0.04       0  5028.5    0.05       0
Bank Sta=5024.5,5028.5
Exp/Cntr=0.3,0.1

Type RM Length L Ch R = 1,2081,362,362,362
BEGIN DESCRIPTION:
Mapping XS 99b1918d
END DESCRIPTION:
XS GIS Cut Line= 3
      2759149.76      6902378.54      2759327.69      6902664.96
      2759670.57      6902873.29
#Sta/Elev= 30
  4666.4  488.94  4766.4  488.44  4803.0  487.01  4818.4  485.83  4904.7  482.51
  4928.2  481.86  4955.4  482.29  4970.7  481.59  4992.0  481.56  4998.3  480.38
  5003.6  480.38  5006.5  477.80  5011.3  477.48  5011.6  476.98  5015.1  476.98
  5015.3  477.48  5022.0  478.82  5027.9  481.26  5043.3  481.61  5049.2  482.99
  5058.8  482.66  5064.7  483.55  5095.2  483.92  5107.3  484.86  5196.4  488.46
  5254.6  490.30  5275.9  490.47  5328.2  492.96  5376.7  494.07  5404.8  495.67
#Mann=3,-1,0
  4666.4    0.05       0  5011.3    0.04       0  5015.3    0.05       0
Bank Sta=5011.3,5015.3
Exp/Cntr=0.3,0.1

Type RM Length L Ch R = 1,1719,385,385,385
BEGIN DESCRIPTION:
Mapping XS ae69c77f
END DESCRIPTION:
XS GIS Cut Line= 3
      2758954.43      6902530.44      2759041.23      6902868.95
      2759357.10      6903076.65
#Sta/Elev= 30
  4658.3  487.04  4725.5  487.15  4731.1  487.56  4751.8  487.18  4782.8  486.01
  4813.7  484.04  4883.4  481.08  4895.4  480.92  4899.9  480.65  4965.0  477.57
  4978.9  477.69  4987.2  475.35  4987.5  474.85  4991.0  474.85  4991.2  475.35
  5005.8  478.11  5013.6  478.19  5026.0  479.66  5041.1  480.66  5085.3  481.19
  5157.1  483.25  5185.7  484.48  5221.9  487.02  5252.0  487.51  5288.2  488.97
  5294.2  489.57  5324.3  490.21  5330.3  490.71  5336.6  490.55  5385.8  492.44
#Mann=5,-1,0
  4658.3    0.05       0  4895.4    0.12       0  4899.9    0.05       0
  4987.2    0.04       0  4991.2    0.05       0
Bank Sta=4987.2,4991.2
Exp/Cntr=0.3,0.1

Type RM Length L Ch R = 1,1334,356,356,356
BEGIN DESCRIPTION:
Caney T15_1 3.0
END DESCRIPTION:
XS GIS Cut Line= 3
      2758768.45      6902611.56      2758727.64      6903007.86
      2759026.03      6903161.02
#Sta/Elev= 30
  4601.6  486.09  4641.2  485.98  4698.3  484.43  4751.8  482.46  4822.2  478.77
  4832.3  478.09  4852.4  475.31  4862.4  477.10  4868.5  477.25  4902.6  476.92
  4922.7  477.56  4973.0  477.06  4983.0  477.34  4993.1  476.12  4999.1  473.74
  5014.4  473.33  5014.7  472.83  5018.2  472.83  5018.4  473.33  5022.0  475.24
  5031.9  475.97  5038.6  474.23  5044.2  477.26  5082.2  478.13  5155.5  481.06
  5208.3  482.52  5218.0  482.95  5245.4  484.33  5254.9  484.10  5335.4  487.09
#Mann=7,-1,0
  4601.6    0.12       0  4698.3     0.1       0  5014.4    0.07       0
  5018.4     0.1       0  5082.2    0.12       0  5208.3     0.1       0
  5218.0    0.05       0
Bank Sta=5014.4,5018.4
Exp/Cntr=0.3,0.1

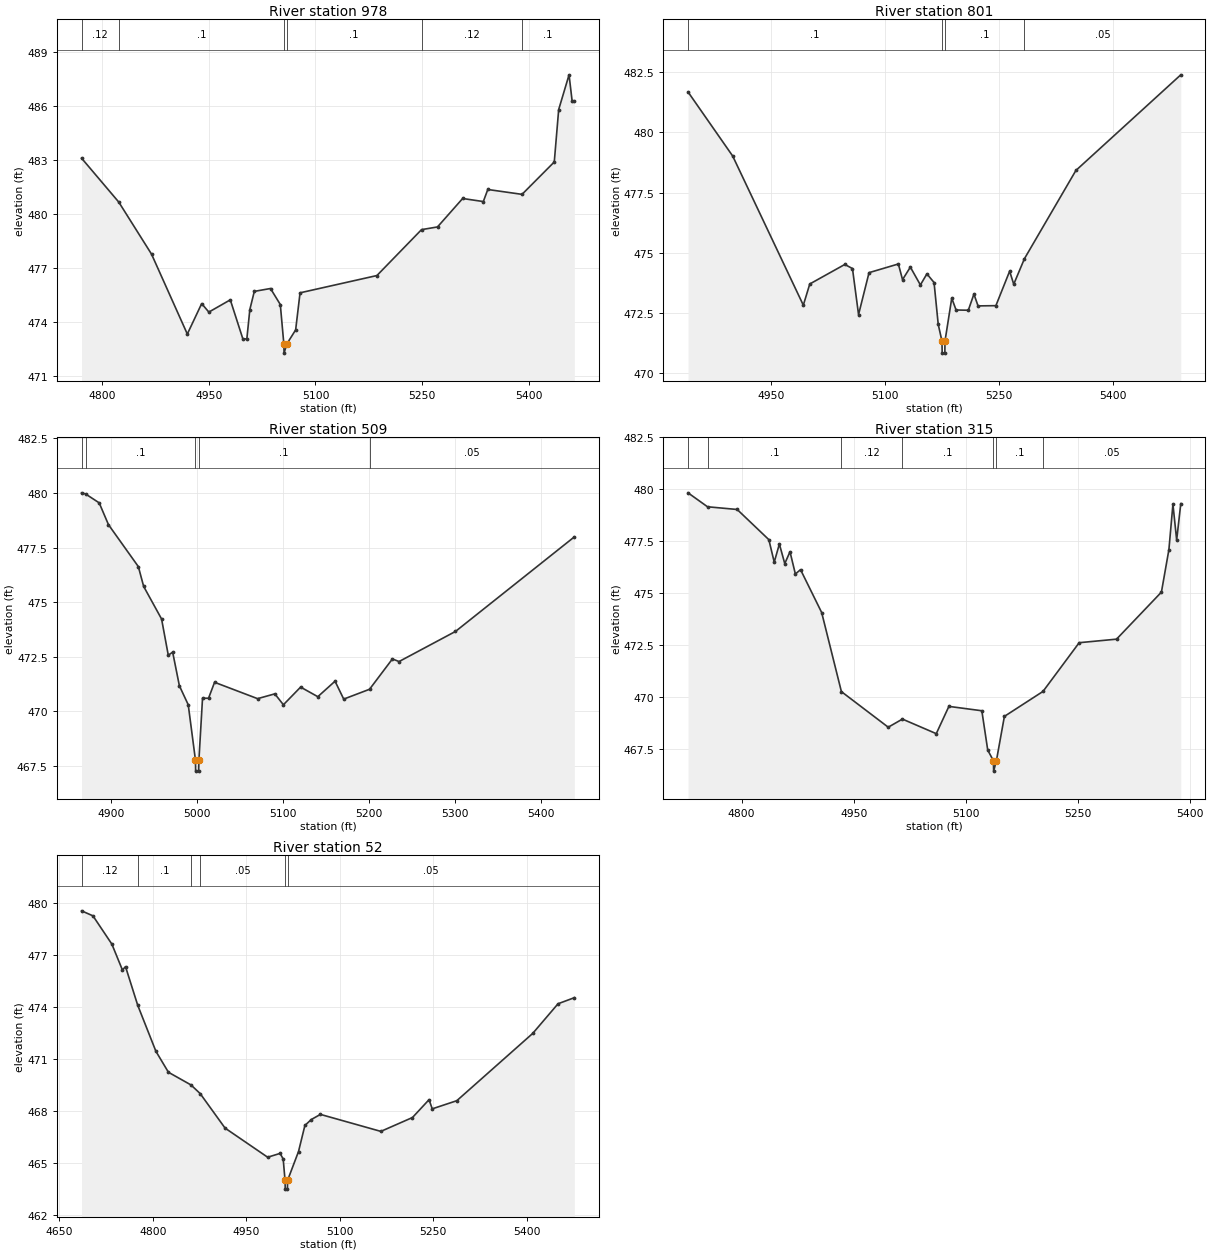
Type RM Length L Ch R = 1,978,177,177,177
BEGIN DESCRIPTION:
Caney T15_1 2.0
END DESCRIPTION:
XS GIS Cut Line= 3
      2758396.69      6902733.27      2758426.00      6902961.00
      2758796.01      6903241.14
#Sta/Elev= 30
  4770.7  483.11  4823.1  480.67  4869.2  477.78  4919.6  473.34  4939.8  475.03
  4949.9  474.56  4980.1  475.24  4997.8  473.07  5003.4  473.07  5007.6  474.70
  5013.9  475.71  5036.7  475.87  5050.5  474.98  5055.5  472.78  5055.8  472.28
  5059.5  472.78  5072.1  473.57  5078.3  475.63  5186.5  476.59  5249.3  479.14
  5271.8  479.29  5307.2  480.87  5336.3  480.70  5342.6  481.37  5390.8  481.10
  5436.2  482.90  5442.4  485.81  5457.0  487.74  5461.3  486.29  5464.4  486.29
#Mann=6,-1,0
  4770.7    0.12       0  4823.1     0.1       0  5055.5    0.07       0
  5059.5     0.1       0  5249.3    0.12       0  5390.8     0.1       0
Bank Sta=5055.5,5059.5
Exp/Cntr=0.3,0.1

Type RM Length L Ch R = 1,801,292,292,292
BEGIN DESCRIPTION:
Mapping XS 2d66b450
END DESCRIPTION:
XS GIS Cut Line= 3
      2758234.64      6902814.13      2758275.88      6902972.57
      2758468.23      6903417.78
#Sta/Elev= 30
  4840.4  481.68  4899.2  479.02  4992.2  472.83  5000.7  473.71  5046.8  474.52
  5056.9  474.35  5064.9  472.44  5078.7  474.18  5117.3  474.54  5122.8  473.89
  5133.1  474.41  5146.3  473.67  5154.9  474.13  5164.3  473.77  5169.8  472.03
  5174.7  471.34  5175.0  470.84  5178.5  470.84  5178.7  471.34  5187.6  473.12
  5193.3  472.63  5209.4  472.62  5216.8  473.29  5222.2  472.80  5245.7  472.81
  5263.8  474.24  5269.2  473.70  5283.3  474.76  5351.0  478.42  5489.1  482.39
#Mann=4,-1,0
  4840.4     0.1       0  5174.7    0.07       0  5178.7     0.1       0
  5283.3    0.05       0
Bank Sta=5174.7,5178.7
Exp/Cntr=0.3,0.1

Type RM Length L Ch R = 1,509,194,194,194
BEGIN DESCRIPTION:
Mapping XS 7197d3b1
END DESCRIPTION:
XS GIS Cut Line= 4
      2758097.93      6902981.25      2758061.04      6903117.97
      2758058.87      6903339.32      2758158.69      6903523.77
#Sta/Elev= 30
  4866.0  480.01  4870.6  479.96  4886.5  479.55  4897.3  478.55  4932.0  476.63
  4938.2  475.72  4959.0  474.23  4966.8  472.57  4971.9  472.71  4979.7  471.17
  4990.0  470.30  4998.4  467.76  4998.6  467.26  5002.1  467.26  5002.4  467.76
  5006.6  470.60  5013.6  470.60  5020.6  471.33  5070.6  470.58  5090.6  470.80
  5100.6  470.30  5120.6  471.11  5140.6  470.67  5160.6  471.38  5170.7  470.56
  5200.7  471.01  5227.3  472.40  5235.0  472.28  5300.6  473.66  5438.7  477.99
#Mann=5,-1,0
  4866.0    0.12       0  4870.6     0.1       0  4998.4    0.07       0
  5002.4     0.1       0  5200.7    0.05       0
Bank Sta=4998.4,5002.4
Exp/Cntr=0.3,0.1

Type RM Length L Ch R = 1,315,263,263,263
BEGIN DESCRIPTION:
Mapping XS 5977b4bc
END DESCRIPTION:
XS GIS Cut Line= 4
      2758074.09      6902966.03      2757885.26      6903161.37
      2757861.39      6903291.58      2757850.57      6903546.88
#Sta/Elev= 30
  4728.2  479.83  4754.3  479.16  4794.0  479.03  4836.4  477.58  4843.6  476.50
  4850.5  477.37  4857.7  476.43  4864.7  477.00  4871.9  475.93  4878.8  476.14
  4907.1  474.08  4933.5  470.28  4996.2  468.57  5015.2  468.96  5060.5  468.26
  5077.4  469.57  5121.5  469.36  5129.4  467.47  5137.0  466.96  5137.3  466.46
  5141.0  466.96  5151.7  469.09  5203.4  470.29  5251.8  472.63  5301.8  472.80
  5361.9  475.06  5371.9  477.10  5377.3  479.28  5382.3  477.56  5387.8  479.31
#Mann=7,-1,0
  4728.2    0.12       0  4754.3     0.1       0  4933.5    0.12       0
  5015.2     0.1       0  5137.0    0.07       0  5141.0     0.1       0
  5203.4    0.05       0
Bank Sta=5137,5141
Exp/Cntr=0.3,0.1

Type RM Length L Ch R = 1,52,0,0,0
BEGIN DESCRIPTION:
Caney T15_1 1.0
END DESCRIPTION:
XS GIS Cut Line= 3
      2758024.19      6902957.37      2757712.69      6902997.66
      2757631.47      6903466.68
#Sta/Elev= 30
  4685.9  479.52  4704.2  479.23  4734.5  477.60  4751.4  476.11  4756.4  476.30
  4776.0  474.07  4805.1  471.42  4825.2  470.21  4861.3  469.48  4876.1  468.98
  4916.0  466.99  4984.3  465.31  5004.2  465.53  5009.2  465.21  5012.2  463.97
  5012.5  463.47  5016.0  463.47  5016.2  463.97  5033.8  465.64  5044.0  467.14
  5054.1  467.48  5068.9  467.78  5165.8  466.80  5216.5  467.60  5243.1  468.63
  5248.2  468.10  5287.6  468.57  5409.3  472.45  5449.9  474.16  5476.0  474.51
#Mann=6,-1,0
  4685.9    0.12       0  4776.0     0.1       0  4861.3    0.12       0
  4876.1    0.05       0  5012.2    0.05       0  5016.2    0.05       0
Bank Sta=5012.2,5016.2
Exp/Cntr=0.3,0.1

Chan Stop Cuts=-1