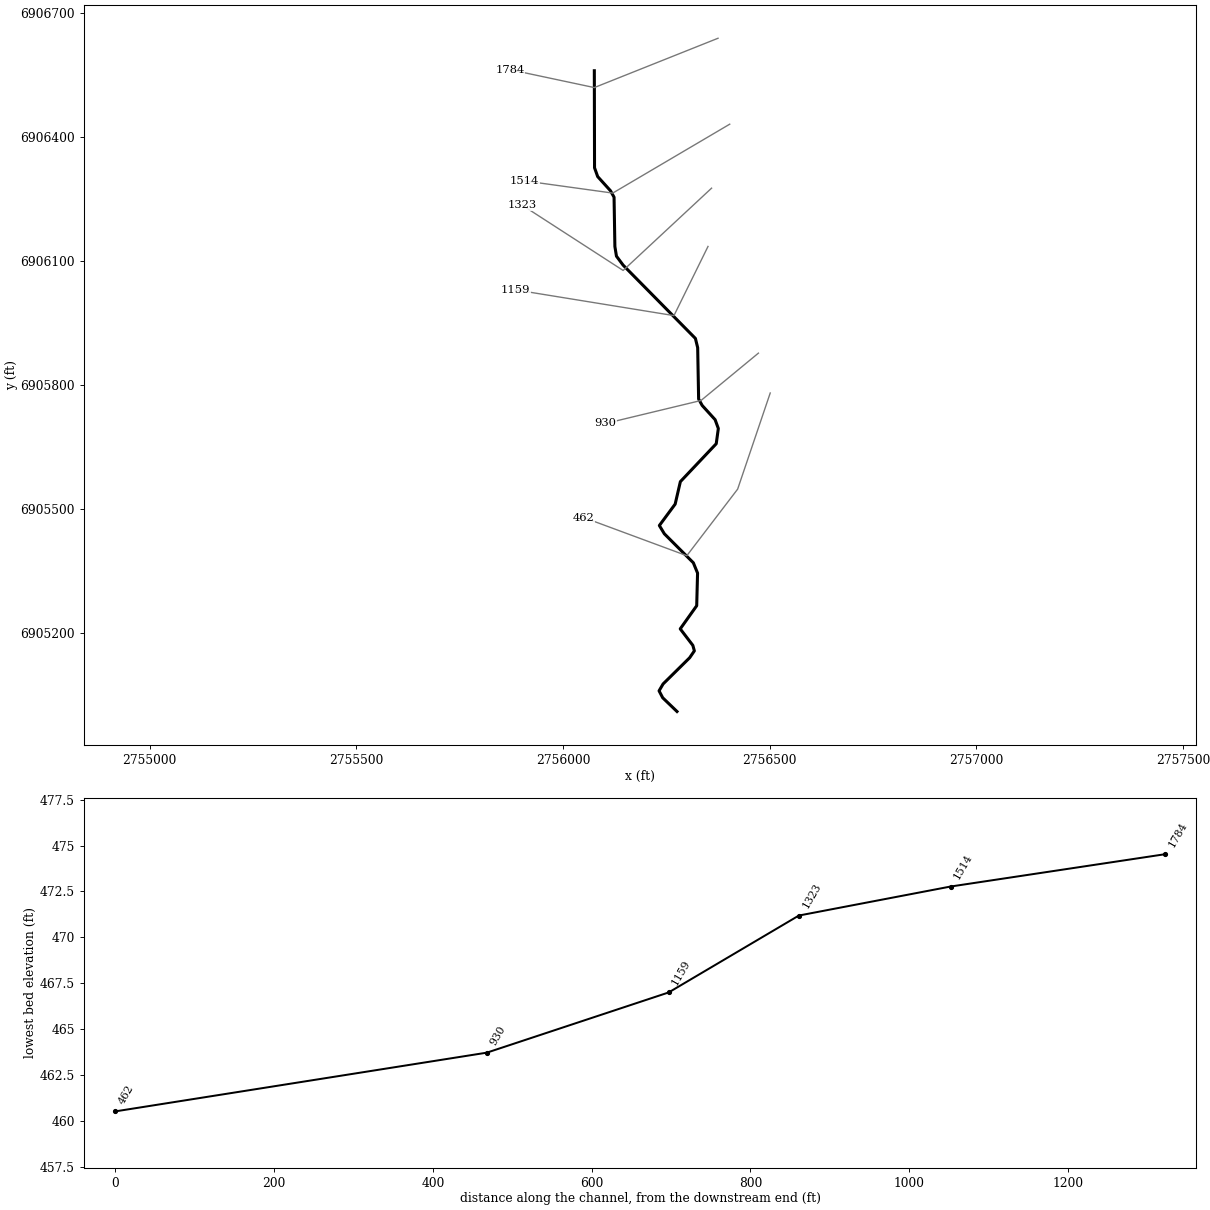
--- Caney T16.prj (project) ---

Proj Title=Caney T16 Base Level Engineering
Current Plan=p01
Default Exp/Contr=0.3,0.1
English Units
Geom File=g01
Flow File=f01
Plan File=p01
BEGIN DESCRIPTION:
Caney T16
END DESCRIPTION:

--- Caney T16.p01 (plan) ---

Plan Title=Multiple Run
Short Identifier=Multiple
Geom File=g01
Flow File=f01
Subcritical Flow
K Sum by GR= 0
Std Step Tol= 0.01
Critical Tol= 0.01
Num of Std Step Trials= 20
Max Error Tol= 0.3
Flow Tol Ratio= 0.001
Split Flow NTrial= 30
Split Flow Tol= 0.02
Split Flow Ratio= 0.02
Log Output Level= 0
Friction Slope Method= 1
Unsteady Friction Slope Method= 2
Unsteady Bridges Friction Slope Method= 1
Parabolic Critical Depth
Global Vel Dist=  1 , 1 , 1
Global Log Level= 0
CheckData=True
Encroach Param= -1, 0, 0, 0
BEGIN DESCRIPTION:
Multiple Run
END DESCRIPTION:

--- Caney T16.f01 (steady flow) ---

Flow Title=Multiple
Number of Profiles=7
Profile Names=10-year,25-year,50-year,1pct_min,100-year,1pct_plu,500-year
River Rch & RM= Caney T16,Reach-1,1784
      66      76      83      45      90     180     107
Boundary for River Rch & Prof#=Caney T16,Reach-1,1
Up Type=0
Dn Type=3
Dn Slope=0.005
Boundary for River Rch & Prof#=Caney T16,Reach-1,2
Up Type=0
Dn Type=3
Dn Slope=0.005
Boundary for River Rch & Prof#=Caney T16,Reach-1,3
Up Type=0
Dn Type=3
Dn Slope=0.005
Boundary for River Rch & Prof#=Caney T16,Reach-1,4
Up Type=0
Dn Type=3
Dn Slope=0.005
Boundary for River Rch & Prof#=Caney T16,Reach-1,5
Up Type=0
Dn Type=3
Dn Slope=0.005
Boundary for River Rch & Prof#=Caney T16,Reach-1,6
Up Type=0
Dn Type=3
Dn Slope=0.005
Boundary for River Rch & Prof#=Caney T16,Reach-1,7
Up Type=0
Dn Type=3
Dn Slope=0.005

--- Caney T16.g01 (geometry) ---

Geom Title=Existing Conditions

River Reach=Caney T16,Reach-1
Reach XY= 30
      2756076.00      6906561.00      2756076.52      6906326.22
      2756084.14      6906304.94      2756115.14      6906270.64
      2756123.73      6906255.06      2756125.73      6906135.89
      2756129.54      6906112.47      2756145.61      6906090.84
      2756320.53      6905913.45      2756326.02      6905891.01
      2756328.30      6905766.93      2756336.92      6905751.33
      2756368.21      6905716.91      2756375.97      6905695.58
      2756370.90      6905658.71      2756284.14      6905567.04
      2756271.54      6905512.65      2756233.30      6905460.92
      2756245.33      6905440.99      2756315.52      6905370.78
      2756325.74      6905345.78      2756323.65      6905266.89
      2756283.81      6905210.90      2756314.31      6905170.99
      2756317.99      6905157.66      2756306.57      6905141.00
      2756242.37      6905077.67      2756232.61      6905061.00
      2756241.40      6905044.22      2756276.00      6905011.00

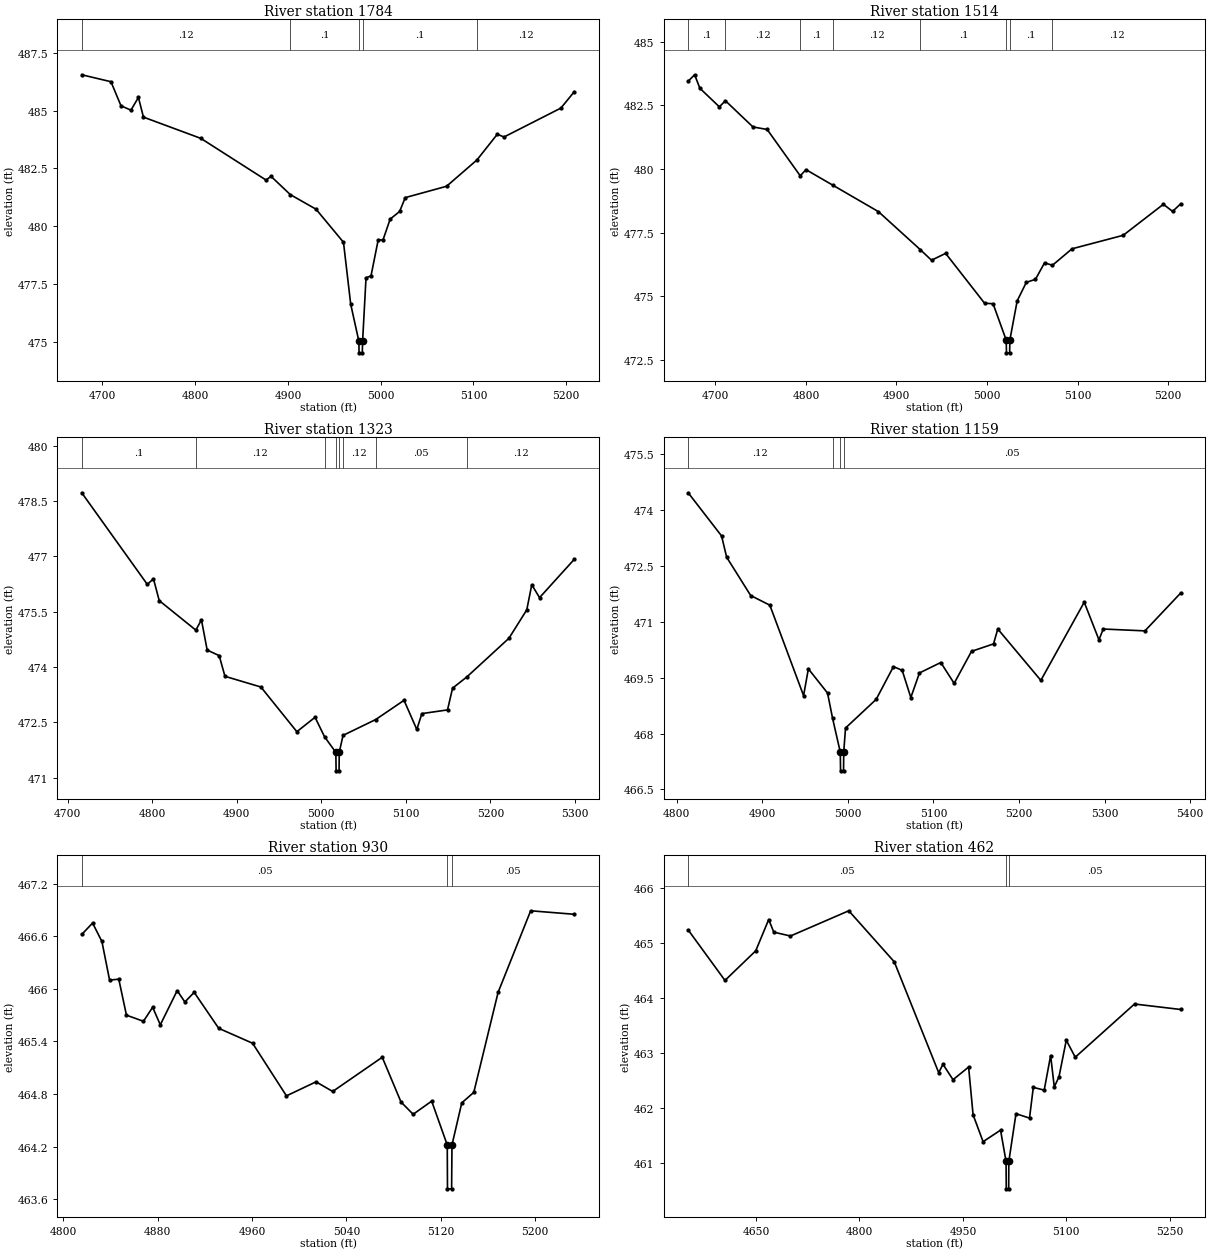
Type RM Length L Ch R = 1,1784,270,270,270
BEGIN DESCRIPTION:
Caney T16 1.0
END DESCRIPTION:
XS GIS Cut Line= 3
      2756375.27      6906639.63      2756075.98      6906520.28
      2755871.85      6906563.68
#Sta/Elev= 30
  4677.8  486.55  4709.3  486.25  4720.1  485.21  4730.8  485.02  4738.9  485.57
  4744.3  484.72  4806.2  483.80  4876.4  482.00  4881.8  482.16  4902.6  481.37
  4930.3  480.74  4959.9  479.31  4967.7  476.63  4976.5  475.03  4976.7  474.53
  4980.2  474.53  4980.5  475.03  4984.2  477.77  4989.6  477.86  4997.3  479.41
  5002.5  479.41  5010.2  480.31  5020.4  480.64  5026.5  481.24  5071.0  481.73
  5103.8  482.87  5125.7  483.98  5132.9  483.86  5194.2  485.11  5208.7  485.82
#Mann=5,-1,0
  4677.8    0.12       0  4902.6     0.1       0  4976.5    0.07       0
  4980.5     0.1       0  5103.8    0.12       0
Bank Sta=4976.5,4980.5
Exp/Cntr=0.3,0.1

Type RM Length L Ch R = 1,1514,191,191,191
BEGIN DESCRIPTION:
Mapping XS 848e7a76
END DESCRIPTION:
XS GIS Cut Line= 3
      2756403.54      6906431.76      2756120.52      6906265.07
      2755907.01      6906294.58
#Sta/Elev= 30
  4670.0  483.45  4677.1  483.70  4682.9  483.17  4704.4  482.44  4711.1  482.68
  4741.5  481.65  4757.2  481.55  4793.7  479.73  4800.1  479.97  4830.2  479.35
  4880.1  478.32  4926.5  476.82  4938.7  476.41  4954.3  476.68  4997.3  474.72
  5006.7  474.70  5021.2  473.27  5021.5  472.77  5025.0  472.77  5025.2  473.27
  5033.3  474.81  5043.4  475.54  5053.5  475.66  5063.6  476.31  5072.2  476.21
  5093.9  476.86  5150.4  477.39  5194.8  478.61  5204.9  478.33  5214.0  478.63
#Mann=8,-1,0
  4670.0     0.1       0  4711.1    0.12       0  4793.7     0.1       0
  4830.2    0.12       0  4926.5     0.1       0  5021.2    0.07       0
  5025.2     0.1       0  5072.2    0.12       0
Bank Sta=5021.2,5025.2
Exp/Cntr=0.3,0.1

Type RM Length L Ch R = 1,1323,164,164,164
BEGIN DESCRIPTION:
Mapping XS 2b8a02a9
END DESCRIPTION:
XS GIS Cut Line= 3
      2756359.62      6906276.97      2756145.66      6906077.92
      2755902.09      6906235.44
#Sta/Elev= 30
  4716.8  478.72  4794.3  476.24  4801.6  476.39  4808.4  475.80  4851.7  475.00
  4858.3  475.28  4865.1  474.46  4879.3  474.31  4886.1  473.75  4928.6  473.46
  4971.1  472.25  4992.6  472.64  5003.9  472.11  5017.2  471.69  5017.5  471.19
  5021.0  471.19  5021.2  471.69  5025.7  472.15  5064.4  472.58  5097.8  473.10
  5112.9  472.31  5118.9  472.74  5149.2  472.84  5155.2  473.43  5171.9  473.73
  5221.8  474.78  5242.9  475.55  5248.8  476.23  5258.0  475.88  5299.1  476.92
#Mann=8,-1,0
  4716.8     0.1       0  4851.7    0.12       0  5003.9    0.05       0
  5017.2    0.07       0  5021.2    0.05       0  5025.7    0.12       0
  5064.4    0.05       0  5171.9    0.12       0
Bank Sta=5017.2,5021.2
Exp/Cntr=0.3,0.1

Type RM Length L Ch R = 1,1159,229,229,229
BEGIN DESCRIPTION:
Mapping XS 54b6e3b5
END DESCRIPTION:
XS GIS Cut Line= 3
      2756351.00      6906135.99      2756268.63      6905968.66
      2755884.66      6906031.02
#Sta/Elev= 30
  4813.5  474.47  4852.5  473.31  4858.4  472.74  4886.5  471.71  4908.9  471.45
  4948.3  469.02  4953.9  469.74  4976.3  469.09  4982.1  468.42  4991.2  467.50
  4991.5  467.00  4995.0  467.00  4995.2  467.50  4997.3  468.15  5033.1  468.92
  5053.3  469.80  5063.5  469.70  5073.6  468.97  5083.7  469.63  5108.6  469.91
  5124.2  469.35  5144.5  470.21  5170.2  470.41  5175.2  470.81  5225.5  469.43
  5276.2  471.53  5293.4  470.52  5298.4  470.81  5347.1  470.76  5389.0  471.78
#Mann=4,-1,0
  4813.5    0.12       0  4982.1    0.05       0  4991.2    0.04       0
  4995.2    0.05       0
Bank Sta=4991.2,4995.2
Exp/Cntr=0.3,0.1

Type RM Length L Ch R = 1,930,468,468,468
BEGIN DESCRIPTION:
Mapping XS d7e33f63
END DESCRIPTION:
XS GIS Cut Line= 3
      2756472.95      6905877.91      2756334.06      6905763.34
      2756103.20      6905707.79
#Sta/Elev= 30
  4815.7  466.62  4824.9  466.75  4832.8  466.54  4839.3  466.10  4847.1  466.11
  4853.6  465.70  4868.0  465.63  4875.8  465.79  4882.3  465.59  4896.6  465.98
  4903.1  465.85  4911.0  465.96  4931.8  465.55  4960.5  465.38  4989.2  464.78
  5014.3  464.94  5028.4  464.83  5070.4  465.22  5086.3  464.71  5096.6  464.57
  5112.3  464.72  5125.5  464.22  5125.7  463.72  5129.2  463.72  5129.5  464.22
  5137.8  464.70  5148.0  464.82  5168.6  465.96  5196.2  466.89  5233.2  466.85
#Mann=3,-1,0
  4815.7    0.05       0  5125.5    0.04       0  5129.5    0.05       0
Bank Sta=5125.5,5129.5
Exp/Cntr=0.3,0.1

Type RM Length L Ch R = 1,462,0,0,0
BEGIN DESCRIPTION:
Caney T16 0.0
END DESCRIPTION:
XS GIS Cut Line= 4
      2756501.52      6905781.49      2756422.71      6905548.95
      2756299.72      6905387.87      2756050.35      6905480.16
#Sta/Elev= 30
  4551.8  465.24  4605.1  464.32  4649.7  464.86  4668.5  465.43  4675.9  465.20
  4700.1  465.13  4784.6  465.59  4850.5  464.66  4914.9  462.64  4921.2  462.79
  4935.7  462.51  4958.3  462.74  4964.8  461.87  4979.3  461.38  5004.6  461.59
  5012.6  461.02  5012.9  460.52  5016.4  460.52  5016.6  461.02  5027.0  461.89
  5046.6  461.81  5052.1  462.37  5067.9  462.32  5077.2  462.95  5082.5  462.38
  5089.3  462.56  5099.9  463.23  5112.9  462.92  5198.8  463.89  5265.9  463.79
#Mann=3,-1,0
  4551.8    0.05       0  5012.6    0.04       0  5016.6    0.05       0
Bank Sta=5012.6,5016.6
Exp/Cntr=0.3,0.1

Chan Stop Cuts=-1