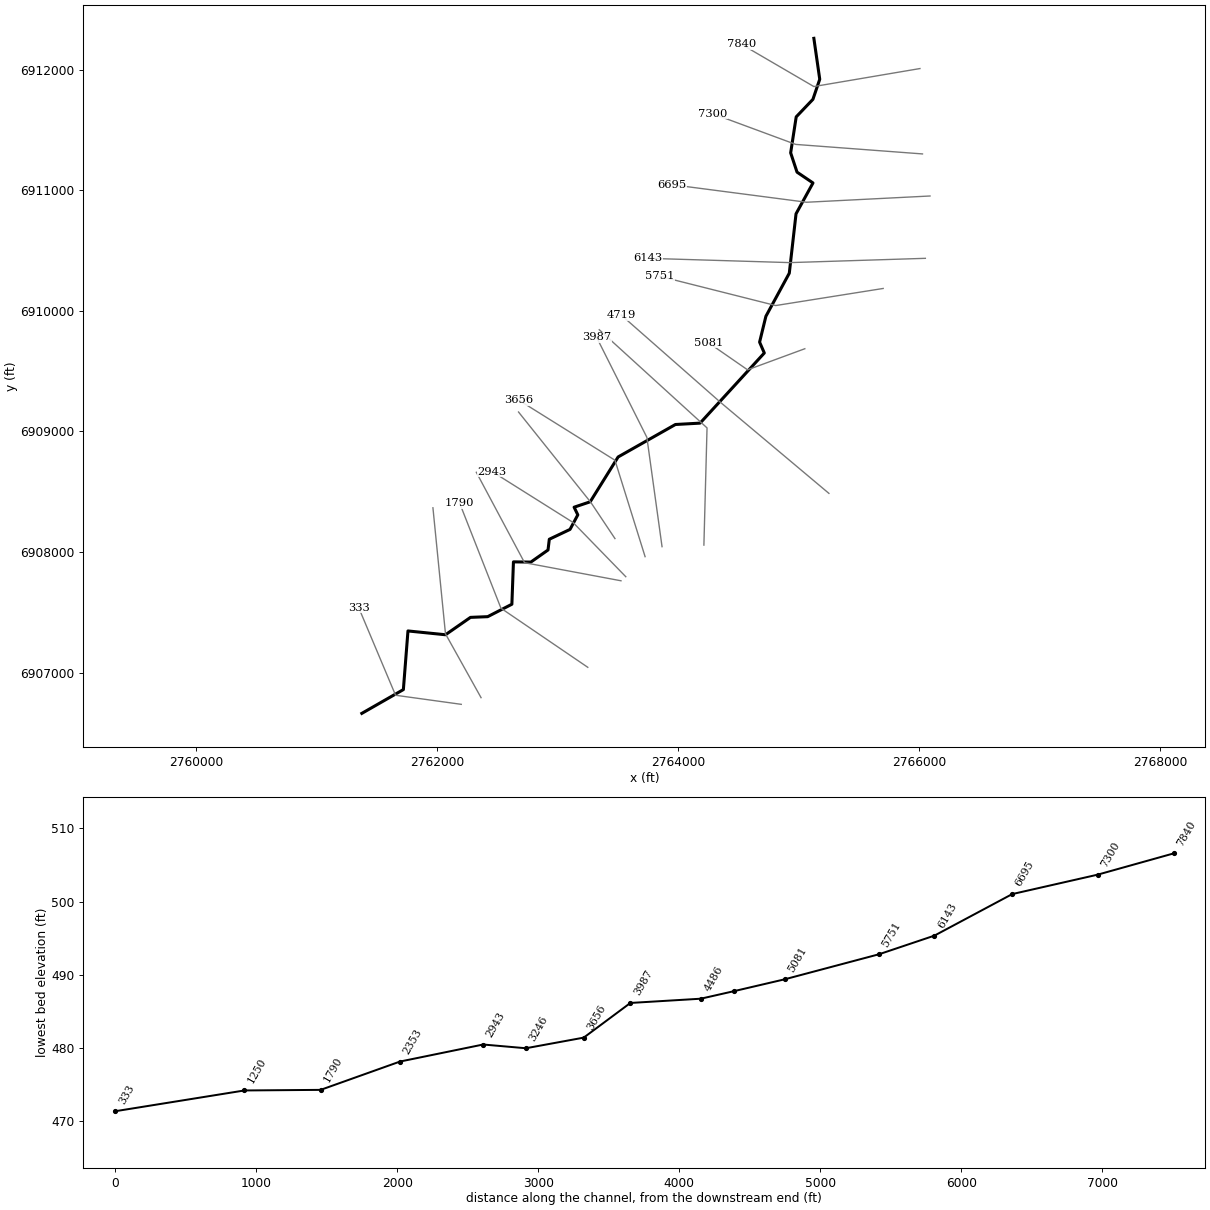
--- Caney T17.prj (project) ---

Proj Title=Caney T17 Base Level Engineering
Current Plan=p01
Default Exp/Contr=0.3,0.1
English Units
Geom File=g01
Flow File=f01
Plan File=p01
Y Axis Title=Elevation
X Axis Title(PF)=Main Channel Distance
X Axis Title(XS)=Station
BEGIN DESCRIPTION:
Caney T17
END DESCRIPTION:
DSS Export Rating Curves= 0
DSS Export Rating Curve Sorted= 0
DSS Export Volume Flow Curves= 0
DXF OffsetX= 0
DXF OffsetY= 0
DXF ScaleX= 1
DXF ScaleY= 10

--- Caney T17.p01 (plan) ---

Plan Title=Multiple Run
Short Identifier=Multiple
Geom File=g01
Flow File=f01
Subcritical Flow
K Sum by GR= 0
Std Step Tol= 0.01
Critical Tol= 0.01
Num of Std Step Trials= 20
Max Error Tol= 0.3
Flow Tol Ratio= 0.001
Split Flow NTrial= 30
Split Flow Tol= 0.02
Split Flow Ratio= 0.02
Log Output Level= 0
Friction Slope Method= 1
Unsteady Friction Slope Method= 2
Unsteady Bridges Friction Slope Method= 1
Parabolic Critical Depth
Global Vel Dist=  1 , 1 , 1
Global Log Level= 0
CheckData=True
Encroach Param= -1, 0, 0, 0
BEGIN DESCRIPTION:
Multiple Run
END DESCRIPTION:

--- Caney T17.f01 (steady flow) ---

Flow Title=Multiple
Number of Profiles=7
Profile Names=10-year,25-year,50-year,1pct_min,100-year,1pct_plu,500-year
River Rch & RM= Caney T17,Reach-1,7840
     496     660     792     473     944    1883    1342
River Rch & RM= Caney T17,Reach-1,4719
     756    1030    1255     760    1517    3027    2220
Boundary for River Rch & Prof#=Caney T17,Reach-1,1
Up Type=0
Dn Type=3
Dn Slope=0.005
Boundary for River Rch & Prof#=Caney T17,Reach-1,2
Up Type=0
Dn Type=3
Dn Slope=0.005
Boundary for River Rch & Prof#=Caney T17,Reach-1,3
Up Type=0
Dn Type=3
Dn Slope=0.005
Boundary for River Rch & Prof#=Caney T17,Reach-1,4
Up Type=0
Dn Type=3
Dn Slope=0.005
Boundary for River Rch & Prof#=Caney T17,Reach-1,5
Up Type=0
Dn Type=3
Dn Slope=0.005
Boundary for River Rch & Prof#=Caney T17,Reach-1,6
Up Type=0
Dn Type=3
Dn Slope=0.005
Boundary for River Rch & Prof#=Caney T17,Reach-1,7
Up Type=0
Dn Type=3
Dn Slope=0.005

--- Caney T17.g01 (geometry) ---

Geom Title=Existing Conditions
Program Version=4.10

River Reach=Caney T17       ,Reach-1
Reach XY= 30
        2765126.        6912261.      2765174.78       6911921.5
      2765118.14      6911754.83      2764979.54      6911609.54
      2764933.56        6911311.      2764986.39       6911150.9
      2765118.77      6911061.31      2764978.07      6910805.14
      2764922.17      6910312.58      2764728.08      6909955.14
      2764675.79      6909740.79      2764714.96      6909650.65
      2764182.19      6909068.81      2763977.47      6909057.45
      2763502.16      6908788.14      2763270.52      6908416.26
      2763137.09      6908371.37      2763167.75      6908307.78
      2763103.15      6908187.16      2762931.28      6908105.49
      2762920.71      6908016.54      2762778.28      6907916.13
       2762633.8      6907917.84      2762620.83      6907566.41
      2762420.07      6907463.25      2762277.47      6907457.45
      2762070.07      6907313.23      2761758.78      6907344.79
      2761720.64       6906858.3        2761376.        6906661.

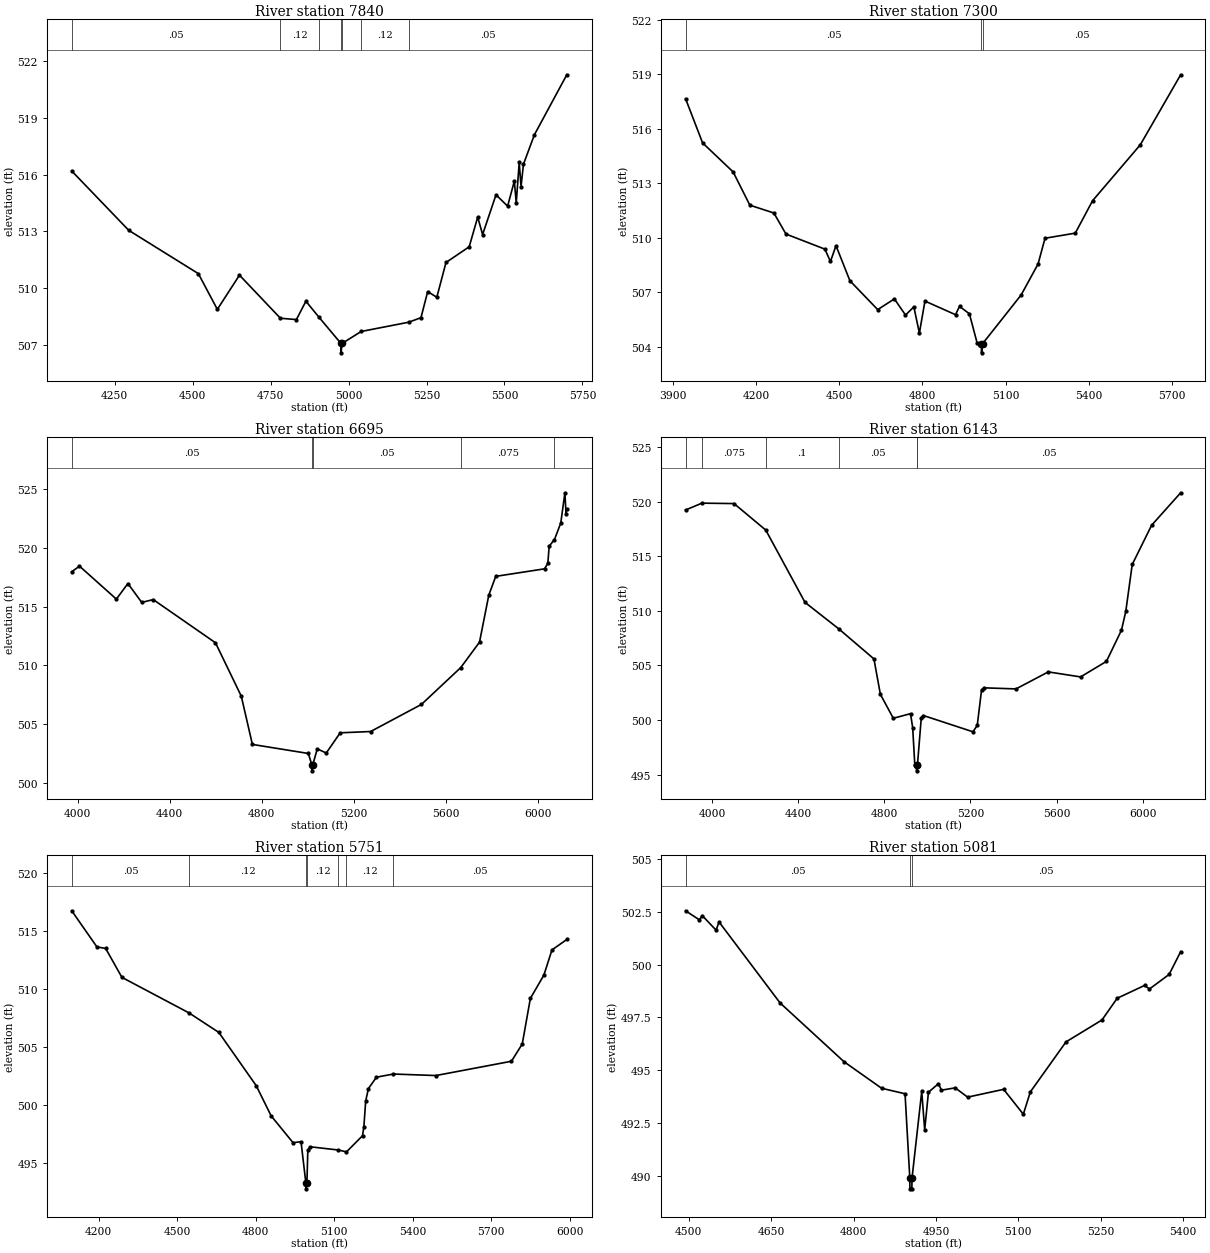
Type RM Length L Ch R = 1 ,7840    ,540,540,540
BEGIN DESCRIPTION:
Caney T17 13.0
END DESCRIPTION:
XS GIS Cut Line= 3
      2766006.28      6912010.39        2765126.        6911861.
      2764525.99      6912211.01
#Sta/Elev= 30
  4112.3   516.2  4295.2  513.06  4518.3  510.77  4579.2  508.88  4650.2  510.69
  4781.5  508.41  4832.7  508.34  4863.2  509.31  4905.3  508.46  4975.5  507.08
  4975.8  506.58  4979.5  507.08  5040.4  507.71  5192.9   508.2  5232.2  508.44
  5253.7  509.82    5283  509.52  5312.4  511.36  5386.8  512.19  5414.1  513.76
  5429.8  512.84  5472.8  514.94    5510  514.34  5531.5  515.66  5537.7  514.52
  5547.2  516.65    5553  515.37  5560.9  516.56    5596  518.12  5699.8  521.29
#Mann= 7 ,-1 , 0
  4112.3     .05       0  4781.5     .12       0  4905.3      .1       0
  4975.5     .07       0  4979.5      .1       0  5040.4     .12       0
  5192.9     .05       0
Bank Sta=4975.5,4979.5
XS Rating Curve= 0 ,0
Exp/Cntr=0.3,0.1

Type RM Length L Ch R = 1 ,7300    ,605,605,605
BEGIN DESCRIPTION:
Caney T17 12.0
END DESCRIPTION:
XS GIS Cut Line= 3
      2766027.16      6911302.05      2764975.82      6911380.98
      2764289.31      6911634.73
#Sta/Elev= 30
  3945.7  517.66    4007  515.23  4117.3  513.63  4177.5   511.8  4264.2  511.37
  4307.9  510.21  4448.3  509.38  4468.3   508.7  4488.4  509.57  4538.5  507.64
  4638.8  506.05    4699  506.64  4739.1  505.75  4769.2   506.2  4789.2  504.76
  4809.3  506.52  4919.6  505.77    4934  506.23  4969.7  505.82  4997.4  504.22
  5013.1  504.17  5013.4  503.67  5017.1  504.17  5156.5  506.86  5217.4  508.56
  5242.5  509.98  5351.6  510.26  5414.3  512.05  5586.1  515.12  5731.9  518.98
#Mann= 3 ,-1 , 0
  3945.7     .05       0  5013.1     .04       0  5017.1     .05       0
Bank Sta=5013.1,5017.1
XS Rating Curve= 0 ,0
Exp/Cntr=0.3,0.1

Type RM Length L Ch R = 1 ,6695    ,552,552,552
BEGIN DESCRIPTION:
Caney T17 11.0
END DESCRIPTION:
XS GIS Cut Line= 3
      2766089.65       6910953.1      2765065.46      6910901.22
      2763950.01      6911046.71
#Sta/Elev= 30
  3974.5  517.98  4008.2  518.46  4168.4  515.65  4218.5  516.98  4278.5  515.37
  4328.6  515.61  4598.9  511.93    4711  507.38  4759.2  503.27  5002.2   502.5
  5017.6  501.52  5017.9  501.02  5021.6  501.52  5040.9  502.89  5080.1  502.54
  5140.6  504.26  5272.8  504.37  5493.6  506.68  5664.4  509.82  5745.7  511.98
  5786.1  515.99  5816.3  517.59  6028.1  518.23  6042.6   518.7  6048.3  520.16
  6071.3  520.72  6098.7  522.13  6116.6  524.71  6121.6  522.91  6124.9   523.3
#Mann= 5 ,-1 , 0
  3974.5     .05       0  5017.6     .05       0  5021.6     .05       0
  5664.4    .075       0  6071.3     .05       0
Bank Sta=5017.6,5021.6
XS Rating Curve= 0 ,0
Exp/Cntr=0.3,0.1

Type RM Length L Ch R = 1 ,6143    ,392,392,392
BEGIN DESCRIPTION:
Caney T17 10.0
END DESCRIPTION:
XS GIS Cut Line= 3
      2766050.97        6910436.      2764927.33      6910400.45
      2763750.97        6910436.
#Sta/Elev= 30
  3875.8  519.25  3951.6  519.88  4100.9  519.84  4248.5  517.41    4431  510.78
  4588.1  508.35  4751.2   505.6  4781.2  502.35  4841.3  500.16  4921.3  500.58
  4931.3   499.3  4941.3  495.85  4949.3  495.84  4949.6  495.34  4953.3  495.84
  4971.3  500.21  4981.3  500.41  5211.4  498.92  5231.4   499.5  5251.4  502.75
  5261.5  502.95  5411.5  502.85  5561.6  504.41  5711.7  503.95  5831.7  505.37
  5901.7  508.23  5921.8  509.95  5951.8  514.26  6041.8  517.85  6176.9  520.83
#Mann= 6 ,-1 , 0
  3875.8     .05       0  3951.6    .075       0  4248.5      .1       0
  4588.1     .05       0  4949.3     .05       0  4953.3     .05       0
Bank Sta=4949.3,4953.3
XS Rating Curve= 0 ,0
Exp/Cntr=0.3,0.1

Type RM Length L Ch R = 1 ,5751    ,670,670,670
BEGIN DESCRIPTION:
Caney T17 9.0
END DESCRIPTION:
XS GIS Cut Line= 3
      2765701.01        6910186.      2764809.51      6910044.26
      2763851.02      6910285.99
#Sta/Elev= 30
  4097.3  516.73  4193.5  513.62  4226.8  513.49    4289     511  4546.1  507.93
  4659.3  506.26    4802  501.68  4859.1  499.08  4942.8  496.77  4973.2  496.86
  4991.7   493.3    4992   492.8  4995.7   493.3  4999.2  496.12  5007.9  496.42
  5116.3  496.14  5146.9  495.98  5208.1  497.37  5213.3  498.14  5220.2  500.35
  5230.5  501.42  5261.4  502.41  5326.3  502.68  5488.3  502.55  5777.1  503.78
  5818.4  505.27  5849.3  509.19  5900.9  511.19  5931.8  513.36  5988.5  514.26
#Mann= 7 ,-1 , 0
  4097.3     .05       0  4546.1     .12       0  4991.7     .07       0
  4995.7     .12       0  5116.3      .1       0  5146.9     .12       0
  5326.3     .05       0
Bank Sta=4991.7,4995.7
XS Rating Curve= 0 ,0
Exp/Cntr=0.3,0.1

Type RM Length L Ch R = 1 ,5081    ,362,362,362
BEGIN DESCRIPTION:
Caney T17 8.0
END DESCRIPTION:
XS GIS Cut Line= 3
      2765050.96      6909685.98        2764576.        6909511.
      2764250.96      6909736.03
#Sta/Elev= 30
  4494.2  502.56  4519.3  502.13  4524.6  502.33  4549.7  501.64  4555.1  502.03
  4666.2  498.19  4782.7   495.4  4851.2  494.14  4893.8  493.88  4902.5  489.87
  4902.7  489.37  4906.2  489.37  4906.5  489.87  4924.2  493.99  4929.6  492.17
  4936.4  493.95  4954.7  494.36    4960  494.05  4985.1  494.16  5007.8  493.72
  5073.3  494.09  5109.2  492.91    5122  493.97  5186.9  496.34  5252.4  497.38
  5280.1  498.41  5330.1  499.02  5338.9  498.85  5374.7  499.54  5395.7  500.62
#Mann= 3 ,-1 , 0
  4494.2     .05       0  4902.5     .04       0  4906.5     .05       0
Bank Sta=4902.5,4906.5
XS Rating Curve= 0 ,0
Exp/Cntr=0.3,0.1

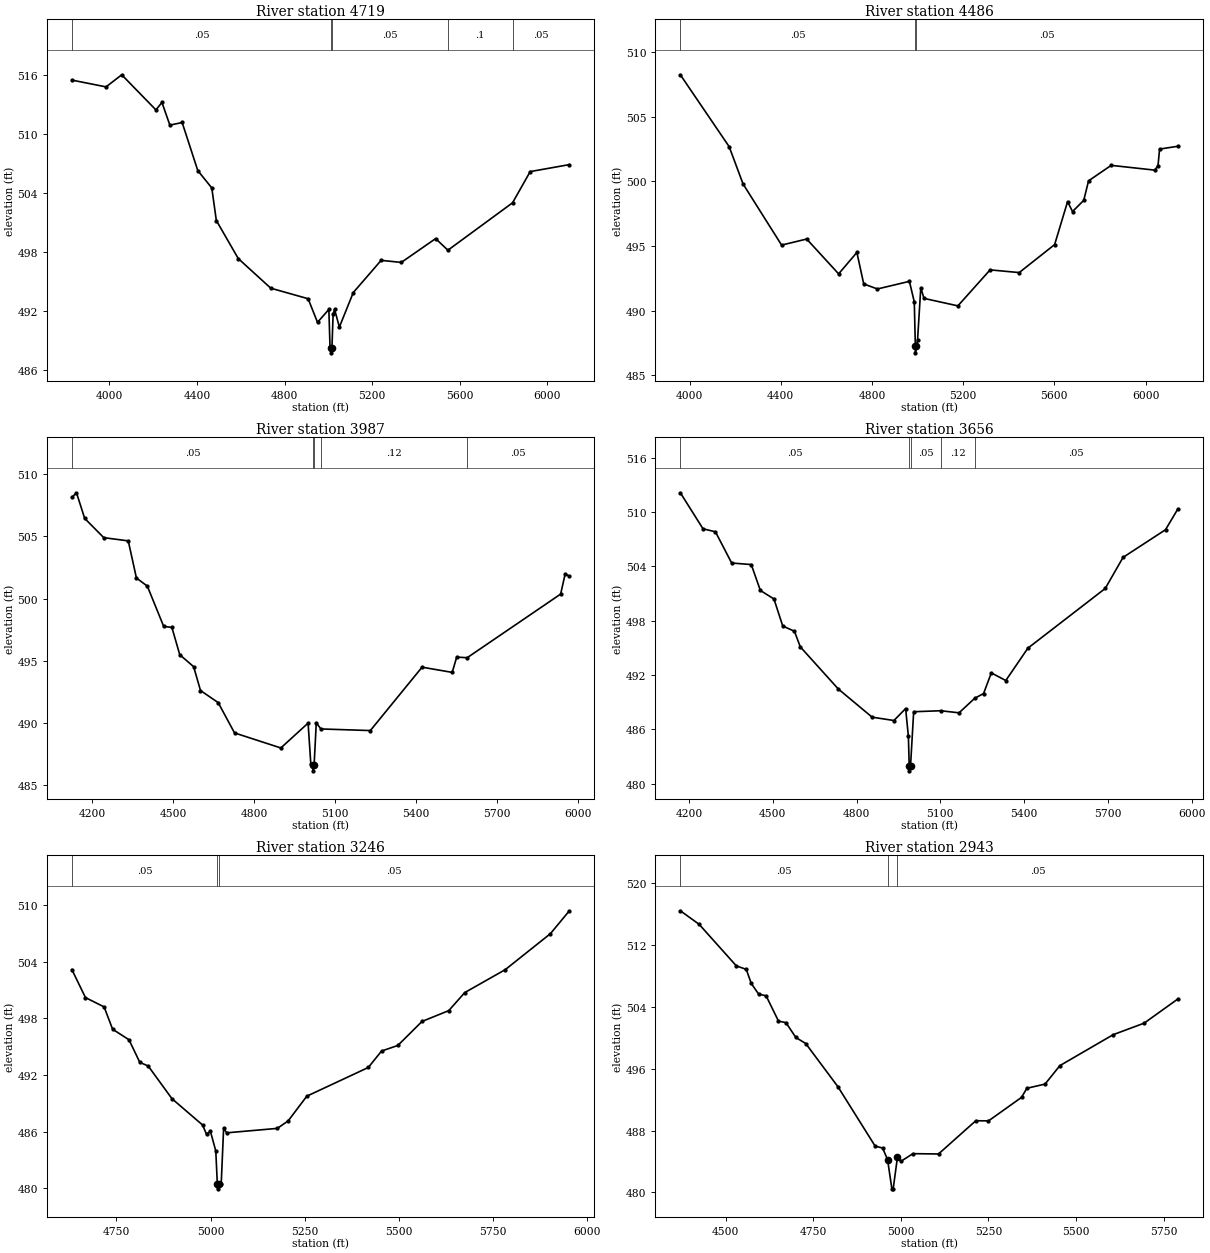
Type RM Length L Ch R = 1 ,4719    ,233,233,233
BEGIN DESCRIPTION:
Caney T17 7.0
END DESCRIPTION:
XS GIS Cut Line= 3
      2765250.97      6908486.03      2764354.04      6909239.02
      2763527.98      6909965.25
#Sta/Elev= 30
  3828.9  515.46    3985  514.77  4056.5     516  4212.6  512.43  4240.1  513.19
  4276.3  510.88  4332.3  511.15  4403.8  506.26  4467.6   504.5  4488.4  501.19
  4588.5  497.32  4736.9  494.31  4907.3  493.24  4950.2  490.84    5002  492.15
  5007.3  488.35  5011.9  488.24  5012.2  487.74  5016.1  488.24  5021.5  491.68
  5028.2  492.15    5050  490.36  5113.6  493.87  5240.7  497.14  5332.8  496.93
  5489.3  499.35  5545.5  498.17  5840.6  502.99    5921  506.16  6099.9  506.87
#Mann= 5 ,-1 , 0
  3828.9     .05       0  5011.9     .04       0  5016.1     .05       0
  5545.5      .1       0  5840.6     .05       0
Bank Sta=5011.9,5016.1
XS Rating Curve= 0 ,0
Exp/Cntr=0.3,0.1

Type RM Length L Ch R = 1 ,4486    ,499,499,499
BEGIN DESCRIPTION:
Caney T17 6.0
END DESCRIPTION:
XS GIS Cut Line= 3
      2764213.75      6908057.01      2764239.79      6909029.19
       2763345.7      6909843.71
#Sta/Elev= 30
  3959.8  508.27  4173.9   502.7  4234.8  499.81  4403.9  495.07    4514  495.54
    4654  492.84  4734.1   494.5  4764.1  492.06  4824.1  491.67  4964.5  492.26
  4985.9  490.66  4990.5  487.22  4990.9  486.72  4994.8  487.22  5000.1  487.69
  5014.3  491.76  5028.5  490.94  5177.1  490.36  5318.3  493.15    5446  492.94
  5601.4  495.11  5658.2  498.44  5679.8  497.67  5729.1  498.54  5750.1  500.05
  5849.4  501.25  6040.6  500.88  6054.8  501.23  6061.6  502.51  6141.8  502.73
#Mann= 3 ,-1 , 0
  3959.8     .05       0  4990.5     .05       0  4994.8     .05       0
Bank Sta=4990.5,4994.8
XS Rating Curve= 0 ,0
Exp/Cntr=0.3,0.1

Type RM Length L Ch R = 1 ,3987    ,331,331,331
BEGIN DESCRIPTION:
Mapping XS 54950b6a
END DESCRIPTION:
XS GIS Cut Line= 3
      2763866.52      6908043.94      2763740.65      6908951.07
        2763324.      6909780.03
#Sta/Elev= 30
  4124.7  508.14  4141.9  508.51  4172.2  506.45  4242.9   504.9  4333.7  504.64
    4364  501.65  4404.4     501    4465  497.76  4495.3  497.68  4524.6  495.48
    4576  494.52  4601.4   492.6  4666.9  491.63  4727.5  489.19  4899.1  487.98
  5000.1  489.98  5010.2   486.7  5018.1  486.64  5018.5  486.14  5022.5  486.64
  5030.4  490.01  5047.4  489.51  5230.7  489.38  5422.4  494.48  5534.1  494.06
  5550.8  495.29  5589.6  495.24  5935.9  500.36  5952.7  501.98  5968.3   501.8
#Mann= 5 ,-1 , 0
  4124.7     .05       0  5018.1     .04       0  5022.5     .05       0
  5047.4     .12       0  5589.6     .05       0
Bank Sta=5018.1,5022.5
XS Rating Curve= 0 ,0
Exp/Cntr=0.3,0.1

Type RM Length L Ch R = 1 ,3656    ,410,410,410
BEGIN DESCRIPTION:
Caney T17 5.0
END DESCRIPTION:
XS GIS Cut Line= 3
      2763725.99      6907961.03        2763476.        6908761.
      2762676.01      6909260.99
#Sta/Elev= 30
  4169.2  512.12  4250.4  508.14  4294.9  507.81    4353  504.36  4423.2  504.19
  4455.7  501.33  4504.4  500.39  4535.9   497.4  4577.8  496.82  4598.7   495.1
  4734.9  490.44  4855.9  487.33    4934  486.96  4975.9  488.28  4985.8  485.21
  4988.8   481.9  4989.3   481.4  4993.4   481.9  5004.7  487.93  5101.2  488.04
  5167.1  487.81  5223.5  489.42    5255  489.94  5282.7  492.22  5334.6  491.38
  5413.6  494.95  5690.7  501.55  5754.4  504.98  5906.5  508.04  5950.7  510.33
#Mann= 5 ,-1 , 0
  4169.2     .05       0  4988.8     .04       0  4993.4     .05       0
  5101.2     .12       0  5223.5     .05       0
Bank Sta=4988.8,4993.4
XS Rating Curve= 0 ,0
Exp/Cntr=0.3,0.1

Type RM Length L Ch R = 1 ,3246    ,303,303,303
BEGIN DESCRIPTION:
Caney T17 4.0
END DESCRIPTION:
XS GIS Cut Line= 3
      2763476.02      6908110.98        2763276.        6908411.
      2762675.97      6909161.04
#Sta/Elev= 30
  4631.6  503.17  4667.7   500.2  4717.3  499.21  4739.8  496.85  4783.4  495.73
  4811.9  493.35  4834.4  492.95  4897.5  489.49  4978.7  486.71  4989.2  485.72
  4999.4  486.06  5013.8  483.96  5017.9  480.45  5018.4  479.95  5022.5  480.45
  5028.2  480.49  5034.6  486.37  5042.6  485.88  5177.1  486.35  5205.9  487.14
  5255.5  489.76  5418.8   492.8    5454  494.54  5497.2  495.13  5561.3  497.67
  5632.5  498.82  5674.9  500.73  5782.2  503.15  5902.2  506.96  5952.7  509.39
#Mann= 3 ,-1 , 0
  4631.6     .05       0  5017.9     .04       0  5022.5     .05       0
Bank Sta=5017.9,5022.5
XS Rating Curve= 0 ,0
Exp/Cntr=0.3,0.1

Type RM Length L Ch R = 1 ,2943    ,590,590,590
BEGIN DESCRIPTION:
Caney T17 3.0
END DESCRIPTION:
XS GIS Cut Line= 3
      2763565.68      6907794.79      2763127.17      6908245.58
      2762458.05      6908666.32
#Sta/Elev= 30
  4371.1  516.43  4424.7  514.68  4530.9   509.3  4559.2  508.85  4573.4  507.03
  4594.5  505.65  4615.8  505.43  4651.1  502.16  4672.4  501.96  4700.6  500.04
  4728.8  499.26  4820.8  493.66  4926.8  485.99  4948.1  485.74  4962.3  484.23
  4974.6  480.46  4978.3  480.46  4990.6  484.59    5000  484.01  5034.6  485.01
  5107.6  484.97    5214  489.27  5250.2  489.25  5344.4  492.29  5359.7  493.47
  5411.5  494.01  5453.9   496.4  5605.8   500.4  5694.1  501.89  5790.4  505.02
#Mann= 3 ,-1 , 0
  4371.1     .05       0  4962.3     .04       0  4990.6     .05       0
Bank Sta=4962.3,4990.6
XS Rating Curve= 0 ,0
Exp/Cntr=0.3,0.1

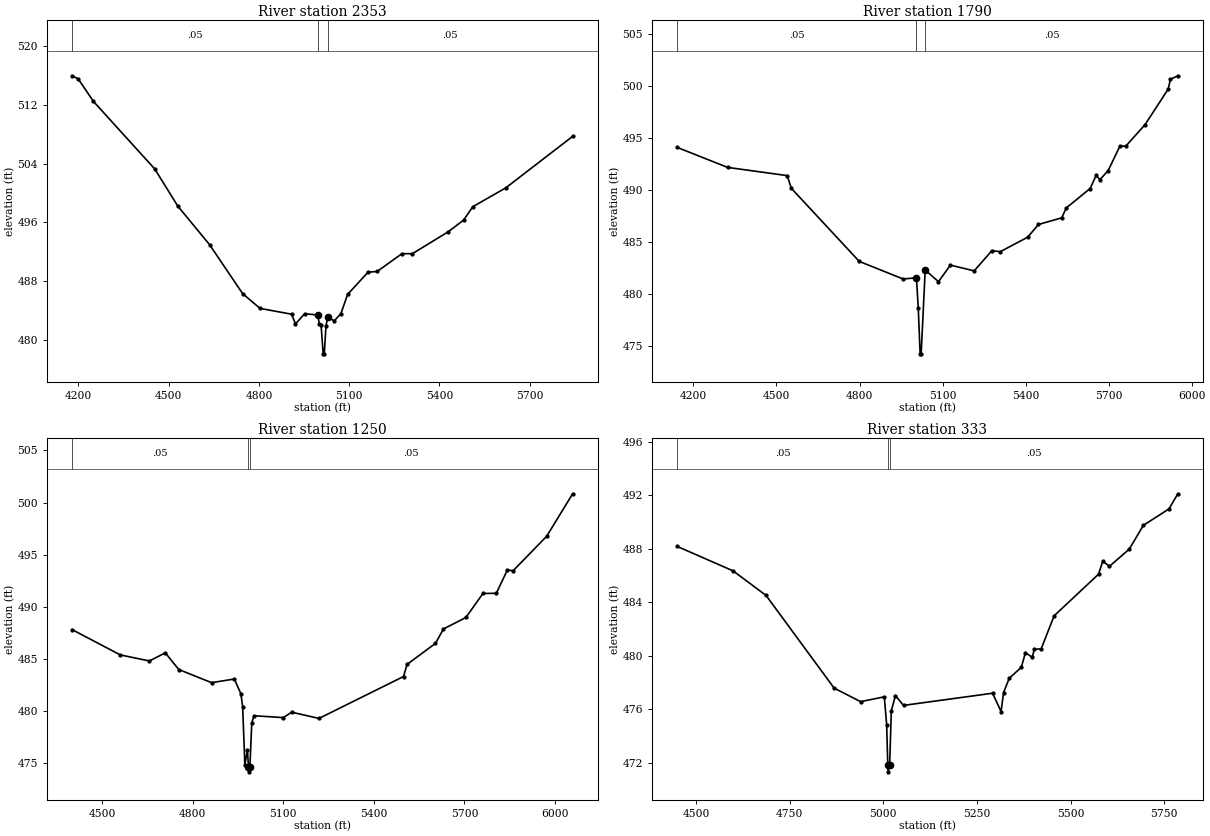
Type RM Length L Ch R = 1 ,2353    ,563,563,563
BEGIN DESCRIPTION:
Caney T17 2.0
END DESCRIPTION:
XS GIS Cut Line= 3
      2763526.04      6907760.99        2762726.        6907911.
      2762325.99      6908661.01
#Sta/Elev= 30
  4178.8  515.95  4199.2  515.54  4250.1  512.46  4453.5  503.29  4530.7  498.21
  4635.8  492.99  4746.1  486.31  4803.7  484.31  4908.8  483.52  4921.6  482.19
  4952.1  483.59  4995.6  483.41  5000.9  482.16  5006.6  482.08  5013.6  478.13
  5017.3  478.13  5022.9   481.9  5028.6  483.09  5050.5  482.62  5072.5   483.6
  5094.8  486.21  5162.8  489.24  5192.9  489.33  5275.1  491.75  5310.1  491.75
  5428.8  494.72  5480.1  496.31  5510.9  498.14  5620.7  500.71  5842.8  507.71
#Mann= 3 ,-1 , 0
  4178.8     .05       0  4995.6     .04       0  5028.6     .05       0
Bank Sta=4995.6,5028.6
XS Rating Curve= 0 ,0
Exp/Cntr=0.3,0.1

Type RM Length L Ch R = 1 ,1790    ,540,540,540
BEGIN DESCRIPTION:
Mapping XS 44783ffd
END DESCRIPTION:
XS GIS Cut Line= 3
      2763250.54      6907043.09      2762530.06      6907533.53
      2762187.19      6908405.91
#Sta/Elev= 30
  4141.3  494.11  4323.2  492.19  4538.7   491.4  4553.6  490.18    4799  483.15
  4957.3  481.46  5005.7  481.57  5012.3  478.63    5019  474.26  5022.7  474.26
  5037.3  482.32  5085.3   481.2  5128.3  482.79  5214.3  482.24  5278.5  484.19
  5308.3  484.08  5407.7  485.48  5446.5   486.7  5530.5  487.34  5547.4   488.3
  5633.3  490.16  5654.8  491.42  5668.7  491.01  5698.5  491.89  5740.8  494.24
  5762.3  494.24  5831.3  496.29  5915.3  499.72  5923.4  500.66  5950.2     501
#Mann= 3 ,-1 , 0
  4141.3     .05       0  5005.7     .04       0  5037.3     .05       0
Bank Sta=5005.7,5037.3
XS Rating Curve= 0 ,0
Exp/Cntr=0.3,0.1

Type RM Length L Ch R = 1 ,1250    ,917,917,917
BEGIN DESCRIPTION:
Mapping XS 10cb2665
END DESCRIPTION:
XS GIS Cut Line= 3
      2762365.15      6906791.31      2762069.99      6907320.86
      2761965.87      6908366.44
#Sta/Elev= 30
  4401.1  487.82    4561  485.39  4657.2  484.81  4709.9  485.59  4754.4  483.99
    4863  482.73  4938.4  483.08  4960.1  481.66  4965.8  480.44  4973.2  474.87
  4981.8  476.27  4985.1  474.68  4985.7  474.18  4989.9  474.68  4996.1  478.88
  5003.5  479.56  5100.5  479.38  5128.1   479.9  5218.5   479.3  5498.3  483.32
    5510  484.48  5604.1   486.5  5630.6  487.88  5704.8  488.98  5761.2  491.28
  5805.5   491.3  5841.6  493.51  5861.7  493.48  5972.2  496.77  6058.1  500.84
#Mann= 3 ,-1 , 0
  4401.1     .05       0  4985.1     .04       0  4989.9     .05       0
Bank Sta=4985.1,4989.9
XS Rating Curve= 0 ,0
Exp/Cntr=0.3,0.1

Type RM Length L Ch R = 1 ,333     ,0,0,0
BEGIN DESCRIPTION:
Caney T17 1.0
END DESCRIPTION:
XS GIS Cut Line= 3
      2762201.01        6906736.      2761655.98      6906811.27
      2761350.99      6907536.01
#Sta/Elev= 30
  4449.8  488.17  4598.6  486.35    4687  484.51  4868.7  477.59  4939.4  476.58
  5002.6  476.94    5009  474.84  5011.9  471.84  5012.6  471.34  5016.9  471.84
  5021.4   475.9  5032.3  477.03    5054   476.3  5291.8  477.21  5314.3  475.84
    5321  477.25    5336  478.32  5368.5  479.15  5379.4  480.24  5397.6  479.89
  5403.1  480.49  5421.4  480.52    5456  482.99  5574.7   486.1  5585.6  487.06
  5603.8  486.69  5656.7  487.97  5694.1  489.74  5762.5  490.97  5786.3   492.1
#Mann= 3 ,-1 , 0
  4449.8     .05       0  5011.9     .04       0  5016.9     .05       0
Bank Sta=5011.9,5016.9
XS Rating Curve= 0 ,0
Exp/Cntr=0.3,0.1

Chan Stop Cuts=-1
Use User Specified Reach Order=0
Composite Channel Slope=5