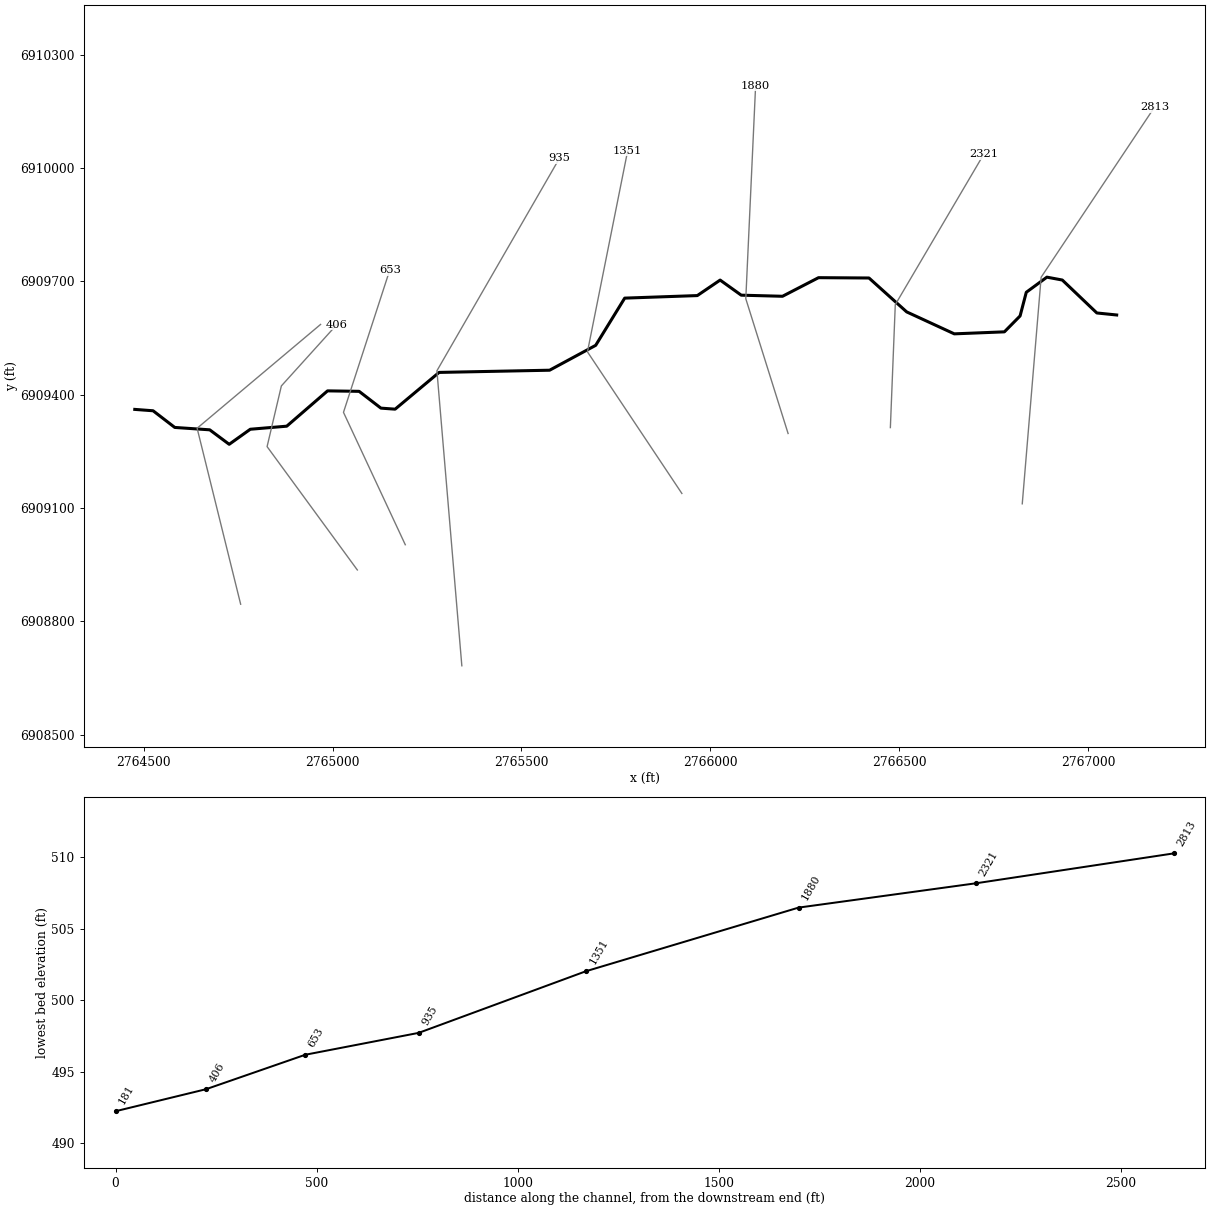
--- Caney T17_1.prj (project) ---

Proj Title=Caney T17_1 Base Level Engineering
Current Plan=p01
Default Exp/Contr=0.3,0.1
English Units
Geom File=g01
Flow File=f01
Plan File=p01
Y Axis Title=Elevation
X Axis Title(PF)=Main Channel Distance
X Axis Title(XS)=Station
BEGIN DESCRIPTION:
Caney T17_1
END DESCRIPTION:
DSS Export Rating Curves= 0
DSS Export Rating Curve Sorted= 0
DSS Export Volume Flow Curves= 0
DXF OffsetX= 0
DXF OffsetY= 0
DXF ScaleX= 1
DXF ScaleY= 10

--- Caney T17_1.p01 (plan) ---

Plan Title=Multiple Run
Short Identifier=Multiple
Geom File=g01
Flow File=f01
Subcritical Flow
K Sum by GR= 0
Std Step Tol= 0.01
Critical Tol= 0.01
Num of Std Step Trials= 20
Max Error Tol= 0.3
Flow Tol Ratio= 0.001
Split Flow NTrial= 30
Split Flow Tol= 0.02
Split Flow Ratio= 0.02
Log Output Level= 0
Friction Slope Method= 1
Unsteady Friction Slope Method= 2
Unsteady Bridges Friction Slope Method= 1
Parabolic Critical Depth
Global Vel Dist=  1 , 1 , 1
Global Log Level= 0
CheckData=True
Encroach Param= -1, 0, 0, 0
BEGIN DESCRIPTION:
Multiple Run
END DESCRIPTION:

--- Caney T17_1.f01 (steady flow) ---

Flow Title=Multiple
Program Version=4.10
Number of Profiles= 7
Profile Names=10-year,25-year,50-year,1pct_min,100-year,1pct_plu,500-year
River Rch & RM=Caney T17_1,Reach-1         ,2813
     236     299     348     202     403     805     542
Boundary for River Rch & Prof#=Caney T17_1,Reach-1         , 1
Up Type= 0
Dn Type= 3
Dn Slope=0.00755
Boundary for River Rch & Prof#=Caney T17_1,Reach-1         , 2
Up Type= 0
Dn Type= 3
Dn Slope=0.00755
Boundary for River Rch & Prof#=Caney T17_1,Reach-1         , 3
Up Type= 0
Dn Type= 3
Dn Slope=0.00755
Boundary for River Rch & Prof#=Caney T17_1,Reach-1         , 4
Up Type= 0
Dn Type= 3
Dn Slope=0.00755
Boundary for River Rch & Prof#=Caney T17_1,Reach-1         , 5
Up Type= 0
Dn Type= 3
Dn Slope=0.00755
Boundary for River Rch & Prof#=Caney T17_1,Reach-1         , 6
Up Type= 0
Dn Type= 3
Dn Slope=0.00755
Boundary for River Rch & Prof#=Caney T17_1,Reach-1         , 7
Up Type= 0
Dn Type= 3
Dn Slope=0.00755
DSS Import GetInterval= 0
DSS Import GetPeak= 0
DSS Import FillOption= 0

--- Caney T17_1.g01 (geometry) ---

Geom Title=Existing Conditions

River Reach=Caney T17_1,Reach-1
Reach XY= 30
      2767076.00      6909611.00      2767023.49      6909616.33
      2766932.03      6909703.55      2766891.23      6909711.16
      2766836.65      6909671.10      2766820.25      6909608.45
      2766778.70      6909566.35      2766646.03      6909561.04
      2766519.95      6909619.16      2766420.14      6909708.95
      2766286.51      6909709.79      2766191.16      6909660.53
      2766081.86      6909663.45      2766026.00      6909703.44
      2765965.56      6909662.38      2765773.30      6909655.64
      2765696.47      6909530.63      2765574.45      6909464.75
      2765281.86      6909458.93      2765165.38      6909361.61
      2765127.75      6909364.34      2765070.03      6909408.81
      2764986.48      6909410.06      2764878.42      6909316.54
      2764781.90      6909308.44      2764726.00      6909268.56
      2764674.50      6909306.91      2764581.92      6909313.22
      2764524.49      6909357.36      2764476.00      6909361.00

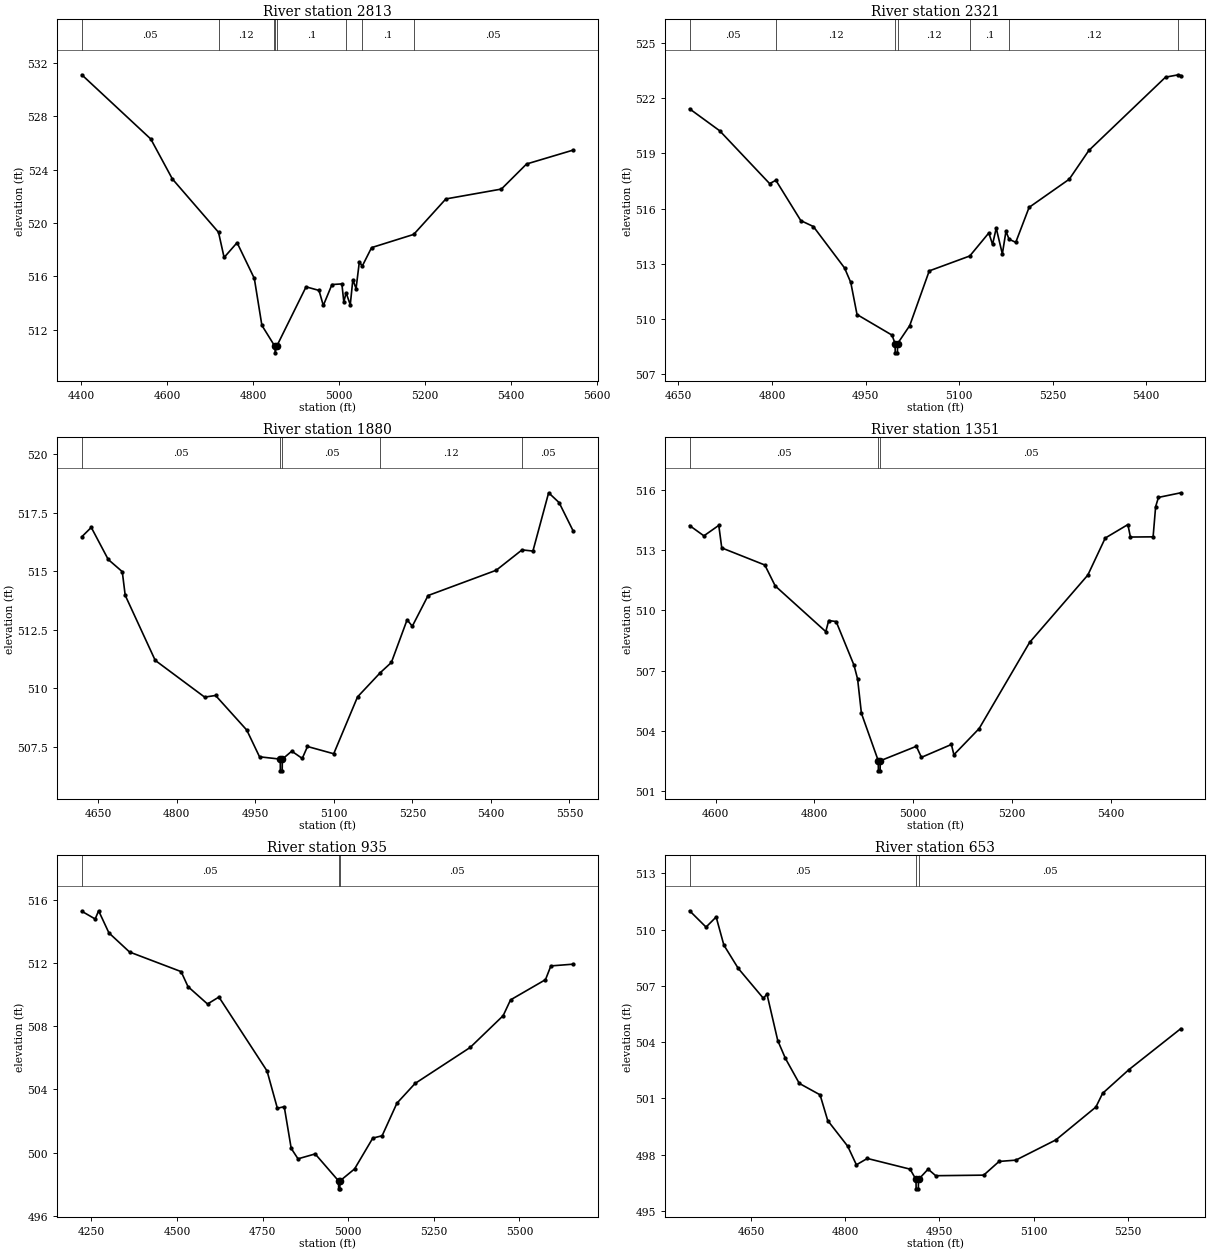
Type RM Length L Ch R = 1,2813,492,492,492
BEGIN DESCRIPTION:
Caney T17_1 5.0
END DESCRIPTION:
XS GIS Cut Line= 3
      2766826.00      6909110.99      2766876.00      6909711.00
      2767175.99      6910160.98
#Sta/Elev= 30
  4401.8  531.11  4562.4  526.29  4612.5  523.30  4719.9  519.30  4732.9  517.41
  4763.1  518.52  4803.2  515.84  4820.8  512.32  4848.7  510.87  4851.4  510.76
  4851.6  510.26  4855.4  510.76  4923.6  515.21  4953.7  514.94  4963.7  513.81
  4983.8  515.38  5006.9  515.43  5011.4  514.08  5016.8  514.76  5026.4  513.86
  5032.4  515.74  5039.9  515.08  5047.5  517.07  5054.4  516.77  5076.0  518.15
  5174.0  519.14  5248.8  521.80  5378.0  522.54  5436.6  524.42  5544.7  525.46
#Mann=8,-1,0
  4401.8    0.05       0  4719.9    0.12       0  4848.7     0.1       0
  4851.4    0.07       0  4855.4     0.1       0  5016.8    0.12       0
  5054.4     0.1       0  5174.0    0.05       0
Bank Sta=4851.4,4855.4
Exp/Cntr=0.3,0.1

Type RM Length L Ch R = 1,2321,441,441,441
BEGIN DESCRIPTION:
Mapping XS 4b3889b4
END DESCRIPTION:
XS GIS Cut Line= 3
      2766476.76      6909312.81      2766489.78      6909638.36
      2766723.92      6910036.39
#Sta/Elev= 30
  4668.0  521.42  4716.2  520.23  4796.3  517.36  4806.3  517.54  4846.3  515.35
  4866.4  515.03  4916.4  512.78  4926.4  511.99  4936.4  510.25  4992.6  509.13
  4997.4  508.67  4997.7  508.17  5001.2  508.17  5001.4  508.67  5020.9  509.65
  5052.2  512.62  5117.2  513.43  5147.7  514.68  5153.7  514.06  5159.6  514.94
  5169.4  513.54  5175.2  514.77  5180.2  514.34  5190.9  514.17  5212.3  516.07
  5276.7  517.60  5308.1  519.16  5431.0  523.14  5451.8  523.27  5455.6  523.23
#Mann=7,-1,0
  4668.0    0.05       0  4806.3    0.12       0  4997.4    0.07       0
  5001.4    0.12       0  5117.2     0.1       0  5180.2    0.12       0
  5451.8    0.05       0
Bank Sta=4997.4,5001.4
Exp/Cntr=0.3,0.1

Type RM Length L Ch R = 1,1880,529,529,529
BEGIN DESCRIPTION:
Mapping XS 767d026b
END DESCRIPTION:
XS GIS Cut Line= 3
      2766205.93      6909297.20      2766093.95      6909653.99
      2766119.92      6910217.54
#Sta/Elev= 30
  4618.7  516.47  4636.8  516.87  4669.2  515.50  4696.0  514.98  4701.6  513.97
  4758.9  511.19  4853.3  509.62  4874.2  509.69  4933.8  508.21  4958.1  507.07
  4997.7  506.97  4997.9  506.47  5001.4  506.47  5001.7  506.97  5019.7  507.31
  5039.7  507.00  5049.7  507.51  5099.8  507.20  5145.3  509.63  5189.0  510.67
  5209.9  511.10  5239.9  512.92  5249.9  512.65  5280.0  513.96  5410.1  515.04
  5459.4  515.91  5480.2  515.86  5510.2  518.35  5530.2  517.93  5556.8  516.73
#Mann=5,-1,0
  4618.7    0.05       0  4997.7    0.04       0  5001.7    0.05       0
  5189.0    0.12       0  5459.4    0.05       0
Bank Sta=4997.7,5001.7
Exp/Cntr=0.3,0.1

Type RM Length L Ch R = 1,1351,416,416,416
BEGIN DESCRIPTION:
Mapping XS f6b0d0a3
END DESCRIPTION:
XS GIS Cut Line= 3
      2765924.66      6909138.39      2765674.68      6909513.36
      2765781.10      6910045.46
#Sta/Elev= 30
  4547.6  514.21  4576.5  513.70  4606.6  514.22  4612.6  513.10  4699.7  512.25
  4720.7  511.21  4822.9  508.94  4828.9  509.49  4843.9  509.44  4880.0  507.27
  4887.3  506.58  4895.0  504.88  4929.1  502.52  4929.3  502.02  4932.8  502.02
  4933.1  502.52  5006.1  503.24  5016.3  502.69  5076.9  503.33  5082.0  502.82
  5133.0  504.12  5235.0  508.40  5352.8  511.75  5388.0  513.59  5433.8  514.26
  5438.9  513.64  5484.8  513.65  5489.9  515.15  5495.6  515.61  5540.9  515.84
#Mann=3,-1,0
  4547.6    0.05       0  4929.1    0.04       0  4933.1    0.05       0
Bank Sta=4929.1,4933.1
Exp/Cntr=0.3,0.1

Type RM Length L Ch R = 1,935,282,282,282
BEGIN DESCRIPTION:
Mapping XS f816c1d9
END DESCRIPTION:
XS GIS Cut Line= 3
      2765342.04      6908682.08      2765276.07      6909463.32
      2765600.78      6910026.38
#Sta/Elev= 30
  4222.3  515.28  4261.4  514.79  4271.4  515.31  4301.5  513.91  4361.7  512.70
  4512.2  511.46  4532.3  510.51  4589.3  509.41  4622.6  509.85  4763.1  505.17
  4793.2  502.81  4813.3  502.91  4833.6  500.27  4853.5  499.61  4903.6  499.92
  4971.9  498.21  4972.1  497.71  4975.6  497.71  4975.9  498.21  5018.6  498.97
  5071.7  500.92  5099.0  501.07  5142.2  503.13  5195.2  504.38  5356.1  506.66
  5452.3  508.67  5473.9  509.67  5575.9  510.95  5591.6  511.82  5656.3  511.93
#Mann=3,-1,0
  4222.3    0.05       0  4971.9    0.04       0  4975.9    0.05       0
Bank Sta=4971.9,4975.9
Exp/Cntr=0.3,0.1

Type RM Length L Ch R = 1,653,247,247,247
BEGIN DESCRIPTION:
Mapping XS c239acc3
END DESCRIPTION:
XS GIS Cut Line= 3
      2765192.29      6909002.64      2765028.64      6909353.17
      2765151.14      6909729.80
#Sta/Elev= 30
  4551.8  511.00  4578.0  510.13  4594.1  510.67  4606.4  509.17  4629.3  507.93
  4669.5  506.33  4675.0  506.57  4692.3  504.08  4704.5  503.13  4726.6  501.80
  4759.7  501.19  4771.9  499.82  4803.8  498.45  4817.6  497.46  4835.0  497.80
  4903.1  497.23  4912.6  496.68  4912.8  496.18  4916.3  496.18  4916.6  496.68
  4931.9  497.23  4944.0  496.88  5020.5  496.91  5045.0  497.64  5071.7  497.71
  5135.6  498.79  5199.3  500.54  5210.0  501.27  5251.8  502.53  5334.7  504.72
#Mann=3,-1,0
  4551.8    0.05       0  4912.6    0.04       0  4916.6    0.05       0
Bank Sta=4912.6,4916.6
Exp/Cntr=0.3,0.1

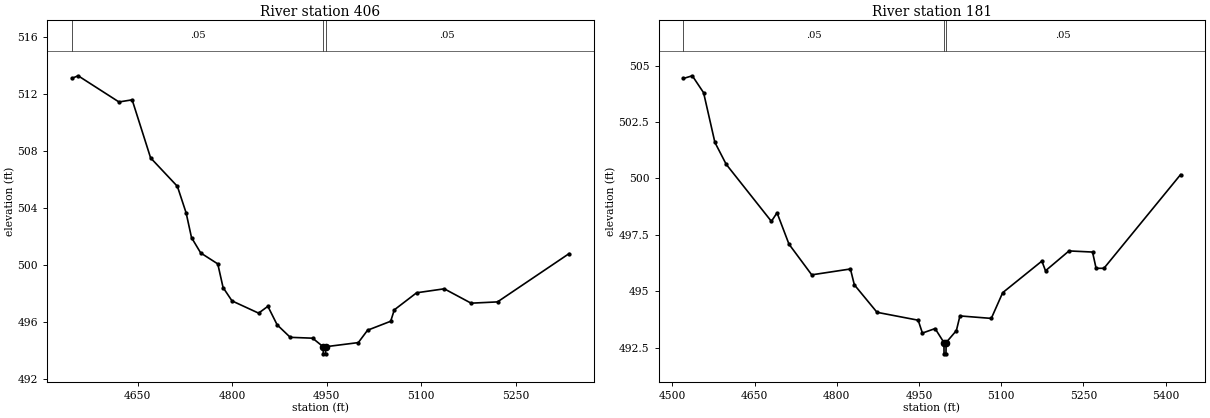
Type RM Length L Ch R = 1,406,225,225,225
BEGIN DESCRIPTION:
Mapping XS a3737581
END DESCRIPTION:
XS GIS Cut Line= 4
      2765065.33      6908935.80      2764826.36      6909262.46
      2764864.18      6909423.15      2765011.16      6909585.75
#Sta/Elev= 30
  4545.6  513.13  4555.6  513.31  4620.4  511.47  4641.3  511.62  4670.6  507.54
  4713.1  505.54  4727.0  503.67  4735.5  501.94  4750.1  500.86  4777.2  500.09
  4785.6  498.43  4799.8  497.49  4842.0  496.63  4856.7  497.11  4871.4  495.81
  4892.2  494.93  4927.7  494.87  4944.4  494.27  4944.7  493.77  4948.2  493.77
  4948.4  494.27  5000.2  494.56  5014.9  495.43  5051.6  496.06  5057.3  496.86
  5092.7  498.06  5136.6  498.34  5179.2  497.33  5221.1  497.42  5334.6  500.81
#Mann=3,-1,0
  4545.6    0.05       0  4944.4    0.04       0  4948.4    0.05       0
Bank Sta=4944.4,4948.4
Exp/Cntr=0.3,0.1

Type RM Length L Ch R = 1,181,0,0,0
BEGIN DESCRIPTION:
Caney T17_1 1.0
END DESCRIPTION:
XS GIS Cut Line= 3
      2764756.36      6908845.14      2764641.09      6909311.10
      2764967.97      6909585.99
#Sta/Elev= 30
  4520.0  504.43  4536.3  504.55  4556.9  503.80  4577.5  501.60  4598.1  500.63
  4680.6  498.10  4690.9  498.48  4712.7  497.09  4754.2  495.73  4824.8  495.99
  4831.9  495.29  4873.3  494.07  4948.4  493.72  4956.1  493.15  4979.3  493.35
  4995.4  492.73  4995.6  492.23  4999.1  492.23  4999.4  492.73  5018.1  493.26
  5024.6  493.91  5081.8  493.80  5102.6  494.94  5174.1  496.34  5180.7  495.91
  5223.6  496.79  5266.5  496.74  5273.0  496.02  5287.3  496.02  5427.1  500.17
#Mann=3,-1,0
  4520.0    0.05       0  4995.4    0.04       0  4999.4    0.05       0
Bank Sta=4995.4,4999.4
Exp/Cntr=0.3,0.1

Chan Stop Cuts=-1