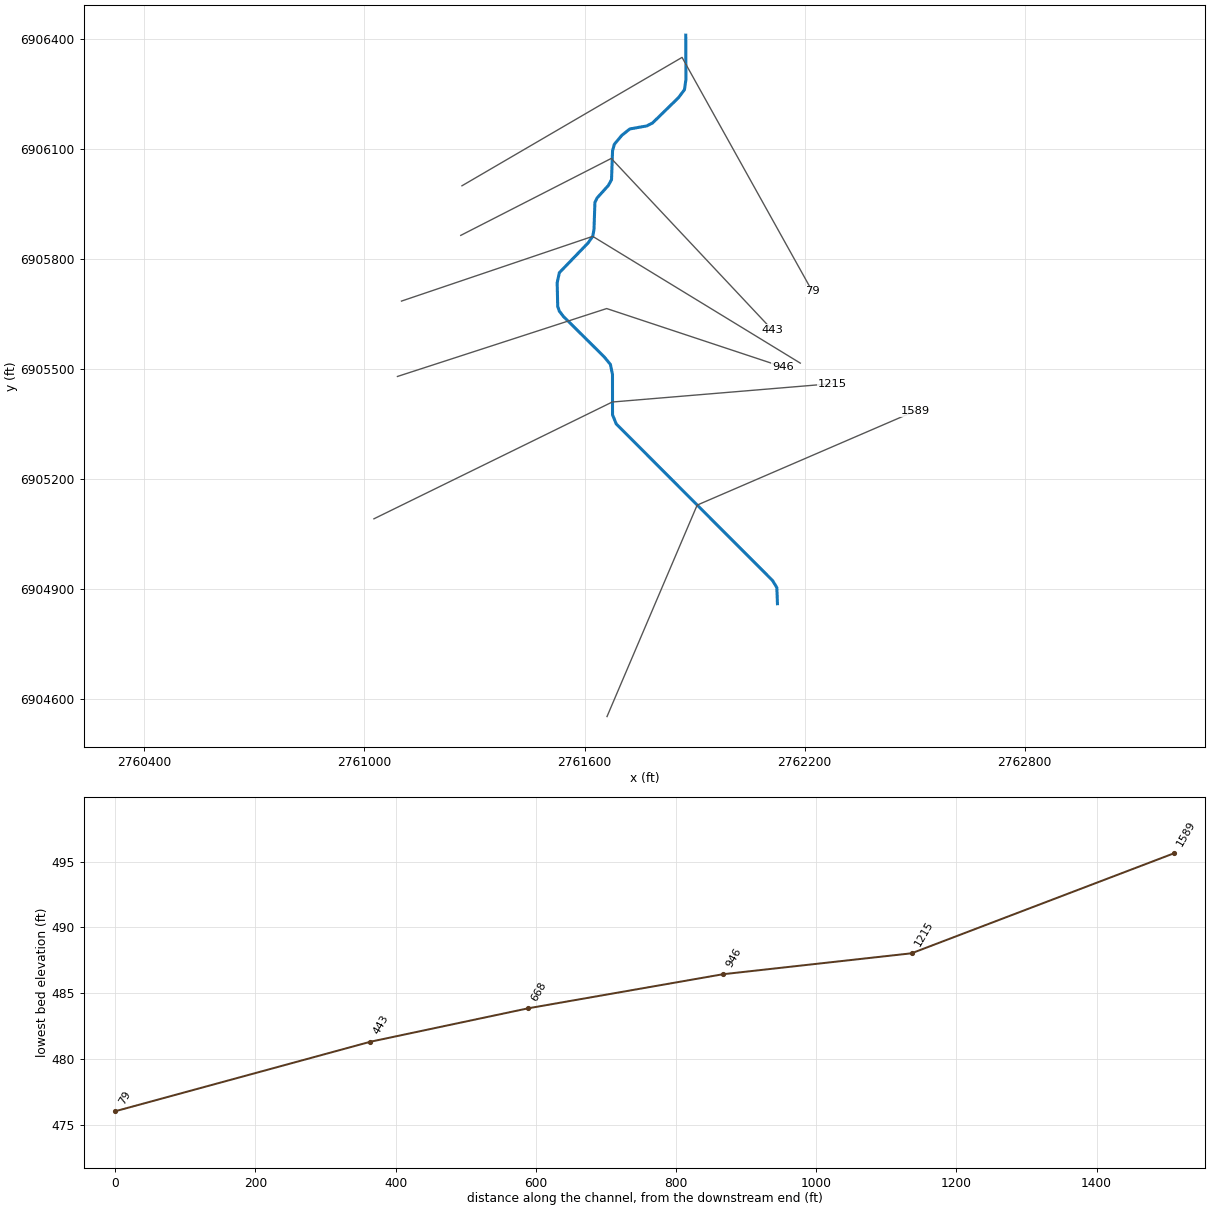
--- Caney T18.prj (project) ---

Proj Title=Caney T18 Base Level Engineering
Current Plan=p01
Default Exp/Contr=0.3,0.1
English Units
Geom File=g01
Flow File=f01
Plan File=p01
BEGIN DESCRIPTION:
Caney T18
END DESCRIPTION:

--- Caney T18.p01 (plan) ---

Plan Title=Multiple Run
Short Identifier=Multiple
Geom File=g01
Flow File=f01
Subcritical Flow
K Sum by GR= 0
Std Step Tol= 0.01
Critical Tol= 0.01
Num of Std Step Trials= 20
Max Error Tol= 0.3
Flow Tol Ratio= 0.001
Split Flow NTrial= 30
Split Flow Tol= 0.02
Split Flow Ratio= 0.02
Log Output Level= 0
Friction Slope Method= 1
Unsteady Friction Slope Method= 2
Unsteady Bridges Friction Slope Method= 1
Parabolic Critical Depth
Global Vel Dist=  1 , 1 , 1
Global Log Level= 0
CheckData=True
Encroach Param= -1, 0, 0, 0
BEGIN DESCRIPTION:
Multiple Run
END DESCRIPTION:

--- Caney T18.f01 (steady flow) ---

Flow Title=Multiple
Number of Profiles=7
Profile Names=10-year,25-year,50-year,1pct_min,100-year,1pct_plu,500-year
River Rch & RM= Caney T18,Reach-1,1589
     184     231     267     155     309     616     411
Boundary for River Rch & Prof#=Caney T18,Reach-1,1
Up Type=0
Dn Type=3
Dn Slope=0.005
Boundary for River Rch & Prof#=Caney T18,Reach-1,2
Up Type=0
Dn Type=3
Dn Slope=0.005
Boundary for River Rch & Prof#=Caney T18,Reach-1,3
Up Type=0
Dn Type=3
Dn Slope=0.005
Boundary for River Rch & Prof#=Caney T18,Reach-1,4
Up Type=0
Dn Type=3
Dn Slope=0.005
Boundary for River Rch & Prof#=Caney T18,Reach-1,5
Up Type=0
Dn Type=3
Dn Slope=0.005
Boundary for River Rch & Prof#=Caney T18,Reach-1,6
Up Type=0
Dn Type=3
Dn Slope=0.005
Boundary for River Rch & Prof#=Caney T18,Reach-1,7
Up Type=0
Dn Type=3
Dn Slope=0.005

--- Caney T18.g01 (geometry) ---

Geom Title=Existing Conditions

River Reach=Caney T18,Reach-1
Reach XY= 30
      2762126.00      6904861.00      2762124.32      6904904.86
      2762112.53      6904924.27      2761686.48      6905351.20
      2761676.40      6905376.16      2761676.27      6905486.11
      2761670.53      6905513.45      2761653.14      6905534.53
      2761542.40      6905644.25      2761531.40      6905658.57
      2761526.93      6905671.48      2761525.50      6905736.03
      2761531.41      6905763.42      2761609.51      6905844.26
      2761622.38      6905862.50      2761625.87      6905881.05
      2761628.36      6905955.02      2761634.19      6905967.04
      2761665.11      6906001.37      2761673.64      6906016.98
      2761676.47      6906095.91      2761681.42      6906113.67
      2761702.05      6906138.19      2761723.43      6906155.26
      2761769.92      6906163.55      2761785.68      6906171.78
      2761856.41      6906240.79      2761872.51      6906262.44
      2761876.52      6906290.78      2761876.00      6906411.00

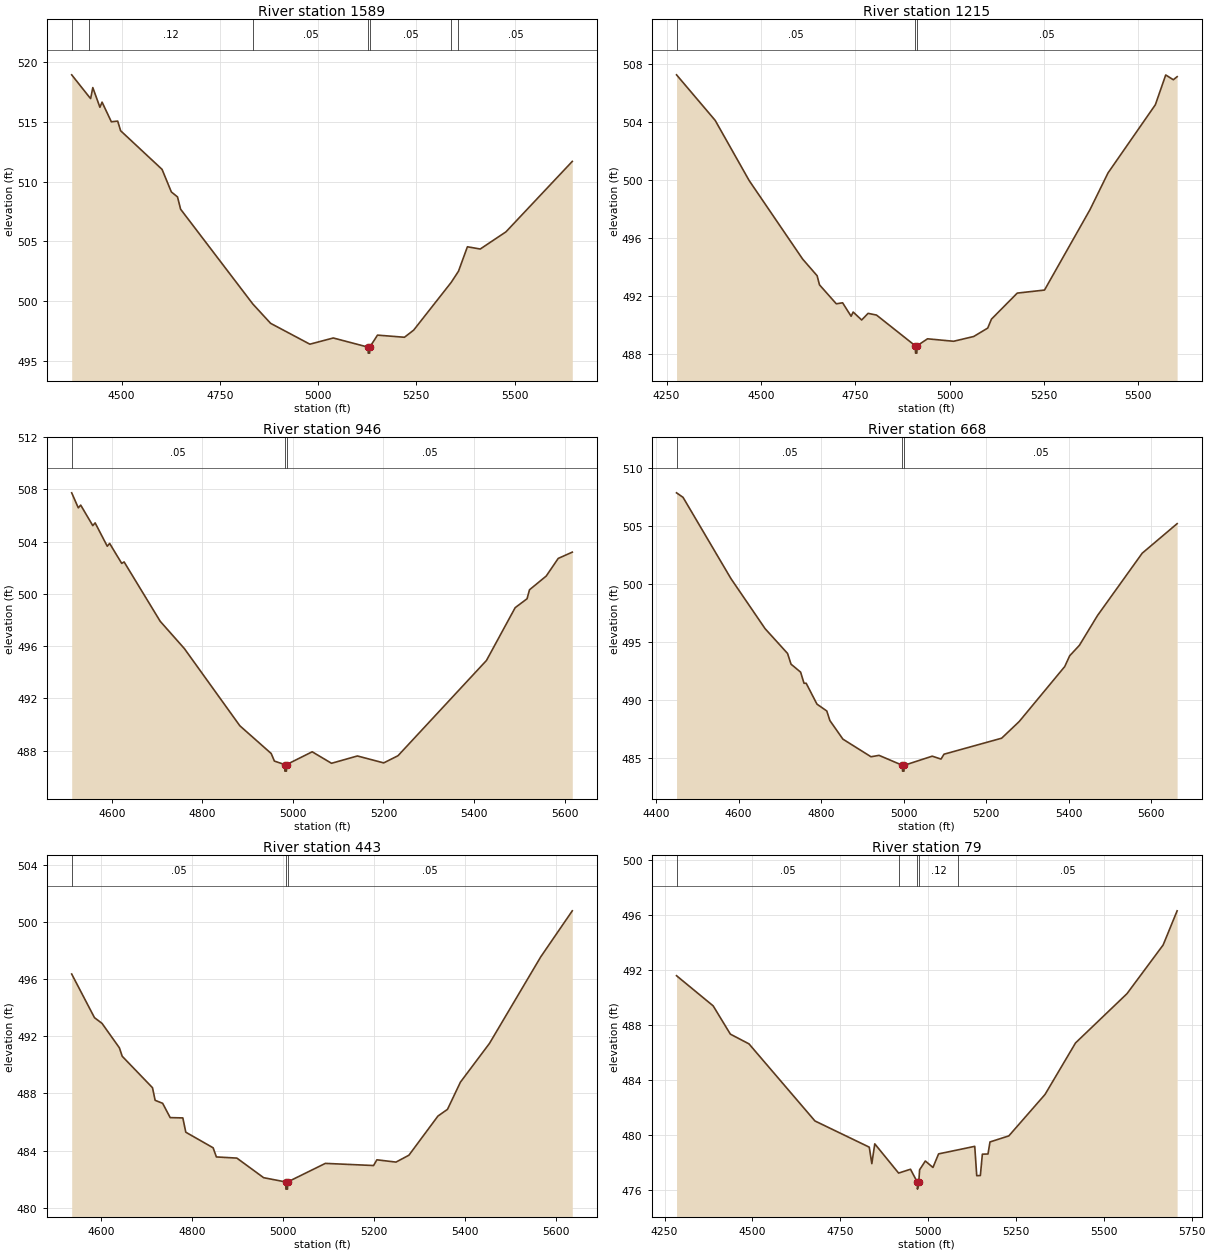
Type RM Length L Ch R = 1,1589,374,374,374
BEGIN DESCRIPTION:
Caney T18 4.0
END DESCRIPTION:
XS GIS Cut Line= 3
      2761661.36      6904553.38      2761907.11      6905129.88
      2762501.03      6905386.01
#Sta/Elev= 30
  4373.3  518.96  4417.8  517.11  4421.5  516.97  4427.0  517.89  4445.1  516.24
  4450.6  516.67  4474.2  515.02  4490.3  515.08  4497.8  514.27  4603.2  511.03
  4626.8  509.14  4642.5  508.72  4650.4  507.69  4834.1  499.74  4879.3  498.12
  4979.2  496.37  5038.8  496.89  5127.5  496.12  5127.7  495.62  5131.2  495.62
  5131.5  496.12  5151.3  497.13  5219.8  496.95  5243.3  497.55  5338.9  501.56
  5357.3  502.49  5380.0  504.54  5412.6  504.35  5478.0  505.79  5646.8  511.70
#Mann=7,-1,0
  4373.3    0.05       0  4417.8    0.12       0  4834.1    0.05       0
  5127.5    0.04       0  5131.5    0.05       0  5338.9    0.12       0
  5357.3    0.05       0
Bank Sta=5127.5,5131.5
Exp/Cntr=0.3,0.1

Type RM Length L Ch R = 1,1215,269,269,269
BEGIN DESCRIPTION:
Caney T18 3.0
END DESCRIPTION:
XS GIS Cut Line= 3
      2761025.95      6905092.48      2761675.64      6905410.85
      2762276.05      6905461.00
#Sta/Elev= 30
  4276.5  507.27  4378.9  504.12  4468.9  499.96  4610.6  494.53  4648.9  493.38
  4655.2  492.75  4699.7  491.44  4716.4  491.51  4738.9  490.58  4744.4  490.87
  4766.9  490.32  4783.9  490.78  4806.3  490.66  4909.3  488.53  4909.6  488.03
  4913.1  488.03  4913.3  488.53  4941.3  489.02  5010.4  488.85  5063.7  489.18
  5100.7  489.76  5110.7  490.38  5179.0  492.18  5251.2  492.39  5371.7  497.95
  5419.5  500.49  5544.8  505.20  5572.3  507.26  5592.4  506.93  5602.5  507.14
#Mann=3,-1,0
  4276.5    0.05       0  4909.3    0.04       0  4913.3    0.05       0
Bank Sta=4909.3,4913.3
Exp/Cntr=0.3,0.1

Type RM Length L Ch R = 1,946,278,278,278
BEGIN DESCRIPTION:
Mapping XS e8b9a22a
END DESCRIPTION:
XS GIS Cut Line= 3
      2761090.06      6905480.52      2761660.42      6905665.69
      2762140.92      6905506.31
#Sta/Elev= 30
  4511.3  507.74  4525.9  506.59  4531.2  506.80  4557.9  505.23  4563.1  505.44
  4589.9  503.65  4595.1  503.87  4621.8  502.34  4627.1  502.45  4706.8  497.91
  4760.2  495.82  4882.8  489.91  4952.0  487.79  4959.1  487.21  4981.9  486.94
  4982.2  486.44  4985.7  486.44  4985.9  486.94  5042.6  487.92  5085.3  487.04
  5142.5  487.60  5200.6  487.07  5232.2  487.62  5427.6  494.91  5491.0  498.95
  5517.2  499.63  5522.7  500.32  5559.6  501.37  5586.1  502.72  5617.2  503.20
#Mann=3,-1,0
  4511.3    0.05       0  4981.9    0.04       0  4985.9    0.05       0
Bank Sta=4981.9,4985.9
Exp/Cntr=0.3,0.1

Type RM Length L Ch R = 1,668,225,225,225
BEGIN DESCRIPTION:
Caney T18 2.0
END DESCRIPTION:
XS GIS Cut Line= 3
      2761101.04      6905686.01      2761622.38      6905862.50
      2762188.30      6905516.90
#Sta/Elev= 30
  4449.6  507.86  4465.4  507.47  4581.5  500.46  4664.3  496.14  4718.8  494.00
  4727.1  493.08  4750.4  492.39  4758.6  491.43  4763.9  491.43  4790.0  489.63
  4813.8  489.04  4821.4  488.21  4852.9  486.61  4921.0  485.09  4940.5  485.21
  4997.3  484.35  4997.5  483.85  5001.0  483.85  5001.3  484.35  5069.4  485.14
  5090.7  484.89  5098.0  485.31  5237.7  486.69  5280.3  488.13  5390.6  492.87
  5402.6  493.80  5426.1  494.70  5470.0  497.27  5578.4  502.65  5663.1  505.20
#Mann=3,-1,0
  4449.6    0.05       0  4997.3    0.04       0  5001.3    0.05       0
Bank Sta=4997.3,5001.3
Exp/Cntr=0.3,0.1

Type RM Length L Ch R = 1,443,364,364,364
BEGIN DESCRIPTION:
Mapping XS 1994aaba
END DESCRIPTION:
XS GIS Cut Line= 3
      2761262.64      6905865.15      2761672.93      6906074.91
      2762111.01      6905608.34
#Sta/Elev= 30
  4535.0  496.35  4585.1  493.30  4601.7  492.90  4639.9  491.19  4646.1  490.60
  4712.7  488.40  4718.5  487.52  4735.0  487.31  4751.6  486.31  4779.4  486.29
  4785.9  485.29  4846.0  484.20  4853.2  483.56  4898.2  483.48  4957.1  482.11
  5005.8  481.81  5006.1  481.31  5009.6  481.31  5009.8  481.81  5092.8  483.11
  5198.8  482.96  5206.1  483.36  5248.1  483.20  5276.5  483.68  5340.4  486.42
  5361.4  486.89  5389.8  488.79  5453.7  491.50  5566.6  497.56  5635.8  500.77
#Mann=3,-1,0
  4535.0    0.05       0  5005.8    0.04       0  5009.8    0.05       0
Bank Sta=5005.8,5009.8
Exp/Cntr=0.3,0.1

Type RM Length L Ch R = 1,79,0,0,0
BEGIN DESCRIPTION:
Caney T18 1.0
END DESCRIPTION:
XS GIS Cut Line= 3
      2761265.93      6906000.36      2761865.95      6906350.37
      2762221.12      6905712.54
#Sta/Elev= 30
  4284.0  491.59  4388.3  489.39  4437.2  487.33  4490.2  486.62  4677.9  481.00
  4832.5  479.09  4839.8  477.89  4848.2  479.33  4916.0  477.20  4949.9  477.48
  4969.4  476.53  4969.7  476.03  4973.4  476.53  4975.8  477.44  4992.1  478.08
  5013.8  477.61  5029.8  478.60  5086.3  478.90  5132.7  479.15  5138.4  477.01
  5148.7  477.02  5154.4  478.58  5170.4  478.59  5176.1  479.47  5229.7  479.91
  5332.7  482.93  5419.6  486.69  5566.0  490.28  5668.9  493.83  5708.7  496.32
#Mann=5,-1,0
  4284.0    0.05       0  4916.0    0.12       0  4969.4    0.07       0
  4973.4    0.12       0  5086.3    0.05       0
Bank Sta=4969.4,4973.4
Exp/Cntr=0.3,0.1

Chan Stop Cuts=-1