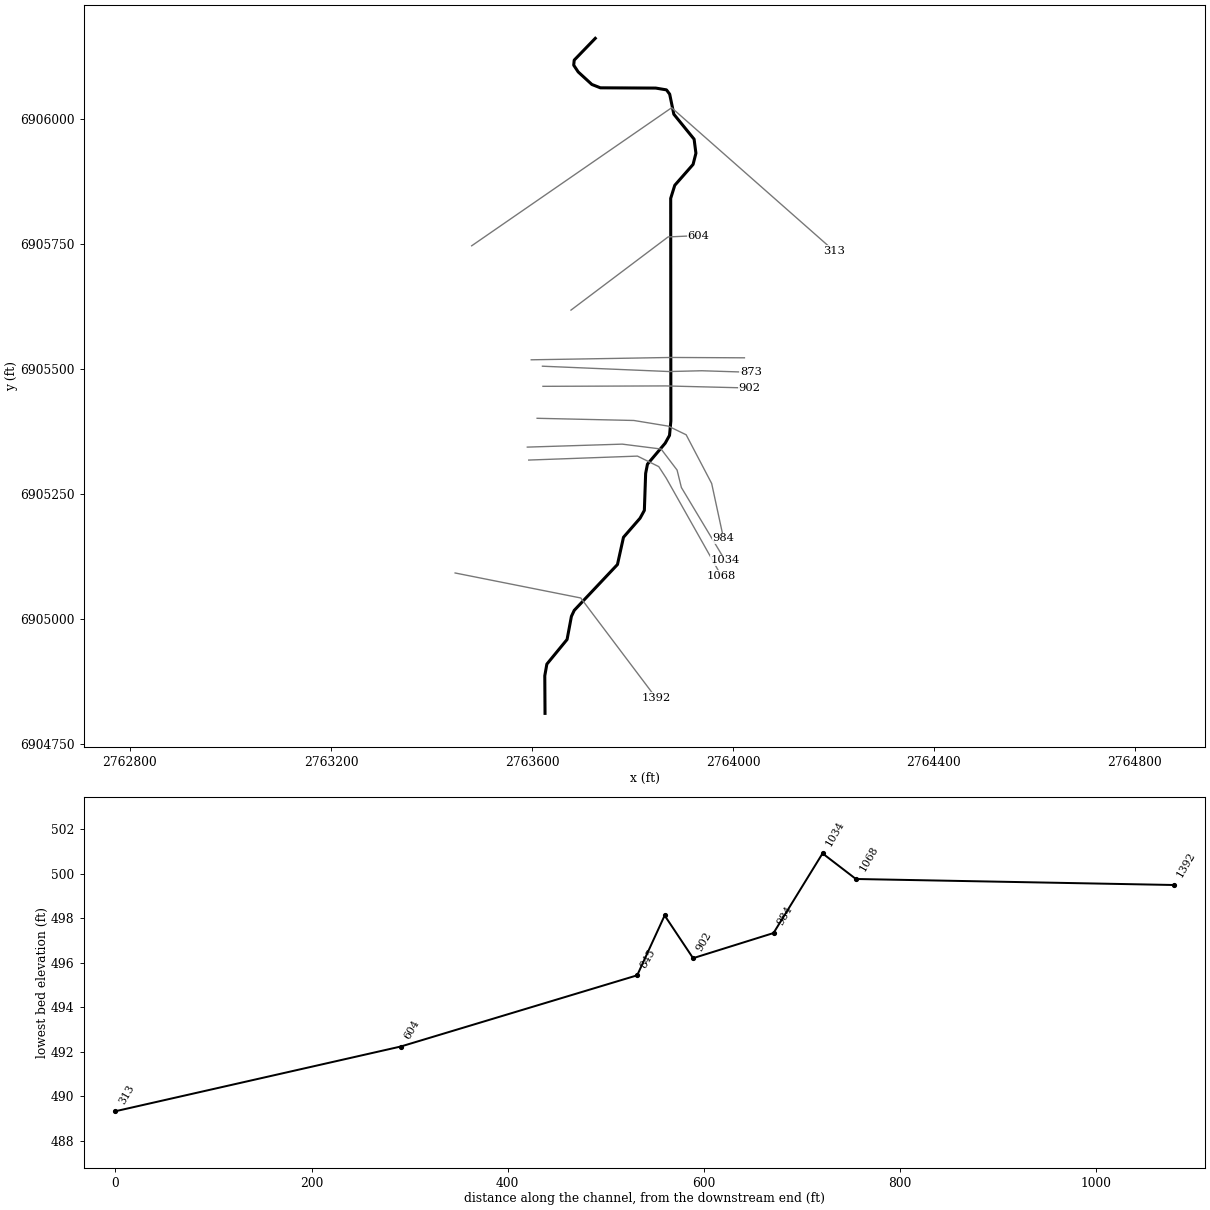
--- Caney T19.prj (project) ---

Proj Title=Caney T19 Base Level Engineering
Current Plan=p01
Default Exp/Contr=0.3,0.1
English Units
Geom File=g01
Flow File=f01
Plan File=p01
Y Axis Title=Elevation
X Axis Title(PF)=Main Channel Distance
X Axis Title(XS)=Station
BEGIN DESCRIPTION:
Caney T19
END DESCRIPTION:
DSS Export Rating Curves= 0
DSS Export Rating Curve Sorted= 0
DSS Export Volume Flow Curves= 0
DXF OffsetX= 0
DXF OffsetY= 0
DXF ScaleX= 1
DXF ScaleY= 10

--- Caney T19.p01 (plan) ---

Plan Title=Multiple Run
Short Identifier=Multiple
Geom File=g01
Flow File=f01
Subcritical Flow
K Sum by GR= 0
Std Step Tol= 0.01
Critical Tol= 0.01
Num of Std Step Trials= 20
Max Error Tol= 0.3
Flow Tol Ratio= 0.001
Split Flow NTrial= 30
Split Flow Tol= 0.02
Split Flow Ratio= 0.02
Log Output Level= 0
Friction Slope Method= 1
Unsteady Friction Slope Method= 2
Unsteady Bridges Friction Slope Method= 1
Parabolic Critical Depth
Global Vel Dist=  1 , 1 , 1
Global Log Level= 0
CheckData=True
Encroach Param= -1, 0, 0, 0
BEGIN DESCRIPTION:
Multiple Run
END DESCRIPTION:

--- Caney T19.f01 (steady flow) ---

Flow Title=Multiple
Program Version=4.10
Number of Profiles= 7
Profile Names=10-year,25-year,50-year,1pct_min,100-year,1pct_plu,500-year
River Rch & RM=Caney T19,Reach-1         ,1392
     130     158     180     102     203     406     260
Boundary for River Rch & Prof#=Caney T19,Reach-1         , 1
Up Type= 0
Dn Type= 3
Dn Slope=0.01
Boundary for River Rch & Prof#=Caney T19,Reach-1         , 2
Up Type= 0
Dn Type= 3
Dn Slope=0.01
Boundary for River Rch & Prof#=Caney T19,Reach-1         , 3
Up Type= 0
Dn Type= 3
Dn Slope=0.01
Boundary for River Rch & Prof#=Caney T19,Reach-1         , 4
Up Type= 0
Dn Type= 3
Dn Slope=0.01
Boundary for River Rch & Prof#=Caney T19,Reach-1         , 5
Up Type= 0
Dn Type= 3
Dn Slope=0.01
Boundary for River Rch & Prof#=Caney T19,Reach-1         , 6
Up Type= 0
Dn Type= 3
Dn Slope=0.01
Boundary for River Rch & Prof#=Caney T19,Reach-1         , 7
Up Type= 0
Dn Type= 3
Dn Slope=0.01
DSS Import GetInterval= 0
DSS Import GetPeak= 0
DSS Import FillOption= 0

--- Caney T19.g01 (geometry) ---

Geom Title=Existing Conditions

River Reach=Caney T19,Reach-1
Reach XY= 30
      2763626.00      6904811.00      2763625.52      6904886.20
      2763629.63      6904909.50      2763669.89      6904958.82
      2763678.50      6905004.96      2763684.16      6905017.05
      2763770.16      6905108.71      2763782.14      6905163.17
      2763815.16      6905201.35      2763823.67      6905216.97
      2763826.24      6905290.90      2763829.86      6905309.40
      2763865.15      6905351.35      2763873.74      6905366.94
      2763876.43      6905395.82      2763876.09      6905840.97
      2763884.19      6905867.08      2763920.63      6905908.82
      2763926.29      6905931.19      2763922.67      6905959.31
      2763882.34      6906009.21      2763874.07      6906049.32
      2763867.72      6906057.93      2763846.43      6906061.51
      2763736.15      6906062.04      2763719.23      6906068.74
      2763692.05      6906093.76      2763683.09      6906107.29
      2763684.09      6906117.42      2763726.00      6906161.00

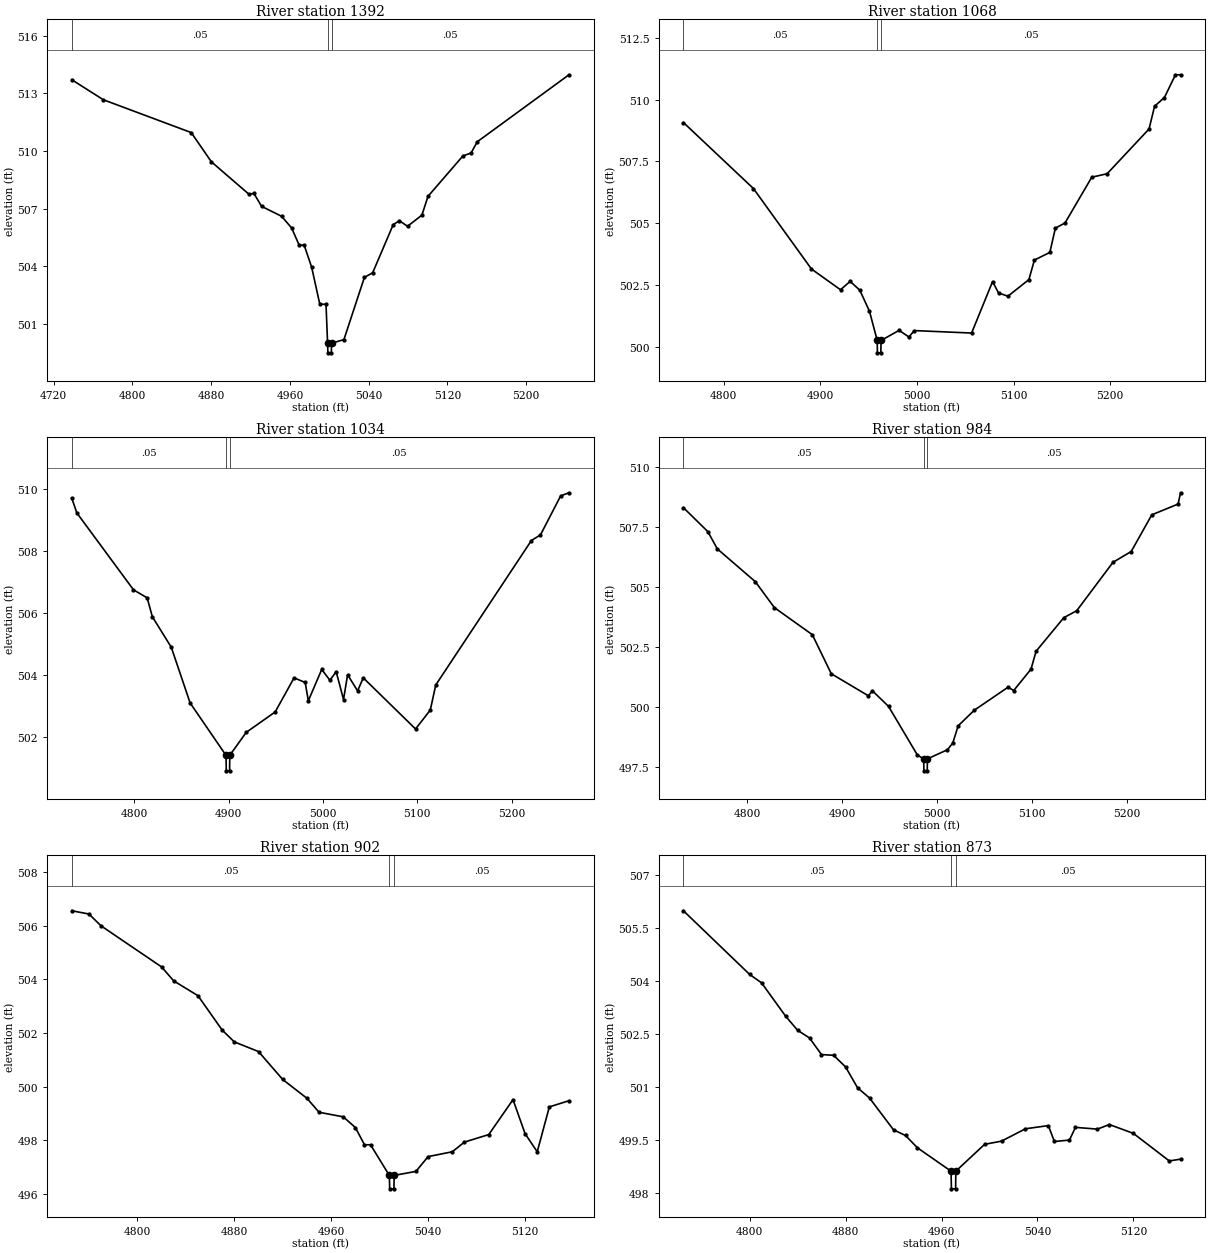
Type RM Length L Ch R = 1,1392,324,324,324
BEGIN DESCRIPTION:
Caney T19 2.0
END DESCRIPTION:
XS GIS Cut Line= 3
      2763447.08      6905091.78      2763697.09      6905041.78
      2763847.11      6904841.75
#Sta/Elev= 30
  4738.4  513.71  4770.4  512.67  4859.7  510.96  4880.1  509.44  4918.3  507.75
  4923.4  507.79  4931.1  507.12  4951.5  506.60  4961.7  505.99  4969.3  505.10
  4974.4  505.10  4982.0  503.95  4990.3  502.02  4996.6  502.02  4998.2  499.99
  4998.5  499.49  5002.0  499.49  5002.2  499.99  5014.8  500.18  5035.6  503.42
  5044.0  503.66  5064.8  506.16  5071.1  506.37  5079.4  506.08  5094.0  506.66
  5100.2  507.64  5135.6  509.74  5144.0  509.90  5150.2  510.48  5243.4  513.97
#Mann=3,-1,0
  4738.4    0.05       0  4998.2    0.04       0  5002.2    0.05       0
Bank Sta=4998.2,5002.2
Exp/Cntr=0.3,0.1

Type RM Length L Ch R = 1,1068,34,34,34
BEGIN DESCRIPTION:
Mapping XS 71e9fc78
END DESCRIPTION:
XS GIS Cut Line= 5
      2763593.54      6905317.59      2763810.03      6905325.51
      2763852.34      6905304.47      2763867.20      6905281.46
      2763976.47      6905086.69
#Sta/Elev= 30
  4758.3  509.07  4830.8  506.40  4890.8  503.15  4920.9  502.31  4930.9  502.65
  4940.9  502.29  4950.9  501.44  4958.9  500.26  4959.1  499.76  4962.6  499.76
  4962.9  500.26  4981.6  500.67  4991.7  500.40  4997.3  500.66  5056.6  500.56
  5078.3  502.64  5084.5  502.18  5094.2  502.05  5115.9  502.72  5121.6  503.51
  5137.6  503.82  5143.3  504.80  5153.3  505.01  5181.0  506.86  5196.9  507.00
  5240.3  508.81  5246.0  509.73  5256.2  510.08  5267.6  511.00  5272.9  511.00
#Mann=3,-1,0
  4758.3    0.05       0  4958.9    0.04       0  4962.9    0.05       0
Bank Sta=4958.9,4962.9
Exp/Cntr=0.3,0.1

Type RM Length L Ch R = 1,1034,50,50,50
BEGIN DESCRIPTION:
Mapping XS e7aebd79
END DESCRIPTION:
XS GIS Cut Line= 6
      2763590.75      6905343.50      2763779.75      6905349.45
      2763856.97      6905339.66      2763888.80      6905297.58
      2763897.35      6905262.72      2763984.51      6905116.80
#Sta/Elev= 30
  4734.0  509.70  4739.3  509.23  4799.3  506.75  4813.8  506.49  4819.3  505.88
  4839.3  504.90  4859.3  503.10  4897.3  501.41  4897.6  500.91  4901.1  500.91
  4901.3  501.41  4918.7  502.15  4949.4  502.81  4969.4  503.91  4981.2  503.76
  4984.5  503.17  4998.7  504.18  5007.4  503.83  5014.0  504.11  5021.8  503.21
  5026.1  504.01  5036.7  503.49  5042.7  503.91  5098.1  502.26  5113.7  502.87
  5119.5  503.68  5220.8  508.34  5230.4  508.52  5251.8  509.78  5260.6  509.88
#Mann=3,-1,0
  4734.0    0.05       0  4897.3    0.04       0  4901.3    0.05       0
Bank Sta=4897.3,4901.3
Exp/Cntr=0.3,0.1

Type RM Length L Ch R = 1,984,82,82,82
BEGIN DESCRIPTION:
Mapping XS f3b2bf31
END DESCRIPTION:
XS GIS Cut Line= 6
      2763610.26      6905401.13      2763802.78      6905396.77
      2763871.24      6905385.47      2763906.85      6905368.16
      2763957.64      6905270.70      2763981.12      6905161.38
#Sta/Elev= 30
  4732.7  508.31  4758.4  507.31  4768.4  506.59  4808.5  505.22  4828.5  504.14
  4868.5  503.01  4888.5  501.38  4927.6  500.46  4931.8  500.67  4948.8  500.02
  4979.2  497.99  4985.8  497.83  4986.1  497.33  4989.6  497.33  4989.8  497.83
  5010.9  498.21  5016.5  498.49  5022.2  499.21  5039.2  499.86  5074.8  500.82
  5080.7  500.68  5098.9  501.57  5104.3  502.32  5133.5  503.72  5147.1  504.01
  5185.3  506.03  5204.5  506.48  5226.2  508.01  5253.9  508.46  5256.5  508.93
#Mann=3,-1,0
  4732.7    0.05       0  4985.8    0.04       0  4989.8    0.05       0
Bank Sta=4985.8,4989.8
Exp/Cntr=0.3,0.1

Type RM Length L Ch R = 1,902,29,29,29
BEGIN DESCRIPTION:
Mapping XS bed9301b
END DESCRIPTION:
XS GIS Cut Line= 3
      2763621.88      6905465.06      2763865.96      6905465.87
      2764032.23      6905461.71
#Sta/Elev= 30
  4745.8  506.55  4759.9  506.43  4769.9  505.99  4819.9  504.46  4829.9  503.94
  4849.9  503.39  4869.9  502.11  4879.9  501.67  4899.9  501.31  4919.9  500.27
  4939.9  499.57  4949.9  499.05  4969.9  498.88  4979.9  498.48  4987.4  497.84
  4992.4  497.84  5007.9  496.70  5008.2  496.20  5011.7  496.20  5011.9  496.70
  5029.9  496.85  5039.9  497.40  5059.9  497.58  5069.9  497.94  5090.0  498.22
  5110.0  499.52  5120.0  498.25  5130.0  497.58  5140.0  499.25  5156.2  499.48
#Mann=3,-1,0
  4745.8    0.05       0  5007.9    0.04       0  5011.9    0.05       0
Bank Sta=5007.9,5011.9
Exp/Cntr=0.3,0.1

Type RM Length L Ch R = 1,873,28,28,28
BEGIN DESCRIPTION:
Mapping XS b9c7323c
END DESCRIPTION:
XS GIS Cut Line= 4
      2763620.86      6905505.30      2763872.95      6905494.62
      2763937.79      6905496.21      2764035.36      6905493.12
#Sta/Elev= 30
  4744.6  505.99  4799.8  504.19  4809.8  503.95  4829.8  503.01  4839.8  502.61
  4849.8  502.39  4859.8  501.92  4869.9  501.90  4879.9  501.57  4889.9  500.98
  4899.9  500.69  4919.9  499.79  4929.9  499.63  4939.9  499.28  4967.9  498.62
  4968.2  498.12  4971.7  498.12  4971.9  498.62  4995.9  499.38  5010.0  499.47
  5030.0  499.82  5049.1  499.91  5054.1  499.46  5066.7  499.50  5071.7  499.86
  5090.0  499.81  5100.0  499.94  5120.0  499.69  5150.0  498.91  5159.4  498.96
#Mann=3,-1,0
  4744.6    0.05       0  4967.9    0.04       0  4971.9    0.05       0
Bank Sta=4967.9,4971.9
Exp/Cntr=0.3,0.1

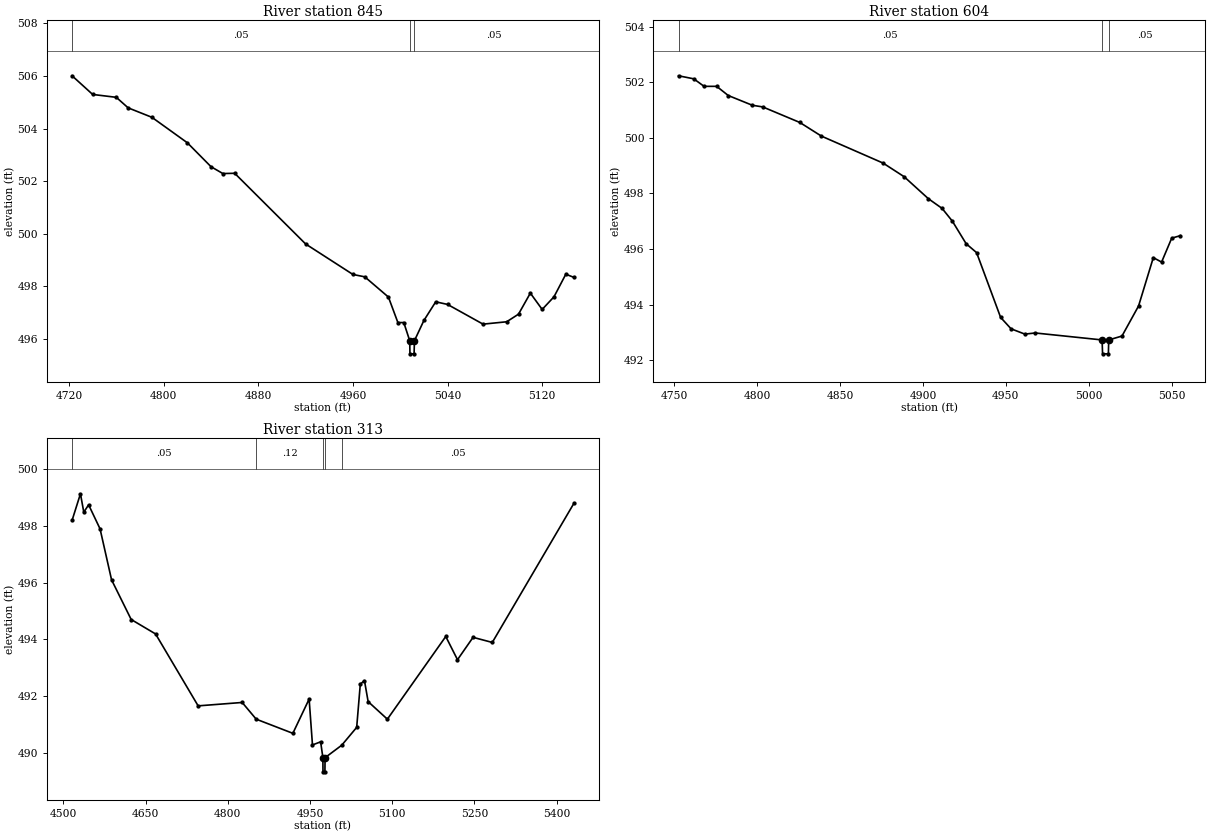
Type RM Length L Ch R = 1,845,241,241,241
BEGIN DESCRIPTION:
Mapping XS f5d7c14a
END DESCRIPTION:
XS GIS Cut Line= 3
      2763598.56      6905518.10      2763876.98      6905522.78
      2764022.82      6905522.09
#Sta/Elev= 30
  4722.5  506.01  4739.9  505.30  4759.9  505.19  4769.9  504.79  4790.0  504.43
  4820.0  503.46  4840.0  502.55  4850.0  502.29  4860.0  502.30  4920.0  499.61
  4960.0  498.45  4970.0  498.36  4990.0  497.59  4998.0  496.62  5003.0  496.62
  5008.0  495.93  5008.2  495.43  5011.7  495.43  5012.0  495.93  5020.0  496.70
  5030.0  497.41  5040.0  497.31  5070.0  496.56  5090.0  496.65  5100.0  496.94
  5110.0  497.74  5120.0  497.12  5130.0  497.60  5140.0  498.46  5146.8  498.34
#Mann=3,-1,0
  4722.5    0.05       0  5008.0    0.04       0  5012.0    0.05       0
Bank Sta=5008,5012
Exp/Cntr=0.3,0.1

Type RM Length L Ch R = 1,604,291,291,291
BEGIN DESCRIPTION:
Mapping XS c84cf697
END DESCRIPTION:
XS GIS Cut Line= 3
      2763677.65      6905617.48      2763870.87      6905763.79
      2763931.15      6905766.57
#Sta/Elev= 30
  4752.6  502.23  4761.8  502.12  4768.0  501.85  4775.6  501.85  4782.6  501.52
  4797.1  501.17  4803.4  501.11  4825.8  500.55  4838.8  500.06  4876.0  499.09
  4888.7  498.60  4903.3  497.81  4911.6  497.46  4917.8  497.00  4926.1  496.19
  4932.4  495.87  4946.9  493.54  4953.2  493.13  4961.5  492.94  4967.8  492.98
  5008.1  492.73  5008.4  492.23  5011.9  492.23  5012.1  492.73  5020.1  492.87
  5030.1  493.95  5039.0  495.69  5044.0  495.53  5050.1  496.39  5055.3  496.48
#Mann=3,-1,0
  4752.6    0.05       0  5008.1    0.04       0  5012.1    0.05       0
Bank Sta=5008.1,5012.1
Exp/Cntr=0.3,0.1

Type RM Length L Ch R = 1,313,0,0,0
BEGIN DESCRIPTION:
Caney T19 1.0
END DESCRIPTION:
XS GIS Cut Line= 3
      2763480.05      6905746.11      2763877.95      6906022.20
      2764201.00      6905736.00
#Sta/Elev= 30
  4515.7  498.20  4531.0  499.14  4537.1  498.49  4545.9  498.75  4566.8  497.90
  4587.8  496.10  4623.6  494.70  4668.1  494.19  4745.8  491.65  4826.2  491.77
  4851.8  491.18  4918.7  490.68  4948.4  491.89  4954.5  490.27  4969.4  490.38
  4973.5  489.82  4973.7  489.32  4977.2  489.32  4977.5  489.82  5007.9  490.26
  5035.2  490.89  5041.8  492.42  5049.4  492.54  5056.1  491.80  5091.2  491.18
  5197.8  494.10  5219.2  493.28  5247.6  494.07  5282.7  493.89  5431.6  498.80
#Mann=5,-1,0
  4515.7    0.05       0  4851.8    0.12       0  4973.5    0.07       0
  4977.5    0.12       0  5007.9    0.05       0
Bank Sta=4973.5,4977.5
Exp/Cntr=0.3,0.1

Chan Stop Cuts=-1