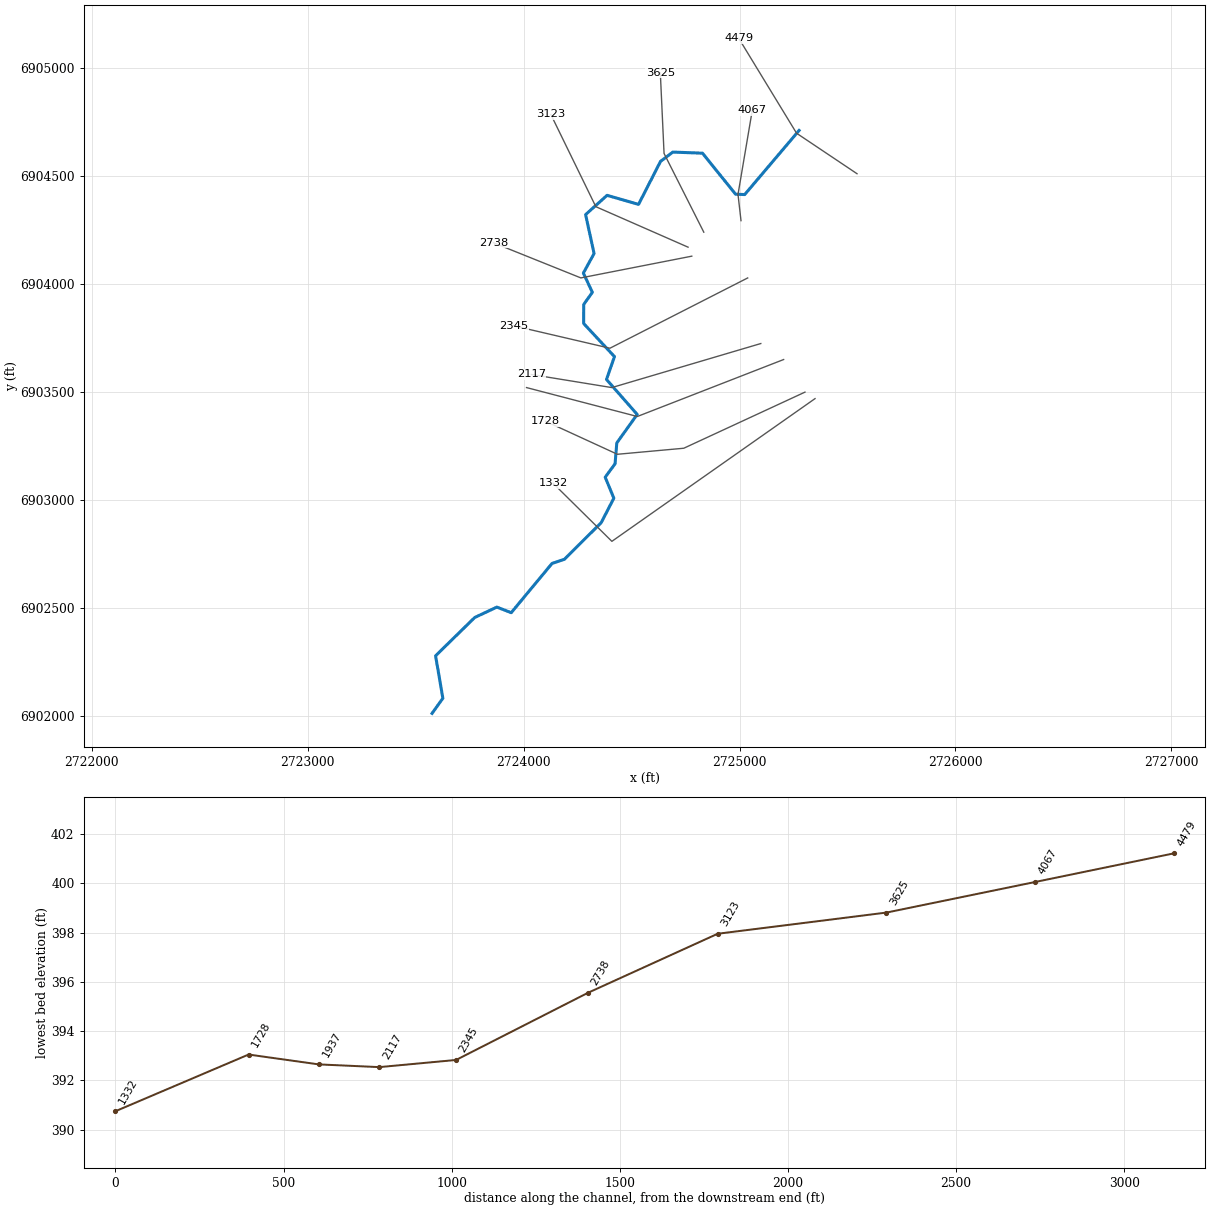
--- Caney T1_1.prj (project) ---

Proj Title=Caney T1_1 Base Level Engineering
Current Plan=p01
Default Exp/Contr=0.3,0.1
English Units
Geom File=g01
Flow File=f01
Plan File=p01
BEGIN DESCRIPTION:
Caney T1_1
END DESCRIPTION:

--- Caney T1_1.p01 (plan) ---

Plan Title=Multiple Run
Short Identifier=Multiple
Geom File=g01
Flow File=f01
Subcritical Flow
K Sum by GR= 0
Std Step Tol= 0.01
Critical Tol= 0.01
Num of Std Step Trials= 20
Max Error Tol= 0.3
Flow Tol Ratio= 0.001
Split Flow NTrial= 30
Split Flow Tol= 0.02
Split Flow Ratio= 0.02
Log Output Level= 0
Friction Slope Method= 1
Unsteady Friction Slope Method= 2
Unsteady Bridges Friction Slope Method= 1
Parabolic Critical Depth
Global Vel Dist=  1 , 1 , 1
Global Log Level= 0
CheckData=True
Encroach Param= -1, 0, 0, 0
BEGIN DESCRIPTION:
Multiple Run
END DESCRIPTION:

--- Caney T1_1.f01 (steady flow) ---

Flow Title=Multiple
Number of Profiles=7
Profile Names=10-year,25-year,50-year,1pct_min,100-year,1pct_plu,500-year
River Rch & RM= Caney T1_1,Reach-1,4479
     481     629     746     439     876    1748    1206
Boundary for River Rch & Prof#=Caney T1_1,Reach-1,1
Up Type=0
Dn Type=3
Dn Slope=0.005
Boundary for River Rch & Prof#=Caney T1_1,Reach-1,2
Up Type=0
Dn Type=3
Dn Slope=0.005
Boundary for River Rch & Prof#=Caney T1_1,Reach-1,3
Up Type=0
Dn Type=3
Dn Slope=0.005
Boundary for River Rch & Prof#=Caney T1_1,Reach-1,4
Up Type=0
Dn Type=3
Dn Slope=0.005
Boundary for River Rch & Prof#=Caney T1_1,Reach-1,5
Up Type=0
Dn Type=3
Dn Slope=0.005
Boundary for River Rch & Prof#=Caney T1_1,Reach-1,6
Up Type=0
Dn Type=3
Dn Slope=0.005
Boundary for River Rch & Prof#=Caney T1_1,Reach-1,7
Up Type=0
Dn Type=3
Dn Slope=0.005

--- Caney T1_1.g01 (geometry) ---

Geom Title=Existing Conditions

River Reach=Caney T1_1,Reach-1
Reach XY= 30
      2725276.00      6904711.00      2725023.99      6904413.95
      2724981.62      6904415.74      2724828.45      6904605.55
      2724691.04      6904610.69      2724634.00      6904567.39
      2724532.34      6904368.37      2724386.61      6904410.40
      2724287.09      6904321.09      2724326.38      6904140.86
      2724276.82      6904050.29      2724318.40      6903961.01
      2724278.36      6903905.10      2724277.97      6903816.89
      2724420.88      6903663.29      2724383.82      6903557.59
      2724526.11      6903395.64      2724431.54      6903263.42
      2724423.62      6903166.97      2724377.86      6903104.87
      2724417.93      6903007.69      2724359.37      6902894.33
      2724188.98      6902724.73      2724131.62      6902705.38
      2723942.67      6902477.39      2723876.09      6902503.22
      2723773.71      6902455.19      2723592.29      6902277.71
      2723626.04      6902081.00      2723576.00      6902011.00

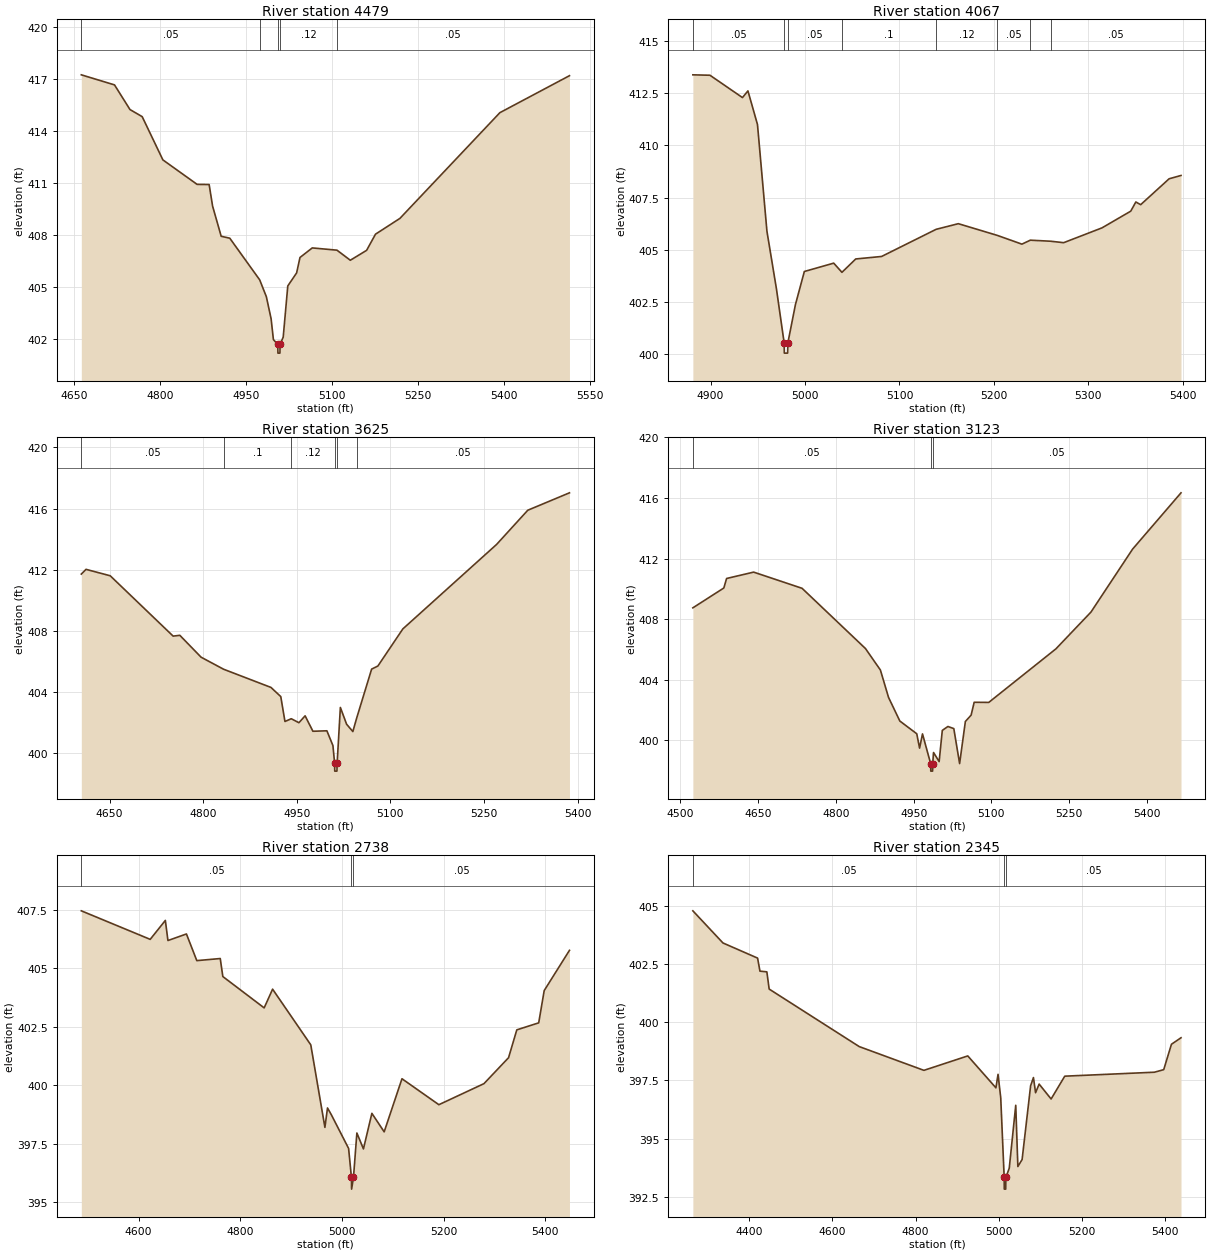
Type RM Length L Ch R = 1,4479,412,412,412
BEGIN DESCRIPTION:
Caney T1_1 2.0
END DESCRIPTION:
XS GIS Cut Line= 3
      2725544.20      6904510.49      2725264.25      6904698.00
      2724996.47      6905137.51
#Sta/Elev= 30
  4662.1  417.24  4720.0  416.66  4747.0  415.24  4768.3  414.83  4804.4  412.34
  4864.1  410.93  4885.1  410.92  4891.1  409.68  4906.1  407.94  4921.1  407.83
  4973.3  405.43  4984.9  404.46  4993.2  403.19  4997.2  401.99  5004.8  401.71
  5005.1  401.21  5008.6  401.21  5008.8  401.71  5014.3  402.13  5022.3  405.08
  5037.7  405.83  5043.6  406.72  5065.0  407.27  5108.1  407.14  5131.4  406.56
  5159.8  407.13  5175.3  408.06  5217.9  408.97  5392.3  415.06  5513.7  417.19
#Mann=5,-1,0
  4662.1    0.05       0  4973.3    0.12       0  5004.8    0.07       0
  5008.8    0.12       0  5108.1    0.05       0
Bank Sta=5004.8,5008.8
Exp/Cntr=0.3,0.1

Type RM Length L Ch R = 1,4067,442,442,442
BEGIN DESCRIPTION:
Mapping XS 119c586d
END DESCRIPTION:
XS GIS Cut Line= 3
      2725006.87      6904293.06      2724992.98      6904414.58
      2725058.94      6904803.42
#Sta/Elev= 30
  4881.3  413.38  4899.4  413.36  4933.8  412.29  4939.6  412.61  4949.7  411.00
  4959.7  405.89  4969.8  403.12  4977.9  400.55  4978.1  400.05  4981.6  400.05
  4981.9  400.55  4989.9  402.38  4999.3  403.96  5030.4  404.36  5039.1  403.92
  5053.7  404.56  5081.1  404.68  5138.8  405.98  5162.3  406.25  5203.5  405.69
  5229.6  405.27  5238.5  405.46  5260.0  405.41  5273.8  405.34  5314.4  406.05
  5344.8  406.85  5350.2  407.29  5355.3  407.16  5385.4  408.40  5398.0  408.56
#Mann=8,-1,0
  4881.3    0.05       0  4977.9    0.04       0  4981.9    0.05       0
  5039.1     0.1       0  5138.8    0.12       0  5203.5    0.05       0
  5238.5    0.12       0  5260.0    0.05       0
Bank Sta=4977.9,4981.9
Exp/Cntr=0.3,0.1

Type RM Length L Ch R = 1,3625,502,502,502
BEGIN DESCRIPTION:
Mapping XS 619f81ec
END DESCRIPTION:
XS GIS Cut Line= 3
      2724834.54      6904239.70      2724650.50      6904604.31
      2724633.22      6904977.68
#Sta/Elev= 30
  4604.8  411.71  4612.3  412.02  4651.1  411.60  4751.9  407.65  4762.7  407.70
  4796.7  406.27  4832.8  405.48  4908.7  404.29  4924.4  403.69  4931.1  402.06
  4941.2  402.24  4953.5  401.98  4963.4  402.43  4975.9  401.42  4998.3  401.45
  5008.0  400.48  5010.7  399.31  5010.9  398.81  5014.4  398.81  5014.7  399.31
  5019.9  402.98  5029.9  401.88  5039.9  401.40  5046.0  402.28  5070.0  405.49
  5080.0  405.69  5120.0  408.12  5270.2  413.65  5320.2  415.89  5387.0  417.03
#Mann=6,-1,0
  4604.8    0.05       0  4832.8     0.1       0  4941.2    0.12       0
  5010.7    0.07       0  5014.7    0.12       0  5046.0    0.05       0
Bank Sta=5010.7,5014.7
Exp/Cntr=0.3,0.1

Type RM Length L Ch R = 1,3123,385,385,385
BEGIN DESCRIPTION:
Mapping XS 173d5848
END DESCRIPTION:
XS GIS Cut Line= 3
      2724761.65      6904170.27      2724334.53      6904357.78
      2724126.18      6904784.90
#Sta/Elev= 30
  4524.1  408.74  4583.8  410.05  4589.2  410.68  4641.4  411.10  4734.8  410.03
  4857.1  406.05  4885.9  404.63  4901.6  402.82  4923.4  401.26  4956.0  400.42
  4961.5  399.47  4967.1  400.41  4982.8  398.45  4983.1  397.95  4986.6  397.95
  4986.8  398.45  4988.4  399.18  4999.2  398.58  5005.3  400.64  5016.1  400.90
  5027.5  400.76  5038.7  398.45  5049.8  401.23  5060.9  401.65  5066.8  402.50
  5094.9  402.49  5224.5  406.03  5292.1  408.46  5372.4  412.62  5465.8  416.34
#Mann=3,-1,0
  4524.1    0.05       0  4982.8    0.04       0  4986.8    0.05       0
Bank Sta=4982.8,4986.8
Exp/Cntr=0.3,0.1

Type RM Length L Ch R = 1,2738,393,393,393
BEGIN DESCRIPTION:
Mapping XS 3d2b4bb3
END DESCRIPTION:
XS GIS Cut Line= 3
      2724778.95      6904128.61      2724265.08      6904027.92
      2723859.90      6904190.69
#Sta/Elev= 30
  4487.4  407.46  4622.9  406.24  4652.7  407.05  4657.8  406.19  4694.2  406.47
  4714.6  405.33  4760.7  405.42  4765.8  404.65  4847.1  403.31  4863.7  404.11
  4938.8  401.73  4966.6  398.20  4971.7  399.03  4979.5  398.73  5013.2  397.30
  5018.8  396.06  5019.1  395.56  5022.8  396.06  5029.5  397.96  5042.4  397.28
  5059.0  398.80  5083.2  398.01  5118.2  400.28  5190.8  399.17  5279.5  400.07
  5327.9  401.18  5344.1  402.37  5387.2  402.67  5398.0  404.05  5447.7  405.77
#Mann=3,-1,0
  4487.4    0.05       0  5018.8    0.04       0  5022.8    0.05       0
Bank Sta=5018.8,5022.8
Exp/Cntr=0.3,0.1

Type RM Length L Ch R = 1,2345,228,228,228
BEGIN DESCRIPTION:
Mapping XS 2ef30b3c
END DESCRIPTION:
XS GIS Cut Line= 3
      2725037.83      6904027.75      2724399.81      6903702.23
      2723953.63      6903806.19
#Sta/Elev= 30
  4264.2  404.78  4336.6  403.40  4419.9  402.75  4425.6  402.19  4442.2  402.16
  4447.8  401.42  4664.5  398.95  4820.1  397.93  4925.6  398.55  4993.3  397.18
  4998.4  397.76  5004.9  396.75  5013.2  393.33  5013.4  392.83  5016.9  392.83
  5017.2  393.33  5025.4  393.73  5041.0  396.43  5046.1  393.80  5056.3  394.10
  5076.8  397.27  5083.6  397.62  5088.7  396.97  5097.3  397.34  5126.1  396.70
  5158.9  397.68  5374.6  397.85  5397.0  397.96  5415.6  399.05  5438.6  399.33
#Mann=3,-1,0
  4264.2    0.05       0  5013.2    0.04       0  5017.2    0.05       0
Bank Sta=5013.2,5017.2
Exp/Cntr=0.3,0.1

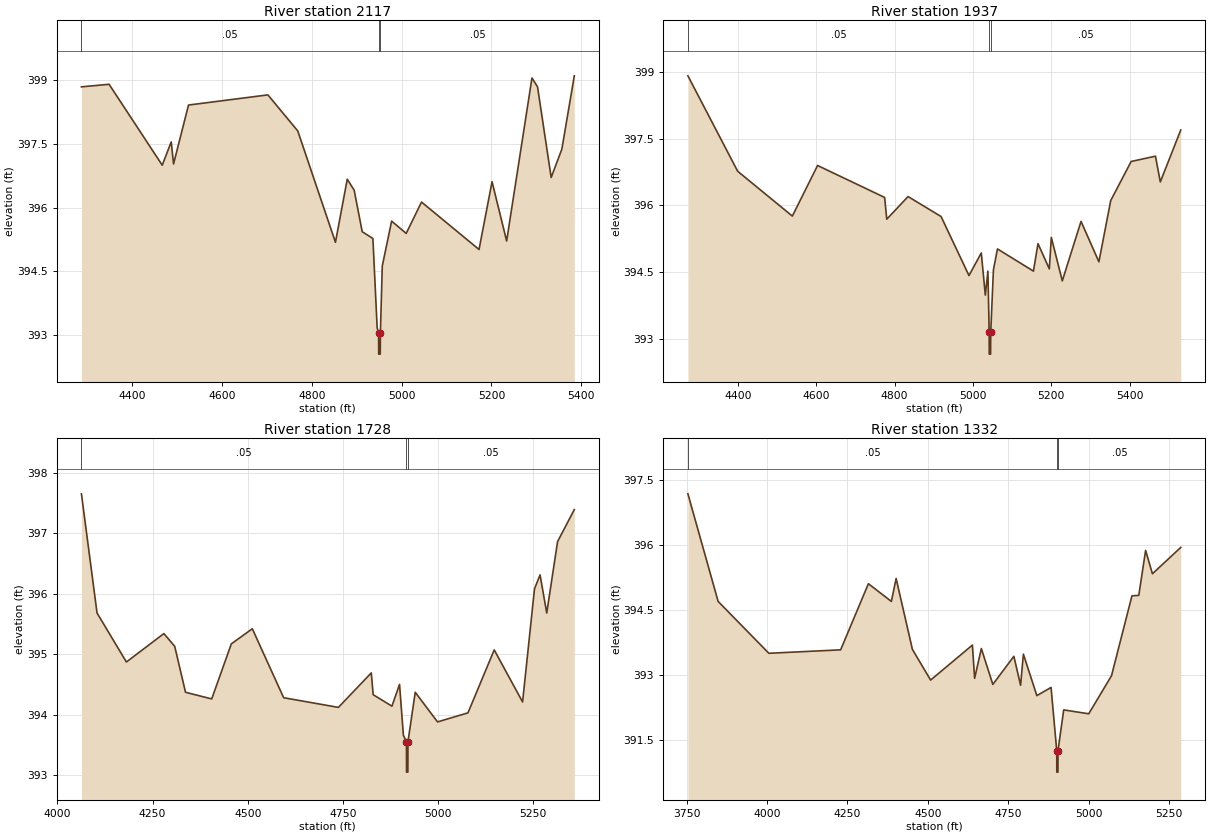
Type RM Length L Ch R = 1,2117,180,180,180
BEGIN DESCRIPTION:
Mapping XS 11befc49
END DESCRIPTION:
XS GIS Cut Line= 3
      2725098.57      6903723.92      2724408.49      6903519.94
      2724035.20      6903580.70
#Sta/Elev= 30
  4286.7  398.85  4348.3  398.91  4466.7  397.00  4486.7  397.55  4491.9  397.03
  4525.2  398.42  4702.0  398.66  4768.5  397.81  4852.5  395.18  4878.8  396.67
  4894.2  396.41  4912.1  395.43  4935.9  395.27  4945.4  393.16  4948.6  393.04
  4948.8  392.54  4952.3  392.54  4952.6  393.04  4956.8  394.62  4977.6  395.68
  5010.1  395.39  5044.2  396.13  5172.3  395.01  5201.3  396.61  5233.8  395.21
  5290.2  399.06  5302.6  398.85  5333.0  396.71  5356.8  397.38  5384.5  399.11
#Mann=3,-1,0
  4286.7    0.05       0  4948.6    0.04       0  4952.6    0.05       0
Bank Sta=4948.6,4952.6
Exp/Cntr=0.3,0.1

Type RM Length L Ch R = 1,1937,209,209,209
BEGIN DESCRIPTION:
Mapping XS 9e3b45d2
END DESCRIPTION:
XS GIS Cut Line= 3
      2725204.34      6903649.86      2724526.59      6903386.00
      2724013.48      6903519.95
#Sta/Elev= 30
  4272.7  398.92  4399.7  396.77  4539.2  395.76  4603.6  396.90  4774.7  396.18
  4780.1  395.69  4834.5  396.20  4918.7  395.75  4989.9  394.42  5021.3  394.93
  5031.6  393.98  5038.2  394.52  5041.4  393.15  5041.6  392.65  5045.1  392.65
  5045.4  393.15  5052.3  394.55  5062.6  395.02  5154.4  394.52  5166.0  395.14
  5194.9  394.57  5200.0  395.28  5228.0  394.30  5275.8  395.64  5321.4  394.73
  5351.6  396.11  5403.7  396.99  5465.7  397.11  5478.1  396.53  5530.3  397.70
#Mann=3,-1,0
  4272.7    0.05       0  5041.4    0.04       0  5045.4    0.05       0
Bank Sta=5041.4,5045.4
Exp/Cntr=0.3,0.1

Type RM Length L Ch R = 1,1728,396,396,396
BEGIN DESCRIPTION:
Mapping XS 7e3c18c1
END DESCRIPTION:
XS GIS Cut Line= 4
      2725303.20      6903498.92      2724741.82      6903239.00
      2724434.56      6903211.04      2724101.06      6903364.31
#Sta/Elev= 30
  4063.3  397.65  4104.3  395.68  4181.4  394.87  4279.8  395.34  4308.2  395.13
  4336.6  394.37  4405.4  394.26  4456.9  395.17  4512.0  395.42  4594.3  394.28
  4738.0  394.12  4824.4  394.69  4829.4  394.33  4878.6  394.14  4898.6  394.50
  4908.7  393.66  4916.7  393.55  4917.0  393.05  4920.5  393.05  4920.7  393.55
  4939.8  394.37  4998.4  393.88  5078.3  394.03  5147.2  395.07  5221.7  394.21
  5253.0  396.08  5267.6  396.31  5285.1  395.68  5313.6  396.86  5357.5  397.39
#Mann=3,-1,0
  4063.3    0.05       0  4916.7    0.04       0  4920.7    0.05       0
Bank Sta=4916.7,4920.7
Exp/Cntr=0.3,0.1

Type RM Length L Ch R = 1,1332,0,0,0
BEGIN DESCRIPTION:
Caney T1_1 1.0
END DESCRIPTION:
XS GIS Cut Line= 3
      2725349.69      6903468.81      2724408.79      6902807.80
      2724136.82      6903076.36
#Sta/Elev= 30
  3754.3  397.19  3848.3  394.70  4006.0  393.50  4229.1  393.58  4315.4  395.11
  4386.8  394.70  4401.6  395.23  4452.2  393.59  4508.8  392.88  4638.7  393.69
  4645.6  392.92  4666.5  393.61  4702.2  392.78  4767.6  393.43  4788.5  392.76
  4797.2  393.48  4839.0  392.52  4883.2  392.71  4900.8  391.25  4901.1  390.75
  4904.6  390.75  4904.8  391.25  4922.5  392.19  5000.3  392.10  5071.1  392.98
  5134.7  394.83  5155.9  394.84  5177.1  395.88  5198.3  395.34  5286.4  395.95
#Mann=3,-1,0
  3754.3    0.05       0  4900.8    0.04       0  4904.8    0.05       0
Bank Sta=4900.8,4904.8
Exp/Cntr=0.3,0.1

Chan Stop Cuts=-1