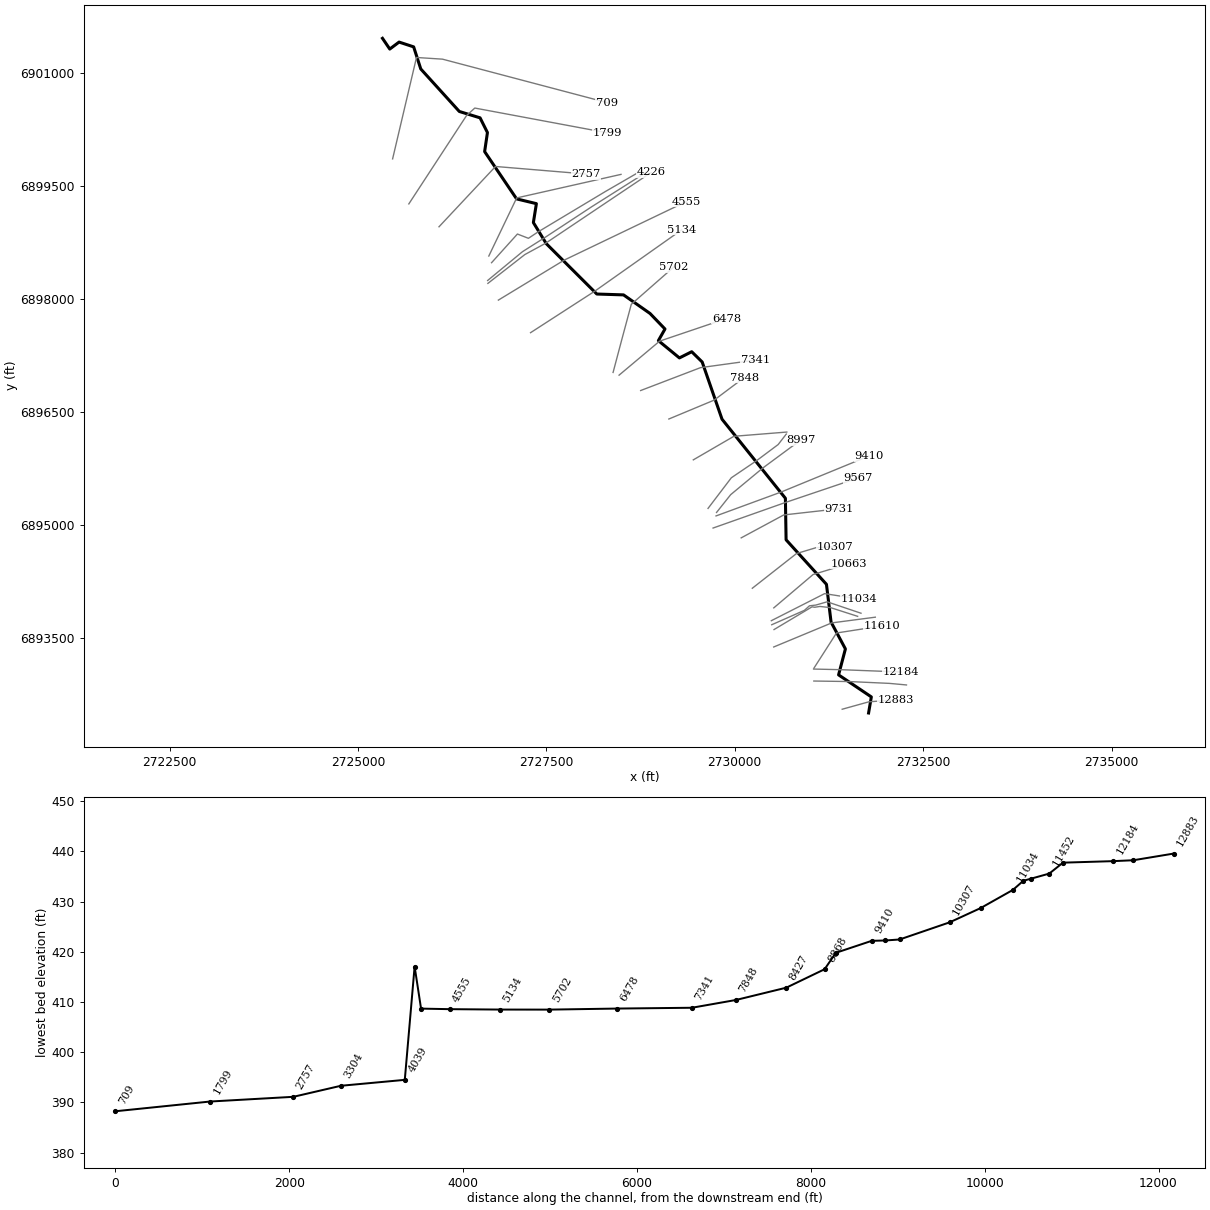
--- Caney T2.prj (project) ---

Proj Title=Caney T2 Base Level Engineering
Current Plan=p01
Default Exp/Contr=0.3,0.1
English Units
Geom File=g01
Flow File=f01
Plan File=p01
Y Axis Title=Elevation
X Axis Title(PF)=Main Channel Distance
X Axis Title(XS)=Station
BEGIN DESCRIPTION:
Caney T2
END DESCRIPTION:
DSS Export Rating Curves= 0
DSS Export Rating Curve Sorted= 0
DSS Export Volume Flow Curves= 0
DXF OffsetX= 0
DXF OffsetY= 0
DXF ScaleX= 1
DXF ScaleY= 10

--- Caney T2.p01 (plan) ---

Plan Title=Multiple Run
Short Identifier=Multiple
Geom File=g01
Flow File=f01
Subcritical Flow
K Sum by GR= 0
Std Step Tol= 0.01
Critical Tol= 0.01
Num of Std Step Trials= 20
Max Error Tol= 0.3
Flow Tol Ratio= 0.001
Split Flow NTrial= 30
Split Flow Tol= 0.02
Split Flow Ratio= 0.02
Log Output Level= 0
Friction Slope Method= 1
Unsteady Friction Slope Method= 2
Unsteady Bridges Friction Slope Method= 1
Parabolic Critical Depth
Global Vel Dist=  1 , 1 , 1
Global Log Level= 0
CheckData=True
Encroach Param= -1, 0, 0, 0
BEGIN DESCRIPTION:
Multiple Run
END DESCRIPTION:

--- Caney T2.f01 (steady flow) ---

Flow Title=Multiple
Program Version=4.10
Number of Profiles= 7
Profile Names=10-year,25-year,50-year,1pct_min,100-year,1pct_plu,500-year
River Rch & RM=Caney T2,Reach-1         ,12883
     523     695     833     497     992    1979    1401
River Rch & RM=Caney T2,Reach-1         ,11452
     851    1164    1424     864    1725    3441    2526
River Rch & RM=Caney T2,Reach-1         ,7848
     956    1314    1611     979    1953    3897    2869
River Rch & RM=Caney T2,Reach-1         ,5702
    1002    1379    1692    1029    2053    4097    3022
River Rch & RM=Caney T2,Reach-1         ,5134
    1312    1830    2267    1390    2773    5533    4149
River Rch & RM=Caney T2,Reach-1         ,4039
    1352    1887    2337    1433    2859    5705    4278
Boundary for River Rch & Prof#=Caney T2,Reach-1         , 1
Up Type= 0
Dn Type= 3
Dn Slope=0.005
Boundary for River Rch & Prof#=Caney T2,Reach-1         , 2
Up Type= 0
Dn Type= 3
Dn Slope=0.005
Boundary for River Rch & Prof#=Caney T2,Reach-1         , 3
Up Type= 0
Dn Type= 3
Dn Slope=0.005
Boundary for River Rch & Prof#=Caney T2,Reach-1         , 4
Up Type= 0
Dn Type= 3
Dn Slope=0.005
Boundary for River Rch & Prof#=Caney T2,Reach-1         , 5
Up Type= 0
Dn Type= 3
Dn Slope=0.005
Boundary for River Rch & Prof#=Caney T2,Reach-1         , 6
Up Type= 0
Dn Type= 3
Dn Slope=0.005
Boundary for River Rch & Prof#=Caney T2,Reach-1         , 7
Up Type= 0
Dn Type= 3
Dn Slope=0.005
DSS Import GetInterval= 0
DSS Import GetPeak= 0
DSS Import FillOption= 0

--- Caney T2.g01 (geometry) ---

Geom Title=Existing Conditions
Program Version=4.10

River Reach=Caney T2        ,Reach-1
Reach XY= 30
        2731776.        6892511.      2731812.46      6892724.38
      2731377.89      6893016.71       2731468.5        6893361.
      2731278.24      6893716.93      2731216.99      6894218.01
      2730681.46      6894808.55      2730672.25      6895359.45
      2729831.31      6896408.48      2729568.14      6897167.17
      2729429.16      6897303.46      2729265.94      6897221.29
      2728986.83      6897450.68      2729074.42      6897604.95
        2728876.        6897811.      2728524.55       6898057.5
      2728169.81      6898068.81      2727499.01      6898737.53
      2727328.14      6899016.97      2727368.25      6899267.82
      2727105.58      6899330.76       2726681.4      6899958.32
      2726718.67       6900211.1      2726620.92      6900405.96
      2726345.63      6900490.52      2725833.85      6901054.81
      2725739.63      6901347.55      2725546.05       6901411.2
      2725422.65      6901318.57        2725326.        6901461.

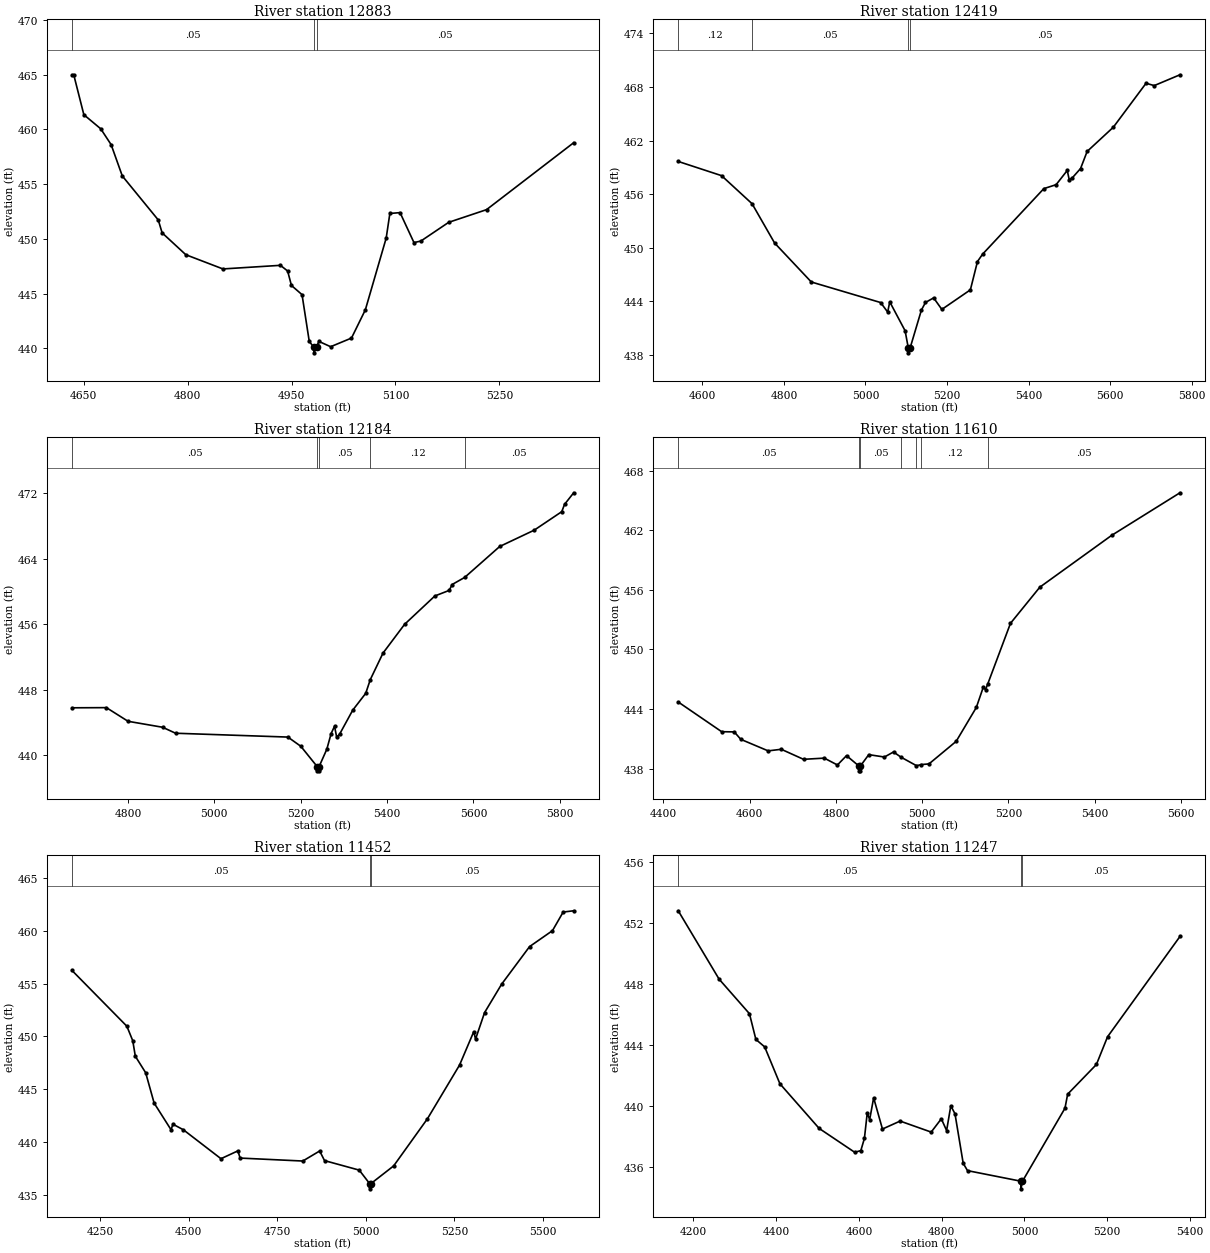
Type RM Length L Ch R = 1 ,12883   ,464,464,464
BEGIN DESCRIPTION:
Caney T2 23.0
END DESCRIPTION:
XS GIS Cut Line= 3
      2731425.96      6892560.99      2731779.64      6892659.36
      2732136.01       6892685.1
#Sta/Elev= 30
  4632.9     465  4635.5     465  4650.1  461.35  4674.5  460.06  4689.5  458.61
  4705.6  455.75  4757.5  451.73  4763.1  450.55  4797.3  448.55  4850.9  447.25
  4933.9  447.58  4944.3  447.06  4949.8  445.74  4965.1   444.9  4975.5  440.64
  4982.1  440.08  4982.3  439.58  4986.1  440.08  4989.3  440.63  5006.4  440.14
  5036.5  440.93  5056.5  443.51  5086.6  450.07  5091.9  452.32  5106.6   452.4
  5126.7  449.66  5136.7   449.8  5176.8  451.51  5231.5  452.67  5357.3  458.79
#Mann= 3 ,-1 , 0
  4632.9     .05       0  4982.1     .05       0  4986.1     .05       0
Bank Sta=4982.1,4986.1
XS Rating Curve= 0 ,0
Exp/Cntr=0.3,0.1

Type RM Length L Ch R = 1 ,12419   ,235,235,235
BEGIN DESCRIPTION:
Mapping XS fb6d42ca
END DESCRIPTION:
XS GIS Cut Line= 4
      2731049.67      6892935.09      2731518.37      6892928.15
      2732053.09      6892903.85       2732278.8      6892883.01
#Sta/Elev= 30
  4540.7  459.67    4647  458.08  4721.8  454.94  4777.1  450.54  4867.1  446.18
  5037.1  443.88  5054.5  442.81  5059.5  443.96  5097.2  440.72  5105.2  438.75
  5105.4  438.25  5109.2  438.75  5137.2  443.04  5147.2  443.89  5167.2   444.4
  5187.3  443.11  5257.3   445.3  5274.7  448.47  5287.4   449.3  5437.5  456.63
  5467.6  457.07  5494.9  458.66  5499.9   457.6  5507.6  457.85  5527.6  458.88
  5543.7  460.79  5607.9   463.5  5688.2  468.42  5708.3  468.16  5771.4  469.37
#Mann= 4 ,-1 , 0
  4540.7     .12       0  4721.8     .05       0  5105.2     .05       0
  5109.2     .05       0
Bank Sta=5105.2,5109.2
XS Rating Curve= 0 ,0
Exp/Cntr=0.3,0.1

Type RM Length L Ch R = 1 ,12184   ,574,574,574
BEGIN DESCRIPTION:
Mapping XS e4abc801
END DESCRIPTION:
XS GIS Cut Line= 3
      2731046.17      6893093.95      2731415.07      6893085.27
      2732207.19      6893054.89
#Sta/Elev= 30
  4670.4  445.78  4750.2   445.8  4800.3  444.13  4880.3   443.4  4910.3  442.67
  5170.4   442.2  5200.4  441.07  5238.5  438.57  5238.7  438.07  5242.2  438.07
  5242.5  438.57  5260.5  440.71  5270.5  442.63  5278.4  443.53  5283.4  442.17
  5290.5  442.59  5320.5  445.49  5350.6  447.55  5361.2  449.23  5390.6  452.47
  5440.6  455.99  5510.7  459.46  5543.9  460.14  5550.7  460.86  5579.8  461.73
  5660.8  465.51  5740.8  467.51  5804.5  469.77  5810.9  470.66  5832.1  472.08
#Mann= 5 ,-1 , 0
  4670.4     .05       0  5238.5     .05       0  5242.5     .05       0
  5361.2     .12       0  5579.8     .05       0
Bank Sta=5238.5,5242.5
XS Rating Curve= 0 ,0
Exp/Cntr=0.3,0.1

Type RM Length L Ch R = 1 ,11610   ,158,158,158
BEGIN DESCRIPTION:
Mapping XS d2a6ebda
END DESCRIPTION:
XS GIS Cut Line= 3
      2731051.13      6893106.25      2731350.11      6893572.25
      2731952.64      6893665.74
#Sta/Elev= 30
  4434.3   444.7    4535  441.71  4564.2  441.69  4579.4  440.94  4642.8  439.78
  4673.2  439.94  4724.8  438.93    4773  439.05  4803.4  438.36  4824.5   439.3
  4852.9  438.27  4853.2  437.77  4856.7  437.77  4856.9  438.27  4876.1   439.4
  4912.4  439.16  4933.5  439.67  4950.7  439.15  4986.7  438.29  4998.1   438.4
  5015.8  438.47  5078.8  440.74  5125.5  444.15  5141.8  446.21  5146.8  445.94
  5151.6  446.47  5204.7  452.62  5272.8  456.26  5439.2  461.47  5597.7  465.76
#Mann= 7 ,-1 , 0
  4434.3     .05       0  4852.9     .07       0  4856.9     .05       0
  4950.7     .12       0  4986.7     .05       0  4998.1     .12       0
  5151.6     .05       0
Bank Sta=4852.9,4856.9
XS Rating Curve= 0 ,0
Exp/Cntr=0.3,0.1

Type RM Length L Ch R = 1 ,11452   ,205,205,205
BEGIN DESCRIPTION:
Mapping XS e89c2700
END DESCRIPTION:
XS GIS Cut Line= 3
      2730517.39      6893386.66      2731286.46      6893706.11
      2731865.42       6893782.1
#Sta/Elev= 30
  4169.9  456.25    4325  450.97  4341.6   449.6  4348.9  448.13  4378.1  446.57
    4402   443.7  4449.7  441.18  4455.1   441.7  4484.4  441.18  4590.7  438.44
  4638.4  439.18  4644.8   438.5  4821.7  438.22  4869.4  439.17  4883.1  438.26
  4981.1  437.36  5010.3  436.09  5010.5  435.59  5014.3  436.09  5078.3  437.76
  5173.7  442.22  5264.4   447.3  5304.5  450.46  5309.5  449.75    5335  452.26
  5383.2  454.95    5462   458.5  5526.7  460.01  5556.9  461.77  5586.6  461.89
#Mann= 3 ,-1 , 0
  4169.9     .05       0  5010.3     .04       0  5014.3     .05       0
Bank Sta=5010.3,5014.3
XS Rating Curve= 0 ,0
Exp/Cntr=0.3,0.1

Type RM Length L Ch R = 1 ,11247   ,93,93,93
BEGIN DESCRIPTION:
Mapping XS 5c52218b
END DESCRIPTION:
XS GIS Cut Line= 6
      2730521.57       6893617.9      2731025.98      6893919.43
      2731061.32      6893913.77      2731130.36      6893924.49
      2731272.64      6893908.36      2731630.69       6893793.4
#Sta/Elev= 30
  4163.2  452.78    4262  448.31  4335.4  446.05  4350.9  444.37  4372.2  443.88
    4409  441.47  4503.9  438.55  4589.8  436.99  4604.6   437.1  4613.3   437.9
  4620.1  439.56    4626  439.13  4635.6  440.55  4656.9  438.51  4699.6  439.03
  4774.7  438.31  4799.2  439.18    4812  438.41  4822.1  440.03  4832.2  439.51
  4852.1  436.27  4862.5  435.79  4991.4   435.1  4991.6   434.6  4995.4   435.1
  5098.1  439.87  5104.6  440.79  5174.1  442.73    5201  444.54  5376.1   451.1
#Mann= 3 ,-1 , 0
  4163.2     .05       0  4991.4     .04       0  4995.4     .05       0
Bank Sta=4991.4,4995.4
XS Rating Curve= 0 ,0
Exp/Cntr=0.3,0.1

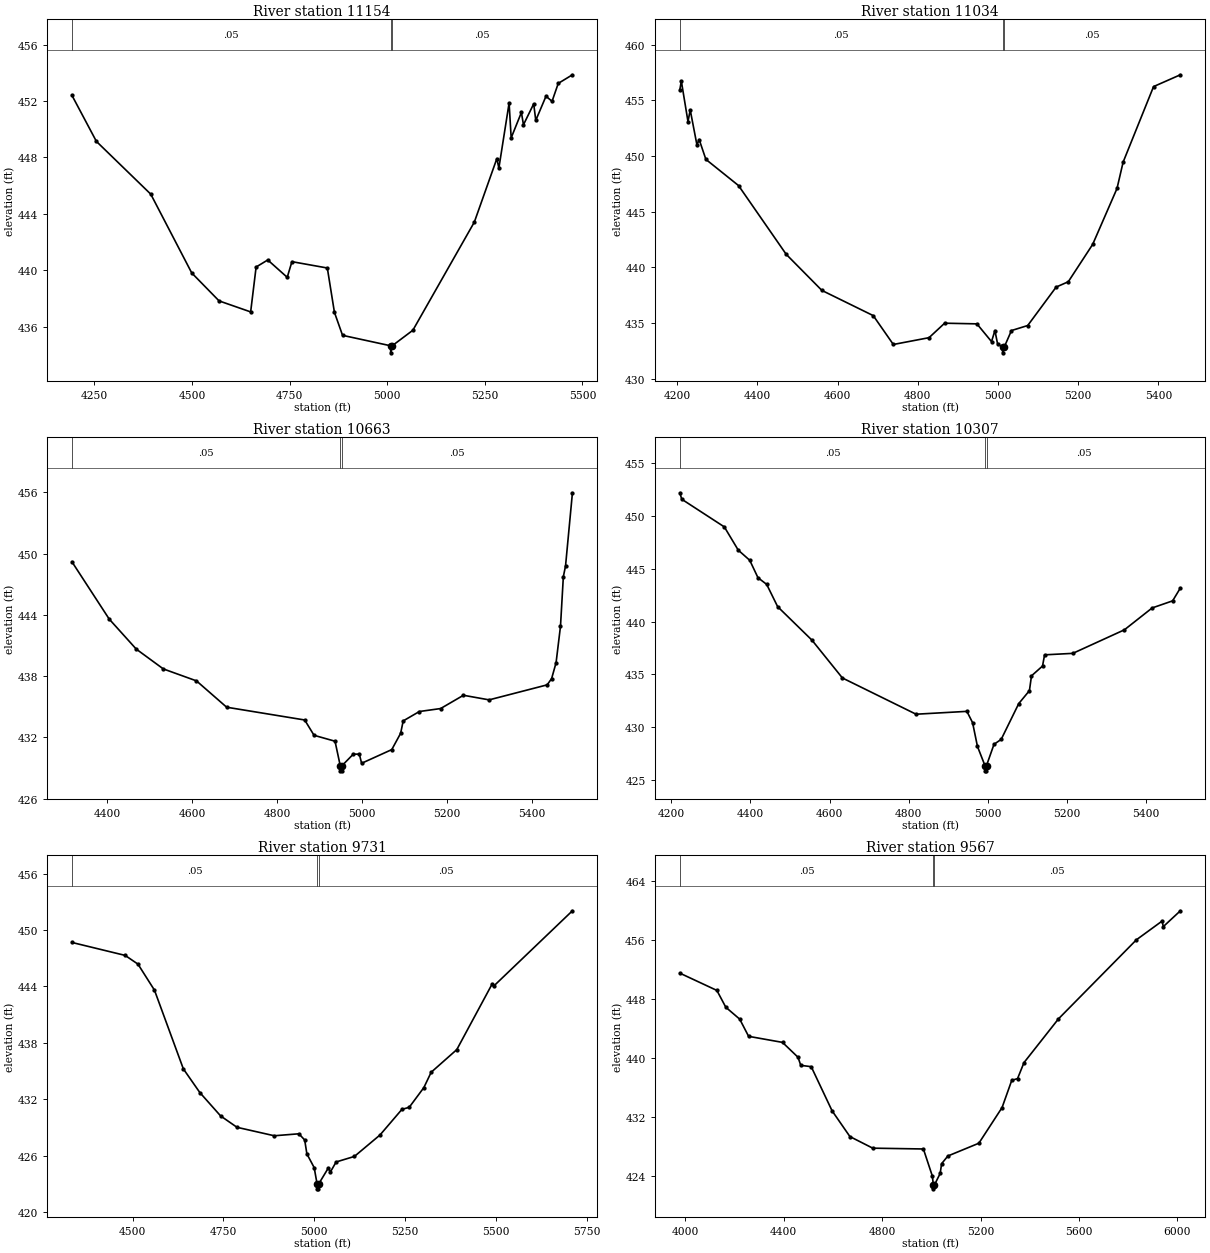
Type RM Length L Ch R = 1 ,11154   ,120,120,120
BEGIN DESCRIPTION:
Mapping XS 07417538
END DESCRIPTION:
XS GIS Cut Line= 6
      2730491.03      6893681.81      2730924.78      6893872.89
      2730991.57      6893932.91      2731076.04      6893942.69
        2731226.        6893986.      2731675.43      6893834.44
#Sta/Elev= 30
  4192.2  452.41    4255  449.14  4394.3   445.4  4499.2  439.82  4569.2  437.84
  4650.1  437.06  4664.1  440.24  4693.9  440.74  4743.8  439.51  4755.8  440.62
  4846.5  440.17  4864.7  437.03  4885.5   435.4  5008.6  434.66  5008.8  434.16
  5012.6  434.66  5065.6  435.76    5223  443.42  5280.7  447.92  5285.9  447.25
  5312.1  451.86  5317.4  449.39  5343.6  451.19  5348.9  450.32  5375.1   451.8
  5380.4  450.63  5406.6  452.34  5422.1  451.98    5438  453.25  5474.3  453.86
#Mann= 3 ,-1 , 0
  4192.2     .05       0  5008.6     .04       0  5012.6     .05       0
Bank Sta=5008.6,5012.6
XS Rating Curve= 0 ,0
Exp/Cntr=0.3,0.1

Type RM Length L Ch R = 1 ,11034   ,371,371,371
BEGIN DESCRIPTION:
Caney T2 19.0
END DESCRIPTION:
XS GIS Cut Line= 3
      2730485.53      6893735.44      2731192.68      6894094.52
      2731642.06      6894023.81
#Sta/Elev= 30
  4206.9  455.95  4210.6  456.73  4227.2  453.09  4232.8  454.13  4249.5     451
  4255.1  451.48  4271.8   449.7  4353.2  447.35  4472.1  441.18  4561.1  437.94
  4689.1  435.68  4739.2  433.09  4828.2   433.7  4867.1     435  4947.6  434.94
    4984  433.35  4992.5  434.34  4999.1  433.14  5011.5  432.84  5011.7  432.34
  5015.5  432.84  5033.7  434.34  5074.2  434.79  5145.1  438.24  5175.4  438.72
  5236.2  442.07  5296.9  447.09  5312.1  449.45    5388  456.23  5454.9  457.29
#Mann= 3 ,-1 , 0
  4206.9     .05       0  5011.5     .04       0  5015.5     .05       0
Bank Sta=5011.5,5015.5
XS Rating Curve= 0 ,0
Exp/Cntr=0.3,0.1

Type RM Length L Ch R = 1 ,10663   ,356,356,356
BEGIN DESCRIPTION:
Caney T2 18.0
END DESCRIPTION:
XS GIS Cut Line= 3
      2730518.15      6893905.56       2731039.3      6894347.65
      2731512.84      6894491.82
#Sta/Elev= 30
  4316.6   449.2  4404.5  443.58  4468.2  440.64  4531.9   438.7  4609.9  437.53
    4681  434.95  4864.7   433.7  4886.7   432.2  4936.1  431.62  4948.4  429.22
  4948.7  428.72  4952.2  428.72  4952.4  429.22    4979  430.35  4993.3  430.36
  4998.7  429.46  5069.7   430.8  5090.6   432.4  5096.6  433.61  5134.7  434.53
  5184.7  434.82  5238.4  436.12  5298.9  435.67  5435.5  437.14    5446  437.75
  5456.5  439.31  5466.9  442.88  5473.6  447.73  5478.8  448.79    5495  455.95
#Mann= 3 ,-1 , 0
  4316.6     .05       0  4948.4     .04       0  4952.4     .05       0
Bank Sta=4948.4,4952.4
XS Rating Curve= 0 ,0
Exp/Cntr=0.3,0.1

Type RM Length L Ch R = 1 ,10307   ,576,576,576
BEGIN DESCRIPTION:
Mapping XS ed9b4bfa
END DESCRIPTION:
XS GIS Cut Line= 4
      2730233.41      6894165.97      2730819.38      6894626.07
       2731079.8      6894704.19      2731327.16      6894717.21
#Sta/Elev= 30
  4221.6   452.2  4226.4  451.59    4334  448.97  4369.2  446.77  4398.2  445.81
    4419  444.16    4441  443.53  4468.7  441.42  4555.4  438.25  4632.3  434.67
  4818.4  431.24  4946.8  431.51  4961.2  430.44  4973.5  428.19  4992.4  426.38
  4992.7  425.88  4996.2  425.88  4996.4  426.38  5015.3  428.39  5033.5  428.86
  5077.9  432.25  5104.8  433.47    5110  434.87  5137.9   435.8  5143.1  436.86
  5214.4     437  5344.8  439.23  5414.9   441.3  5466.6  441.97  5486.2  443.19
#Mann= 3 ,-1 , 0
  4221.6     .05       0  4992.4     .04       0  4996.4     .05       0
Bank Sta=4992.4,4996.4
XS Rating Curve= 0 ,0
Exp/Cntr=0.3,0.1

Type RM Length L Ch R = 1 ,9731    ,164,164,164
BEGIN DESCRIPTION:
Mapping XS 421f9d89
END DESCRIPTION:
XS GIS Cut Line= 3
      2730085.87       6894834.4      2730650.11      6895138.22
      2731382.36      6895220.54
#Sta/Elev= 30
  4333.1  448.69  4479.7  447.31    4515  446.38  4560.4  443.61  4639.9  435.23
  4685.3  432.71  4742.5  430.22  4787.6  429.01  4890.2  428.11  4957.9  428.32
  4973.9  427.66  4979.9  426.18    5000  424.72  5008.1  422.96  5008.3  422.46
  5011.8  422.46  5012.1  422.96  5039.4  424.71  5044.4  424.24  5060.4  425.32
  5110.7  425.91  5181.1  428.19  5241.5  430.92  5261.6  431.14  5301.9  433.24
    5322  434.87  5392.5  437.28  5489.6  444.25  5494.6  444.06  5710.8  452.06
#Mann= 3 ,-1 , 0
  4333.1     .05       0  5008.1     .04       0  5012.1     .05       0
Bank Sta=5008.1,5012.1
XS Rating Curve= 0 ,0
Exp/Cntr=0.3,0.1

Type RM Length L Ch R = 1 ,9567    ,157,157,157
BEGIN DESCRIPTION:
Mapping XS 722606f4
END DESCRIPTION:
XS GIS Cut Line= 3
       2729712.6      6894964.61      2730658.79      6895298.81
      2731635.31      6895628.66
#Sta/Elev= 30
    3978  451.48  4128.5  449.14  4164.8  446.86  4221.3  445.25  4257.5  442.92
  4395.2   442.1  4458.1  440.09  4469.5  438.99  4511.9  438.81  4596.7  432.83
  4669.2  429.34    4762  427.77  4967.8  427.66  5004.4  423.97  5008.2  422.76
  5008.4  422.26  5012.2  422.76  5035.9  424.34  5041.9  425.67  5067.3  426.71
  5193.2  428.44  5287.5  433.27  5326.8  436.95  5350.5   437.2  5376.6  439.36
  5516.8  445.29  5833.5     456  5937.6  458.53  5942.9  457.79  6012.2  459.93
#Mann= 3 ,-1 , 0
    3978     .05       0  5008.2     .04       0  5012.2     .05       0
Bank Sta=5008.2,5012.2
XS Rating Curve= 0 ,0
Exp/Cntr=0.3,0.1

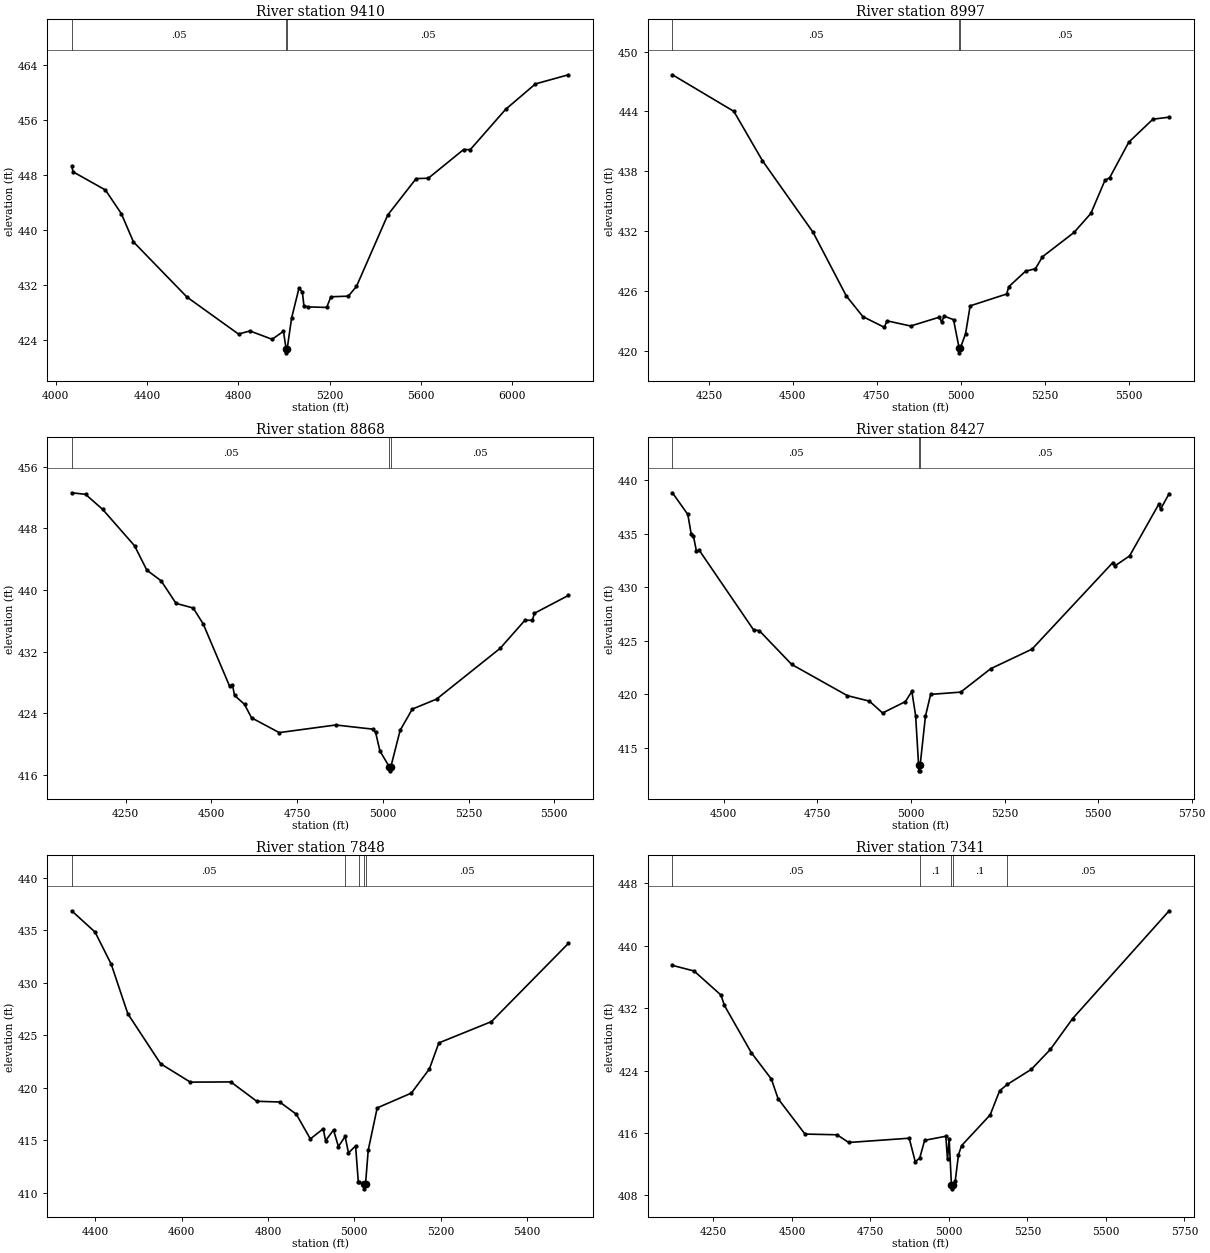
Type RM Length L Ch R = 1 ,9410    ,413,413,413
BEGIN DESCRIPTION:
Mapping XS d932ac1d
END DESCRIPTION:
XS GIS Cut Line= 3
       2729751.7      6895125.21      2730615.39      6895442.04
      2731778.56      6895919.46
#Sta/Elev= 30
  4069.5  449.33  4075.6   448.5  4217.4  445.86  4287.1  442.42  4340.4  438.31
  4574.7   430.3  4800.7  424.92  4851.1  425.37  4947.9  424.16  4997.7  425.32
  5009.7  422.69    5010  422.19  5013.7  422.69  5033.4  427.24  5065.8  431.58
  5080.5  431.07  5087.4  429.05  5104.4  428.87  5187.2  428.79  5205.7  430.34
    5282  430.43  5317.9  431.85  5454.9  442.23  5579.3  447.52  5632.6  447.57
  5787.3  451.74  5816.7  451.73  5971.4  457.58  6102.1  461.28  6246.8  462.61
#Mann= 3 ,-1 , 0
  4069.5     .05       0  5009.7     .05       0  5013.7     .05       0
Bank Sta=5009.7,5013.7
XS Rating Curve= 0 ,0
Exp/Cntr=0.3,0.1

Type RM Length L Ch R = 1 ,8997    ,129,129,129
BEGIN DESCRIPTION:
Mapping XS e82e1d2f
END DESCRIPTION:
XS GIS Cut Line= 5
      2729758.62      6895171.21      2729946.12      6895407.32
       2730373.2      6895761.48      2730758.62      6896046.21
      2730876.65      6896126.05
#Sta/Elev= 30
  4141.8  447.68  4324.6  444.01  4409.7  439.06  4560.1  431.89    4659  425.51
  4708.5  423.43  4772.3  422.36  4780.1  423.01  4850.5  422.49  4936.4  423.38
  4942.9  422.87  4949.8  423.48  4978.1  423.13  4994.7   420.3  4994.9   419.8
  4998.7   420.3    5014  421.72  5027.6  424.51  5136.3   425.7  5142.5  426.43
  5192.6  427.99  5221.8  428.23  5242.7  429.43  5336.7  431.87  5386.8  433.78
  5428.5  437.08  5443.1  437.38  5499.6  440.92  5571.5  443.23  5619.8  443.43
#Mann= 3 ,-1 , 0
  4141.8     .05       0  4994.7     .04       0  4998.7     .05       0
Bank Sta=4994.7,4998.7
XS Rating Curve= 0 ,0
Exp/Cntr=0.3,0.1

Type RM Length L Ch R = 1 ,8868    ,441,441,441
BEGIN DESCRIPTION:
Mapping XS ceb8d468
END DESCRIPTION:
XS GIS Cut Line= 5
      2729645.79      6895225.05       2729954.8      6895631.28
      2730288.13      6895856.97      2730576.33      6896072.25
      2730683.97      6896211.15
#Sta/Elev= 30
  4092.9  452.61  4133.2  452.41  4183.1  450.46  4276.3  445.73    4312  442.57
  4353.6  441.19  4397.2  438.26  4447.1  437.66  4476.2  435.61  4553.2  427.53
  4561.5  427.71  4567.8  426.32  4596.8  425.16  4617.3  423.41  4698.1  421.49
  4862.9  422.48  4970.8  421.94  4979.1  421.52  4991.8   419.1  5019.4  417.03
  5019.7  416.53  5023.4  417.03  5050.6  421.78    5086  424.54  5156.9  425.84
  5342.4  432.43  5414.6  436.07    5436  436.07  5442.4  436.98  5541.3  439.29
#Mann= 3 ,-1 , 0
  4092.9     .05       0  5019.4     .03       0  5023.4     .05       0
Bank Sta=5019.4,5023.4
XS Rating Curve= 0 ,0
Exp/Cntr=0.3,0.1

Type RM Length L Ch R = 1 ,8427    ,579,579,579
BEGIN DESCRIPTION:
Mapping XS bccf46cd
END DESCRIPTION:
XS GIS Cut Line= 3
      2729450.46      6895869.12      2729988.65      6896181.62
      2730691.35      6896238.01
#Sta/Elev= 30
  4362.6  438.85  4403.7  436.82  4412.8  434.97  4418.6  434.82  4426.8  433.36
  4434.3  433.47  4579.2  426.04  4594.9  425.95  4681.2   422.8  4830.1  419.88
  4888.8  419.37  4924.1  418.26  4984.9  419.32  5002.3  420.28  5012.4  418.01
  5020.4  413.35  5020.7  412.85  5024.2  412.85  5024.4  413.35  5038.6  417.95
  5052.5     420  5132.8  420.21    5213   422.4  5323.4  424.23  5539.4  432.33
  5544.4     432  5584.2  432.95  5662.1  437.78  5667.1  437.33  5689.9  438.78
#Mann= 3 ,-1 , 0
  4362.6     .05       0  5020.4     .04       0  5024.4     .05       0
Bank Sta=5020.4,5024.4
XS Rating Curve= 0 ,0
Exp/Cntr=0.3,0.1

Type RM Length L Ch R = 1 ,7848    ,507,507,507
BEGIN DESCRIPTION:
Caney T2 12.0
END DESCRIPTION:
XS GIS Cut Line= 3
      2729125.96      6896410.98        2729726.        6896661.
      2730125.96      6896960.97
#Sta/Elev= 30
  4345.7  436.85  4399.9  434.82  4437.3  431.76  4475.7  427.05  4551.6   422.3
  4620.4  420.55  4714.1  420.57  4774.2  418.73  4827.3  418.66  4865.7   417.5
  4898.2  415.15    4928  416.11  4933.5  414.98  4951.9     416  4963.2  414.42
  4978.8  415.38  4986.5  413.82    5003  414.48  5009.3  411.04  5011.5  411.02
  5021.7   410.9  5022.1   410.4  5026.1   410.9  5032.2  414.07    5053   418.1
  5132.2  419.51  5173.9  421.81  5195.7  424.28  5317.6  426.31  5495.7  433.75
#Mann= 5 ,-1 , 0
  4345.7     .05       0  4978.8      .1       0  5011.5     .05       0
  5021.7     .07       0  5026.1     .05       0
Bank Sta=5021.7,5026.1
XS Rating Curve= 0 ,0
Exp/Cntr=0.3,0.1

Type RM Length L Ch R = 1 ,7341    ,863,863,863
BEGIN DESCRIPTION:
Mapping XS f29580d9
END DESCRIPTION:
XS GIS Cut Line= 3
      2728751.68      6896788.61      2729545.95      6897092.43
      2730270.81      6897192.26
#Sta/Elev= 30
  4119.4  437.49  4188.3  436.77  4273.9  433.69    4285  432.35  4370.3  426.32
  4434.5  422.92  4455.9   420.4  4541.6  415.87  4643.6  415.78  4680.8  414.79
  4873.5  415.34  4892.7  412.33  4906.9  412.78  4922.7  415.07    4990  415.59
  4995.5  412.62  5000.6  415.29    5008  409.35  5008.4  408.85  5012.4  409.35
  5020.3  409.91  5030.4  413.22  5040.5   414.4  5131.4  418.33  5161.6  421.43
  5185.9  422.23  5262.6  424.17  5323.1  426.72  5393.8  430.66  5701.5  444.49
#Mann= 5 ,-1 , 0
  4119.4     .05       0  4906.9      .1       0    5008     .07       0
  5012.4      .1       0  5185.9     .05       0
Bank Sta=5008,5012.4
XS Rating Curve= 0 ,0
Exp/Cntr=0.3,0.1

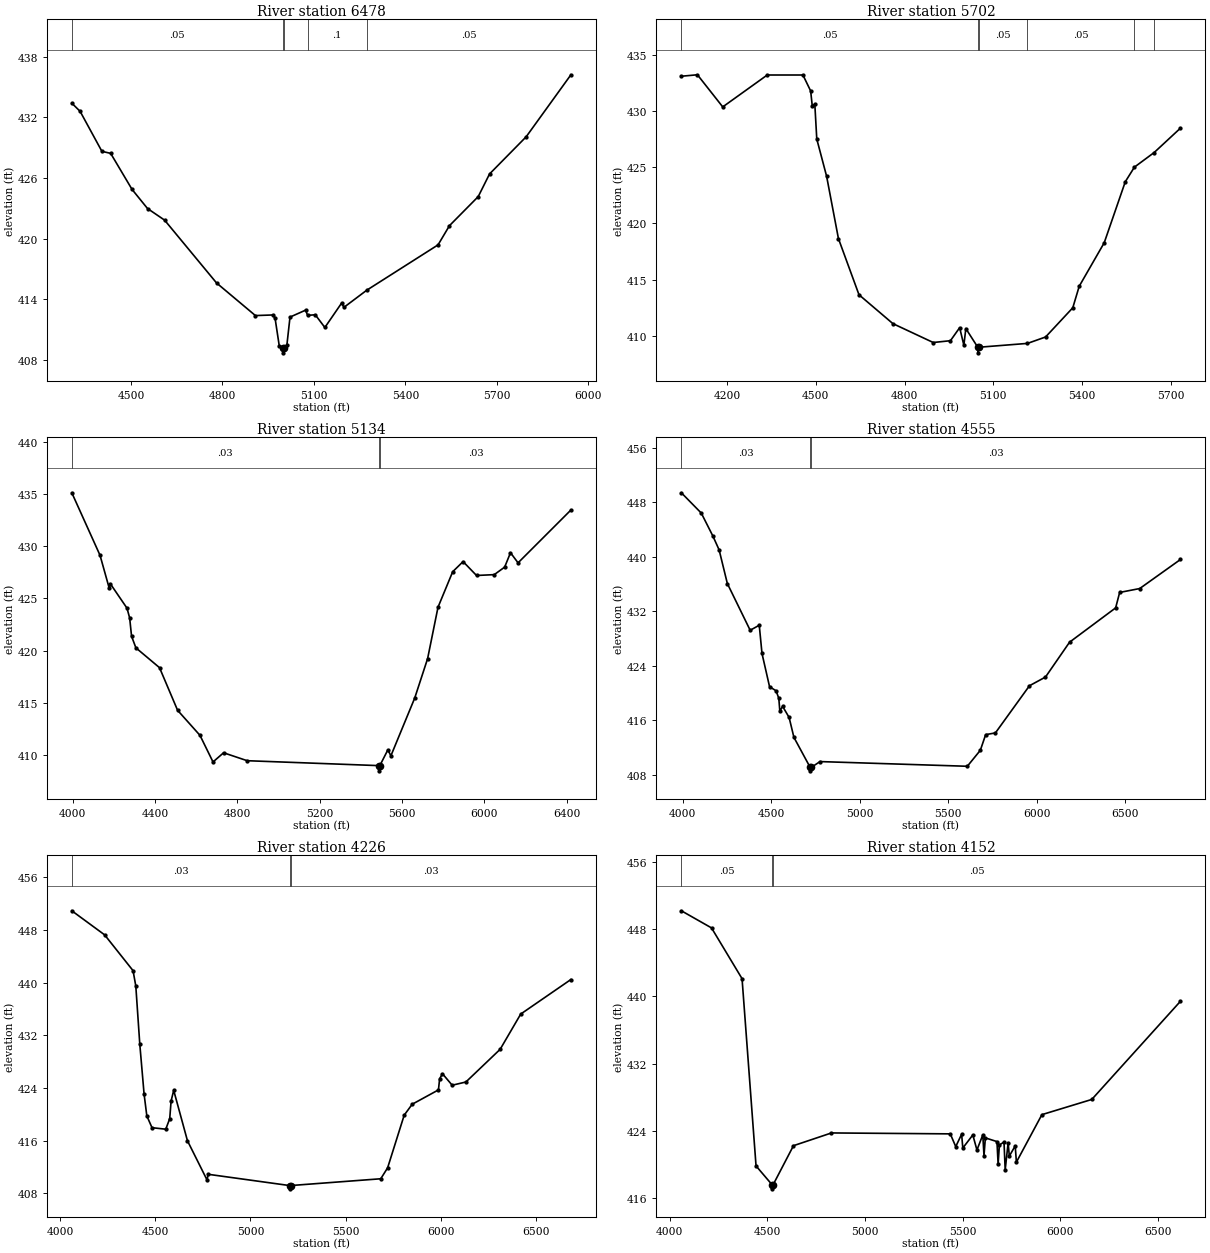
Type RM Length L Ch R = 1 ,6478    ,776,776,776
BEGIN DESCRIPTION:
Mapping XS d4dc5cb8
END DESCRIPTION:
XS GIS Cut Line= 3
      2728465.24      6896992.62      2729003.41      6897443.99
      2729888.84      6897743.48
#Sta/Elev= 30
    4306  433.41  4333.2   432.6  4404.7  428.64  4433.4  428.44  4503.6  424.87
  4554.3  422.98  4610.3  421.83  4780.7  415.61  4908.2  412.38  4965.5  412.44
  4972.6  412.14  4986.3  409.41  4998.4  409.19  4998.8  408.69  5002.9  409.19
  5011.5  409.47  5021.7  412.23  5073.1  412.92  5079.3   412.4  5104.6  412.46
    5136   411.2  5190.6   413.6  5198.9   413.2  5273.4  414.89  5507.3  419.38
  5544.7  421.28  5639.1  424.16  5676.2   426.4  5796.3  430.08  5943.1  436.22
#Mann= 5 ,-1 , 0
    4306     .05       0  4998.4     .04       0  5002.9     .05       0
  5079.3      .1       0  5273.4     .05       0
Bank Sta=4998.4,5002.9
XS Rating Curve= 0 ,0
Exp/Cntr=0.3,0.1

Type RM Length L Ch R = 1 ,5702    ,568,568,568
BEGIN DESCRIPTION:
Mapping XS c7f82102
END DESCRIPTION:
XS GIS Cut Line= 4
      2728385.75      6897028.48      2728499.24      6897456.56
      2728627.54      6897932.71      2729192.24      6898428.11
#Sta/Elev= 30
  4045.4   433.1  4099.7  433.23  4185.3  430.37  4335.8  433.21  4456.4  433.21
  4482.5  431.79    4488  430.44  4496.5  430.64  4503.2  427.51  4536.5  424.19
  4576.4  418.65  4645.9  413.65  4760.5  411.08  4896.8   409.4    4955  409.56
  4986.2  410.72  5000.4  409.16  5007.1  410.64  5047.4  408.98  5047.9  408.48
  5052.2  408.98  5215.5  409.32  5276.6  409.89  5368.6  412.49  5390.4  414.41
  5474.9  418.28  5546.1  423.71    5577  425.01  5643.7  426.31  5732.6  428.48
#Mann= 6 ,-1 , 0
  4045.4     .05       0  5047.4     .03       0  5052.2     .05       0
  5215.5     .05       0    5577     .12       0  5643.7     .05       0
Bank Sta=5047.4,5052.2
XS Rating Curve= 0 ,0
Exp/Cntr=0.3,0.1

Type RM Length L Ch R = 1 ,5134    ,579,579,579
BEGIN DESCRIPTION:
Mapping XS 77fc70da
END DESCRIPTION:
XS GIS Cut Line= 3
      2727290.77      6897555.99       2728144.9      6898108.06
      2729295.92      6898920.54
#Sta/Elev= 30
  3994.9  435.12  4132.1  429.13  4176.5     426  4182.4   426.4  4263.1  424.07
  4276.1  423.13  4285.3  421.38  4306.4  420.27  4421.2  418.37    4509  414.29
  4617.8  411.89  4681.2  409.34  4732.6  410.22  4847.4  409.46  5486.2  408.99
  5487.2  408.49  5492.1  408.99    5531   410.5  5545.8  409.93  5661.6  415.46
  5724.3  419.24  5774.8  424.16  5846.2  427.56  5896.7  428.53    5962   427.2
  6048.2  427.28  6098.7     428  6127.1  429.38  6163.9  428.41  6420.8  433.47
#Mann= 3 ,-1 , 0
  3994.9     .03       0  5486.2     .03       0  5492.1     .03       0
Bank Sta=5486.2,5492.1
XS Rating Curve= 0 ,0
Exp/Cntr=0.3,0.1

Type RM Length L Ch R = 1 ,4555    ,329,329,329
BEGIN DESCRIPTION:
Mapping XS 41c847b7
END DESCRIPTION:
XS GIS Cut Line= 3
      2726863.68      6897988.28      2727738.65      6898519.51
      2729358.43      6899295.55
#Sta/Elev= 30
  3991.8  449.42  4104.3  446.44    4170  443.06  4205.2  441.03  4251.6  436.09
  4380.6  429.22  4431.9  429.96  4447.4  425.81  4490.1  420.93  4526.9  420.33
  4542.4  419.22  4548.2  417.32  4563.7  418.05  4600.5  416.42  4627.7  413.49
  4719.7  409.07  4720.7  408.57  4725.6  409.07    4775  409.93  5607.4  409.24
  5680.9  411.59    5711  413.89    5766  414.14  5958.4  421.07    6049  422.35
    6185  427.47  6445.3  432.51    6468  434.78  6581.3  435.35  6811.5  439.62
#Mann= 3 ,-1 , 0
  3991.8     .03       0  4719.7     .03       0  4725.6     .03       0
Bank Sta=4719.7,4725.6
XS Rating Curve= 0 ,0
Exp/Cntr=0.3,0.1

Type RM Length L Ch R = 1 ,4226    ,74,74,74
BEGIN DESCRIPTION:
Mapping XS 200981e2
END DESCRIPTION:
XS GIS Cut Line= 4
      2726724.77      6898210.05      2727214.35        6898592.
      2727488.65       6898741.3      2728891.19      6899682.11
#Sta/Elev= 30
  4061.7  450.92  4234.2  447.26  4383.5  441.82  4397.9  439.49  4418.8  430.67
  4441.4  423.08  4455.8  419.76    4483  417.97  4555.3  417.74  4576.1  419.34
  4583.3  422.02    4597  423.64  4669.3  415.98  4772.3  410.02    4778  410.89
  5205.5  409.18  5206.5  408.68  5211.4  409.18  5684.8  410.21  5720.8  411.87
  5807.9  419.87  5849.9  421.53  5987.9  423.71    5994  425.39  6008.9  426.17
    6060  424.42    6132  424.91  6312.1  429.88  6420.1  435.23  6683.8  440.48
#Mann= 3 ,-1 , 0
  4061.7     .03       0  5205.5     .03       0  5211.4     .03       0
Bank Sta=5205.5,5211.4
XS Rating Curve= 0 ,0
Exp/Cntr=0.3,0.1

Type RM Length L Ch R = 1 ,4152    ,113,113,113
BEGIN DESCRIPTION:
Mapping XS d06e68bc
END DESCRIPTION:
XS GIS Cut Line= 5
       2726721.3      6898248.25       2727183.1      6898630.19
       2727495.6      6898828.11      2728103.24      6899227.41
      2728828.94      6899685.75
#Sta/Elev= 30
  4060.4   450.2  4214.8  448.16  4371.1  442.11  4442.7   419.8  4524.3  417.57
  4525.3  417.07  4530.4  417.57  4634.2  422.21  4828.8  423.73  5436.9  423.62
  5464.8   422.1    5495  423.58  5500.9  421.93  5552.2  423.49  5573.3   421.7
  5603.4   423.5  5609.4  421.01  5616.4  423.14  5675.8   422.7  5681.7  420.02
  5688.2   422.3  5711.9  422.64  5717.9  419.33    5733  422.56    5739  420.97
  5769.3  422.19  5775.2  420.25  5905.8  425.91  6161.1  427.72    6615  439.42
#Mann= 3 ,-1 , 0
  4060.4     .05       0  4524.3     .04       0  4530.4     .05       0
Bank Sta=4524.3,4530.4
XS Rating Curve= 0 ,0
Exp/Cntr=0.3,0.1

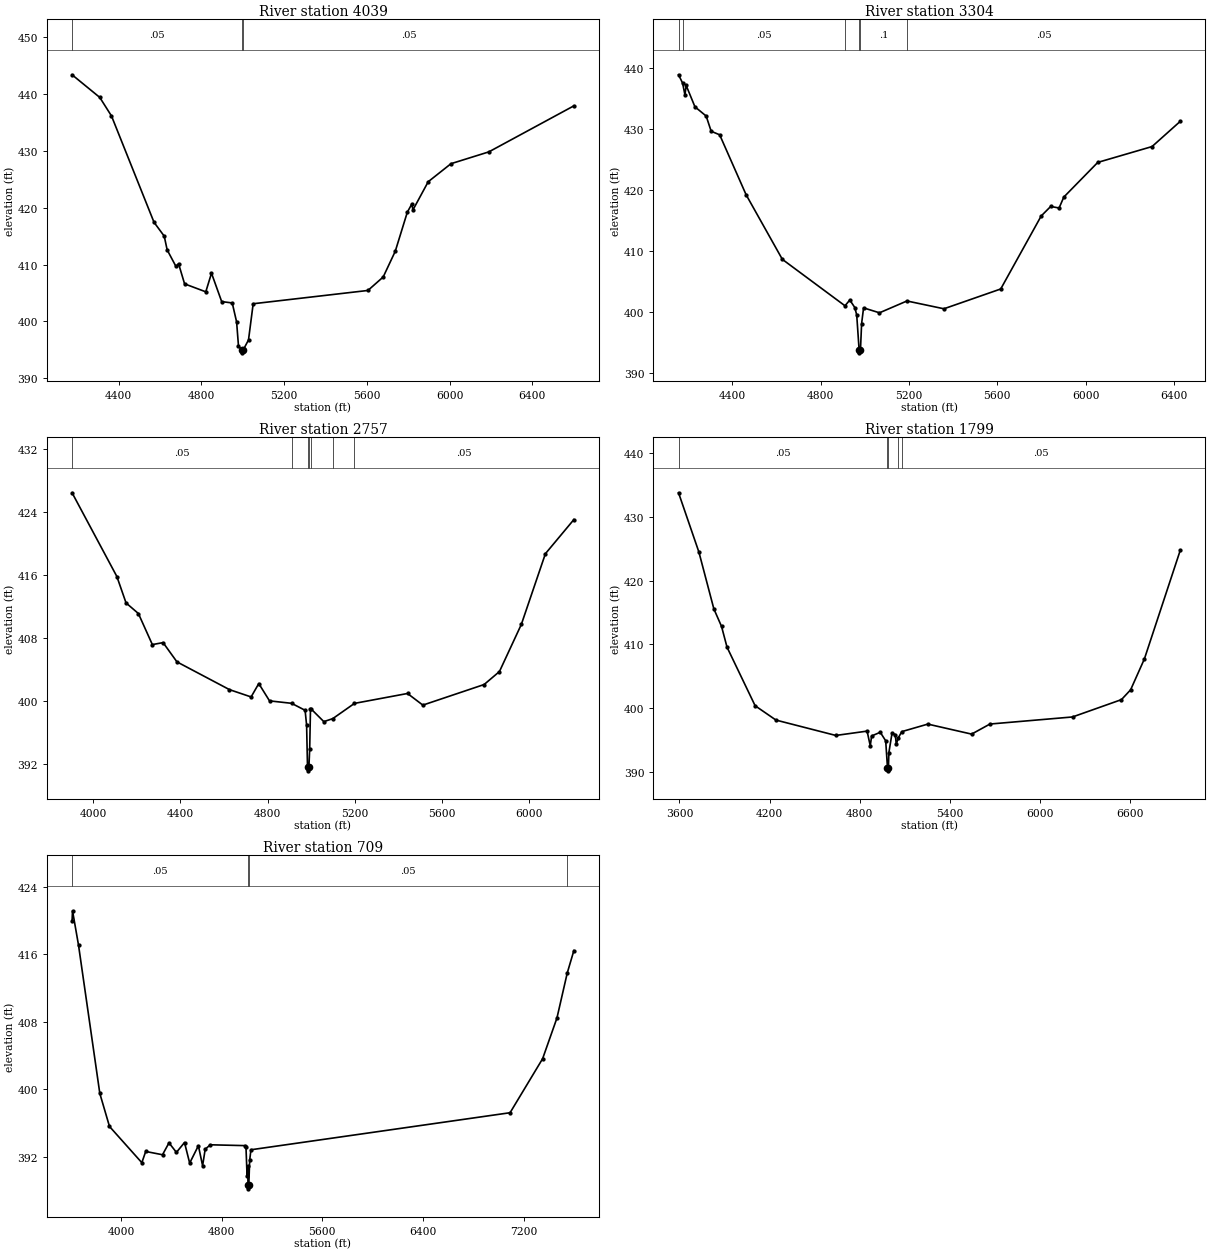
Type RM Length L Ch R = 1 ,4039    ,735,735,735
BEGIN DESCRIPTION:
Mapping XS dd8755f6
END DESCRIPTION:
XS GIS Cut Line= 6
      2726773.39      6898484.37      2727116.41      6898864.75
      2727262.46      6898808.13      2727392.67      6898894.34
      2728283.79       6899428.8      2728769.89      6899710.04
#Sta/Elev= 30
    4175  443.42  4308.8  439.44  4365.6  436.17  4571.1  417.46  4620.5  415.02
  4634.7   412.6  4677.3  409.68  4689.7  410.18  4718.9  406.62  4821.4  405.22
    4849   408.5  4898.2   403.5  4949.3  403.26  4970.4  399.92  4979.5  395.67
  4995.9  394.98  4996.9  394.48  5002.1  394.98  5027.9  396.75  5050.5  403.12
  5605.2  405.46    5679  407.83  5737.4  412.36  5795.7  419.24    5817  420.65
  5822.9  419.64  5896.7   424.6  6006.7  427.77  6189.7  429.85  6600.7  437.95
#Mann= 3 ,-1 , 0
    4175     .05       0  4995.9     .04       0  5002.1     .05       0
Bank Sta=4995.9,5002.1
XS Rating Curve= 0 ,0
Exp/Cntr=0.3,0.1

Type RM Length L Ch R = 1 ,3304    ,547,547,547
BEGIN DESCRIPTION:
Mapping XS f71b2cfc
END DESCRIPTION:
XS GIS Cut Line= 3
      2726736.93      6898572.92      2727106.71      6899343.73
      2728491.01      6899655.98
#Sta/Elev= 30
  4155.6  438.93    4174  437.57  4184.7  435.62  4190.2  437.18    4230  433.67
  4280.8  432.16  4303.5  429.66    4342  429.08    4462  419.23  4626.1  408.64
    4910  401.02  4931.7  401.97  4954.3  400.74  4963.1  399.51  4973.9   393.8
  4974.9   393.3  4980.1   393.8  4985.3  398.11  4994.1  400.68  5066.2  399.87
  5190.7  401.81  5358.3  400.53  5615.7  403.78  5799.1  415.76  5842.1  417.32
  5880.2  417.07  5901.6  418.86  6055.4  424.55  6301.4  427.15  6429.6   431.3
#Mann= 6 ,-1 , 0
  4155.6     .12       0    4174     .05       0    4910      .1       0
  4973.9     .07       0  4980.1      .1       0  5190.7     .05       0
Bank Sta=4973.9,4980.1
XS Rating Curve= 0 ,0
Exp/Cntr=0.3,0.1

Type RM Length L Ch R = 1 ,2757    ,958,958,958
BEGIN DESCRIPTION:
Caney T2 2.0
END DESCRIPTION:
XS GIS Cut Line= 3
      2726075.98      6898960.97        2726826.        6899761.
      2728026.02        6899661.
#Sta/Elev= 30
  3903.4  426.47  4108.8  415.82  4150.9  412.46  4207.5  411.11  4271.5  407.16
  4320.8  407.41  4384.3  404.96  4625.1  401.43  4724.3   400.5  4759.5   402.2
  4808.8     400  4909.9  399.69  4971.9   398.8  4978.8  396.91  4982.9   391.6
  4983.9   391.1  4989.3   391.6  4992.9  393.84  4996.6  398.99  4998.8  398.99
  5057.7  397.36  5098.7  397.74  5198.3  399.68  5441.5  400.94  5511.8  399.46
  5792.8  402.08    5863  403.73  5963.3  409.72  6073.7  418.72  6204.2  423.06
#Mann= 7 ,-1 , 0
  3903.4     .05       0  4909.9      .1       0  4982.9     .05       0
  4989.3      .1       0  4998.8      .1       0  5098.7     .12       0
  5198.3     .05       0
Bank Sta=4982.9,4989.3
XS Rating Curve= 0 ,0
Exp/Cntr=0.3,0.1

Type RM Length L Ch R = 1 ,1799    ,1090,1090,1090
BEGIN DESCRIPTION:
Mapping XS c7e430a5
END DESCRIPTION:
XS GIS Cut Line= 4
       2725675.7      6899264.38      2726441.35      6900436.29
        2726551.        6900536.      2728311.07      6900207.13
#Sta/Elev= 30
  3593.8  433.77  3729.3  424.47  3828.8  415.56  3880.1   412.8  3916.3  409.56
  4103.4  400.37  4242.1  398.12  4640.3  395.71  4848.4  396.39  4869.4  394.08
  4878.6  395.63  4935.9  396.21  4972.1  394.87    4984  390.66    4985  390.16
  4990.4  390.66  4993.2  393.01  5014.2  396.06  5035.8  395.85  5042.5  394.34
  5056.1  395.33  5079.1  396.31  5252.3  397.49  5543.7  395.92  5665.8   397.5
  6215.1  398.61  6540.7  401.33  6601.7  402.87  6693.3  407.71  6932.4  424.78
#Mann= 5 ,-1 , 0
  3593.8     .05       0    4984     .04       0  4990.4     .05       0
  5056.1      .1       0  5079.1     .05       0
Bank Sta=4984,4990.4
XS Rating Curve= 0 ,0
Exp/Cntr=0.3,0.1

Type RM Length L Ch R = 1 ,709     ,0,0,0
BEGIN DESCRIPTION:
Caney T2 1.0
END DESCRIPTION:
XS GIS Cut Line= 4
       2725460.4       6899861.6      2725777.18      6901206.81
      2726122.28      6901184.58      2728305.96      6900608.16
#Sta/Elev= 30
  3611.9  419.95  3615.5  421.17    3663  417.11  3832.4  399.52  3909.2  395.61
  4166.1  391.32  4196.9  392.65  4330.4  392.26  4381.8  393.67  4440.9  392.54
  4505.1  393.71  4546.2  391.27  4615.4  393.33  4648.9  390.96  4669.5  392.92
  4710.6  393.44  4987.9  393.34  4993.5  393.15  5002.1  389.76  5007.1   390.9
  5009.5  388.72  5010.6  388.22    5016  388.72  5022.8   391.6  5032.8  392.85
  7091.5  397.24    7350  403.64  7463.8  408.46  7545.9  413.81  7598.2  416.45
#Mann= 4 ,-1 , 0
  3611.9     .05       0  5009.5     .04       0    5016     .05       0
  7545.9      .1       0
Bank Sta=5009.5,5016
XS Rating Curve= 0 ,0
Exp/Cntr=0.3,0.1

Chan Stop Cuts=-1
Use User Specified Reach Order=0
Composite Channel Slope=5