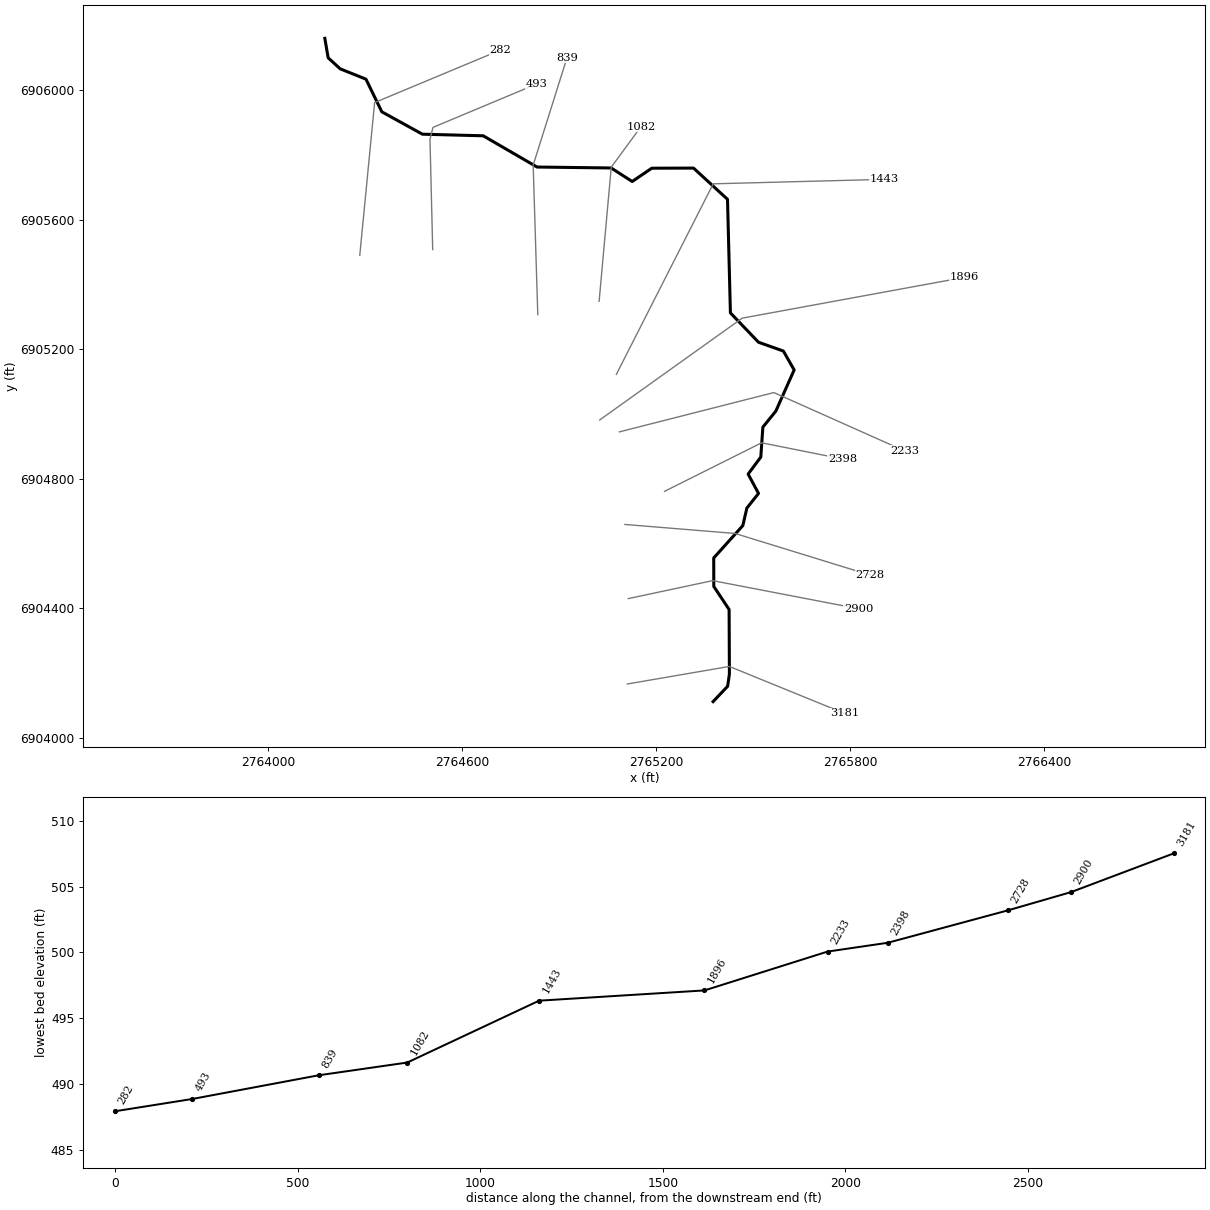
--- Caney T20.prj (project) ---

Proj Title=Caney T20 Base Level Engineering
Current Plan=p01
Default Exp/Contr=0.3,0.1
English Units
Geom File=g01
Flow File=f01
Plan File=p01
Y Axis Title=Elevation
X Axis Title(PF)=Main Channel Distance
X Axis Title(XS)=Station
BEGIN DESCRIPTION:
Caney T20
END DESCRIPTION:
DSS Export Rating Curves= 0
DSS Export Rating Curve Sorted= 0
DSS Export Volume Flow Curves= 0
DXF OffsetX= 0
DXF OffsetY= 0
DXF ScaleX= 1
DXF ScaleY= 10

--- Caney T20.p01 (plan) ---

Plan Title=Multiple Run
Short Identifier=Multiple
Geom File=g01
Flow File=f01
Subcritical Flow
K Sum by GR= 0
Std Step Tol= 0.01
Critical Tol= 0.01
Num of Std Step Trials= 20
Max Error Tol= 0.3
Flow Tol Ratio= 0.001
Split Flow NTrial= 30
Split Flow Tol= 0.02
Split Flow Ratio= 0.02
Log Output Level= 0
Friction Slope Method= 1
Unsteady Friction Slope Method= 2
Unsteady Bridges Friction Slope Method= 1
Parabolic Critical Depth
Global Vel Dist=  1 , 1 , 1
Global Log Level= 0
CheckData=True
Encroach Param= -1, 0, 0, 0
BEGIN DESCRIPTION:
Multiple Run
END DESCRIPTION:

--- Caney T20.f01 (steady flow) ---

Flow Title=Multiple
Number of Profiles=7
Profile Names=10-year,25-year,50-year,1pct_min,100-year,1pct_plu,500-year
River Rch & RM= Caney T20,Reach-1,3181
     334     434     512     301     601    1200     829
Boundary for River Rch & Prof#=Caney T20,Reach-1,1
Up Type=0
Dn Type=3
Dn Slope=0.005
Boundary for River Rch & Prof#=Caney T20,Reach-1,2
Up Type=0
Dn Type=3
Dn Slope=0.005
Boundary for River Rch & Prof#=Caney T20,Reach-1,3
Up Type=0
Dn Type=3
Dn Slope=0.005
Boundary for River Rch & Prof#=Caney T20,Reach-1,4
Up Type=0
Dn Type=3
Dn Slope=0.005
Boundary for River Rch & Prof#=Caney T20,Reach-1,5
Up Type=0
Dn Type=3
Dn Slope=0.005
Boundary for River Rch & Prof#=Caney T20,Reach-1,6
Up Type=0
Dn Type=3
Dn Slope=0.005
Boundary for River Rch & Prof#=Caney T20,Reach-1,7
Up Type=0
Dn Type=3
Dn Slope=0.005

--- Caney T20.g01 (geometry) ---

Geom Title=Existing Conditions

River Reach=Caney T20,Reach-1
Reach XY= 30
      2765376.00      6904111.00      2765420.86      6904158.41
      2765426.41      6904195.83      2765425.48      6904395.78
      2765378.16      6904466.98      2765377.97      6904555.11
      2765467.86      6904654.96      2765480.44      6904709.35
      2765516.42      6904754.45      2765484.28      6904814.22
      2765523.46      6904866.89      2765529.82      6904959.41
      2765569.89      6905008.82      2765626.54      6905136.12
      2765593.22      6905194.50      2765516.32      6905221.78
      2765429.53      6905312.45      2765420.55      6905663.47
      2765315.57      6905759.97      2765186.44      6905759.63
      2765126.00      6905718.56      2765060.84      6905760.34
      2764831.93      6905763.24      2764665.50      6905859.80
      2764477.55      6905864.75      2764352.16      6905933.86
      2764303.14      6906034.83      2764223.52      6906066.72
      2764186.33      6906100.75      2764176.00      6906161.00

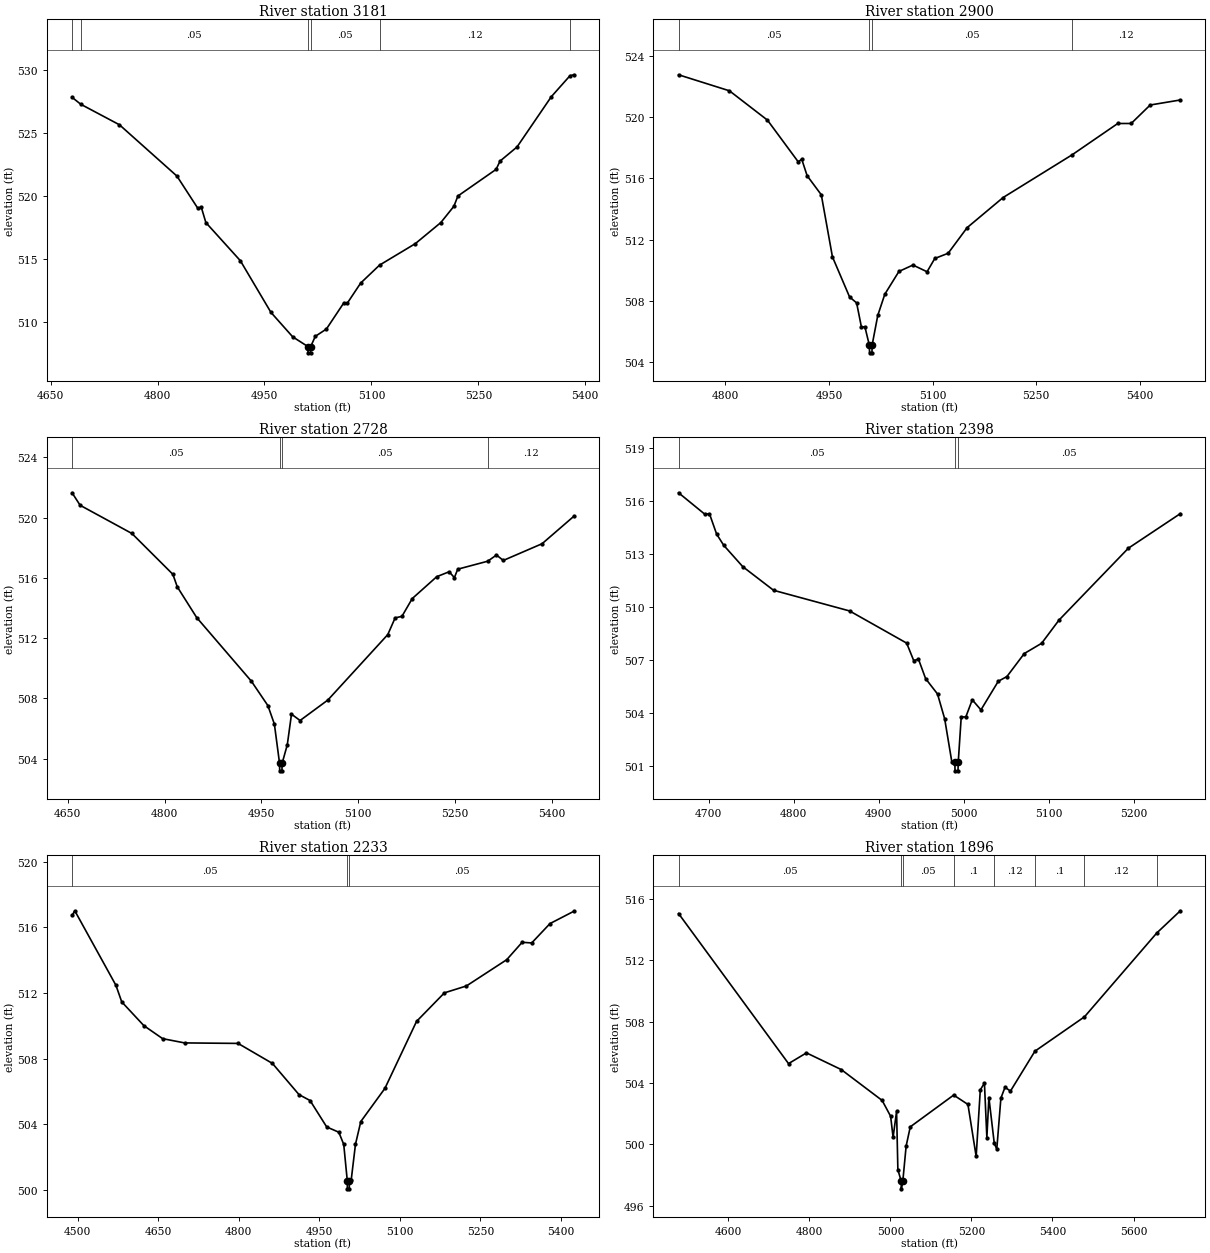
Type RM Length L Ch R = 1,3181,281,281,281
BEGIN DESCRIPTION:
Caney T20 5.0
END DESCRIPTION:
XS GIS Cut Line= 3
      2765111.01      6904165.51      2765426.28      6904219.73
      2765781.83      6904074.69
#Sta/Elev= 30
  4680.1  527.80  4692.3  527.25  4746.6  525.62  4827.2  521.55  4856.3  519.01
  4861.4  519.07  4867.8  517.86  4916.2  514.83  4959.1  510.73  4989.6  508.79
  5010.9  508.02  5011.1  507.52  5014.6  507.52  5014.9  508.02  5021.3  508.83
  5036.9  509.41  5061.0  511.46  5066.4  511.48  5085.0  513.06  5111.4  514.48
  5161.7  516.19  5197.4  517.86  5215.7  519.15  5221.4  519.97  5274.9  522.08
  5280.5  522.74  5304.3  523.86  5352.4  527.85  5378.5  529.51  5384.0  529.59
#Mann=6,-1,0
  4680.1    0.12       0  4692.3    0.05       0  5010.9    0.04       0
  5014.9    0.05       0  5111.4    0.12       0  5378.5    0.05       0
Bank Sta=5010.9,5014.9
Exp/Cntr=0.3,0.1

Type RM Length L Ch R = 1,2900,172,172,172
BEGIN DESCRIPTION:
Mapping XS c746c35d
END DESCRIPTION:
XS GIS Cut Line= 3
      2765114.05      6904429.40      2765374.44      6904484.95
      2765825.82      6904398.15
#Sta/Elev= 30
  4732.5  522.79  4806.1  521.74  4861.1  519.82  4905.6  517.09  4910.7  517.26
  4918.5  516.18  4939.0  514.93  4955.1  510.87  4979.9  508.24  4990.1  507.85
  4997.0  506.28  5002.1  506.28  5008.5  505.08  5008.8  504.58  5012.3  504.58
  5012.5  505.08  5020.7  507.03  5030.9  508.42  5051.3  509.91  5071.6  510.33
  5092.0  509.89  5103.2  510.76  5122.5  511.10  5150.0  512.78  5202.0  514.75
  5301.9  517.55  5367.9  519.60  5387.3  519.60  5414.8  520.81  5458.4  521.14
#Mann=4,-1,0
  4732.5    0.05       0  5008.5    0.05       0  5012.5    0.05       0
  5301.9    0.12       0
Bank Sta=5008.5,5012.5
Exp/Cntr=0.3,0.1

Type RM Length L Ch R = 1,2728,330,330,330
BEGIN DESCRIPTION:
Mapping XS 5fa84443
END DESCRIPTION:
XS GIS Cut Line= 3
      2765103.58      6904658.56      2765443.88      6904630.78
      2765860.59      6904502.30
#Sta/Elev= 30
  4656.7  521.65  4669.2  520.82  4749.4  518.95  4812.9  516.24  4819.7  515.41
  4849.8  513.37  4934.5  509.15  4960.1  507.53  4970.2  506.30  4978.2  503.70
  4978.4  503.20  4981.9  503.20  4982.2  503.70  4990.2  504.93  4996.7  506.96
  5010.0  506.54  5053.1  507.90  5145.9  512.24  5157.3  513.35  5167.8  513.45
  5183.8  514.63  5221.7  516.08  5241.0  516.41  5249.1  516.02  5254.3  516.58
  5300.8  517.11  5314.3  517.52  5324.9  517.16  5385.0  518.27  5434.2  520.09
#Mann=4,-1,0
  4656.7    0.05       0  4978.2    0.04       0  4982.2    0.05       0
  5300.8    0.12       0
Bank Sta=4978.2,4982.2
Exp/Cntr=0.3,0.1

Type RM Length L Ch R = 1,2398,165,165,165
BEGIN DESCRIPTION:
Caney T20 4.0
END DESCRIPTION:
XS GIS Cut Line= 3
      2765225.97      6904760.98      2765526.00      6904911.00
      2765776.00      6904861.00
#Sta/Elev= 30
  4664.6  516.47  4695.4  515.26  4701.0  515.28  4709.4  514.13  4717.7  513.50
  4740.1  512.29  4776.4  510.95  4865.9  509.78  4933.0  507.96  4941.3  506.97
  4946.9  507.05  4955.3  505.95  4969.3  505.08  4977.7  503.68  4986.1  501.25
  4989.7  501.23  4989.9  500.73  4993.4  500.73  4993.7  501.23  4997.2  503.78
  5002.6  503.78  5010.2  504.75  5020.4  504.18  5040.8  505.80  5051.0  506.07
  5071.4  507.37  5091.8  507.95  5112.2  509.26  5193.8  513.33  5255.0  515.29
#Mann=3,-1,0
  4664.6    0.05       0  4989.7    0.04       0  4993.7    0.05       0
Bank Sta=4989.7,4993.7
Exp/Cntr=0.3,0.1

Type RM Length L Ch R = 1,2233,337,337,337
BEGIN DESCRIPTION:
Mapping XS c6011cad
END DESCRIPTION:
XS GIS Cut Line= 3
      2765086.37      6904944.68      2765563.76      6905066.20
      2765967.39      6904886.09
#Sta/Elev= 30
  4489.5  516.72  4494.6  517.00  4571.2  512.46  4582.0  511.45  4623.3  510.00
  4658.2  509.21  4699.1  508.95  4798.7  508.92  4862.7  507.70  4912.2  505.80
  4932.8  505.44  4963.8  503.83  4986.3  503.51  4995.5  502.77  5002.1  500.56
  5002.3  500.06  5005.8  500.06  5006.1  500.56  5009.5  500.62  5017.4  502.78
  5027.3  504.16  5072.2  506.18  5131.1  510.26  5183.0  512.00  5224.0  512.42
  5299.1  514.02  5327.8  515.08  5345.6  515.04  5379.7  516.22  5424.1  516.97
#Mann=3,-1,0
  4489.5    0.05       0  5002.1    0.04       0  5006.1    0.05       0
Bank Sta=5002.1,5006.1
Exp/Cntr=0.3,0.1

Type RM Length L Ch R = 1,1896,453,453,453
BEGIN DESCRIPTION:
Mapping XS 92d958c5
END DESCRIPTION:
XS GIS Cut Line= 3
      2765025.57      6904981.56      2765466.11      6905296.24
      2766151.48      6905422.03
#Sta/Elev= 30
  4477.3  515.05  4748.7  505.27  4792.9  505.97  4878.9  504.88  4979.7  502.87
  5000.6  501.84  5006.7  500.47  5015.3  502.15  5018.5  498.36  5026.7  497.61
  5027.0  497.11  5030.7  497.61  5038.9  499.90  5049.1  501.15  5156.2  503.22
  5191.4  502.61  5211.7  499.22  5221.9  503.56  5232.1  504.00  5238.1  500.45
  5243.1  503.06  5256.4  500.07  5262.6  499.70  5272.7  503.02  5282.9  503.73
  5296.3  503.48  5356.7  506.08  5479.0  508.32  5657.3  513.78  5715.5  515.23
#Mann=8,-1,0
  4477.3    0.05       0  5026.7    0.04       0  5030.7    0.05       0
  5156.2     0.1       0  5256.4    0.12       0  5356.7     0.1       0
  5479.0    0.12       0  5657.3    0.05       0
Bank Sta=5026.7,5030.7
Exp/Cntr=0.3,0.1

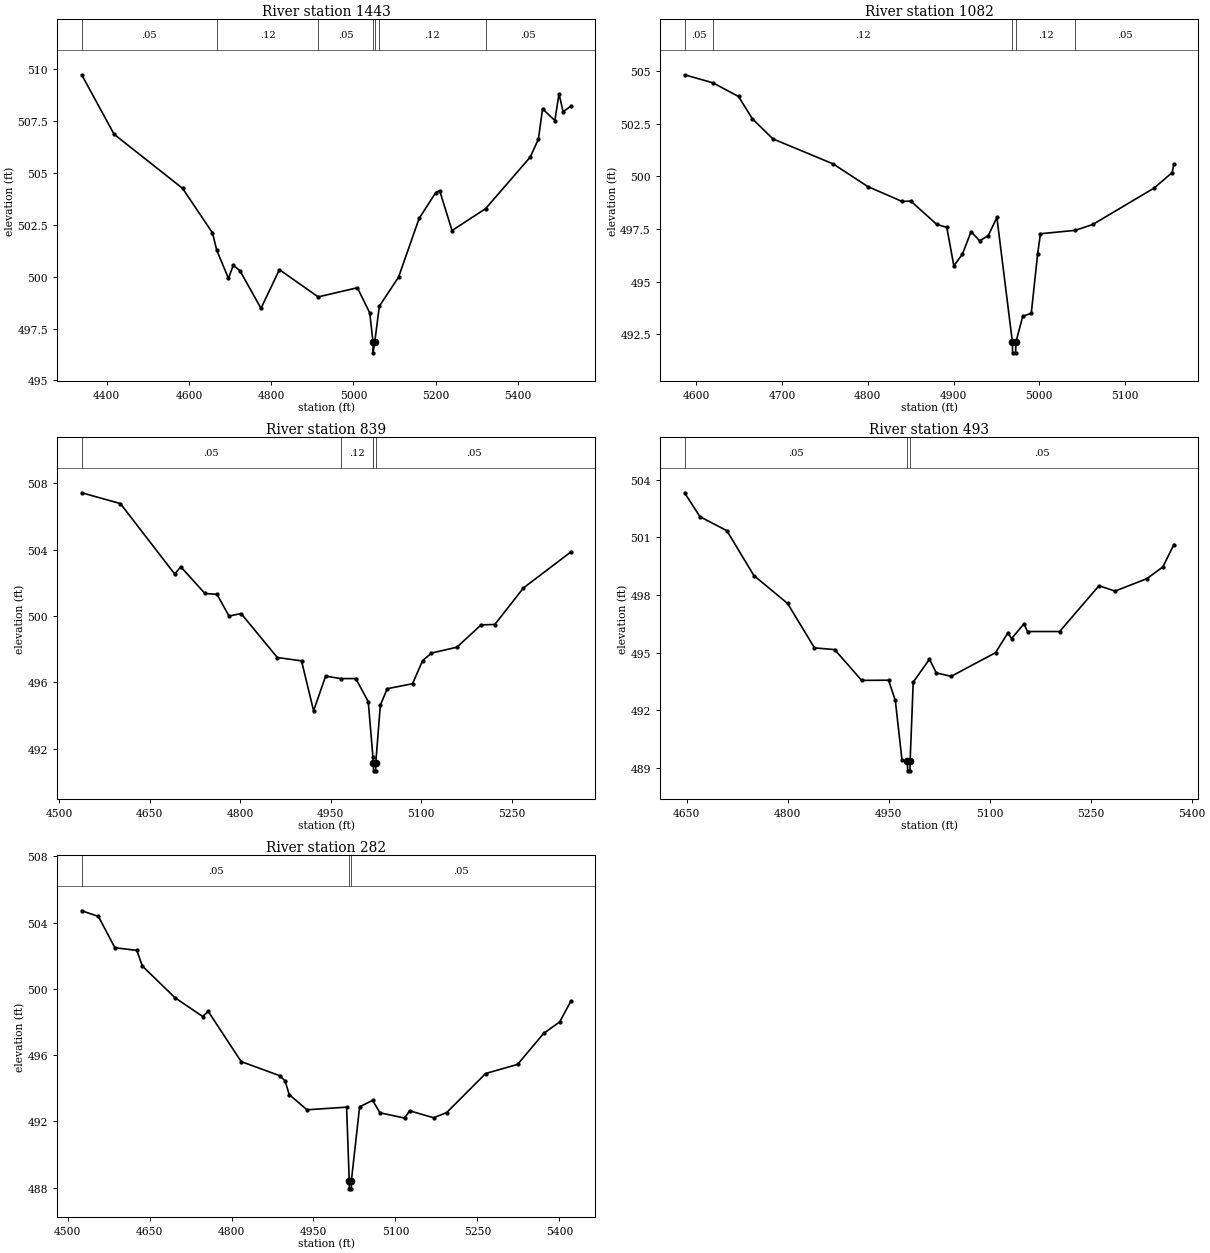
Type RM Length L Ch R = 1,1443,361,361,361
BEGIN DESCRIPTION:
Caney T20 2.0
END DESCRIPTION:
XS GIS Cut Line= 3
      2765077.01      6905122.46      2765376.35      6905711.35
      2765905.17      6905725.15
#Sta/Elev= 30
  4339.4  509.70  4418.2  506.84  4584.6  504.24  4657.3  502.10  4667.8  501.26
  4696.2  499.91  4707.9  500.54  4724.1  500.28  4775.3  498.47  4820.1  500.33
  4914.3  499.02  5009.7  499.46  5039.7  498.25  5047.7  496.83  5047.9  496.33
  5051.7  496.83  5063.0  498.57  5109.7  499.97  5159.7  502.79  5199.7  504.02
  5209.7  504.13  5239.7  502.21  5321.2  503.26  5429.8  505.74  5449.8  506.61
  5459.8  508.06  5489.8  507.50  5499.8  508.79  5509.8  507.92  5529.0  508.20
#Mann=7,-1,0
  4339.4    0.05       0  4667.8    0.12       0  4914.3    0.05       0
  5047.7    0.04       0  5051.7    0.05       0  5063.0    0.12       0
  5321.2    0.05       0
Bank Sta=5047.7,5051.7
Exp/Cntr=0.3,0.1

Type RM Length L Ch R = 1,1082,243,243,243
BEGIN DESCRIPTION:
Mapping XS 0a11399c
END DESCRIPTION:
XS GIS Cut Line= 3
      2765023.77      6905348.40      2765061.22      6905762.80
      2765152.51      6905887.21
#Sta/Elev= 30
  4586.4  504.82  4619.4  504.44  4649.3  503.79  4665.5  502.73  4689.4  501.78
  4759.7  500.59  4799.9  499.52  4840.0  498.81  4850.1  498.83  4880.2  497.73
  4892.1  497.58  4900.3  495.76  4910.3  496.31  4920.4  497.38  4930.4  496.94
  4940.4  497.19  4950.5  498.05  4968.6  492.13  4968.8  491.63  4972.3  491.63
  4972.6  492.13  4980.6  493.36  4990.6  493.51  4997.9  496.30  5001.3  497.28
  5041.8  497.44  5062.3  497.72  5133.9  499.45  5154.8  500.18  5156.8  500.59
#Mann=5,-1,0
  4586.4    0.05       0  4619.4    0.12       0  4968.6    0.07       0
  4972.6    0.12       0  5041.8    0.05       0
Bank Sta=4968.6,4972.6
Exp/Cntr=0.3,0.1

Type RM Length L Ch R = 1,839,346,346,346
BEGIN DESCRIPTION:
Mapping XS a90386bc
END DESCRIPTION:
XS GIS Cut Line= 3
      2764834.19      6905306.91      2764819.92      6905769.09
      2764924.60      6906101.50
#Sta/Elev= 30
  4537.6  507.42  4601.7  506.77  4691.8  502.52  4701.8  502.96  4741.8  501.35
  4761.8  501.30  4781.8  499.99  4801.8  500.14  4861.8  497.49  4901.9  497.29
  4921.9  494.28  4941.9  496.37  4966.5  496.22  4991.9  496.22  5012.5  494.83
  5020.2  491.51  5021.0  491.16  5021.2  490.66  5024.7  490.66  5025.0  491.16
  5032.5  494.61  5043.9  495.61  5085.9  495.91  5102.5  497.30  5117.3  497.76
  5159.3  498.11  5199.6  499.46  5222.2  499.48  5269.6  501.68  5348.5  503.86
#Mann=5,-1,0
  4537.6    0.05       0  4966.5    0.12       0  5020.2    0.05       0
  5021.0    0.07       0  5025.0    0.05       0
Bank Sta=5021,5025
Exp/Cntr=0.3,0.1

Type RM Length L Ch R = 1,493,211,211,211
BEGIN DESCRIPTION:
Mapping XS b90cce65
END DESCRIPTION:
XS GIS Cut Line= 4
      2764509.40      6905508.17      2764501.01      6905849.17
      2764510.37      6905885.77      2764831.01      6906020.05
#Sta/Elev= 30
  4647.0  503.31  4669.8  502.07  4709.8  501.34  4749.9  499.01  4799.9  497.56
  4839.9  495.25  4869.9  495.16  4909.9  493.56  4949.9  493.57  4959.9  492.52
  4969.9  489.40  4977.9  489.36  4978.2  488.86  4981.7  488.86  4981.9  489.36
  4986.5  493.47  5010.6  494.66  5020.8  493.95  5042.8  493.77  5108.7  495.00
  5127.1  496.03  5132.5  495.73  5150.9  496.50  5156.3  496.10  5203.9  496.10
  5262.3  498.48  5286.1  498.20  5333.6  498.85  5357.2  499.46  5373.5  500.62
#Mann=3,-1,0
  4647.0    0.05       0  4977.9    0.04       0  4981.9    0.05       0
Bank Sta=4977.9,4981.9
Exp/Cntr=0.3,0.1

Type RM Length L Ch R = 1,282,0,0,0
BEGIN DESCRIPTION:
Caney T20 1.0
END DESCRIPTION:
XS GIS Cut Line= 3
      2764284.04      6905490.58      2764329.90      6905962.46
      2764718.60      6906124.70
#Sta/Elev= 30
  4525.9  504.71  4556.5  504.37  4586.6  502.48  4626.8  502.32  4636.8  501.38
  4696.7  499.46  4747.4  498.33  4757.4  498.64  4817.7  495.61  4888.0  494.76
  4898.1  494.45  4905.5  493.62  4938.2  492.70  5010.6  492.86  5015.4  488.43
  5015.7  487.93  5019.2  487.93  5019.4  488.43  5034.4  492.88  5058.2  493.27
  5071.6  492.52  5116.7  492.20  5125.8  492.64  5169.8  492.22  5193.6  492.53
  5265.0  494.89  5323.5  495.44  5371.1  497.31  5400.4  498.00  5421.2  499.27
#Mann=3,-1,0
  4525.9    0.05       0  5015.4    0.04       0  5019.4    0.05       0
Bank Sta=5015.4,5019.4
Exp/Cntr=0.3,0.1

Chan Stop Cuts=-1