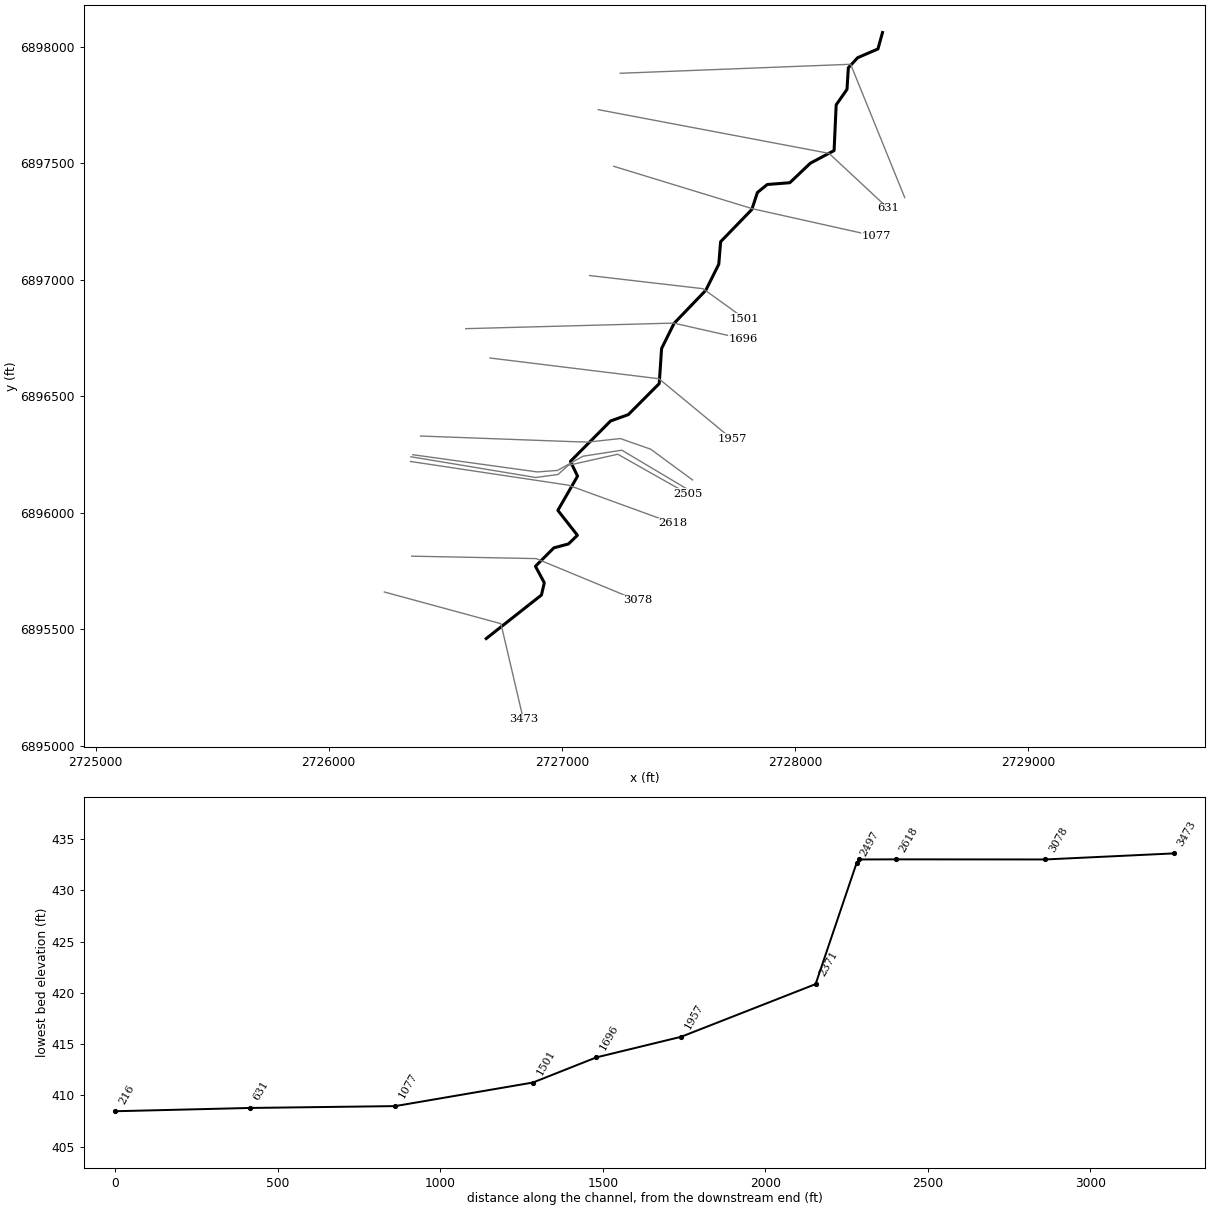
--- Caney T2_1.prj (project) ---

Proj Title=Caney T2_1 Base Level Engineering
Current Plan=p01
Default Exp/Contr=0.3,0.1
English Units
Geom File=g01
Flow File=f01
Plan File=p01
BEGIN DESCRIPTION:
Caney T2_1
END DESCRIPTION:

--- Caney T2_1.p01 (plan) ---

Plan Title=Multiple Run
Short Identifier=Multiple
Geom File=g01
Flow File=f01
Subcritical Flow
K Sum by GR= 0
Std Step Tol= 0.01
Critical Tol= 0.01
Num of Std Step Trials= 20
Max Error Tol= 0.3
Flow Tol Ratio= 0.001
Split Flow NTrial= 30
Split Flow Tol= 0.02
Split Flow Ratio= 0.02
Log Output Level= 0
Friction Slope Method= 1
Unsteady Friction Slope Method= 2
Unsteady Bridges Friction Slope Method= 1
Parabolic Critical Depth
Global Vel Dist=  1 , 1 , 1
Global Log Level= 0
CheckData=True
Encroach Param= -1, 0, 0, 0
BEGIN DESCRIPTION:
Multiple Run
END DESCRIPTION:

--- Caney T2_1.f01 (steady flow) ---

Flow Title=Multiple
Number of Profiles=7
Profile Names=10-year,25-year,50-year,1pct_min,100-year,1pct_plu,500-year
River Rch & RM= Caney T2_1,Reach-1,3473
     471     618     733     433     863    1723    1194
Boundary for River Rch & Prof#=Caney T2_1,Reach-1,1
Up Type=0
Dn Type=3
Dn Slope=0.005
Boundary for River Rch & Prof#=Caney T2_1,Reach-1,2
Up Type=0
Dn Type=3
Dn Slope=0.005
Boundary for River Rch & Prof#=Caney T2_1,Reach-1,3
Up Type=0
Dn Type=3
Dn Slope=0.005
Boundary for River Rch & Prof#=Caney T2_1,Reach-1,4
Up Type=0
Dn Type=3
Dn Slope=0.005
Boundary for River Rch & Prof#=Caney T2_1,Reach-1,5
Up Type=0
Dn Type=3
Dn Slope=0.005
Boundary for River Rch & Prof#=Caney T2_1,Reach-1,6
Up Type=0
Dn Type=3
Dn Slope=0.005
Boundary for River Rch & Prof#=Caney T2_1,Reach-1,7
Up Type=0
Dn Type=3
Dn Slope=0.005

--- Caney T2_1.g01 (geometry) ---

Geom Title=Existing Conditions

River Reach=Caney T2_1,Reach-1
Reach XY= 30
      2726676.00      6895461.00      2726912.88      6895647.76
      2726925.11      6895700.36      2726887.11      6895771.08
      2726966.31      6895850.22      2727028.86      6895866.86
      2727067.15      6895904.05      2726983.31      6896010.91
      2727067.75      6896157.77      2727037.24      6896221.00
      2727209.33      6896394.35      2727285.68      6896421.78
      2727418.18      6896554.81      2727428.25      6896705.07
      2727481.83      6896813.30      2727617.86      6896954.94
      2727673.67      6897066.97      2727681.52      6897163.43
      2727815.21      6897301.34      2727839.46      6897374.63
      2727881.71      6897408.92      2727978.42      6897416.54
      2728066.35      6897500.19      2728168.31      6897554.52
      2728177.22      6897750.50      2728223.64      6897816.98
      2728229.52      6897909.72      2728269.63      6897952.99
      2728356.44      6897990.37      2728376.00      6898061.00

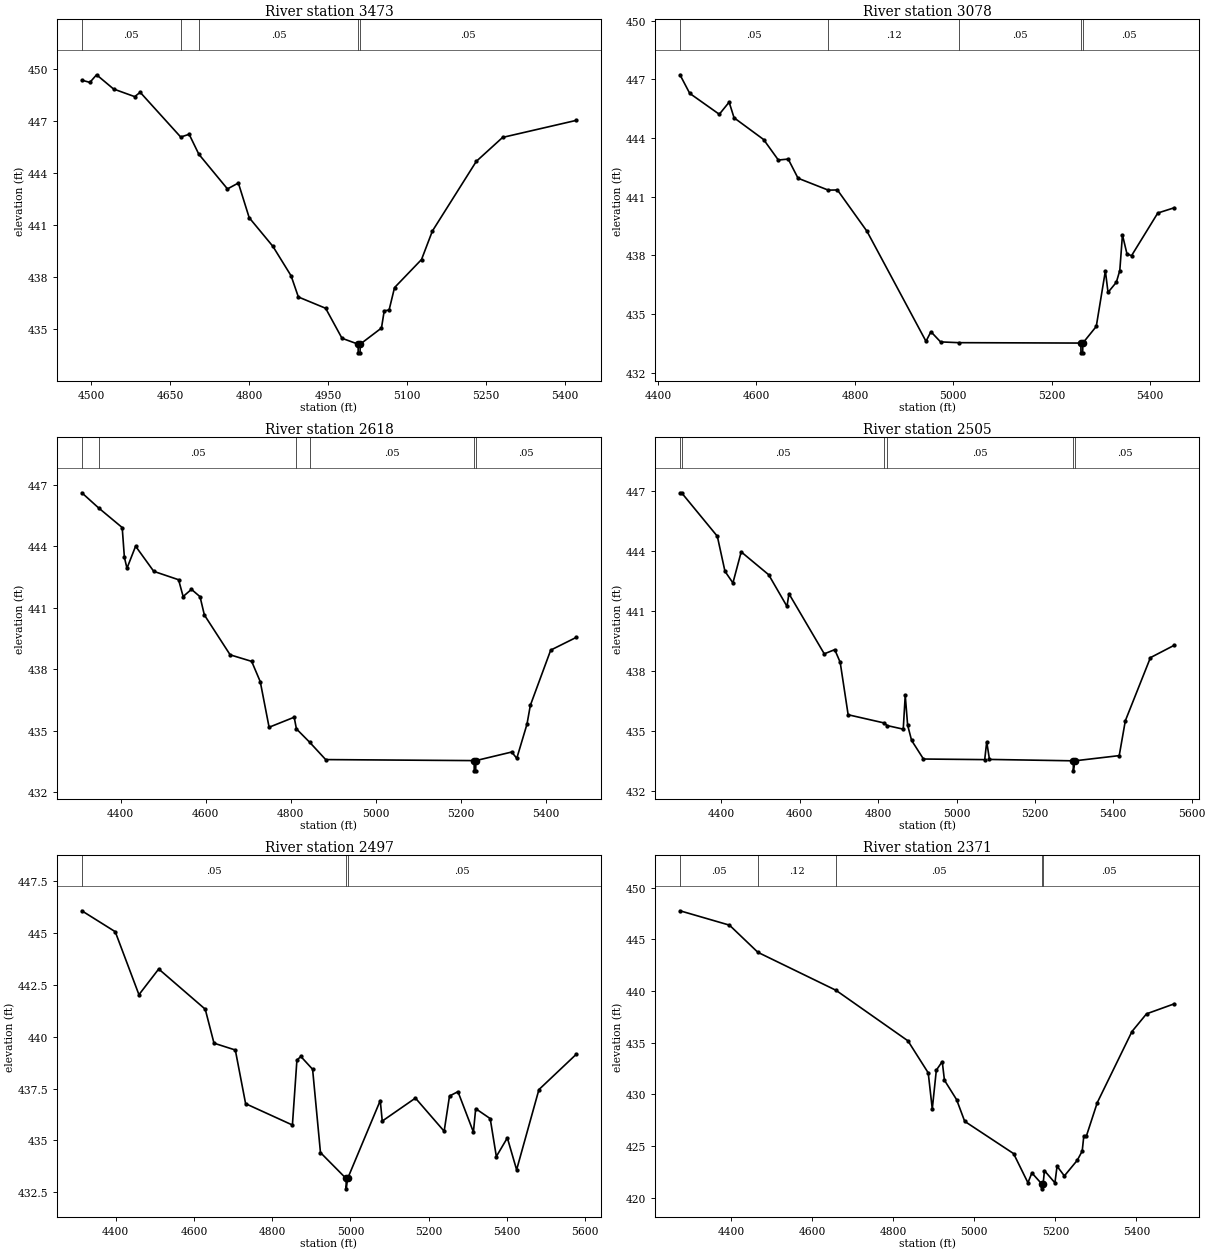
Type RM Length L Ch R = 1,3473,395,395,395
BEGIN DESCRIPTION:
Caney T2_1 7.0
END DESCRIPTION:
XS GIS Cut Line= 3
      2726239.01      6895660.77      2726739.15      6895524.78
      2726835.10      6895114.96
#Sta/Elev= 30
  4481.7  449.33  4497.0  449.20  4509.7  449.64  4542.0  448.82  4582.2  448.38
  4592.6  448.63  4669.6  446.05  4685.6  446.21  4704.0  445.06  4758.4  443.06
  4779.1  443.40  4799.7  441.40  4844.7  439.75  4879.3  438.05  4893.1  436.83
  4944.9  436.18  4976.0  434.45  5006.6  434.11  5006.8  433.61  5010.3  433.61
  5010.6  434.11  5051.0  435.04  5056.2  436.03  5065.5  436.08  5075.8  437.37
  5127.1  438.99  5147.7  440.63  5231.2  444.65  5281.2  446.03  5420.9  447.01
#Mann=5,-1,0
  4481.7    0.05       0  4669.6    0.12       0  4704.0    0.05       0
  5006.6    0.04       0  5010.6    0.05       0
Bank Sta=5006.6,5010.6
Exp/Cntr=0.3,0.1

Type RM Length L Ch R = 1,3078,460,460,460
BEGIN DESCRIPTION:
Mapping XS 4c75f2aa
END DESCRIPTION:
XS GIS Cut Line= 3
      2726356.16      6895814.42      2726890.04      6895804.01
      2727324.90      6895624.33
#Sta/Elev= 30
  4444.6  447.24  4464.4  446.29  4524.5  445.22  4544.5  445.84  4554.5  445.04
  4614.5  443.93  4644.5  442.88  4664.5  442.93  4684.5  441.95  4746.0  441.34
  4764.5  441.35  4824.5  439.24  4944.5  433.61  4954.5  434.10  4974.1  433.58
  5010.8  433.54  5259.2  433.52  5259.4  433.02  5262.9  433.02  5263.2  433.52
  5290.5  434.37  5309.0  437.21  5314.4  436.11  5331.3  436.63  5338.3  437.23
  5343.7  439.05  5352.9  438.08  5362.2  437.99  5415.5  440.17  5449.1  440.44
#Mann=5,-1,0
  4444.6    0.05       0  4746.0    0.12       0  5010.8    0.05       0
  5259.2    0.07       0  5263.2    0.05       0
Bank Sta=5259.2,5263.2
Exp/Cntr=0.3,0.1

Type RM Length L Ch R = 1,2618,113,113,113
BEGIN DESCRIPTION:
Mapping XS bb9ce7f1
END DESCRIPTION:
XS GIS Cut Line= 3
      2726350.94      6896220.68      2727028.06      6896119.11
      2727477.31      6895955.51
#Sta/Elev= 30
  4308.4  446.62  4347.9  445.88  4403.4  444.92  4408.5  443.47  4414.6  442.93
  4434.9  444.01  4477.6  442.78  4536.0  442.37  4546.7  441.55  4566.3  441.90
  4586.5  441.54  4596.6  440.65  4657.3  438.70  4707.9  438.38  4728.1  437.39
  4748.9  435.16  4807.9  435.65  4813.2  435.08  4844.2  434.43  4882.0  433.58
  5231.2  433.53  5231.4  433.03  5234.9  433.03  5235.2  433.53  5319.6  433.95
  5331.5  433.64  5355.5  435.31  5363.4  436.23  5411.3  438.93  5471.2  439.55
#Mann=6,-1,0
  4308.4    0.12       0  4347.9    0.05       0  4813.2    0.12       0
  4844.2    0.05       0  5231.2    0.03       0  5235.2    0.05       0
Bank Sta=5231.2,5235.2
Exp/Cntr=0.3,0.1

Type RM Length L Ch R = 1,2505,8,8,8
BEGIN DESCRIPTION:
Mapping XS deb60ad7
END DESCRIPTION:
XS GIS Cut Line= 6
      2726352.74      6896240.89      2726888.77      6896151.91
      2726984.26      6896164.94      2727027.66      6896204.00
      2727240.33      6896251.74      2727539.82      6896082.47
#Sta/Elev= 30
  4294.4  446.90  4298.5  446.90  4389.7  444.73  4409.2  442.98  4429.5  442.40
  4450.6  443.95  4520.7  442.81  4567.4  441.23  4572.5  441.86  4662.6  438.86
  4689.3  439.07  4703.2  438.44  4723.5  435.82  4815.3  435.41  4823.0  435.28
  4864.1  435.10  4869.2  436.79  4875.3  435.30  4885.4  434.54  4915.7  433.61
  5072.0  433.58  5077.1  434.47  5084.1  433.59  5297.9  433.52  5298.2  433.02
  5301.9  433.52  5415.2  433.78  5430.8  435.52  5494.8  438.67  5555.8  439.29
#Mann=6,-1,0
  4294.4    0.12       0  4298.5    0.05       0  4815.3    0.12       0
  4823.0    0.05       0  5297.9    0.04       0  5301.9    0.05       0
Bank Sta=5297.9,5301.9
Exp/Cntr=0.3,0.1

Type RM Length L Ch R = 1,2497,126,126,126
BEGIN DESCRIPTION:
Mapping XS f19f9b20
END DESCRIPTION:
XS GIS Cut Line= 6
      2726361.38      6896249.58      2726895.28      6896175.79
      2726982.09      6896182.30      2727090.59      6896243.06
      2727257.70      6896269.10      2727551.88      6896093.97
#Sta/Elev= 30
  4313.4  446.08  4398.8  445.07  4459.4  442.03  4509.9  443.27  4628.8  441.33
  4651.2  439.69  4705.7  439.36  4732.0  436.77  4851.6  435.74  4863.1  438.87
  4873.1  439.05  4903.2  438.43  4923.3  434.41  4988.8  433.16  4989.1  432.66
  4992.8  433.16  5076.1  436.92  5081.2  435.93  5166.0  437.04  5239.4  435.44
  5253.1  437.14  5274.7  437.35  5314.2  435.40  5320.0  436.53  5357.1  436.05
  5372.8  434.22  5400.9  435.12  5424.6  433.58  5481.6  437.45  5576.8  439.15
#Mann=3,-1,0
  4313.4    0.05       0  4988.8    0.04       0  4992.8    0.05       0
Bank Sta=4988.8,4992.8
Exp/Cntr=0.3,0.1

Type RM Length L Ch R = 1,2371,414,414,414
BEGIN DESCRIPTION:
Mapping XS ce9bc18c
END DESCRIPTION:
XS GIS Cut Line= 6
      2726393.94      6896329.87      2727040.68      6896305.99
      2727112.30      6896303.82      2727251.18      6896319.02
      2727381.39      6896273.44      2727561.25      6896141.26
#Sta/Elev= 30
  4273.9  447.76  4396.0  446.37  4466.2  443.74  4658.7  440.07  4836.3  435.18
  4886.4  432.08  4896.4  428.59  4906.4  432.34  4921.0  433.17  4926.4  431.37
  4956.4  429.49  4976.4  427.39  5097.0  424.27  5132.4  421.45  5142.2  422.40
  5165.9  421.36  5166.2  420.86  5169.9  421.36  5173.2  422.62  5199.0  421.44
  5204.3  423.05  5222.3  422.11  5254.1  423.62  5266.3  424.51  5270.2  425.94
  5276.4  425.94  5303.5  429.20  5389.1  436.08  5425.0  437.79  5493.6  438.76
#Mann=5,-1,0
  4273.9    0.05       0  4466.2    0.12       0  4658.7    0.05       0
  5165.9    0.04       0  5169.9    0.05       0
Bank Sta=5165.9,5169.9
Exp/Cntr=0.3,0.1

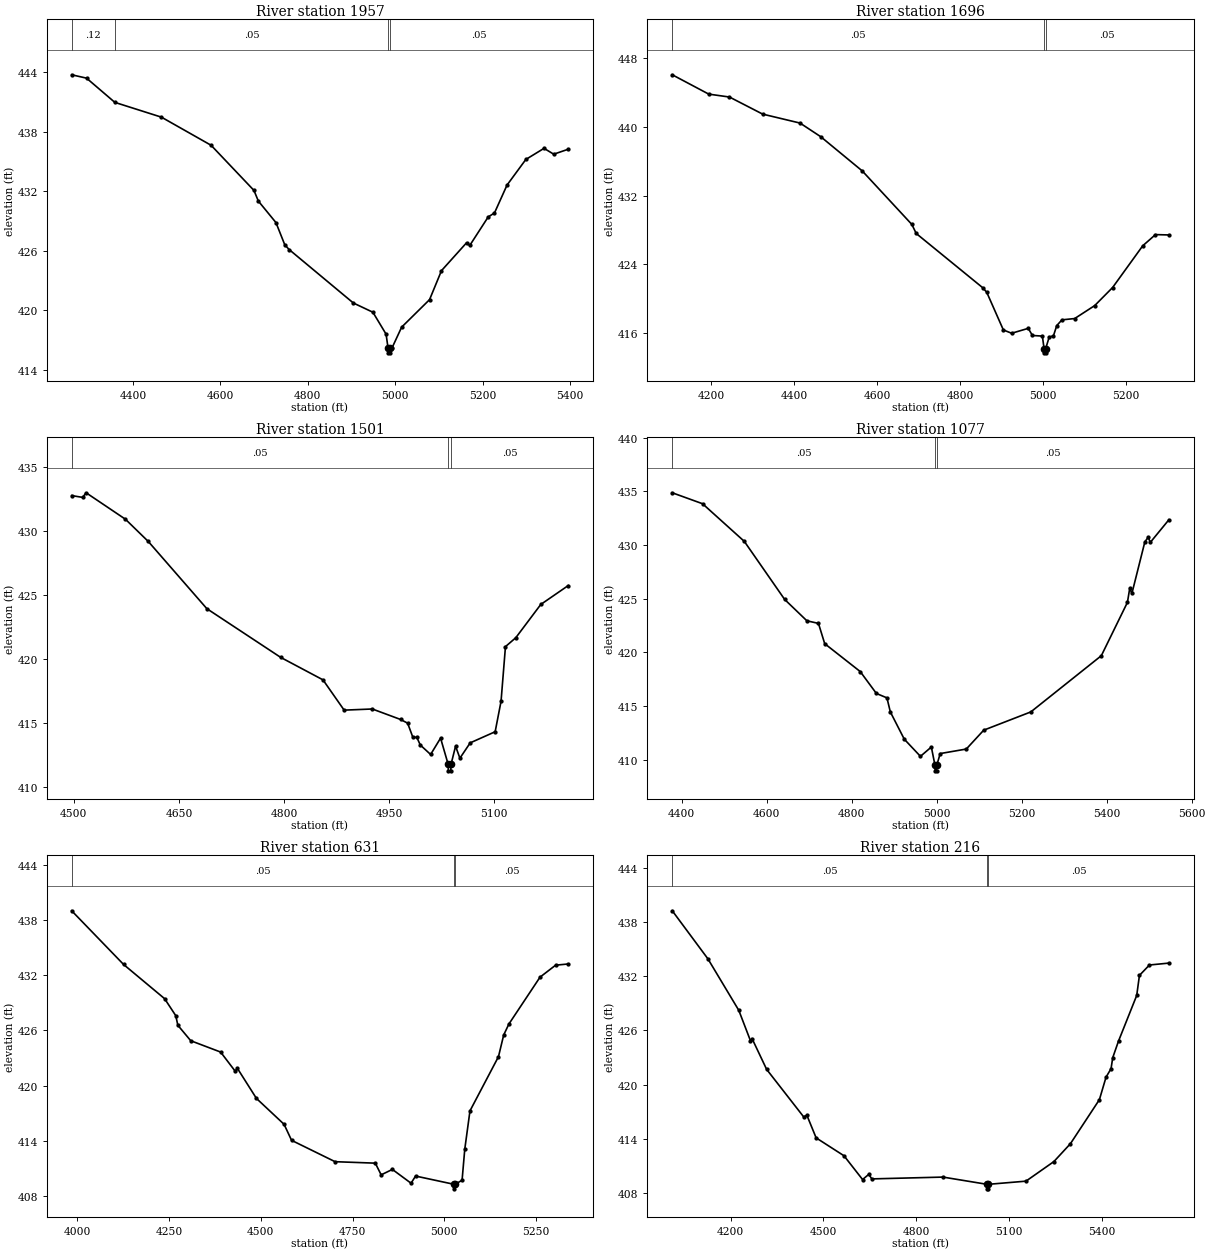
Type RM Length L Ch R = 1,1957,261,261,261
BEGIN DESCRIPTION:
Mapping XS 2336d410
END DESCRIPTION:
XS GIS Cut Line= 3
      2726692.25      6896664.56      2727417.10      6896575.58
      2727729.61      6896317.33
#Sta/Elev= 30
  4260.1  443.73  4294.1  443.39  4358.8  440.95  4465.4  439.46  4578.9  436.63
  4677.0  432.08  4687.0  431.01  4727.3  428.84  4747.5  426.60  4757.6  426.12
  4904.3  420.74  4949.0  419.81  4979.2  417.60  4983.6  416.22  4983.9  415.72
  4987.4  415.72  4987.6  416.22  4992.9  416.23  5014.8  418.31  5078.6  421.08
  5105.9  424.00  5163.3  426.81  5170.6  426.54  5212.7  429.41  5227.1  429.81
  5255.8  432.62  5298.8  435.20  5340.4  436.32  5362.6  435.73  5395.8  436.23
#Mann=4,-1,0
  4260.1    0.12       0  4358.8    0.05       0  4983.6    0.04       0
  4987.6    0.05       0
Bank Sta=4983.6,4987.6
Exp/Cntr=0.3,0.1

Type RM Length L Ch R = 1,1696,195,195,195
BEGIN DESCRIPTION:
Mapping XS 8498ff27
END DESCRIPTION:
XS GIS Cut Line= 3
      2726588.12      6896790.43      2727480.03      6896814.30
      2727777.39      6896747.01
#Sta/Elev= 30
  4105.6  446.07  4193.5  443.82  4243.5  443.48  4323.6  441.49  4413.6  440.45
  4463.6  438.86  4563.6  434.88  4683.2  428.65  4693.7  427.60  4853.7  421.30
  4863.7  420.76  4903.8  416.37  4923.8  415.99  4963.8  416.56  4973.8  415.73
  4997.8  415.66  5001.9  414.21  5002.2  413.71  5005.7  413.71  5005.9  414.21
  5014.2  415.54  5024.5  415.69  5032.5  416.88  5045.0  417.55  5075.7  417.70
  5124.0  419.21  5167.1  421.31  5239.8  426.17  5270.5  427.47  5302.7  427.43
#Mann=3,-1,0
  4105.6    0.05       0  5001.9    0.04       0  5005.9    0.05       0
Bank Sta=5001.9,5005.9
Exp/Cntr=0.3,0.1

Type RM Length L Ch R = 1,1501,424,424,424
BEGIN DESCRIPTION:
Mapping XS bd8bfd61
END DESCRIPTION:
XS GIS Cut Line= 3
      2727119.81      6897018.29      2727605.90      6896961.87
      2727783.87      6896833.82
#Sta/Elev= 30
  4496.9  432.80  4512.5  432.66  4517.5  433.02  4573.6  430.95  4606.2  429.21
  4689.8  423.95  4795.1  420.14  4855.5  418.38  4885.7  416.01  4925.9  416.10
  4966.2  415.28  4976.3  414.99  4983.8  413.88  4989.4  413.88  4994.4  413.28
  5009.1  412.54  5023.3  413.82  5034.2  411.76  5034.4  411.26  5037.9  411.26
  5038.2  411.76  5044.7  413.19  5050.9  412.25  5065.6  413.45  5101.2  414.32
  5109.6  416.70  5115.9  420.98  5130.7  421.68  5166.3  424.28  5205.5  425.76
#Mann=3,-1,0
  4496.9    0.05       0  5034.2    0.04       0  5038.2    0.05       0
Bank Sta=5034.2,5038.2
Exp/Cntr=0.3,0.1

Type RM Length L Ch R = 1,1077,446,446,446
BEGIN DESCRIPTION:
Mapping XS 931a1f17
END DESCRIPTION:
XS GIS Cut Line= 3
      2727223.13      6897486.88      2727817.83      6897304.97
      2728351.02      6897186.00
#Sta/Elev= 30
  4378.1  434.87  4449.3  433.85  4547.6  430.34  4642.5  424.93  4694.8  422.94
  4722.0  422.70  4736.7  420.81  4820.3  418.21  4858.3  416.17  4883.1  415.76
  4891.1  414.45  4923.9  411.91  4961.9  410.31  4987.6  411.18  4996.2  409.46
  4996.5  408.96  5000.0  408.96  5000.2  409.46  5008.4  410.57  5069.8  410.99
  5110.8  412.75  5221.6  414.45  5387.5  419.69  5448.9  424.66  5454.3  425.97
  5459.4  425.49  5489.9  430.30  5497.7  430.72  5502.8  430.25  5546.3  432.35
#Mann=3,-1,0
  4378.1    0.05       0  4996.2    0.04       0  5000.2    0.05       0
Bank Sta=4996.2,5000.2
Exp/Cntr=0.3,0.1

Type RM Length L Ch R = 1,631,415,415,415
BEGIN DESCRIPTION:
Mapping XS c85c2629
END DESCRIPTION:
XS GIS Cut Line= 3
      2727157.12      6897729.95      2728146.70      6897542.45
      2728400.18      6897306.34
#Sta/Elev= 30
  3984.4  438.99  4125.8  433.16  4237.7  429.44  4268.2  427.59  4273.8  426.55
  4309.0  424.87  4390.4  423.64  4430.7  421.53  4435.8  421.89  4488.1  418.60
  4563.4  415.79  4583.8  414.05  4702.4  411.73  4812.1  411.57  4828.0  410.30
  4858.6  410.89  4909.5  409.39  4921.8  410.17  5025.6  409.28  5025.8  408.78
  5029.6  409.28  5048.6  409.71  5055.9  413.08  5070.1  417.25  5147.8  423.14
  5162.0  425.49  5176.1  426.68  5261.1  431.78  5303.6  433.08  5338.0  433.21
#Mann=3,-1,0
  3984.4    0.05       0  5025.6    0.04       0  5029.6    0.05       0
Bank Sta=5025.6,5029.6
Exp/Cntr=0.3,0.1

Type RM Length L Ch R = 1,216,0,0,0
BEGIN DESCRIPTION:
Caney T2_1 1.0
END DESCRIPTION:
XS GIS Cut Line= 3
      2727251.01      6897886.00      2728239.26      6897924.66
      2728471.30      6897352.84
#Sta/Elev= 30
  4011.0  439.23  4126.1  433.92  4226.2  428.21  4264.0  424.84  4269.0  425.09
  4316.2  421.68  4436.3  416.41  4446.3  416.61  4476.3  414.10  4566.4  412.12
  4626.5  409.49  4646.5  410.06  4656.5  409.56  4886.7  409.76  5029.1  408.96
  5029.3  408.46  5032.8  408.46  5033.1  408.96  5155.0  409.31  5245.4  411.48
  5298.9  413.46  5392.5  418.33  5414.0  420.82  5430.2  421.76  5435.6  422.97
  5454.3  424.81  5513.2  429.86  5522.0  432.08  5554.3  433.23  5617.1  433.44
#Mann=3,-1,0
  4011.0    0.05       0  5029.1    0.03       0  5033.1    0.05       0
Bank Sta=5029.1,5033.1
Exp/Cntr=0.3,0.1

Chan Stop Cuts=-1