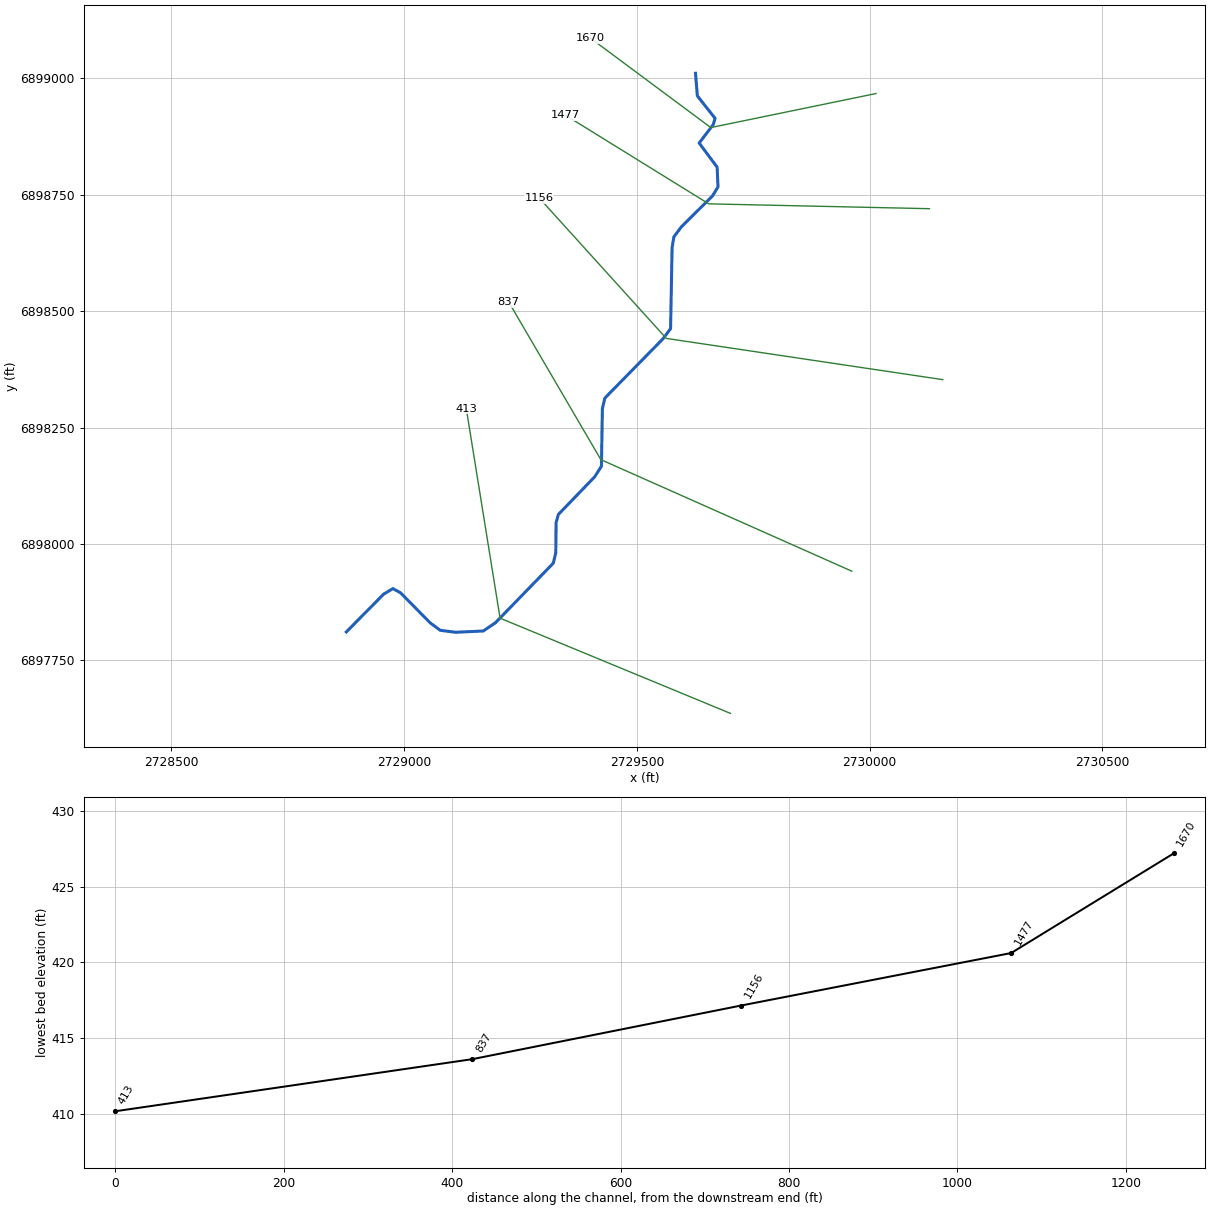
--- Caney T2_2.prj (project) ---

Proj Title=Caney T2_2 Base Level Engineering
Current Plan=p01
Default Exp/Contr=0.3,0.1
English Units
Geom File=g01
Flow File=f01
Plan File=p01
BEGIN DESCRIPTION:
Caney T2_2
END DESCRIPTION:

--- Caney T2_2.p01 (plan) ---

Plan Title=Multiple Run
Short Identifier=Multiple
Geom File=g01
Flow File=f01
Subcritical Flow
K Sum by GR= 0
Std Step Tol= 0.01
Critical Tol= 0.01
Num of Std Step Trials= 20
Max Error Tol= 0.3
Flow Tol Ratio= 0.001
Split Flow NTrial= 30
Split Flow Tol= 0.02
Split Flow Ratio= 0.02
Log Output Level= 0
Friction Slope Method= 1
Unsteady Friction Slope Method= 2
Unsteady Bridges Friction Slope Method= 1
Parabolic Critical Depth
Global Vel Dist=  1 , 1 , 1
Global Log Level= 0
CheckData=True
Encroach Param= -1, 0, 0, 0
BEGIN DESCRIPTION:
Multiple Run
END DESCRIPTION:

--- Caney T2_2.f01 (steady flow) ---

Flow Title=Multiple
Number of Profiles=7
Profile Names=10-year,25-year,50-year,1pct_min,100-year,1pct_plu,500-year
River Rch & RM= Caney T2_2,Reach-1,1670
     150     182     206     116     232     462     292
Boundary for River Rch & Prof#=Caney T2_2,Reach-1,1
Up Type=0
Dn Type=3
Dn Slope=0.005
Boundary for River Rch & Prof#=Caney T2_2,Reach-1,2
Up Type=0
Dn Type=3
Dn Slope=0.005
Boundary for River Rch & Prof#=Caney T2_2,Reach-1,3
Up Type=0
Dn Type=3
Dn Slope=0.005
Boundary for River Rch & Prof#=Caney T2_2,Reach-1,4
Up Type=0
Dn Type=3
Dn Slope=0.005
Boundary for River Rch & Prof#=Caney T2_2,Reach-1,5
Up Type=0
Dn Type=3
Dn Slope=0.005
Boundary for River Rch & Prof#=Caney T2_2,Reach-1,6
Up Type=0
Dn Type=3
Dn Slope=0.005
Boundary for River Rch & Prof#=Caney T2_2,Reach-1,7
Up Type=0
Dn Type=3
Dn Slope=0.005

--- Caney T2_2.g01 (geometry) ---

Geom Title=Existing Conditions

River Reach=Caney T2_2,Reach-1
Reach XY= 30
      2729626.00      6899011.00      2729629.98      6898962.36
      2729668.01      6898914.26      2729664.23      6898900.97
      2729633.80      6898861.09      2729672.44      6898809.35
      2729674.34      6898767.05      2729662.84      6898747.80
      2729595.65      6898681.15      2729579.55      6898659.53
      2729575.71      6898636.12      2729572.46      6898462.46
      2729556.39      6898440.84      2729431.47      6898313.45
      2729425.98      6898291.01      2729423.92      6898166.86
      2729409.53      6898144.25      2729331.54      6898063.42
      2729326.53      6898045.78      2729325.87      6897981.05
      2729320.48      6897958.57      2729196.16      6897830.58
      2729170.11      6897812.96      2729110.92      6897810.22
      2729077.50      6897814.48      2729055.85      6897830.67
      2728992.65      6897894.78      2728975.99      6897904.02
      2728956.00      6897892.00      2728876.00      6897811.00

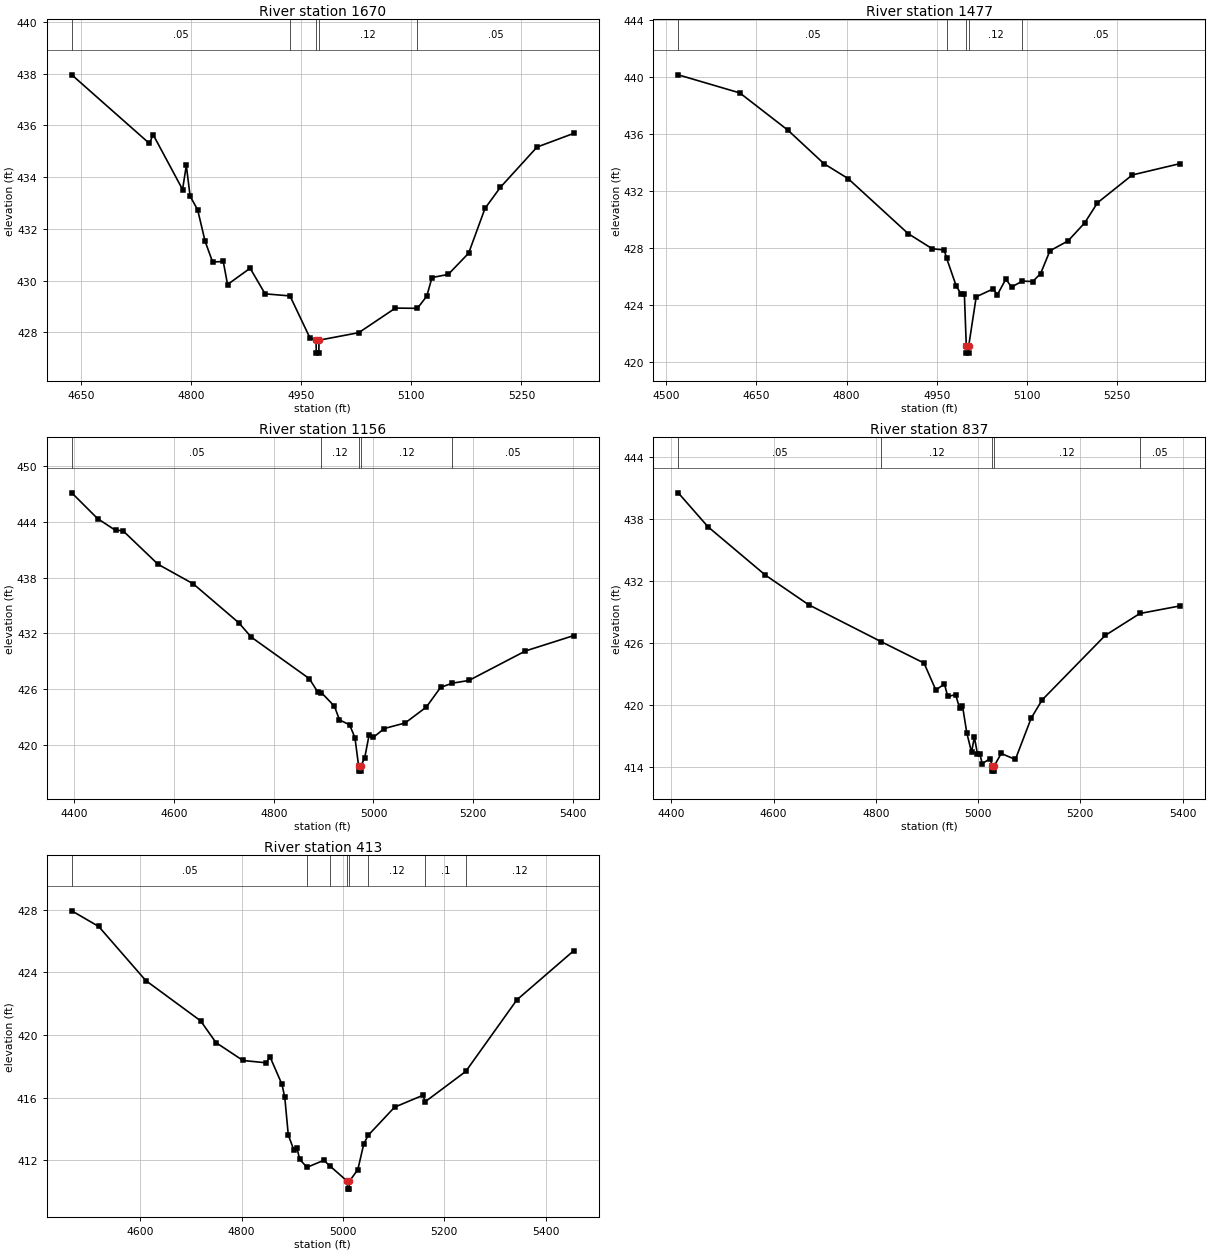
Type RM Length L Ch R = 1,1670,193,193,193
BEGIN DESCRIPTION:
Caney T2_2 3.0
END DESCRIPTION:
XS GIS Cut Line= 3
      2730013.86      6898967.47      2729658.82      6898894.32
      2729400.97      6899086.02
#Sta/Elev= 30
  4637.5  437.95  4743.2  435.30  4748.3  435.64  4788.4  433.52  4793.5  434.45
  4798.7  433.26  4808.9  432.74  4819.1  431.52  4829.3  430.72  4843.8  430.74
  4849.7  429.85  4880.4  430.48  4900.8  429.49  4934.7  429.41  4962.0  427.78
  4970.2  427.70  4970.5  427.20  4974.0  427.20  4974.2  427.70  5028.4  427.99
  5078.3  428.94  5108.2  428.93  5121.0  429.40  5128.1  430.12  5150.2  430.24
  5178.0  431.06  5200.3  432.79  5221.1  433.60  5271.2  435.16  5321.3  435.69
#Mann=5,-1,0
  4637.5    0.05       0  4934.7    0.12       0  4970.2    0.07       0
  4974.2    0.12       0  5108.2    0.05       0
Bank Sta=4970.2,4974.2
Exp/Cntr=0.3,0.1

Type RM Length L Ch R = 1,1477,321,321,321
BEGIN DESCRIPTION:
Mapping XS c0756023
END DESCRIPTION:
XS GIS Cut Line= 3
      2730128.43      6898720.08      2729654.50      6898730.49
      2729347.19      6898920.61
#Sta/Elev= 30
  4519.9  440.13  4622.4  438.86  4702.4  436.25  4762.4  433.90  4802.4  432.86
  4902.4  429.00  4942.4  427.94  4962.4  427.85  4966.5  427.27  4982.4  425.33
  4990.7  424.75  4996.0  424.75  4999.2  421.12  4999.5  420.62  5003.0  420.62
  5003.2  421.12  5015.7  424.57  5043.8  425.12  5051.0  424.72  5065.0  425.81
  5074.5  425.25  5092.4  425.67  5109.8  425.64  5122.9  426.20  5138.3  427.79
  5168.6  428.49  5196.2  429.75  5217.5  431.16  5275.4  433.11  5355.3  433.91
#Mann=5,-1,0
  4519.9    0.05       0  4966.5    0.12       0  4999.2    0.07       0
  5003.2    0.12       0  5092.4    0.05       0
Bank Sta=4999.2,5003.2
Exp/Cntr=0.3,0.1

Type RM Length L Ch R = 1,1156,319,319,319
BEGIN DESCRIPTION:
Mapping XS 9a0736db
END DESCRIPTION:
XS GIS Cut Line= 3
      2730157.07      6898352.89      2729563.35      6898441.43
      2729290.48      6898742.89
#Sta/Elev= 30
  4395.0  447.14  4446.6  444.37  4482.9  443.09  4497.2  443.08  4568.0  439.44
  4638.7  437.33  4729.7  433.15  4755.0  431.59  4871.3  427.12  4888.6  425.65
  4895.6  425.61  4921.8  424.14  4931.9  422.67  4952.2  422.14  4962.9  420.75
  4970.4  417.65  4970.6  417.15  4974.1  417.15  4974.4  417.65  4982.5  418.59
  4991.4  421.08  5000.1  420.80  5021.7  421.74  5063.6  422.34  5106.2  424.06
  5134.6  426.17  5158.4  426.63  5191.4  426.92  5304.9  430.10  5401.9  431.76
#Mann=5,-1,0
  4395.0    0.05       0  4895.6    0.12       0  4970.4    0.07       0
  4974.4    0.12       0  5158.4    0.05       0
Bank Sta=4970.4,4974.4
Exp/Cntr=0.3,0.1

Type RM Length L Ch R = 1,837,424,424,424
BEGIN DESCRIPTION:
Mapping XS 86b8088e
END DESCRIPTION:
XS GIS Cut Line= 3
      2729961.76      6897941.45      2729422.73      6898181.01
      2729224.82      6898519.54
#Sta/Elev= 30
  4413.6  440.57  4471.6  437.29  4584.0  432.60  4668.6  429.73  4810.9  426.14
  4894.3  424.08  4917.5  421.46  4934.2  422.06  4940.8  420.84  4956.1  421.02
  4964.0  419.70  4969.5  419.96  4978.0  417.31  4987.3  415.44  4992.8  416.91
  4998.9  415.27  5003.5  415.27  5008.1  414.34  5023.8  414.82  5027.6  414.11
  5027.8  413.61  5031.3  413.61  5031.6  414.11  5045.3  415.32  5073.0  414.74
  5103.9  418.74  5125.4  420.51  5248.6  426.75  5316.5  428.88  5395.6  429.62
#Mann=5,-1,0
  4413.6    0.05       0  4810.9    0.12       0  5027.6    0.07       0
  5031.6    0.12       0  5316.5    0.05       0
Bank Sta=5027.6,5031.6
Exp/Cntr=0.3,0.1

Type RM Length L Ch R = 1,413,0,0,0
BEGIN DESCRIPTION:
Caney T2_2 1.0
END DESCRIPTION:
XS GIS Cut Line= 3
      2729701.01      6897636.00      2729206.20      6897840.49
      2729133.67      6898290.38
#Sta/Elev= 30
  4464.6  427.93  4517.8  426.93  4610.7  423.48  4718.9  420.91  4749.3  419.52
  4802.5  418.38  4848.7  418.23  4855.7  418.63  4879.6  416.85  4885.1  416.02
  4892.0  413.63  4902.8  412.68  4909.0  412.82  4914.4  412.08  4928.8  411.56
  4962.2  412.01  4974.5  411.64  5008.6  410.67  5008.9  410.17  5012.4  410.17
  5012.6  410.67  5029.3  411.42  5041.0  413.05  5049.6  413.60  5101.8  415.40
  5157.9  416.16  5162.4  415.75  5242.3  417.68  5343.3  422.25  5455.7  425.39
#Mann=8,-1,0
  4464.6    0.05       0  4928.8    0.12       0  4974.5     0.1       0
  5008.6    0.07       0  5012.6     0.1       0  5049.6    0.12       0
  5162.4     0.1       0  5242.3    0.12       0
Bank Sta=5008.6,5012.6
Exp/Cntr=0.3,0.1

Chan Stop Cuts=-1