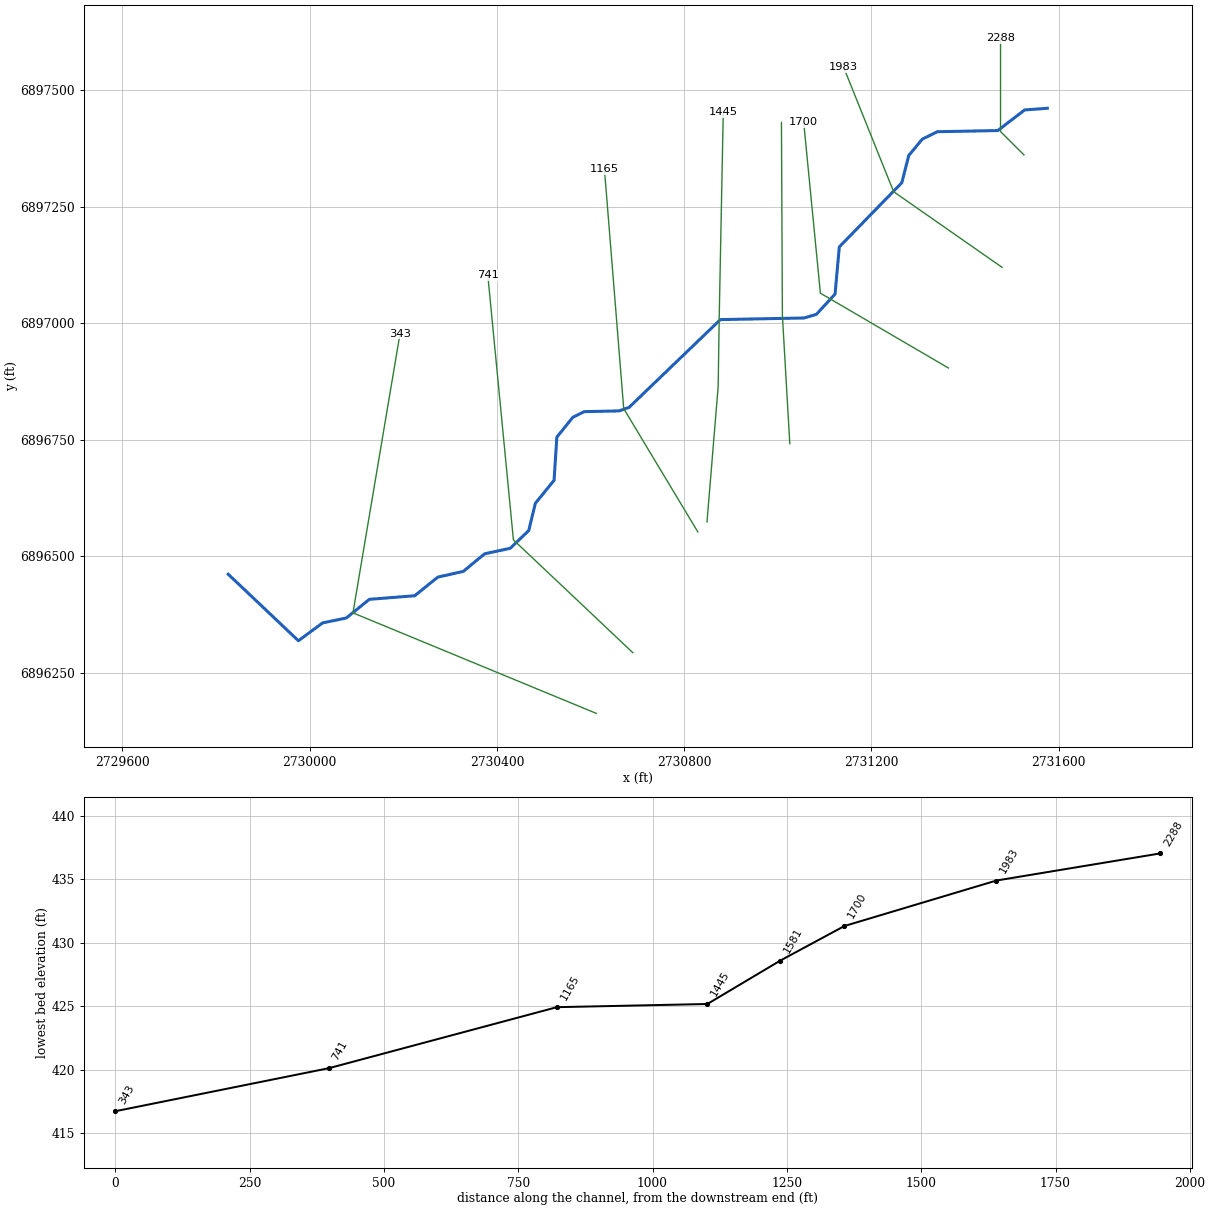
--- Caney T2_3.prj (project) ---

Proj Title=Caney T2_3 Base Level Engineering
Current Plan=p01
Default Exp/Contr=0.3,0.1
English Units
Geom File=g01
Flow File=f01
Plan File=p01
BEGIN DESCRIPTION:
Caney T2_3
END DESCRIPTION:

--- Caney T2_3.p01 (plan) ---

Plan Title=Multiple Run
Short Identifier=Multiple
Geom File=g01
Flow File=f01
Subcritical Flow
K Sum by GR= 0
Std Step Tol= 0.01
Critical Tol= 0.01
Num of Std Step Trials= 20
Max Error Tol= 0.3
Flow Tol Ratio= 0.001
Split Flow NTrial= 30
Split Flow Tol= 0.02
Split Flow Ratio= 0.02
Log Output Level= 0
Friction Slope Method= 1
Unsteady Friction Slope Method= 2
Unsteady Bridges Friction Slope Method= 1
Parabolic Critical Depth
Global Vel Dist=  1 , 1 , 1
Global Log Level= 0
CheckData=True
Encroach Param= -1, 0, 0, 0
BEGIN DESCRIPTION:
Multiple Run
END DESCRIPTION:

--- Caney T2_3.f01 (steady flow) ---

Flow Title=Multiple
Number of Profiles=7
Profile Names=10-year,25-year,50-year,1pct_min,100-year,1pct_plu,500-year
River Rch & RM= Caney T2_3,Reach-1,2288
     264     336     391     228     454     906     609
Boundary for River Rch & Prof#=Caney T2_3,Reach-1,1
Up Type=0
Dn Type=3
Dn Slope=0.005
Boundary for River Rch & Prof#=Caney T2_3,Reach-1,2
Up Type=0
Dn Type=3
Dn Slope=0.005
Boundary for River Rch & Prof#=Caney T2_3,Reach-1,3
Up Type=0
Dn Type=3
Dn Slope=0.005
Boundary for River Rch & Prof#=Caney T2_3,Reach-1,4
Up Type=0
Dn Type=3
Dn Slope=0.005
Boundary for River Rch & Prof#=Caney T2_3,Reach-1,5
Up Type=0
Dn Type=3
Dn Slope=0.005
Boundary for River Rch & Prof#=Caney T2_3,Reach-1,6
Up Type=0
Dn Type=3
Dn Slope=0.005
Boundary for River Rch & Prof#=Caney T2_3,Reach-1,7
Up Type=0
Dn Type=3
Dn Slope=0.005

--- Caney T2_3.g01 (geometry) ---

Geom Title=Existing Conditions

River Reach=Caney T2_3,Reach-1
Reach XY= 30
      2731576.00      6897461.00      2731527.51      6897457.35
      2731470.11      6897413.14      2731341.04      6897410.66
      2731308.86      6897394.72      2731279.87      6897359.60
      2731265.21      6897301.34      2731131.53      6897163.42
      2731122.49      6897062.25      2731082.52      6897018.68
      2731056.13      6897010.91      2730877.46      6897007.46
      2730682.17      6896818.86      2730660.78      6896811.53
      2730586.31      6896809.90      2730562.28      6896797.77
      2730528.07      6896755.31      2730522.17      6896662.59
      2730482.15      6896613.15      2730467.98      6896554.66
      2730428.55      6896516.73      2730373.84      6896504.89
      2730328.20      6896467.08      2730273.82      6896454.88
      2730224.42      6896414.83      2730127.58      6896407.17
      2730078.17      6896367.09      2730027.63      6896356.57
      2729975.91      6896318.28      2729826.00      6896461.00

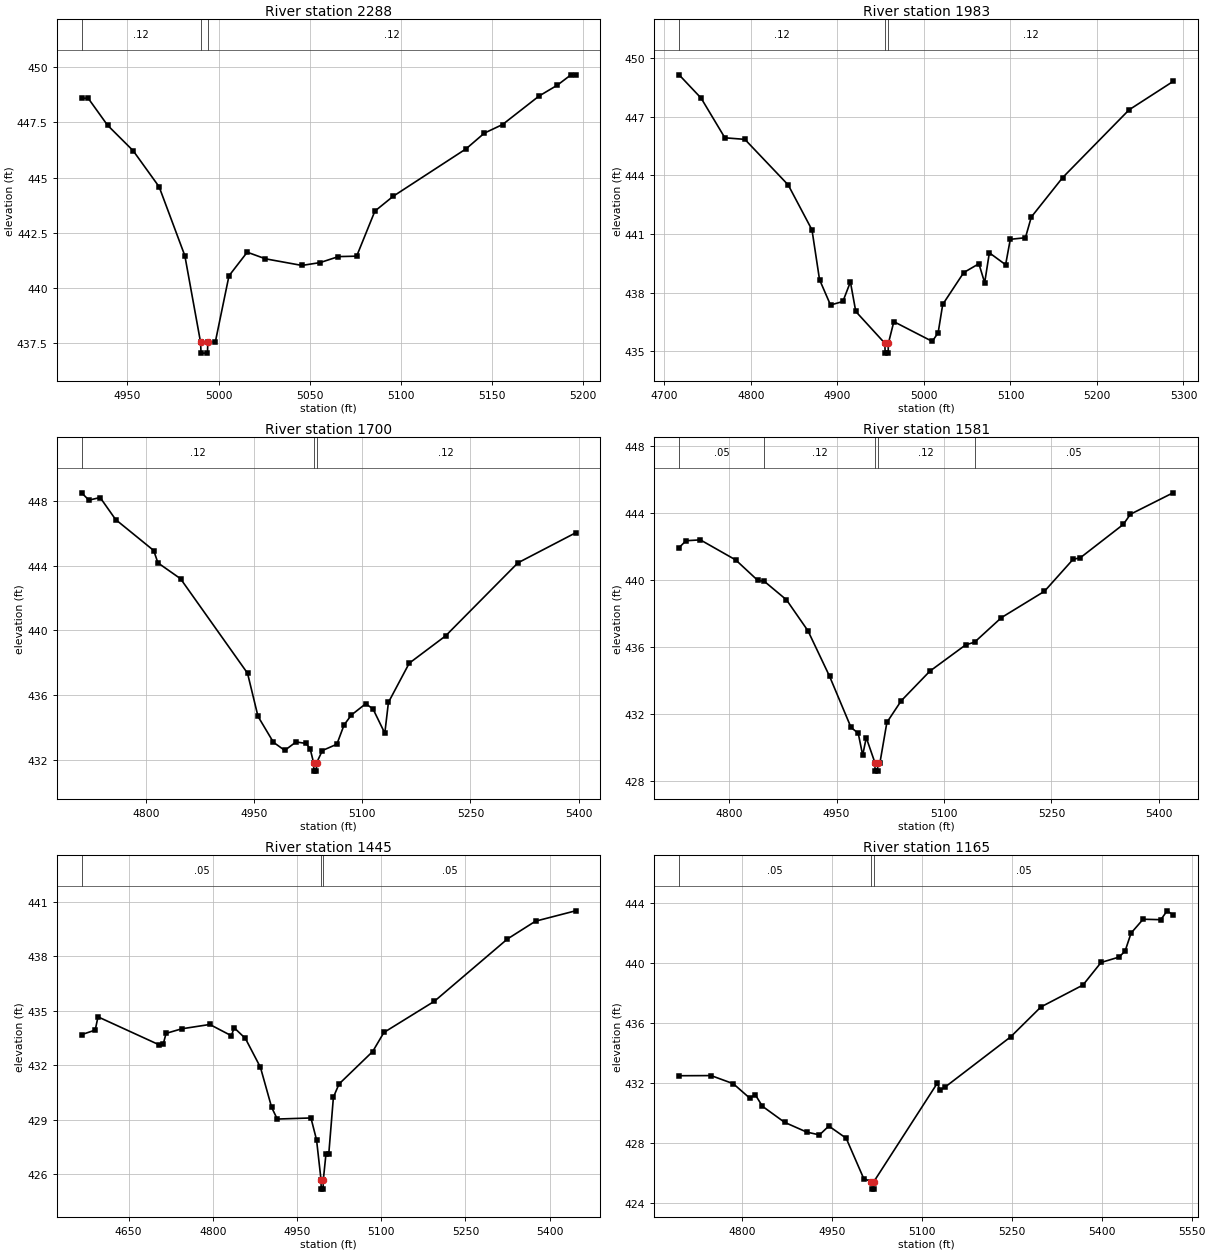
Type RM Length L Ch R = 1,2288,305,305,305
BEGIN DESCRIPTION:
Caney T2_3 5.0
END DESCRIPTION:
XS GIS Cut Line= 3
      2731526.03      6897360.97      2731476.00      6897411.00
      2731476.00      6897611.05
#Sta/Elev= 27
  4924.9  448.59  4928.5  448.59  4939.1  447.37  4953.2  446.21  4967.4  444.58
  4981.5  441.46  4990.1  437.55  4990.4  437.05  4993.9  437.05  4994.1  437.55
  4998.2  437.55  5005.7  440.55  5015.7  441.62  5025.7  441.32  5045.7  441.02
  5055.7  441.15  5065.7  441.42  5075.7  441.44  5085.7  443.48  5095.7  444.15
  5135.7  446.30  5145.7  447.01  5155.7  447.40  5175.7  448.69  5185.7  449.18
  5193.2  449.65  5195.7  449.65
#Mann=3,-1,0
  4924.9    0.12       0  4990.1    0.07       0  4994.1    0.12       0
Bank Sta=4990.1,4994.1
Exp/Cntr=0.3,0.1

Type RM Length L Ch R = 1,1983,283,283,283
BEGIN DESCRIPTION:
Mapping XS 771ba6af
END DESCRIPTION:
XS GIS Cut Line= 3
      2731479.28      6897119.60      2731247.60      6897281.97
      2731140.65      6897549.36
#Sta/Elev= 30
  4717.0  449.14  4742.4  447.95  4769.9  445.92  4793.0  445.84  4843.1  443.51
  4870.6  441.21  4879.3  438.67  4892.0  437.37  4906.3  437.55  4915.0  438.55
  4921.2  437.04  4954.9  435.41  4955.1  434.91  4958.6  434.91  4958.9  435.41
  4965.2  436.52  5009.6  435.51  5016.4  435.95  5021.7  437.40  5046.0  439.03
  5063.5  439.48  5070.2  438.51  5075.6  440.04  5094.4  439.43  5099.8  440.73
  5117.3  440.81  5124.1  441.87  5160.4  443.89  5237.1  447.35  5287.9  448.80
#Mann=3,-1,0
  4717.0    0.12       0  4954.9    0.07       0  4958.9    0.12       0
Bank Sta=4954.9,4958.9
Exp/Cntr=0.3,0.1

Type RM Length L Ch R = 1,1700,119,119,119
BEGIN DESCRIPTION:
Mapping XS a75da902
END DESCRIPTION:
XS GIS Cut Line= 3
      2731364.45      6896903.70      2731091.15      6897064.12
      2731055.50      6897430.49
#Sta/Elev= 30
  4710.8  448.49  4720.9  448.04  4736.5  448.20  4758.0  446.84  4810.8  444.93
  4816.6  444.17  4848.0  443.19  4940.9  437.36  4955.4  434.70  4976.8  433.10
  4992.5  432.60  5008.2  433.12  5022.0  433.03  5027.7  432.71  5032.6  431.82
  5032.9  431.32  5036.4  431.32  5036.6  431.82  5044.7  432.59  5064.8  432.98
  5074.8  434.17  5084.9  434.78  5104.9  435.48  5115.0  435.15  5131.3  433.66
  5136.3  435.56  5165.2  437.98  5215.5  439.66  5315.9  444.17  5395.8  446.02
#Mann=3,-1,0
  4710.8    0.12       0  5032.6    0.07       0  5036.6    0.12       0
Bank Sta=5032.6,5036.6
Exp/Cntr=0.3,0.1

Type RM Length L Ch R = 1,1581,136,136,136
BEGIN DESCRIPTION:
Mapping XS a76c22b3
END DESCRIPTION:
XS GIS Cut Line= 3
      2731025.79      6896741.35      2731009.95      6897016.59
      2731007.97      6897430.49
#Sta/Elev= 30
  4730.2  441.95  4739.9  442.36  4759.9  442.41  4809.3  441.21  4840.0  439.99
  4849.0  439.94  4880.1  438.83  4910.1  436.98  4940.2  434.27  4970.2  431.21
  4980.3  430.86  4986.5  429.55  4991.5  430.60  5003.6  429.10  5003.8  428.60
  5007.3  428.60  5007.6  429.10  5010.6  429.10  5020.3  431.51  5040.3  432.80
  5080.3  434.57  5130.3  436.14  5142.7  436.30  5180.3  437.77  5240.3  439.34
  5280.3  441.25  5290.3  441.34  5350.3  443.33  5360.3  443.94  5419.8  445.22
#Mann=5,-1,0
  4730.2    0.05       0  4849.0    0.12       0  5003.6    0.07       0
  5007.6    0.12       0  5142.7    0.05       0
Bank Sta=5003.6,5007.6
Exp/Cntr=0.3,0.1

Type RM Length L Ch R = 1,1445,280,280,280
BEGIN DESCRIPTION:
Mapping XS 21a8b14a
END DESCRIPTION:
XS GIS Cut Line= 4
      2730848.90      6896573.39      2730872.77      6896864.22
      2730874.94      6897009.62      2730883.62      6897452.31
#Sta/Elev= 30
  4566.2  433.68  4590.4  433.93  4595.4  434.66  4704.3  433.12  4711.7  433.17
  4716.7  433.75  4744.4  434.00  4794.6  434.24  4833.0  433.62  4838.0  434.06
  4858.0  433.47  4884.8  431.88  4904.8  429.67  4914.8  429.03  4974.8  429.09
  4984.8  427.88  4992.8  425.67  4993.0  425.17  4996.5  425.17  4996.8  425.67
  5001.6  427.12  5006.6  427.12  5014.8  430.23  5024.8  430.96  5084.8  432.75
  5104.8  433.80  5194.8  435.52  5324.9  438.95  5374.9  439.93  5446.2  440.50
#Mann=3,-1,0
  4566.2    0.05       0  4992.8    0.05       0  4996.8    0.05       0
Bank Sta=4992.8,4996.8
Exp/Cntr=0.3,0.1

Type RM Length L Ch R = 1,1165,424,424,424
BEGIN DESCRIPTION:
Mapping XS e292adbb
END DESCRIPTION:
XS GIS Cut Line= 3
      2730829.38      6896551.70      2730670.95      6896816.48
      2730629.72      6897330.77
#Sta/Elev= 30
  4694.4  432.47  4747.8  432.48  4784.8  431.94  4812.0  430.99  4821.8  431.19
  4833.4  430.44  4870.4  429.37  4907.3  428.72  4928.7  428.53  4944.3  429.12
  4973.3  428.31  5002.6  425.62  5015.5  425.42  5015.8  424.92  5019.3  424.92
  5019.5  425.42  5125.2  431.96  5130.2  431.52  5137.9  431.70  5247.9  435.06
  5298.4  437.05  5368.6  438.51  5398.7  440.01  5428.8  440.37  5438.9  440.77
  5448.9  441.97  5469.0  442.89  5498.5  442.86  5509.1  443.45  5518.9  443.18
#Mann=3,-1,0
  4694.4    0.05       0  5015.5    0.04       0  5019.5    0.05       0
Bank Sta=5015.5,5019.5
Exp/Cntr=0.3,0.1

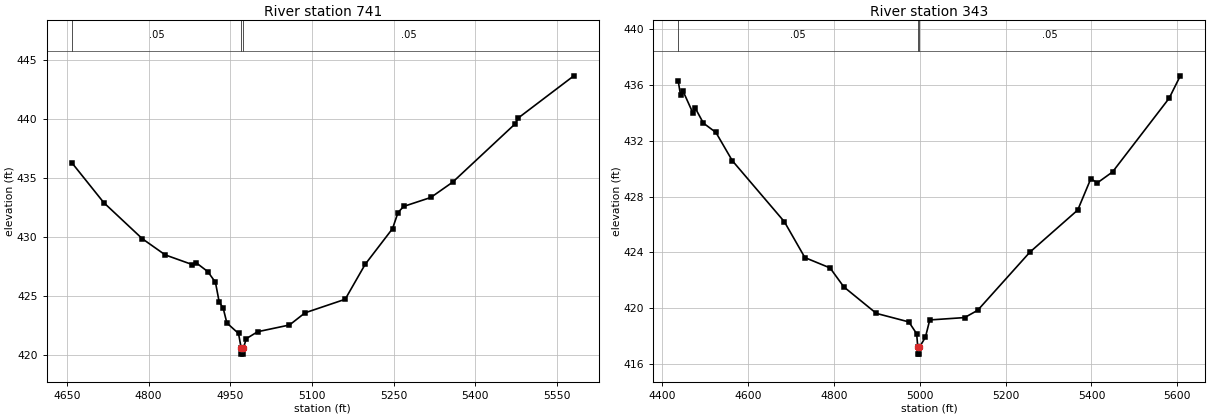
Type RM Length L Ch R = 1,741,398,398,398
BEGIN DESCRIPTION:
Mapping XS eeaf2675
END DESCRIPTION:
XS GIS Cut Line= 3
      2730690.51      6896292.58      2730435.27      6896534.79
      2730380.59      6897102.49
#Sta/Elev= 30
  4658.8  436.34  4717.6  432.95  4788.4  429.89  4830.5  428.52  4880.2  427.70
  4887.1  427.86  4908.5  427.11  4922.7  426.20  4929.6  424.52  4936.8  424.03
  4943.7  422.75  4965.1  421.86  4970.0  420.61  4970.3  420.11  4973.8  420.11
  4974.0  420.61  4979.3  421.42  5000.3  422.01  5058.7  422.58  5087.2  423.61
  5161.0  424.76  5197.7  427.72  5248.0  430.75  5258.0  432.11  5268.4  432.63
  5318.3  433.39  5358.5  434.69  5473.2  439.63  5479.0  440.13  5581.0  443.70
#Mann=3,-1,0
  4658.8    0.05       0  4970.0    0.04       0  4974.0    0.05       0
Bank Sta=4970,4974
Exp/Cntr=0.3,0.1

Type RM Length L Ch R = 1,343,0,0,0
BEGIN DESCRIPTION:
Caney T2_3 1.0
END DESCRIPTION:
XS GIS Cut Line= 3
      2730612.32      6896162.41      2730092.48      6896378.08
      2730192.95      6896976.71
#Sta/Elev= 30
  4437.2  436.28  4442.6  435.27  4448.0  435.59  4471.9  433.96  4477.3  434.32
  4495.8  433.27  4525.0  432.60  4563.1  430.58  4684.5  426.20  4732.3  423.63
  4790.9  422.89  4823.0  421.53  4898.8  419.63  4974.5  419.02  4992.7  418.17
  4995.3  417.21  4995.5  416.71  4999.0  416.71  4999.3  417.21  5013.1  417.92
  5023.2  419.16  5104.4  419.33  5134.8  419.85  5256.5  424.02  5368.0  427.04
  5398.4  429.28  5413.8  428.99  5449.1  429.77  5580.9  435.05  5607.0  436.66
#Mann=3,-1,0
  4437.2    0.05       0  4995.3    0.04       0  4999.3    0.05       0
Bank Sta=4995.3,4999.3
Exp/Cntr=0.3,0.1

Chan Stop Cuts=-1