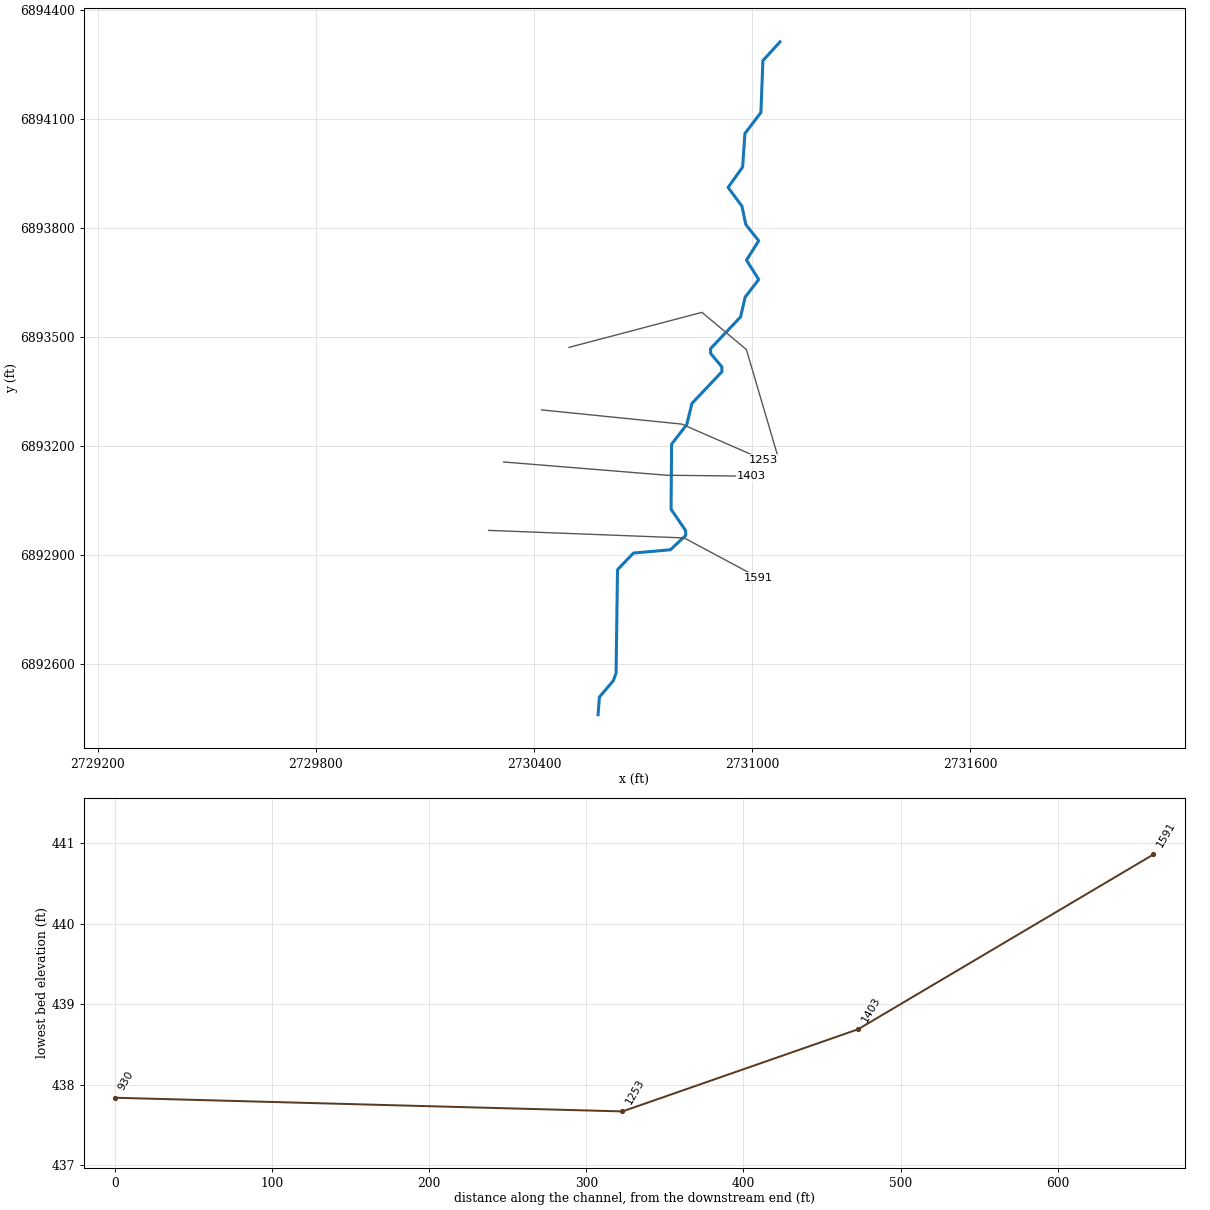
--- Caney T2_4.prj (project) ---

Proj Title=Caney T2_4 Base Level Engineering
Current Plan=p01
Default Exp/Contr=0.3,0.1
English Units
Geom File=g01
Flow File=f01
Plan File=p01
BEGIN DESCRIPTION:
Caney T2_4
END DESCRIPTION:

--- Caney T2_4.p01 (plan) ---

Plan Title=Multiple Run
Short Identifier=Multiple
Geom File=g01
Flow File=f01
Subcritical Flow
K Sum by GR= 0
Std Step Tol= 0.01
Critical Tol= 0.01
Num of Std Step Trials= 20
Max Error Tol= 0.3
Flow Tol Ratio= 0.001
Split Flow NTrial= 30
Split Flow Tol= 0.02
Split Flow Ratio= 0.02
Log Output Level= 0
Friction Slope Method= 1
Unsteady Friction Slope Method= 2
Unsteady Bridges Friction Slope Method= 1
Parabolic Critical Depth
Global Vel Dist=  1 , 1 , 1
Global Log Level= 0
CheckData=True
Encroach Param= -1, 0, 0, 0
BEGIN DESCRIPTION:
Multiple Run
END DESCRIPTION:

--- Caney T2_4.f01 (steady flow) ---

Flow Title=Multiple
Number of Profiles=7
Profile Names=10-year,25-year,50-year,1pct_min,100-year,1pct_plu,500-year
River Rch & RM= Caney T2_4,Reach-1,1591
     265     336     390     226     450     898     597
Boundary for River Rch & Prof#=Caney T2_4,Reach-1,1
Up Type=0
Dn Type=3
Dn Slope=0.005
Boundary for River Rch & Prof#=Caney T2_4,Reach-1,2
Up Type=0
Dn Type=3
Dn Slope=0.005
Boundary for River Rch & Prof#=Caney T2_4,Reach-1,3
Up Type=0
Dn Type=3
Dn Slope=0.005
Boundary for River Rch & Prof#=Caney T2_4,Reach-1,4
Up Type=0
Dn Type=3
Dn Slope=0.005
Boundary for River Rch & Prof#=Caney T2_4,Reach-1,5
Up Type=0
Dn Type=3
Dn Slope=0.005
Boundary for River Rch & Prof#=Caney T2_4,Reach-1,6
Up Type=0
Dn Type=3
Dn Slope=0.005
Boundary for River Rch & Prof#=Caney T2_4,Reach-1,7
Up Type=0
Dn Type=3
Dn Slope=0.005

--- Caney T2_4.g01 (geometry) ---

Geom Title=Existing Conditions

River Reach=Caney T2_4,Reach-1
Reach XY= 30
      2730576.00      6892461.00      2730579.65      6892509.49
      2730618.11      6892554.84      2730625.55      6892576.19
      2730629.44      6892859.78      2730673.29      6892905.59
      2730774.98      6892914.61      2730817.01      6892953.93
      2730816.79      6892967.36      2730776.66      6893026.15
      2730778.24      6893205.07      2730819.86      6893258.83
      2730834.18      6893317.06      2730916.68      6893404.34
      2730916.38      6893417.67      2730885.62      6893454.33
      2730885.32      6893467.66      2730967.84      6893554.95
      2730980.44      6893609.35      2731017.77      6893657.77
      2730984.03      6893711.00      2731017.77      6893764.23
      2730982.35      6893808.71      2730971.61      6893859.35
      2730933.53      6893910.99      2730973.45      6893966.89
      2730979.85      6894059.40      2731023.73      6894116.94
      2731029.30      6894259.63      2731076.00      6894311.00

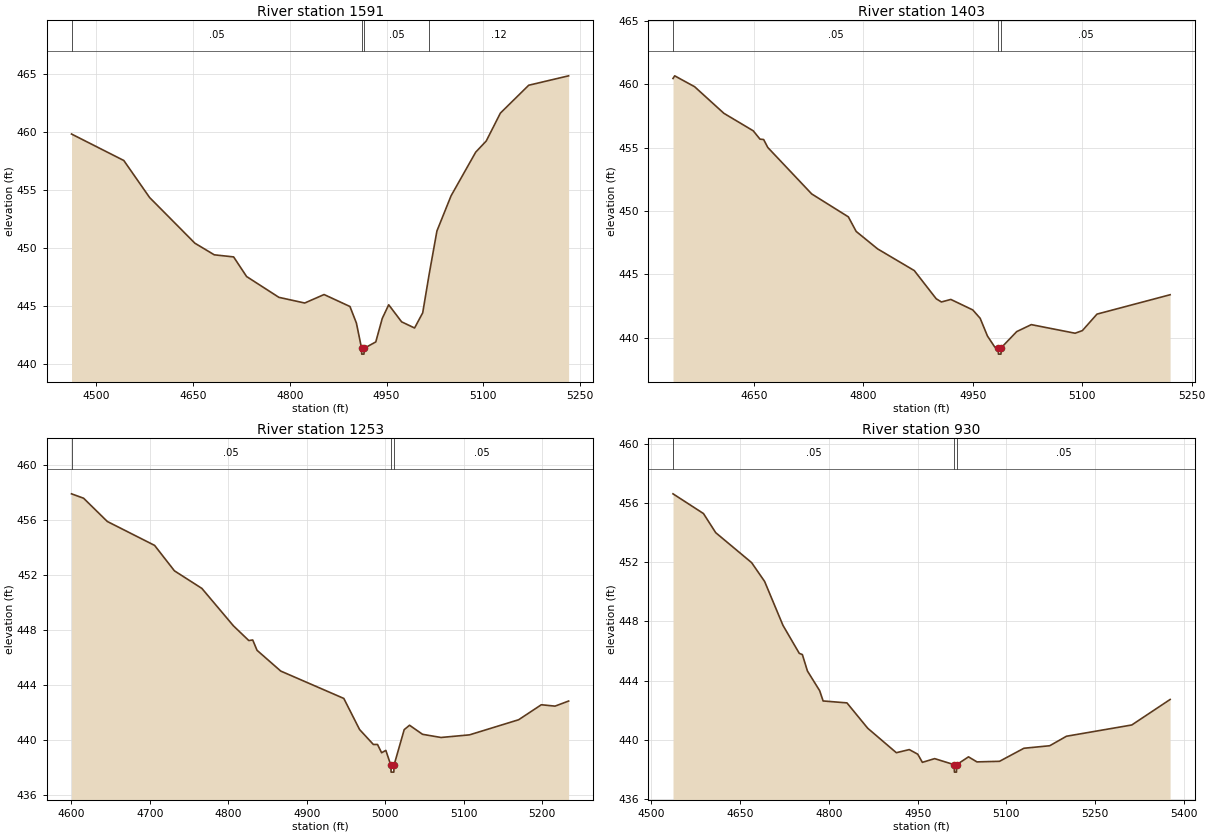
Type RM Length L Ch R = 1,1591,188,188,188
BEGIN DESCRIPTION:
Caney T2_4 2.0
END DESCRIPTION:
XS GIS Cut Line= 3
      2730275.04      6892967.93      2730812.64      6892947.20
      2731017.20      6892837.74
#Sta/Elev= 30
  4462.0  459.81  4543.0  457.53  4583.0  454.34  4653.1  450.41  4683.1  449.41
  4713.1  449.23  4733.2  447.54  4783.2  445.75  4823.2  445.26  4853.2  445.99
  4893.3  444.96  4903.3  443.53  4911.3  441.36  4911.5  440.86  4915.0  440.86
  4915.3  441.36  4933.3  441.91  4943.3  443.93  4953.3  445.11  4973.3  443.64
  4993.4  443.11  5006.0  444.42  5015.7  447.65  5028.0  451.46  5049.9  454.49
  5088.1  458.25  5104.4  459.21  5126.3  461.61  5170.2  464.01  5232.0  464.82
#Mann=4,-1,0
  4462.0    0.05       0  4911.3    0.05       0  4915.3    0.05       0
  5015.7    0.12       0
Bank Sta=4911.3,4915.3
Exp/Cntr=0.3,0.1

Type RM Length L Ch R = 1,1403,150,150,150
BEGIN DESCRIPTION:
Mapping XS 1224c145
END DESCRIPTION:
XS GIS Cut Line= 3
      2730316.51      6893156.01      2730764.41      6893119.56
      2730996.22      6893116.95
#Sta/Elev= 30
  4539.2  460.46  4541.5  460.67  4568.8  459.81  4608.9  457.71  4649.1  456.33
  4658.4  455.67  4663.4  455.64  4669.1  455.01  4729.3  451.34  4779.5  449.53
  4790.2  448.38  4819.6  447.00  4869.8  445.29  4899.9  443.06  4907.0  442.81
  4919.9  443.01  4950.0  442.18  4960.1  441.52  4970.1  440.12  4980.1  439.25
  4984.9  439.19  4985.1  438.69  4988.6  438.69  4988.9  439.19  5010.2  440.47
  5030.2  441.02  5090.2  440.34  5100.2  440.55  5120.2  441.85  5220.4  443.38
#Mann=3,-1,0
  4539.2    0.05       0  4984.9    0.05       0  4988.9    0.05       0
Bank Sta=4984.9,4988.9
Exp/Cntr=0.3,0.1

Type RM Length L Ch R = 1,1253,323,323,323
BEGIN DESCRIPTION:
Mapping XS 40e200bf
END DESCRIPTION:
XS GIS Cut Line= 3
      2730420.68      6893299.24      2730806.08      6893260.18
      2731031.81      6893161.59
#Sta/Elev= 30
  4600.1  457.91  4615.5  457.59  4645.7  455.90  4706.0  454.16  4731.3  452.31
  4766.3  451.03  4806.5  448.31  4826.1  447.24  4831.1  447.28  4836.6  446.53
  4866.8  445.02  4947.2  443.03  4967.3  440.77  4984.9  439.68  4990.2  439.68
  4995.4  439.08  5000.8  439.25  5007.2  438.17  5007.5  437.67  5011.0  437.67
  5011.2  438.17  5024.2  440.76  5031.0  441.08  5047.6  440.42  5071.1  440.19
  5107.4  440.38  5170.1  441.48  5199.0  442.57  5216.5  442.47  5233.8  442.84
#Mann=3,-1,0
  4600.1    0.05       0  5007.2    0.04       0  5011.2    0.05       0
Bank Sta=5007.2,5011.2
Exp/Cntr=0.3,0.1

Type RM Length L Ch R = 1,930,0,0,0
BEGIN DESCRIPTION:
Mapping XS bca2fa7e
END DESCRIPTION:
XS GIS Cut Line= 4
      2730496.21      6893471.13      2730861.58      6893567.47
      2730983.89      6893465.15      2731069.45      6893174.29
#Sta/Elev= 30
  4536.4  456.61  4587.9  455.28  4608.6  453.99  4669.3  451.97  4691.3  450.70
  4722.3  447.74  4749.9  445.85  4755.1  445.77  4763.7  444.66  4784.4  443.33
  4790.2  442.64  4830.5  442.51  4865.6  440.80  4914.0  439.15  4935.9  439.36
  4950.2  439.05  4958.0  438.50  4978.8  438.75  5011.9  438.34  5012.2  437.84
  5015.7  437.84  5015.9  438.34  5036.0  438.87  5050.3  438.53  5088.5  438.57
  5129.7  439.45  5173.4  439.62  5201.6  440.26  5312.1  441.02  5376.9  442.74
#Mann=3,-1,0
  4536.4    0.05       0  5011.9    0.04       0  5015.9    0.05       0
Bank Sta=5011.9,5015.9
Exp/Cntr=0.3,0.1

Chan Stop Cuts=-1