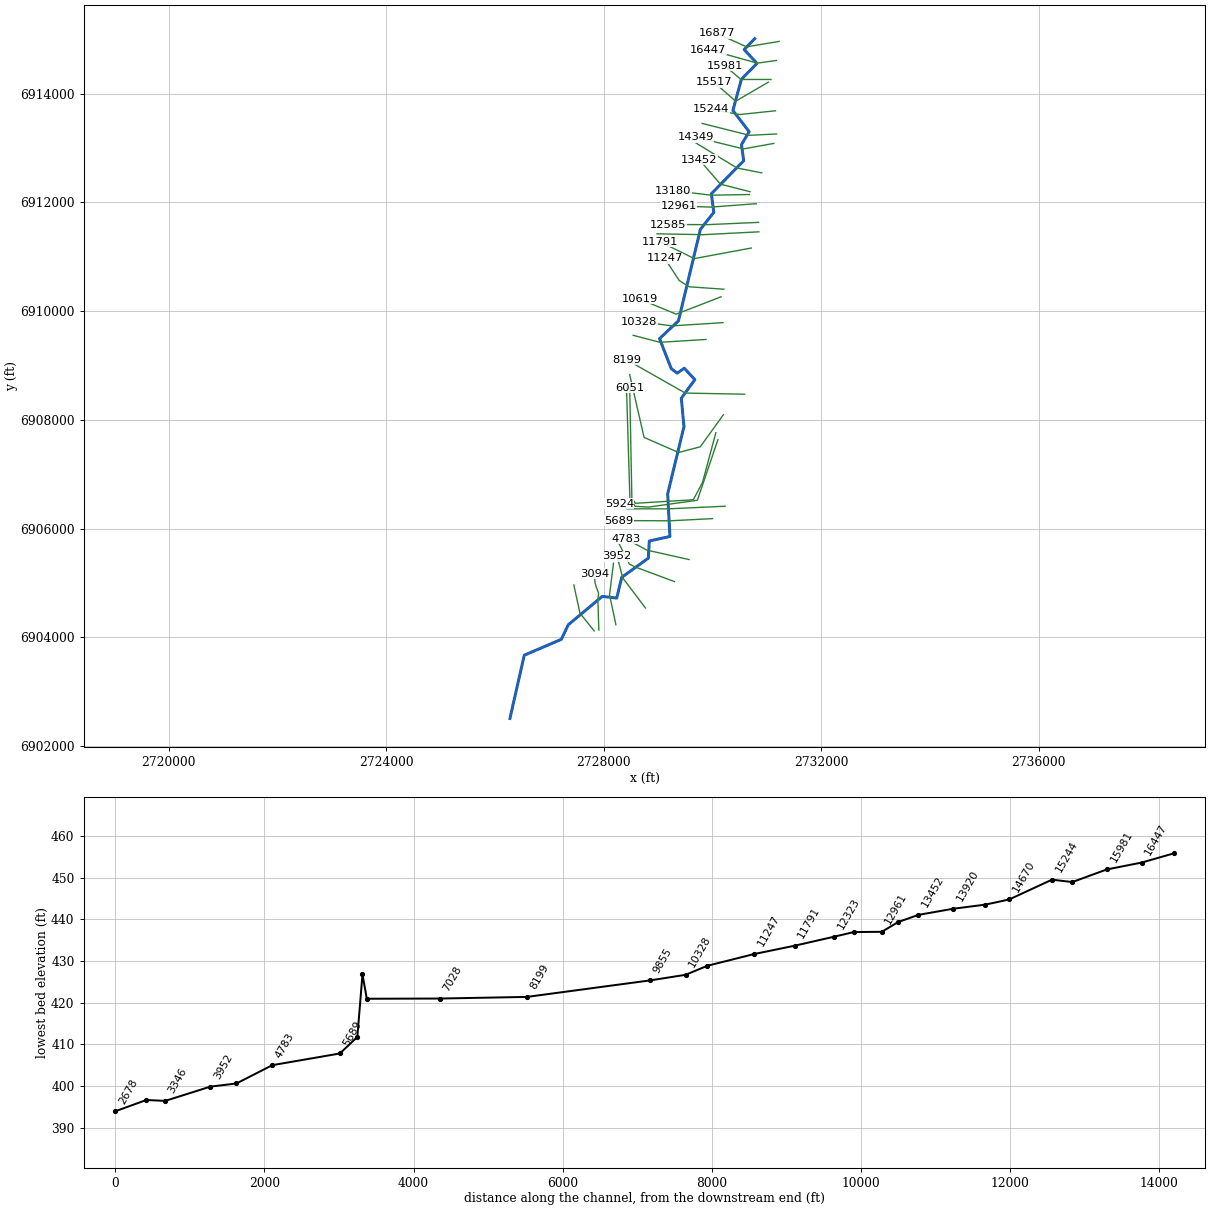
--- Caney T3.prj (project) ---

Proj Title=Caney T3 Base Level Engineering
Current Plan=p01
Default Exp/Contr=0.3,0.1
English Units
Geom File=g01
Flow File=f01
Plan File=p01
Y Axis Title=Elevation
X Axis Title(PF)=Main Channel Distance
X Axis Title(XS)=Station
BEGIN DESCRIPTION:
Caney T3
END DESCRIPTION:
DSS Export Rating Curves= 0
DSS Export Rating Curve Sorted= 0
DSS Export Volume Flow Curves= 0
DXF OffsetX= 0
DXF OffsetY= 0
DXF ScaleX= 1
DXF ScaleY= 10

--- Caney T3.p01 (plan) ---

Plan Title=Multiple Run
Short Identifier=Multiple
Geom File=g01
Flow File=f01
Subcritical Flow
K Sum by GR= 0
Std Step Tol= 0.01
Critical Tol= 0.01
Num of Std Step Trials= 20
Max Error Tol= 0.3
Flow Tol Ratio= 0.001
Split Flow NTrial= 30
Split Flow Tol= 0.02
Split Flow Ratio= 0.02
Log Output Level= 0
Friction Slope Method= 1
Unsteady Friction Slope Method= 2
Unsteady Bridges Friction Slope Method= 1
Parabolic Critical Depth
Global Vel Dist=  1 , 1 , 1
Global Log Level= 0
CheckData=True
Encroach Param= -1, 0, 0, 0
BEGIN DESCRIPTION:
Multiple Run
END DESCRIPTION:

--- Caney T3.f01 (steady flow) ---

Flow Title=Multiple
Number of Profiles=7
Profile Names=10-year,25-year,50-year,1pct_min,100-year,1pct_plu,500-year
River Rch & RM= Caney T3,Reach-1,16877
     558     737     879     521    1039    2073    1449
River Rch & RM= Caney T3,Reach-1,11791
     788    1060    1281     767    1531    3054    2183
River Rch & RM= Caney T3,Reach-1,5924
     943    1283    1560     940    1876    3743    2709
Boundary for River Rch & Prof#=Caney T3,Reach-1,1
Up Type=0
Dn Type=3
Dn Slope=0.005
Boundary for River Rch & Prof#=Caney T3,Reach-1,2
Up Type=0
Dn Type=3
Dn Slope=0.005
Boundary for River Rch & Prof#=Caney T3,Reach-1,3
Up Type=0
Dn Type=3
Dn Slope=0.005
Boundary for River Rch & Prof#=Caney T3,Reach-1,4
Up Type=0
Dn Type=3
Dn Slope=0.005
Boundary for River Rch & Prof#=Caney T3,Reach-1,5
Up Type=0
Dn Type=3
Dn Slope=0.005
Boundary for River Rch & Prof#=Caney T3,Reach-1,6
Up Type=0
Dn Type=3
Dn Slope=0.005
Boundary for River Rch & Prof#=Caney T3,Reach-1,7
Up Type=0
Dn Type=3
Dn Slope=0.005

--- Caney T3.g01 (geometry) ---

Geom Title=Existing Conditions
Program Version=4.10

River Reach=Caney T3        ,Reach-1
Reach XY= 30
        2730776.        6915011.      2730583.07      6914810.99
      2730818.33      6914557.35       2730531.7      6914263.54
      2730375.79      6913690.94       2730674.9      6913300.45
      2730533.82      6913064.41      2730574.03      6912766.89
      2729979.54      6912159.54       2730024.2      6911817.11
      2729777.89      6911505.29       2729374.8      6909823.02
      2729026.53      6909495.45       2729242.3      6908944.27
        2729351.      6908860.56      2729482.64      6908951.63
       2729676.5      6908740.77      2729427.06      6908400.56
      2729475.91      6907876.39      2729176.07      6906640.97
      2729218.13      6905857.38      2728839.23      6905774.73
      2728820.61      6905458.56      2728331.41      6905105.82
      2728239.41      6904724.52      2727973.55      6904755.53
      2727349.05      6904234.33      2727220.59      6903966.18
      2726539.37      6903674.31        2726276.        6902511.

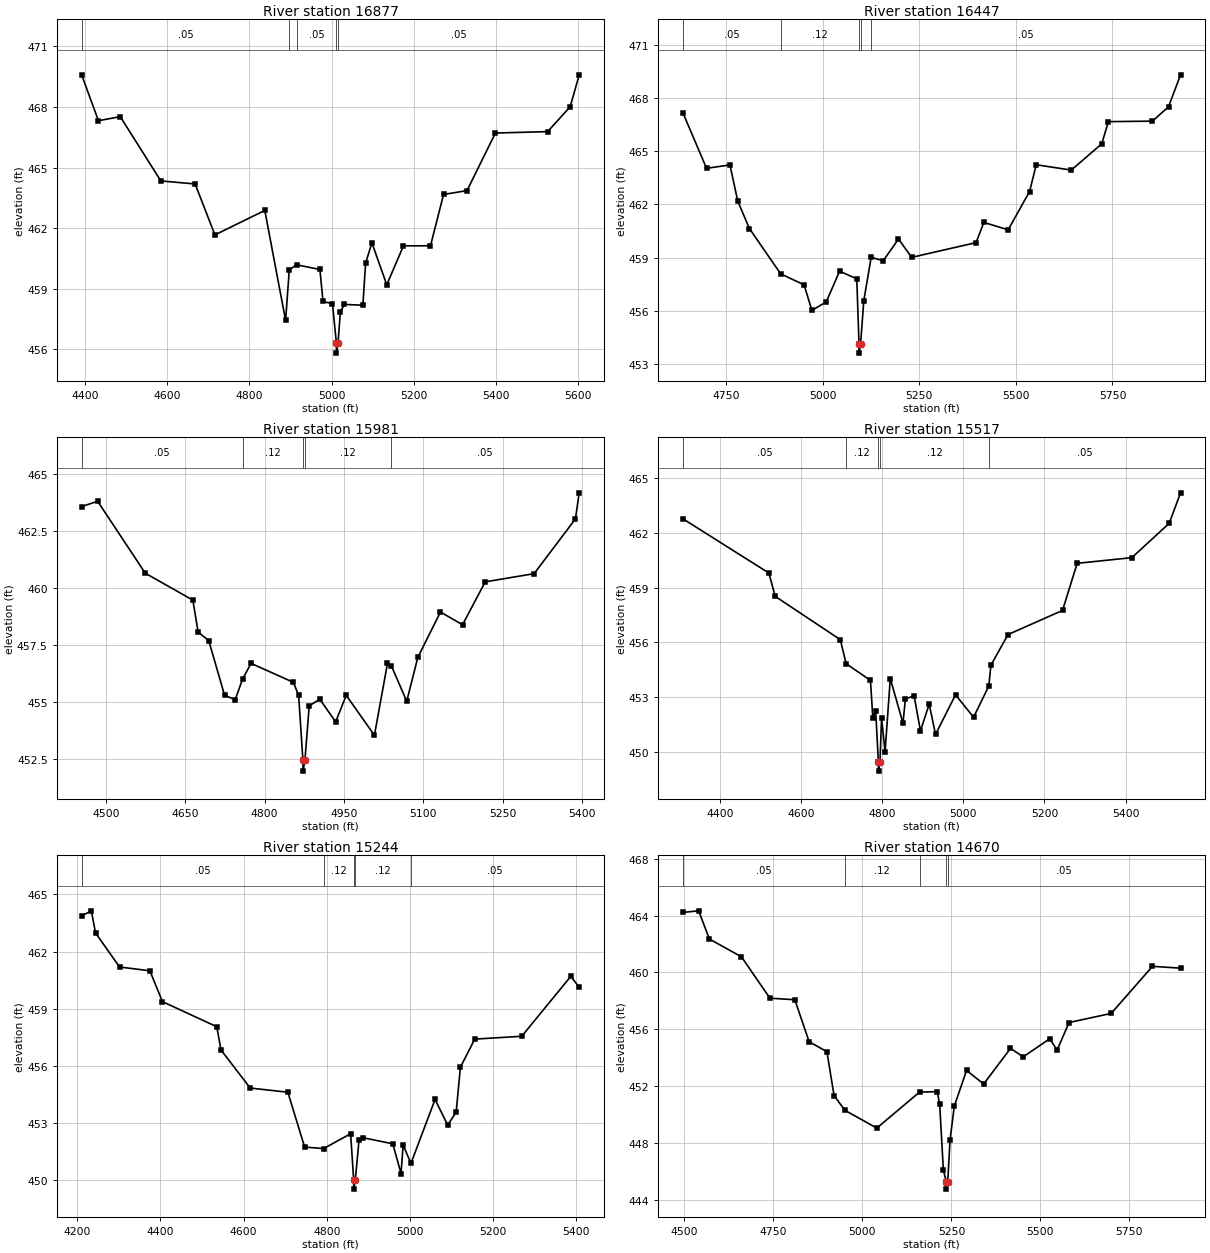
Type RM Length L Ch R = 1 ,16877   ,430,430,430
BEGIN DESCRIPTION:
Caney T3 29.0
END DESCRIPTION:
XS GIS Cut Line= 3
      2731226.04      6914961.01        2730626.        6914861.
      2730075.97      6915111.01
#Sta/Elev= 30
  4391.3  469.57  4431.9  467.32  4485.1  467.52    4584  464.34  4667.6  464.19
  4715.8  461.67  4837.4  462.88  4888.1  457.44  4897.1  459.95  4915.2  460.19
  4971.7  459.96  4979.3  458.38  5002.4  458.26  5011.9  456.32  5012.1  455.82
  5015.9  456.32  5021.6  457.87  5031.5  458.23  5076.5  458.19  5083.1  460.27
  5098.5  461.28  5134.7   459.2  5175.4  461.13  5241.3  461.13  5273.1  463.67
  5330.3  463.86  5399.5  466.71  5526.9  466.78  5581.8  468.01  5603.8  469.59
#Mann= 5 ,-1 , 0
  4391.3     .05       0  4897.1     .12       0  4915.2     .05       0
  5011.9     .04       0  5015.9     .05       0
Bank Sta=5011.9,5015.9
XS Rating Curve= 0 ,0
Exp/Cntr=0.3,0.1

Type RM Length L Ch R = 1 ,16447   ,466,466,466
BEGIN DESCRIPTION:
Caney T3 28.0
END DESCRIPTION:
XS GIS Cut Line= 3
      2731175.96      6914610.99        2730826.        6914561.
      2729925.99        6914811.
#Sta/Elev= 30
  4638.6  467.14  4699.2  464.04  4759.8  464.23    4780  462.19  4810.3  460.64
  4891.1  458.09  4951.7  457.47  4971.9  456.03  5009.2  456.51  5043.5  458.24
  5088.1  457.81  5093.9  454.12  5094.1  453.62  5097.9  454.12  5106.3  456.58
  5125.3  459.02  5156.6  458.83  5196.1  460.05  5230.3  459.02  5396.9  459.85
  5417.1  460.99  5479.9  460.57  5535.4  462.73  5552.6  464.24  5643.4  463.94
  5722.2  465.42  5739.4  466.67  5853.5   466.7  5895.1  467.51  5926.2  469.31
#Mann= 5 ,-1 , 0
  4638.6     .05       0  4891.1     .12       0  5093.9     .07       0
  5097.9     .12       0  5125.3     .05       0
Bank Sta=5093.9,5097.9
XS Rating Curve= 0 ,0
Exp/Cntr=0.3,0.1

Type RM Length L Ch R = 1 ,15981   ,464,464,464
BEGIN DESCRIPTION:
Caney T3 27.0
END DESCRIPTION:
XS GIS Cut Line= 3
        2731076.        6914261.        2730526.        6914261.
      2730226.01      6914510.99
#Sta/Elev= 30
  4454.5  463.57  4484.5   463.8  4574.5  460.65  4664.5  459.47  4674.5  458.07
  4694.5   457.7  4724.5   455.3  4744.5  455.11  4758.5  456.01  4774.5   456.7
  4854.5  455.87  4864.5   455.3  4872.5  452.48  4872.8  451.98  4876.5  452.48
  4884.5  454.84  4904.5  455.13  4934.5  454.14  4954.5   455.3  5007.8  453.55
  5032.5   456.7  5039.7   456.6  5068.9  455.04  5089.8  456.96  5132.7  458.95
  5174.4  458.39  5217.3  460.27  5309.8  460.63  5387.9  463.03    5395  464.17
#Mann= 5 ,-1 , 0
  4454.5     .05       0  4758.5     .12       0  4872.5     .07       0
  4876.5     .12       0  5039.7     .05       0
Bank Sta=4872.5,4876.5
XS Rating Curve= 0 ,0
Exp/Cntr=0.3,0.1

Type RM Length L Ch R = 1 ,15517   ,273,273,273
BEGIN DESCRIPTION:
Caney T3 26.0
END DESCRIPTION:
XS GIS Cut Line= 3
      2731025.98      6914210.99        2730426.        6913861.
        2730026.        6914211.
#Sta/Elev= 30
  4309.4  462.76  4520.7   459.8  4536.4  458.52  4696.8  456.15  4711.3  454.83
  4771.2  453.92    4777  451.85    4784  452.26  4790.7  449.45    4791  448.95
  4794.7  449.45  4798.5  451.86  4807.2  450.01    4820  454.02  4851.4  451.57
  4857.2   452.9  4878.7  453.08  4894.4  451.15  4915.9  452.62  4931.6  450.96
  4980.8  453.13  5025.4   451.9  5062.8  453.61  5068.1  454.75  5110.3  456.43
  5244.6  457.75  5280.7  460.33  5415.4  460.64  5507.5  462.52  5535.5  464.19
#Mann= 5 ,-1 , 0
  4309.4     .05       0  4711.3     .12       0  4790.7     .07       0
  4794.7     .12       0  5062.8     .05       0
Bank Sta=4790.7,4794.7
XS Rating Curve= 0 ,0
Exp/Cntr=0.3,0.1

Type RM Length L Ch R = 1 ,15244   ,574,574,574
BEGIN DESCRIPTION:
Mapping XS ff2e5e10
END DESCRIPTION:
XS GIS Cut Line= 3
      2731158.79      6913685.83      2730502.52      6913616.38
      2729974.72      6913710.14
#Sta/Elev= 30
  4210.9  463.88  4233.8  464.14  4243.9  462.98  4301.7  461.19  4374.6  460.99
  4404.8  459.37  4535.5  458.05  4545.6  456.83  4615.9  454.83  4706.4  454.61
  4746.7  451.73  4792.4  451.65  4857.3  452.43  4864.6  450.02  4864.8  449.52
  4868.6  450.02  4877.5  452.09  4887.6  452.22  4958.7   451.9  4978.5  450.34
  4983.6  451.84  5002.3  450.87  5060.3  454.23  5090.7  452.88  5111.1  453.57
  5121.2  455.92  5155.7   457.4  5268.7  457.55  5386.8   460.7  5406.9  460.12
#Mann= 5 ,-1 , 0
  4210.9     .05       0  4792.4     .12       0  4864.6     .07       0
  4868.6     .12       0  5002.3     .05       0
Bank Sta=4864.6,4868.6
XS Rating Curve= 0 ,0
Exp/Cntr=0.3,0.1

Type RM Length L Ch R = 1 ,14670   ,321,321,321
BEGIN DESCRIPTION:
Mapping XS 2e54c7d7
END DESCRIPTION:
XS GIS Cut Line= 3
      2731179.57      6913258.74      2730679.61      6913234.44
      2729809.54      6913452.82
#Sta/Elev= 30
  4496.2  464.22  4539.8  464.33  4569.9  462.35    4660   461.1  4740.1  458.19
  4810.1  458.08  4850.2  455.13  4900.2  454.43  4920.3  451.34  4950.8  450.31
  5040.4  449.06  5160.4  451.59  5210.2  451.62    5217  450.75  5227.3  446.14
  5235.6  445.27  5235.9  444.77  5239.6  445.27  5246.2  448.24  5258.2  450.61
  5292.5  453.11  5340.7  452.16    5416  454.66    5452  454.07  5526.3  455.34
  5546.9  454.54  5580.6  456.48  5698.9  457.12    5815  460.43  5893.8   460.3
#Mann= 5 ,-1 , 0
  4496.2     .05       0  4950.8     .12       0  5160.4     .05       0
  5235.6     .07       0  5239.6     .05       0
Bank Sta=5235.6,5239.6
XS Rating Curve= 0 ,0
Exp/Cntr=0.3,0.1

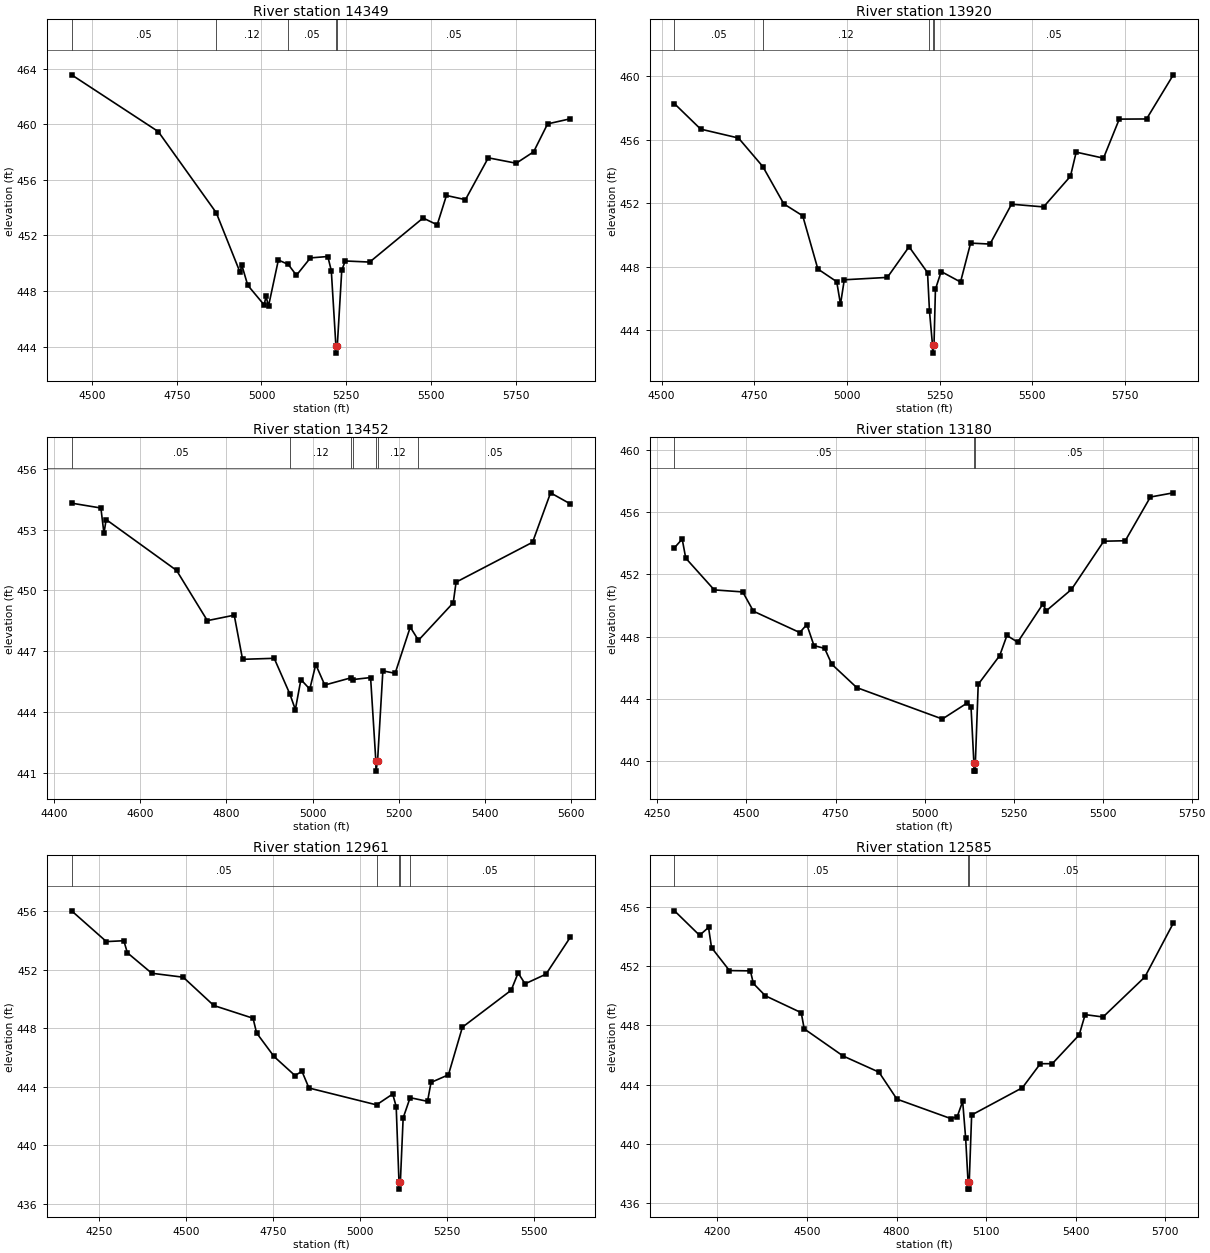
Type RM Length L Ch R = 1 ,14349   ,429,429,429
BEGIN DESCRIPTION:
Mapping XS 8d809c3f
END DESCRIPTION:
XS GIS Cut Line= 3
      2731127.51      6913085.13      2730571.97      6912984.44
      2729690.55      6913199.59
#Sta/Elev= 30
  4439.7  463.55  4695.3  459.47  4866.5  453.63  4936.8  449.34  4941.9  449.86
  4959.5  448.41  5008.1  446.99  5013.2  447.63  5020.7  446.91  5049.8  450.23
    5079  449.91  5103.1  449.13  5144.3  450.38  5195.7  450.48    5206  449.46
  5219.6  444.03  5219.9  443.53  5223.6  444.03  5236.9   449.5  5247.2  450.16
  5319.2  450.08  5476.8  453.25  5518.5  452.76  5545.7  454.87  5601.8  454.57
  5669.2  457.58  5751.6  457.19    5803  458.01  5844.2  460.02  5911.6  460.39
#Mann= 5 ,-1 , 0
  4439.7     .05       0  4866.5     .12       0    5079     .05       0
  5219.6     .07       0  5223.6     .05       0
Bank Sta=5219.6,5223.6
XS Rating Curve= 0 ,0
Exp/Cntr=0.3,0.1

Type RM Length L Ch R = 1 ,13920   ,468,468,468
BEGIN DESCRIPTION:
Mapping XS b93aa1d2
END DESCRIPTION:
XS GIS Cut Line= 3
      2730905.27      6912543.47      2730450.44      6912633.74
      2729696.99      6913092.07
#Sta/Elev= 30
  4534.6  458.26  4605.2  456.66  4707.2   456.1  4772.9   454.3  4829.5  451.95
  4880.5   451.2  4921.3  447.85  4972.2  447.05  4982.4  445.63  4992.6  447.17
  5108.8  447.32  5167.4  449.25  5217.2  447.62  5222.4  445.21  5230.6  443.05
  5230.9  442.55  5234.6  443.05  5238.5  446.57    5254  447.69  5306.2  447.03
  5333.4  449.48  5385.7  449.42  5443.8  451.93  5530.2  451.76  5602.7  453.69
  5618.2  455.21  5691.8  454.83  5734.4  457.29    5808   457.3  5880.2  460.08
#Mann= 5 ,-1 , 0
  4534.6     .05       0  4772.9     .12       0  5222.4     .05       0
  5230.6     .07       0  5234.6     .05       0
Bank Sta=5230.6,5234.6
XS Rating Curve= 0 ,0
Exp/Cntr=0.3,0.1

Type RM Length L Ch R = 1 ,13452   ,272,272,272
BEGIN DESCRIPTION:
Mapping XS a3233260
END DESCRIPTION:
XS GIS Cut Line= 3
      2730691.86      6912196.98       2730147.2      6912335.86
      2729757.12      6912786.61
#Sta/Elev= 30
  4440.5  454.31  4508.5  454.07  4515.6  452.82  4520.7   453.5  4684.2  450.99
  4755.7  448.51  4818.1  448.78  4837.4   446.6  4910.9  446.65  4947.2  444.89
    4960  444.12  4972.9   445.6  4993.5  445.13  5007.4  446.34  5028.3  445.33
  5089.7  445.69  5093.1   445.6  5134.7   445.7  5146.9  441.58  5147.2  441.08
  5150.9  441.58  5163.2  446.03  5191.7  445.91  5226.8  448.19  5245.8  447.54
  5326.6  449.39  5333.2  450.41  5510.8  452.38  5552.6  454.82  5598.7  454.27
#Mann= 7 ,-1 , 0
  4440.5     .05       0  4947.2     .12       0  5089.7      .1       0
  5093.1     .12       0  5146.9     .07       0  5150.9     .12       0
  5245.8     .05       0
Bank Sta=5146.9,5150.9
XS Rating Curve= 0 ,0
Exp/Cntr=0.3,0.1

Type RM Length L Ch R = 1 ,13180   ,219,219,219
BEGIN DESCRIPTION:
Mapping XS 4c95bb9f
END DESCRIPTION:
XS GIS Cut Line= 3
      2730677.57      6912145.75      2729979.66      6912132.73
      2729282.05      6912216.03
#Sta/Elev= 30
  4297.9  453.71  4319.5  454.27  4329.5  453.04  4409.5     451  4489.5  450.87
  4519.5  449.63  4649.5  448.26  4669.5  448.77  4689.5  447.42  4719.5  447.24
  4739.6  446.22  4809.6  444.72    5050   442.7  5120.5  443.74  5130.5  443.48
  5138.6  439.85  5138.9  439.35  5142.4  439.35  5142.6  439.85  5150.7  444.93
  5211.1  446.78  5231.3  448.07  5261.5  447.64    5332  450.08    5342  449.66
  5412.5  451.03  5503.2  454.13  5563.6  454.16  5634.1  456.97  5698.5  457.24
#Mann= 3 ,-1 , 0
  4297.9     .05       0  5138.6     .04       0  5142.6     .05       0
Bank Sta=5138.6,5142.6
XS Rating Curve= 0 ,0
Exp/Cntr=0.3,0.1

Type RM Length L Ch R = 1 ,12961   ,376,376,376
BEGIN DESCRIPTION:
Mapping XS 76dd0ce2
END DESCRIPTION:
XS GIS Cut Line= 3
      2730805.57      6911976.91      2729977.49      6911914.41
       2729375.9      6911932.64
#Sta/Elev= 30
  4171.2  456.01  4271.1  453.91  4321.2  453.97  4331.2  453.15  4401.4  451.75
  4491.7  451.48  4579.4  449.55  4692.2  448.68  4702.3  447.68  4752.4  446.07
  4812.6  444.77  4832.6  445.06  4852.7  443.92  5046.7  442.77  5093.2  443.51
  5103.2  442.65  5111.2  437.52  5111.4  437.02  5115.2  437.52  5123.2  441.88
  5143.2  443.26  5193.2  443.01  5203.2   444.3  5253.2  444.82  5293.3  448.07
  5433.3  450.59  5453.3  451.77  5473.3  451.03  5533.4  451.69  5603.5  454.22
#Mann= 5 ,-1 , 0
  4171.2     .05       0  5046.7     .12       0  5111.2     .04       0
  5115.2     .12       0  5143.2     .05       0
Bank Sta=5111.2,5115.2
XS Rating Curve= 0 ,0
Exp/Cntr=0.3,0.1

Type RM Length L Ch R = 1 ,12585   ,262,262,262
BEGIN DESCRIPTION:
Mapping XS 5869a68d
END DESCRIPTION:
XS GIS Cut Line= 3
      2730849.86      6911633.16      2729904.58       6911591.5
      2729180.78       6911594.1
#Sta/Elev= 30
  4056.6  455.72  4140.5  454.07  4170.6   454.6  4180.6  453.24  4240.6  451.69
  4310.7  451.67  4320.7  450.82  4360.8  449.99  4480.9  448.85  4490.9  447.76
    4621  445.93  4741.1  444.84  4801.2  443.02  4981.4  441.71  5002.8  441.82
  5021.4  442.87  5031.4  440.37  5039.4  437.45  5039.6  436.95  5043.1  436.95
  5043.4  437.45  5051.4  441.95  5221.4  443.79  5281.4  445.41  5321.4  445.41
  5411.4  447.35  5431.4  448.72  5491.4  448.56  5631.4  451.26  5726.6  454.89
#Mann= 3 ,-1 , 0
  4056.6     .05       0  5039.4     .05       0  5043.4     .05       0
Bank Sta=5039.4,5043.4
XS Rating Curve= 0 ,0
Exp/Cntr=0.3,0.1

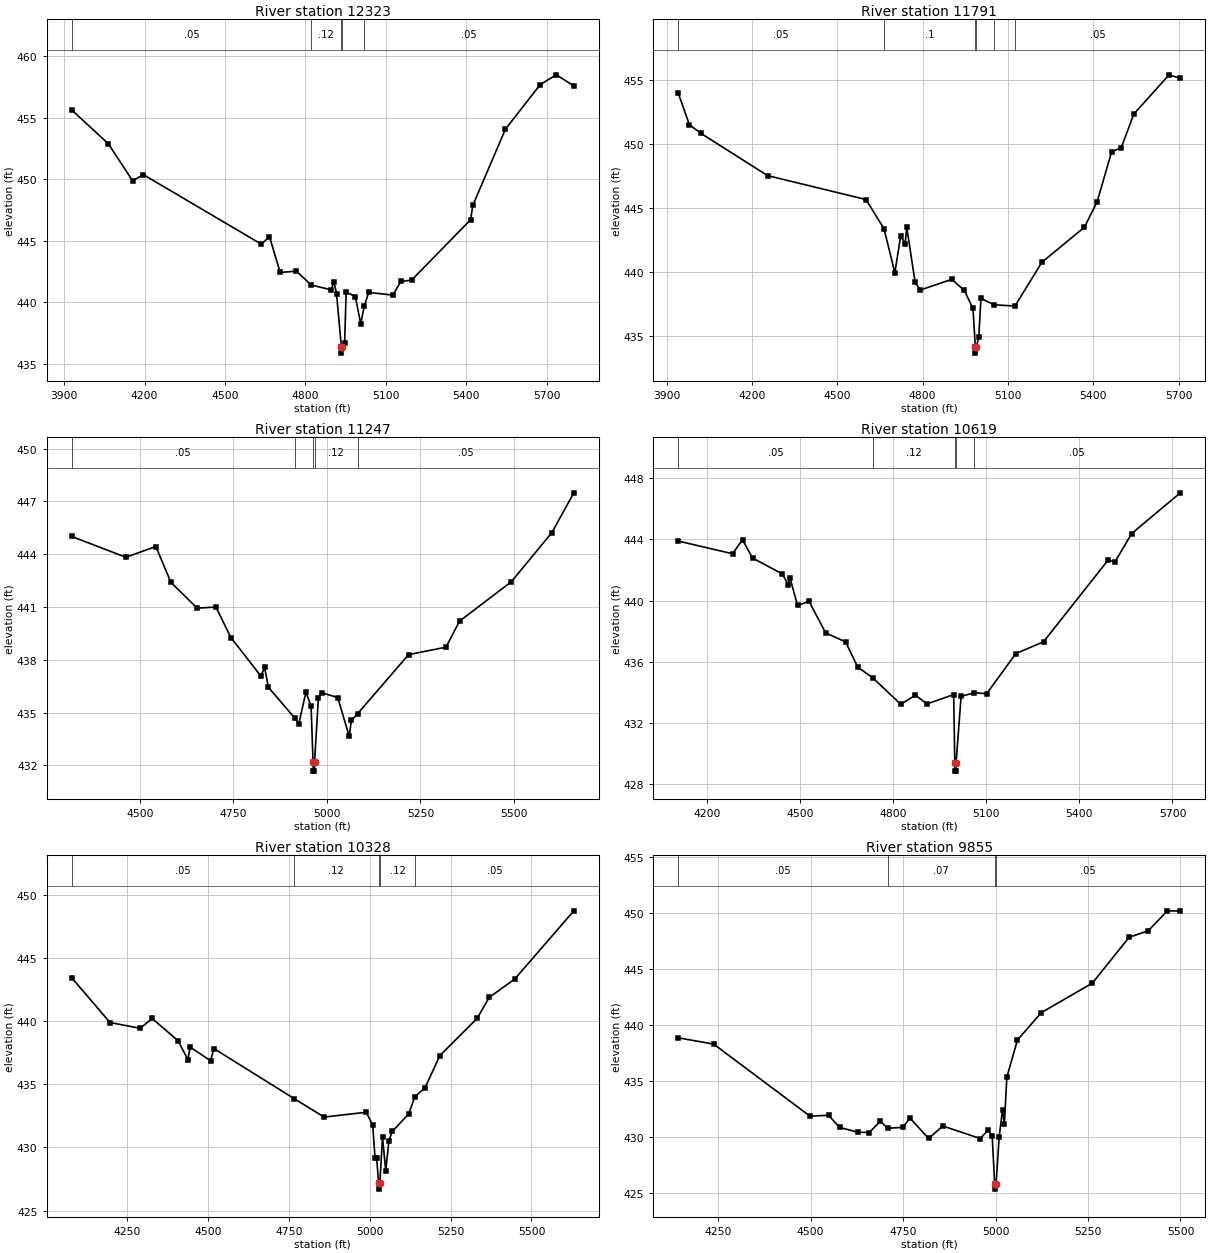
Type RM Length L Ch R = 1 ,12323   ,532,532,532
BEGIN DESCRIPTION:
Mapping XS ad3923eb
END DESCRIPTION:
XS GIS Cut Line= 3
      2730852.73      6911459.34      2729829.27      6911407.25
       2728980.7      6911422.87
#Sta/Elev= 30
  3928.2  455.63  4065.1  452.87  4155.2  449.87  4195.5  450.37  4635.8  444.71
  4665.9  445.33  4705.9  442.41    4766  442.52    4822  441.39  4896.2     441
  4906.2  441.67  4916.2  440.69  4934.2  436.35  4934.5  435.85  4938.2  436.35
  4946.3  436.68  4952.1  440.82  4986.3  440.45  5006.3  438.25  5020.1   439.7
  5036.3  440.79  5126.3  440.57  5156.3  441.68  5196.3  441.79  5416.3   446.7
  5424.8  447.87  5546.4  454.07  5676.4   457.7  5736.4  458.49  5801.7  457.59
#Mann= 5 ,-1 , 0
  3928.2     .05       0    4822     .12       0  4934.2     .07       0
  4938.2     .12       0  5020.1     .05       0
Bank Sta=4934.2,4938.2
XS Rating Curve= 0 ,0
Exp/Cntr=0.3,0.1

Type RM Length L Ch R = 1 ,11791   ,544,544,544
BEGIN DESCRIPTION:
Mapping XS 4f0f6003
END DESCRIPTION:
XS GIS Cut Line= 3
      2730714.67      6911161.59      2729666.08      6910967.15
       2729039.5      6911275.25
#Sta/Elev= 30
  3941.2  454.01  3980.5  451.54  4021.2  450.86  4255.1  447.56  4600.9  445.69
  4664.4  443.41  4702.6  439.96    4723  442.84    4739  442.23  4744.1  443.57
  4773.8  439.21  4791.8  438.61  4902.6  439.45  4946.7  438.58  4977.2  437.17
  4985.4  434.18  4985.7  433.68  4989.4  434.18  4997.6  434.97  5005.2  437.96
  5051.6  437.46  5124.6  437.36  5219.5  440.79  5368.8  443.52  5413.7  445.52
  5464.6  449.43  5498.1  449.73  5542.6  452.38  5666.5  455.44  5705.9  455.16
#Mann= 6 ,-1 , 0
  3941.2     .05       0  4664.4      .1       0  4985.4     .07       0
  4989.4      .1       0  5051.6     .12       0  5124.6     .05       0
Bank Sta=4985.4,4989.4
XS Rating Curve= 0 ,0
Exp/Cntr=0.3,0.1

Type RM Length L Ch R = 1 ,11247   ,628,628,628
BEGIN DESCRIPTION:
Mapping XS 3b0f0e9a
END DESCRIPTION:
XS GIS Cut Line= 4
      2730210.17       6910404.3      2729572.16      6910448.57
      2729389.86      6910563.16      2729121.62      6910969.43
#Sta/Elev= 30
  4318.2  445.01  4462.7  443.83  4542.9  444.44    4583  442.41  4653.2  440.94
  4703.3     441  4743.4  439.27  4823.6  437.08  4833.6  437.57  4843.6  436.44
  4913.5  434.71  4924.7  434.36  4943.9  436.16  4957.7  435.39    4963  432.18
  4963.3  431.68  4966.8  431.68    4967  432.18  4977.2  435.84  4986.6  436.13
    5029  435.86  5059.5  433.66  5065.5  434.56  5082.3  434.95  5218.4   438.3
  5318.2  438.72  5354.4   440.2  5492.9  442.44  5601.2  445.23  5659.9  447.49
#Mann= 5 ,-1 , 0
  4318.2     .05       0  4913.5     .12       0    4963     .07       0
    4967     .12       0  5082.3     .05       0
Bank Sta=4963,4967
XS Rating Curve= 0 ,0
Exp/Cntr=0.3,0.1

Type RM Length L Ch R = 1 ,10619   ,291,291,291
BEGIN DESCRIPTION:
Mapping XS 5842a23d
END DESCRIPTION:
XS GIS Cut Line= 3
      2730159.27      6910264.84      2729332.86      6909945.39
      2728656.59       6910226.3
#Sta/Elev= 30
  4106.9  443.89  4281.9  443.06  4314.1  443.98  4346.3  442.78  4442.8  441.74
  4461.5  441.03  4466.9   441.5  4491.5  439.68  4528.5  439.95  4582.1  437.89
  4646.5   437.3  4685.1  435.66  4734.1  434.95  4824.1  433.23  4871.6  433.82
  4908.6  433.25  4994.7  433.86  4998.3  429.36  4998.6  428.86  5002.1  428.86
  5002.3  429.36  5018.6  433.74  5060.5  433.98    5101  433.92  5195.2  436.54
  5284.3  437.31  5491.4  442.62  5515.3  442.55  5568.4  444.38  5725.2  447.04
#Mann= 5 ,-1 , 0
  4106.9     .05       0  4734.1     .12       0  4998.3     .07       0
  5002.3     .12       0  5060.5     .05       0
Bank Sta=4998.3,5002.3
XS Rating Curve= 0 ,0
Exp/Cntr=0.3,0.1

Type RM Length L Ch R = 1 ,10328   ,473,473,473
BEGIN DESCRIPTION:
Mapping XS ca985bc6
END DESCRIPTION:
XS GIS Cut Line= 3
      2730193.92      6909789.14      2729256.47      6909730.11
       2728649.9      6909809.83
#Sta/Elev= 30
  4079.8  443.44    4198   439.9    4291  439.44  4328.2  440.22  4408.4  438.45
  4438.4  436.96  4445.7  437.95  4508.6  436.87  4518.6  437.84  4766.2  433.88
  4859.3  432.41  4989.5  432.79  5009.6  431.76  5016.8  429.13  5021.9  429.13
  5027.7   427.2  5027.9   426.7  5031.7   427.2  5039.8  430.81  5049.8  428.14
  5059.6  430.55    5070  431.27  5120.4  432.65  5139.9  434.03  5170.9  434.72
    5217  437.28  5332.3  440.23  5369.4  441.89  5448.1  443.34  5630.9  448.75
#Mann= 5 ,-1 , 0
  4079.8     .05       0  4766.2     .12       0  5027.7     .07       0
  5031.7     .12       0  5139.9     .05       0
Bank Sta=5027.7,5031.7
XS Rating Curve= 0 ,0
Exp/Cntr=0.3,0.1

Type RM Length L Ch R = 1 ,9855    ,1656,1656,1656
BEGIN DESCRIPTION:
Mapping XS 92324e2e
END DESCRIPTION:
XS GIS Cut Line= 3
      2729881.49      6909480.11      2729034.25      6909428.03
      2728542.12      6909556.26
#Sta/Elev= 30
  4142.1  438.87  4237.8  438.31  4498.3  431.88  4548.4  431.96  4578.4  430.87
  4628.5  430.45  4658.6  430.42  4688.6  431.43  4708.3   430.8  4748.7  430.88
  4768.8   431.7  4818.9  429.89  4857.5     431  4959.1  429.88  4979.2  430.64
  4990.9  430.15  4997.5  425.87  4997.7  425.37  5001.5  425.87  5009.8  430.04
  5018.8  432.42  5023.9  431.22  5030.5  435.37  5059.3  438.68  5123.5  441.11
  5261.7  443.75  5361.1  447.84  5412.8  448.42  5464.5   450.2  5499.5  450.18
#Mann= 4 ,-1 , 0
  4142.1     .05       0  4708.3     .07       0  4997.5     .03       0
  5001.5     .05       0
Bank Sta=4997.5,5001.5
XS Rating Curve= 0 ,0
Exp/Cntr=0.3,0.1

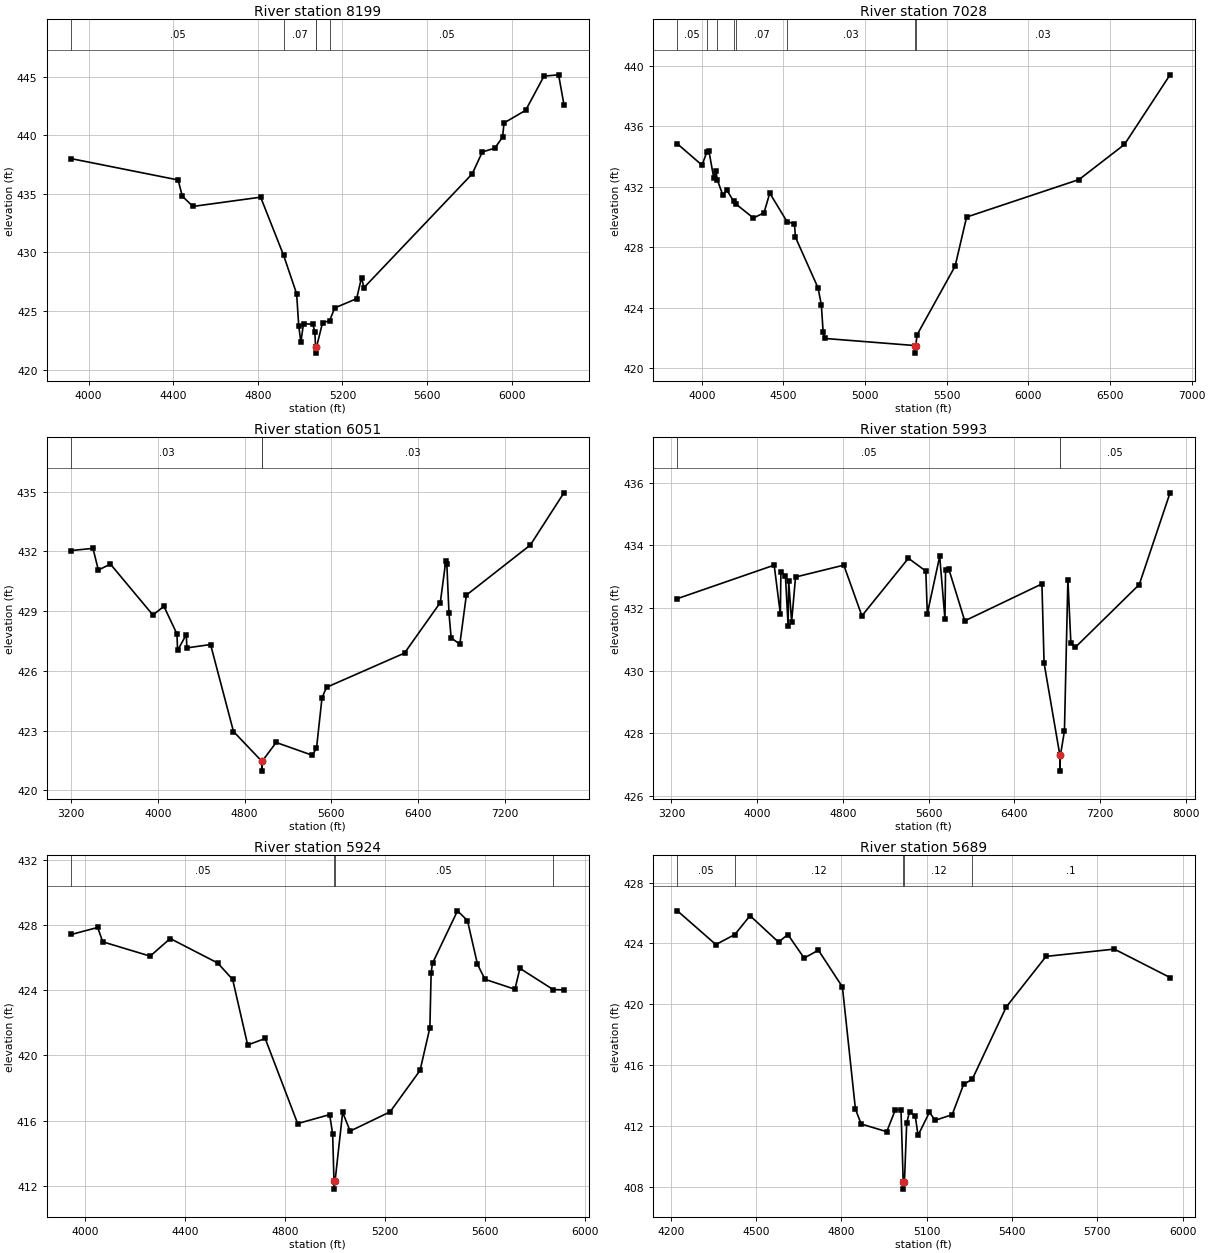
Type RM Length L Ch R = 1 ,8199    ,1171,1171,1171
BEGIN DESCRIPTION:
Mapping XS f5802d65
END DESCRIPTION:
XS GIS Cut Line= 3
      2730590.68      6908473.57      2729500.44      6908494.41
      2728424.06      6909105.51
#Sta/Elev= 30
  3918.6  438.01  4423.4  436.19  4443.4   434.8  4493.4  433.93  4813.4  434.72
  4922.3  429.74  4983.5  426.47  4993.5  423.72  5003.5  422.34  5016.1  423.93
  5060.1  423.85  5069.5  423.24  5073.1   421.9  5073.4   421.4  5077.3   421.9
  5106.1  424.01  5138.9  424.15  5163.6  425.26  5267.1  426.05  5290.1  427.85
  5301.6  426.99  5813.3  436.71  5861.1  438.58  5920.3  438.91  5957.1  439.86
  5963.5  441.06  6065.9  442.14  6152.6  445.06  6221.6  445.17  6246.8  442.63
#Mann= 5 ,-1 , 0
  3918.6     .05       0  4922.3     .07       0  5073.1     .05       0
  5077.3     .07       0  5138.9     .05       0
Bank Sta=5073.1,5077.3
XS Rating Curve= 0 ,0
Exp/Cntr=0.3,0.1

Type RM Length L Ch R = 1 ,7028    ,977,977,977
BEGIN DESCRIPTION:
Mapping XS c57264eb
END DESCRIPTION:
XS GIS Cut Line= 5
      2730200.82      6908096.22       2729775.5      6907505.98
      2729376.19      6907401.81      2728742.51      6907679.59
      2728477.74      6908834.14
#Sta/Elev= 30
    3851  434.84  4001.9  433.43  4031.8  434.32  4043.7  434.39  4073.1  432.61
  4087.8  433.02    4095  432.47  4129.6  431.44  4152.8   431.8  4195.8  431.04
  4211.8  430.84  4316.1  429.94  4381.1  430.28  4416.7  431.58  4522.8  429.69
  4567.6  429.56  4573.8  428.67  4712.3  425.32  4732.4   424.2  4743.4   422.4
  4753.7  421.98  5305.8  421.51  5306.2  421.01  5310.2  421.51    5319  422.23
  5551.6  426.76  5621.8     430  6310.4  432.48  6588.6   434.8  6867.6   439.4
#Mann= 8 ,-1 , 0
    3851     .05       0  4031.8     .12       0    4095     .05       0
  4195.8      .1       0  4211.8     .07       0  4522.8     .03       0
  5305.8     .03       0  5310.2     .03       0
Bank Sta=5305.8,5310.2
XS Rating Curve= 0 ,0
Exp/Cntr=0.3,0.1

Type RM Length L Ch R = 1 ,6051    ,58,58,58
BEGIN DESCRIPTION:
Mapping XS 6a93a9ac
END DESCRIPTION:
XS GIS Cut Line= 6
      2730061.95      6907764.71      2729817.16       6906850.6
      2729647.89      6906532.89      2728582.79      6906467.79
      2728517.68      6906561.54      2728478.62      6908590.17
#Sta/Elev= 30
  3201.9  432.04  3401.9  432.15  3451.2  431.06  3562.6  431.36  3954.5   428.8
  4055.5  429.24  4176.2  427.85  4181.5  427.02  4262.1  427.82  4267.5  427.15
  4485.9  427.32  4697.2  422.95  4957.7  421.46  4958.1  420.96  4962.2  421.46
  5090.4   422.4  5422.2  421.76  5462.5   422.1  5513.2  424.64  5554.8  425.17
    6274  426.89  6604.1  429.43  6654.1   431.5  6664.1  431.37  6684.1  428.88
  6704.1  427.65  6784.1  427.34  6844.1   429.8  7434.4  432.32  7743.8  434.94
#Mann= 3 ,-1 , 0
  3201.9     .03       0  4957.7     .03       0  4962.2     .03       0
Bank Sta=4957.7,4962.2
XS Rating Curve= 0 ,0
Exp/Cntr=0.3,0.1

Type RM Length L Ch R = 1 ,5993    ,69,69,69
BEGIN DESCRIPTION:
Mapping XS 25caba30
END DESCRIPTION:
XS GIS Cut Line= 6
      2730100.13      6907636.81      2729722.55      6906523.56
      2728821.94      6906397.69      2728576.71      6906412.88
      2728481.23      6906562.62      2728418.29      6908625.51
#Sta/Elev= 30
  3256.2   432.3  4159.4  433.37  4216.9  431.81  4222.1  433.16  4264.4  433.02
  4289.5  431.42  4294.7  432.87  4322.1  431.56  4358.7  432.99  4809.1  433.37
  4977.8  431.75  5412.1  433.59  5574.4  433.18  5588.6  431.82    5704  433.65
  5753.1  431.65  5758.4   433.2  5789.5  433.24  5937.9  431.59    6658  432.77
  6678.2  430.24  6825.9  427.29  6826.4  426.79  6830.4  427.29  6868.2  428.07
  6900.3  432.91  6928.3  430.88  6968.3  430.74  7566.5  432.75  7853.7  435.68
#Mann= 3 ,-1 , 0
  3256.2     .05       0  6825.9     .04       0  6830.4     .05       0
Bank Sta=6825.9,6830.4
XS Rating Curve= 0 ,0
Exp/Cntr=0.3,0.1

Type RM Length L Ch R = 1 ,5924    ,235,235,235
BEGIN DESCRIPTION:
Mapping XS 6f7d5600
END DESCRIPTION:
XS GIS Cut Line= 4
      2730231.64      6906413.75       2729176.1      6906365.14
      2728428.98      6906366.82      2728285.67      6906456.97
#Sta/Elev= 30
  3943.2  427.42    4049  427.85    4069  426.97  4259.2  426.09  4339.3  427.17
  4529.5  425.67  4589.5  424.66  4649.6  420.64  4719.7  421.04  4849.8  415.82
    4978  416.37    4990  415.18  4995.2   412.3  4995.6   411.8  4999.7   412.3
    5030  416.51    5060  415.36    5220  416.54    5340  419.08  5379.4   421.7
  5384.4  425.08    5390  425.66    5490  428.87    5530  428.27    5570  425.59
    5600  424.67    5720  424.06    5740  425.34  5873.2  424.04  5916.3  424.02
#Mann= 4 ,-1 , 0
  3943.2     .05       0  4995.2     .04       0  4999.7     .05       0
  5873.2     .12       0
Bank Sta=4995.2,4999.7
XS Rating Curve= 0 ,0
Exp/Cntr=0.3,0.1

Type RM Length L Ch R = 1 ,5689    ,906,906,906
BEGIN DESCRIPTION:
Mapping XS cc2dd1f2
END DESCRIPTION:
XS GIS Cut Line= 3
      2730001.04        6906186.      2729225.48      6906145.78
      2728270.09      6906150.26
#Sta/Elev= 30
  4223.4  426.15  4358.6  423.93  4425.4  424.59  4478.8  425.83  4578.9  424.09
  4611.8  424.59    4669  423.04  4719.1  423.56  4803.5  421.14  4849.3   413.1
  4869.3  412.12  4959.4  411.61  4989.5  413.05  5009.5  413.07  5017.2  408.33
  5017.7  407.83  5021.7  408.33  5029.5  412.16  5039.5  412.93  5059.5  412.66
  5069.5  411.37  5109.5  412.89  5129.5  412.36  5189.5  412.73  5229.5  414.72
  5260.3  415.07  5379.5  419.82  5519.5  423.15  5759.5  423.63  5955.4  421.76
#Mann= 5 ,-1 , 0
  4223.4     .05       0  4425.4     .12       0  5017.2     .07       0
  5021.7     .12       0  5260.3      .1       0
Bank Sta=5017.2,5021.7
XS Rating Curve= 0 ,0
Exp/Cntr=0.3,0.1

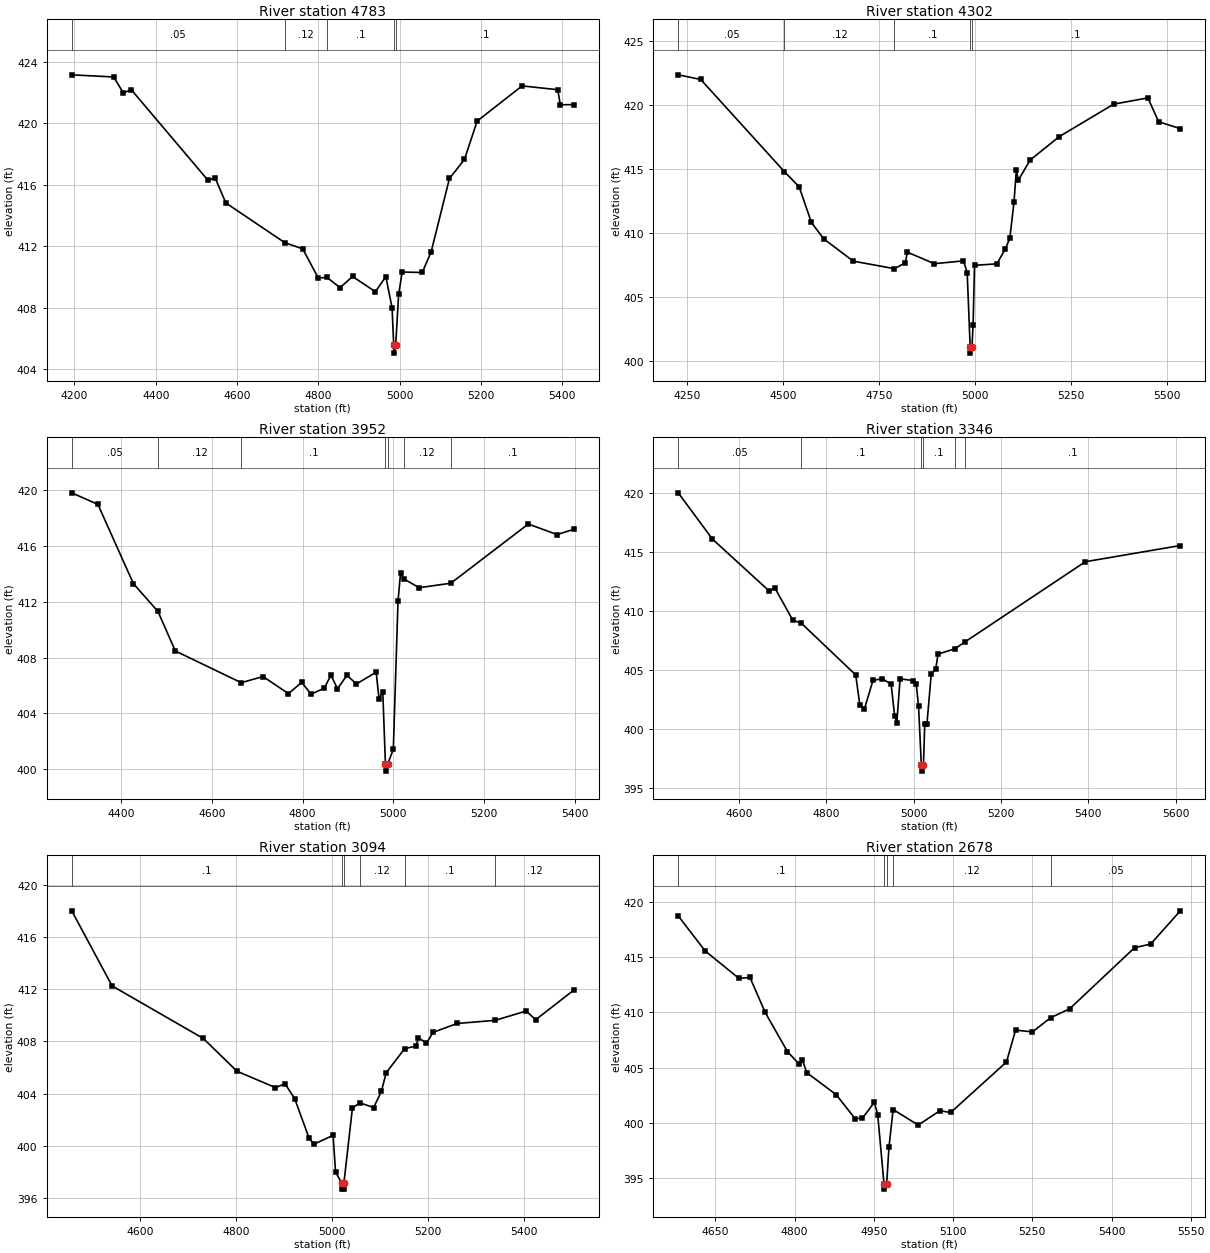
Type RM Length L Ch R = 1 ,4783    ,481,481,481
BEGIN DESCRIPTION:
Mapping XS 9ad420b2
END DESCRIPTION:
XS GIS Cut Line= 3
      2729569.86      6905433.16      2728792.97      6905606.76
      2728406.71      6905815.08
#Sta/Elev= 30
  4193.4  423.15  4296.4  423.01  4320.3  421.97  4339.8  422.18  4528.9  416.27
  4545.7  416.46  4572.3  414.81  4717.4  412.22  4761.4  411.82  4799.7  409.92
  4821.1  409.96  4853.3  409.29  4883.9  410.02  4940.2  409.03  4965.9  410.01
  4981.2  407.98  4985.3  405.53  4985.8  405.03    4990  405.53  4997.4  408.85
    5006  410.31  5055.4  410.28  5077.3  411.62  5122.3   416.4  5159.2  417.64
  5190.5  420.14  5301.1  422.43  5388.7  422.18    5395   421.2  5428.3  421.21
#Mann= 5 ,-1 , 0
  4193.4     .05       0  4717.4     .12       0  4821.1      .1       0
  4985.3     .07       0    4990      .1       0
Bank Sta=4985.3,4990
XS Rating Curve= 0 ,0
Exp/Cntr=0.3,0.1

Type RM Length L Ch R = 1 ,4302    ,350,350,350
BEGIN DESCRIPTION:
Mapping XS 6b360f55
END DESCRIPTION:
XS GIS Cut Line= 4
      2729300.79      6905027.77      2728575.09       6905298.6
      2728470.93      6905350.69      2728283.43       6905722.2
#Sta/Elev= 30
  4227.5  422.36    4286     422    4504   414.8  4542.3  413.62  4574.2  410.84
  4606.2  409.56  4683.1  407.82  4790.3  407.23  4818.7  407.69    4824  408.52
  4894.4  407.62  4970.2  407.84  4979.8  406.93  4987.5  401.14    4988  400.64
  4992.3  401.14  4995.2  402.86  4998.9  407.49    5057  407.61  5079.3  408.78
  5090.9  409.62  5101.7  412.43  5107.7   414.9  5113.3  414.15  5143.7  415.71
  5219.7  417.54  5361.1  420.07  5450.3  420.56  5478.2   418.7  5534.7  418.16
#Mann= 5 ,-1 , 0
  4227.5     .05       0    4504     .12       0  4790.3      .1       0
  4987.5     .07       0  4992.3      .1       0
Bank Sta=4987.5,4992.3
XS Rating Curve= 0 ,0
Exp/Cntr=0.3,0.1

Type RM Length L Ch R = 1 ,3952    ,606,606,606
BEGIN DESCRIPTION:
Mapping XS cad1196a
END DESCRIPTION:
XS GIS Cut Line= 3
      2728767.79      6904542.54      2728348.53      6905097.22
      2728247.26      6905497.09
#Sta/Elev= 30
  4290.7  419.77  4348.4  418.94  4426.7  413.28  4480.9  411.29  4519.1  408.47
  4664.6   406.2  4712.6  406.64  4768.8  405.42    4798  406.22  4818.8  405.38
  4847.9  405.81  4862.5  406.73    4877  405.77  4897.9  406.73  4918.7  406.11
  4962.4  406.95  4968.6  405.06  4976.9  405.56  4982.8  400.38  4983.4  399.88
  4987.6  400.38  5000.2  401.45  5010.5  412.01  5016.2  414.07  5022.7  413.63
  5057.2  412.99  5127.1  413.31    5298  417.54  5361.3  416.79  5398.5  417.16
#Mann= 7 ,-1 , 0
  4290.7     .05       0  4480.9     .12       0  4664.6      .1       0
  4982.8     .07       0  4987.6      .1       0  5022.7     .12       0
  5127.1      .1       0
Bank Sta=4982.8,4987.6
XS Rating Curve= 0 ,0
Exp/Cntr=0.3,0.1

Type RM Length L Ch R = 1 ,3346    ,252,252,252
BEGIN DESCRIPTION:
Mapping XS 4b6f50fc
END DESCRIPTION:
XS GIS Cut Line= 3
      2728224.41      6904234.33      2728107.21      6904786.45
      2728180.05      6905366.58
#Sta/Elev= 30
  4461.3  420.01  4539.7  416.09  4668.9  411.72  4682.8  411.94  4723.7  409.22
  4742.3     409  4867.5   404.6    4877  402.04  4887.3   401.7  4906.9  404.13
  4928.1  404.29  4948.6  403.81  4956.5  401.16  4961.6  400.55    4969  404.27
  4999.7  404.12  5006.1   403.8  5011.3  401.97  5017.7  396.96  5018.3  396.46
  5022.5  396.96  5025.5  400.44  5030.5  400.44  5040.4   404.7  5050.5  405.06
  5055.8  406.36  5094.1  406.81  5117.4  407.39  5393.1  414.18  5610.4  415.55
#Mann= 6 ,-1 , 0
  4461.3     .05       0  4742.3      .1       0  5017.7     .07       0
  5022.5      .1       0  5094.1     .12       0  5117.4      .1       0
Bank Sta=5017.7,5022.5
XS Rating Curve= 0 ,0
Exp/Cntr=0.3,0.1

Type RM Length L Ch R = 1 ,3094    ,416,416,416
BEGIN DESCRIPTION:
Mapping XS 6bcccd8e
END DESCRIPTION:
XS GIS Cut Line= 6
      2727910.45       6904137.1      2727893.09      6904686.19
      2727906.11      6904814.23      2727864.88      6904924.91
      2727841.01      6905003.03      2727827.98      6905170.16
#Sta/Elev= 30
  4458.5     418  4542.4  412.25  4732.5  408.22  4802.6  405.71  4882.6  404.46
  4902.6  404.75  4922.6  403.62  4952.6  400.59  4962.7  400.12  5002.7   400.8
  5007.8  397.98  5020.2  397.18  5020.9  396.68  5024.7  396.68  5025.3  397.18
  5042.9  402.89  5058.5  403.29  5087.1  402.93  5103.2  404.16  5113.2  405.59
  5151.6  407.44  5175.2  407.64  5180.5  408.28  5197.1  407.86  5210.8  408.69
    5261  409.37  5340.1  409.61  5404.5  410.32  5424.6  409.66    5504  411.93
#Mann= 6 ,-1 , 0
  4458.5      .1       0  5020.2     .07       0  5025.3      .1       0
  5058.5     .12       0  5151.6      .1       0  5340.1     .12       0
Bank Sta=5020.2,5025.3
XS Rating Curve= 0 ,0
Exp/Cntr=0.3,0.1

Type RM Length L Ch R = 1 ,2678    ,571,571,571
BEGIN DESCRIPTION:
Mapping XS 4a06534c
END DESCRIPTION:
XS GIS Cut Line= 3
      2727825.79      6904119.81      2727563.23      6904447.48
      2727450.93      6904965.76
#Sta/Elev= 30
  4579.9  418.76  4630.9  415.58  4694.9  413.09  4715.7  413.18  4744.5     410
  4786.5  406.46  4808.6  405.32    4815  405.68    4823  404.55    4879  402.54
  4914.6  400.37  4928.6  400.42    4951  401.85  4957.4  400.74  4969.3  394.48
  4969.9  393.98  4974.4  394.48  4978.7  397.78  4986.6   401.2  5034.1  399.79
    5075  401.09  5095.5  400.93  5201.1  405.51  5218.3   408.4  5250.3  408.24
  5285.1  409.54  5320.6  410.33  5443.4  415.87  5474.1  416.21  5530.1  419.22
#Mann= 5 ,-1 , 0
  4579.9      .1       0  4969.3     .07       0  4974.4      .1       0
  4986.6     .12       0  5285.1     .05       0
Bank Sta=4969.3,4974.4
XS Rating Curve= 0 ,0
Exp/Cntr=0.3,0.1