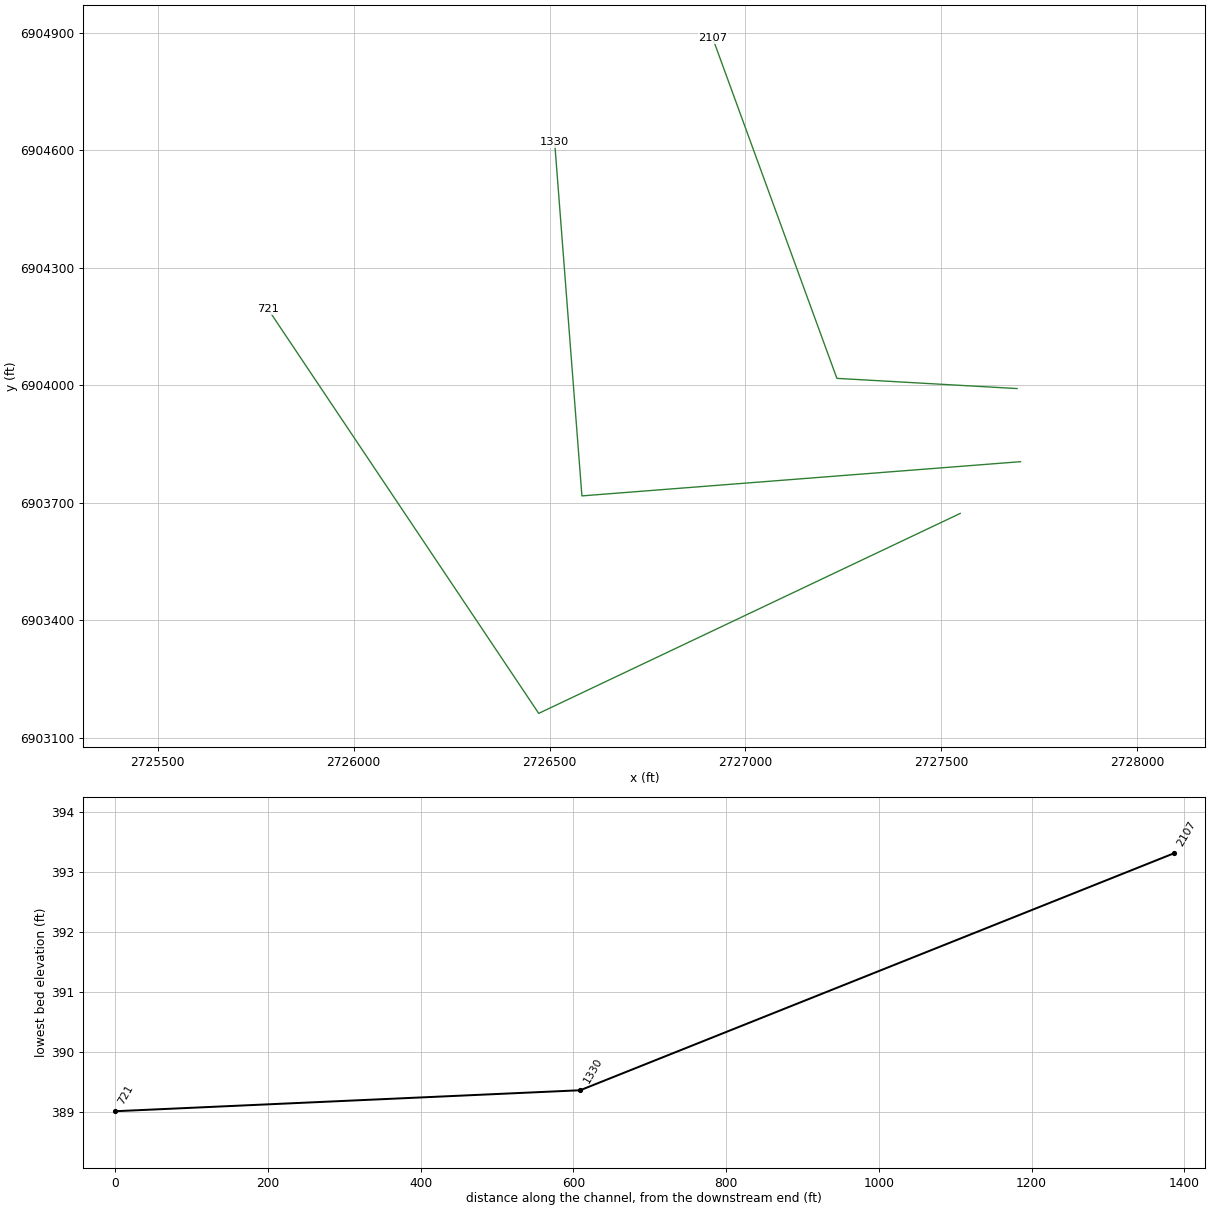
HEC-RAS study Caney T3.prj: Caney T3 Base Level Engineering

--- Caney T3.g01 (geometry) --- (continued)

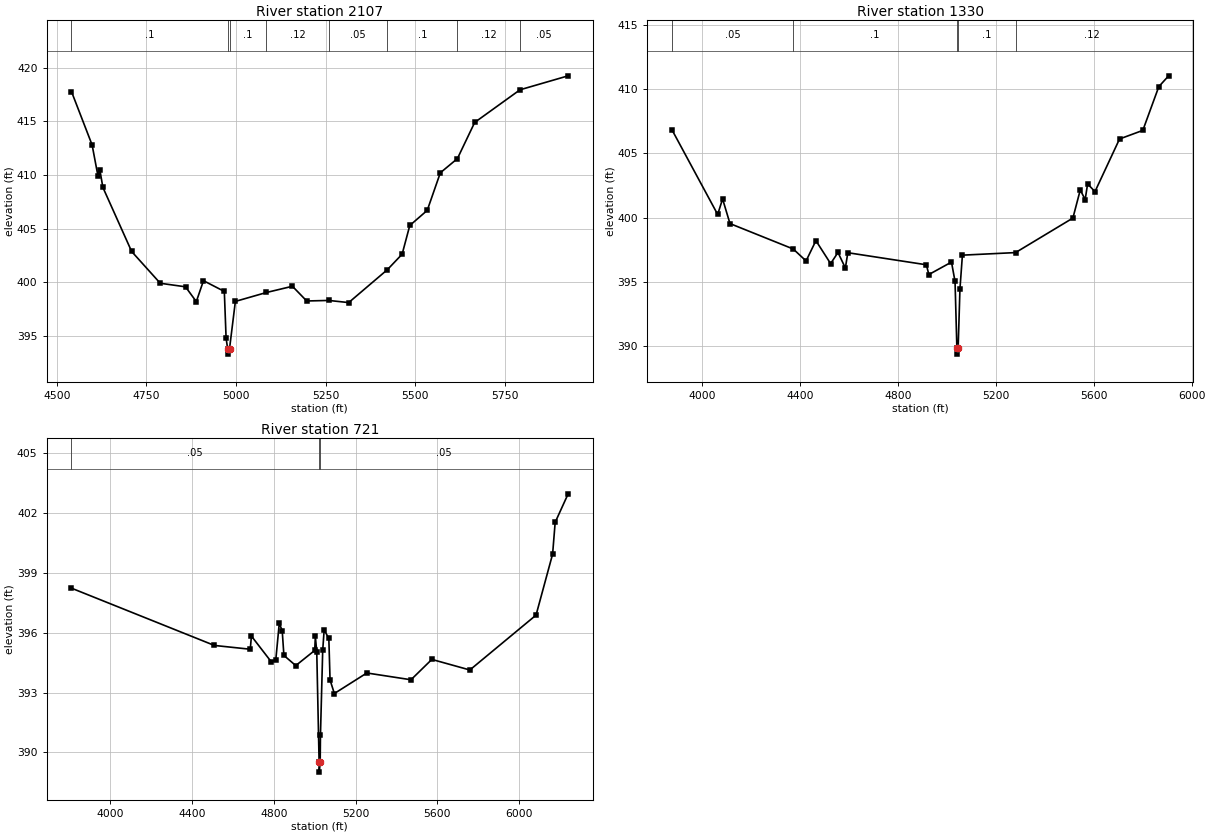
Type RM Length L Ch R = 1 ,2107    ,777,777,777
BEGIN DESCRIPTION:
Mapping XS db83b59a
END DESCRIPTION:
XS GIS Cut Line= 3
       2727693.4      6903991.75      2727233.37      6904017.79
      2726916.54      6904885.81
#Sta/Elev= 30
  4541.3  417.76  4598.8  412.79  4615.2  409.88  4620.2   410.5  4628.8  408.84
    4709  402.87  4788.8  399.91  4859.2  399.58  4889.3   398.2  4909.3  400.15
  4967.4  399.15  4972.4  394.77  4976.8  393.81  4977.5  393.31  4981.9  393.81
  4998.2  398.22  5084.8  399.05  5157.3  399.63  5197.1  398.26  5258.8  398.31
  5314.2  398.11  5422.2  401.18  5463.2  402.62  5484.5  405.29  5533.2   406.7
  5569.7   410.2  5617.3  411.52  5665.5  414.89  5791.9  417.93  5926.1  419.23
#Mann= 8 ,-1 , 0
  4541.3      .1       0  4976.8     .07       0  4981.9      .1       0
  5084.8     .12       0  5258.8     .05       0  5422.2      .1       0
  5617.3     .12       0  5791.9     .05       0
Bank Sta=4976.8,4981.9
XS Rating Curve= 0 ,0
Exp/Cntr=0.3,0.1

Type RM Length L Ch R = 1 ,1330    ,609,609,609
BEGIN DESCRIPTION:
Caney T3 2.0
END DESCRIPTION:
XS GIS Cut Line= 3
      2727702.08      6903805.11      2726582.48      6903717.76
      2726512.88      6904621.08
#Sta/Elev= 30
    3877  406.83  4063.6  400.24  4083.7  401.45  4113.8  399.53  4372.2  397.55
  4424.7  396.62  4464.9   398.2    4525  396.41  4555.1  397.28  4585.2  396.07
  4595.3  397.26  4916.2  396.32  4926.3  395.56  5018.8  396.53  5033.3  395.02
  5040.8  389.86  5041.5  389.36    5046  389.86  5053.4  394.45  5063.4  397.07
  5280.5  397.27  5514.8  399.96  5544.9  402.15  5564.9   401.4  5574.9  402.62
    5605  402.02  5705.3  406.12  5800.5  406.79  5865.8   410.2    5906  411.04
#Mann= 5 ,-1 , 0
    3877     .05       0  4372.2      .1       0  5040.8     .07       0
    5046      .1       0  5280.5     .12       0
Bank Sta=5040.8,5046
XS Rating Curve= 0 ,0
Exp/Cntr=0.3,0.1

Type RM Length L Ch R = 1 ,721     ,0,0,0
BEGIN DESCRIPTION:
Caney T3 1.0
END DESCRIPTION:
XS GIS Cut Line= 3
      2727548.19      6903672.98      2726472.22      6903162.57
      2725781.71      6904193.84
#Sta/Elev= 30
  3809.1  398.23  4508.8  395.36  4684.5  395.17  4690.1  395.83  4786.5  394.55
  4809.3  394.62  4826.5  396.47  4840.9   396.1  4849.2  394.86  4907.3  394.35
    5000  395.11  5003.2  395.81  5010.1  395.03  5021.6  389.51  5022.3  389.01
  5026.8  389.51  5028.2  390.87  5039.2  395.11  5046.3  396.14  5069.2  395.71
  5075.2  393.63  5096.2  392.95  5255.3  393.98  5471.5  393.64  5573.6  394.66
  5759.7  394.13  6083.9  396.88    6165  399.94  6177.5  401.53  6241.1  402.96
#Mann= 3 ,-1 , 0
  3809.1     .05       0  5021.6     .04       0  5026.8     .05       0
Bank Sta=5021.6,5026.8
XS Rating Curve= 0 ,0
Exp/Cntr=0.3,0.1

Chan Stop Cuts=-1
Use User Specified Reach Order=0
Composite Channel Slope=5