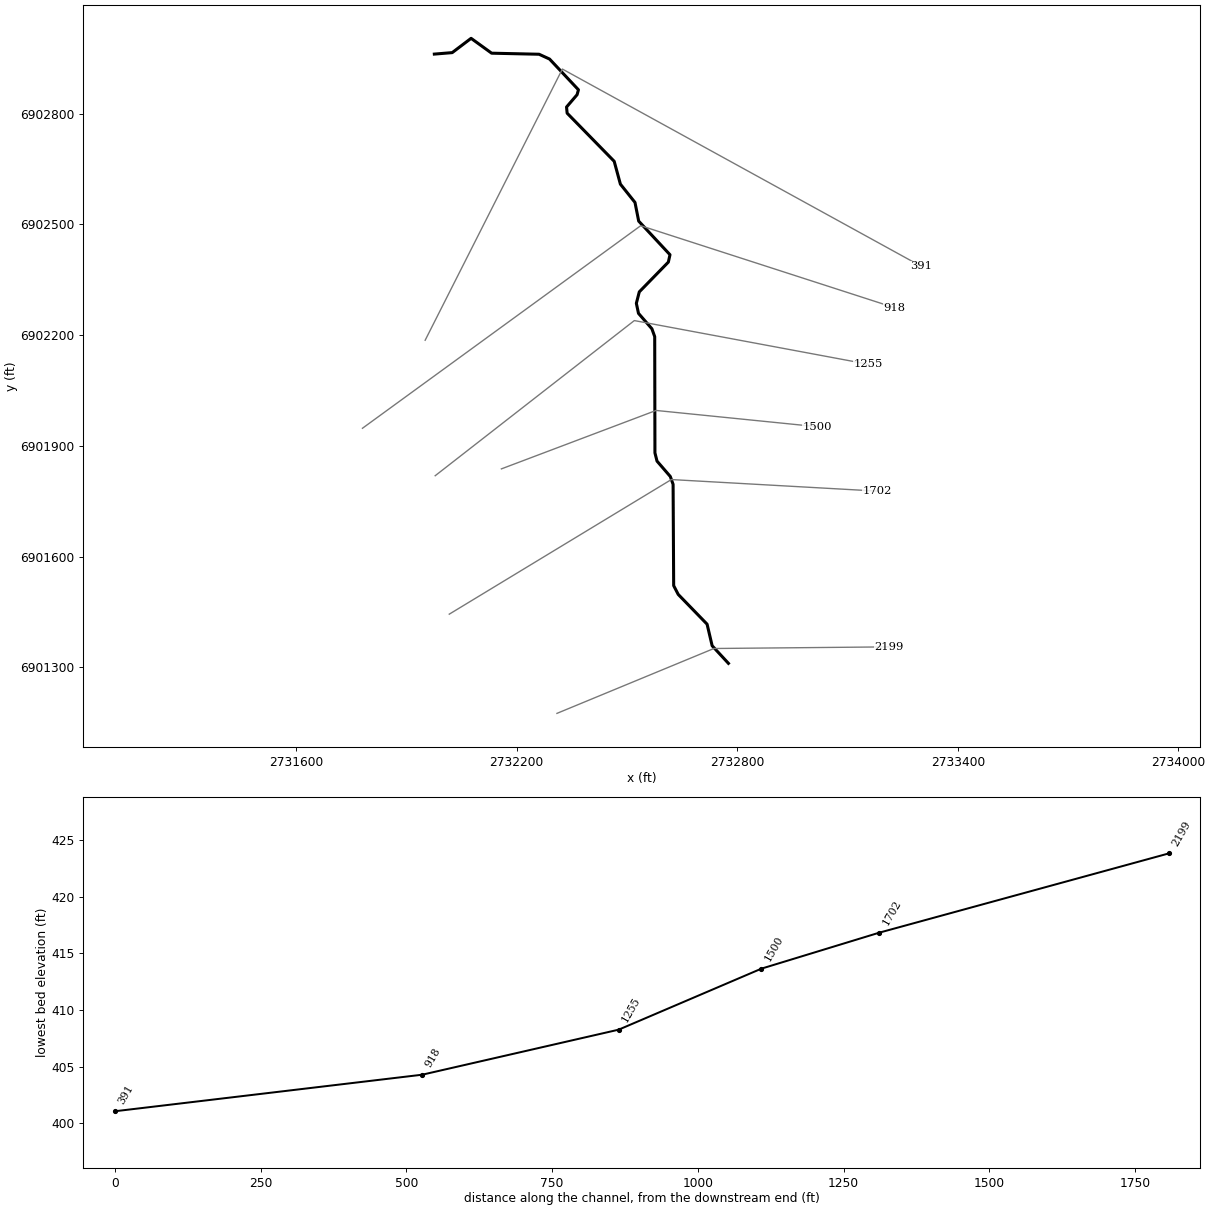
--- Caney T4.prj (project) ---

Proj Title=Caney T4 Base Level Engineering
Current Plan=p01
Default Exp/Contr=0.3,0.1
English Units
Geom File=g01
Flow File=f01
Plan File=p01
Y Axis Title=Elevation
X Axis Title(PF)=Main Channel Distance
X Axis Title(XS)=Station
BEGIN DESCRIPTION:
Caney T4
END DESCRIPTION:
DSS Export Rating Curves= 0
DSS Export Rating Curve Sorted= 0
DSS Export Volume Flow Curves= 0
DXF OffsetX= 0
DXF OffsetY= 0
DXF ScaleX= 1
DXF ScaleY= 10

--- Caney T4.p01 (plan) ---

Plan Title=Multiple Run
Short Identifier=Multiple
Geom File=g01
Flow File=f01
Subcritical Flow
K Sum by GR= 0
Std Step Tol= 0.01
Critical Tol= 0.01
Num of Std Step Trials= 20
Max Error Tol= 0.3
Flow Tol Ratio= 0.001
Split Flow NTrial= 30
Split Flow Tol= 0.02
Split Flow Ratio= 0.02
Log Output Level= 0
Friction Slope Method= 1
Unsteady Friction Slope Method= 2
Unsteady Bridges Friction Slope Method= 1
Parabolic Critical Depth
Global Vel Dist=  1 , 1 , 1
Global Log Level= 0
CheckData=True
Encroach Param= -1, 0, 0, 0
BEGIN DESCRIPTION:
Multiple Run
END DESCRIPTION:

--- Caney T4.f01 (steady flow) ---

Flow Title=Multiple
Program Version=4.10
Number of Profiles= 7
Profile Names=10-year,25-year,50-year,1pct_min,100-year,1pct_plu,500-year
River Rch & RM=Caney T4,Reach-1         ,2199
     151     184     209     118     236     471     299
Boundary for River Rch & Prof#=Caney T4,Reach-1         , 1
Up Type= 0
Dn Type= 3
Dn Slope=0.005
Boundary for River Rch & Prof#=Caney T4,Reach-1         , 2
Up Type= 0
Dn Type= 3
Dn Slope=0.005
Boundary for River Rch & Prof#=Caney T4,Reach-1         , 3
Up Type= 0
Dn Type= 3
Dn Slope=0.005
Boundary for River Rch & Prof#=Caney T4,Reach-1         , 4
Up Type= 0
Dn Type= 3
Dn Slope=0.005
Boundary for River Rch & Prof#=Caney T4,Reach-1         , 5
Up Type= 0
Dn Type= 3
Dn Slope=0.005
Boundary for River Rch & Prof#=Caney T4,Reach-1         , 6
Up Type= 0
Dn Type= 3
Dn Slope=0.005
Boundary for River Rch & Prof#=Caney T4,Reach-1         , 7
Up Type= 0
Dn Type= 3
Dn Slope=0.005
DSS Import GetInterval= 0
DSS Import GetPeak= 0
DSS Import FillOption= 0

--- Caney T4.g01 (geometry) ---

Geom Title=Existing Conditions

River Reach=Caney T4,Reach-1
Reach XY= 30
      2732776.00      6901311.00      2732731.70      6901358.65
      2732717.93      6901417.08      2732639.40      6901497.69
      2732627.05      6901521.44      2732625.48      6901795.78
      2732617.86      6901817.06      2732581.75      6901858.67
      2732576.07      6901881.03      2732575.46      6902195.79
      2732567.81      6902217.08      2732531.35      6902258.83
      2732525.51      6902286.04      2732533.52      6902317.06
      2732612.56      6902397.68      2732617.02      6902417.66
      2732531.86      6902508.70      2732521.81      6902559.26
      2732482.10      6902608.81      2732465.23      6902670.68
      2732337.24      6902801.00      2732335.62      6902817.67
      2732364.30      6902851.01      2732368.00      6902864.35
      2732289.37      6902947.63      2732260.85      6902960.60
      2732131.86      6902963.46      2732075.96      6903003.69
      2732024.64      6902965.00      2731976.00      6902961.00

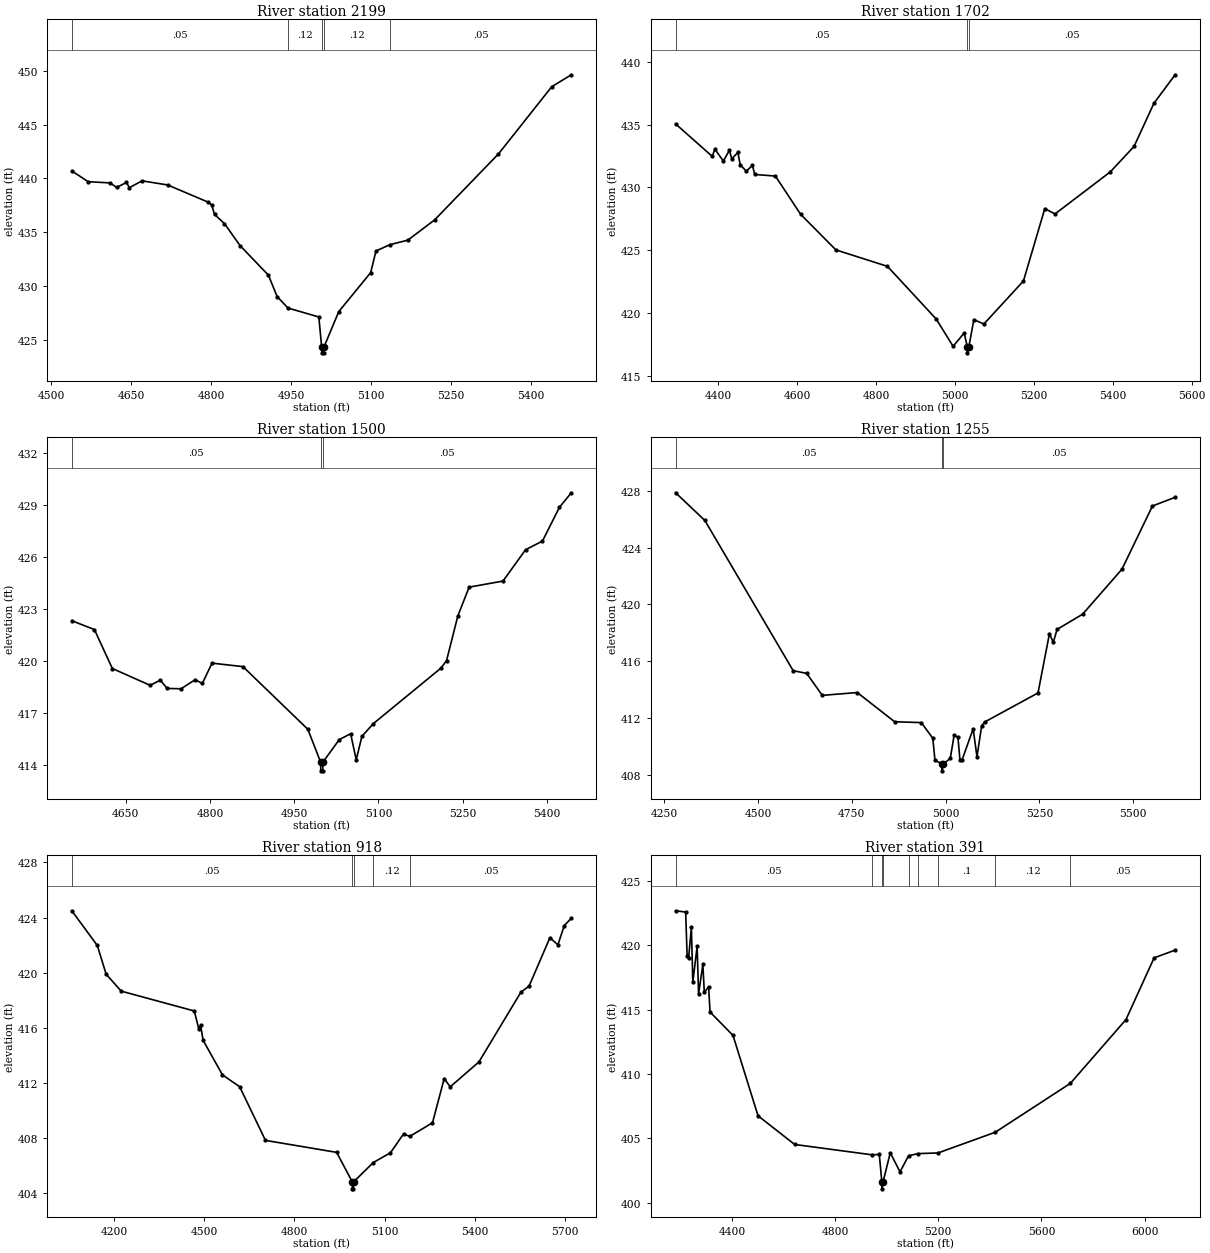
Type RM Length L Ch R = 1,2199,497,497,497
BEGIN DESCRIPTION:
Caney T4 2.0
END DESCRIPTION:
XS GIS Cut Line= 3
      2732309.53      6901175.52      2732736.50      6901351.21
      2733212.78      6901355.63
#Sta/Elev= 30
  4538.3  440.69  4569.1  439.69  4610.2  439.58  4622.4  439.16  4640.9  439.62
  4646.3  439.14  4670.3  439.77  4718.2  439.39  4794.0  437.80  4800.9  437.54
  4806.3  436.65  4824.8  435.81  4854.2  433.76  4907.5  431.01  4923.8  429.03
  4944.2  427.96  5002.2  427.13  5007.5  424.30  5007.7  423.80  5011.2  423.80
  5011.5  424.30  5039.5  427.62  5099.5  431.25  5109.5  433.26  5135.5  433.84
  5169.5  434.27  5219.5  436.14  5339.5  442.27  5439.5  448.51  5476.3  449.62
#Mann=5,-1,0
  4538.3    0.05       0  4944.2    0.12       0  5007.5    0.07       0
  5011.5    0.12       0  5135.5    0.05       0
Bank Sta=5007.5,5011.5
Exp/Cntr=0.3,0.1

Type RM Length L Ch R = 1,1702,202,202,202
BEGIN DESCRIPTION:
Mapping XS 5c56e97b
END DESCRIPTION:
XS GIS Cut Line= 3
      2732016.57      6901444.19      2732620.72      6901808.77
      2733179.72      6901777.52
#Sta/Elev= 30
  4292.6  435.07  4385.4  432.48  4392.0  433.06  4413.4  432.11  4428.9  432.96
  4434.8  432.28  4450.3  432.80  4456.1  431.82  4471.6  431.30  4487.2  431.76
  4493.0  431.04  4545.4  430.91  4609.5  427.85  4698.7  425.02  4829.2  423.71
  4953.0  419.50  4995.6  417.33  5023.6  418.39  5031.6  417.31  5031.8  416.81
  5035.6  417.31  5048.2  419.46  5073.6  419.11  5173.8  422.54  5227.9  428.31
  5253.9  427.89  5394.1  431.25  5454.2  433.28  5504.3  436.71  5558.1  438.99
#Mann=3,-1,0
  4292.6    0.05       0  5031.6    0.05       0  5035.6    0.05       0
Bank Sta=5031.6,5035.6
Exp/Cntr=0.3,0.1

Type RM Length L Ch R = 1,1500,245,245,245
BEGIN DESCRIPTION:
Mapping XS a99d38a5
END DESCRIPTION:
XS GIS Cut Line= 3
      2732158.41      6901837.67      2732579.17      6901995.92
      2733017.13      6901951.95
#Sta/Elev= 30
  4553.9  422.31  4594.1  421.80  4626.1  419.55  4693.4  418.58  4711.6  418.88
  4723.6  418.40  4748.5  418.38  4773.4  418.90  4786.4  418.69  4803.6  419.86
  4858.7  419.66  4974.3  416.04  4997.1  414.14  4997.3  413.64  5000.8  413.64
  5001.1  414.14  5030.4  415.45  5050.5  415.78  5060.5  414.28  5070.6  415.63
  5090.7  416.36  5211.3  419.57  5221.4  420.01  5241.5  422.59  5261.6  424.25
  5321.9  424.60  5362.1  426.41  5392.2  426.91  5422.4  428.86  5443.6  429.70
#Mann=3,-1,0
  4553.9    0.05       0  4997.1    0.05       0  5001.1    0.05       0
Bank Sta=4997.1,5001.1
Exp/Cntr=0.3,0.1

Type RM Length L Ch R = 1,1255,337,337,337
BEGIN DESCRIPTION:
Mapping XS e3095da2
END DESCRIPTION:
XS GIS Cut Line= 3
      2731978.33      6901819.15      2732520.03      6902239.32
      2733155.40      6902121.27
#Sta/Elev= 30
  4280.1  427.86  4358.0  425.91  4593.5  415.32  4629.5  415.13  4671.2  413.58
  4764.4  413.78  4864.0  411.72  4935.2  411.66  4965.7  410.56  4971.7  408.99
  4990.1  408.76  4990.3  408.26  4994.1  408.76  5012.4  409.13  5022.6  410.76
  5032.8  410.63  5038.2  409.04  5043.3  408.99  5073.4  411.22  5083.6  409.25
  5096.1  411.43  5104.0  411.70  5246.3  413.75  5276.9  417.94  5287.0  417.31
  5297.2  418.23  5365.2  419.30  5470.1  422.47  5551.5  426.93  5611.9  427.54
#Mann=3,-1,0
  4280.1    0.05       0  4990.1    0.05       0  4994.1    0.05       0
Bank Sta=4990.1,4994.1
Exp/Cntr=0.3,0.1

Type RM Length L Ch R = 1,918,527,527,527
BEGIN DESCRIPTION:
Mapping XS 474b693f
END DESCRIPTION:
XS GIS Cut Line= 3
      2731780.48      6901947.68      2732537.39      6902496.27
      2733228.33      6902274.05
#Sta/Elev= 30
  4059.9  424.49  4144.6  421.97  4174.0  419.88  4224.3  418.65  4467.1  417.21
  4481.7  415.93  4487.9  416.17  4496.4  415.08  4560.7  412.57  4617.8  411.71
  4703.7  407.81  4940.3  406.94  4992.5  404.79  4992.7  404.29  4996.2  404.29
  4996.5  404.79  5062.2  406.20  5119.3  406.91  5162.7  408.28  5183.5  408.10
  5259.0  409.09  5297.9  412.30  5317.9  411.70  5413.4  413.51  5553.0  418.58
  5579.9  419.01  5649.3  422.53  5676.0  422.02  5697.0  423.41  5720.5  423.95
#Mann=5,-1,0
  4059.9    0.05       0  4992.5    0.05       0  4996.5    0.05       0
  5062.2    0.12       0  5183.5    0.05       0
Bank Sta=4992.5,4996.5
Exp/Cntr=0.3,0.1

Type RM Length L Ch R = 1,391,0,0,0
BEGIN DESCRIPTION:
Caney T4 1.0
END DESCRIPTION:
XS GIS Cut Line= 3
      2731951.02      6902186.04      2732324.26      6902920.55
      2733300.96      6902386.02
#Sta/Elev= 30
  4181.3  422.69  4220.2  422.59  4225.8  419.20  4231.7  419.03  4242.4  421.40
  4248.0  417.15  4264.7  419.92  4270.3  416.22  4286.9  418.52  4292.5  416.34
  4309.2  416.78  4314.8  414.82  4403.8  413.00  4500.9  406.75  4643.0  404.52
  4941.5  403.72  4971.2  403.74  4981.3  401.57  4981.5  401.07  4985.3  401.57
  5013.8  403.87  5051.7  402.39  5084.6  403.64  5121.6  403.81  5199.0  403.86
  5421.0  405.47  5712.3  409.27  5928.0  414.23  6037.1  419.03  6118.6  419.63
#Mann=9,-1,0
  4181.3    0.05       0  4941.5    0.12       0  4981.3    0.07       0
  4985.3    0.12       0  5084.6     0.1       0  5121.6    0.12       0
  5199.0     0.1       0  5421.0    0.12       0  5712.3    0.05       0
Bank Sta=4981.3,4985.3
Exp/Cntr=0.3,0.1

Chan Stop Cuts=-1