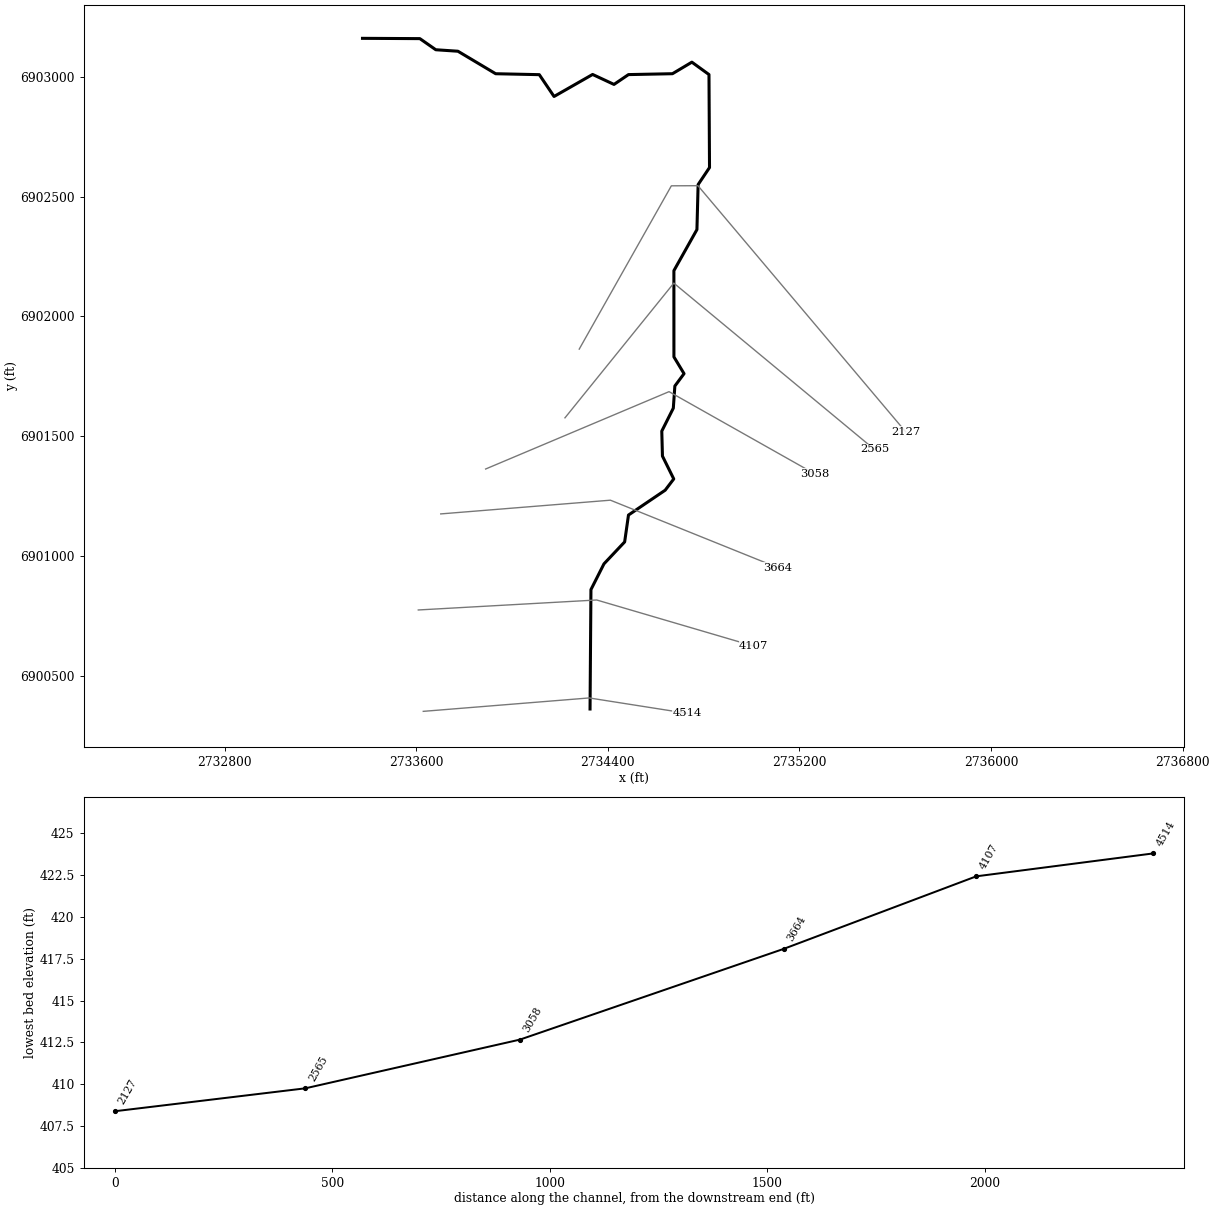
--- Caney T5.prj (project) ---

Proj Title=Caney T5 Base Level Engineering
Current Plan=p01
Default Exp/Contr=0.3,0.1
English Units
Geom File=g01
Flow File=f01
Plan File=p01
Y Axis Title=Elevation
X Axis Title(PF)=Main Channel Distance
X Axis Title(XS)=Station
BEGIN DESCRIPTION:
Caney T5
END DESCRIPTION:
DSS Export Rating Curves= 0
DSS Export Rating Curve Sorted= 0
DSS Export Volume Flow Curves= 0
DXF OffsetX= 0
DXF OffsetY= 0
DXF ScaleX= 1
DXF ScaleY= 10

--- Caney T5.p01 (plan) ---

Plan Title=Multiple Run
Short Identifier=Multiple
Geom File=g01
Flow File=f01
Subcritical Flow
K Sum by GR= 0
Std Step Tol= 0.01
Critical Tol= 0.01
Num of Std Step Trials= 20
Max Error Tol= 0.3
Flow Tol Ratio= 0.001
Split Flow NTrial= 30
Split Flow Tol= 0.02
Split Flow Ratio= 0.02
Log Output Level= 0
Friction Slope Method= 1
Unsteady Friction Slope Method= 2
Unsteady Bridges Friction Slope Method= 1
Parabolic Critical Depth
Global Vel Dist=  1 , 1 , 1
Global Log Level= 0
CheckData=True
Encroach Param= -1, 0, 0, 0
BEGIN DESCRIPTION:
Multiple Run
END DESCRIPTION:

--- Caney T5.f01 (steady flow) ---

Flow Title=Multiple
Number of Profiles=7
Profile Names=10-year,25-year,50-year,1pct_min,100-year,1pct_plu,500-year
River Rch & RM= Caney T5,Reach-1,4514
     391     508     599     352     703    1402     962
Boundary for River Rch & Prof#=Caney T5,Reach-1,1
Up Type=0
Dn Type=3
Dn Slope=0.005
Boundary for River Rch & Prof#=Caney T5,Reach-1,2
Up Type=0
Dn Type=3
Dn Slope=0.005
Boundary for River Rch & Prof#=Caney T5,Reach-1,3
Up Type=0
Dn Type=3
Dn Slope=0.005
Boundary for River Rch & Prof#=Caney T5,Reach-1,4
Up Type=0
Dn Type=3
Dn Slope=0.005
Boundary for River Rch & Prof#=Caney T5,Reach-1,5
Up Type=0
Dn Type=3
Dn Slope=0.005
Boundary for River Rch & Prof#=Caney T5,Reach-1,6
Up Type=0
Dn Type=3
Dn Slope=0.005
Boundary for River Rch & Prof#=Caney T5,Reach-1,7
Up Type=0
Dn Type=3
Dn Slope=0.005

--- Caney T5.g01 (geometry) ---

Geom Title=Existing Conditions
Program Version=4.10

River Reach=Caney T5        ,Reach-1
Reach XY= 30
        2734326.        6900361.      2734329.75      6900859.45
      2734384.16      6900967.05      2734470.46      6901058.58
      2734486.51      6901170.81       2734639.7      6901274.49
      2734675.47      6901321.47      2734628.28      6901416.93
       2734625.5      6901521.17      2734673.65      6901616.98
      2734680.09       6901709.5      2734718.44        6901761.
      2734676.18      6901830.98      2734676.06      6902190.97
      2734772.25      6902362.55      2734777.22      6902550.49
      2734824.78       6902621.5      2734822.55      6903009.81
      2734751.13      6903061.54      2734670.07      6903013.29
      2734486.44      6903009.62      2734425.99      6902968.59
       2734336.7       6903010.2      2734175.71      6902918.23
      2734114.17      6903009.34      2733931.93      6903013.24
      2733774.42      6903107.17      2733681.98      6903113.36
       2733615.5      6903159.78        2733376.        6903161.

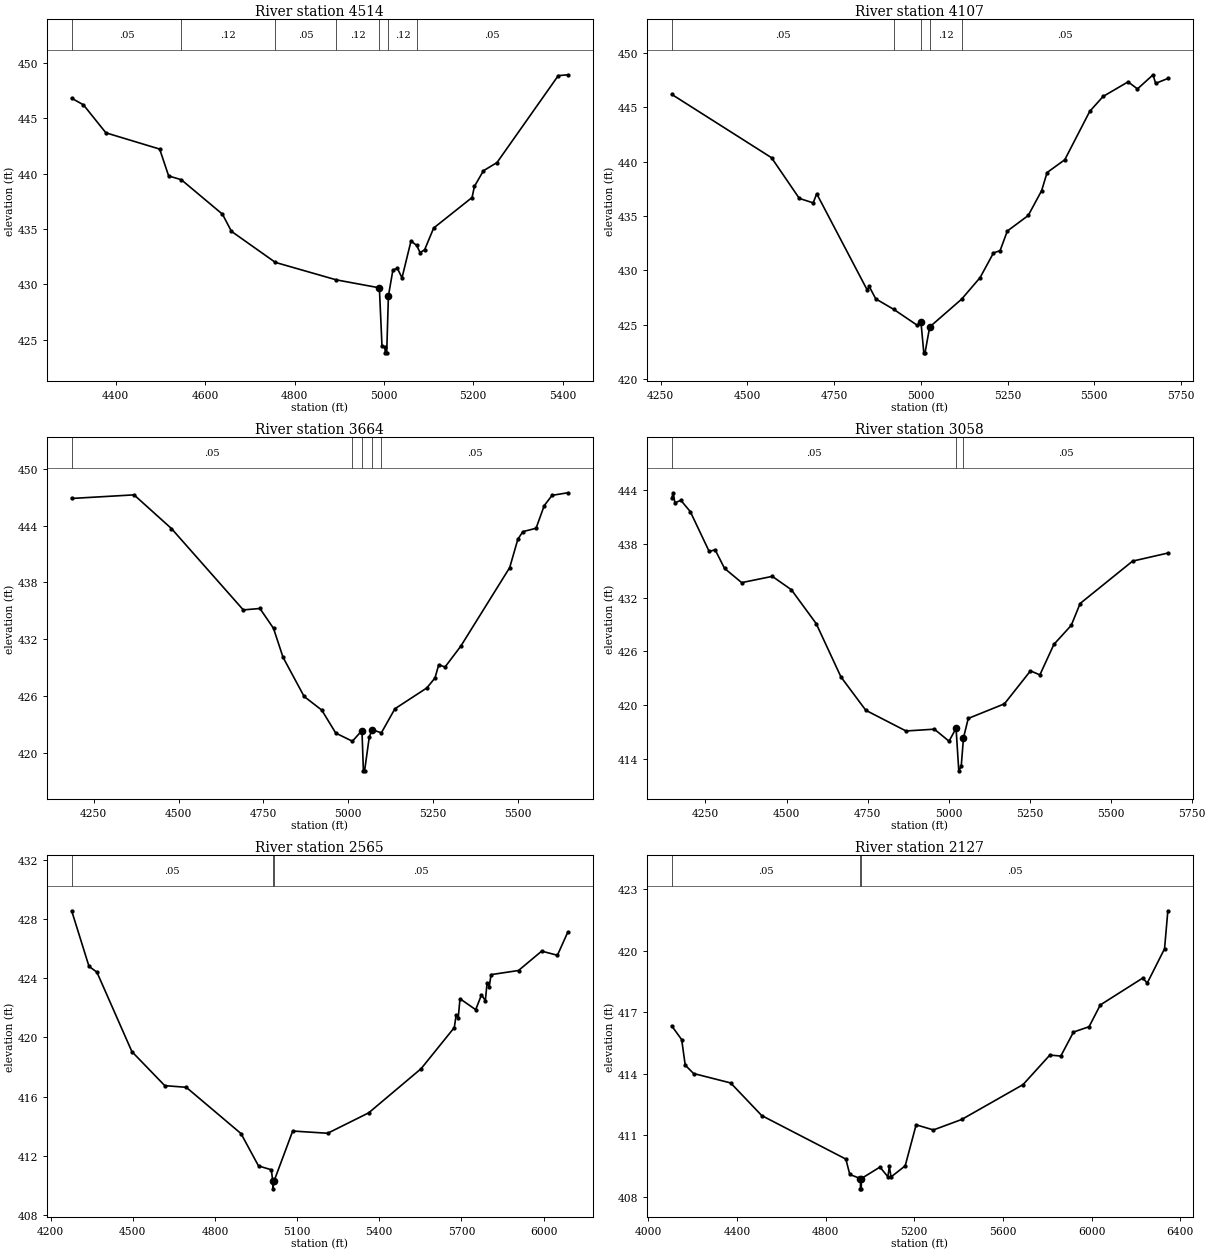
Type RM Length L Ch R = 1 ,4514    ,407,407,407
BEGIN DESCRIPTION:
Caney T5 3.0
END DESCRIPTION:
XS GIS Cut Line= 3
       2733629.7      6900351.19      2734322.53      6900407.18
      2734732.41      6900342.75
#Sta/Elev= 30
  4301.4  446.83  4327.8  446.23    4378   443.7  4498.3  442.23  4518.4   439.8
  4546.7  439.46  4638.8  436.34  4658.9  434.79  4757.2  431.98  4893.6   430.4
  4989.9  429.68  4995.7  424.46  5002.6   424.3  5002.8   423.8  5006.3   423.8
  5010.1  428.94  5020.2   431.3  5030.4  431.43  5040.5  430.58  5060.7  433.92
  5073.4  433.51    5081  432.87  5091.1  433.12  5111.4  435.09  5197.3  437.85
  5202.5  438.85  5222.7  440.27  5253.1  441.01  5390.1  448.87  5411.4  448.95
#Mann= 7 ,-1 , 0
  4301.4     .05       0  4546.7     .12       0  4757.2     .05       0
  4893.6     .12       0  4989.9     .07       0  5010.1     .12       0
  5073.4     .05       0
Bank Sta=4989.9,5010.1
XS Rating Curve= 0 ,0
Exp/Cntr=0.3,0.1

Type RM Length L Ch R = 1 ,4107    ,443,443,443
BEGIN DESCRIPTION:
Mapping XS ed06908f
END DESCRIPTION:
XS GIS Cut Line= 3
      2733608.89      6900774.46       2734353.7      6900816.13
      2735009.92      6900623.43
#Sta/Elev= 30
  4282.2  446.18  4569.8  440.36  4649.9  436.62  4689.9  436.21    4700  437.05
    4846  428.18    4851  428.55  4870.2  427.39  4922.3  426.42  4990.4  424.95
  5000.4   425.3  5008.7  422.43  5012.2  422.43  5025.7  424.81  5117.6  427.36
  5170.9  429.34  5209.5  431.61  5228.6  431.82  5249.4  433.62  5309.7  435.05
  5348.3  437.33  5364.1     439    5415  440.17    5487  444.62  5525.6  445.99
  5597.5  447.33  5624.6  446.68  5669.5  447.98  5676.8  447.19  5712.1  447.64
#Mann= 5 ,-1 , 0
  4282.2     .05       0  4922.3     .12       0  5000.4     .07       0
  5025.7     .12       0  5117.6     .05       0
Bank Sta=5000.4,5025.7
XS Rating Curve= 0 ,0
Exp/Cntr=0.3,0.1

Type RM Length L Ch R = 1 ,3664    ,606,606,606
BEGIN DESCRIPTION:
Mapping XS 9bd96743
END DESCRIPTION:
XS GIS Cut Line= 3
      2733702.64       6901175.5      2734410.99      6901232.79
      2735108.89      6900951.55
#Sta/Elev= 30
  4184.8  446.88  4368.8  447.26  4479.1   443.7    4691   435.1    4740  435.25
  4780.1  433.15  4808.2  430.09  4870.4  425.95  4922.4  424.51  4963.7  422.08
  5012.7  421.22    5041  422.35  5045.2  418.09  5048.7  418.09  5062.6  421.68
  5071.1  422.43  5098.2  422.11  5138.1  424.65  5232.2  426.85  5256.4  427.91
  5267.4  429.31  5285.9  429.06  5332.1  431.25  5476.6  439.57  5500.7  442.57
  5515.4  443.37  5554.4  443.73  5578.6  446.13  5601.7  447.21  5647.9  447.48
#Mann= 5 ,-1 , 0
  4184.8     .05       0  5012.7     .12       0    5041     .04       0
  5071.1     .12       0  5098.2     .05       0
Bank Sta=5041,5071.1
XS Rating Curve= 0 ,0
Exp/Cntr=0.3,0.1

Type RM Length L Ch R = 1 ,3058    ,493,493,493
BEGIN DESCRIPTION:
Mapping XS e350c46b
END DESCRIPTION:
XS GIS Cut Line= 3
      2733890.12      6901362.99      2734655.78      6901685.92
      2735265.14      6901342.18
#Sta/Elev= 30
  4145.9  443.12  4150.3  443.71  4155.7  442.59    4174  442.87  4203.1  441.61
  4261.4  437.16  4279.7  437.35  4308.8  435.27  4361.7  433.68  4456.2  434.38
  4514.9  432.89  4591.5  429.11    4668  423.15  4744.6  419.43  4868.6  417.12
  4956.1  417.32  5001.4  415.98  5023.1  417.42  5031.5  412.67    5039  413.17
    5046  416.35  5060.7  418.52  5172.3  420.15  5252.7  423.83  5281.7  423.38
    5325  426.79  5378.5  428.91  5405.9  431.35  5567.7  436.08  5676.5  436.98
#Mann= 3 ,-1 , 0
  4145.9     .05       0  5023.1     .04       0    5046     .05       0
Bank Sta=5023.1,5046
XS Rating Curve= 0 ,0
Exp/Cntr=0.3,0.1

Type RM Length L Ch R = 1 ,2565    ,438,438,438
BEGIN DESCRIPTION:
Mapping XS 83bdb777
END DESCRIPTION:
XS GIS Cut Line= 3
      2734221.31      6901576.59      2734675.75      6902139.04
      2735513.43      6901444.59
#Sta/Elev= 30
  4276.9  428.57  4340.2  424.81    4369  424.42  4496.9  419.04  4616.9  416.74
  4695.2  416.63  4895.1   413.5  4959.1  411.31  5005.8  411.05  5011.3  410.26
  5011.6  409.76  5015.3  410.26  5083.9  413.67  5211.5  413.52  5361.3   414.9
  5552.8  417.89  5673.9  420.67  5680.4  421.49  5688.2  421.32  5694.7  422.62
    5752  421.88  5772.9  422.87  5787.2   422.5  5793.7  423.71  5801.5  423.43
    5808  424.25  5908.3  424.53  5992.9  425.84  6050.3  425.56  6088.1  427.12
#Mann= 3 ,-1 , 0
  4276.9     .05       0  5011.3     .04       0  5015.3     .05       0
Bank Sta=5011.3,5015.3
XS Rating Curve= 0 ,0
Exp/Cntr=0.3,0.1

Type RM Length L Ch R = 1 ,2127    ,0,0,0
BEGIN DESCRIPTION:
Mapping XS afb6886e
END DESCRIPTION:
XS GIS Cut Line= 4
      2734280.83      6901863.54      2734665.51      6902545.28
      2734776.52      6902545.78      2735643.63      6901518.39
#Sta/Elev= 30
  4106.2  416.33  4151.1  415.66    4167  414.42  4204.6  414.01  4372.1  413.55
  4512.2  411.96  4891.7  409.84  4909.5  409.09  4957.5  408.89  4957.7  408.39
  4961.2  408.39  4961.5  408.89  5045.5  409.45  5081.3  408.98  5087.9  409.48
  5095.6  408.97  5159.4  409.51  5208.8  411.51  5286.8  411.26  5414.3  411.77
  5691.2  413.47  5812.1  414.91  5861.5  414.86  5918.7  416.03    5989  416.29
  6039.6  417.35  6230.8  418.66  6251.6  418.42  6329.6  420.09  6344.4  421.94
#Mann= 3 ,-1 , 0
  4106.2     .05       0  4957.5     .04       0  4961.5     .05       0
Bank Sta=4957.5,4961.5
XS Rating Curve= 0 ,0
Exp/Cntr=0.3,0.1

Chan Stop Cuts=-1
Use User Specified Reach Order=0
Composite Channel Slope=5