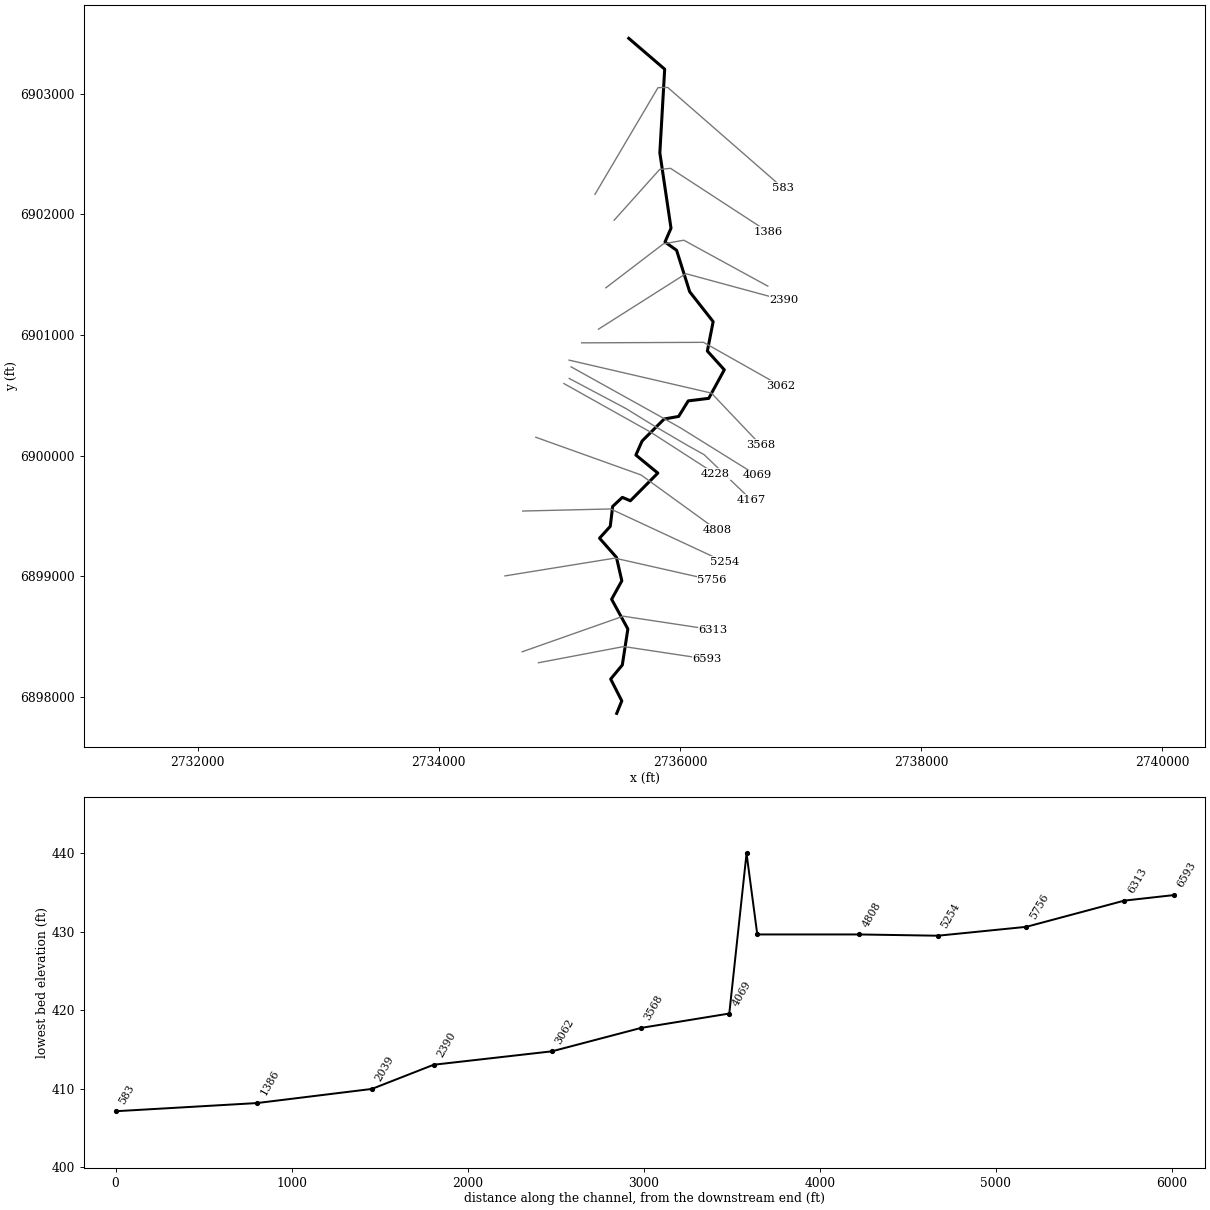
--- Caney T6.prj (project) ---

Proj Title=Caney T6 Base Level Engineering
Current Plan=p01
Default Exp/Contr=0.3,0.1
English Units
Geom File=g01
Flow File=f01
Plan File=p01
Y Axis Title=Elevation
X Axis Title(PF)=Main Channel Distance
X Axis Title(XS)=Station
BEGIN DESCRIPTION:
Caney T6
END DESCRIPTION:
DSS Export Rating Curves= 0
DSS Export Rating Curve Sorted= 0
DSS Export Volume Flow Curves= 0
DXF OffsetX= 0
DXF OffsetY= 0
DXF ScaleX= 1
DXF ScaleY= 10

--- Caney T6.p01 (plan) ---

Plan Title=Multiple Run
Short Identifier=Multiple
Geom File=g01
Flow File=f01
Subcritical Flow
K Sum by GR= 0
Std Step Tol= 0.01
Critical Tol= 0.01
Num of Std Step Trials= 20
Max Error Tol= 0.3
Flow Tol Ratio= 0.001
Split Flow NTrial= 30
Split Flow Tol= 0.02
Split Flow Ratio= 0.02
Log Output Level= 0
Friction Slope Method= 1
Unsteady Friction Slope Method= 2
Unsteady Bridges Friction Slope Method= 1
Parabolic Critical Depth
Global Vel Dist=  1 , 1 , 1
Global Log Level= 0
CheckData=True
Encroach Param= -1, 0, 0, 0
BEGIN DESCRIPTION:
Multiple Run
END DESCRIPTION:

--- Caney T6.f01 (steady flow) ---

Flow Title=Multiple
Number of Profiles=7
Profile Names=10-year,25-year,50-year,1pct_min,100-year,1pct_plu,500-year
River Rch & RM= Caney T6,Reach-1,6593
     597     796     957     571    1139    2272    1610
River Rch & RM= Caney T6,Reach-1,4069
     637     853    1028     615    1227    2449    1745
River Rch & RM= Caney T6,Reach-1,2390
     742    1002    1214     730    1456    2905    2092
Boundary for River Rch & Prof#=Caney T6,Reach-1,1
Up Type=0
Dn Type=3
Dn Slope=0.005
Boundary for River Rch & Prof#=Caney T6,Reach-1,2
Up Type=0
Dn Type=3
Dn Slope=0.005
Boundary for River Rch & Prof#=Caney T6,Reach-1,3
Up Type=0
Dn Type=3
Dn Slope=0.005
Boundary for River Rch & Prof#=Caney T6,Reach-1,4
Up Type=0
Dn Type=3
Dn Slope=0.005
Boundary for River Rch & Prof#=Caney T6,Reach-1,5
Up Type=0
Dn Type=3
Dn Slope=0.005
Boundary for River Rch & Prof#=Caney T6,Reach-1,6
Up Type=0
Dn Type=3
Dn Slope=0.005
Boundary for River Rch & Prof#=Caney T6,Reach-1,7
Up Type=0
Dn Type=3
Dn Slope=0.005

--- Caney T6.g01 (geometry) ---

Geom Title=Existing Conditions
Program Version=4.10

River Reach=Caney T6        ,Reach-1
Reach XY= 30
        2735476.        6897861.      2735518.14      6897964.28
      2735425.95      6898145.66      2735522.45      6898262.47
      2735568.44        6898561.      2735433.79       6898807.6
      2735518.47      6898960.99      2735473.93      6899155.14
       2735333.6      6899314.33      2735422.43      6899412.47
      2735442.43      6899577.83      2735522.65        6899653.
      2735589.33      6899624.65      2735817.05      6899854.34
      2735634.99      6900003.99      2735686.75      6900120.68
      2735869.83      6900303.14      2735989.65      6900324.26
      2736069.53       6900453.3      2736239.35      6900474.36
      2736368.69       6900711.1      2736228.05      6900866.86
        2736276.        6901111.      2736081.47      6901358.55
       2735972.8      6901702.65      2735876.56      6901771.48
      2735926.39        6901886.      2735833.78       6902511.1
      2735873.94      6903205.15        2735576.        6903461.

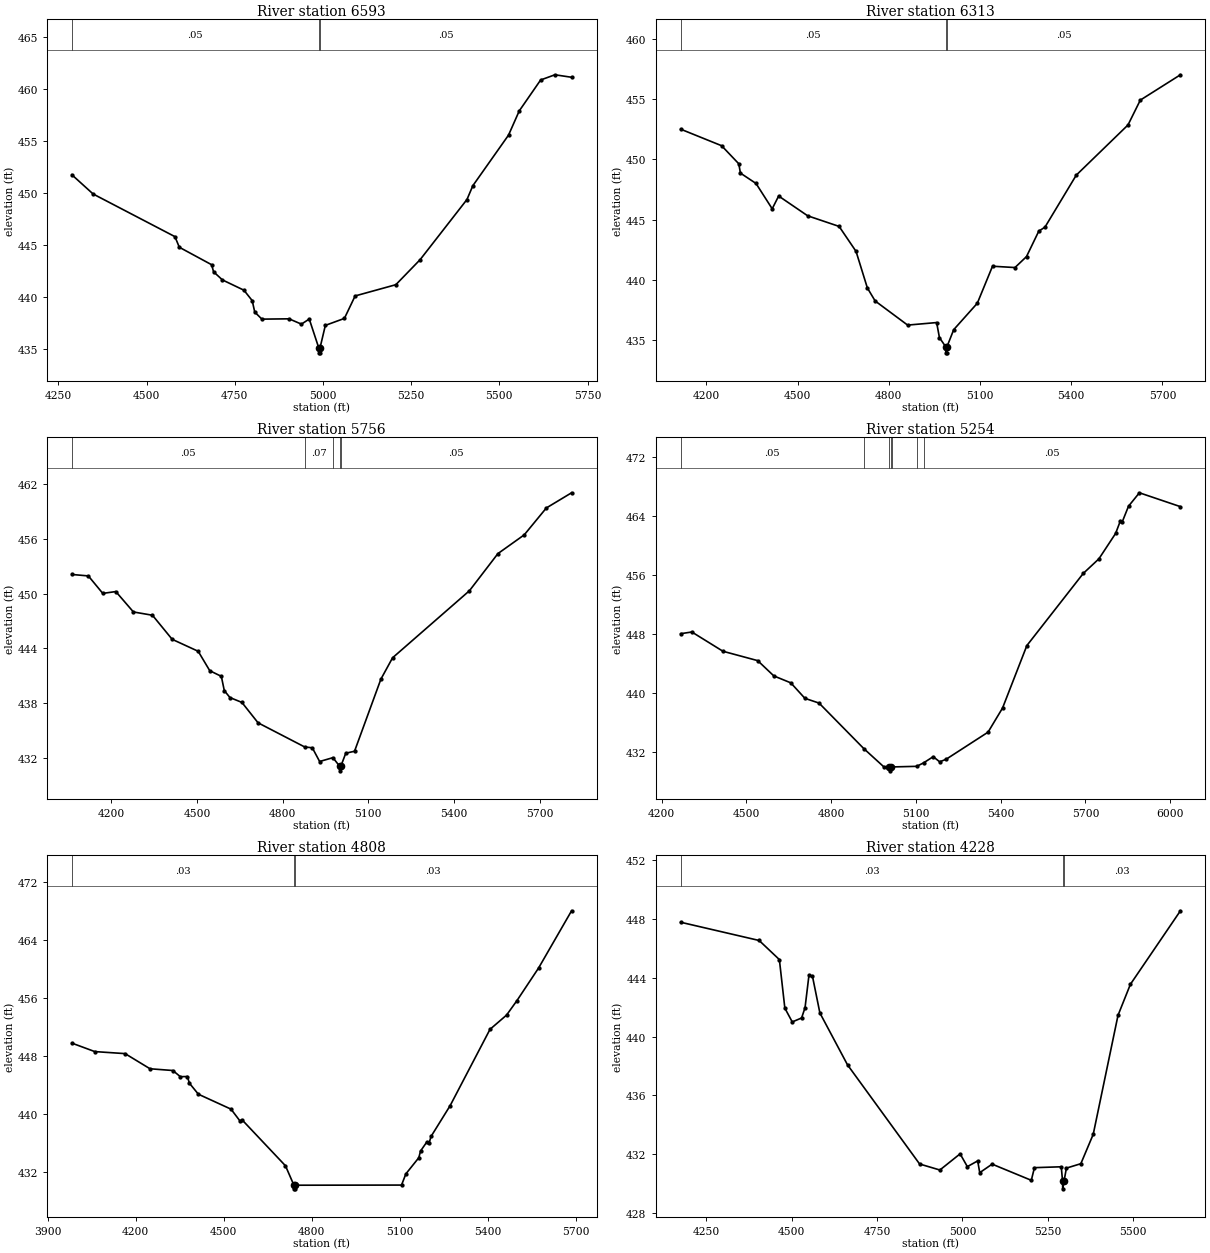
Type RM Length L Ch R = 1 ,6593    ,280,280,280
BEGIN DESCRIPTION:
Mapping XS caec9c72
END DESCRIPTION:
XS GIS Cut Line= 3
      2734826.75      6898280.88      2735534.25      6898415.43
      2736222.67      6898311.52
#Sta/Elev= 30
  4288.3  451.78  4348.6  449.93  4580.5  445.83  4592.9  444.81  4684.5  443.13
    4690  442.45  4715.1  441.67  4776.1  440.68  4799.5  439.68  4806.7  438.58
    4827   437.9  4903.9  437.93    4939  437.42  4961.2  437.91  4987.9  435.16
  4988.2  434.66  4991.7  434.66  4991.9  435.16  5006.8   437.3  5060.8  437.97
  5091.2  440.13  5206.6  441.21  5275.5  443.62  5408.2   449.4  5424.9  450.73
    5526  455.59  5556.4  457.92    5617  460.89  5657.5  461.39  5704.7  461.15
#Mann= 3 ,-1 , 0
  4288.3     .05       0  4987.9    .035       0  4991.9     .05       0
Bank Sta=4987.9,4991.9
XS Rating Curve= 0 ,0
Exp/Cntr=0.3,0.1

Type RM Length L Ch R = 1 ,6313    ,557,557,557
BEGIN DESCRIPTION:
Mapping XS ba27acbd
END DESCRIPTION:
XS GIS Cut Line= 3
      2734692.19      6898372.01      2735529.91      6898667.17
      2736276.43      6898554.32
#Sta/Elev= 30
  4115.8   452.5  4250.3  451.13  4306.9  449.63  4312.2  448.86  4363.5     448
  4416.7   445.9  4437.9  446.96  4533.3  445.32  4636.7  444.44  4692.4  442.37
  4729.6  439.34  4755.2  438.26    4862  436.26  4957.4  436.47  4966.6  435.22
  4987.3  434.46  4987.5  433.96    4991  433.96  4991.3  434.46  5013.5  435.88
  5091.1  438.07  5141.1  441.14    5215  441.03  5252.9  441.94  5293.3  444.05
  5313.6  444.38  5416.5  448.69  5586.6  452.85  5627.1  454.91    5759  457.01
#Mann= 3 ,-1 , 0
  4115.8     .05       0  4987.3     .04       0  4991.3     .05       0
Bank Sta=4987.3,4991.3
XS Rating Curve= 0 ,0
Exp/Cntr=0.3,0.1

Type RM Length L Ch R = 1 ,5756    ,502,502,502
BEGIN DESCRIPTION:
Mapping XS c6808d98
END DESCRIPTION:
XS GIS Cut Line= 3
      2734548.98      6899001.37      2735460.46      6899148.94
      2736267.79      6898966.64
#Sta/Elev= 30
  4061.1  452.09  4118.9  451.93  4169.5  450.02  4215.2  450.22  4276.8  447.99
  4343.6  447.63  4412.6     445  4503.8  443.69  4544.3  441.57  4584.9  440.95
  4595.3  439.39  4615.2  438.63    4657   438.1  4713.6  435.87    4877  433.23
  4903.7  433.14  4929.3  431.64  4975.8  432.06  4999.6  431.12  4999.9  430.62
  5003.6  431.12  5020.9  432.55  5051.6  432.76  5143.9  440.64  5184.9  442.98
  5454.2  450.31    5554  454.37  5646.2  456.42  5723.7  459.36  5812.1  461.02
#Mann= 5 ,-1 , 0
  4061.1     .05       0    4877     .07       0  4975.8     .05       0
  4999.6     .04       0  5003.6     .05       0
Bank Sta=4999.6,5003.6
XS Rating Curve= 0 ,0
Exp/Cntr=0.3,0.1

Type RM Length L Ch R = 1 ,5254    ,446,446,446
BEGIN DESCRIPTION:
Mapping XS f9267072
END DESCRIPTION:
XS GIS Cut Line= 3
      2734696.53      6899539.56      2735425.74      6899556.92
       2736367.6      6899118.55
#Sta/Elev= 30
  4267.8  448.07  4307.3   448.3  4417.3  445.69  4540.3  444.42  4597.4  442.35
  4657.4  441.41  4707.4  439.31  4757.4  438.67  4915.8   432.5  4987.5     430
  5006.5  429.99  5006.8  429.49  5010.5  429.99  5016.8  430.02  5102.9   430.1
  5127.2  430.57  5161.4  431.41  5184.2  430.71  5207.1  431.06  5355.4  434.73
  5406.7     438  5492.7  446.46  5692.4  456.24  5747.6  458.21  5806.7  461.65
    5824  463.39  5829.6  463.16  5852.4  465.34  5890.9  467.16  6036.1  465.28
#Mann= 7 ,-1 , 0
  4267.8     .05       0  4915.8     .05       0  5006.5     .03       0
  5010.5     .05       0  5016.8     .05       0  5102.9     .12       0
  5127.2     .05       0
Bank Sta=5006.5,5010.5
XS Rating Curve= 0 ,0
Exp/Cntr=0.3,0.1

Type RM Length L Ch R = 1 ,4808    ,580,580,580
BEGIN DESCRIPTION:
Mapping XS 4e83faf1
END DESCRIPTION:
XS GIS Cut Line= 3
      2734805.11      6900151.53      2735677.47      6899839.04
      2736306.84      6899383.29
#Sta/Elev= 30
  3982.6  449.75  4060.8  448.58  4164.1   448.3  4249.1  446.21    4327  445.97
  4352.4  445.12  4376.6  445.14  4383.2  444.23    4414   442.7  4525.3  440.64
  4557.1  438.94  4562.4  439.19  4710.9  432.83  4739.7  430.15  4739.9  429.65
  4743.4  429.65  4743.7  430.15  5106.6  430.17  5121.3  431.71  5165.4  433.94
  5171.5  434.87  5192.4  436.09  5200.9     436  5207.1  436.87  5272.1  441.11
  5408.2  451.65  5464.6  453.61  5500.2  455.62  5573.7   460.1  5686.3     468
#Mann= 3 ,-1 , 0
  3982.6     .03       0  4739.7     .03       0  4743.7     .03       0
Bank Sta=4739.7,4743.7
XS Rating Curve= 0 ,0
Exp/Cntr=0.3,0.1

Type RM Length L Ch R = 1 ,4228    ,61,61,61
BEGIN DESCRIPTION:
Mapping XS 78c1381d
END DESCRIPTION:
XS GIS Cut Line= 3
      2735038.12      6900597.07      2735756.84      6900194.31
      2736295.07      6899847.06
#Sta/Elev= 30
  4174.4  447.78  4404.3  446.54  4463.6  445.24  4479.6  441.94  4501.3     441
  4528.7  441.27  4538.8  441.97  4550.4   444.2  4560.6   444.1  4582.3  441.61
  4663.3  438.08  4874.5  431.34  4933.9  430.93  4993.2  432.03  5014.4  431.16
  5044.7  431.55  5050.7  430.75    5087  431.33  5201.8  430.23    5211  431.09
  5289.6  431.15  5293.5  430.15  5293.8  429.65  5297.5  430.15  5304.7  431.06
    5347  431.36  5383.3  433.36  5455.9  441.45  5492.2  443.56  5638.8  448.56
#Mann= 3 ,-1 , 0
  4174.4     .03       0  5293.5     .03       0  5297.5     .03       0
Bank Sta=5293.5,5297.5
XS Rating Curve= 0 ,0
Exp/Cntr=0.3,0.1

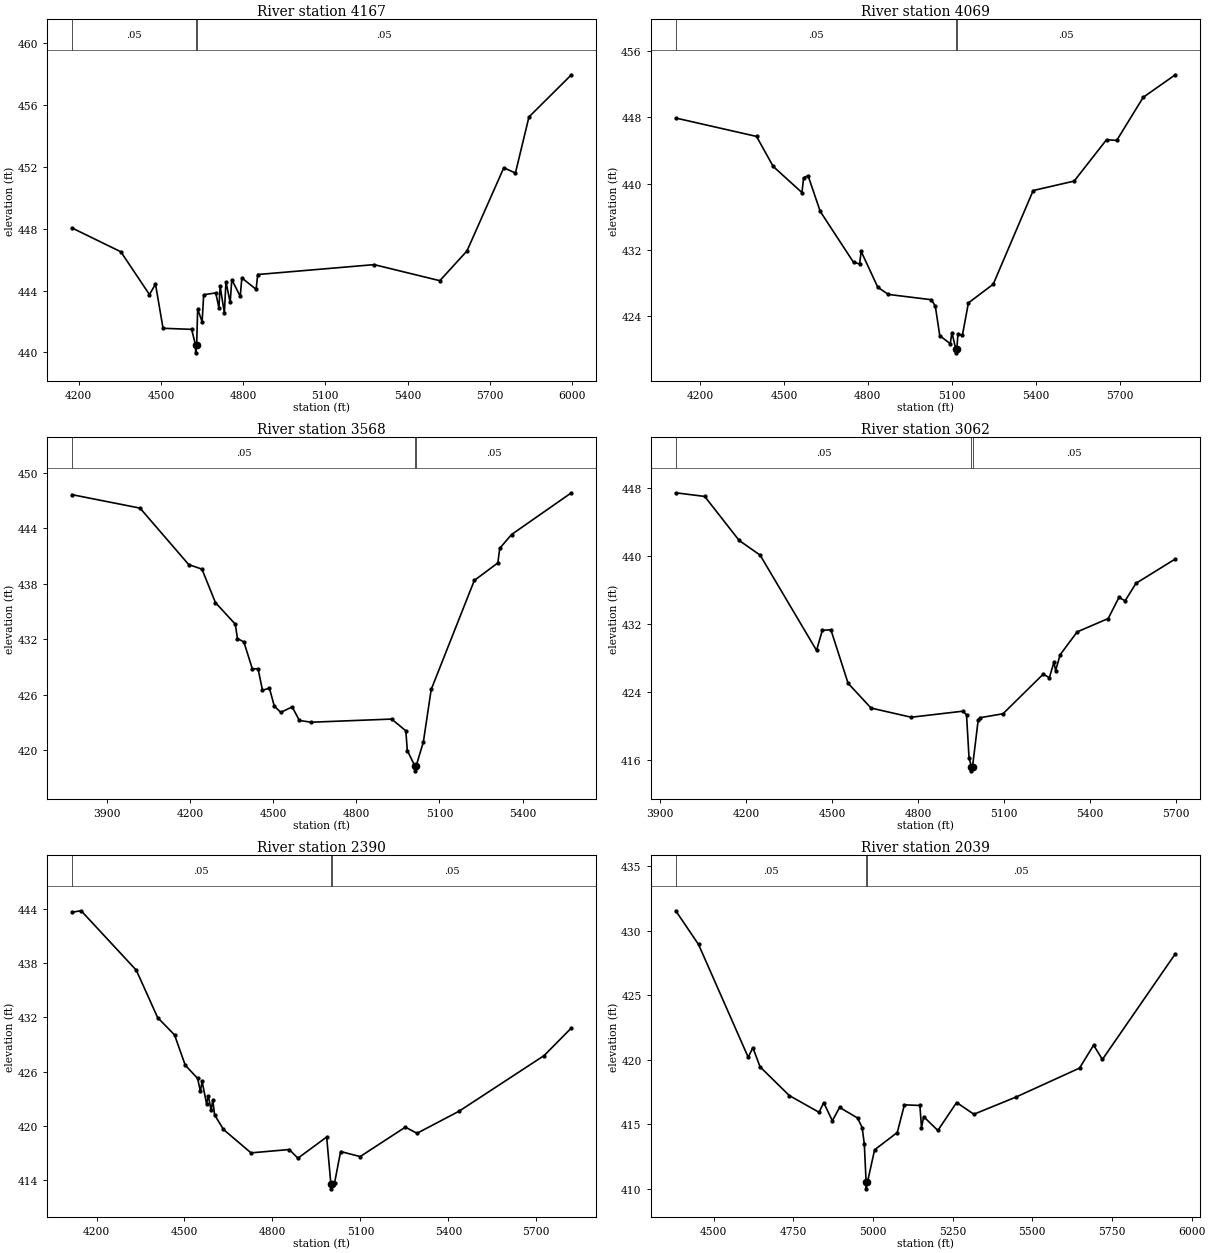
Type RM Length L Ch R = 1 ,4167    ,98,98,98
BEGIN DESCRIPTION:
Mapping XS 6a9be149
END DESCRIPTION:
XS GIS Cut Line= 6
      2735082.04      6900639.41      2735553.43      6900389.39
      2735764.37      6900259.18      2736066.45       6900082.1
      2736201.87      6900006.58      2736588.95      6899635.08
#Sta/Elev= 30
  4174.9  448.06  4353.9  446.51  4458.2  443.74  4480.2  444.42  4507.8  441.56
  4612.1  441.49  4626.4  440.47  4626.7  439.97  4630.4  440.47  4634.1   442.8
  4650.4  441.98  4656.1  443.73  4700.1  443.85  4711.7  442.89  4716.2  444.27
  4731.6  442.56  4737.4  444.57  4752.8  443.23  4758.7  444.71  4789.5  443.63
  4795.4  444.82  4847.4  444.08  4853.3  445.04    5278  445.68    5518  444.64
  5617.1  446.57  5751.4  451.95  5793.8  451.61  5843.2  455.24  5998.1  457.97
#Mann= 3 ,-1 , 0
  4174.9     .05       0  4626.4     .04       0  4630.4     .05       0
Bank Sta=4626.4,4630.4
XS Rating Curve= 0 ,0
Exp/Cntr=0.3,0.1

Type RM Length L Ch R = 1 ,4069    ,501,501,501
BEGIN DESCRIPTION:
Mapping XS cd37026f
END DESCRIPTION:
XS GIS Cut Line= 4
      2735097.67      6900735.76      2735860.72      6900311.26
      2736011.76      6900225.33      2736638.35      6899835.33
#Sta/Elev= 30
  4113.5  447.92  4402.2   445.7  4461.7  442.08  4564.6  438.92  4570.3   440.7
  4586.3  440.97  4629.8  436.65  4748.7  430.51  4770.4  430.31  4776.1  431.82
  4835.6  427.49  4873.3  426.63  5027.3  425.99  5041.1  425.19    5057  421.65
  5094.5  420.68  5100.2  422.02  5114.1  420.08  5114.4  419.58  5118.1  420.08
  5121.9  421.86  5137.7  421.69  5159.3  425.61  5247.9  427.86  5390.7  439.17
  5537.1  440.31  5652.7   445.3  5689.3  445.22  5783.8  450.42  5898.5  453.14
#Mann= 3 ,-1 , 0
  4113.5     .05       0  5114.1     .04       0  5118.1     .05       0
Bank Sta=5114.1,5118.1
XS Rating Curve= 0 ,0
Exp/Cntr=0.3,0.1

Type RM Length L Ch R = 1 ,3568    ,506,506,506
BEGIN DESCRIPTION:
Mapping XS acc54267
END DESCRIPTION:
XS GIS Cut Line= 3
      2735080.77      6900791.52      2736261.33      6900518.08
      2736669.29      6900088.42
#Sta/Elev= 30
  3772.3  447.63  4018.6  446.17  4194.5  440.06  4242.3  439.57  4290.9  435.95
  4362.8  433.61  4370.4  432.06  4393.6   431.7  4424.3  428.78  4444.9  428.79
  4460.9  426.47  4485.9  426.69  4503.6  424.75    4527  424.07  4568.1  424.67
  4594.1   423.2  4636.8  423.01  4927.3  423.35  4978.6  422.08  4983.9  419.95
  5011.6  418.25  5011.9  417.75  5015.6  418.25  5041.9  420.87  5070.2  426.55
    5226  438.35  5310.9  440.24  5317.8  441.82  5360.3  443.31  5576.6  447.83
#Mann= 3 ,-1 , 0
  3772.3     .05       0  5011.6     .04       0  5015.6     .05       0
Bank Sta=5011.6,5015.6
XS Rating Curve= 0 ,0
Exp/Cntr=0.3,0.1

Type RM Length L Ch R = 1 ,3062    ,672,672,672
BEGIN DESCRIPTION:
Mapping XS 627bd9c3
END DESCRIPTION:
XS GIS Cut Line= 3
      2735184.91      6900934.74      2736196.22      6900939.09
      2736832.66      6900579.74
#Sta/Elev= 30
    3955  447.45  4056.1  447.02  4176.1  441.85  4249.3  440.12  4446.1  428.92
  4466.1  431.28  4496.1  431.35  4556.1  425.06  4636.1  422.15  4776.1  421.07
  4956.1  421.78  4969.1  421.37  4977.9  416.28  4986.1  415.27  4986.4  414.77
  4990.1  415.27  5009.8  420.75  5015.5  421.01  5096.4  421.48  5236.5  426.13
  5258.1  425.72    5274  427.54  5279.8  426.55  5295.7  428.42  5354.9   431.1
  5463.2  432.67  5500.7  435.15  5522.4  434.76    5560  436.81  5697.2  439.67
#Mann= 3 ,-1 , 0
    3955     .05       0  4986.1     .04       0  4990.1     .05       0
Bank Sta=4986.1,4990.1
XS Rating Curve= 0 ,0
Exp/Cntr=0.3,0.1

Type RM Length L Ch R = 1 ,2390    ,351,351,351
BEGIN DESCRIPTION:
Mapping XS eeda5c7f
END DESCRIPTION:
XS GIS Cut Line= 3
      2735324.95      6901048.44      2736049.81      6901508.53
      2736865.77      6901287.18
#Sta/Elev= 30
  4115.7  443.59  4147.5  443.75  4335.6  437.19  4408.4  431.96    4466  430.05
  4502.5  426.71  4544.8  425.25  4554.1  423.82  4560.1  424.91  4575.3  422.44
  4581.2  423.33  4590.6  421.77  4596.5  422.84  4602.6  421.23  4632.9  419.61
  4726.9  417.03  4857.4   417.4  4886.8  416.44  4984.9  418.78  4999.4  413.56
  4999.6  413.06  5003.4  413.56  5011.7  413.68  5032.5  417.18  5099.2  416.62
  5253.3  419.87  5293.1  419.19  5436.6  421.63  5726.7  427.77  5819.7  430.82
#Mann= 3 ,-1 , 0
  4115.7     .05       0  4999.4     .04       0  5003.4     .05       0
Bank Sta=4999.4,5003.4
XS Rating Curve= 0 ,0
Exp/Cntr=0.3,0.1

Type RM Length L Ch R = 1 ,2039    ,653,653,653
BEGIN DESCRIPTION:
Mapping XS cc46f2c3
END DESCRIPTION:
XS GIS Cut Line= 4
      2735385.79      6901391.37      2735863.18      6901755.93
      2736032.45      6901786.31      2736729.66      6901405.23
#Sta/Elev= 30
  4381.5  431.56    4453  428.95  4608.9  420.19  4623.5  420.94    4646  419.45
  4737.8  417.22  4831.2  415.92  4845.7  416.67  4872.9  415.26  4895.6   416.3
  4951.8  415.48  4966.3  414.74  4973.1  413.46  4978.8  410.48    4979  409.98
  4982.8  410.48  5005.4  413.01  5076.5  414.35  5098.8   416.5  5147.5  416.45
  5152.5  414.71  5159.3  415.58  5203.8  414.51  5262.7  416.68  5316.8  415.77
  5447.7  417.09  5648.2  419.35  5692.5  421.13    5720  420.02  5948.7  428.22
#Mann= 3 ,-1 , 0
  4381.5     .05       0  4978.8     .04       0  4982.8     .05       0
Bank Sta=4978.8,4982.8
XS Rating Curve= 0 ,0
Exp/Cntr=0.3,0.1

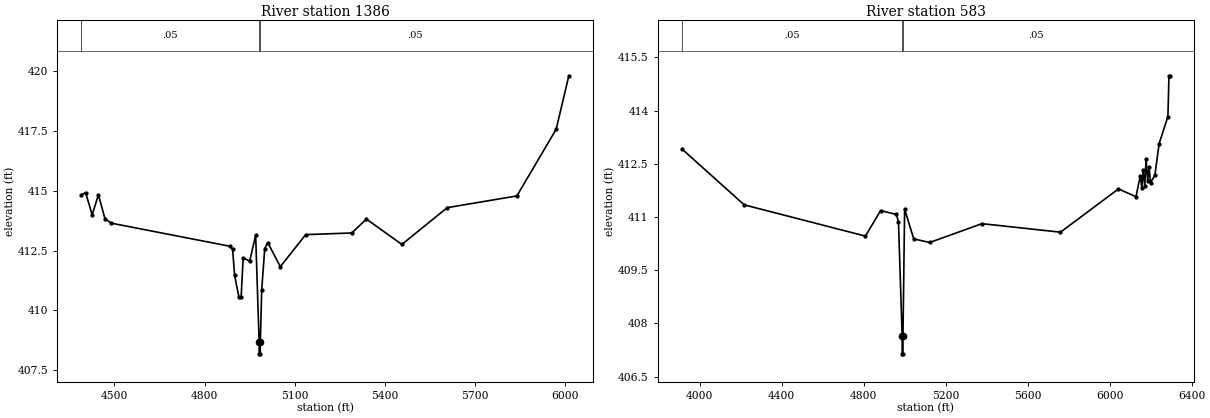
Type RM Length L Ch R = 1 ,1386    ,803,803,803
BEGIN DESCRIPTION:
Mapping XS d3637ec1
END DESCRIPTION:
XS GIS Cut Line= 4
      2735454.95      6901952.27      2735832.08       6902373.4
      2735922.78      6902382.48      2736730.85      6901855.85
#Sta/Elev= 30
  4390.4  414.83  4404.2  414.93  4425.9     414  4446.8  414.84  4468.5  413.84
  4489.4  413.65  4885.6  412.68  4893.1  412.55  4899.8  411.46    4914  410.56
  4921.5  410.57  4928.2   412.2  4949.9  412.06  4969.7  413.15  4981.3  408.68
  4981.5  408.18    4985  408.18  4985.3  408.68  4989.8  410.85  4999.9  412.58
  5009.9  412.84  5051.8  411.83  5136.1  413.17  5289.4  413.24  5338.3  413.82
  5456.1  412.76    5607   414.3  5838.5  414.79  5969.2  417.58  6011.4  419.82
#Mann= 3 ,-1 , 0
  4390.4     .05       0  4981.3     .04       0  4985.3     .05       0
Bank Sta=4981.3,4985.3
XS Rating Curve= 0 ,0
Exp/Cntr=0.3,0.1

Type RM Length L Ch R = 1 ,583     ,0,0,0
BEGIN DESCRIPTION:
Caney T6 1.0
END DESCRIPTION:
XS GIS Cut Line= 4
      2735295.97       6902167.3      2735818.44       6903051.8
      2735899.04      6903053.71      2736855.42      6902219.18
#Sta/Elev= 30
  3914.7  412.91  4217.3  411.34  4808.4  410.46  4882.6  411.18  4959.6  411.07
  4969.6  410.86  4987.6  407.64  4987.8  407.14  4991.3  407.14  4991.6  407.64
  4999.6  411.22    5044  410.38  5121.9  410.28  5376.9  410.81  5759.8  410.57
  6042.7  411.79  6128.1  411.57    6149  412.16  6156.6  411.82  6163.2  412.32
  6170.8  411.88  6177.5  412.63  6185.1  412.01  6191.7  412.41  6199.3  411.97
  6220.2  412.17  6241.1  413.07  6283.8  413.83    6289  414.98  6291.9  414.98
#Mann= 3 ,-1 , 0
  3914.7     .05       0  4987.6     .04       0  4991.6     .05       0
Bank Sta=4987.6,4991.6
XS Rating Curve= 0 ,0
Exp/Cntr=0.3,0.1

Chan Stop Cuts=-1
Use User Specified Reach Order=0
Composite Channel Slope=5