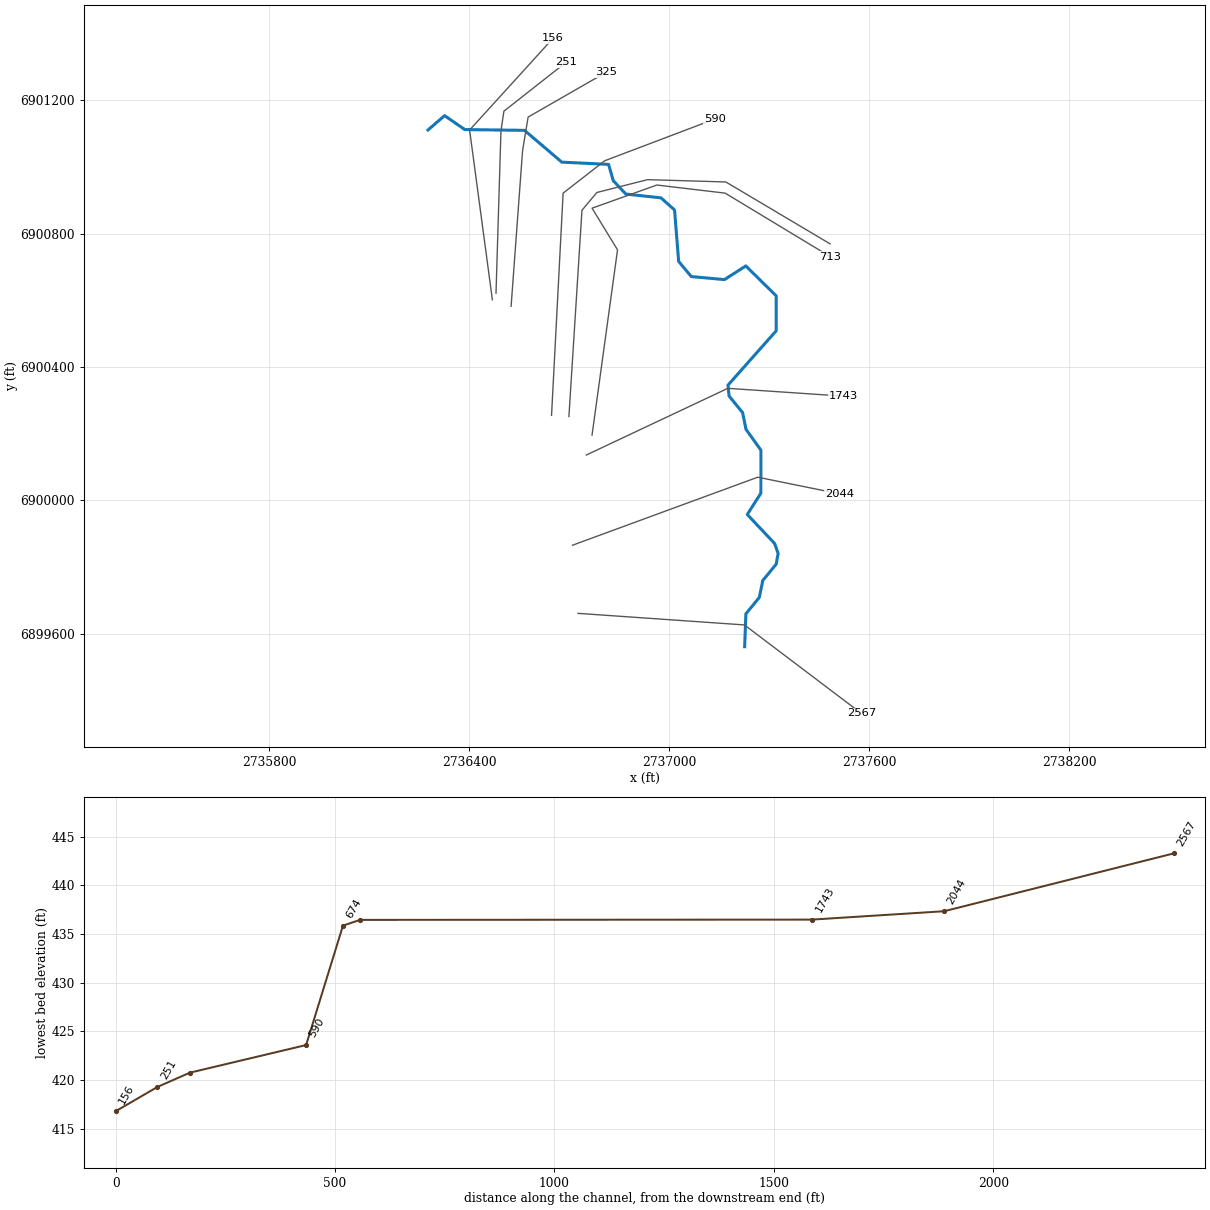
--- Caney T6_1.prj (project) ---

Proj Title=Caney T6_1 Base Level Engineering
Current Plan=p01
Default Exp/Contr=0.3,0.1
English Units
Geom File=g01
Flow File=f01
Plan File=p01
BEGIN DESCRIPTION:
Caney T6_1
END DESCRIPTION:

--- Caney T6_1.p01 (plan) ---

Plan Title=Multiple Run
Short Identifier=Multiple
Geom File=g01
Flow File=f01
Subcritical Flow
K Sum by GR= 0
Std Step Tol= 0.01
Critical Tol= 0.01
Num of Std Step Trials= 20
Max Error Tol= 0.3
Flow Tol Ratio= 0.001
Split Flow NTrial= 30
Split Flow Tol= 0.02
Split Flow Ratio= 0.02
Log Output Level= 0
Friction Slope Method= 1
Unsteady Friction Slope Method= 2
Unsteady Bridges Friction Slope Method= 1
Parabolic Critical Depth
Global Vel Dist=  1 , 1 , 1
Global Log Level= 0
CheckData=True
Encroach Param= -1, 0, 0, 0
BEGIN DESCRIPTION:
Multiple Run
END DESCRIPTION:

--- Caney T6_1.f01 (steady flow) ---

Flow Title=Multiple
Number of Profiles=7
Profile Names=10-year,25-year,50-year,1pct_min,100-year,1pct_plu,500-year
River Rch & RM= Caney T6_1,Reach-1,2567
     201     250     286     164     327     652     423
Boundary for River Rch & Prof#=Caney T6_1,Reach-1,1
Up Type=0
Dn Type=3
Dn Slope=0.005
Boundary for River Rch & Prof#=Caney T6_1,Reach-1,2
Up Type=0
Dn Type=3
Dn Slope=0.005
Boundary for River Rch & Prof#=Caney T6_1,Reach-1,3
Up Type=0
Dn Type=3
Dn Slope=0.005
Boundary for River Rch & Prof#=Caney T6_1,Reach-1,4
Up Type=0
Dn Type=3
Dn Slope=0.005
Boundary for River Rch & Prof#=Caney T6_1,Reach-1,5
Up Type=0
Dn Type=3
Dn Slope=0.005
Boundary for River Rch & Prof#=Caney T6_1,Reach-1,6
Up Type=0
Dn Type=3
Dn Slope=0.005
Boundary for River Rch & Prof#=Caney T6_1,Reach-1,7
Up Type=0
Dn Type=3
Dn Slope=0.005

--- Caney T6_1.g01 (geometry) ---

Geom Title=Existing Conditions

River Reach=Caney T6_1,Reach-1
Reach XY= 30
      2737226.00      6899561.00      2737229.63      6899659.50
      2737269.92      6899708.81      2737280.22      6899759.28
      2737320.69      6899808.81      2737326.40      6899840.87
      2737315.77      6899870.68      2737233.81      6899957.59
      2737274.62      6900021.44      2737274.81      6900150.50
      2737230.19      6900212.74      2737219.84      6900263.20
      2737179.31      6900312.74      2737175.95      6900345.66
      2737320.60      6900508.57      2737320.60      6900613.46
      2737229.43      6900703.21      2737165.51      6900662.27
      2737065.84      6900671.28      2737027.98      6900716.65
      2737015.67      6900871.17      2736974.75      6900907.49
      2736869.57      6900918.79      2736831.90      6900958.82
      2736817.68      6901007.89      2736677.48      6901014.56
      2736565.56      6901109.94      2736386.42      6901112.31
      2736325.86      6901154.09      2736276.00      6901111.00

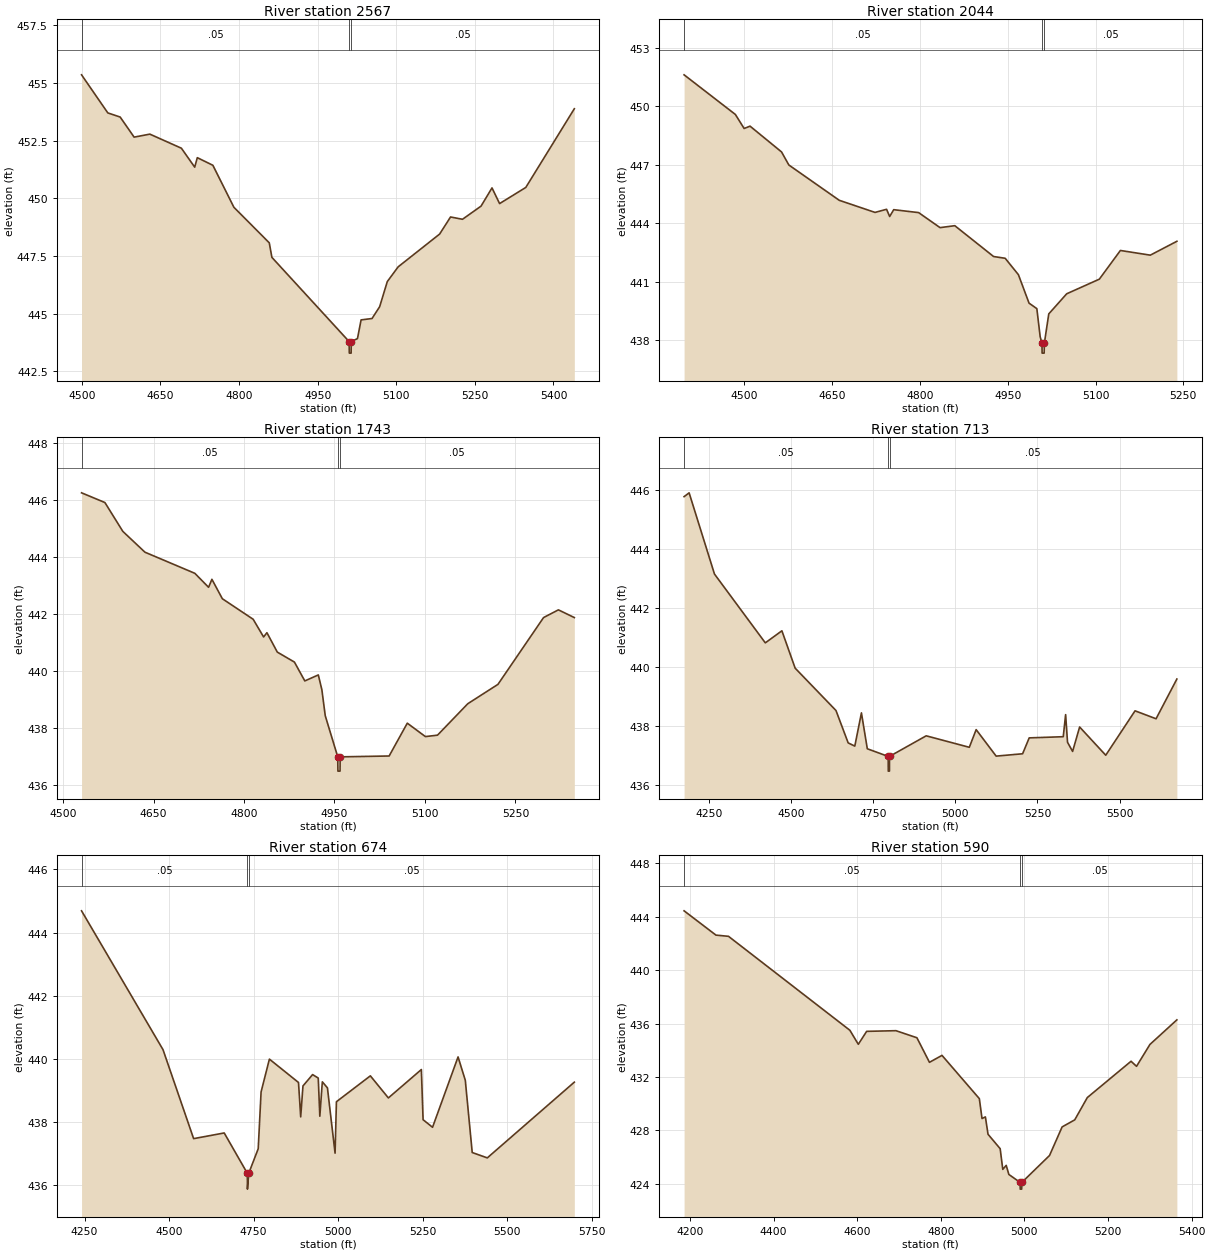
Type RM Length L Ch R = 1,2567,523,523,523
BEGIN DESCRIPTION:
Caney T6_1 3.0
END DESCRIPTION:
XS GIS Cut Line= 3
      2736725.99      6899661.00      2737225.28      6899626.30
      2737576.04      6899360.97
#Sta/Elev= 30
  4499.5  455.35  4549.6  453.70  4573.2  453.52  4599.8  452.65  4629.8  452.78
  4690.0  452.17  4715.4  451.35  4720.4  451.76  4750.1  451.43  4790.2  449.61
  4857.7  448.07  4862.7  447.44  5010.1  443.79  5010.4  443.29  5013.9  443.29
  5014.1  443.79  5026.0  443.92  5032.9  444.73  5053.8  444.79  5068.3  445.30
  5082.9  446.39  5103.7  447.03  5182.8  448.45  5203.6  449.19  5226.4  449.09
  5261.8  449.66  5282.7  450.45  5297.2  449.77  5347.2  450.47  5439.8  453.88
#Mann=3,-1,0
  4499.5    0.05       0  5010.1    0.04       0  5014.1    0.05       0
Bank Sta=5010.1,5014.1
Exp/Cntr=0.3,0.1

Type RM Length L Ch R = 1,2044,301,301,301
BEGIN DESCRIPTION:
Mapping XS 59f25b27
END DESCRIPTION:
XS GIS Cut Line= 3
      2736709.73      6899865.46      2737265.27      6900069.45
      2737510.54      6900019.53
#Sta/Elev= 30
  4396.8  451.61  4484.4  449.58  4499.4  448.86  4509.5  448.98  4563.3  447.66
  4575.8  446.99  4662.0  445.18  4723.1  444.56  4742.8  444.72  4748.1  444.35
  4755.0  444.70  4797.6  444.55  4834.2  443.78  4859.4  443.88  4925.7  442.30
  4945.5  442.21  4968.1  441.37  4986.3  439.91  4999.6  439.63  5005.3  438.19
  5008.4  437.85  5008.6  437.35  5012.1  437.35  5012.4  437.85  5020.0  439.36
  5050.6  440.39  5106.4  441.14  5142.4  442.61  5193.5  442.37  5238.9  443.08
#Mann=3,-1,0
  4396.8    0.05       0  5008.4   0.035       0  5012.4    0.05       0
Bank Sta=5008.4,5012.4
Exp/Cntr=0.3,0.1

Type RM Length L Ch R = 1,1743,1030,1030,1030
BEGIN DESCRIPTION:
Mapping XS de6247f0
END DESCRIPTION:
XS GIS Cut Line= 3
      2736750.97      6900135.98      2737175.49      6900336.04
      2737522.30      6900312.59
#Sta/Elev= 30
  4530.7  446.24  4569.4  445.90  4599.1  444.89  4635.8  444.16  4718.5  443.42
  4741.3  442.93  4746.8  443.21  4764.1  442.53  4815.2  441.81  4832.5  441.19
  4838.0  441.34  4855.2  440.66  4883.6  440.31  4900.8  439.65  4923.2  439.86
  4929.1  439.34  4934.7  438.43  4955.4  436.99  4955.7  436.49  4959.2  436.49
  4959.4  436.99  5040.6  437.02  5070.7  438.17  5100.7  437.70  5120.8  437.75
  5170.9  438.85  5221.0  439.53  5296.6  441.87  5321.2  442.14  5347.6  441.87
#Mann=3,-1,0
  4530.7    0.05       0  4955.4    0.04       0  4959.4    0.05       0
Bank Sta=4955.4,4959.4
Exp/Cntr=0.3,0.1

Type RM Length L Ch R = 1,713,39,39,39
BEGIN DESCRIPTION:
Mapping XS 6ecc52af
END DESCRIPTION:
XS GIS Cut Line= 6
      2736768.20      6900195.87      2736844.60      6900751.46
      2736768.21      6900876.46      2736962.65      6900945.90
      2737167.51      6900921.59      2737482.22      6900731.39
#Sta/Elev= 30
  4173.5  445.79  4188.8  445.92  4266.0  443.16  4420.9  440.82  4471.4  441.23
  4511.8  439.96  4636.2  438.52  4673.3  437.42  4693.5  437.31  4713.7  438.44
  4731.6  437.22  4795.2  436.96  4795.5  436.46  4799.0  436.46  4799.2  436.96
  4911.0  437.66  5042.3  437.27  5063.2  437.87  5124.1  436.97  5204.7  437.05
  5224.8  437.59  5328.5  437.63  5335.7  438.38  5341.5  437.44  5357.0  437.13
  5378.4  437.96  5457.9  437.00  5547.2  438.51  5611.2  438.24  5674.6  439.59
#Mann=3,-1,0
  4173.5    0.05       0  4795.2    0.03       0  4799.2    0.05       0
Bank Sta=4795.2,4799.2
Exp/Cntr=0.3,0.1

Type RM Length L Ch R = 1,674,84,84,84
BEGIN DESCRIPTION:
Mapping XS f056bf78
END DESCRIPTION:
XS GIS Cut Line= 6
      2736698.76      6900251.45      2736737.92      6900870.16
      2736782.63      6900923.54      2736934.72      6900962.05
      2737169.53      6900955.10      2737482.24      6900769.50
#Sta/Elev= 30
  4241.2  444.69  4482.2  440.29  4572.8  437.47  4663.3  437.65  4731.8  436.37
  4732.0  435.87  4735.8  436.37  4763.9  437.15  4772.4  438.95  4797.0  439.99
  4883.1  439.25  4889.6  438.16  4896.3  439.14  4924.8  439.50  4941.5  439.39
  4946.2  438.18  4953.6  439.27  4968.7  439.08  4991.3  437.01  4995.3  438.64
  5095.7  439.46  5149.0  438.76  5246.6  439.66  5251.7  438.07  5279.7  437.83
  5355.2  440.06  5376.6  439.32  5397.1  437.03  5441.7  436.86  5699.2  439.26
#Mann=3,-1,0
  4241.2    0.05       0  4731.8    0.03       0  4735.8    0.05       0
Bank Sta=4731.8,4735.8
Exp/Cntr=0.3,0.1

Type RM Length L Ch R = 1,590,265,265,265
BEGIN DESCRIPTION:
Mapping XS 3ed245fa
END DESCRIPTION:
XS GIS Cut Line= 4
      2736646.68      6900254.90      2736681.40      6900921.59
      2736806.40      6901018.82      2737136.26      6901143.81
#Sta/Elev= 30
  4186.0  444.45  4262.2  442.63  4292.2  442.54  4582.6  435.50  4602.7  434.45
  4622.7  435.42  4692.8  435.47  4742.9  434.94  4772.9  433.10  4802.9  433.62
  4892.2  430.38  4898.6  428.89  4906.7  429.01  4913.0  427.71  4942.0  426.63
  4948.3  425.08  4956.5  425.38  4962.8  424.70  4989.8  424.10  4990.0  423.60
  4993.5  423.60  4993.8  424.10  5060.1  426.12  5090.2  428.26  5120.4  428.79
  5150.5  430.46  5255.1  433.18  5268.2  432.80  5300.3  434.44  5364.7  436.28
#Mann=3,-1,0
  4186.0    0.05       0  4989.8    0.04       0  4993.8    0.05       0
Bank Sta=4989.8,4993.8
Exp/Cntr=0.3,0.1

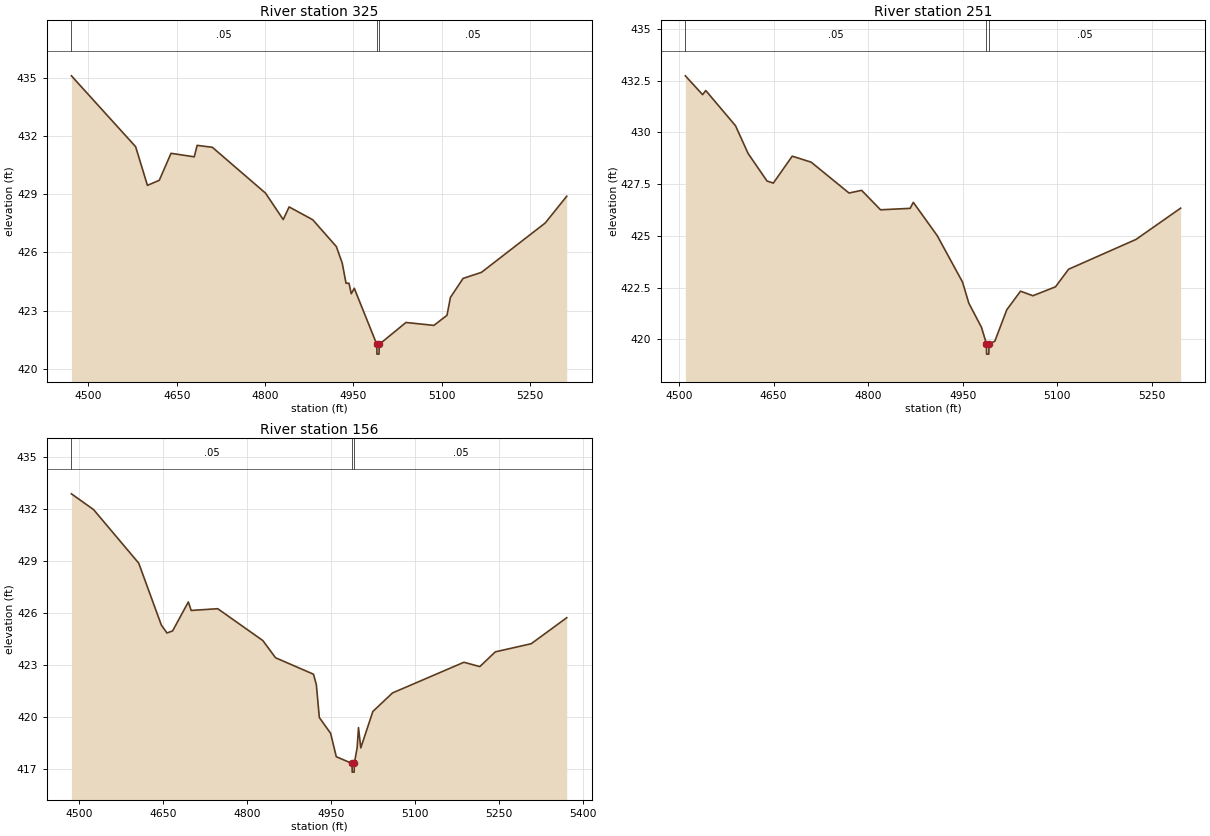
Type RM Length L Ch R = 1,325,74,74,74
BEGIN DESCRIPTION:
Mapping XS 78b5bbb1
END DESCRIPTION:
XS GIS Cut Line= 4
      2736525.36      6900582.22      2736559.74      6901048.89
      2736576.41      6901149.73      2736811.60      6901284.87
#Sta/Elev= 30
  4471.1  435.09  4580.2  431.44  4600.2  429.45  4620.3  429.71  4640.3  431.10
  4679.7  430.92  4684.7  431.51  4710.5  431.41  4800.8  429.05  4830.9  427.69
  4840.9  428.34  4881.0  427.68  4921.1  426.30  4931.1  425.45  4937.6  424.41
  4942.6  424.41  4946.5  423.87  4951.6  424.15  4989.9  421.26  4990.1  420.76
  4993.6  420.76  4993.9  421.26  5039.4  422.39  5086.9  422.24  5109.1  422.76
  5114.9  423.68  5136.5  424.66  5167.6  424.97  5275.9  427.51  5312.5  428.89
#Mann=3,-1,0
  4471.1    0.05       0  4989.9    0.04       0  4993.9    0.05       0
Bank Sta=4989.9,4993.9
Exp/Cntr=0.3,0.1

Type RM Length L Ch R = 1,251,95,95,95
BEGIN DESCRIPTION:
Mapping XS df0e6538
END DESCRIPTION:
XS GIS Cut Line= 4
      2736480.08      6900621.44      2736494.91      6901108.40
      2736503.77      6901167.49      2736691.65      6901315.16
#Sta/Elev= 30
  4510.0  432.73  4537.4  431.82  4542.4  432.02  4589.6  430.32  4609.6  428.98
  4639.6  427.65  4649.6  427.55  4679.6  428.85  4709.7  428.56  4769.7  427.07
  4789.7  427.20  4819.7  426.26  4866.7  426.33  4871.7  426.62  4909.7  425.01
  4949.8  422.77  4959.8  421.75  4979.8  420.59  4987.8  419.79  4988.0  419.29
  4991.5  419.29  4991.8  419.79  5001.0  419.91  5020.0  421.43  5041.8  422.33
  5061.5  422.11  5097.3  422.54  5118.1  423.39  5225.1  424.83  5295.9  426.34
#Mann=3,-1,0
  4510.0    0.05       0  4987.8    0.04       0  4991.8    0.05       0
Bank Sta=4987.8,4991.8
Exp/Cntr=0.3,0.1

Type RM Length L Ch R = 1,156,0,0,0
BEGIN DESCRIPTION:
Caney T6_1 1.0
END DESCRIPTION:
XS GIS Cut Line= 3
      2736469.18      6900601.72      2736400.88      6901110.86
      2736650.98      6901385.97
#Sta/Elev= 30
  4486.3  432.86  4525.9  431.95  4606.6  428.86  4647.0  425.29  4657.1  424.83
  4667.2  424.95  4695.3  426.62  4700.4  426.13  4747.9  426.23  4828.6  424.39
  4851.2  423.40  4919.1  422.45  4924.2  421.84  4929.5  419.95  4949.7  419.04
  4959.8  417.69  4988.0  417.30  4988.3  416.80  4991.8  416.80  4992.0  417.30
  4997.1  418.20  4999.5  419.37  5003.6  418.20  5025.2  420.30  5060.3  421.37
  5188.0  423.14  5216.4  422.89  5244.1  423.74  5308.3  424.21  5371.8  425.71
#Mann=3,-1,0
  4486.3    0.05       0  4988.0    0.04       0  4992.0    0.05       0
Bank Sta=4988,4992
Exp/Cntr=0.3,0.1

Chan Stop Cuts=-1