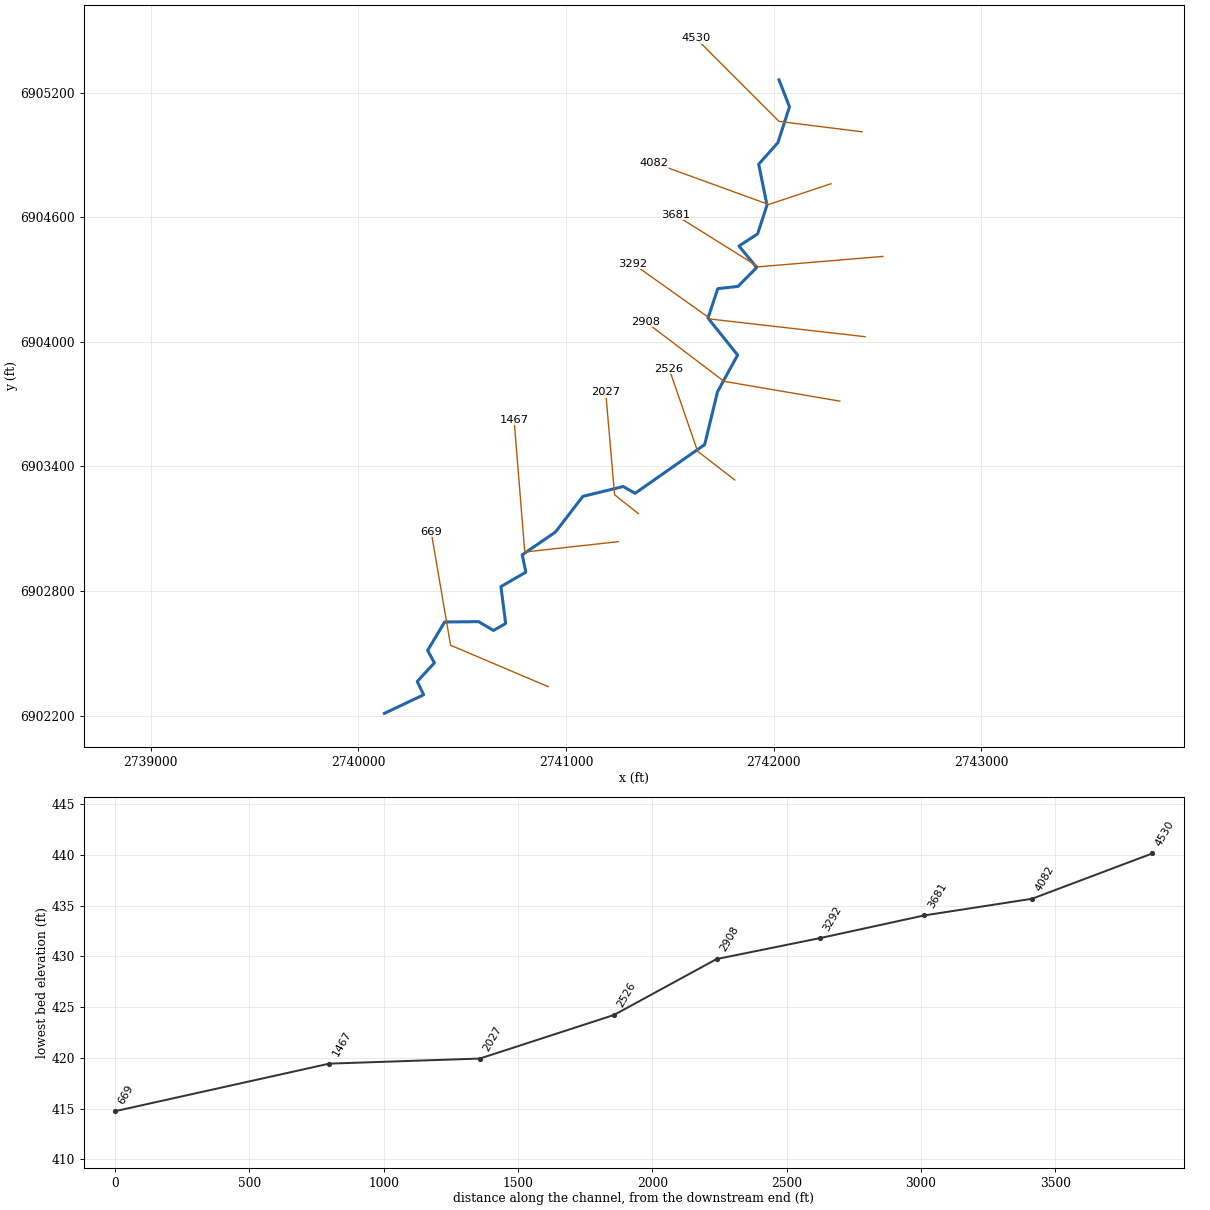
--- Caney T7.prj (project) ---

Proj Title=Caney T7 Base Level Engineering
Current Plan=p01
Default Exp/Contr=0.3,0.1
English Units
Geom File=g01
Flow File=f01
Plan File=p01
BEGIN DESCRIPTION:
Caney T7
END DESCRIPTION:

--- Caney T7.p01 (plan) ---

Plan Title=Multiple Run
Short Identifier=Multiple
Geom File=g01
Flow File=f01
Subcritical Flow
K Sum by GR= 0
Std Step Tol= 0.01
Critical Tol= 0.01
Num of Std Step Trials= 20
Max Error Tol= 0.3
Flow Tol Ratio= 0.001
Split Flow NTrial= 30
Split Flow Tol= 0.02
Split Flow Ratio= 0.02
Log Output Level= 0
Friction Slope Method= 1
Unsteady Friction Slope Method= 2
Unsteady Bridges Friction Slope Method= 1
Parabolic Critical Depth
Global Vel Dist=  1 , 1 , 1
Global Log Level= 0
CheckData=True
Encroach Param= -1, 0, 0, 0
BEGIN DESCRIPTION:
Multiple Run
END DESCRIPTION:

--- Caney T7.f01 (steady flow) ---

Flow Title=Multiple
Number of Profiles=7
Profile Names=10-year,25-year,50-year,1pct_min,100-year,1pct_plu,500-year
River Rch & RM= Caney T7,Reach-1,4530
     371     483     573     338     674    1345     934
Boundary for River Rch & Prof#=Caney T7,Reach-1,1
Up Type=0
Dn Type=3
Dn Slope=0.005
Boundary for River Rch & Prof#=Caney T7,Reach-1,2
Up Type=0
Dn Type=3
Dn Slope=0.005
Boundary for River Rch & Prof#=Caney T7,Reach-1,3
Up Type=0
Dn Type=3
Dn Slope=0.005
Boundary for River Rch & Prof#=Caney T7,Reach-1,4
Up Type=0
Dn Type=3
Dn Slope=0.005
Boundary for River Rch & Prof#=Caney T7,Reach-1,5
Up Type=0
Dn Type=3
Dn Slope=0.005
Boundary for River Rch & Prof#=Caney T7,Reach-1,6
Up Type=0
Dn Type=3
Dn Slope=0.005
Boundary for River Rch & Prof#=Caney T7,Reach-1,7
Up Type=0
Dn Type=3
Dn Slope=0.005

--- Caney T7.g01 (geometry) ---

Geom Title=Existing Conditions

River Reach=Caney T7,Reach-1
Reach XY= 30
      2742026.00      6905261.00      2742076.11      6905131.08
      2742020.46      6904958.58      2741928.06      6904855.14
      2741967.92      6904657.69      2741922.79      6904519.34
      2741833.04      6904461.20      2741918.40      6904357.65
      2741828.39      6904266.55      2741731.11      6904255.89
      2741683.87      6904114.22      2741826.51      6903936.04
      2741729.76      6903759.44      2741667.87      6903504.93
      2741332.66      6903270.31      2741276.10      6903303.19
      2741081.44      6903255.81      2740949.47      6903084.01
      2740789.64      6902974.36      2740806.78      6902890.62
      2740686.97      6902821.38      2740709.75      6902643.70
      2740651.10      6902610.55      2740579.24      6902652.68
      2740416.00      6902650.93      2740334.25      6902514.23
      2740366.67      6902454.33      2740284.04      6902364.32
      2740314.91      6902300.63      2740126.00      6902211.00

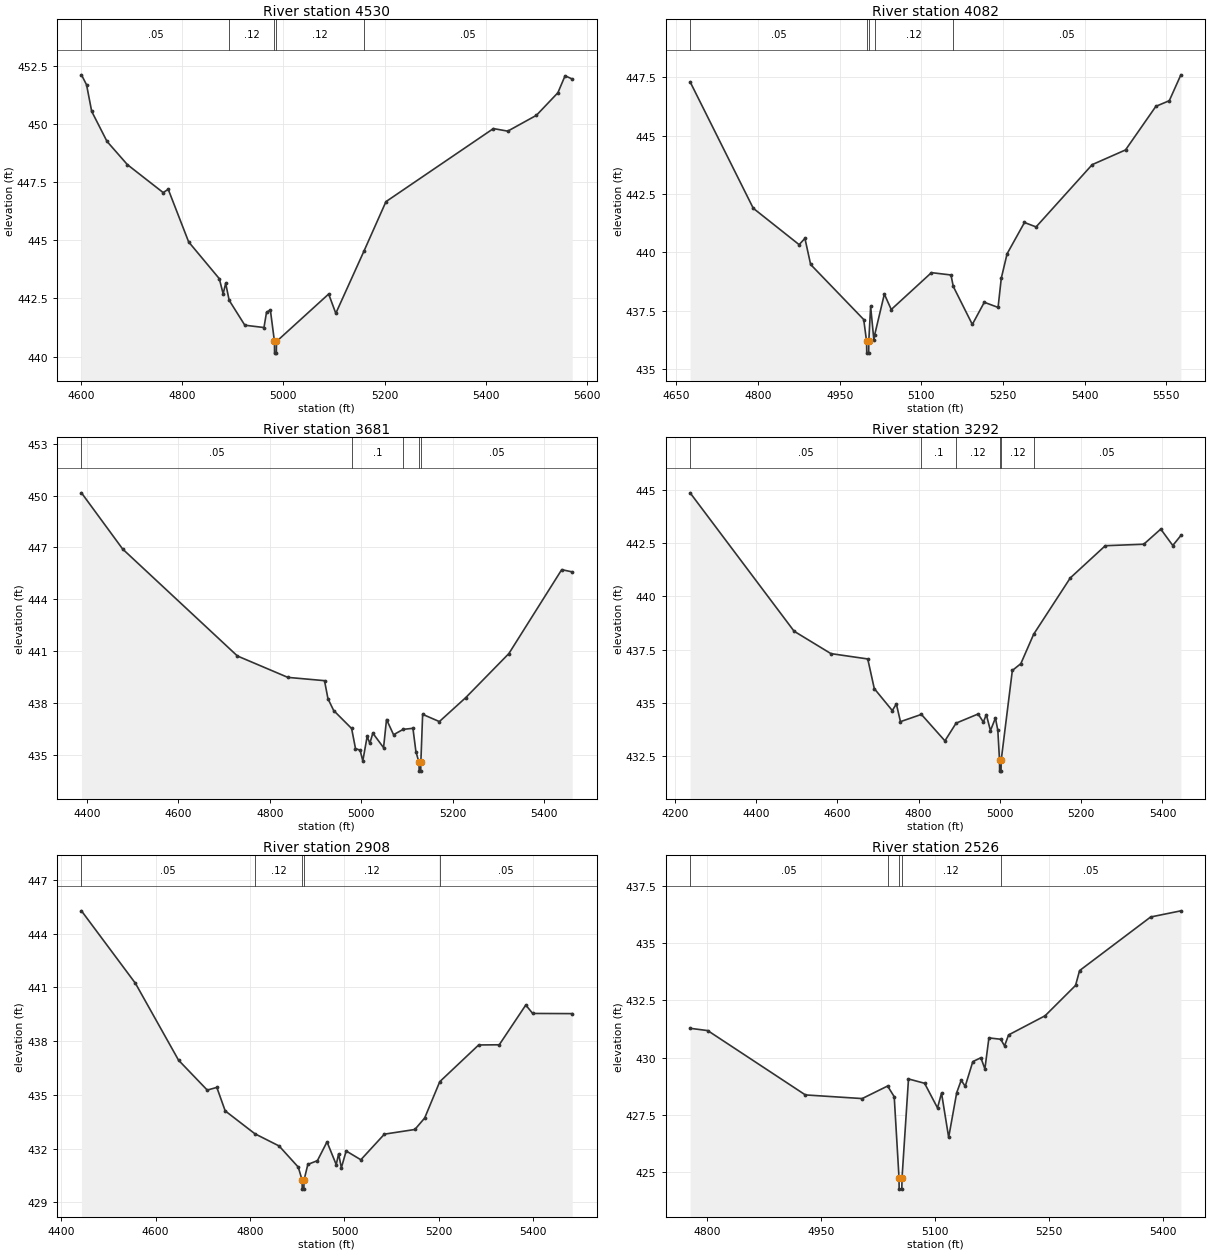
Type RM Length L Ch R = 1,4530,448,448,448
BEGIN DESCRIPTION:
Caney T7 7.0
END DESCRIPTION:
XS GIS Cut Line= 3
      2742426.01      6905011.00      2742026.00      6905061.00
      2741626.00      6905461.00
#Sta/Elev= 30
  4601.3  452.11  4611.4  451.68  4621.5  450.54  4651.7  449.25  4692.0  448.25
  4762.6  447.05  4772.6  447.19  4812.9  444.93  4873.4  443.35  4881.0  442.70
  4886.0  443.15  4892.9  442.42  4923.8  441.35  4961.6  441.25  4966.6  441.90
  4974.2  442.01  4982.3  440.65  4982.5  440.15  4986.0  440.15  4986.3  440.65
  5089.3  442.69  5103.4  441.86  5158.9  444.53  5202.4  446.66  5414.5  449.80
  5442.8  449.69  5499.4  450.37  5541.8  451.34  5556.0  452.07  5570.1  451.93
#Mann=5,-1,0
  4601.3    0.05       0  4892.9    0.12       0  4982.3    0.07       0
  4986.3    0.12       0  5158.9    0.05       0
Bank Sta=4982.3,4986.3
Exp/Cntr=0.3,0.1

Type RM Length L Ch R = 1,4082,401,401,401
BEGIN DESCRIPTION:
Caney T7 6.0
END DESCRIPTION:
XS GIS Cut Line= 3
      2742276.04      6904761.01      2741976.00      6904661.00
      2741426.00      6904861.00
#Sta/Elev= 30
  4675.2  447.31  4791.2  441.89  4875.5  440.33  4886.1  440.60  4896.6  439.48
  4994.1  437.12  4999.4  436.18  4999.7  435.68  5003.2  435.68  5003.4  436.18
  5006.8  437.68  5012.7  436.26  5014.0  436.44  5032.0  438.21  5044.7  437.55
  5118.5  439.13  5154.4  439.03  5158.6  438.54  5193.6  436.91  5215.6  437.86
  5240.9  437.64  5246.8  438.89  5257.5  439.94  5289.4  441.28  5310.7  441.09
  5413.8  443.76  5475.0  444.39  5530.8  446.26  5555.4  446.50  5576.7  447.61
#Mann=5,-1,0
  4675.2    0.05       0  4999.4    0.04       0  5003.4    0.05       0
  5014.0    0.12       0  5158.6    0.05       0
Bank Sta=4999.4,5003.4
Exp/Cntr=0.3,0.1

Type RM Length L Ch R = 1,3681,389,389,389
BEGIN DESCRIPTION:
Caney T7 5.0
END DESCRIPTION:
XS GIS Cut Line= 3
      2742526.00      6904411.00      2741926.00      6904361.00
      2741525.98      6904611.01
#Sta/Elev= 30
  4388.0  450.16  4478.3  446.90  4729.2  440.71  4839.6  439.47  4919.8  439.28
  4927.4  438.23  4939.9  437.55  4979.1  436.51  4987.6  435.35  4997.7  435.25
  5003.6  434.63  5013.1  436.05  5019.0  435.65  5025.5  436.24  5049.0  435.40
  5055.5  437.03  5070.9  436.15  5092.0  436.46  5113.3  436.52  5119.8  435.17
  5126.6  434.54  5126.9  434.04  5130.4  434.04  5130.6  434.54  5134.5  437.33
  5171.1  436.91  5228.9  438.30  5323.2  440.85  5438.8  445.71  5461.8  445.58
#Mann=5,-1,0
  4388.0    0.05       0  4979.1     0.1       0  5092.0    0.05       0
  5126.6    0.07       0  5130.6    0.05       0
Bank Sta=5126.6,5130.6
Exp/Cntr=0.3,0.1

Type RM Length L Ch R = 1,3292,384,384,384
BEGIN DESCRIPTION:
Mapping XS 99e9fc6b
END DESCRIPTION:
XS GIS Cut Line= 3
      2742440.25      6904024.54      2741698.05      6904109.17
      2741322.67      6904376.07
#Sta/Elev= 30
  4237.7  444.85  4493.6  438.36  4584.2  437.31  4674.8  437.06  4690.9  435.67
  4735.2  434.64  4745.2  434.95  4755.3  434.12  4806.8  434.46  4864.7  433.22
  4892.2  434.05  4946.5  434.48  4959.2  434.10  4966.6  434.45  4976.7  433.70
  4989.0  434.29  4994.9  433.71  4999.1  432.30  4999.3  431.80  5002.8  431.80
  5003.1  432.30  5030.6  436.52  5051.5  436.84  5083.1  438.22  5173.2  440.86
  5259.3  442.37  5354.0  442.44  5395.8  443.15  5425.4  442.38  5445.3  442.85
#Mann=6,-1,0
  4237.7    0.05       0  4806.8     0.1       0  4892.2    0.12       0
  4999.1    0.07       0  5003.1    0.12       0  5083.1    0.05       0
Bank Sta=4999.1,5003.1
Exp/Cntr=0.3,0.1

Type RM Length L Ch R = 1,2908,382,382,382
BEGIN DESCRIPTION:
Mapping XS c6960df6
END DESCRIPTION:
XS GIS Cut Line= 3
      2742318.73      6903714.21      2741760.99      6903809.69
      2741383.48      6904096.08
#Sta/Elev= 30
  4442.8  445.28  4557.2  441.23  4648.5  436.94  4709.3  435.27  4729.6  435.42
  4747.3  434.11  4810.3  432.83  4861.5  432.15  4902.1  430.97  4910.3  430.24
  4910.5  429.74  4914.0  429.74  4914.3  430.24  4922.4  431.12  4942.7  431.33
  4963.0  432.38  4982.5  431.11  4987.6  431.71  4993.4  430.93  5003.6  431.87
  5034.7  431.38  5084.6  432.81  5149.1  433.07  5169.9  433.71  5201.9  435.74
  5284.3  437.79  5327.9  437.80  5384.1  440.02  5398.7  439.55  5482.5  439.54
#Mann=5,-1,0
  4442.8    0.05       0  4810.3    0.12       0  4910.3    0.07       0
  4914.3    0.12       0  5201.9    0.05       0
Bank Sta=4910.3,4914.3
Exp/Cntr=0.3,0.1

Type RM Length L Ch R = 1,2526,499,499,499
BEGIN DESCRIPTION:
Mapping XS 2b482b4e
END DESCRIPTION:
XS GIS Cut Line= 3
      2741813.03      6903334.70      2741633.79      6903473.27
      2741496.75      6903870.01
#Sta/Elev= 30
  4777.1  431.28  4800.3  431.18  4928.9  428.36  5003.7  428.20  5037.2  428.75
  5045.9  428.28  5052.2  424.73  5052.4  424.23  5055.9  424.23  5056.2  424.73
  5064.7  429.06  5085.9  428.87  5102.9  427.79  5108.2  428.44  5117.6  426.50
  5128.2  428.46  5134.1  429.00  5139.4  428.74  5149.4  429.82  5160.0  429.99
  5165.3  429.50  5170.6  430.86  5186.1  430.80  5191.2  430.51  5196.5  430.99
  5244.6  431.83  5284.7  433.16  5290.0  433.81  5383.6  436.16  5423.4  436.43
#Mann=5,-1,0
  4777.1    0.05       0  5037.2    0.12       0  5052.2    0.04       0
  5056.2    0.12       0  5186.1    0.05       0
Bank Sta=5052.2,5056.2
Exp/Cntr=0.3,0.1

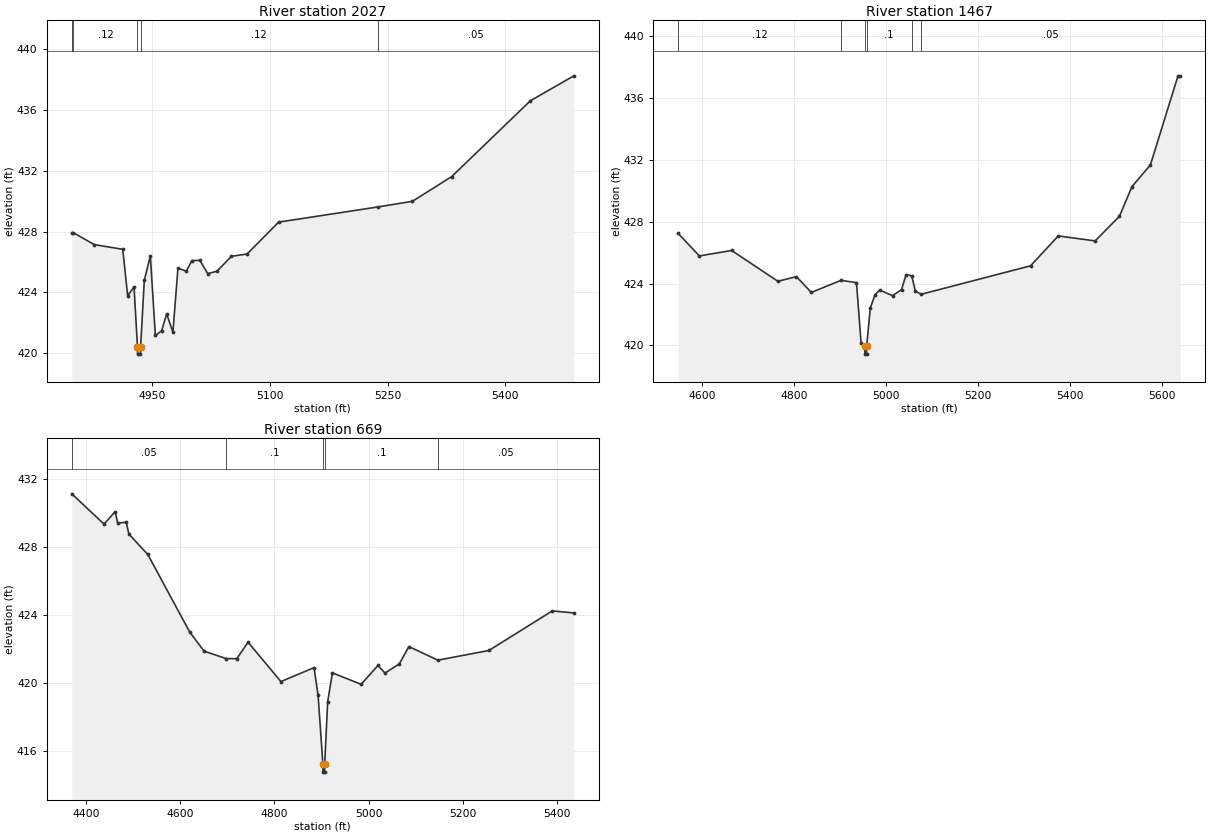
Type RM Length L Ch R = 1,2027,560,560,560
BEGIN DESCRIPTION:
Mapping XS 99a82a9f
END DESCRIPTION:
XS GIS Cut Line= 3
      2741348.46      6903172.90      2741234.11      6903263.70
      2741191.56      6903756.15
#Sta/Elev= 30
  4847.2  427.93  4849.3  427.93  4875.9  427.15  4912.2  426.84  4918.5  423.78
  4926.6  424.36  4931.0  420.44  4931.2  419.94  4934.7  419.94  4935.0  420.44
  4939.7  424.79  4947.4  426.41  4953.8  421.17  4961.8  421.47  4968.2  422.59
  4976.2  421.38  4982.6  425.60  4993.2  425.40  5000.5  426.10  5010.6  426.11
  5020.6  425.24  5032.5  425.40  5050.7  426.38  5070.8  426.53  5111.0  428.63
  5237.8  429.63  5281.6  430.00  5331.8  431.63  5432.1  436.62  5487.5  438.26
#Mann=5,-1,0
  4847.2    0.05       0  4849.3    0.12       0  4931.0    0.07       0
  4935.0    0.12       0  5237.8    0.05       0
Bank Sta=4931,4935
Exp/Cntr=0.3,0.1

Type RM Length L Ch R = 1,1467,798,798,798
BEGIN DESCRIPTION:
Mapping XS 71d0ee5e
END DESCRIPTION:
XS GIS Cut Line= 3
      2741251.58      6903037.68      2740801.75      6902987.73
      2740750.13      6903625.84
#Sta/Elev= 30
  4547.4  427.24  4593.3  425.79  4663.7  426.14  4764.3  424.15  4804.6  424.45
  4837.1  423.43  4901.9  424.21  4935.4  424.06  4945.4  420.16  4953.5  419.94
  4953.7  419.44  4957.2  419.44  4957.5  419.94  4965.5  422.43  4975.6  423.27
  4985.7  423.58  5013.8  423.22  5033.4  423.61  5043.4  424.58  5055.7  424.50
  5063.5  423.51  5076.4  423.31  5314.3  425.15  5374.5  427.08  5454.8  426.76
  5507.7  428.35  5535.0  430.27  5575.1  431.67  5635.2  437.43  5640.2  437.43
#Mann=6,-1,0
  4547.4    0.12       0  4901.9     0.1       0  4953.5    0.07       0
  4957.5     0.1       0  5055.7    0.12       0  5076.4    0.05       0
Bank Sta=4953.5,4957.5
Exp/Cntr=0.3,0.1

Type RM Length L Ch R = 1,669,0,0,0
BEGIN DESCRIPTION:
Caney T7 1.0
END DESCRIPTION:
XS GIS Cut Line= 3
      2740914.62      6902339.54      2740444.58      6902539.01
      2740350.99      6903086.05
#Sta/Elev= 30
  4370.2  431.13  4438.6  429.35  4462.3  430.08  4467.7  429.40  4485.9  429.46
  4491.4  428.76  4531.6  427.56  4620.6  422.99  4651.1  421.87  4698.2  421.43
  4720.6  421.43  4744.3  422.40  4814.1  420.08  4884.4  420.90  4893.0  419.27
  4903.1  415.25  4903.4  414.75  4906.9  414.75  4907.1  415.25  4913.3  418.89
  4923.4  420.59  4984.3  419.92  5020.2  421.03  5035.0  420.58  5065.4  421.12
  5085.7  422.14  5147.1  421.34  5255.5  421.91  5390.1  424.24  5435.8  424.12
#Mann=5,-1,0
  4370.2    0.05       0  4698.2     0.1       0  4903.1    0.07       0
  4907.1     0.1       0  5147.1    0.05       0
Bank Sta=4903.1,4907.1
Exp/Cntr=0.3,0.1

Chan Stop Cuts=-1