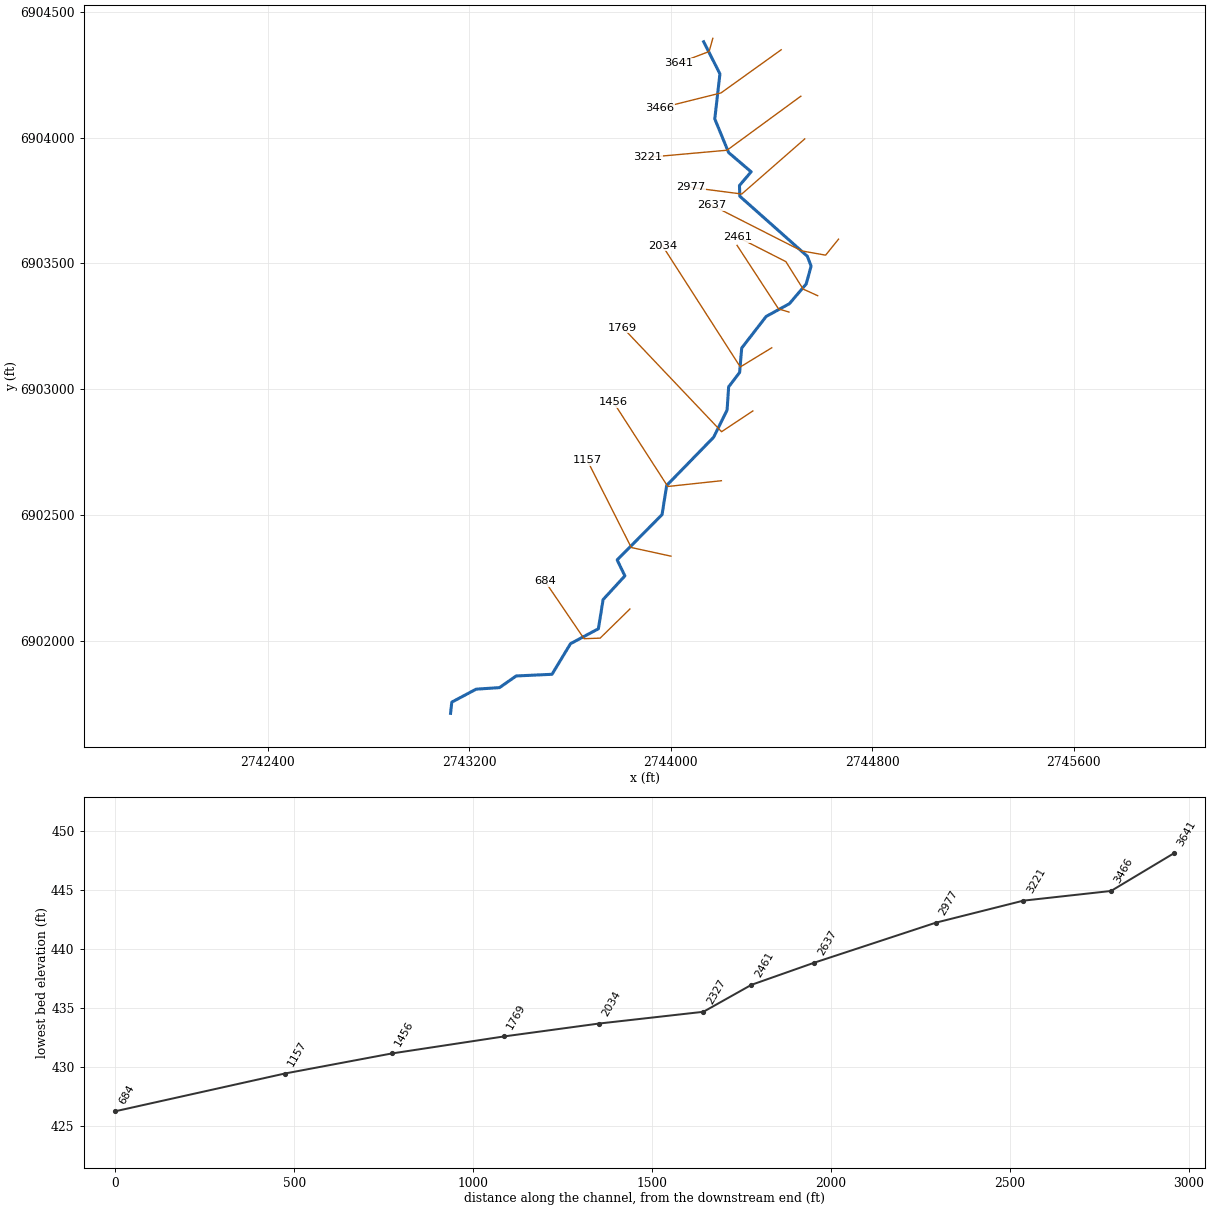
--- Caney T8.prj (project) ---

Proj Title=Caney T8 Base Level Engineering
Current Plan=p01
Default Exp/Contr=0.3,0.1
English Units
Geom File=g01
Flow File=f01
Plan File=p01
Y Axis Title=Elevation
X Axis Title(PF)=Main Channel Distance
X Axis Title(XS)=Station
BEGIN DESCRIPTION:
Caney T8
END DESCRIPTION:
DSS Export Rating Curves= 0
DSS Export Rating Curve Sorted= 0
DSS Export Volume Flow Curves= 0
DXF OffsetX= 0
DXF OffsetY= 0
DXF ScaleX= 1
DXF ScaleY= 10

--- Caney T8.p01 (plan) ---

Plan Title=Multiple Run
Short Identifier=Multiple
Geom File=g01
Flow File=f01
Subcritical Flow
K Sum by GR= 0
Std Step Tol= 0.01
Critical Tol= 0.01
Num of Std Step Trials= 20
Max Error Tol= 0.3
Flow Tol Ratio= 0.001
Split Flow NTrial= 30
Split Flow Tol= 0.02
Split Flow Ratio= 0.02
Log Output Level= 0
Friction Slope Method= 1
Unsteady Friction Slope Method= 2
Unsteady Bridges Friction Slope Method= 1
Parabolic Critical Depth
Global Vel Dist=  1 , 1 , 1
Global Log Level= 0
CheckData=True
Encroach Param= -1, 0, 0, 0
BEGIN DESCRIPTION:
Multiple Run
END DESCRIPTION:

--- Caney T8.f01 (steady flow) ---

Flow Title=Multiple
Number of Profiles=7
Profile Names=10-year,25-year,50-year,1pct_min,100-year,1pct_plu,500-year
River Rch & RM= Caney T8,Reach-1,3641
     143     174     198     112     224     447     286
Boundary for River Rch & Prof#=Caney T8,Reach-1,1
Up Type=0
Dn Type=3
Dn Slope=0.005
Boundary for River Rch & Prof#=Caney T8,Reach-1,2
Up Type=0
Dn Type=3
Dn Slope=0.005
Boundary for River Rch & Prof#=Caney T8,Reach-1,3
Up Type=0
Dn Type=3
Dn Slope=0.005
Boundary for River Rch & Prof#=Caney T8,Reach-1,4
Up Type=0
Dn Type=3
Dn Slope=0.005
Boundary for River Rch & Prof#=Caney T8,Reach-1,5
Up Type=0
Dn Type=3
Dn Slope=0.005
Boundary for River Rch & Prof#=Caney T8,Reach-1,6
Up Type=0
Dn Type=3
Dn Slope=0.005
Boundary for River Rch & Prof#=Caney T8,Reach-1,7
Up Type=0
Dn Type=3
Dn Slope=0.005

--- Caney T8.g01 (geometry) ---

Geom Title=Existing Conditions
Program Version=4.10

River Reach=Caney T8        ,Reach-1
Reach XY= 30
      2744130.69      6904381.14      2744195.22      6904253.65
      2744174.79      6904074.55      2744229.68      6903940.71
      2744319.08      6903864.26      2744272.82       6903809.6
      2744274.22      6903767.02      2744542.07      6903528.59
      2744557.16      6903489.24      2744537.65      6903418.16
      2744470.89      6903339.72      2744378.76      6903289.16
       2744281.6      6903163.37      2744273.53      6903066.57
      2744229.85       6903009.4      2744223.67      6902916.97
      2744170.17       6902808.7      2743983.86      6902617.17
      2743965.48      6902501.21      2743787.24        6902321.
      2743817.98      6902257.67      2743731.55      6902163.42
      2743712.74      6902047.35      2743602.17      6901988.13
       2743528.7      6901866.36      2743386.51      6901859.77
      2743320.43      6901813.47      2743227.55      6901807.21
       2743130.9      6901755.72        2743126.        6901711.

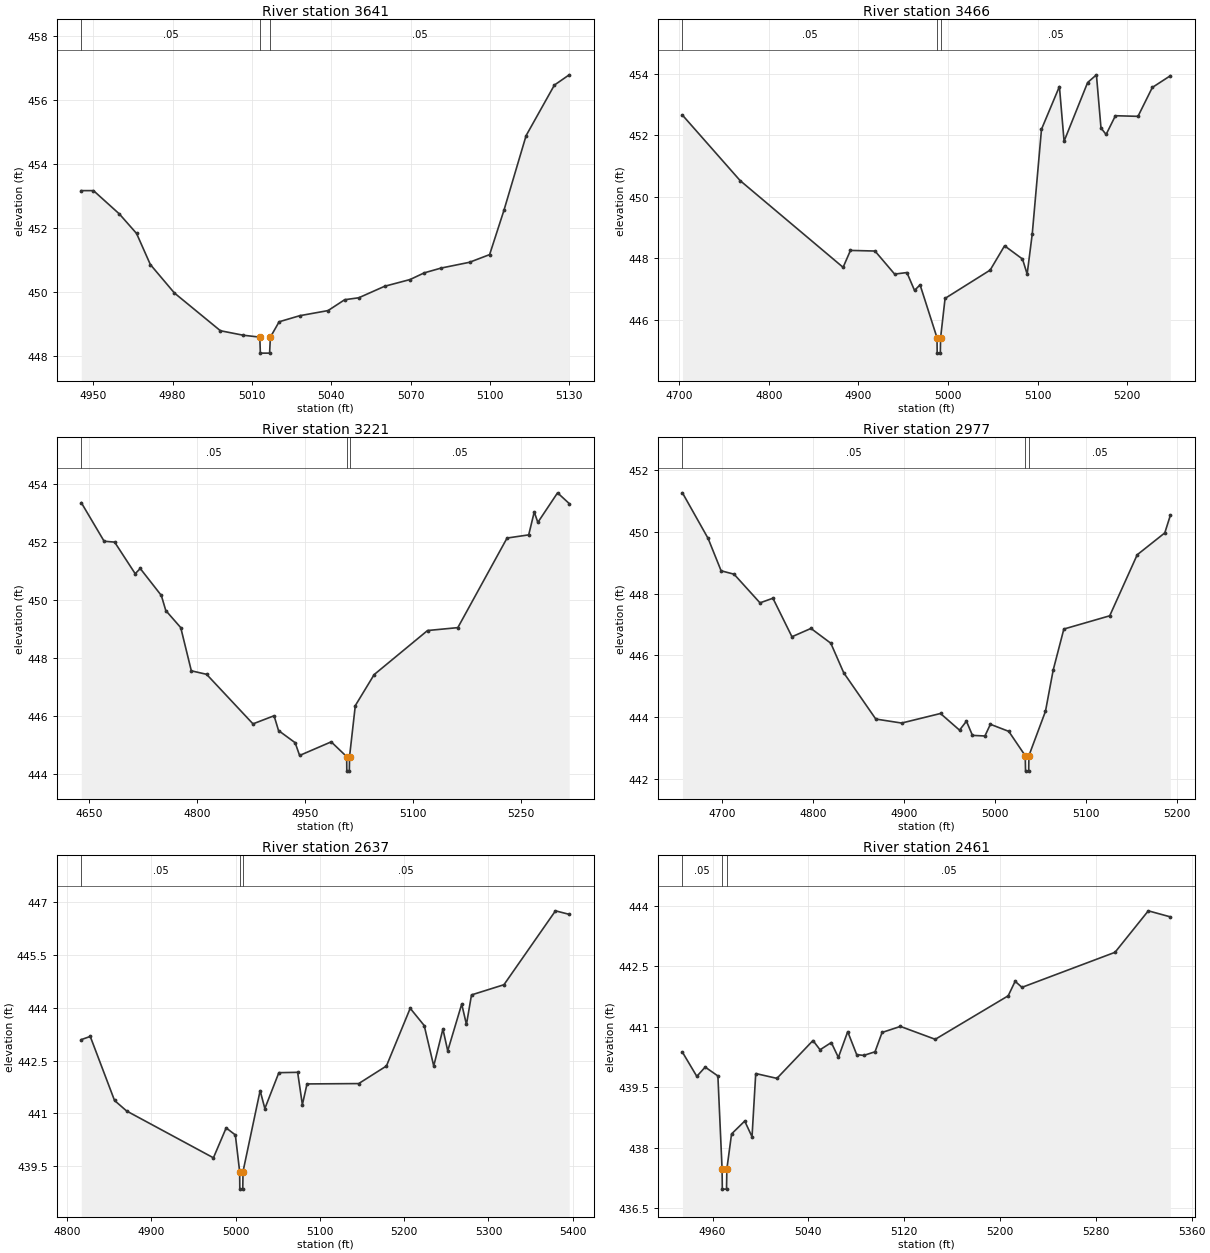
Type RM Length L Ch R = 1 ,3641    ,175,175,175
BEGIN DESCRIPTION:
Caney T8 1.0
END DESCRIPTION:
XS GIS Cut Line= 3
      2744167.01      6904394.86      2744152.28      6904342.39
       2744030.8      6904296.08
#Sta/Elev= 27
  4945.5  453.18  4950.1  453.18  4959.9  452.45  4966.4  451.84  4971.6  450.87
  4980.7  449.98  4998.1   448.8  5006.7  448.66    5013   448.6  5013.2   448.1
  5016.7   448.1    5017   448.6  5020.3  449.08  5028.1  449.27  5038.8  449.43
  5045.1  449.77  5050.4  449.83  5060.2  450.19  5069.8   450.4  5075.2  450.61
  5081.6  450.76  5092.3  450.94  5099.9  451.18  5105.3  452.56  5113.7   454.9
  5124.4  456.48    5130   456.8
#Mann= 3 ,-1 , 0
  4945.5     .05       0    5013     .04       0    5017     .05       0
Bank Sta=5013,5017
XS Rating Curve= 0 ,0
Exp/Cntr=0.3,0.1

Type RM Length L Ch R = 1 ,3466    ,245,245,245
BEGIN DESCRIPTION:
Mapping XS 77b99525
END DESCRIPTION:
XS GIS Cut Line= 3
      2744438.31      6904349.33      2744199.57      6904177.87
      2743956.48       6904117.1
#Sta/Elev= 30
  4703.7  452.66  4768.1  450.53    4883  447.71  4891.2  448.26  4918.6  448.24
  4940.5  447.49  4954.2  447.54  4962.7  446.96  4968.9  447.14  4987.8  445.42
    4988  444.92  4991.5  444.92  4991.8  445.42  4996.8   446.7  5047.1  447.62
  5063.2  448.41  5083.2  447.98  5088.4  447.49  5094.1   448.8  5104.4   452.2
  5124.4  453.59  5129.6  451.81  5155.9  453.72  5165.7  453.97  5170.8  452.24
  5176.5  452.03  5186.9  452.64  5212.1  452.62  5228.1  453.56  5248.2  453.94
#Mann= 3 ,-1 , 0
  4703.7     .05       0  4987.8     .04       0  4991.8     .05       0
Bank Sta=4987.8,4991.8
XS Rating Curve= 0 ,0
Exp/Cntr=0.3,0.1

Type RM Length L Ch R = 1 ,3221    ,244,244,244
BEGIN DESCRIPTION:
Mapping XS b5e8ead8
END DESCRIPTION:
XS GIS Cut Line= 3
      2744516.41      6904164.85      2744223.44      6903950.01
       2743909.9       6903921.9
#Sta/Elev= 30
  4638.9  453.36  4670.6  452.03  4685.2     452  4713.8  450.91  4720.8  451.09
  4750.1  450.16  4756.3  449.64  4777.1  449.05  4791.8  447.56    4813  447.44
  4877.5  445.73  4906.8  446.01    4913   445.5  4936.1  445.08  4942.3  444.64
  4986.2  445.11  5007.7   444.6  5007.9   444.1  5011.4   444.1  5011.7   444.6
  5019.7  446.36  5045.9  447.43  5120.1  448.95  5162.2  449.05  5230.6  452.14
  5260.7  452.25  5268.4  453.04  5273.4  452.68  5300.8   453.7    5317  453.33
#Mann= 3 ,-1 , 0
  4638.9     .05       0  5007.7     .04       0  5011.7     .05       0
Bank Sta=5007.7,5011.7
XS Rating Curve= 0 ,0
Exp/Cntr=0.3,0.1

Type RM Length L Ch R = 1 ,2977    ,340,340,340
BEGIN DESCRIPTION:
Mapping XS 9b78606f
END DESCRIPTION:
XS GIS Cut Line= 3
      2744531.85      6903994.96      2744281.94      6903775.93
      2744079.94      6903802.11
#Sta/Elev= 30
  4656.3  451.27  4684.5  449.79  4698.8  448.74    4713  448.63  4741.5   447.7
  4755.7  447.85  4776.6   446.6  4797.5  446.87  4819.3  446.39  4833.5  445.43
  4868.7  443.93  4897.1   443.8  4939.8  444.11  4960.7  443.57  4968.3  443.86
  4974.9   443.4  4988.6  443.38  4994.6  443.76  5014.8  443.53  5032.9  442.74
  5033.2  442.24  5036.7  442.24  5036.9  442.74  5055.1  444.18  5063.6  445.52
  5075.3  446.85  5125.7  447.28  5155.9  449.26  5186.2  449.97  5192.3  450.54
#Mann= 3 ,-1 , 0
  4656.3     .05       0  5032.9     .04       0  5036.9     .05       0
Bank Sta=5032.9,5036.9
XS Rating Curve= 0 ,0
Exp/Cntr=0.3,0.1

Type RM Length L Ch R = 1 ,2637    ,176,176,176
BEGIN DESCRIPTION:
Mapping XS b1cd34e1
END DESCRIPTION:
XS GIS Cut Line= 5
      2744665.98      6903596.35      2744614.75       6903532.8
       2744520.5      6903549.59      2744438.87      6903590.93
      2744162.76      6903731.51
#Sta/Elev= 30
  4817.1   443.1  4827.7  443.19  4856.5  441.37  4870.9  441.07  4973.8  439.74
  4988.9  440.59  4999.8  440.39  5004.9  439.35  5005.1  438.85  5008.6  438.85
  5008.9  439.35  5029.2  441.65  5034.8  441.14  5051.4  442.16  5073.7  442.17
  5079.3  441.25  5084.8  441.84  5146.1  441.85    5179  442.35  5207.2  443.99
  5223.8   443.5  5235.1  442.35    5246   443.4  5251.7  442.78  5268.3  444.11
  5273.9  443.53  5279.9  444.37  5318.4  444.66  5379.5  446.76  5395.8  446.66
#Mann= 3 ,-1 , 0
  4817.1     .05       0  5004.9     .04       0  5008.9     .05       0
Bank Sta=5004.9,5008.9
XS Rating Curve= 0 ,0
Exp/Cntr=0.3,0.1

Type RM Length L Ch R = 1 ,2461    ,134,134,134
BEGIN DESCRIPTION:
Mapping XS d41a5a1e
END DESCRIPTION:
XS GIS Cut Line= 4
       2744583.3      6903371.64      2744525.48      6903397.96
      2744456.88      6903507.15      2744265.39      6903604.74
#Sta/Elev= 30
  4934.8  440.37  4946.8  439.77  4953.8     440  4964.4  439.78  4967.9  437.47
  4968.1  436.97  4971.6  436.97  4971.9  437.47  4975.8  438.34  4986.8  438.66
  4992.9  438.27    4996  439.84  5013.7  439.72  5043.8  440.66  5049.7  440.43
  5059.1  440.61    5065  440.24  5072.8  440.88  5080.3  440.31  5086.2  440.29
  5095.6  440.38  5101.5  440.86  5116.8  441.01  5145.9  440.69  5206.8  441.77
  5212.6  442.13  5218.3  441.98    5296  442.85  5323.8  443.88  5342.2  443.73
#Mann= 3 ,-1 , 0
  4934.8     .05       0  4967.9     .04       0  4971.9     .05       0
Bank Sta=4967.9,4971.9
XS Rating Curve= 0 ,0
Exp/Cntr=0.3,0.1

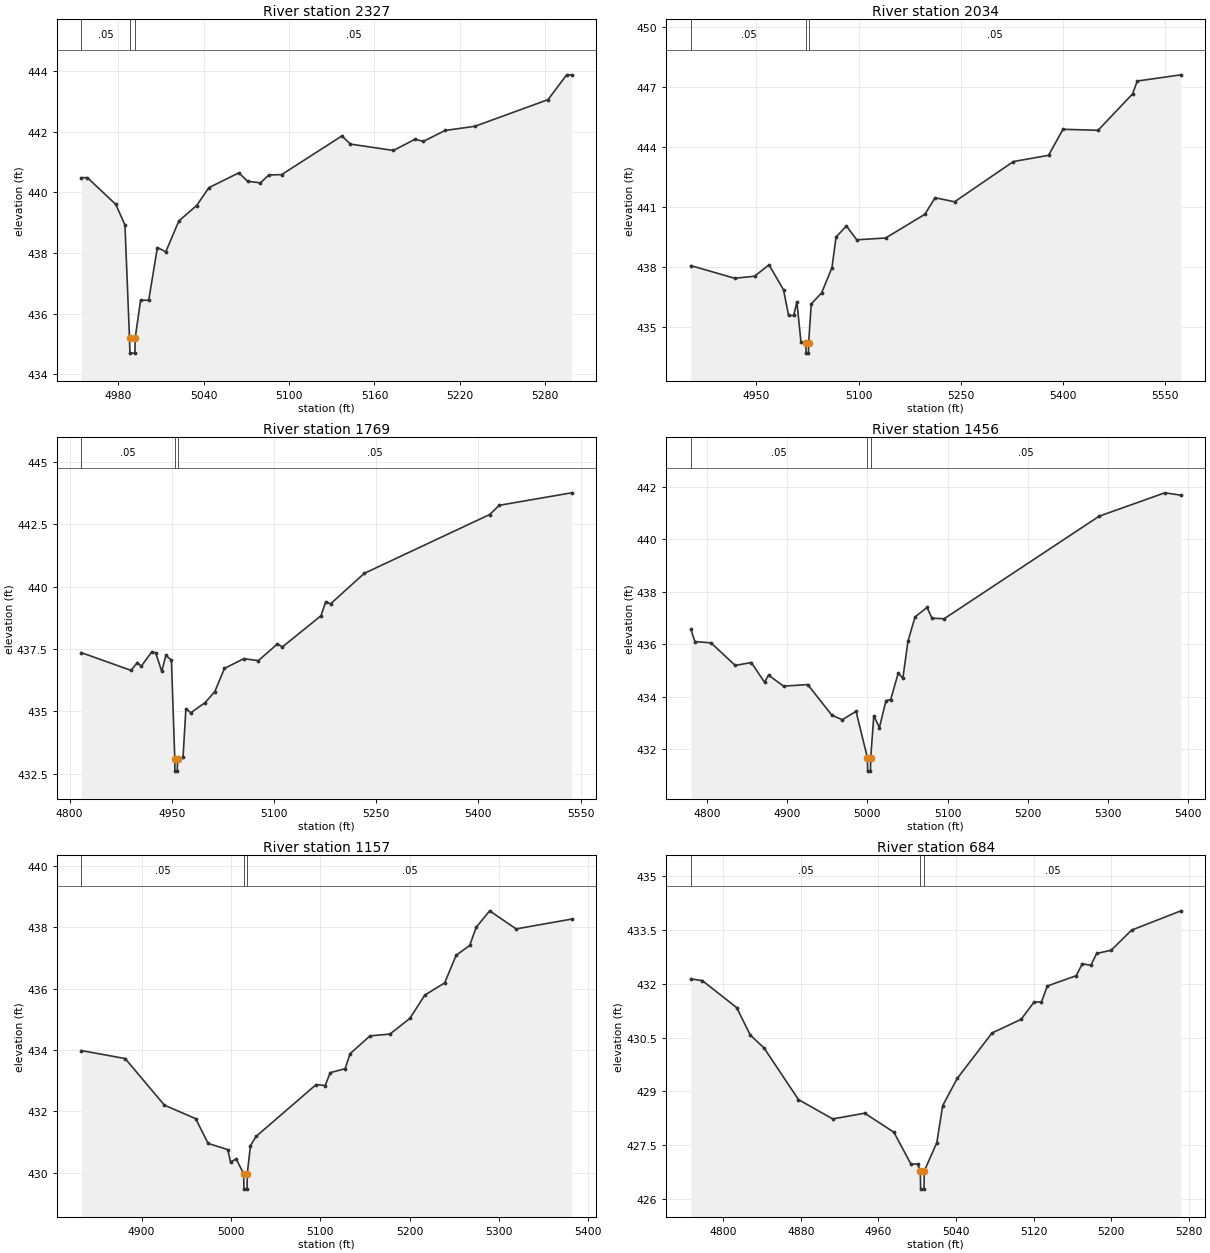
Type RM Length L Ch R = 1 ,2327    ,293,293,293
BEGIN DESCRIPTION:
Mapping XS b2580959
END DESCRIPTION:
XS GIS Cut Line= 3
      2744469.04      6903306.55      2744427.66      6903319.41
      2744263.27      6903571.76
#Sta/Elev= 30
    4954  440.49  4958.2  440.49  4978.1  439.61  4984.6  438.93  4987.8  435.19
  4988.1  434.69  4991.6  434.69  4991.8  435.19  4995.6  436.44  5001.3  436.44
  5007.4  438.18  5013.3  438.04  5022.5  439.06    5035  439.57  5043.6  440.16
  5064.7  440.65  5070.8  440.37  5079.8  440.32  5085.8  440.58  5094.7  440.59
  5137.1  441.87  5143.1   441.6  5173.3  441.39  5188.5  441.76  5194.4  441.69
  5209.6  442.05  5230.7  442.19    5282  443.07  5295.1  443.89  5298.5  443.89
#Mann= 3 ,-1 , 0
    4954     .05       0  4987.8     .04       0  4991.8     .05       0
Bank Sta=4987.8,4991.8
XS Rating Curve= 0 ,0
Exp/Cntr=0.3,0.1

Type RM Length L Ch R = 1 ,2034    ,265,265,265
BEGIN DESCRIPTION:
Mapping XS a2944aeb
END DESCRIPTION:
XS GIS Cut Line= 3
      2744400.97      6903164.61      2744276.06      6903088.25
      2743966.91       6903570.7
#Sta/Elev= 30
  4853.6  438.06    4918  437.43  4947.1  437.53  4968.4   438.1  4989.7  436.85
  4997.1  435.57  5004.6  435.57  5009.3  436.26  5015.2  434.26  5022.5  434.19
  5022.7  433.69  5026.2  433.69  5026.5  434.19  5030.4  436.15  5045.6   436.7
  5060.8  437.96  5066.8  439.49    5082  440.04  5097.2  439.35  5139.5  439.44
    5197  440.62  5212.2  441.45  5240.8  441.25  5327.2  443.26  5378.7  443.57
  5399.9  444.87  5451.4  444.82  5502.1  446.64  5508.9  447.28    5573  447.59
#Mann= 3 ,-1 , 0
  4853.6     .05       0  5022.5     .04       0  5026.5     .05       0
Bank Sta=5022.5,5026.5
XS Rating Curve= 0 ,0
Exp/Cntr=0.3,0.1

Type RM Length L Ch R = 1 ,1769    ,313,313,313
BEGIN DESCRIPTION:
Mapping XS 2a040ce9
END DESCRIPTION:
XS GIS Cut Line= 3
      2744325.98      6902913.48      2744201.84      6902830.83
      2743809.73      6903244.62
#Sta/Elev= 30
  4817.4  437.35  4890.2  436.64  4899.3  436.95  4905.3  436.81  4920.3  437.37
  4926.3  437.35  4935.3   436.6  4941.3  437.24  4949.5  437.05  4954.4   433.1
  4954.6   432.6  4958.1   432.6  4958.4   433.1  4966.5  433.15  4970.7   435.1
    4978  434.94    4999  435.35  5013.2  435.79  5027.3  436.72  5055.7  437.11
    5077  437.03    5105   437.7  5112.3  437.58  5168.9  438.83  5175.8  439.38
  5183.1  439.31  5232.4  440.53  5416.5  442.89  5430.6  443.26  5536.6  443.76
#Mann= 3 ,-1 , 0
  4817.4     .05       0  4954.4     .04       0  4958.4     .05       0
Bank Sta=4954.4,4958.4
XS Rating Curve= 0 ,0
Exp/Cntr=0.3,0.1

Type RM Length L Ch R = 1 ,1456    ,299,299,299
BEGIN DESCRIPTION:
Mapping XS 632217da
END DESCRIPTION:
XS GIS Cut Line= 3
      2744201.04        6902636.       2743988.2      6902613.09
      2743773.05      6902947.48
#Sta/Elev= 30
  4779.6  436.57  4784.7   436.1  4804.8  436.05    4835  435.19  4855.1   435.3
  4871.6  434.55  4876.6  434.82  4895.3   434.4  4925.5  434.46  4955.7  433.29
  4968.6  433.12  4985.8  433.44  5000.1  431.66  5000.3  431.16  5003.8  431.16
  5004.1  431.66    5008  433.27    5015  432.82  5023.2  433.85  5029.1  433.89
  5038.4  434.89  5044.3  434.71  5050.6  436.11  5059.5  437.04  5074.4   437.4
  5080.6  436.99  5095.8  436.97  5289.3  440.88  5371.2  441.77  5391.3  441.68
#Mann= 3 ,-1 , 0
  4779.6     .05       0  5000.1     .04       0  5004.1     .05       0
Bank Sta=5000.1,5004.1
XS Rating Curve= 0 ,0
Exp/Cntr=0.3,0.1

Type RM Length L Ch R = 1 ,1157    ,473,473,473
BEGIN DESCRIPTION:
Mapping XS 8a640338
END DESCRIPTION:
XS GIS Cut Line= 3
      2744000.96      6902336.01      2743843.23      6902370.47
      2743668.96       6902716.4
#Sta/Elev= 30
  4832.6  433.98  4881.6  433.72  4925.5   432.2  4960.5  431.76  4974.5  430.95
  4996.5  430.75  4999.6  430.34  5005.8  430.45  5014.3  429.96  5014.6  429.46
  5018.1  429.46  5018.3  429.96  5021.9  430.88  5028.2  431.18  5095.4  432.87
  5105.6  432.84  5111.2  433.26  5127.9  433.39  5133.5  433.88  5155.8  434.46
  5178.1  434.52  5200.4  435.03  5217.1  435.79  5239.4  436.19  5252.2  437.09
  5267.4  437.41  5274.6     438  5289.7  438.54  5319.4  437.95  5381.4  438.27
#Mann= 3 ,-1 , 0
  4832.6     .05       0  5014.3     .04       0  5018.3     .05       0
Bank Sta=5014.3,5018.3
XS Rating Curve= 0 ,0
Exp/Cntr=0.3,0.1

Type RM Length L Ch R = 1 ,684     ,0,0,0
BEGIN DESCRIPTION:
Caney T8 0.0
END DESCRIPTION:
XS GIS Cut Line= 4
      2743837.86      6902125.91      2743719.68      6902010.09
      2743655.87      6902007.91      2743501.01      6902235.99
#Sta/Elev= 30
  4766.7  432.14  4778.6  432.09  4813.9  431.34    4828  430.57  4842.2  430.21
  4877.6  428.77  4912.9  428.23  4945.9  428.39  4975.9  427.86  4993.5  426.97
  5000.4  426.97  5003.2  426.77  5003.5  426.27    5007  426.27  5007.2  426.77
  5020.2  427.57  5026.2   428.6  5041.2  429.36  5077.1  430.63    5107  431.01
  5120.6   431.5    5128  431.49    5134  431.94  5163.9  432.23    5170  432.56
  5178.9  432.52  5184.9  432.85  5199.9  432.94  5220.8   433.5  5271.7  434.04
#Mann= 3 ,-1 , 0
  4766.7     .05       0  5003.2     .04       0  5007.2     .05       0
Bank Sta=5003.2,5007.2
XS Rating Curve= 0 ,0
Exp/Cntr=0.3,0.1

Chan Stop Cuts=-1
Use User Specified Reach Order=0
Composite Channel Slope=5