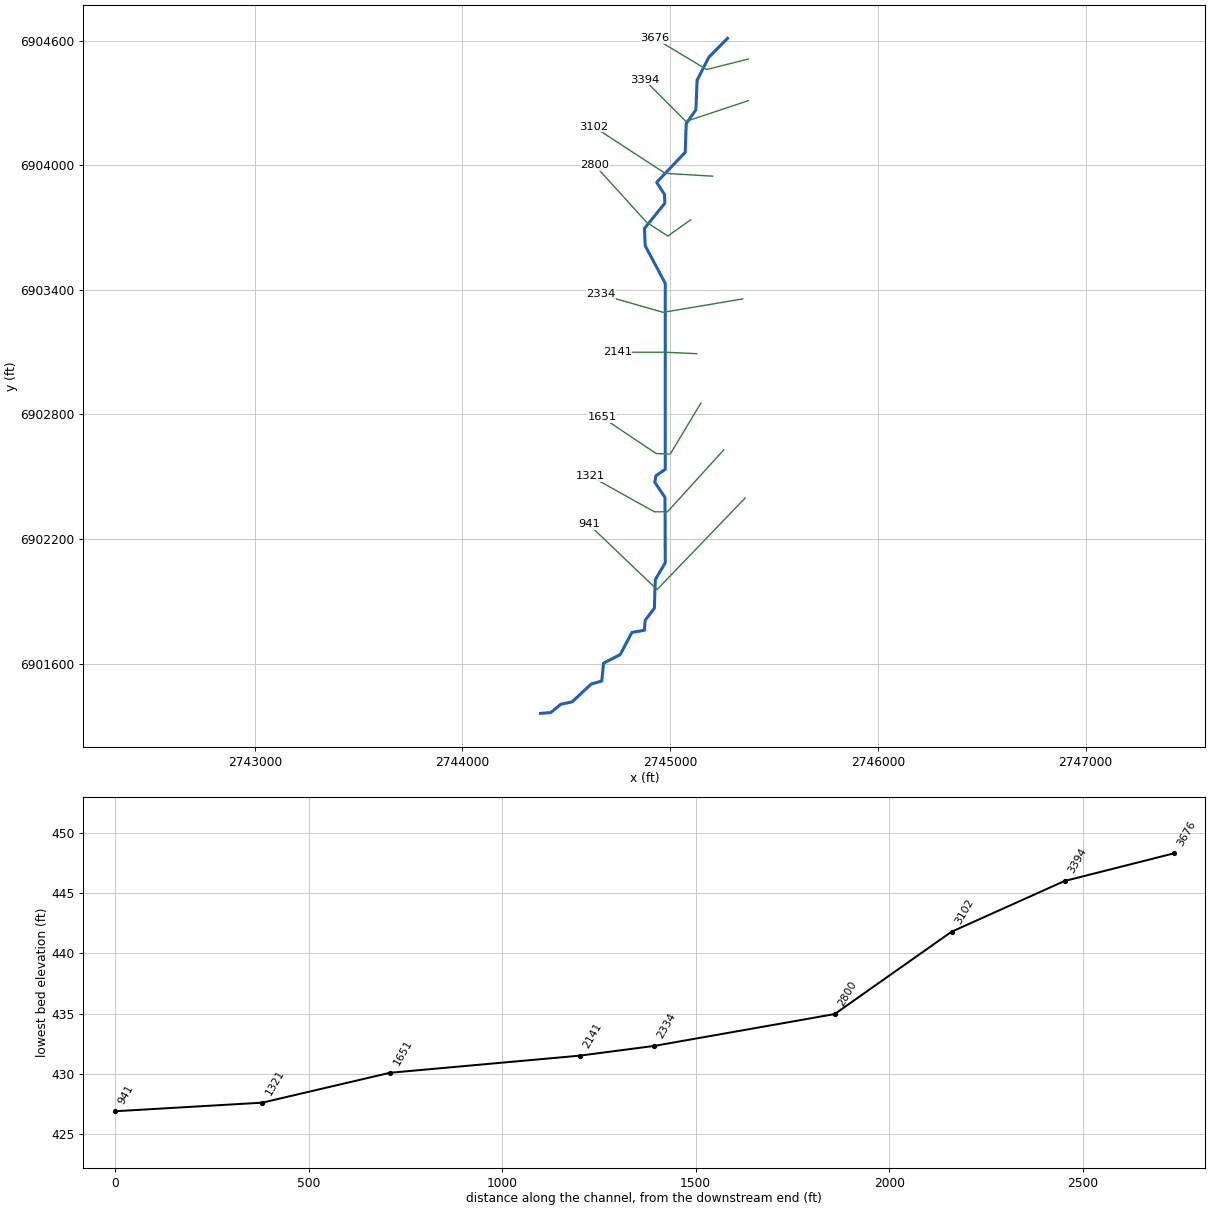
--- Caney T9.prj (project) ---

Proj Title=Caney T9 Base Level Engineering
Current Plan=p01
Default Exp/Contr=0.3,0.1
English Units
Geom File=g01
Flow File=f01
Plan File=p01
Y Axis Title=Elevation
X Axis Title(PF)=Main Channel Distance
X Axis Title(XS)=Station
BEGIN DESCRIPTION:
Caney T9
END DESCRIPTION:
DSS Export Rating Curves= 0
DSS Export Rating Curve Sorted= 0
DSS Export Volume Flow Curves= 0
DXF OffsetX= 0
DXF OffsetY= 0
DXF ScaleX= 1
DXF ScaleY= 10

--- Caney T9.p01 (plan) ---

Plan Title=Multiple Run
Short Identifier=Multiple
Geom File=g01
Flow File=f01
Subcritical Flow
K Sum by GR= 0
Std Step Tol= 0.01
Critical Tol= 0.01
Num of Std Step Trials= 20
Max Error Tol= 0.3
Flow Tol Ratio= 0.001
Split Flow NTrial= 30
Split Flow Tol= 0.02
Split Flow Ratio= 0.02
Log Output Level= 0
Friction Slope Method= 1
Unsteady Friction Slope Method= 2
Unsteady Bridges Friction Slope Method= 1
Parabolic Critical Depth
Global Vel Dist=  1 , 1 , 1
Global Log Level= 0
CheckData=True
Encroach Param= -1, 0, 0, 0
BEGIN DESCRIPTION:
Multiple Run
END DESCRIPTION:

--- Caney T9.f01 (steady flow) ---

Flow Title=Multiple
Number of Profiles=7
Profile Names=10-year,25-year,50-year,1pct_min,100-year,1pct_plu,500-year
River Rch & RM= Caney T9,Reach-1,3676
     257     327     382     223     445     887     601
Boundary for River Rch & Prof#=Caney T9,Reach-1,1
Up Type=0
Dn Type=3
Dn Slope=0.005
Boundary for River Rch & Prof#=Caney T9,Reach-1,2
Up Type=0
Dn Type=3
Dn Slope=0.005
Boundary for River Rch & Prof#=Caney T9,Reach-1,3
Up Type=0
Dn Type=3
Dn Slope=0.005
Boundary for River Rch & Prof#=Caney T9,Reach-1,4
Up Type=0
Dn Type=3
Dn Slope=0.005
Boundary for River Rch & Prof#=Caney T9,Reach-1,5
Up Type=0
Dn Type=3
Dn Slope=0.005
Boundary for River Rch & Prof#=Caney T9,Reach-1,6
Up Type=0
Dn Type=3
Dn Slope=0.005
Boundary for River Rch & Prof#=Caney T9,Reach-1,7
Up Type=0
Dn Type=3
Dn Slope=0.005

--- Caney T9.g01 (geometry) ---

Geom Title=Existing Conditions
Program Version=4.10

River Reach=Caney T9        ,Reach-1
Reach XY= 30
        2745276.        6904611.       2745186.7      6904520.71
      2745129.76      6904409.44      2745123.73      6904266.94
      2745077.23      6904200.49      2745072.46      6904062.47
      2744935.15      6903917.73      2744972.41      6903859.35
      2744974.33      6903817.05      2744876.25      6903695.78
      2744879.67      6903612.59      2744976.36      6903431.15
      2744976.21      6902535.79      2744931.61      6902505.39
      2744925.56      6902474.24      2744975.04       6902400.6
       2744976.2      6902085.92      2744928.27      6902005.06
      2744923.86      6901866.88      2744879.65      6901809.49
        2744876.        6901761.      2744815.75      6901750.67
      2744759.42      6901643.99      2744679.23      6901602.56
      2744670.71      6901516.54       2744620.3      6901502.68
       2744528.3      6901416.83      2744473.76      6901405.03
      2744424.51       6901364.6        2744376.        6901361.

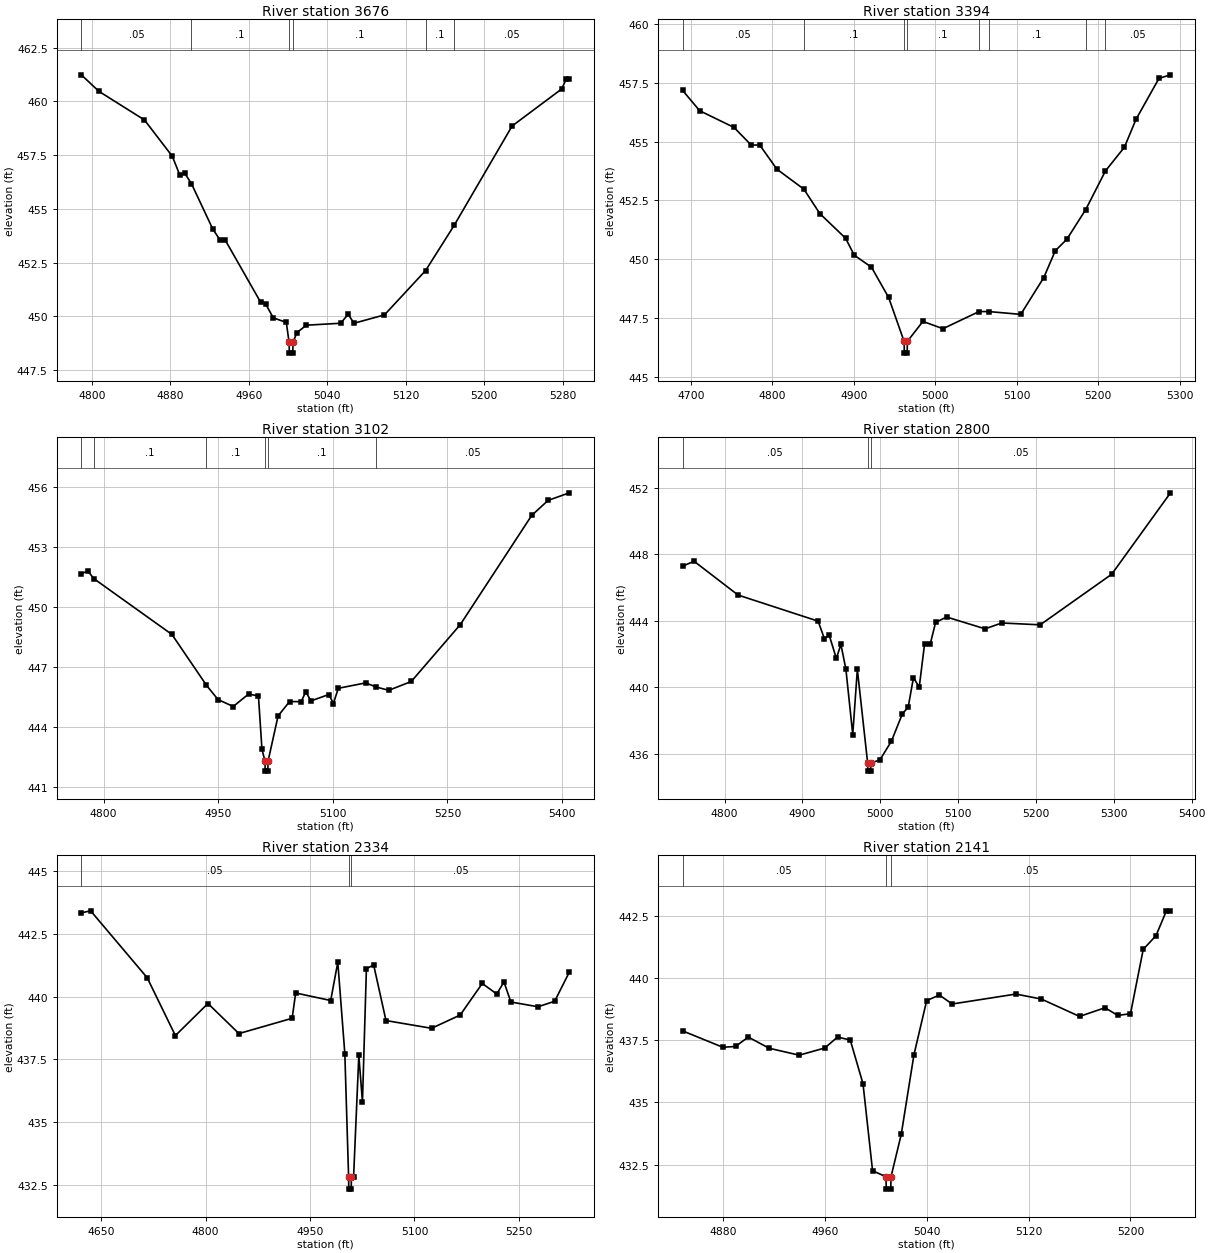
Type RM Length L Ch R = 1 ,3676    ,282,282,282
BEGIN DESCRIPTION:
Caney T9 4.0
END DESCRIPTION:
XS GIS Cut Line= 3
      2745375.99        6904511.        2745176.        6904461.
        2744926.        6904611.
#Sta/Elev= 30
  4789.2  461.24  4807.2  460.47  4853.6  459.14    4882  457.45  4889.7  456.57
  4894.8  456.65  4901.5  456.18  4923.2  454.07  4930.9  453.54  4936.1  453.54
  4972.2  450.65  4977.3  450.57    4985  449.93  4998.3  449.72  5001.1  448.79
  5001.4  448.29  5004.9  448.29  5005.1  448.79    5009  449.24  5018.7  449.59
  5053.7  449.68  5061.4   450.1  5067.3  449.68  5098.4  450.07  5140.3  452.13
  5169.4  454.23  5228.6  458.86  5279.1  460.58    5284  461.06  5286.9  461.06
#Mann= 6 ,-1 , 0
  4789.2     .05       0  4901.5      .1       0  5001.1     .04       0
  5005.1      .1       0  5140.3      .1       0  5169.4     .05       0
Bank Sta=5001.1,5005.1
XS Rating Curve= 0 ,0
Exp/Cntr=0.3,0.1

Type RM Length L Ch R = 1 ,3394    ,292,292,292
BEGIN DESCRIPTION:
Caney T9 3.0
END DESCRIPTION:
XS GIS Cut Line= 3
      2745375.97      6904310.99        2745076.        6904211.
      2744876.03      6904410.97
#Sta/Elev= 30
  4689.6  457.19  4710.7  456.32  4752.8  455.61  4773.9  454.86  4784.4  454.86
  4805.5  453.83  4838.6  452.98  4858.2  451.94  4889.8  450.89  4900.4  450.17
  4921.5  449.66  4942.6  448.37  4961.6   446.5  4961.9     446  4965.4     446
  4965.6   446.5  4984.7  447.35  5009.3  447.04  5053.6  447.77  5065.4  447.77
  5104.8  447.65  5133.1  449.22  5147.2  450.36  5161.4  450.85  5184.5  452.11
  5208.8  453.76  5232.1  454.77  5246.2  455.95  5274.5   457.7  5288.6  457.85
#Mann= 8 ,-1 , 0
  4689.6     .05       0  4838.6      .1       0  4961.6     .04       0
  4965.6      .1       0  5053.6      .1       0  5065.4      .1       0
  5184.5     .12       0  5208.8     .05       0
Bank Sta=4961.6,4965.6
XS Rating Curve= 0 ,0
Exp/Cntr=0.3,0.1

Type RM Length L Ch R = 1 ,3102    ,302,302,302
BEGIN DESCRIPTION:
Caney T9 2.0
END DESCRIPTION:
XS GIS Cut Line= 3
      2745204.44      6903947.33        2744976.        6903961.
      2744632.72      6904184.73
#Sta/Elev= 30
  4770.8  451.65  4779.3   451.8  4787.2  451.41  4889.4  448.62  4934.6  446.08
  4949.6  445.37  4969.6  445.02  4989.6  445.64  5002.6  445.55  5007.2  442.88
  5011.2  442.29  5011.4  441.79  5014.9  441.79  5015.2  442.29  5028.3  444.55
  5043.4  445.27  5058.6  445.26  5064.5  445.76  5071.3   445.3  5094.8  445.62
  5100.7  445.17  5107.1  445.93  5142.9   446.2    5157  445.99  5173.2  445.83
  5202.6  446.27  5266.7  449.11  5360.2  454.57  5381.6  455.32  5409.4   455.7
#Mann= 6 ,-1 , 0
  4770.8     .05       0  4787.2      .1       0  4934.6      .1       0
  5011.2     .04       0  5015.2      .1       0    5157     .05       0
Bank Sta=5011.2,5015.2
XS Rating Curve= 0 ,0
Exp/Cntr=0.3,0.1

Type RM Length L Ch R = 1 ,2800    ,466,466,466
BEGIN DESCRIPTION:
Mapping XS 8fa69876
END DESCRIPTION:
XS GIS Cut Line= 4
      2745098.91      6903737.53      2744988.98      6903659.19
      2744887.71      6903724.29      2744637.97      6903999.34
#Sta/Elev= 30
  4745.9  447.27  4760.7  447.57  4817.2  445.54  4920.1  443.97  4928.3   442.9
  4934.2  443.15  4943.5  441.73  4949.4  442.57  4955.8  441.08  4964.6  437.16
  4970.5  441.07  4983.7  435.46    4984  434.96  4987.5  434.96  4987.7  435.46
  4999.3  435.62  5014.2  436.75  5028.4  438.41  5035.8   438.8  5042.6  440.58
    5050     440  5056.8  442.58  5064.2  442.61    5071  443.89  5085.1  444.22
  5134.5  443.51  5156.1  443.86  5205.4  443.75  5297.3  446.79  5372.8  451.68
#Mann= 3 ,-1 , 0
  4745.9     .05       0  4983.7     .04       0  4987.7     .05       0
Bank Sta=4983.7,4987.7
XS Rating Curve= 0 ,0
Exp/Cntr=0.3,0.1

Type RM Length L Ch R = 1 ,2334    ,193,193,193
BEGIN DESCRIPTION:
Mapping XS 9dc0975d
END DESCRIPTION:
XS GIS Cut Line= 3
      2745349.23      6903356.46      2744966.39      6903291.85
      2744665.77      6903377.73
#Sta/Elev= 30
  4621.5  443.35  4634.9  443.43  4716.1  440.76  4756.6  438.45  4803.4  439.73
  4847.9  438.53  4924.3  439.14  4929.4  440.15  4979.7  439.85  4989.9  441.38
    5000  437.73  5005.4  432.82  5005.7  432.32  5009.2  432.32  5009.4  432.82
  5012.6  432.82  5020.1  437.66  5025.3   435.8    5031  441.12  5041.4  441.27
  5059.1  439.05  5124.6  438.74  5165.7  439.27  5197.4  440.53  5218.2  440.11
  5228.6  440.59  5238.5  439.79  5277.5   439.6  5301.4  439.82  5322.4  440.98
#Mann= 3 ,-1 , 0
  4621.5     .05       0  5005.4     .04       0  5009.4     .05       0
Bank Sta=5005.4,5009.4
XS Rating Curve= 0 ,0
Exp/Cntr=0.3,0.1

Type RM Length L Ch R = 1 ,2141    ,490,490,490
BEGIN DESCRIPTION:
Mapping XS 63ef10dc
END DESCRIPTION:
XS GIS Cut Line= 3
      2745127.55      6903092.75      2744976.01      6903099.85
      2744744.61      6903099.75
#Sta/Elev= 30
  4848.3  437.88  4879.9  437.22  4889.9  437.25  4899.9  437.63  4916.3  437.18
  4939.9   436.9    4960  437.19    4970  437.63    4980  437.51    4990  435.75
  4997.5  432.25    5008  432.01  5008.3  431.51  5011.8  431.51    5012  432.01
    5020  433.71    5030  436.92    5040   439.1    5050  439.32    5060  438.96
    5110  439.36    5130  439.16    5160  438.46    5180  438.81    5190   438.5
    5200  438.57    5210  441.16    5220  441.71  5228.2  442.71  5231.4  442.71
#Mann= 3 ,-1 , 0
  4848.3     .05       0    5008     .04       0    5012     .05       0
Bank Sta=5008,5012
XS Rating Curve= 0 ,0
Exp/Cntr=0.3,0.1

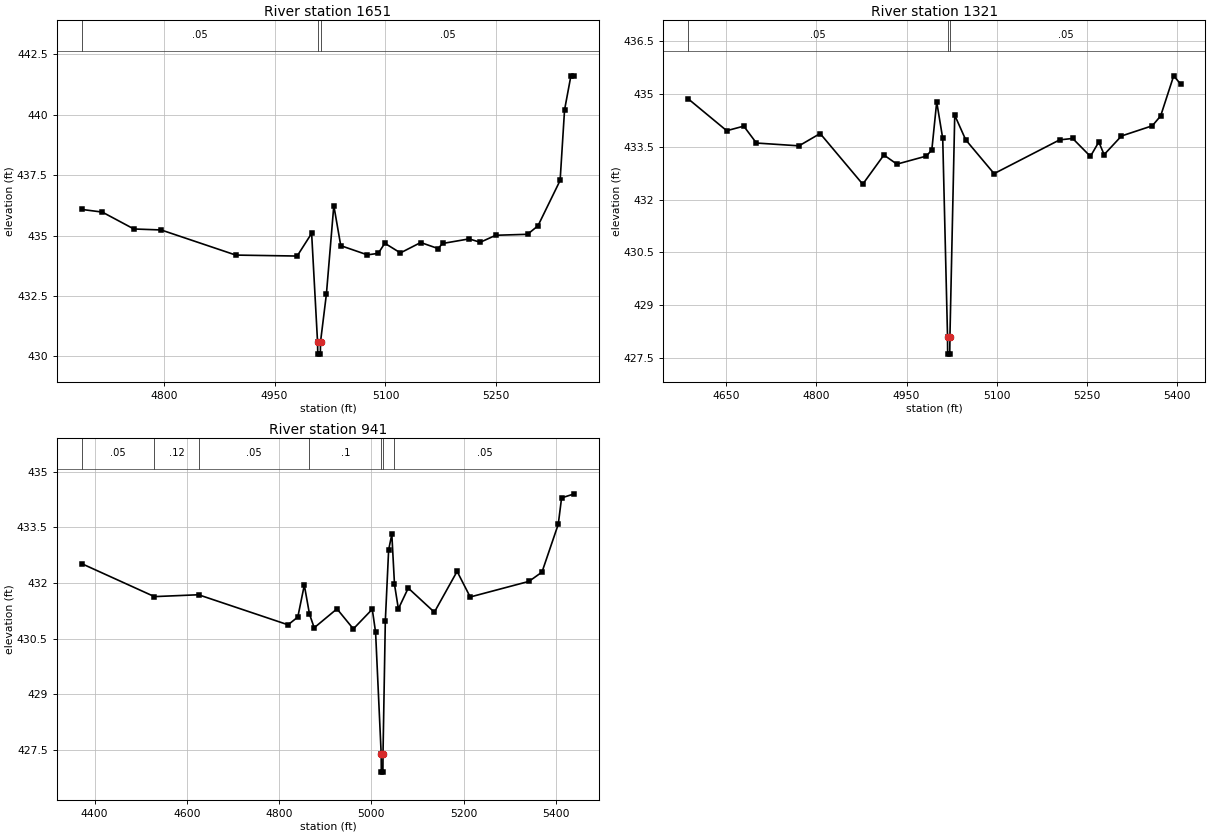
Type RM Length L Ch R = 1 ,1651    ,330,330,330
BEGIN DESCRIPTION:
Mapping XS 1a0a7a5a
END DESCRIPTION:
XS GIS Cut Line= 4
      2745148.23      6902855.42      2745000.18      6902609.43
       2744932.3      6902612.13      2744673.38      6902785.58
#Sta/Elev= 30
  4688.8  436.08  4716.8  435.97  4759.6  435.27  4796.5  435.23  4897.5  434.19
  4980.5  434.15  5000.1  435.09  5008.1  430.59  5008.4  430.09  5011.9  430.09
  5012.1  430.59  5020.1  432.58  5030.1  436.24  5039.5  434.58  5075.5   434.2
  5090.2  434.26  5099.1  434.68  5120.2  434.28  5147.7  434.71  5171.2  434.46
  5177.2  434.67  5213.2  434.86  5228.2  434.72  5249.2  435.01  5292.2  435.05
  5306.3   435.4  5336.3  437.28  5342.3   440.2  5350.9  441.61  5355.5  441.61
#Mann= 3 ,-1 , 0
  4688.8     .05       0  5008.1     .04       0  5012.1     .05       0
Bank Sta=5008.1,5012.1
XS Rating Curve= 0 ,0
Exp/Cntr=0.3,0.1

Type RM Length L Ch R = 1 ,1321    ,380,380,380
BEGIN DESCRIPTION:
Mapping XS 51ad8829
END DESCRIPTION:
XS GIS Cut Line= 4
      2745257.92      6902629.75      2744987.05      6902331.59
      2744924.37      6902331.38      2744614.56      6902503.88
#Sta/Elev= 30
  4586.3  434.87  4650.7  433.96  4679.1  434.09  4700.1  433.61    4771  433.53
  4806.2  433.88  4877.1  432.44  4912.3  433.27  4933.9  433.01  4983.2  433.24
  4992.1  433.42  5000.2  434.78  5010.2  433.74  5018.2  428.11  5018.4  427.61
  5021.9  427.61  5022.2  428.11  5030.2   434.4  5048.5   433.7  5095.7  432.74
  5204.8   433.7  5226.5  433.74    5256  433.23    5270  433.64  5278.8  433.28
  5307.7  433.81    5359   434.1  5372.9  434.38  5394.6  435.52  5406.4  435.28
#Mann= 3 ,-1 , 0
  4586.3     .05       0  5018.2     .04       0  5022.2     .05       0
Bank Sta=5018.2,5022.2
XS Rating Curve= 0 ,0
Exp/Cntr=0.3,0.1

Type RM Length L Ch R = 1 ,941     ,0,0,0
BEGIN DESCRIPTION:
Caney T9 1.0
END DESCRIPTION:
XS GIS Cut Line= 3
      2745361.48      6902398.51      2744936.93      6901956.92
      2744607.41       6902271.6
#Sta/Elev= 30
  4371.8  432.52  4529.7  431.63  4625.4  431.68  4819.5  430.87  4840.6  431.08
  4854.7  431.94  4865.9  431.16  4876.1  430.79  4925.5   431.3    4961  430.76
    5002  431.29  5009.2  430.67  5021.3   427.4  5021.6   426.9  5025.1   426.9
  5025.3   427.4  5030.3  430.97  5037.5  432.89  5044.4  433.31  5050.2  431.96
  5058.6   431.3    5080  431.86  5136.6  431.21  5185.9  432.31  5214.3  431.62
  5341.6  432.04  5369.9  432.29  5405.2  433.58  5412.4  434.29    5440   434.4
#Mann= 7 ,-1 , 0
  4371.8     .05       0  4529.7     .12       0  4625.4     .05       0
  4865.9      .1       0  5021.3     .04       0  5025.3      .1       0
  5050.2     .05       0
Bank Sta=5021.3,5025.3
XS Rating Curve= 0 ,0
Exp/Cntr=0.3,0.1

Chan Stop Cuts=-1
Use User Specified Reach Order=0
Composite Channel Slope=5