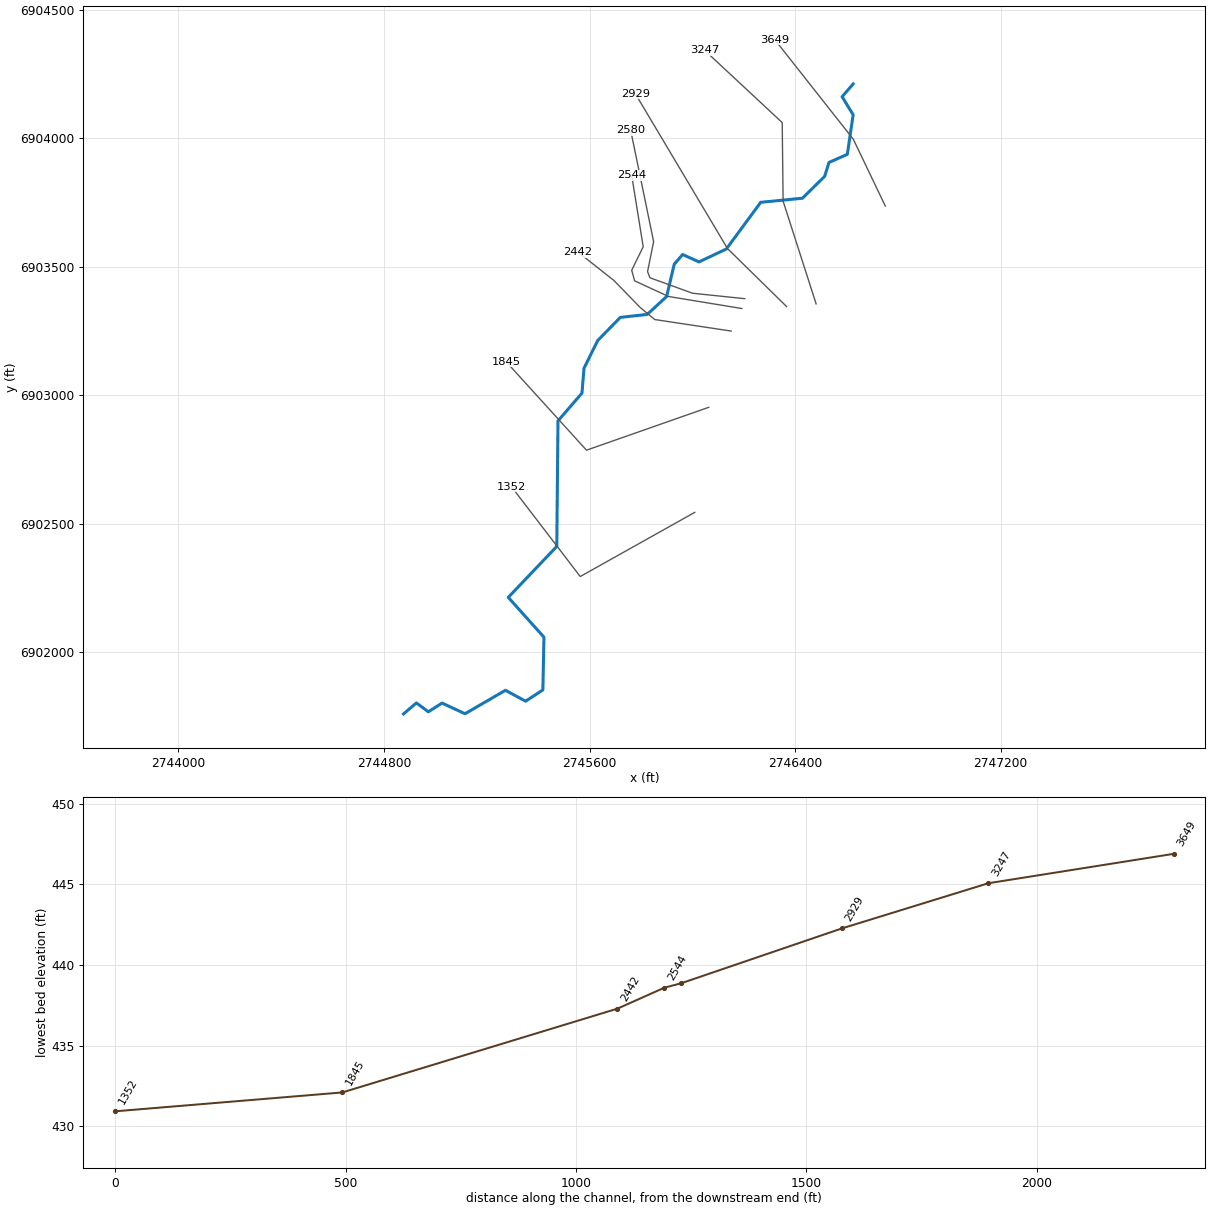
--- Caney T9_1.prj (project) ---

Proj Title=Caney T9_1 Base Level Engineering
Current Plan=p01
Default Exp/Contr=0.3,0.1
English Units
Geom File=g01
Flow File=f01
Plan File=p01
BEGIN DESCRIPTION:
Caney T9_1
END DESCRIPTION:

--- Caney T9_1.p01 (plan) ---

Plan Title=Multiple Run
Short Identifier=Multiple
Geom File=g01
Flow File=f01
Subcritical Flow
K Sum by GR= 0
Std Step Tol= 0.01
Critical Tol= 0.01
Num of Std Step Trials= 20
Max Error Tol= 0.3
Flow Tol Ratio= 0.001
Split Flow NTrial= 30
Split Flow Tol= 0.02
Split Flow Ratio= 0.02
Log Output Level= 0
Friction Slope Method= 1
Unsteady Friction Slope Method= 2
Unsteady Bridges Friction Slope Method= 1
Parabolic Critical Depth
Global Vel Dist=  1 , 1 , 1
Global Log Level= 0
CheckData=True
Encroach Param= -1, 0, 0, 0
BEGIN DESCRIPTION:
Multiple Run
END DESCRIPTION:

--- Caney T9_1.f01 (steady flow) ---

Flow Title=Multiple
Number of Profiles=7
Profile Names=10-year,25-year,50-year,1pct_min,100-year,1pct_plu,500-year
River Rch & RM= Caney T9_1,Reach-1,3649
     194     242     279     160     320     638     420
Boundary for River Rch & Prof#=Caney T9_1,Reach-1,1
Up Type=0
Dn Type=3
Dn Slope=0.005
Boundary for River Rch & Prof#=Caney T9_1,Reach-1,2
Up Type=0
Dn Type=3
Dn Slope=0.005
Boundary for River Rch & Prof#=Caney T9_1,Reach-1,3
Up Type=0
Dn Type=3
Dn Slope=0.005
Boundary for River Rch & Prof#=Caney T9_1,Reach-1,4
Up Type=0
Dn Type=3
Dn Slope=0.005
Boundary for River Rch & Prof#=Caney T9_1,Reach-1,5
Up Type=0
Dn Type=3
Dn Slope=0.005
Boundary for River Rch & Prof#=Caney T9_1,Reach-1,6
Up Type=0
Dn Type=3
Dn Slope=0.005
Boundary for River Rch & Prof#=Caney T9_1,Reach-1,7
Up Type=0
Dn Type=3
Dn Slope=0.005

--- Caney T9_1.g01 (geometry) ---

Geom Title=Existing Conditions

River Reach=Caney T9_1,Reach-1
Reach XY= 30
      2746626.00      6904211.00      2746582.91      6904161.14
      2746625.88      6904091.01      2746603.18      6903937.15
      2746531.65      6903905.36      2746515.12      6903851.56
      2746428.46      6903766.46      2746266.18      6903750.53
      2746132.33      6903569.00      2746025.90      6903518.78
      2745962.25      6903547.53      2745929.61      6903509.97
      2745899.85      6903384.07      2745824.51      6903314.61
      2745719.81      6903303.14      2745631.82      6903213.31
      2745578.33      6903105.03      2745570.46      6903008.58
      2745477.06      6902900.56      2745472.46      6902412.46
      2745283.59      6902214.33      2745422.46      6902059.54
      2745418.31      6901854.43      2745351.10      6901810.55
      2745272.69      6901852.93      2745115.30      6901761.80
      2745025.91      6901803.19      2744972.66      6901769.36
      2744926.00      6901803.79      2744876.00      6901761.00

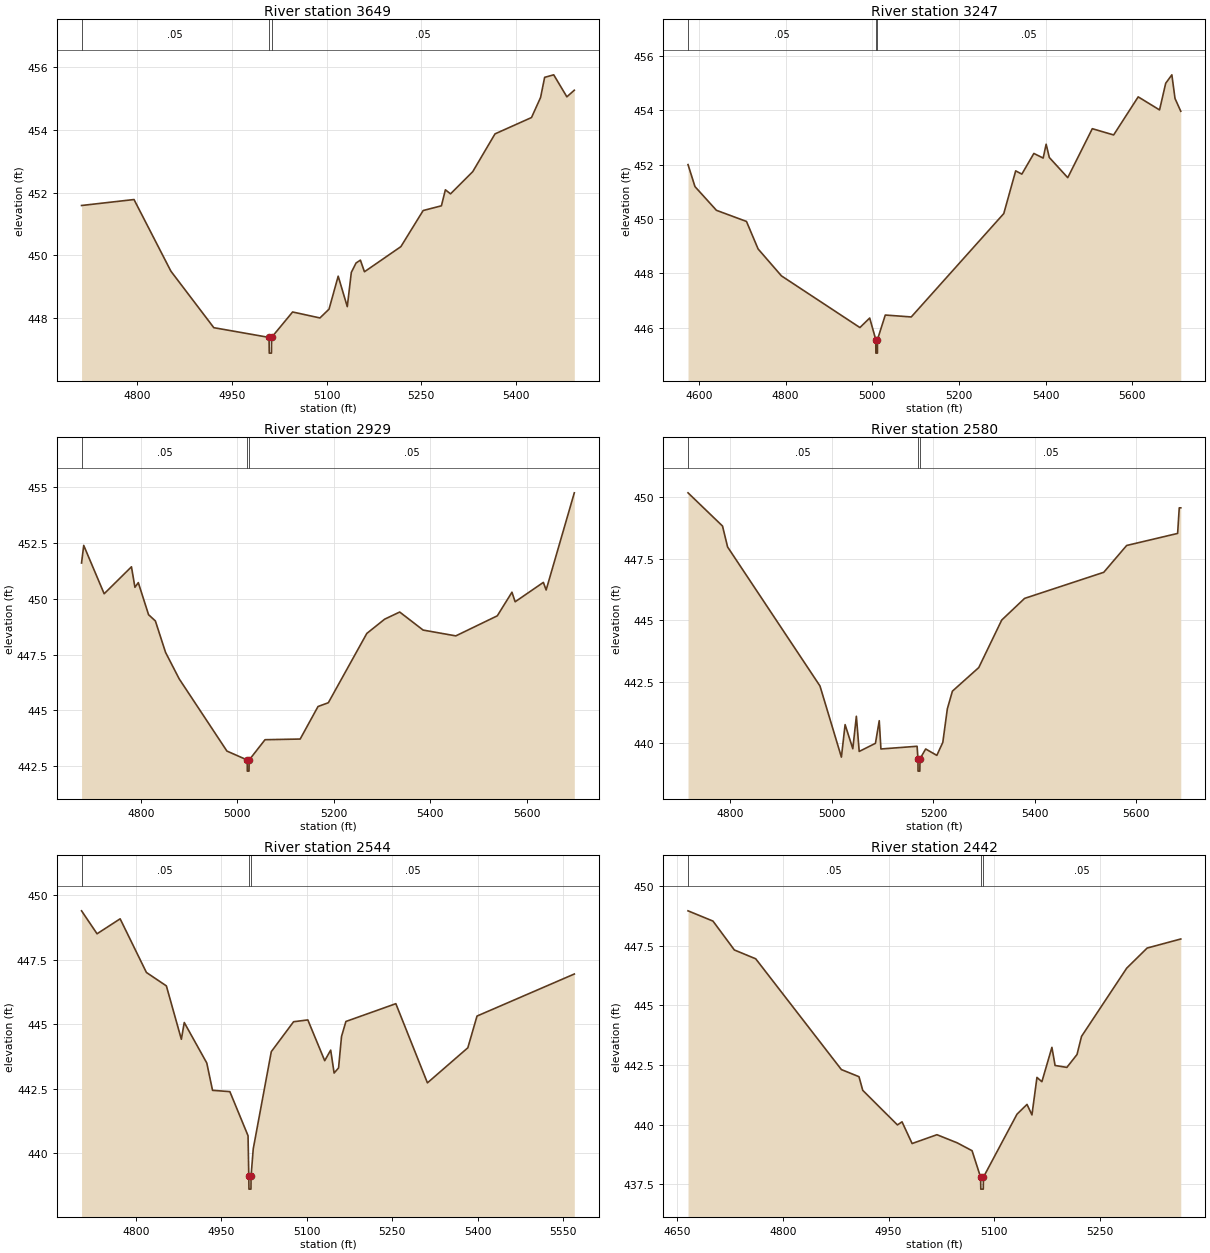
Type RM Length L Ch R = 1,3649,402,402,402
BEGIN DESCRIPTION:
Caney T9_1 1.0
END DESCRIPTION:
XS GIS Cut Line= 3
      2746750.99      6903736.03      2746626.55      6903995.76
      2746321.47      6904382.39
#Sta/Elev= 30
  4712.0  451.59  4795.1  451.78  4853.5  449.50  4921.5  447.70  5009.0  447.39
  5009.3  446.89  5012.8  446.89  5013.0  447.39  5046.3  448.20  5089.6  448.01
  5104.0  448.29  5118.5  449.34  5132.9  448.37  5139.3  449.46  5146.8  449.76
  5153.7  449.85  5160.1  449.48  5217.8  450.28  5253.1  451.43  5282.0  451.58
  5288.3  452.09  5296.4  451.96  5331.7  452.67  5366.9  453.87  5424.7  454.39
  5439.1  455.03  5445.5  455.67  5459.9  455.75  5480.7  455.05  5492.5  455.26
#Mann=3,-1,0
  4712.0    0.05       0  5009.0    0.04       0  5013.0    0.05       0
Bank Sta=5009,5013
Exp/Cntr=0.3,0.1

Type RM Length L Ch R = 1,3247,318,318,318
BEGIN DESCRIPTION:
Mapping XS fd04b764
END DESCRIPTION:
XS GIS Cut Line= 4
      2746481.76      6903355.64      2746353.28      6903754.97
      2746349.81      6904060.52      2746047.73      6904341.77
#Sta/Elev= 30
  4574.5  452.00  4590.6  451.19  4640.1  450.32  4709.5  449.91  4736.3  448.90
  4790.2  447.91  4971.4  446.01  4994.0  446.36  5008.0  445.57  5008.3  445.07
  5011.8  445.07  5012.0  445.57  5030.0  446.47  5090.0  446.40  5303.6  450.20
  5331.1  451.77  5345.3  451.65  5373.1  452.41  5394.6  452.24  5401.4  452.75
  5408.8  452.26  5451.3  451.52  5508.0  453.32  5557.3  453.09  5614.0  454.49
  5663.3  454.01  5677.5  454.99  5691.7  455.30  5699.0  454.43  5712.3  453.96
#Mann=3,-1,0
  4574.5    0.05       0  5008.0    0.04       0  5012.0    0.05       0
Bank Sta=5008,5012
Exp/Cntr=0.3,0.1

Type RM Length L Ch R = 1,2929,349,349,349
BEGIN DESCRIPTION:
Mapping XS e3ddfa6c
END DESCRIPTION:
XS GIS Cut Line= 3
      2746366.70      6903345.27      2746136.70      6903570.94
      2745778.63      6904172.05
#Sta/Elev= 30
  4676.8  451.61  4681.3  452.40  4723.7  450.23  4780.3  451.44  4787.5  450.52
  4794.5  450.73  4815.8  449.29  4829.9  449.01  4851.0  447.60  4879.3  446.41
  4978.3  443.17  5020.4  442.77  5020.6  442.27  5024.1  442.27  5024.4  442.77
  5057.3  443.68  5130.2  443.71  5167.2  445.17  5188.6  445.34  5268.4  448.45
  5305.4  449.09  5336.6  449.41  5385.2  448.60  5453.0  448.34  5539.0  449.24
  5569.4  450.30  5576.0  449.87  5634.5  450.74  5640.3  450.40  5698.7  454.76
#Mann=3,-1,0
  4676.8    0.05       0  5020.4    0.04       0  5024.4    0.05       0
Bank Sta=5020.4,5024.4
Exp/Cntr=0.3,0.1

Type RM Length L Ch R = 1,2580,36,36,36
BEGIN DESCRIPTION:
Mapping XS 41dfde9a
END DESCRIPTION:
XS GIS Cut Line= 6
      2746203.62      6903375.86      2746000.80      6903396.96
      2745835.14      6903457.05      2745825.76      6903481.07
      2745849.35      6903597.67      2745759.74      6904031.94
#Sta/Elev= 30
  4716.4  450.18  4784.4  448.83  4794.4  447.98  4976.5  442.33  5018.7  439.44
  5026.0  440.76  5041.2  439.78  5048.2  441.10  5053.8  439.67  5085.8  440.00
  5093.3  440.92  5096.6  439.77  5167.9  439.88  5169.6  439.37  5169.8  438.87
  5173.3  438.87  5173.6  439.37  5184.8  439.77  5206.8  439.51  5218.6  440.04
  5227.5  441.40  5237.5  442.12  5289.5  443.08  5334.7  445.01  5379.8  445.89
  5535.8  446.95  5580.9  448.04  5681.4  448.53  5684.6  449.57  5687.6  449.57
#Mann=3,-1,0
  4716.4    0.05       0  5169.6    0.04       0  5173.6    0.05       0
Bank Sta=5169.6,5173.6
Exp/Cntr=0.3,0.1

Type RM Length L Ch R = 1,2544,102,102,102
BEGIN DESCRIPTION:
Mapping XS 682bdded
END DESCRIPTION:
XS GIS Cut Line= 6
      2746192.80      6903337.50      2745907.26      6903384.32
      2745775.30      6903445.22      2745764.05      6903486.52
      2745808.78      6903577.64      2745763.98      6903855.43
#Sta/Elev= 30
  4704.9  449.39  4732.1  448.50  4772.6  449.08  4818.7  447.00  4853.7  446.48
  4880.0  444.41  4885.1  445.06  4924.6  443.49  4934.7  442.43  4965.1  442.38
  4997.0  440.67  4998.3  439.10  4998.6  438.60  5002.1  438.60  5002.3  439.10
  5006.1  440.16  5037.8  443.93  5076.9  445.09  5101.9  445.16  5131.5  443.58
  5142.0  443.99  5148.0  443.10  5155.8  443.30  5161.0  444.52  5168.7  445.10
  5256.3  445.79  5311.7  442.72  5382.6  444.08  5398.7  445.31  5569.4  446.94
#Mann=3,-1,0
  4704.9    0.05       0  4998.3    0.04       0  5002.3    0.05       0
Bank Sta=4998.3,5002.3
Exp/Cntr=0.3,0.1

Type RM Length L Ch R = 1,2442,597,597,597
BEGIN DESCRIPTION:
Mapping XS 49a0e720
END DESCRIPTION:
XS GIS Cut Line= 5
      2746150.97      6903249.90      2745853.70      6903294.71
      2745796.85      6903341.83      2745694.62      6903446.75
      2745555.20      6903556.83
#Sta/Elev= 30
  4665.7  448.96  4701.1  448.53  4731.4  447.32  4761.7  446.95  4883.1  442.31
  4908.1  442.01  4913.4  441.44  4962.6  439.99  4969.1  440.12  4983.4  439.21
  5018.6  439.58  5047.3  439.24  5068.4  438.91  5080.5  437.80  5080.8  437.30
  5084.3  437.30  5084.5  437.80  5132.1  440.44  5146.3  440.85  5153.3  440.41
  5160.4  441.98  5167.4  441.80  5181.6  443.24  5186.1  442.48  5202.8  442.40
  5217.2  442.94  5223.6  443.70  5287.7  446.56  5316.6  447.40  5364.3  447.78
#Mann=3,-1,0
  4665.7    0.05       0  5080.5    0.04       0  5084.5    0.05       0
Bank Sta=5080.5,5084.5
Exp/Cntr=0.3,0.1

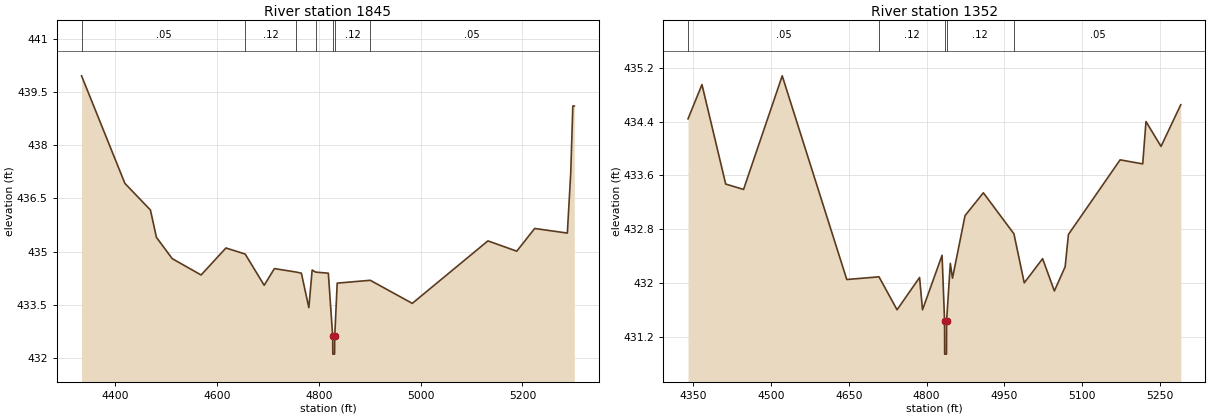
Type RM Length L Ch R = 1,1845,493,493,493
BEGIN DESCRIPTION:
Mapping XS 07818170
END DESCRIPTION:
XS GIS Cut Line= 3
      2746063.80      6902953.33      2745588.09      6902786.65
      2745275.61      6903130.38
#Sta/Elev= 30
  4333.3  439.95  4418.5  436.92  4468.7  436.17  4480.5  435.40  4511.5  434.80
  4568.3  434.34  4617.1  435.10  4654.9  434.93  4692.3  434.05  4712.4  434.52
  4755.7  434.42  4765.4  434.39  4780.1  433.42  4786.6  434.48  4793.7  434.42
  4818.4  434.39  4827.0  432.61  4827.2  432.11  4830.7  432.11  4831.0  432.61
  4835.8  434.11  4900.8  434.19  4983.4  433.54  5132.1  435.30  5188.8  435.01
  5224.0  435.65  5288.2  435.52  5294.9  437.22  5299.0  439.10  5301.9  439.10
#Mann=7,-1,0
  4333.3    0.05       0  4654.9    0.12       0  4755.7    0.05       0
  4793.7    0.12       0  4827.0    0.04       0  4831.0    0.12       0
  4900.8    0.05       0
Bank Sta=4827,4831
Exp/Cntr=0.3,0.1

Type RM Length L Ch R = 1,1352,0,0,0
BEGIN DESCRIPTION:
Caney T9_1 0.0
END DESCRIPTION:
XS GIS Cut Line= 3
      2746009.44      6902544.85      2745563.78      6902295.33
      2745296.35      6902644.29
#Sta/Elev= 30
  4339.9  434.44  4366.8  434.95  4412.6  433.47  4447.0  433.39  4521.6  435.08
  4646.1  432.05  4708.2  432.09  4743.1  431.60  4786.5  432.08  4792.2  431.60
  4829.9  432.41  4834.7  431.44  4834.9  430.94  4838.4  430.94  4838.7  431.44
  4845.8  432.29  4850.0  432.07  4874.2  433.00  4909.5  433.34  4968.5  432.73
  4988.4  432.00  5023.8  432.36  5046.5  431.88  5067.3  432.24  5073.6  432.72
  5173.3  433.83  5216.9  433.77  5223.2  434.40  5252.2  434.03  5290.3  434.65
#Mann=5,-1,0
  4339.9    0.05       0  4708.2    0.12       0  4834.7    0.04       0
  4838.7    0.12       0  4968.5    0.05       0
Bank Sta=4834.7,4838.7
Exp/Cntr=0.3,0.1

Chan Stop Cuts=-1