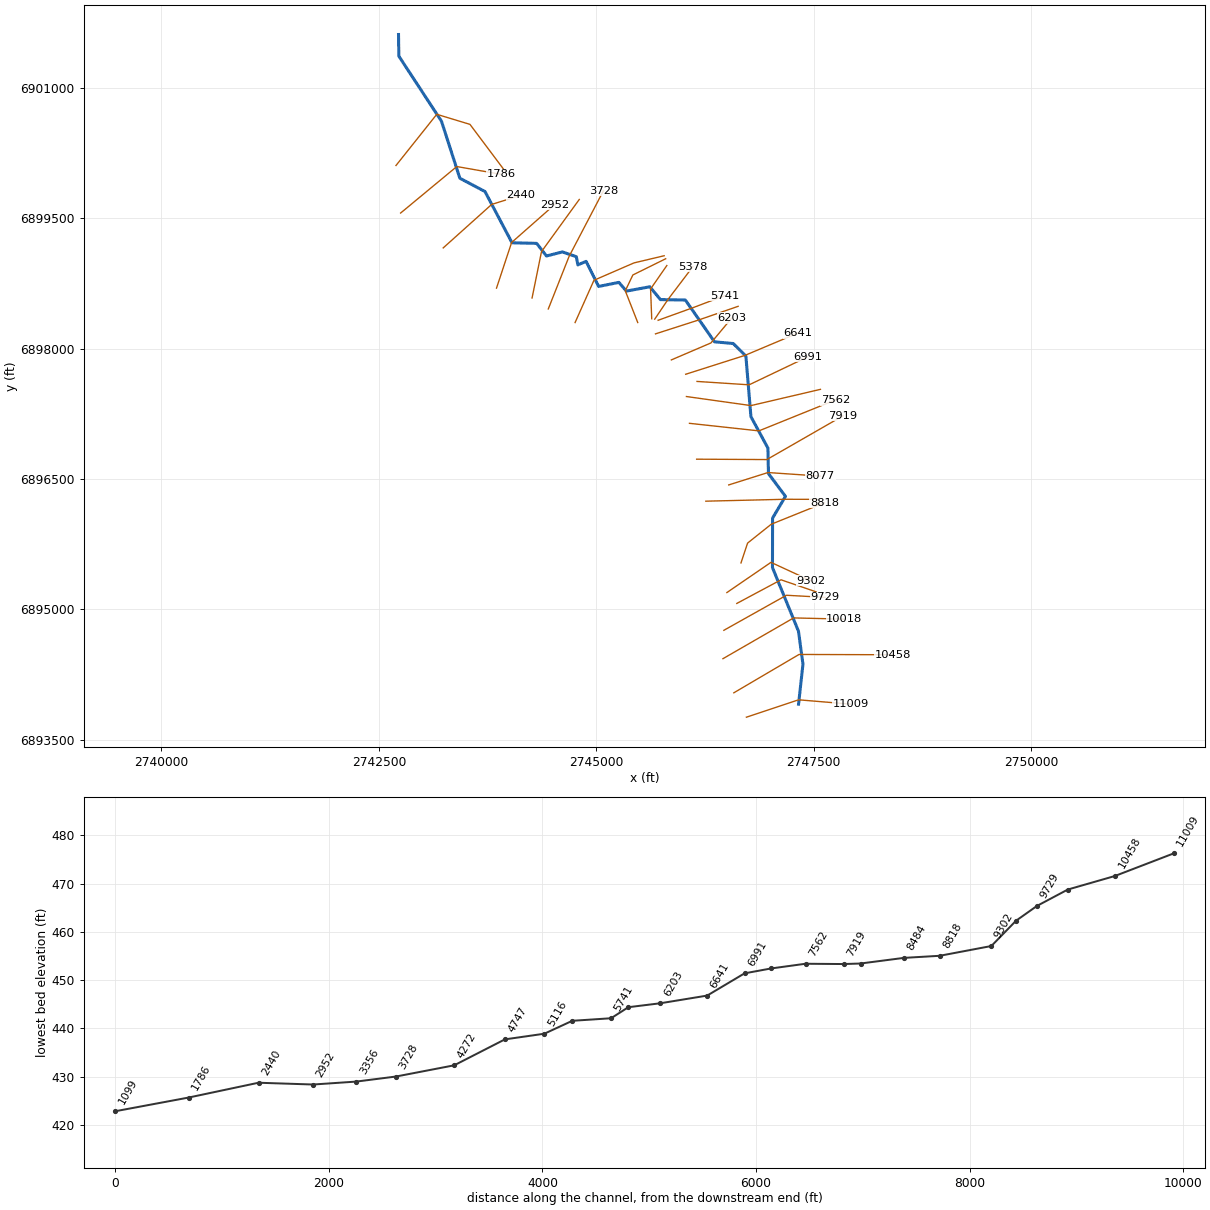
--- Dawson Creek.prj (project) ---

Proj Title=Dawson Creek Base Level Engineering
Current Plan=p01
Default Exp/Contr=0.3,0.1
English Units
Geom File=g01
Flow File=f01
Plan File=p01
Y Axis Title=Elevation
X Axis Title(PF)=Main Channel Distance
X Axis Title(XS)=Station
BEGIN DESCRIPTION:
Dawson Creek
END DESCRIPTION:
DSS Export Rating Curves= 0
DSS Export Rating Curve Sorted= 0
DSS Export Volume Flow Curves= 0
DXF OffsetX= 0
DXF OffsetY= 0
DXF ScaleX= 1
DXF ScaleY= 10

--- Dawson Creek.p01 (plan) ---

Plan Title=Multiple Run
Short Identifier=Multiple
Geom File=g01
Flow File=f01
Subcritical Flow
K Sum by GR= 0
Std Step Tol= 0.01
Critical Tol= 0.01
Num of Std Step Trials= 20
Max Error Tol= 0.3
Flow Tol Ratio= 0.001
Split Flow NTrial= 30
Split Flow Tol= 0.02
Split Flow Ratio= 0.02
Log Output Level= 0
Friction Slope Method= 1
Unsteady Friction Slope Method= 2
Unsteady Bridges Friction Slope Method= 1
Parabolic Critical Depth
Global Vel Dist=  1 , 1 , 1
Global Log Level= 0
CheckData=True
Encroach Param= -1, 0, 0, 0
BEGIN DESCRIPTION:
Multiple Run
END DESCRIPTION:

--- Dawson Creek.f01 (steady flow) ---

Flow Title=Multiple
Program Version=4.10
Number of Profiles= 7
Profile Names=10-year,25-year,50-year,1pct_min,100-year,1pct_plu,500-year
River Rch & RM=Dawson Creek,Reach-1         ,11009
     166     206     236     135     270     539     353
River Rch & RM=Dawson Creek,Reach-1         ,8818
     459     603     718     425     849    1693    1186
River Rch & RM=Dawson Creek,Reach-1         ,8484
     553     735     881     525    1048    2090    1483
River Rch & RM=Dawson Creek,Reach-1         ,6203
     651     874    1055     632    1261    2517    1808
River Rch & RM=Dawson Creek,Reach-1         ,4272
     712     961    1164     700    1397    2788    2018
River Rch & RM=Dawson Creek,Reach-1         ,3728
     844    1148    1398     845    1686    3364    2458
Boundary for River Rch & Prof#=Dawson Creek,Reach-1         , 1
Up Type= 0
Dn Type= 3
Dn Slope=0.00458
Boundary for River Rch & Prof#=Dawson Creek,Reach-1         , 2
Up Type= 0
Dn Type= 3
Dn Slope=0.00458
Boundary for River Rch & Prof#=Dawson Creek,Reach-1         , 3
Up Type= 0
Dn Type= 3
Dn Slope=0.00458
Boundary for River Rch & Prof#=Dawson Creek,Reach-1         , 4
Up Type= 0
Dn Type= 3
Dn Slope=0.00458
Boundary for River Rch & Prof#=Dawson Creek,Reach-1         , 5
Up Type= 0
Dn Type= 3
Dn Slope=0.00458
Boundary for River Rch & Prof#=Dawson Creek,Reach-1         , 6
Up Type= 0
Dn Type= 3
Dn Slope=0.00458
Boundary for River Rch & Prof#=Dawson Creek,Reach-1         , 7
Up Type= 0
Dn Type= 3
Dn Slope=0.00458
DSS Import GetInterval= 0
DSS Import GetPeak= 0
DSS Import FillOption= 0

--- Dawson Creek.g01 (geometry) ---

Geom Title=Existing Conditions
Program Version=4.10

River Reach=Dawson Creek    ,Reach-1
Reach XY= 30
        2747326.        6893911.      2747376.45      6894371.19
      2747324.78       6894750.5      2747025.94      6895480.99
      2747027.08      6896050.46       2747175.3       6896300.3
       2746979.6      6896562.49      2746973.74      6896855.06
      2746778.06      6897216.86      2746720.17       6897913.3
      2746574.64      6898057.73       2746359.2      6898077.41
      2746024.38      6898557.87      2745737.87      6898562.74
      2745615.38       6898710.4      2745346.26      6898660.59
      2745259.99      6898760.76      2745026.99      6898714.12
      2744882.73      6899002.52      2744787.74      6898962.12
      2744770.86      6899055.81      2744610.61      6899110.91
      2744427.49      6899064.46      2744314.17      6899209.38
      2744031.08      6899216.03      2743720.38      6899805.38
      2743431.35      6899958.27      2743220.29      6900613.35
      2742729.55      6901362.47        2742726.        6901611.

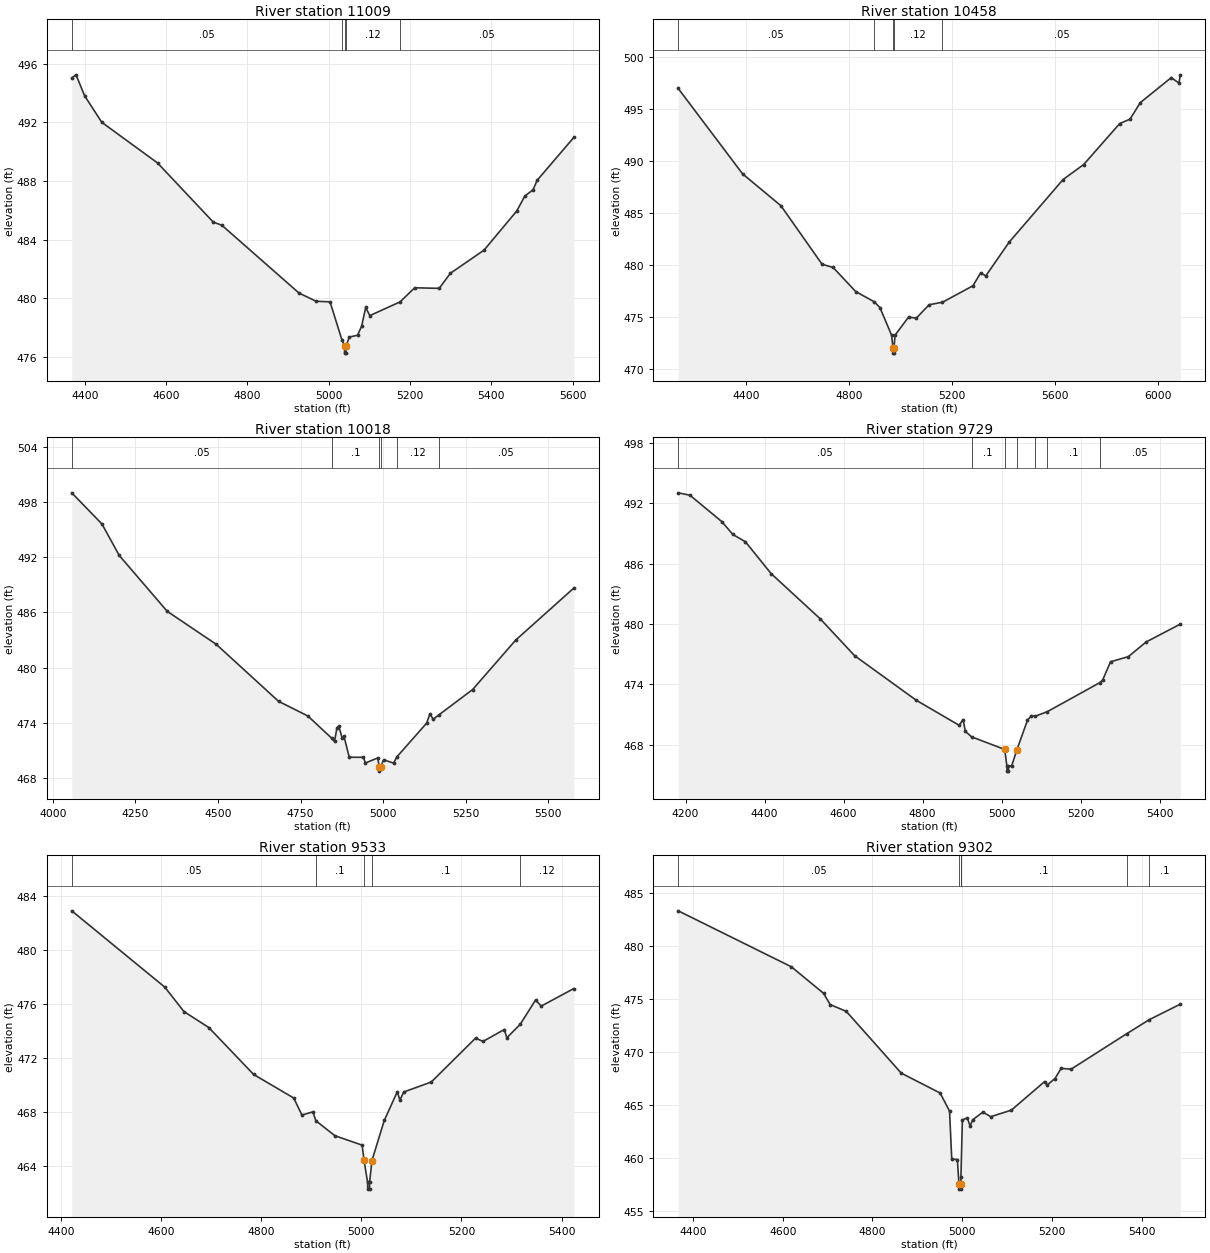
Type RM Length L Ch R = 1 ,11009   ,551,551,551
BEGIN DESCRIPTION:
Dawson Creek 20.0
END DESCRIPTION:
XS GIS Cut Line= 3
        2746726.        6893761.        2747326.        6893961.
      2747925.96        6893911.
#Sta/Elev= 30
  4368.2  495.04  4378.7  495.25  4399.8  493.82    4442  492.01    4579  489.24
  4716.1   485.2  4737.1  484.99  4926.9  480.36    4969   479.8  5003.2  479.76
  5032.4  477.17  5038.8  476.76    5039  476.26  5042.5  476.26  5042.8  476.76
  5050.8  477.36  5070.9  477.48  5080.9   478.1    5091  479.38    5101  478.82
  5175.6  479.76  5211.4  480.72  5271.6  480.68  5299.2  481.71    5382  483.29
  5462.3  485.96  5482.3  486.98  5502.4  487.41  5512.4  488.05  5602.7  490.98
#Mann= 5 ,-1 , 0
  4368.2     .05       0  5032.4     .12       0  5038.8     .05       0
  5042.8     .12       0  5175.6     .05       0
Bank Sta=5038.8,5042.8
XS Rating Curve= 0 ,0
Exp/Cntr=0.3,0.1

Type RM Length L Ch R = 1 ,10458   ,440,440,440
BEGIN DESCRIPTION:
Mapping XS f385eca2
END DESCRIPTION:
XS GIS Cut Line= 3
      2746581.69      6894041.56      2747331.69      6894482.54
      2748411.25      6894479.07
#Sta/Elev= 30
  4136.3     497  4386.3  488.79  4534.8  485.74  4694.9  480.11  4737.8   479.8
  4825.7  477.48    4897  476.51  4919.4  475.95  4964.9  473.29  4970.2  472.07
  4970.5  471.57    4974  471.57  4974.2  472.07    4978  473.29  5030.6  475.03
  5060.6  474.93  5110.6  476.22  5162.4  476.46  5280.6  478.04  5310.6  479.28
  5330.6  478.99  5420.6  482.21  5630.6  488.25  5710.6  489.69  5850.6  493.63
  5890.6  494.05  5930.6  495.64  6050.6  498.04  6080.6  497.52  6085.9  498.31
#Mann= 5 ,-1 , 0
  4136.3     .05       0    4897     .12       0  4970.2     .07       0
  4974.2     .12       0  5162.4     .05       0
Bank Sta=4970.2,4974.2
XS Rating Curve= 0 ,0
Exp/Cntr=0.3,0.1

Type RM Length L Ch R = 1 ,10018   ,289,289,289
BEGIN DESCRIPTION:
Mapping XS c3f0b1f3
END DESCRIPTION:
XS GIS Cut Line= 3
      2746456.71      6894433.94      2747269.19      6894902.68
      2747851.73      6894888.81
#Sta/Elev= 30
    4057  498.99  4148.5   495.6  4200.8  492.19  4345.9  486.13  4494.9  482.53
  4683.4  476.35    4772  474.76  4844.7  472.33  4852.8  471.99  4860.1  473.46
  4865.8  473.65  4875.8  472.39  4881.6  472.54  4897.4  470.28  4940.5  470.27
  4946.3  469.65  4983.6   470.2  4988.3  469.27  4988.5  468.77  4992.3  469.27
  5001.8     470  5031.8  469.64  5041.7  470.32  5131.8  473.98  5141.8  474.98
  5151.8   474.4  5168.6  474.87  5271.2  477.63  5401.9  483.01  5577.7  488.65
#Mann= 6 ,-1 , 0
    4057     .05       0  4844.7      .1       0  4988.3     .07       0
  4992.3      .1       0  5041.7     .12       0  5168.6     .05       0
Bank Sta=4988.3,4992.3
XS Rating Curve= 0 ,0
Exp/Cntr=0.3,0.1

Type RM Length L Ch R = 1 ,9729    ,196,196,196
BEGIN DESCRIPTION:
Mapping XS 6dced45e
END DESCRIPTION:
XS GIS Cut Line= 3
      2746467.07       6894760.3      2747185.86      6895163.09
      2747632.35      6895138.86
#Sta/Elev= 30
  4181.3  493.06  4211.1  492.82  4292.1  490.18  4319.5  488.92  4351.4  488.19
  4416.5  485.02  4540.9  480.52  4627.7  476.86    4784  472.42  4892.5  469.93
  4902.2   470.5  4908.4  469.32  4923.9  468.78  5007.8  467.53  5013.4  465.87
  5013.7  465.37  5017.2  465.37  5017.4  465.87  5025.4  465.89 5038.92 467.518
  5065.5  470.44  5075.5  470.89  5084.4  470.82  5115.8  471.29  5248.1  474.16
  5255.8  474.44  5275.8  476.25  5320.8  476.76  5365.9  478.22  5452.4     480
#Mann= 7 ,-1 , 0
  4181.3     .05       0  4923.9      .1       0  5007.8     .07       0
 5038.92      .1       0  5084.4     .12       0  5115.8      .1       0
  5248.1     .05       0
Bank Sta=5007.8,5038.92
XS Rating Curve= 0 ,0
Exp/Cntr=0.3,0.1

Type RM Length L Ch R = 1 ,9533    ,231,231,231
BEGIN DESCRIPTION:
Mapping XS 9d2408fa
END DESCRIPTION:
XS GIS Cut Line= 3
      2746615.62      6895068.94      2747123.89      6895340.94
      2747527.57       6895202.6
#Sta/Elev= 30
  4421.4  482.93  4607.4  477.27  4645.6  475.46  4695.2  474.28  4784.8   470.8
    4865  469.05  4881.3  467.79  4903.2  468.03  4909.1  467.37  4947.1  466.26
  5001.6  465.56 5005.33 464.451  5012.5   462.8  5012.8   462.3  5016.3   462.3
  5016.5   462.8  5021.2  464.42  5045.8  467.39  5071.8  469.52  5077.1   468.9
  5084.7   469.5  5139.7  470.24  5228.2  473.49  5243.2  473.25  5285.5  474.13
  5290.8  473.52  5317.5  474.52    5348  476.31  5359.5  475.87  5424.6  477.17
#Mann= 5 ,-1 , 0
  4421.4     .05       0  4909.1      .1       0 5005.33     .07       0
  5021.2      .1       0  5317.5     .12       0
Bank Sta=5005.33,5021.2
XS Rating Curve= 0 ,0
Exp/Cntr=0.3,0.1

Type RM Length L Ch R = 1 ,9302    ,484,484,484
BEGIN DESCRIPTION:
Mapping XS 22e89af3
END DESCRIPTION:
XS GIS Cut Line= 3
       2746501.8      6895194.32      2747008.77      6895541.56
      2747467.11      6895329.76
#Sta/Elev= 30
    4367  483.33  4619.1  478.05  4690.9  475.55  4705.8  474.48  4741.7  473.84
  4864.2  468.01  4950.9  466.13  4971.9  464.43  4976.8   459.9  4989.3  459.85
  4992.9  457.56  4993.1  457.06  4996.6  457.06  4996.9  457.56  4997.3  458.23
  5000.5  463.59  5011.5  463.79  5017.8  463.01  5023.3   463.6  5046.2  464.33
  5063.7   463.9  5109.5  464.51  5183.8  467.21  5189.4  466.88  5206.8  467.49
  5220.8  468.46  5242.8  468.38  5366.5  471.72  5417.4  473.06  5486.4  474.52
#Mann= 6 ,-1 , 0
    4367     .05       0  4992.9     .07       0  4996.9     .05       0
  4997.3      .1       0  5366.5     .12       0  5417.4      .1       0
Bank Sta=4992.9,4996.9
XS Rating Curve= 0 ,0
Exp/Cntr=0.3,0.1

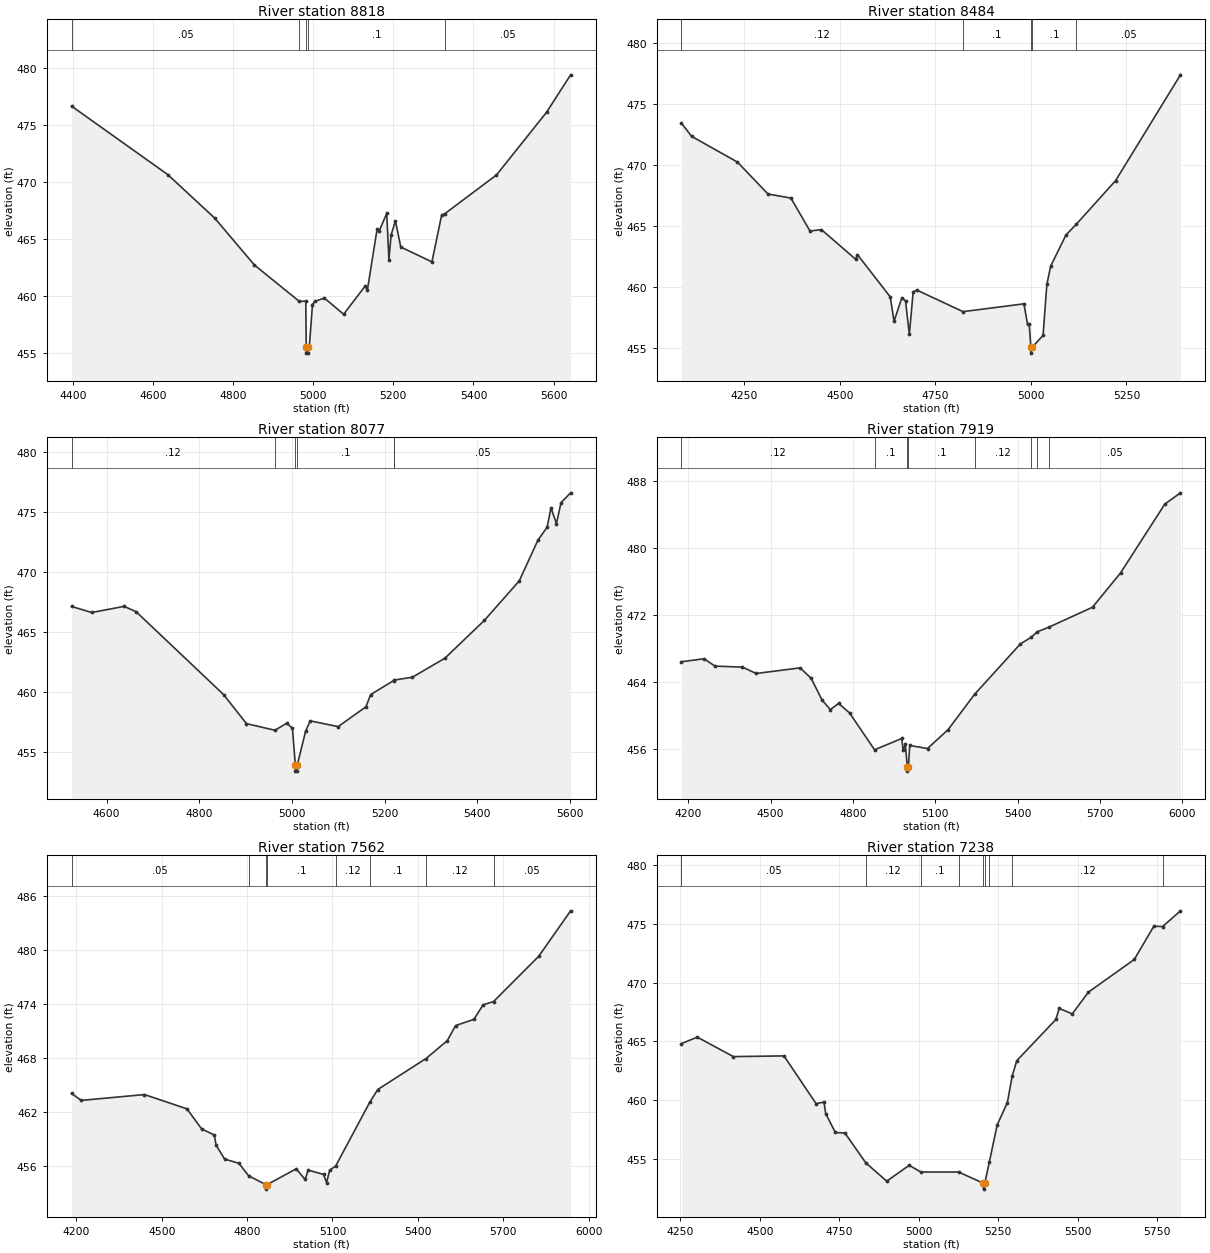
Type RM Length L Ch R = 1 ,8818    ,334,334,334
BEGIN DESCRIPTION:
Mapping XS 2098c606
END DESCRIPTION:
XS GIS Cut Line= 4
      2746663.83      6895535.09      2746739.75      6895762.92
      2747011.72      6895979.88      2747621.41      6896225.61
#Sta/Elev= 30
    4397  476.63  4637.1  470.64  4754.1  466.84  4853.4  462.73  4965.5  459.55
  4981.5  459.58  4982.6  455.53  4982.8  455.03  4986.3  455.03  4986.6  455.53
  4990.1  455.53  4998.2  459.28  5003.6  459.55  5027.8  459.85  5075.9  458.43
  5129.8   460.9  5135.2  460.55  5159.4  465.86  5164.7  465.72  5183.5  467.25
  5188.9  463.21  5194.5  465.38  5205.3  466.59  5218.5  464.31  5296.3  463.01
  5320.5   467.1  5328.7  467.23  5457.4  470.61  5582.7  476.11  5642.4  479.37
#Mann= 5 ,-1 , 0
    4397     .05       0  4965.5      .1       0  4982.6     .07       0
  4986.6      .1       0  5328.7     .05       0
Bank Sta=4982.6,4986.6
XS Rating Curve= 0 ,0
Exp/Cntr=0.3,0.1

Type RM Length L Ch R = 1 ,8484    ,407,407,407
BEGIN DESCRIPTION:
Mapping XS 4ada5299
END DESCRIPTION:
XS GIS Cut Line= 3
      2746259.57      6896244.94       2747169.8      6896266.83
       2747565.8      6896265.97
#Sta/Elev= 30
    4085  473.45  4111.4  472.37  4231.5  470.26  4311.5  467.64  4371.5  467.31
  4421.5  464.61  4451.5  464.72  4540.8   462.3  4545.8  462.67  4631.6  459.21
  4641.6  457.21  4661.6   459.1  4671.6   458.9  4681.6  456.13  4691.6  459.62
  4701.6  459.76  4822.3     458  4981.7  458.64  4991.1  456.95  4995.5  456.95
  4999.7   455.1  4999.9   454.6  5003.7   455.1  5031.7  456.05  5041.7  460.23
  5051.7  461.73  5091.7  464.28  5118.4  465.15  5221.7  468.74  5391.5  477.41
#Mann= 5 ,-1 , 0
    4085     .12       0  4822.3      .1       0  4999.7     .07       0
  5003.7      .1       0  5118.4     .05       0
Bank Sta=4999.7,5003.7
XS Rating Curve= 0 ,0
Exp/Cntr=0.3,0.1

Type RM Length L Ch R = 1 ,8077    ,158,158,158
BEGIN DESCRIPTION:
Mapping XS dfe74dd1
END DESCRIPTION:
XS GIS Cut Line= 3
      2746523.11      6896431.81      2746974.32      6896574.28
      2747576.56      6896533.36
#Sta/Elev= 30
  4524.4  467.12  4567.8  466.62  4637.7  467.13  4663.8  466.68  4852.5  459.79
  4901.7  457.38    4963  456.83  4988.8  457.41  5000.9  456.99  5007.2  453.93
  5007.5  453.43    5011  453.43  5011.3  453.93  5029.3  456.74  5039.3  457.61
  5099.5  457.13  5159.6  458.78  5169.6  459.79  5219.3  460.96  5220.6     461
  5259.9  461.24    5330  462.82    5415  465.96  5490.4  469.25  5530.5  472.62
  5550.5  473.71  5558.9  475.32  5570.6  474.01  5580.6  475.75  5601.2  476.57
#Mann= 6 ,-1 , 0
  4524.4     .12       0    4963      .1       0  5007.2     .07       0
  5011.3      .1       0  5219.3     .12       0  5220.6     .05       0
Bank Sta=5007.2,5011.3
XS Rating Curve= 0 ,0
Exp/Cntr=0.3,0.1

Type RM Length L Ch R = 1 ,7919    ,357,357,357
BEGIN DESCRIPTION:
Mapping XS 69177b69
END DESCRIPTION:
XS GIS Cut Line= 3
      2746153.92      6896727.81      2746961.18      6896723.47
      2747837.06      6897226.45
#Sta/Elev= 30
  4175.6  466.39  4257.7  466.75  4297.7  465.87  4397.7  465.75  4447.7  464.99
  4607.7  465.66  4647.7  464.42  4687.7  461.81  4717.7  460.67  4747.7  461.41
  4787.7  460.28  4878.8  455.87  4977.7  457.22  4982.8  455.85  4991.1  456.51
  4997.9  453.82  4998.2  453.32  5002.1  453.82  5006.9  456.39  5071.6  456.02
  5146.4  458.27  5243.4  462.51  5409.5  468.51  5448.5   469.3  5471.8  469.98
  5512.7  470.51  5672.6  472.91  5774.7  477.01  5935.8  485.23  5992.9  486.58
#Mann= 8 ,-1 , 0
  4175.6     .12       0  4878.8      .1       0  4997.9     .07       0
  5002.1      .1       0  5243.4     .12       0  5448.5      .1       0
  5471.8     .12       0  5512.7     .05       0
Bank Sta=4997.9,5002.1
XS Rating Curve= 0 ,0
Exp/Cntr=0.3,0.1

Type RM Length L Ch R = 1 ,7562    ,324,324,324
BEGIN DESCRIPTION:
Mapping XS 75f137f7
END DESCRIPTION:
XS GIS Cut Line= 3
      2746071.42      6897140.13      2746870.03      6897053.33
      2747751.06      6897409.21
#Sta/Elev= 30
  4183.3  464.04  4217.3  463.27  4439.4  463.92  4588.5  462.33  4640.6  460.08
    4685  459.41  4690.8  458.29    4721  456.73  4771.3  456.26  4805.1  454.87
    4866  453.88  4866.3  453.38  4870.3  453.88  4972.5  455.64  5003.8  454.46
  5014.6   455.5  5068.5  455.02  5079.3  454.11  5090.1  455.47  5111.6  455.98
  5230.7  463.04    5259  464.48  5428.9  467.94  5503.2  469.92  5532.7  471.61
    5597   472.3  5629.3  473.92  5666.1  474.29  5825.2  479.35  5936.8   484.4
#Mann= 8 ,-1 , 0
  4183.3     .05       0  4805.1      .1       0    4866     .07       0
  4870.3      .1       0  5111.6     .12       0  5230.7      .1       0
  5428.9     .12       0  5666.1     .05       0
Bank Sta=4866,4870.3
XS Rating Curve= 0 ,0
Exp/Cntr=0.3,0.1

Type RM Length L Ch R = 1 ,7238    ,247,247,247
BEGIN DESCRIPTION:
Mapping XS 73adae97
END DESCRIPTION:
XS GIS Cut Line= 3
      2746036.71      6897448.29      2746778.88      6897344.12
      2747577.52      6897530.76
#Sta/Elev= 30
  4253.5  464.81  4303.3  465.36  4416.6   463.7  4575.9  463.76  4676.9  459.69
  4701.9  459.82  4707.2  458.84  4737.5  457.23  4767.8  457.18    4833  454.65
  4899.1  453.08  4969.7  454.43  5006.3  453.86  5125.3  453.86  5203.2   452.9
  5203.6   452.4  5207.5   452.9  5221.9  454.71  5246.5  457.87  5278.6  459.78
  5293.7  462.03  5308.1  463.35  5431.3  466.87  5441.6  467.81  5482.7  467.34
  5533.7   469.2  5677.8  471.98  5739.4  474.82    5767  474.79  5823.1  476.13
#Mann= 9 ,-1 , 0
  4253.5     .05       0    4833     .12       0  5006.3      .1       0
  5125.3     .12       0  5203.2     .07       0  5207.5     .12       0
  5221.9      .1       0  5293.7     .12       0    5767     .05       0
Bank Sta=5203.2,5207.5
XS Rating Curve= 0 ,0
Exp/Cntr=0.3,0.1

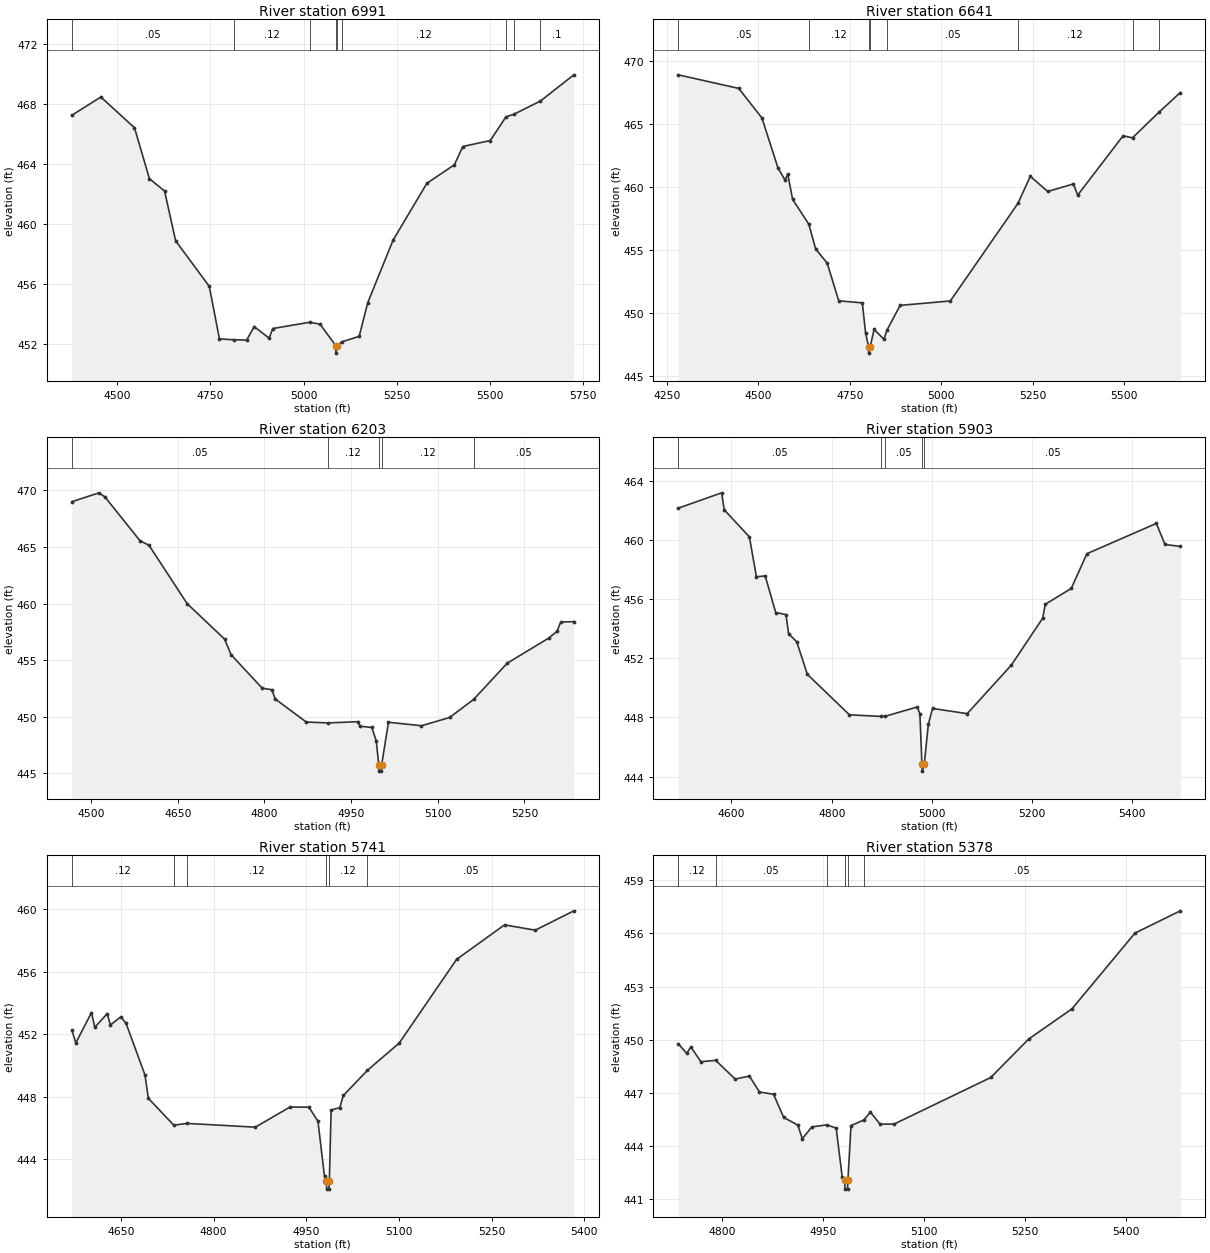
Type RM Length L Ch R = 1 ,6991    ,350,350,350
BEGIN DESCRIPTION:
Mapping XS 2aa498d5
END DESCRIPTION:
XS GIS Cut Line= 3
      2746158.22       6897621.9      2746757.18      6897582.84
      2747429.91      6897904.01
#Sta/Elev= 30
  4378.9  467.25  4456.8  468.47    4547  466.42  4587.1  463.02  4627.7   462.2
  4657.3  458.88  4747.5  455.84  4774.7  452.34  4813.3  452.28  4847.7  452.26
  4867.7  453.16  4907.8  452.39  4917.8  453.03  5016.4  453.45  5044.3  453.32
  5086.5  451.89  5086.8  451.39  5090.8  451.89  5102.4  452.14  5149.3  452.51
    5172  454.74    5240  458.92  5330.8  462.72  5404.4  463.95    5427  465.17
  5500.6  465.57  5542.7  467.15  5563.1  467.31  5634.9   468.2  5724.6  469.95
#Mann= 9 ,-1 , 0
  4378.9     .05       0  4813.3     .12       0  5016.4      .1       0
  5086.5     .07       0  5090.8      .1       0  5102.4     .12       0
  5542.7      .1       0  5563.1     .12       0  5634.9      .1       0
Bank Sta=5086.5,5090.8
XS Rating Curve= 0 ,0
Exp/Cntr=0.3,0.1

Type RM Length L Ch R = 1 ,6641    ,438,438,438
BEGIN DESCRIPTION:
Mapping XS 184f6731
END DESCRIPTION:
XS GIS Cut Line= 3
        2746028.      6897704.36      2746709.44      6897921.38
      2747315.37      6898176.74
#Sta/Elev= 30
  4280.6  468.92    4446  467.84  4509.4  465.49  4553.1  461.53  4572.4  460.55
  4580.1  461.03  4593.3  459.01  4637.4  457.05  4656.3  455.07  4687.8  453.94
  4719.5  450.94  4783.9  450.78  4792.8  448.39    4801  447.28  4801.4  446.78
  4805.4  447.28  4816.1  448.67  4843.1  447.88    4851  448.59  4887.2  450.58
  5024.6  450.93  5209.3  458.69  5243.2  460.85  5290.7  459.64    5361  460.24
  5372.7  459.35  5496.8  464.07  5522.6  463.91  5594.7  465.94  5653.3  467.51
#Mann= 8 ,-1 , 0
  4280.6     .05       0  4637.4     .12       0    4801     .04       0
  4805.4     .12       0    4851     .05       0  5209.3     .12       0
  5522.6      .1       0  5594.7     .12       0
Bank Sta=4801,4805.4
XS Rating Curve= 0 ,0
Exp/Cntr=0.3,0.1

Type RM Length L Ch R = 1 ,6203    ,300,300,300
BEGIN DESCRIPTION:
Mapping XS 37c8e3d3
END DESCRIPTION:
XS GIS Cut Line= 3
      2745863.11      6897869.31      2746318.82      6898064.61
      2746557.54      6898351.08
#Sta/Elev= 30
  4466.7  468.99  4513.9  469.78  4524.2  469.41  4584.7  465.55  4600.4  465.14
  4666.3  459.99    4731  456.86  4742.4  455.47  4796.2  452.52  4813.1  452.38
  4818.6  451.57  4872.4  449.53  4909.9  449.45  4962.5  449.56  4965.1  449.16
  4985.9  449.05  4993.7  447.82  4997.9  445.69  4998.4  445.19  5002.1  445.19
  5002.7  445.69  5014.6  449.51  5071.8   449.2  5120.5  449.93  5162.1  451.53
  5220.2  454.73  5291.8  456.94  5306.2  457.53  5312.7  458.36  5335.4   458.4
#Mann= 5 ,-1 , 0
  4466.7     .05       0  4909.9     .12       0  4997.9     .07       0
  5002.7     .12       0  5162.1     .05       0
Bank Sta=4997.9,5002.7
XS Rating Curve= 0 ,0
Exp/Cntr=0.3,0.1

Type RM Length L Ch R = 1 ,5903    ,162,162,162
BEGIN DESCRIPTION:
Mapping XS dd1ffaed
END DESCRIPTION:
XS GIS Cut Line= 3
      2745680.82      6898168.79      2746166.91      6898325.03
      2746631.16      6898485.56
#Sta/Elev= 30
  4493.8  462.16  4580.4   463.2  4585.6  462.05  4635.8  460.22  4649.8  457.52
  4667.3  457.58  4688.3   455.1  4708.8  454.96    4714  453.67  4730.3  453.12
  4751.4  450.92  4835.4  448.18    4899  448.07  4906.5  448.08  4970.8  448.71
    4976  448.24    4980  444.87  4980.6  444.37  4984.8  444.87  4992.9  447.56
  5001.3  448.61  5070.4  448.26  5158.6  451.55  5220.9  454.71  5226.2  455.66
    5278  456.73  5309.2  459.08  5447.8  461.13    5465  459.71  5495.6  459.57
#Mann= 5 ,-1 , 0
  4493.8     .05       0    4899     .12       0  4906.5     .05       0
    4980     .05       0  4984.8     .05       0
Bank Sta=4980,4984.8
XS Rating Curve= 0 ,0
Exp/Cntr=0.3,0.1

Type RM Length L Ch R = 1 ,5741    ,363,363,363
BEGIN DESCRIPTION:
Mapping XS b802c196
END DESCRIPTION:
XS GIS Cut Line= 3
      2745711.22      6898325.04      2746119.16       6898472.6
      2746473.57      6898606.58
#Sta/Elev= 30
  4570.4  452.28    4577  451.45  4602.3  453.39  4607.7  452.45  4627.7  453.32
    4633   452.6  4649.9  453.12  4658.3   452.7    4689  449.38  4694.3   447.9
  4735.5  446.18    4757  446.29  4867.6  446.05  4923.6  447.34  4954.2  447.33
  4968.9  446.43  4979.5  442.89  4982.5  442.58    4983  442.08  4986.7  442.08
  4987.3  442.58  4990.2  447.15  5004.2   447.3    5010  448.08  5048.9  449.69
  5100.5  451.44  5193.3   456.8  5270.9  459.01  5320.6  458.67  5383.1  459.91
#Mann= 6 ,-1 , 0
  4570.4     .12       0  4735.5     .05       0    4757     .12       0
  4982.5     .07       0  4987.3     .12       0  5048.9     .05       0
Bank Sta=4982.5,4987.3
XS Rating Curve= 0 ,0
Exp/Cntr=0.3,0.1

Type RM Length L Ch R = 1 ,5378    ,262,262,262
BEGIN DESCRIPTION:
Mapping XS 0c220247
END DESCRIPTION:
XS GIS Cut Line= 3
      2745672.13      6898338.07      2745824.02      6898563.74
      2746110.49      6898941.36
#Sta/Elev= 30
  4734.4  449.77  4747.1  449.22  4753.1  449.59  4768.1  448.75  4789.9  448.83
  4819.1  447.77  4840.1  447.94  4855.1  447.04  4876.1  446.91  4891.1   445.6
  4912.1  445.17  4918.7   444.4  4933.1  445.07  4955.1  445.18  4969.1     445
    4978  442.25  4981.7  442.05  4982.2  441.55  4985.9  441.55  4986.5  442.05
  4991.1  445.14  5010.2  445.46  5019.9   445.9  5034.4  445.22  5055.3  445.23
  5198.8  447.86    5255  450.03  5319.4  451.74    5413  456.02  5480.4  457.28
#Mann= 6 ,-1 , 0
  4734.4     .12       0  4789.9     .05       0  4955.1     .12       0
  4981.7     .07       0  4986.5     .12       0  5010.2     .05       0
Bank Sta=4981.7,4986.5
XS Rating Curve= 0 ,0
Exp/Cntr=0.3,0.1

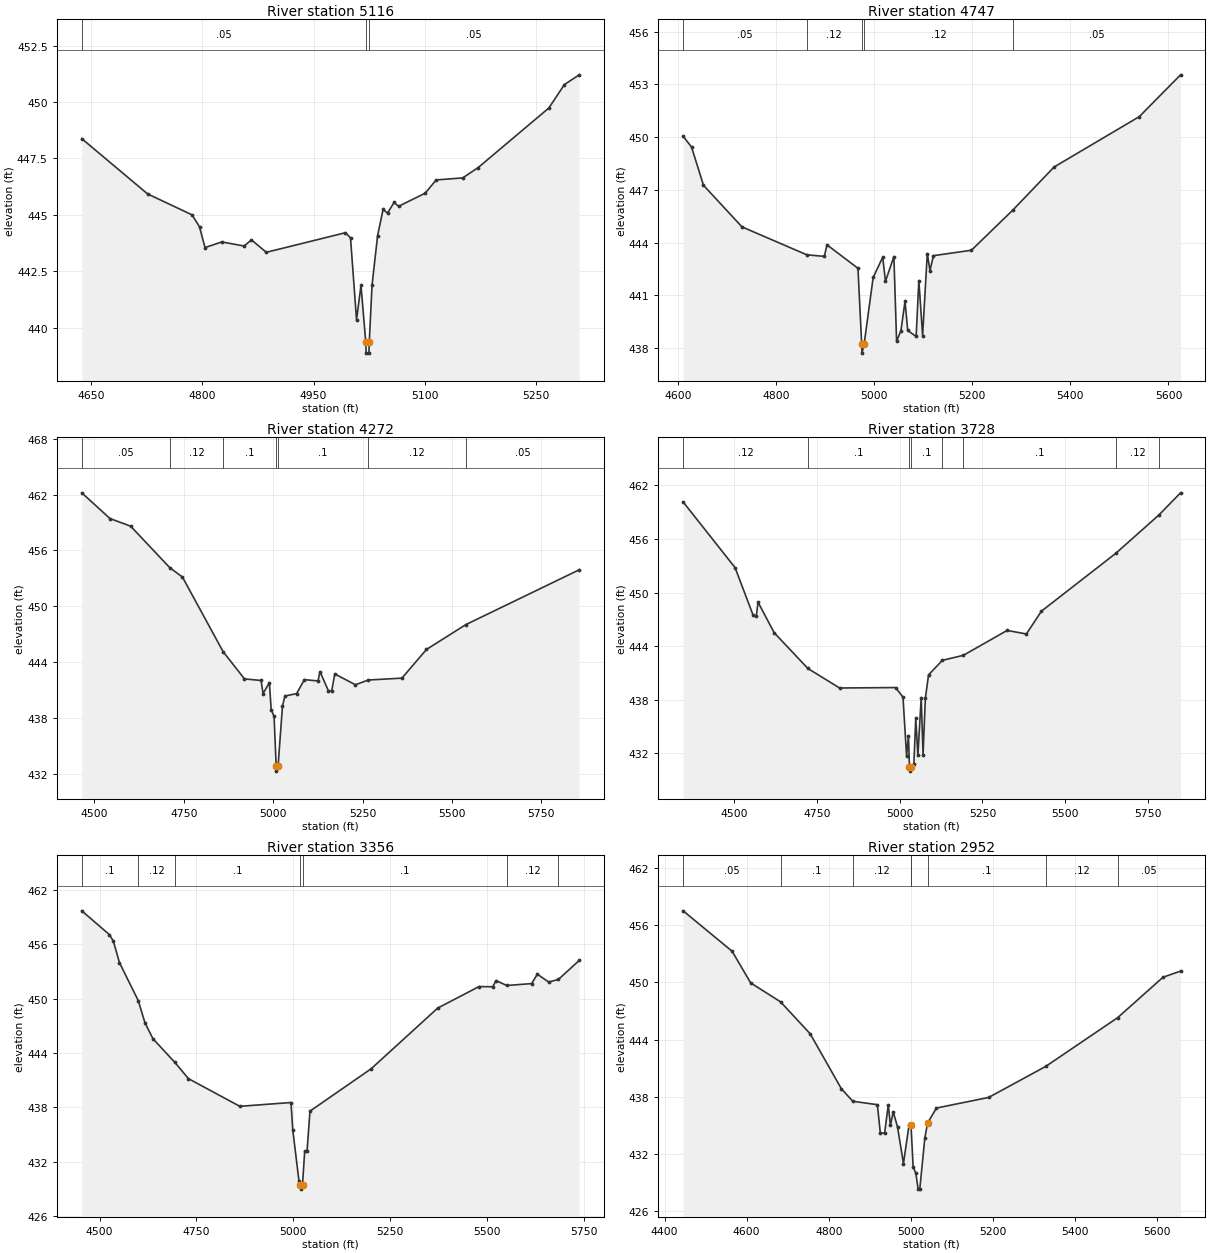
Type RM Length L Ch R = 1 ,5116    ,369,369,369
BEGIN DESCRIPTION:
Mapping XS 44a8bd18
END DESCRIPTION:
XS GIS Cut Line= 3
      2745637.39      6898342.37      2745624.37      6898685.27
      2745810.98      6898954.34
#Sta/Elev= 30
  4637.6  448.38  4726.3  445.93  4786.3     445  4796.3  444.47  4803.7  443.55
  4826.4   443.8  4856.4  443.62  4866.4  443.89  4886.4  443.34  4993.1  444.21
  4999.9  443.98    5008  440.35    5014  441.87  5020.4  439.37    5021  438.87
  5024.7  438.87  5025.2  439.37  5028.9  441.88  5036.4  444.08  5043.8  445.24
  5049.8  445.08  5058.6  445.55  5064.7  445.38  5100.5  445.96  5115.4  446.55
  5151.2  446.64  5172.1   447.1  5267.3  449.74  5288.3  450.78  5308.2  451.21
#Mann= 3 ,-1 , 0
  4637.6     .05       0  5020.4     .04       0  5025.2     .05       0
Bank Sta=5020.4,5025.2
XS Rating Curve= 0 ,0
Exp/Cntr=0.3,0.1

Type RM Length L Ch R = 1 ,4747    ,475,475,475
BEGIN DESCRIPTION:
Mapping XS be50d47c
END DESCRIPTION:
XS GIS Cut Line= 4
      2745476.81      6898298.97      2745333.57      6898663.57
      2745420.38      6898845.86      2745797.95      6899032.48
#Sta/Elev= 30
  4609.9  450.05    4627  449.44  4651.4  447.26    4730  444.89  4862.2   443.3
    4898  443.21  4903.4  443.87  4966.6  442.53  4974.2   438.2  4974.8   437.7
  4979.1   438.2  4997.6  442.01  5017.1  443.16  5022.7  441.79  5039.9   443.2
  5045.4  438.38  5054.2  438.97  5062.6  440.65  5068.1  438.99  5085.3  438.65
  5090.8  441.83  5098.5   438.7    5108  443.37  5113.5   442.4  5120.6  443.25
  5198.1  443.56    5283  445.86  5366.7   448.3  5540.6  451.17  5624.7  453.55
#Mann= 5 ,-1 , 0
  4609.9     .05       0  4862.2     .12       0  4974.2     .07       0
  4979.1     .12       0    5283     .05       0
Bank Sta=4974.2,4979.1
XS Rating Curve= 0 ,0
Exp/Cntr=0.3,0.1

Type RM Length L Ch R = 1 ,4272    ,544,544,544
BEGIN DESCRIPTION:
Mapping XS a043a7d6
END DESCRIPTION:
XS GIS Cut Line= 4
      2744756.32      6898299.01      2744973.33       6898785.1
       2745433.4      6898984.75      2745780.59      6899067.21
#Sta/Elev= 30
  4464.9  462.19  4543.7  459.43  4601.5  458.61  4711.1  454.15  4746.3  453.15
  4859.9  445.15  4919.7  442.22  4966.2  442.05  4971.7  440.65  4989.4  441.82
  4994.4  438.92  5002.5   438.2  5008.4  432.82  5009.1  432.32  5013.6  432.82
    5026   439.3  5032.8  440.38  5065.5  440.64  5087.3  442.14  5125.3     442
    5131  442.99  5154.2  440.96  5163.7  440.93  5172.2  442.75    5230  441.59
    5266   442.1  5359.9   442.3  5428.6  445.38  5538.4  448.04  5855.6  453.93
#Mann= 7 ,-1 , 0
  4464.9     .05       0  4711.1     .12       0  4859.9      .1       0
  5008.4     .07       0  5013.6      .1       0    5266     .12       0
  5538.4     .05       0
Bank Sta=5008.4,5013.6
XS Rating Curve= 0 ,0
Exp/Cntr=0.3,0.1

Type RM Length L Ch R = 1 ,3728    ,372,372,372
BEGIN DESCRIPTION:
Mapping XS fac1459f
END DESCRIPTION:
XS GIS Cut Line= 3
      2744448.17      6898455.28      2744686.87      6899058.53
      2745081.41      6899812.93
#Sta/Elev= 30
  4347.2  460.15  4503.9  452.79  4557.7  447.52  4567.7  447.33  4573.1  448.92
  4621.8   445.5  4723.4   441.5    4819  439.31  4987.9  439.36  5010.3  438.28
  5021.1  431.68  5026.7  433.98  5029.8   430.5  5030.6     430  5035.4   430.5
  5043.1  430.85  5048.8  435.91  5055.2  431.76  5065.2  438.24  5070.8  431.85
  5077.7  438.15  5087.3  440.78    5129  442.41  5192.2  442.97  5324.5  445.76
  5382.4  445.36  5427.6  447.91  5651.9  454.39  5782.4   458.7  5847.3  461.17
#Mann= 8 ,-1 , 0
  4347.2     .12       0  4723.4      .1       0  5029.8     .07       0
  5035.4      .1       0    5129     .12       0  5192.2      .1       0
  5651.9     .12       0  5782.4     .05       0
Bank Sta=5029.8,5035.4
XS Rating Curve= 0 ,0
Exp/Cntr=0.3,0.1

Type RM Length L Ch R = 1 ,3356    ,404,404,404
BEGIN DESCRIPTION:
Mapping XS 041a70a1
END DESCRIPTION:
XS GIS Cut Line= 3
      2744261.52      6898581.09      2744370.03      6899114.96
      2744804.08      6899713.95
#Sta/Elev= 30
  4454.2   459.7  4525.5  457.07  4535.7  456.35  4551.5  453.97    4600  449.78
  4617.4  447.32  4637.8  445.58  4694.6  442.95  4729.6  441.16  4862.3   438.1
  4994.4  438.52    4999  435.51  5015.1  429.83  5018.5  429.45  5019.4  428.95
  5024.2  429.45  5029.8  433.14    5036  433.21  5043.5  437.57  5201.5  442.25
  5373.2  448.95  5479.9  451.33  5515.4  451.31  5523.9  451.99  5551.6  451.45
  5615.9  451.66  5630.6   452.7    5660  451.83  5685.1  452.12  5738.7  454.22
#Mann= 7 ,-1 , 0
  4454.2      .1       0    4600     .12       0  4694.6      .1       0
  5018.5     .07       0  5024.2      .1       0  5551.6     .12       0
  5685.1     .05       0
Bank Sta=5018.5,5024.2
XS Rating Curve= 0 ,0
Exp/Cntr=0.3,0.1

Type RM Length L Ch R = 1 ,2952    ,512,512,512
BEGIN DESCRIPTION:
Mapping XS 9cc79a0a
END DESCRIPTION:
XS GIS Cut Line= 3
      2743852.68      6898694.85      2744026.28      6899219.12
      2744521.57      6899655.54
#Sta/Elev= 30
  4445.1  457.51  4564.6  453.27  4609.6  449.96  4682.6  447.97  4754.8  444.62
  4830.8  438.86  4858.6  437.55  4918.6  437.19  4925.6  434.27  4936.1  434.18
  4945.1  437.16  4950.4  435.03  4957.2  436.44  4967.7  434.85  4982.1  431.02
  4995.7  435.05    5000  435.05  5000.5  435.05  5005.7  430.69  5012.4  429.99
  5017.9  428.34  5021.9  428.34  5034.2  433.69  5040.8  435.25  5062.6  436.84
  5189.8  437.95  5328.8   441.2  5504.2  446.31  5614.8  450.55  5657.5  451.19
#Mann= 8 ,-1 , 0
  4445.1     .05       0  4682.6      .1       0  4858.6     .12       0
    5000      .1       0  5000.5     .05       0  5040.8      .1       0
  5328.8     .12       0  5504.2     .05       0
Bank Sta=5000.5,5040.8
XS Rating Curve= 0 ,0
Exp/Cntr=0.3,0.1

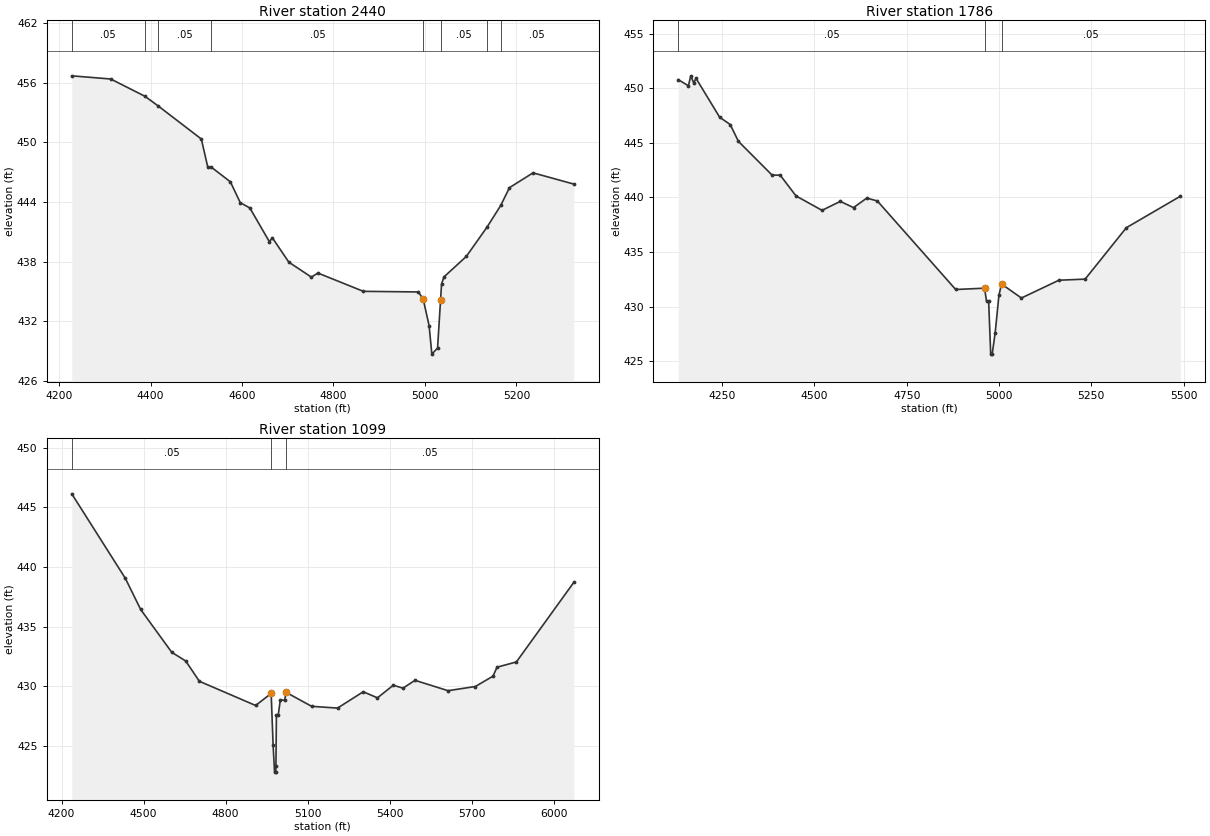
Type RM Length L Ch R = 1 ,2440    ,654,654,654
BEGIN DESCRIPTION:
Mapping XS b41b1c59
END DESCRIPTION:
XS GIS Cut Line= 3
      2743239.83      6899157.11      2743797.09      6899657.08
      2744130.42      6899761.25
#Sta/Elev= 30
  4227.7  456.68  4312.9  456.36  4387.5  454.63  4416.5  453.66    4511  450.33
  4525.2  447.49  4533.1  447.49  4574.5  446.03  4596.2  443.93  4617.1   443.4
  4659.7  440.02  4666.5  440.39  4702.4  437.95  4751.7  436.45  4765.9  436.86
  4865.3  435.02  4985.7  434.96  4996.2  434.23  5009.1  431.57  5015.1  428.71
  5027.6  429.32 5034.19 434.191  5036.3  435.75  5041.6  436.47  5090.5  438.53
    5136  441.49  5165.7  443.65  5184.8  445.44  5236.4  446.93  5325.6   445.8
#Mann= 8 ,-1 , 0
  4227.7     .05       0  4387.5      .1       0  4416.5     .05       0
  4533.1     .05       0  4996.2     .03       0 5034.19     .05       0
    5136      .1       0  5165.7     .05       0
Bank Sta=4996.2,5034.19
XS Rating Curve= 0 ,0
Exp/Cntr=0.3,0.1

Type RM Length L Ch R = 1 ,1786    ,687,687,687
BEGIN DESCRIPTION:
Mapping XS 86005160
END DESCRIPTION:
XS GIS Cut Line= 3
      2742750.19       6899558.1      2743396.05      6900092.84
      2743909.98      6900002.56
#Sta/Elev= 30
    4131  450.78  4158.5  450.22    4165  451.13  4172.9  450.49  4179.4  450.89
  4243.2  447.34  4271.8  446.67    4294  445.13  4385.2  442.04  4407.3  442.03
  4450.1  440.13  4520.6  438.81  4570.1  439.63  4605.9  439.06  4641.8  439.93
  4670.4  439.67  4882.7  431.56  4960.9  431.68  4966.2  430.51    4972  430.51
  4977.6  425.64  4981.6  425.64  4989.8  427.62  4999.9  431.04    5007  432.06
  5060.8  430.78  5162.4  432.41  5233.4  432.51  5345.1  437.22  5491.3   440.1
#Mann= 3 ,-1 , 0
    4131     .05       0  4960.9     .03       0    5007     .05       0
Bank Sta=4960.9,5007
XS Rating Curve= 0 ,0
Exp/Cntr=0.3,0.1

Type RM Length L Ch R = 1 ,1099    ,0,0,0
BEGIN DESCRIPTION:
Mapping XS ad22c74c
END DESCRIPTION:
XS GIS Cut Line= 4
       2742697.1      6900105.01      2743165.84      6900693.54
      2743547.43      6900577.79      2743958.35      6900029.54
#Sta/Elev= 30
  4237.3  446.14  4433.3  439.05  4489.3  436.44    4603  432.85  4654.1  432.12
  4703.9  430.42  4909.7  428.39  4966.6   429.4  4973.7  425.05    4979   422.8
    4983   422.8    4984   423.3  4985.8  427.59  4992.4  427.59  5000.3  428.87
  5015.8  428.82  5021.2  429.49  5114.5  428.32  5209.3  428.17  5303.4  429.54
  5355.3  429.03  5413.4  430.09  5448.8  429.84  5492.6   430.5  5613.4  429.63
  5713.4  429.98    5778  430.85  5792.6   431.6  5863.4  432.04  6073.6  438.72
#Mann= 3 ,-1 , 0
  4237.3     .05       0  4966.6     .03       0  5021.2     .05       0
Bank Sta=4966.6,5021.2
XS Rating Curve= 0 ,0
Exp/Cntr=0.3,0.1

Chan Stop Cuts=-1
Use User Specified Reach Order=0
Composite Channel Slope=5