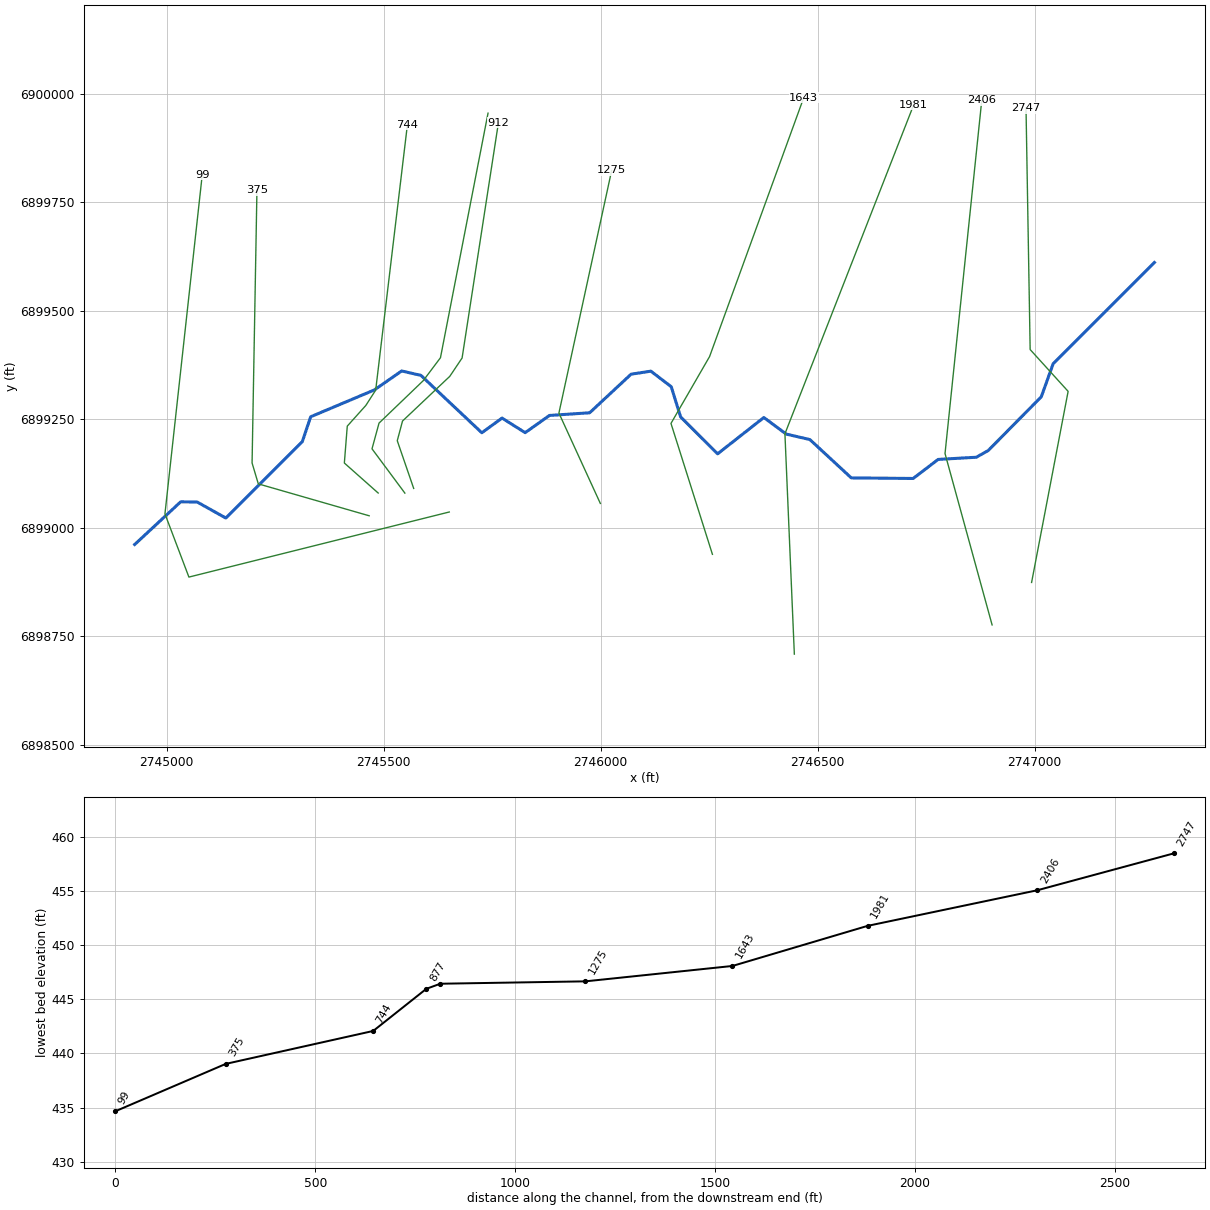
--- Dawson T1.prj (project) ---

Proj Title=Dawson T1 Base Level Engineering
Current Plan=p01
Default Exp/Contr=0.3,0.1
English Units
Geom File=g01
Flow File=f01
Plan File=p01
Y Axis Title=Elevation
X Axis Title(PF)=Main Channel Distance
X Axis Title(XS)=Station
BEGIN DESCRIPTION:
Dawson T1
END DESCRIPTION:
DSS Export Rating Curves= 0
DSS Export Rating Curve Sorted= 0
DSS Export Volume Flow Curves= 0
DXF OffsetX= 0
DXF OffsetY= 0
DXF ScaleX= 1
DXF ScaleY= 10

--- Dawson T1.p01 (plan) ---

Plan Title=Multiple Run
Short Identifier=Multiple
Geom File=g01
Flow File=f01
Subcritical Flow
K Sum by GR= 0
Std Step Tol= 0.01
Critical Tol= 0.01
Num of Std Step Trials= 20
Max Error Tol= 0.3
Flow Tol Ratio= 0.001
Split Flow NTrial= 30
Split Flow Tol= 0.02
Split Flow Ratio= 0.02
Log Output Level= 0
Friction Slope Method= 1
Unsteady Friction Slope Method= 2
Unsteady Bridges Friction Slope Method= 1
Parabolic Critical Depth
Global Vel Dist=  1 , 1 , 1
Global Log Level= 0
CheckData=True
Encroach Param= -1, 0, 0, 0
BEGIN DESCRIPTION:
Multiple Run
END DESCRIPTION:

--- Dawson T1.f01 (steady flow) ---

Flow Title=Multiple
Number of Profiles=7
Profile Names=10-year,25-year,50-year,1pct_min,100-year,1pct_plu,500-year
River Rch & RM= Dawson T1,Reach-1,2747
     189     236     273     157     314     626     414
Boundary for River Rch & Prof#=Dawson T1,Reach-1,1
Up Type=0
Dn Type=3
Dn Slope=0.005
Boundary for River Rch & Prof#=Dawson T1,Reach-1,2
Up Type=0
Dn Type=3
Dn Slope=0.005
Boundary for River Rch & Prof#=Dawson T1,Reach-1,3
Up Type=0
Dn Type=3
Dn Slope=0.005
Boundary for River Rch & Prof#=Dawson T1,Reach-1,4
Up Type=0
Dn Type=3
Dn Slope=0.005
Boundary for River Rch & Prof#=Dawson T1,Reach-1,5
Up Type=0
Dn Type=3
Dn Slope=0.005
Boundary for River Rch & Prof#=Dawson T1,Reach-1,6
Up Type=0
Dn Type=3
Dn Slope=0.005
Boundary for River Rch & Prof#=Dawson T1,Reach-1,7
Up Type=0
Dn Type=3
Dn Slope=0.005

--- Dawson T1.g01 (geometry) ---

Geom Title=Existing Conditions

River Reach=Dawson T1,Reach-1
Reach XY= 30
      2747276.00      6899611.00      2747042.65      6899377.67
      2747015.22      6899301.32      2746892.75      6899177.46
      2746865.52      6899162.16      2746777.60      6899157.14
      2746720.06      6899113.25      2746577.47      6899114.54
      2746482.04      6899202.86      2746427.65      6899215.46
      2746375.91      6899253.69      2746269.32      6899169.96
      2746184.17      6899254.94      2746162.51      6899324.71
      2746115.51      6899360.51      2746069.98      6899353.53
      2745974.50      6899264.62      2745881.89      6899258.45
      2745825.90      6899218.78      2745772.66      6899252.43
      2745726.00      6899218.54      2745585.68      6899350.81
      2745541.41      6899360.98      2745478.19      6899317.16
      2745331.61      6899255.41      2745312.27      6899198.02
      2745136.05      6899022.11      2745069.96      6899059.02
      2745032.04      6899059.40      2744926.00      6898961.00

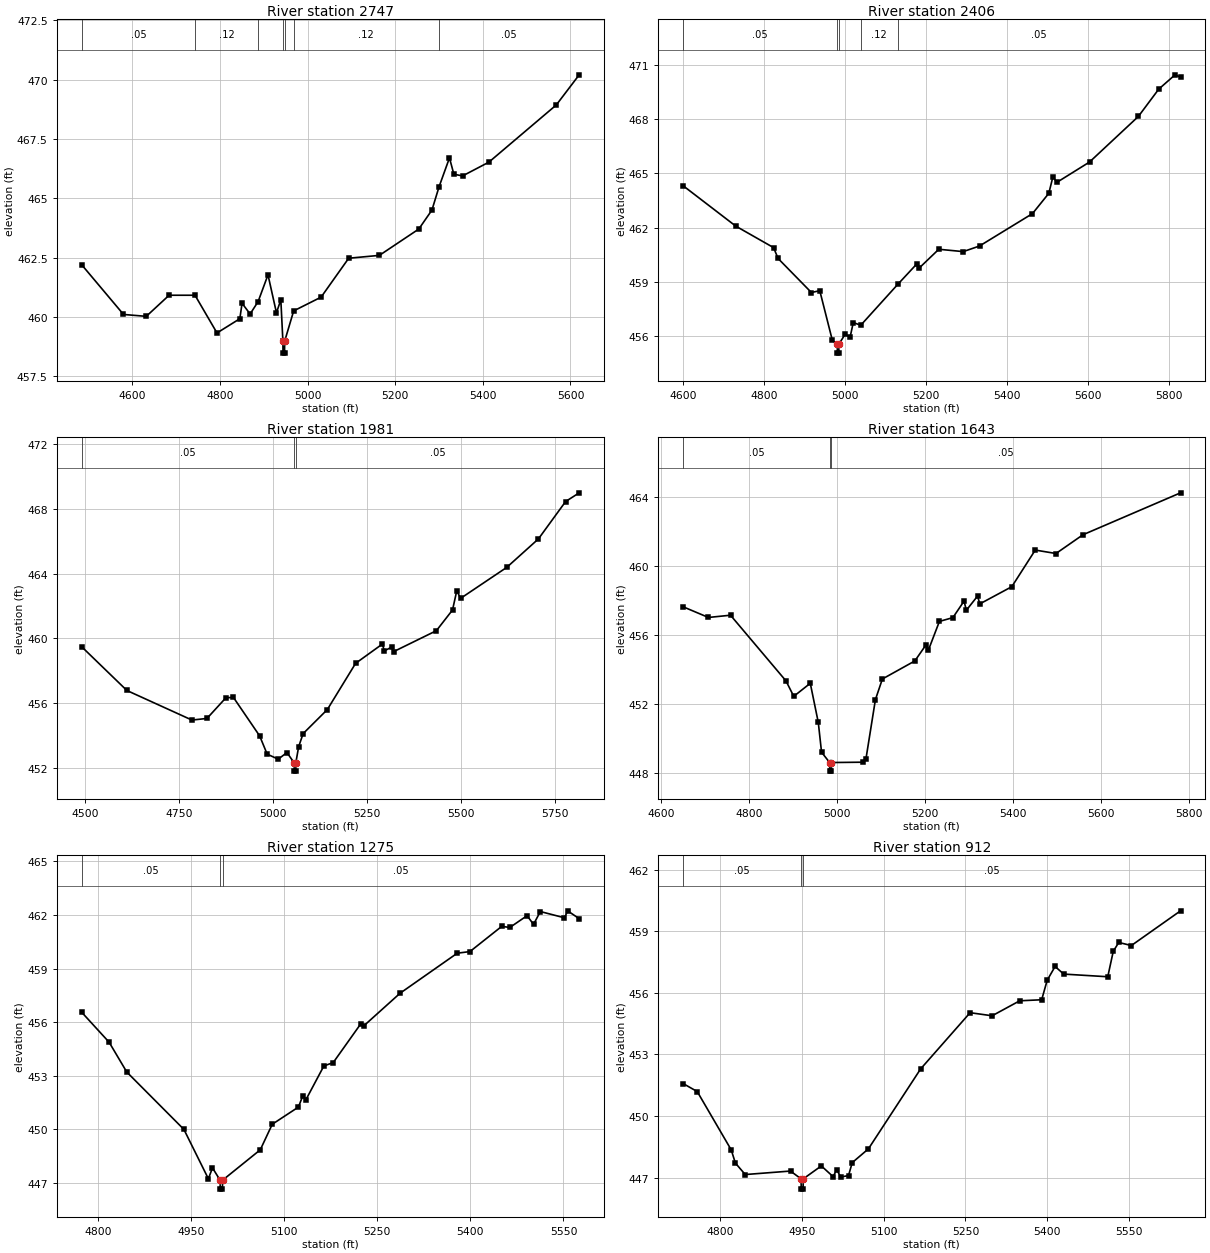
Type RM Length L Ch R = 1,2747,341,341,341
BEGIN DESCRIPTION:
Dawson T1 2.0
END DESCRIPTION:
XS GIS Cut Line= 4
      2746992.93      6898873.59      2747077.12      6899313.98
      2746989.62      6899410.34      2746980.08      6899967.03
#Sta/Elev= 30
  4484.6  462.19  4579.8  460.10  4631.8  460.02  4683.9  460.91  4743.0  460.91
  4793.2  459.32  4845.3  459.92  4850.4  460.57  4868.8  460.12  4887.0  460.64
  4909.6  461.77  4928.9  460.17  4938.9  460.72  4943.6  458.97  4943.9  458.47
  4947.4  458.47  4947.6  458.97  4968.2  460.25  5030.8  460.83  5093.8  462.47
  5163.8  462.59  5253.8  463.70  5283.8  464.50  5300.0  465.48  5323.8  466.70
  5333.8  466.01  5353.8  465.94  5413.8  466.52  5567.6  468.93  5619.9  470.20
#Mann=7,-1,0
  4484.6    0.05       0  4743.0    0.12       0  4887.0    0.05       0
  4943.6    0.07       0  4947.6    0.05       0  4968.2    0.12       0
  5300.0    0.05       0
Bank Sta=4943.6,4947.6
Exp/Cntr=0.3,0.1

Type RM Length L Ch R = 1,2406,425,425,425
BEGIN DESCRIPTION:
Mapping XS f67d4b63
END DESCRIPTION:
XS GIS Cut Line= 3
      2746901.93      6898775.72      2746793.44      6899170.66
      2746878.07      6899984.50
#Sta/Elev= 30
  4600.7  464.32  4730.6  462.09  4824.0  460.90  4835.1  460.30  4917.3  458.42
  4938.0  458.52  4969.1  455.77  4981.2  455.57  4981.5  455.07  4985.0  455.07
  4985.2  455.57  5000.3  456.10  5013.0  455.97  5020.7  456.76  5039.1  456.61
  5130.5  458.87  5178.3  460.02  5183.3  459.77  5231.8  460.81  5292.1  460.68
  5332.3  460.99  5463.0  462.78  5503.3  463.90  5513.3  464.80  5523.4  464.51
  5603.8  465.63  5724.4  468.15  5774.7  469.66  5814.9  470.45  5828.5  470.32
#Mann=5,-1,0
  4600.7    0.05       0  4981.2    0.04       0  4985.2    0.05       0
  5039.1    0.12       0  5130.5    0.05       0
Bank Sta=4981.2,4985.2
Exp/Cntr=0.3,0.1

Type RM Length L Ch R = 1,1981,338,338,338
BEGIN DESCRIPTION:
Mapping XS af83727c
END DESCRIPTION:
XS GIS Cut Line= 3
      2746446.21      6898708.41      2746424.51      6899216.23
      2746721.40      6899974.71
#Sta/Elev= 30
  4491.0  459.47  4610.9  456.77  4783.9  454.94  4823.9  455.04  4873.9  456.31
  4894.0  456.35  4964.0  453.96  4984.0  452.83  5013.4  452.52  5036.6  452.93
  5056.1  452.28  5056.3  451.78  5059.8  451.78  5060.1  452.28  5067.7  453.29
  5079.6  454.10  5144.0  455.59  5219.2  458.45  5290.2  459.64  5295.6  459.22
  5314.7  459.45  5320.0  459.17  5434.0  460.47  5476.9  461.75  5488.2  462.94
  5498.4  462.47  5621.3  464.39  5705.4  466.15  5777.6  468.46  5813.8  469.00
#Mann=3,-1,0
  4491.0    0.05       0  5056.1    0.04       0  5060.1    0.05       0
Bank Sta=5056.1,5060.1
Exp/Cntr=0.3,0.1

Type RM Length L Ch R = 1,1643,368,368,368
BEGIN DESCRIPTION:
Mapping XS 383c66fb
END DESCRIPTION:
XS GIS Cut Line= 4
      2746257.42      6898938.43      2746161.93      6899240.10
      2746250.90      6899394.18      2746467.93      6899991.00
#Sta/Elev= 30
  4650.9  457.64  4708.3  457.02  4758.5  457.15  4884.4  453.33  4902.1  452.43
  4939.6  453.19  4957.8  450.91  4965.2  449.18  4983.6  448.58  4983.8  448.08
  4987.3  448.08  4987.6  448.58  5060.2  448.60  5066.0  448.79  5087.5  452.24
  5103.3  453.44  5177.0  454.49  5202.2  455.42  5207.5  455.10  5232.8  456.79
  5263.4  457.01  5288.7  457.97  5294.0  457.44  5319.3  458.26  5324.6  457.81
  5397.2  458.81  5450.4  460.94  5497.5  460.74  5558.7  461.83  5780.3  464.27
#Mann=3,-1,0
  4650.9    0.05       0  4983.6    0.04       0  4987.6    0.05       0
Bank Sta=4983.6,4987.6
Exp/Cntr=0.3,0.1

Type RM Length L Ch R = 1,1275,363,363,363
BEGIN DESCRIPTION:
Mapping XS e1236ff9
END DESCRIPTION:
XS GIS Cut Line= 3
      2745999.16      6899055.65      2745903.68      6899263.97
      2746025.20      6899822.96
#Sta/Elev= 30
  4774.1  456.55  4818.1  454.88  4846.6  453.21  4938.6  450.00  4978.0  447.24
  4984.6  447.85  4996.9  447.16  4997.1  446.66  5000.6  446.66  5000.9  447.16
  5061.6  448.86  5080.9  450.29  5123.0  451.25  5130.0  451.87  5135.1  451.66
  5164.0  453.55  5179.1  453.74  5223.1  455.89  5228.2  455.79  5286.8  457.62
  5378.9  459.86  5399.3  459.95  5450.5  461.36  5463.6  461.30  5491.4  461.96
  5501.7  461.47  5512.7  462.19  5551.6  461.84  5556.7  462.23  5575.3  461.79
#Mann=3,-1,0
  4774.1    0.05       0  4996.9    0.04       0  5000.9    0.05       0
Bank Sta=4996.9,5000.9
Exp/Cntr=0.3,0.1

Type RM Length L Ch R = 1,912,35,35,35
BEGIN DESCRIPTION:
Mapping XS f2512eff
END DESCRIPTION:
XS GIS Cut Line= 6
      2745569.01      6899090.33      2745531.17      6899200.26
      2745543.28      6899245.58      2745652.26      6899348.64
      2745680.57      6899390.88      2745764.33      6899933.25
#Sta/Elev= 30
  4731.7  451.58  4757.6  451.19  4820.0  448.35  4827.6  447.71  4845.7  447.15
  4928.8  447.32  4948.2  446.94  4948.5  446.44  4952.0  446.44  4952.2  446.94
  4985.4  447.57  5006.9  447.05  5013.7  447.38  5021.1  447.03  5035.3  447.10
  5042.1  447.73  5071.8  448.40  5167.6  452.29  5258.5  455.03  5298.9  454.88
  5349.6  455.61  5389.9  455.66  5400.0  456.61  5414.5  457.28  5430.3  456.91
  5511.2  456.78  5521.3  458.02  5531.4  458.45  5554.5  458.30  5644.8  459.99
#Mann=3,-1,0
  4731.7    0.05       0  4948.2    0.04       0  4952.2    0.05       0
Bank Sta=4948.2,4952.2
Exp/Cntr=0.3,0.1

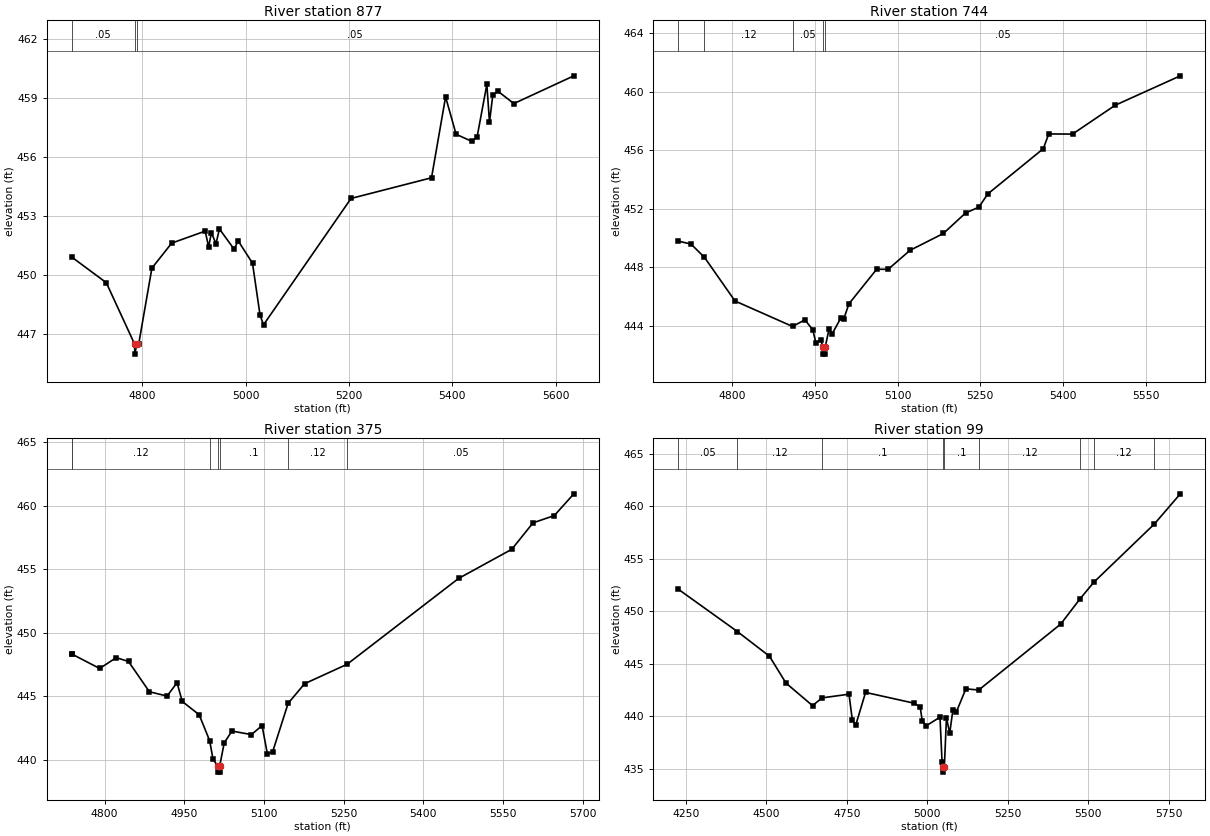
Type RM Length L Ch R = 1,877,133,133,133
BEGIN DESCRIPTION:
Mapping XS dc8ff745
END DESCRIPTION:
XS GIS Cut Line= 6
      2745548.72      6899079.48      2745472.97      6899181.55
      2745489.14      6899240.82      2745590.91      6899338.51
      2745630.70      6899391.42      2745740.34      6899955.14
#Sta/Elev= 30
  4663.9  450.90  4730.7  449.60  4785.6  446.47  4785.8  445.97  4789.6  446.47
  4793.3  446.47  4818.9  450.34  4857.2  451.61  4922.0  452.22  4928.6  451.42
  4934.0  452.13  4942.9  451.58  4949.5  452.33  4978.0  451.30  4985.7  451.73
  5013.5  450.59  5028.1  447.95  5034.8  447.46  5204.1  453.88  5359.8  454.93
  5387.0  459.04  5407.3  457.14  5437.8  456.78  5448.0  457.01  5466.8  459.67
  5471.9  457.76  5478.5  459.16  5488.6  459.32  5519.1  458.70  5635.1  460.11
#Mann=3,-1,0
  4663.9    0.05       0  4785.6    0.04       0  4789.6    0.05       0
Bank Sta=4785.6,4789.6
Exp/Cntr=0.3,0.1

Type RM Length L Ch R = 1,744,369,369,369
BEGIN DESCRIPTION:
Mapping XS e8097441
END DESCRIPTION:
XS GIS Cut Line= 6
      2745487.18      6899079.68      2745409.23      6899148.84
      2745415.98      6899233.86      2745458.83      6899281.65
      2745481.45      6899316.83      2745554.48      6899927.98
#Sta/Elev= 30
  4701.9  449.80  4725.0  449.60  4749.5  448.69  4804.9  445.71  4909.3  443.97
  4931.7  444.42  4945.9  443.75  4951.8  442.84  4960.2  443.04  4964.7  442.58
  4964.9  442.08  4968.4  442.08  4968.7  442.58  4975.4  443.77  4981.3  443.47
  4996.5  444.52  5002.0  444.46  5011.7  445.52  5062.0  447.88  5082.6  447.87
  5122.5  449.17  5182.9  450.32  5223.2  451.72  5247.4  452.12  5263.5  453.02
  5364.2  456.11  5374.2  457.12  5417.3  457.11  5494.7  459.08  5612.9  461.09
#Mann=5,-1,0
  4701.9    0.05       0  4749.5    0.12       0  4909.3    0.05       0
  4964.7    0.04       0  4968.7    0.05       0
Bank Sta=4964.7,4968.7
Exp/Cntr=0.3,0.1

Type RM Length L Ch R = 1,375,276,276,276
BEGIN DESCRIPTION:
Mapping XS 9a6040fc
END DESCRIPTION:
XS GIS Cut Line= 4
      2745466.44      6899027.25      2745210.94      6899100.79
      2745196.59      6899148.93      2745207.81      6899777.82
#Sta/Elev= 30
  4738.1  448.32  4738.4  448.32  4790.6  447.19  4821.8  448.04  4844.9  447.74
  4884.2  445.36  4917.5  445.02  4936.3  446.07  4946.0  444.60  4977.9  443.55
  4997.7  441.51  5003.9  440.07  5012.6  439.54  5012.9  439.04  5016.4  439.04
  5016.6  439.54  5025.1  441.35  5039.7  442.27  5076.3  441.99  5096.3  442.70
  5106.3  440.48  5116.3  440.65  5145.4  444.45  5176.3  445.99  5256.4  447.52
  5466.3  454.27  5566.4  456.56  5606.4  458.64  5646.4  459.21  5683.2  460.92
#Mann=7,-1,0
  4738.1    0.05       0  4738.4    0.12       0  4997.7     0.1       0
  5012.6    0.07       0  5016.6     0.1       0  5145.4    0.12       0
  5256.4    0.05       0
Bank Sta=5012.6,5016.6
Exp/Cntr=0.3,0.1

Type RM Length L Ch R = 1,99,0,0,0
BEGIN DESCRIPTION:
Dawson T1 1.0
END DESCRIPTION:
XS GIS Cut Line= 4
      2745651.01      6899036.00      2745051.00      6898886.00
      2744995.80      6899031.72      2745081.83      6899813.70
#Sta/Elev= 30
  4225.7  452.09  4409.8  448.05  4509.2  445.71  4560.7  443.15  4643.2  441.00
  4672.7  441.74  4756.6  442.09  4766.9  439.65  4777.2  439.11  4808.1  442.26
  4959.4  441.23  4977.8  440.88  4984.3  439.57  4996.9  439.09  5039.5  439.90
  5046.0  435.61  5049.1  435.17  5049.3  434.67  5053.1  435.17  5059.6  439.85
  5069.7  438.37  5079.8  440.63  5089.8  440.36  5120.0  442.60  5160.0  442.49
  5415.0  448.77  5475.2  451.18  5518.4  452.77  5705.8  458.29  5786.7  461.17
#Mann=9,-1,0
  4225.7    0.05       0  4409.8    0.12       0  4672.7     0.1       0
  5049.1    0.07       0  5053.1     0.1       0  5160.0    0.12       0
  5475.2    0.05       0  5518.4    0.12       0  5705.8    0.05       0
Bank Sta=5049.1,5053.1
Exp/Cntr=0.3,0.1

Chan Stop Cuts=-1