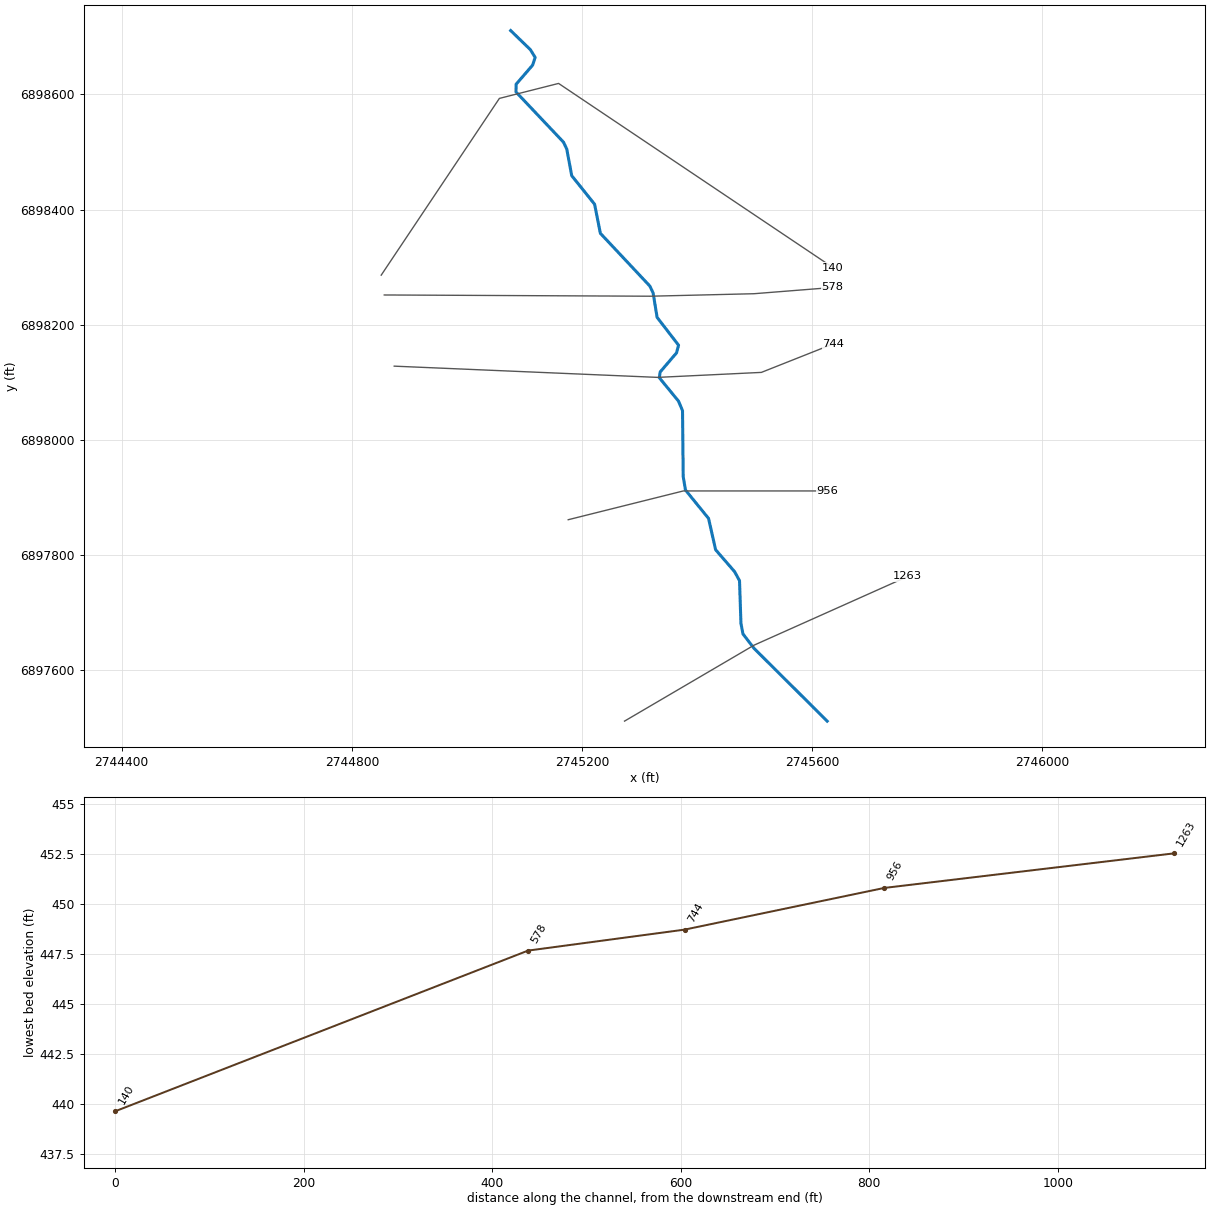
--- Dawson T2.prj (project) ---

Proj Title=Dawson T2 Base Level Engineering
Current Plan=p01
Default Exp/Contr=0.3,0.1
English Units
Geom File=g01
Flow File=f01
Plan File=p01
BEGIN DESCRIPTION:
Dawson T2
END DESCRIPTION:

--- Dawson T2.p01 (plan) ---

Plan Title=Multiple Run
Short Identifier=Multiple
Geom File=g01
Flow File=f01
Subcritical Flow
K Sum by GR= 0
Std Step Tol= 0.01
Critical Tol= 0.01
Num of Std Step Trials= 20
Max Error Tol= 0.3
Flow Tol Ratio= 0.001
Split Flow NTrial= 30
Split Flow Tol= 0.02
Split Flow Ratio= 0.02
Log Output Level= 0
Friction Slope Method= 1
Unsteady Friction Slope Method= 2
Unsteady Bridges Friction Slope Method= 1
Parabolic Critical Depth
Global Vel Dist=  1 , 1 , 1
Global Log Level= 0
CheckData=True
Encroach Param= -1, 0, 0, 0
BEGIN DESCRIPTION:
Multiple Run
END DESCRIPTION:

--- Dawson T2.f01 (steady flow) ---

Flow Title=Multiple
Number of Profiles=7
Profile Names=10-year,25-year,50-year,1pct_min,100-year,1pct_plu,500-year
River Rch & RM= Dawson T2,Reach-1,1263
     154     191     218     125     249     497     324
Boundary for River Rch & Prof#=Dawson T2,Reach-1,1
Up Type=0
Dn Type=3
Dn Slope=0.005
Boundary for River Rch & Prof#=Dawson T2,Reach-1,2
Up Type=0
Dn Type=3
Dn Slope=0.005
Boundary for River Rch & Prof#=Dawson T2,Reach-1,3
Up Type=0
Dn Type=3
Dn Slope=0.005
Boundary for River Rch & Prof#=Dawson T2,Reach-1,4
Up Type=0
Dn Type=3
Dn Slope=0.005
Boundary for River Rch & Prof#=Dawson T2,Reach-1,5
Up Type=0
Dn Type=3
Dn Slope=0.005
Boundary for River Rch & Prof#=Dawson T2,Reach-1,6
Up Type=0
Dn Type=3
Dn Slope=0.005
Boundary for River Rch & Prof#=Dawson T2,Reach-1,7
Up Type=0
Dn Type=3
Dn Slope=0.005

--- Dawson T2.g01 (geometry) ---

Geom Title=Existing Conditions

River Reach=Dawson T2,Reach-1
Reach XY= 30
      2745626.00      6897511.00      2745498.87      6897637.47
      2745479.61      6897662.49      2745476.13      6897681.05
      2745473.67      6897755.03      2745465.16      6897770.65
      2745432.11      6897808.82      2745419.88      6897863.18
      2745379.76      6897912.56      2745375.81      6897935.92
      2745374.61      6898050.56      2745367.56      6898067.19
      2745334.28      6898107.78      2745335.77      6898117.73
      2745364.19      6898150.96      2745367.76      6898164.23
      2745330.44      6898212.65      2745323.53      6898254.95
      2745317.86      6898267.04      2745231.85      6898358.71
      2745221.81      6898409.27      2745182.10      6898458.81
      2745173.48      6898504.97      2745167.82      6898517.06
      2745085.21      6898604.34      2745085.36      6898617.67
      2745114.15      6898651.00      2745118.48      6898664.33
      2745110.31      6898677.78      2745076.00      6898711.00

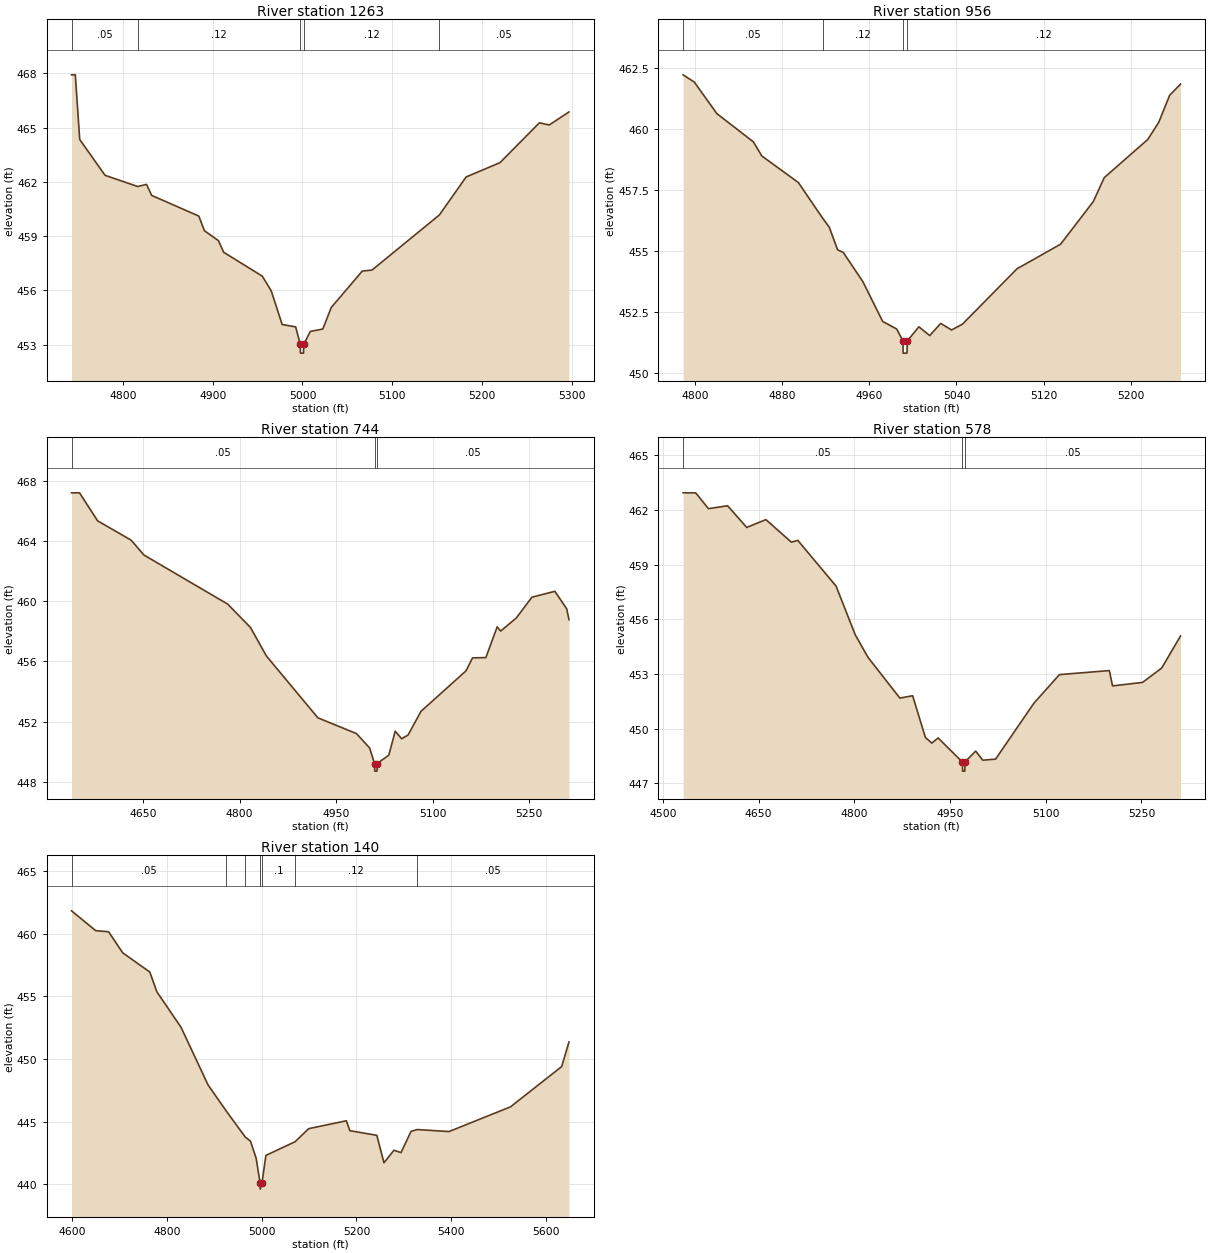
Type RM Length L Ch R = 1,1263,307,307,307
BEGIN DESCRIPTION:
Dawson T2 3.0
END DESCRIPTION:
XS GIS Cut Line= 3
      2745273.83      6897511.00      2745499.06      6897643.05
      2745766.01      6897762.41
#Sta/Elev= 30
  4743.0  467.91  4747.2  467.91  4752.1  464.34  4780.3  462.36  4816.7  461.74
  4826.4  461.86  4832.2  461.25  4884.6  460.11  4890.9  459.30  4906.5  458.75
  4912.3  458.11  4955.3  456.79  4965.2  455.98  4977.4  454.12  4992.4  453.99
  4997.4  453.04  4997.7  452.54  5001.2  452.54  5001.4  453.04  5008.8  453.74
  5022.6  453.87  5032.0  455.06  5066.5  457.07  5077.4  457.13  5152.3  460.17
  5182.1  462.27  5219.8  463.06  5263.6  465.26  5274.6  465.14  5296.5  465.86
#Mann=5,-1,0
  4743.0    0.05       0  4816.7    0.12       0  4997.4    0.07       0
  5001.4    0.12       0  5152.3    0.05       0
Bank Sta=4997.4,5001.4
Exp/Cntr=0.3,0.1

Type RM Length L Ch R = 1,956,212,212,212
BEGIN DESCRIPTION:
Dawson T2 2.0
END DESCRIPTION:
XS GIS Cut Line= 3
      2745175.99      6897861.00      2745376.00      6897911.00
      2745626.04      6897911.00
#Sta/Elev= 30
  4789.3  462.23  4799.6  461.93  4820.2  460.64  4853.7  459.48  4861.5  458.90
  4895.0  457.81  4917.2  456.35  4923.3  455.98  4931.0  455.05  4936.2  454.94
  4954.2  453.74  4972.3  452.11  4985.2  451.80  4990.9  451.31  4991.1  450.81
  4994.6  450.81  4994.9  451.31  5005.5  451.89  5015.5  451.53  5025.5  452.03
  5035.5  451.76  5045.5  452.00  5095.5  454.27  5135.5  455.28  5165.5  457.03
  5175.5  458.01  5215.5  459.58  5225.5  460.28  5235.5  461.39  5245.5  461.85
#Mann=4,-1,0
  4789.3    0.05       0  4917.2    0.12       0  4990.9    0.07       0
  4994.9    0.12       0
Bank Sta=4990.9,4994.9
Exp/Cntr=0.3,0.1

Type RM Length L Ch R = 1,744,166,166,166
BEGIN DESCRIPTION:
Mapping XS 88e86f06
END DESCRIPTION:
XS GIS Cut Line= 4
      2744873.60      6898127.86      2745331.53      6898108.33
      2745511.65      6898117.01      2745636.33      6898166.45
#Sta/Elev= 30
  4539.0  467.20  4551.4  467.20  4579.5  465.34  4631.5  464.06  4651.5  463.07
  4781.6  459.81  4817.0  458.26  4841.7  456.37  4921.7  452.26  4981.8  451.21
  5002.1  450.26  5009.8  449.22  5010.1  448.72  5013.6  448.72  5013.8  449.22
  5031.9  449.78  5041.9  451.37  5051.9  450.87  5061.9  451.12  5081.9  452.69
  5151.9  455.38  5162.0  456.24  5182.7  456.26  5200.3  458.30  5205.7  458.02
  5230.0  458.89  5254.3  460.27  5289.9  460.66  5308.3  459.50  5311.8  458.78
#Mann=3,-1,0
  4539.0    0.05       0  5009.8    0.05       0  5013.8    0.05       0
Bank Sta=5009.8,5013.8
Exp/Cntr=0.3,0.1

Type RM Length L Ch R = 1,578,438,438,438
BEGIN DESCRIPTION:
Mapping XS 54144963
END DESCRIPTION:
XS GIS Cut Line= 4
      2744856.27      6898251.56      2745318.51      6898249.39
      2745498.63      6898253.73      2745635.38      6898264.58
#Sta/Elev= 30
  4531.6  462.95  4551.3  462.95  4571.3  462.08  4601.3  462.24  4631.3  461.05
  4661.3  461.48  4701.3  460.24  4711.3  460.34  4771.3  457.83  4801.3  455.16
  4821.3  453.92  4871.3  451.68  4891.3  451.81  4911.3  449.52  4921.3  449.21
  4931.3  449.49  4969.3  448.17  4969.6  447.67  4973.1  447.67  4973.3  448.17
  4990.1  448.77  5001.3  448.27  5021.3  448.33  5081.4  451.40  5121.4  452.97
  5199.6  453.19  5204.6  452.35  5251.6  452.54  5281.7  453.33  5311.2  455.09
#Mann=3,-1,0
  4531.6    0.05       0  4969.3    0.04       0  4973.3    0.05       0
Bank Sta=4969.3,4973.3
Exp/Cntr=0.3,0.1

Type RM Length L Ch R = 1,140,0,0,0
BEGIN DESCRIPTION:
Dawson T2 1.0
END DESCRIPTION:
XS GIS Cut Line= 4
      2744851.00      6898286.01      2745056.35      6898593.14
      2745159.22      6898619.18      2745636.21      6898299.09
#Sta/Elev= 30
  4598.7  461.81  4649.7  460.23  4676.9  460.14  4706.8  458.46  4763.9  456.93
  4778.9  455.35  4829.9  452.52  4887.0  447.92  4925.5  445.84  4965.5  443.77
  4976.4  443.45  4988.4  442.08  4996.7  440.12  4997.0  439.62  5000.7  440.12
  5009.0  442.31  5070.7  443.40  5099.2  444.44  5178.8  445.07  5186.2  444.28
  5243.2  443.91  5258.2  441.72  5279.3  442.72  5294.2  442.53  5315.3  444.22
  5328.3  444.37  5395.5  444.21  5525.3  446.18  5633.3  449.39  5648.7  451.35
#Mann=7,-1,0
  4598.7    0.05       0  4925.5    0.12       0  4965.5     0.1       0
  4996.7    0.07       0  5000.7     0.1       0  5070.7    0.12       0
  5328.3    0.05       0
Bank Sta=4996.7,5000.7
Exp/Cntr=0.3,0.1

Chan Stop Cuts=-1