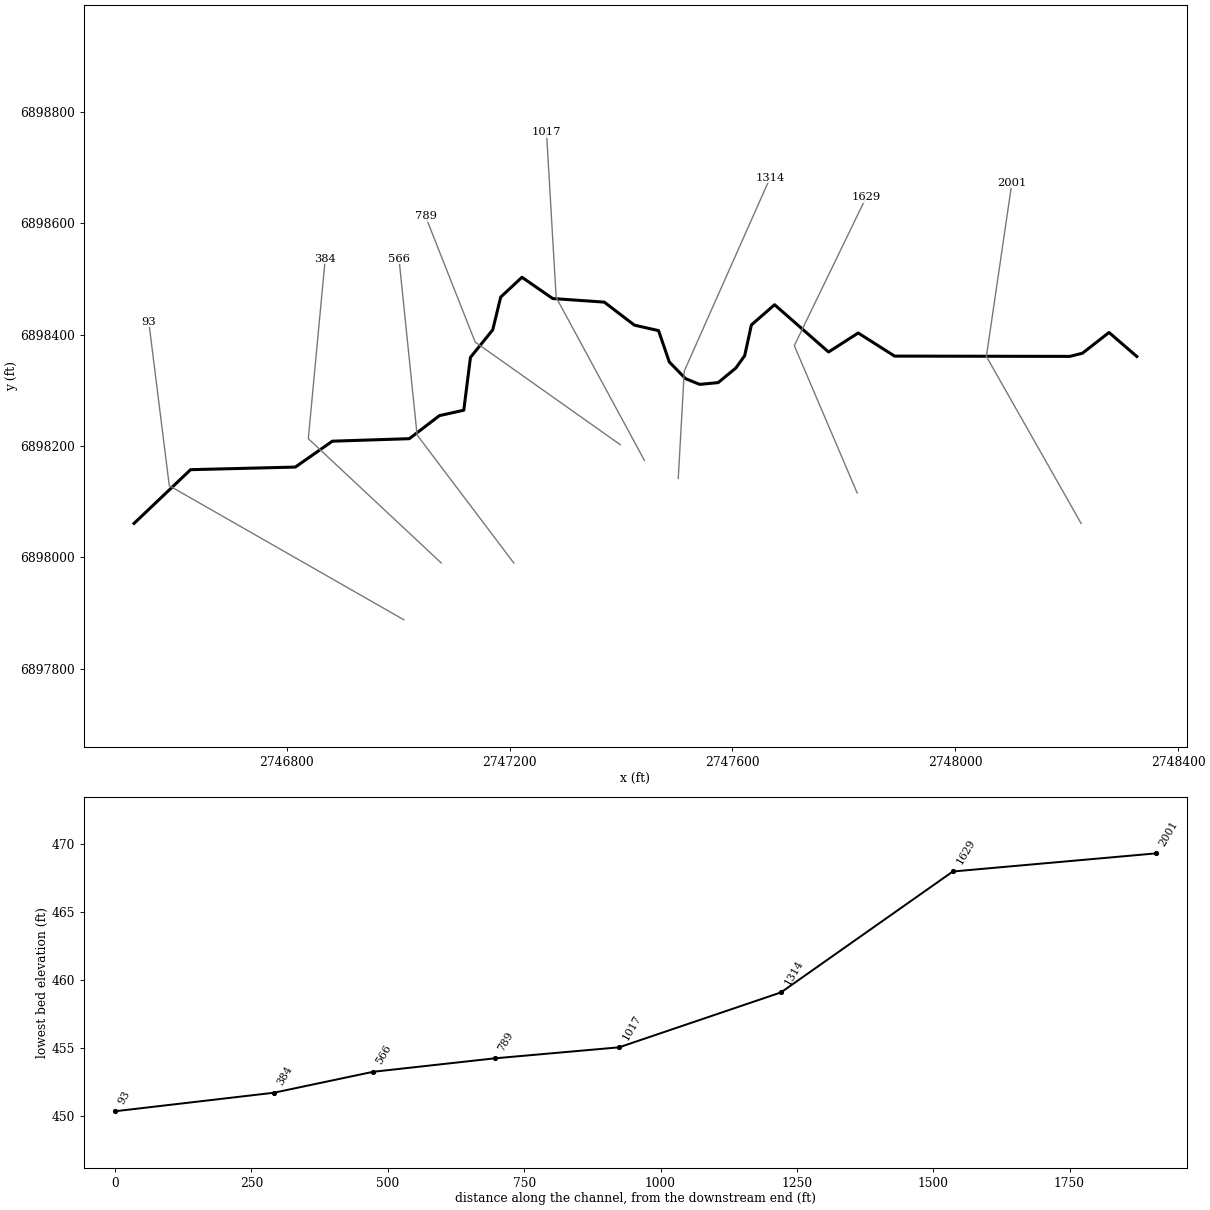
--- Dawson T3.prj (project) ---

Proj Title=Dawson T3 Base Level Engineering
Current Plan=p01
Default Exp/Contr=0.3,0.1
English Units
Geom File=g01
Flow File=f01
Plan File=p01
Y Axis Title=Elevation
X Axis Title(PF)=Main Channel Distance
X Axis Title(XS)=Station
BEGIN DESCRIPTION:
Dawson T3
END DESCRIPTION:
DSS Export Rating Curves= 0
DSS Export Rating Curve Sorted= 0
DSS Export Volume Flow Curves= 0
DXF OffsetX= 0
DXF OffsetY= 0
DXF ScaleX= 1
DXF ScaleY= 10

--- Dawson T3.p01 (plan) ---

Plan Title=Multiple Run
Short Identifier=Multiple
Geom File=g01
Flow File=f01
Subcritical Flow
K Sum by GR= 0
Std Step Tol= 0.01
Critical Tol= 0.01
Num of Std Step Trials= 20
Max Error Tol= 0.3
Flow Tol Ratio= 0.001
Split Flow NTrial= 30
Split Flow Tol= 0.02
Split Flow Ratio= 0.02
Log Output Level= 0
Friction Slope Method= 1
Unsteady Friction Slope Method= 2
Unsteady Bridges Friction Slope Method= 1
Parabolic Critical Depth
Global Vel Dist=  1 , 1 , 1
Global Log Level= 0
CheckData=True
Encroach Param= -1, 0, 0, 0
BEGIN DESCRIPTION:
Multiple Run
END DESCRIPTION:

--- Dawson T3.f01 (steady flow) ---

Flow Title=Multiple
Program Version=4.10
Number of Profiles= 7
Profile Names=10-year,25-year,50-year,1pct_min,100-year,1pct_plu,500-year
River Rch & RM=Dawson T3,Reach-1         ,2001
     175     218     251     144     287     573     377
Boundary for River Rch & Prof#=Dawson T3,Reach-1         , 1
Up Type= 0
Dn Type= 3
Dn Slope=0.00535
Boundary for River Rch & Prof#=Dawson T3,Reach-1         , 2
Up Type= 0
Dn Type= 3
Dn Slope=0.00535
Boundary for River Rch & Prof#=Dawson T3,Reach-1         , 3
Up Type= 0
Dn Type= 3
Dn Slope=0.00535
Boundary for River Rch & Prof#=Dawson T3,Reach-1         , 4
Up Type= 0
Dn Type= 3
Dn Slope=0.00535
Boundary for River Rch & Prof#=Dawson T3,Reach-1         , 5
Up Type= 0
Dn Type= 3
Dn Slope=0.00535
Boundary for River Rch & Prof#=Dawson T3,Reach-1         , 6
Up Type= 0
Dn Type= 3
Dn Slope=0.00535
Boundary for River Rch & Prof#=Dawson T3,Reach-1         , 7
Up Type= 0
Dn Type= 3
Dn Slope=0.00535
DSS Import GetInterval= 0
DSS Import GetPeak= 0
DSS Import FillOption= 0

--- Dawson T3.g01 (geometry) ---

Geom Title=Existing Conditions
Program Version=4.10

River Reach=Dawson T3       ,Reach-1
Reach XY= 30
        2748326.        6898361.      2748276.14      6898404.09
      2748228.48      6898366.88      2748206.02      6898361.14
      2747891.16      6898361.65       2747825.9      6898403.19
      2747772.66      6898369.02      2747675.79      6898453.99
      2747634.17      6898417.69      2747622.11      6898362.43
      2747606.36      6898340.33      2747574.54        6898314.
       2747541.3      6898310.83      2747516.04      6898321.09
      2747486.76      6898351.15      2747467.51      6898407.46
      2747424.16      6898417.27      2747370.06      6898458.68
      2747277.49      6898465.11      2747222.33      6898503.31
      2747184.13       6898467.7      2747169.86      6898408.88
      2747129.86      6898359.35      2747117.85      6898264.37
      2747074.22       6898254.7      2747020.09      6898213.24
      2746881.94      6898208.73      2746815.49      6898162.22
      2746627.44      6898157.52        2746526.        6898061.

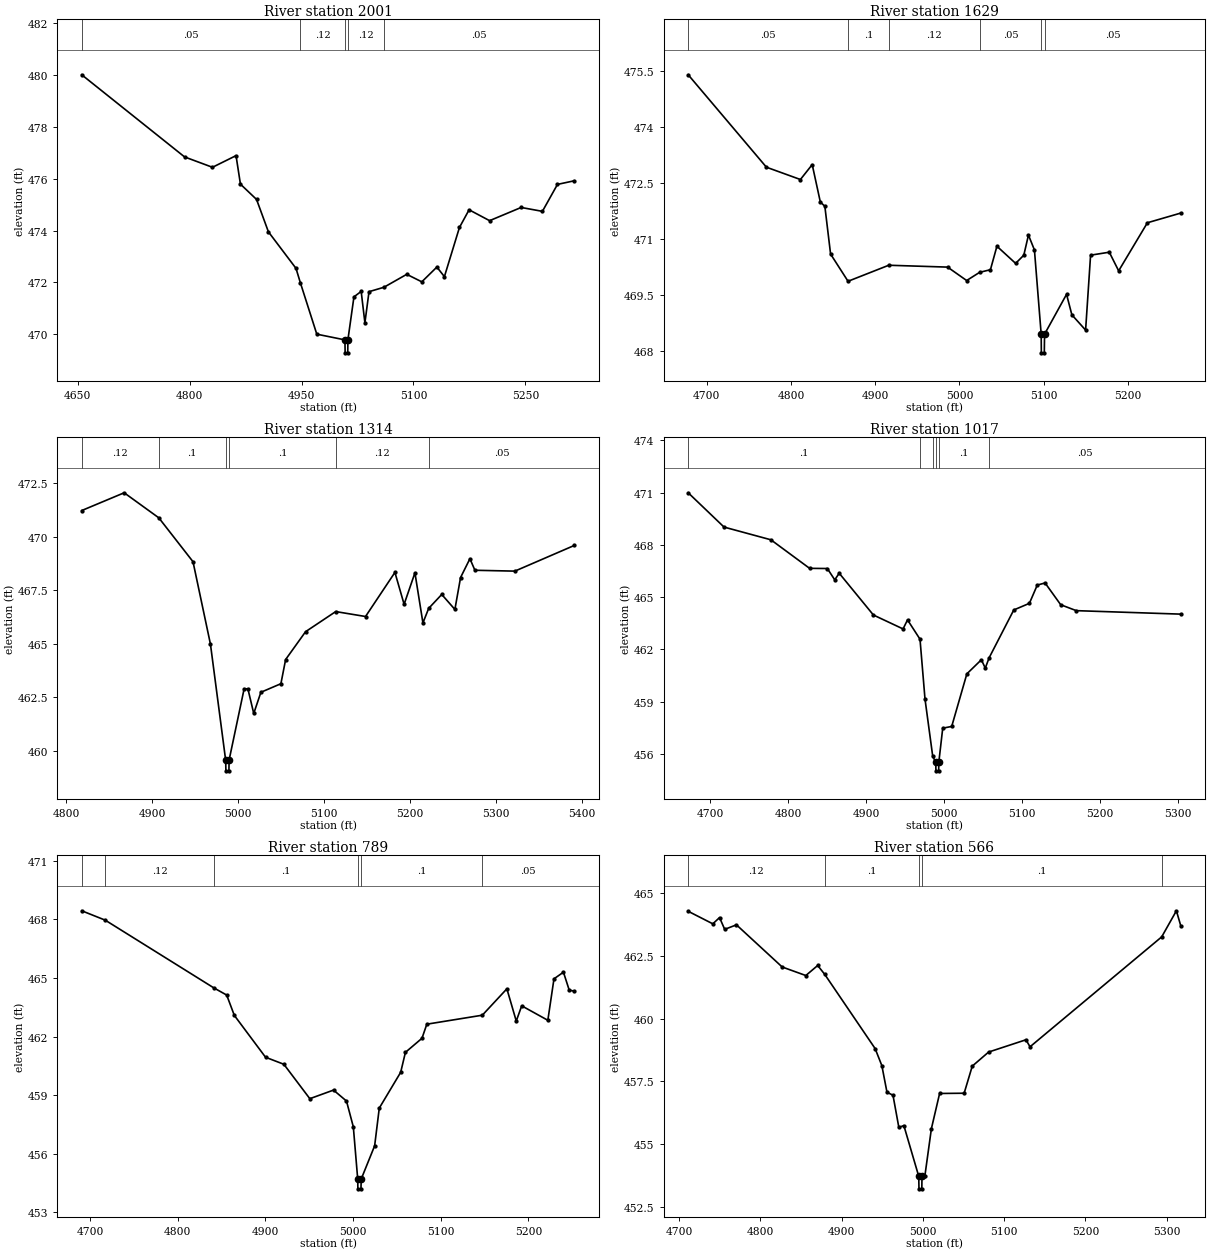
Type RM Length L Ch R = 1 ,2001    ,372,372,372
BEGIN DESCRIPTION:
Dawson T3 2.0
END DESCRIPTION:
XS GIS Cut Line= 3
      2748225.99      6898061.01        2748056.        6898361.
      2748101.82      6898673.35
#Sta/Elev= 30
  4655.2  480.01  4793.1  476.84  4830.5  476.44  4862.1  476.89    4868  475.79
  4889.6   475.2  4905.5  473.95  4942.5  472.54  4948.3  471.99  4970.4     470
  5008.1  469.78  5008.4  469.28  5011.9  469.28  5012.1  469.78  5020.2  471.44
  5029.9  471.65  5034.9  470.44  5040.4  471.64  5060.4  471.81    5091  472.31
  5111.2  472.02  5131.4  472.59  5141.5  472.22  5161.7  474.12  5174.6   474.8
  5202.1  474.38  5244.4  474.89  5272.9  474.74  5293.1  475.78  5315.7  475.92
#Mann= 5 ,-1 , 0
  4655.2     .05       0  4948.3     .12       0  5008.1     .07       0
  5012.1     .12       0  5060.4     .05       0
Bank Sta=5008.1,5012.1
XS Rating Curve= 0 ,0
Exp/Cntr=0.3,0.1

Type RM Length L Ch R = 1 ,1629    ,315,315,315
BEGIN DESCRIPTION:
Mapping XS b5fa6263
END DESCRIPTION:
XS GIS Cut Line= 3
      2747824.04      6898115.65      2747711.19      6898380.41
      2747840.33       6898647.3
#Sta/Elev= 30
  4678.2  475.41    4771  472.93  4811.3   472.6  4825.3     473  4834.9     472
  4840.3  471.88  4847.1   470.6  4867.8  469.87  4916.1   470.3  4985.9  470.25
  5008.5  469.89  5023.9  470.11  5036.7  470.18  5044.4  470.81  5066.6  470.35
  5076.3  470.57  5081.8  471.11  5088.9  470.71  5096.9  468.45  5097.1  467.95
  5100.6  467.95  5100.9  468.45    5127  469.52  5133.3  468.97  5149.6  468.56
  5155.5  470.57  5177.7  470.65  5188.8  470.15  5222.9  471.44  5262.5   471.7
#Mann= 6 ,-1 , 0
  4678.2     .05       0  4867.8      .1       0  4916.1     .12       0
  5023.9     .05       0  5096.9     .07       0  5100.9     .05       0
Bank Sta=5096.9,5100.9
XS Rating Curve= 0 ,0
Exp/Cntr=0.3,0.1

Type RM Length L Ch R = 1 ,1314    ,297,297,297
BEGIN DESCRIPTION:
Mapping XS da43998b
END DESCRIPTION:
XS GIS Cut Line= 3
      2747502.86      6898141.72      2747513.71      6898334.84
      2747667.79      6898682.06
#Sta/Elev= 30
  4817.9  471.22  4867.3  472.05  4907.6  470.88  4947.4  468.83  4967.7  464.98
  4985.4  459.56  4985.7  459.06  4989.2  459.06  4989.4  459.56  5006.9  462.89
  5011.3  462.89  5018.1  461.74  5026.4  462.73  5049.7  463.13  5055.2  464.26
  5078.4  465.56  5113.5   466.5  5148.2  466.27  5182.4  468.33  5193.1  466.84
  5205.7  468.31    5215  465.97  5221.7  466.65  5236.9   467.3  5252.2   466.6
  5258.8  468.09  5269.7  468.97  5275.5  468.43    5322  468.39  5391.2  469.59
#Mann= 6 ,-1 , 0
  4817.9     .12       0  4907.6      .1       0  4985.4     .07       0
  4989.4      .1       0  5113.5     .12       0  5221.7     .05       0
Bank Sta=4985.4,4989.4
XS Rating Curve= 0 ,0
Exp/Cntr=0.3,0.1

Type RM Length L Ch R = 1 ,1017    ,228,228,228
BEGIN DESCRIPTION:
Mapping XS 5f8e951f
END DESCRIPTION:
XS GIS Cut Line= 3
      2747442.11      6898174.23      2747283.68      6898467.21
      2747266.32      6898764.53
#Sta/Elev= 30
  4672.2  470.99  4718.1  469.02  4778.1  468.29  4827.7  466.65  4850.4  466.64
  4859.9  465.99  4865.6  466.37  4909.4  463.97  4947.4  463.17  4953.1  463.69
  4969.1  462.58  4975.5  459.14  4985.4  455.85  4989.2  455.52  4989.5  455.02
    4993  455.02  4993.2  455.52  4998.2  457.47  5009.7  457.57  5029.1  460.59
  5047.7   461.4  5052.7  460.92  5057.7  461.52  5089.2  464.26  5109.2  464.64
  5119.3  465.69  5129.3  465.81  5149.3  464.56  5169.3  464.22  5303.1  464.02
#Mann= 6 ,-1 , 0
  4672.2      .1       0  4969.1     .12       0  4985.4      .1       0
  4989.2     .07       0  4993.2      .1       0  5057.7     .05       0
Bank Sta=4989.2,4993.2
XS Rating Curve= 0 ,0
Exp/Cntr=0.3,0.1

Type RM Length L Ch R = 1 ,789     ,223,223,223
BEGIN DESCRIPTION:
Mapping XS 995bf61e
END DESCRIPTION:
XS GIS Cut Line= 3
      2747398.71      6898202.45      2747138.28      6898386.92
      2747049.32      6898612.57
#Sta/Elev= 30
  4690.7  468.43  4717.5  467.95  4841.2  464.49    4856  464.12  4864.7  463.08
  4900.3  460.94  4921.2  460.58  4950.8  458.82  4977.8  459.26  4992.6   458.7
  5000.4  457.38  5005.4  454.71  5005.6  454.21  5009.1  454.21  5009.4  454.71
  5024.7  456.41    5030  458.34  5054.4  460.17  5059.8  461.19  5078.7  461.91
  5084.2  462.63  5147.5  463.09  5175.5  464.44  5186.2  462.79  5192.4  463.57
  5222.2  462.83  5229.2  464.95    5240  465.29  5246.6  464.37  5252.4  464.32
#Mann= 6 ,-1 , 0
  4690.7      .1       0  4717.5     .12       0  4841.2      .1       0
  5005.4     .07       0  5009.4      .1       0  5147.5     .05       0
Bank Sta=5005.4,5009.4
XS Rating Curve= 0 ,0
Exp/Cntr=0.3,0.1

Type RM Length L Ch R = 1 ,566     ,182,182,182
BEGIN DESCRIPTION:
Mapping XS ca63a60e
END DESCRIPTION:
XS GIS Cut Line= 3
      2747207.73      6897989.78      2747034.11      6898219.82
      2747001.59      6898536.35
#Sta/Elev= 30
  4711.1  464.28  4741.4  463.78  4749.7  464.03    4756  463.56  4770.5  463.74
  4826.8  462.06  4855.9  461.72  4870.5  462.12  4879.1  461.77  4941.2  458.81
  4949.5  458.13  4955.8  457.07  4963.2  456.95  4970.4  455.67  4976.6  455.74
  4994.9  453.72  4995.2  453.22  4998.7  453.22  4998.9  453.72  5002.4  453.72
  5010.5  455.62  5020.6  457.02  5050.8  457.03  5060.8  458.11  5080.9  458.67
  5126.9  459.16  5131.9  458.88    5294  463.26  5312.1   464.3  5317.5   463.7
#Mann= 5 ,-1 , 0
  4711.1     .12       0  4879.1      .1       0  4994.9     .07       0
  4998.9      .1       0    5294     .05       0
Bank Sta=4994.9,4998.9
XS Rating Curve= 0 ,0
Exp/Cntr=0.3,0.1

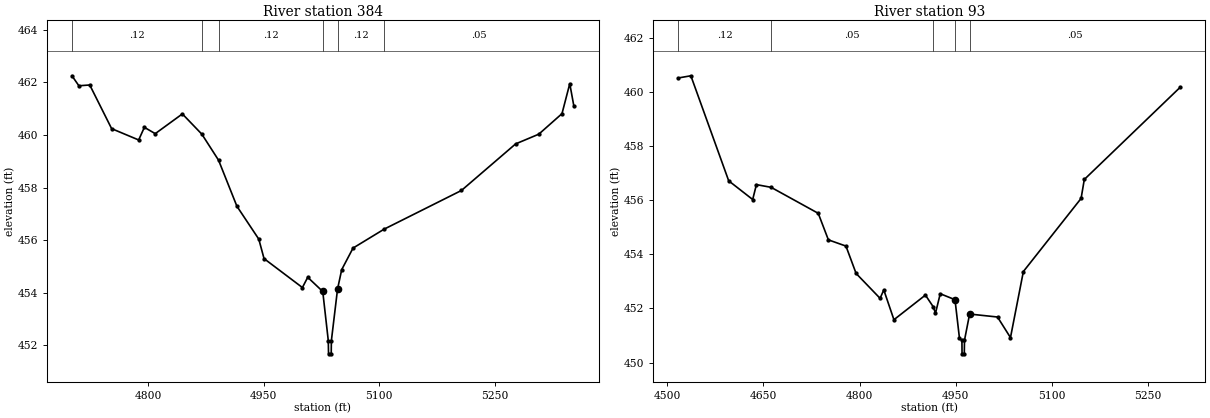
Type RM Length L Ch R = 1 ,384     ,291,291,291
BEGIN DESCRIPTION:
Mapping XS 37d2cd55
END DESCRIPTION:
XS GIS Cut Line= 3
      2747077.48      6897989.82       2746838.8      6898213.31
      2746869.15      6898536.31
#Sta/Elev= 30
  4701.2  462.25  4710.2  461.87  4724.3   461.9  4752.7  460.24  4787.8  459.81
  4795.2  460.29  4809.3  460.05  4844.5   460.8  4869.8  460.03  4891.5  459.04
  4915.3  457.29  4943.7  456.04  4950.5   455.3  5000.3   454.2  5007.2  454.59
  5026.7  454.05  5033.9  452.18  5034.2  451.68  5037.7  451.68  5037.9  452.18
  5045.9  454.14  5051.3  454.88    5066   455.7  5106.4  456.42  5206.7  457.89
    5277  459.66  5307.1  460.03  5337.2  460.81  5347.3  461.95  5352.6   461.1
#Mann= 6 ,-1 , 0
  4701.2     .12       0  4869.8     .05       0  4891.5     .12       0
  5026.7     .04       0  5045.9     .12       0  5106.4     .05       0
Bank Sta=5026.7,5045.9
XS Rating Curve= 0 ,0
Exp/Cntr=0.3,0.1

Type RM Length L Ch R = 1 ,93      ,0,0,0
BEGIN DESCRIPTION:
Dawson T3 1.0
END DESCRIPTION:
XS GIS Cut Line= 3
      2747010.27      6897887.77      2746589.23      6898128.67
      2746552.34      6898423.79
#Sta/Elev= 30
  4517.6  460.51    4537  460.59    4596  456.71  4633.4  456.02  4639.2  456.57
  4662.1  456.47  4735.6  455.51  4751.4  454.53  4778.8   454.3  4794.6  453.29
    4832  452.37  4837.8  452.68  4853.6  451.58  4902.7  452.49  4914.8  452.06
  4918.4  451.82  4925.8  452.54  4948.8  452.32  4955.8  450.89  4959.6  450.82
  4959.8  450.32  4963.3  450.32  4963.6  450.82  4971.6  451.79  5015.1  451.68
  5035.3  450.92  5055.4  453.36  5145.4  456.06  5150.4  456.76  5300.1  460.17
#Mann= 5 ,-1 , 0
  4517.6     .12       0  4662.1     .05       0  4914.8     .12       0
  4948.8     .04       0  4971.6     .05       0
Bank Sta=4948.8,4971.6
XS Rating Curve= 0 ,0
Exp/Cntr=0.3,0.1

Chan Stop Cuts=-1
Use User Specified Reach Order=0
Composite Channel Slope=5