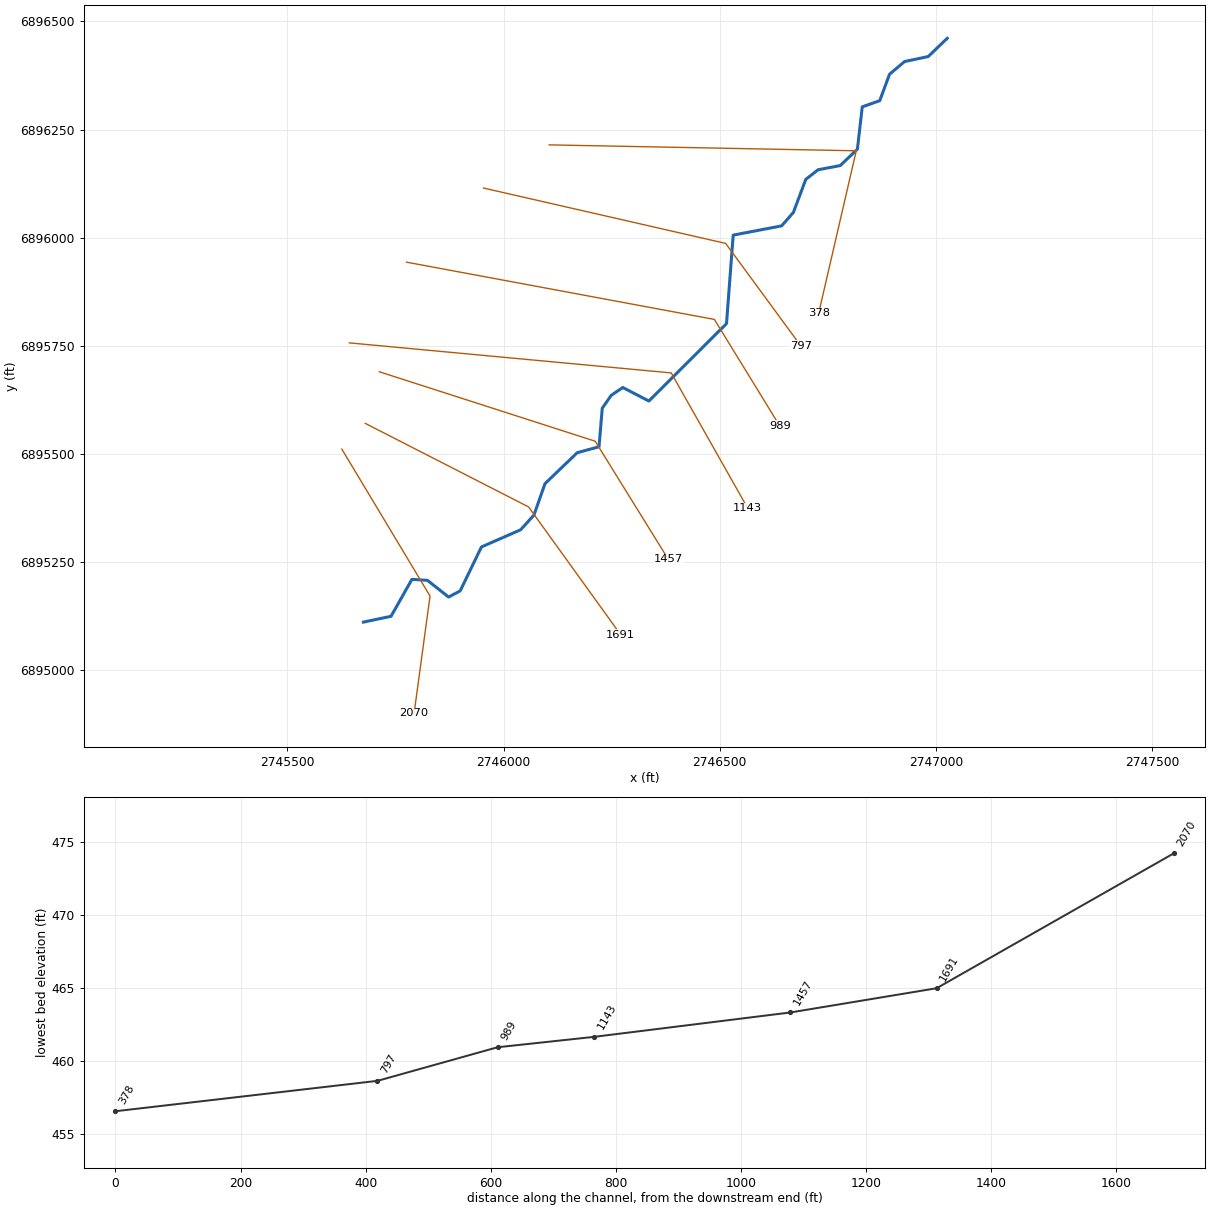
--- Dawson T4.prj (project) ---

Proj Title=Dawson T4 Base Level Engineering
Current Plan=p01
Default Exp/Contr=0.3,0.1
English Units
Geom File=g01
Flow File=f01
Plan File=p01
Y Axis Title=Elevation
X Axis Title(PF)=Main Channel Distance
X Axis Title(XS)=Station
BEGIN DESCRIPTION:
Dawson T4
END DESCRIPTION:
DSS File=dss
DSS Export Rating Curves= 0
DSS Export Rating Curve Sorted= 0
DSS Export Volume Flow Curves= 0
DXF OffsetX= 0
DXF OffsetY= 0
DXF ScaleX= 1
DXF ScaleY= 10

--- Dawson T4.p01 (plan) ---

Plan Title=Multiple Run
Program Version=4.10
Short Identifier=Multiple Run
Geom File=g01
Flow File=f01
Subcritical Flow
K Sum by GR= 0
Std Step Tol= 0.01
Critical Tol= 0.01
Num of Std Step Trials= 20
Max Error Tol= 0.3
Flow Tol Ratio= 0.001
Split Flow NTrial= 30
Split Flow Tol= 0.02
Split Flow Ratio= 0.02
Log Output Level= 0
Friction Slope Method= 1
Unsteady Friction Slope Method= 2
Unsteady Bridges Friction Slope Method= 1
Parabolic Critical Depth
Global Vel Dist= 1 , 1 , 1
Global Log Level= 0
CheckData=True
Encroach Param=-1 ,0,0, 0
BEGIN DESCRIPTION:
Multiple Run
END DESCRIPTION:
Computation Interval=1HOUR
Output Interval=1HOUR
Run HTab= 0
Run UNet= 0
Run PostProcess= 0
Run WQNet= 0
UNET Theta= 1
UNET Theta Warmup= 1
UNET ZTol= 0.02
UNET ZSATol= 0.05
UNET MxIter= 20
UNET MaxInSteps= 0
UNET DtIC= 0
UNET DtMin= 0
UNET MaxCRTS= 20
UNET WFStab= 2
UNET SFStab= 1
UNET WFX= 1
UNET SFX= 1
UNET DSS MLevel= 4
UNET DZMax Abort= 100
UNET Convert EG Bridges= 0
UNET Use Existing IB Tables=-1
UNET Froude Reduction=False
UNET Froude Limit= 1
UNET Froude Power= 10
UNET Time Slicing=0,0, 5
UNET Junction Losses=0
Instantaneous Interval=1HOUR
DSS File=dss
Write IC File= 0
Write IC File at Sim End=0
Echo Input=False
Echo Parameters=False
Echo Output=False
Write Detailed= 0
WQ AD Non Conservative
WQ ULTIMATE=-1
WQ Max Comp Step=1HOUR
WQ Output Interval=15MIN
WQ Output Selected Increments= 0
WQ Output face flow=0
WQ Output face velocity=0
WQ Output face area=0
WQ Output face dispersion=0
WQ Output cell volume=0
WQ Output cell surface area=0
WQ Output cell continuity=0
WQ Output cumulative cell continuity=0
WQ Output face conc=0
WQ Output face dconc_dx=0
WQ Output face courant=0
WQ Output face peclet=0
WQ Output face adv mass=0
WQ Output face disp mass=0
WQ Output cell mass=0
WQ Output cell source sink temp=0
WQ Output cell source sink nsm=0
WQ Output MaxMinRange=-1
WQ Daily Max Min Mean=-1
WQ Daily Range=0
WQ Daily Time=0
WQ Create Restart=0
WQ Fixed Restart=0
WQ System Summary=0
WQ Use Fixed Temperature=0
Sorting and Armoring Iterations= 10
XS Update Threshold= 0.02
Hydraulics Update Threshold= 0.02
Energy Slope Method= 1
Volume Change Method= 0
XS Weighting Method= 0
Number of US Weighted Cross Sections= 1
Number of DS Weighted Cross Sections= 1
Upstream XS Weight=0.25
Main XS Weight=0.5
Downstream XS Weight=0.25
Number of DS XS's Weighted with US Boundary= 1
Upstream Boundary Weight= 1
Weight of XSs Associated with US Boundary= 0
Number of US XS's Weighted with DS Boundary= 1
Downstream Boundary Weight= 0.5
Weight of XSs Associated with DS Boundary= 0.5
Sediment Output Level= 4
Mass or Volume Output= 0
Output Increment Type= 1
Profile and TS Output Increment= 10
XS Output Flag= 0
XS Output Increment= 10
Disregard all LS=0
Disregard all Conn=0
Disregard all Breaches=0
Disregard all Pumps=0

--- Dawson T4.f01 (steady flow) ---

Flow Title=Multiple
Program Version=4.10
Number of Profiles= 7
Profile Names=10-year,25-year,50-year,1pct_min,100-year,1pct_plu,500-year
River Rch & RM=Dawson T4,Reach-1         ,2070
     151     185     211     121     241     480     311
Boundary for River Rch & Prof#=Dawson T4,Reach-1         , 1
Up Type= 0
Dn Type= 3
Dn Slope=0.00715
Boundary for River Rch & Prof#=Dawson T4,Reach-1         , 2
Up Type= 0
Dn Type= 3
Dn Slope=0.00715
Boundary for River Rch & Prof#=Dawson T4,Reach-1         , 3
Up Type= 0
Dn Type= 3
Dn Slope=0.00715
Boundary for River Rch & Prof#=Dawson T4,Reach-1         , 4
Up Type= 0
Dn Type= 3
Dn Slope=0.00715
Boundary for River Rch & Prof#=Dawson T4,Reach-1         , 5
Up Type= 0
Dn Type= 3
Dn Slope=0.00715
Boundary for River Rch & Prof#=Dawson T4,Reach-1         , 6
Up Type= 0
Dn Type= 3
Dn Slope=0.00715
Boundary for River Rch & Prof#=Dawson T4,Reach-1         , 7
Up Type= 0
Dn Type= 3
Dn Slope=0.00715
DSS Import GetInterval= 0
DSS Import GetPeak= 0
DSS Import FillOption= 0

--- Dawson T4.g01 (geometry) ---

Geom Title=Existing Conditions
Program Version=4.10

River Reach=Dawson T4       ,Reach-1
Reach XY= 30
        2745676.        6895111.      2745739.74      6895124.38
      2745788.02      6895209.79        2745824.      6895207.56
      2745872.92      6895168.85      2745899.72      6895183.31
      2745948.87      6895284.82      2746039.55      6895324.49
      2746070.25      6895358.47      2746095.78      6895431.12
      2746170.28       6895502.7      2746220.74      6895516.48
      2746228.19      6895605.41      2746248.88       6895635.4
      2746275.76      6895653.54      2746335.99      6895622.25
      2746515.52       6895801.2      2746531.04      6896005.92
       2746643.1      6896027.32      2746670.25      6896058.45
      2746698.87      6896134.83      2746727.47       6896157.1
      2746778.55      6896166.75      2746818.24      6896204.59
       2746829.5      6896302.52      2746869.94      6896316.83
      2746892.53      6896377.87      2746927.35      6896407.26
      2746982.11      6896418.95        2747026.        6896461.

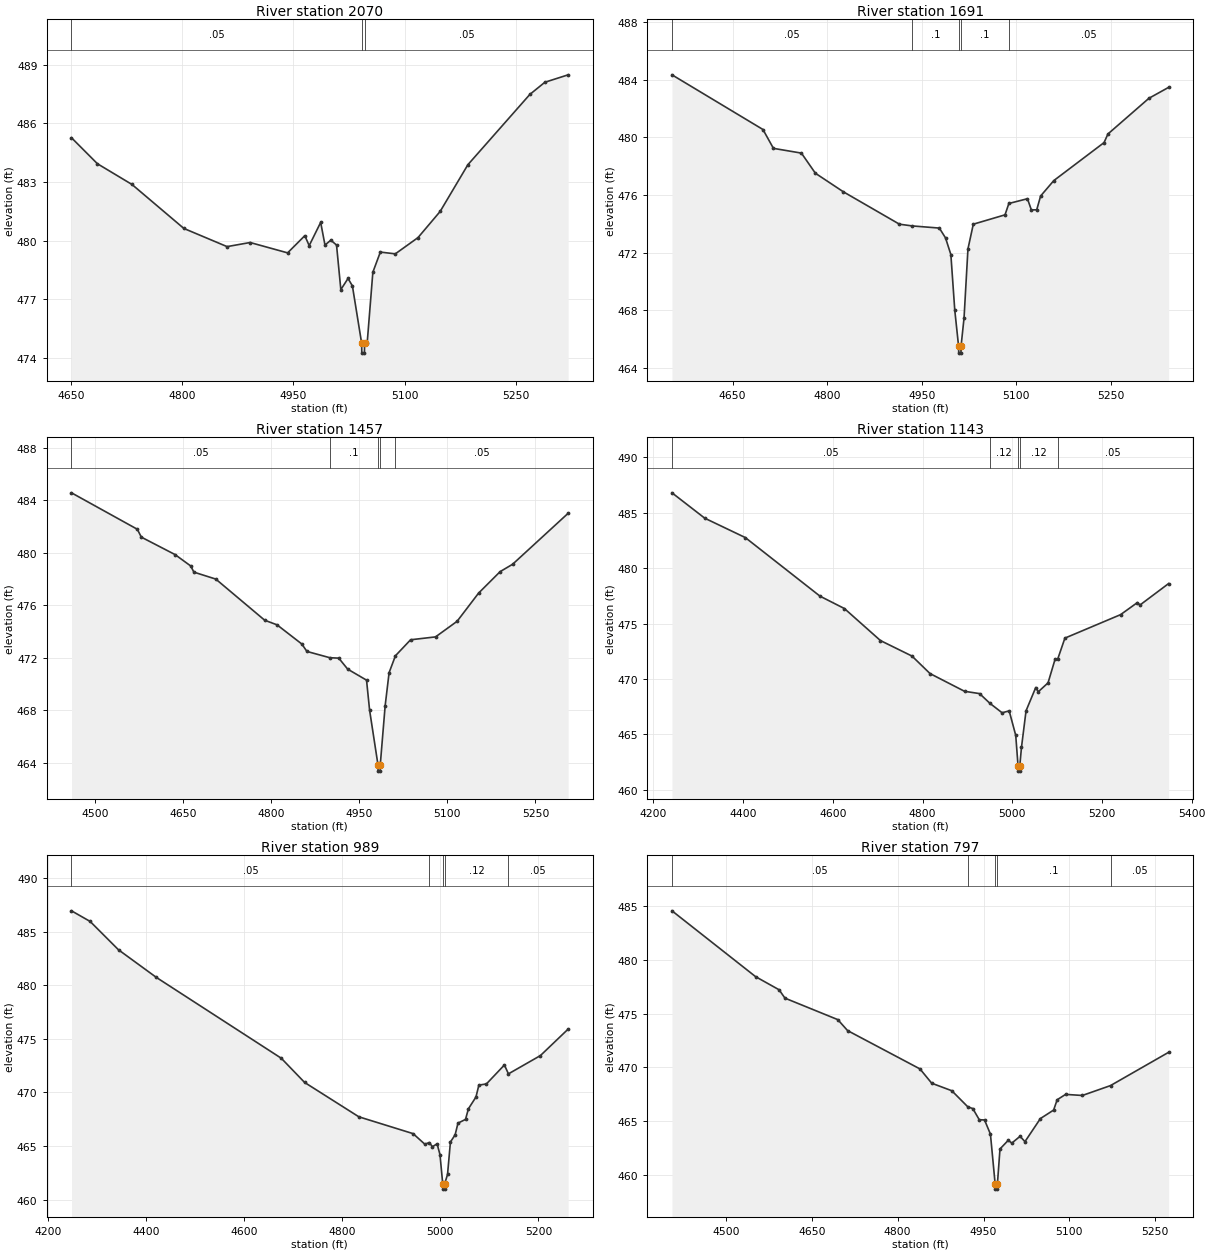
Type RM Length L Ch R = 1 ,2070    ,379,379,379
BEGIN DESCRIPTION:
Dawson T4 3.0
END DESCRIPTION:
XS GIS Cut Line= 3
      2745626.01      6895510.99      2745829.95      6895171.21
      2745793.05       6894899.9
#Sta/Elev= 30
  4650.5  485.26  4685.5  483.93  4732.1  482.87  4802.1  480.62  4860.4  479.69
  4891.5   479.9  4942.1  479.37  4965.3  480.25  4971.2  479.74  4986.7  480.93
  4992.5  479.77  5000.4  480.02  5008.1  479.77  5013.9  477.49  5023.6  478.06
  5029.5  477.68    5042  474.74  5042.2  474.24  5045.7  474.24    5046  474.74
  5049.4  474.74  5057.1  478.38  5067.2  479.41  5087.4  479.32    5118  480.15
  5147.9  481.49  5185.3  483.88    5269  487.48  5289.2   488.1  5320.6  488.48
#Mann= 3 ,-1 , 0
  4650.5     .05       0    5042     .04       0    5046     .05       0
Bank Sta=5042,5046
XS Rating Curve= 0 ,0
Exp/Cntr=0.3,0.1

Type RM Length L Ch R = 1 ,1691    ,234,234,234
BEGIN DESCRIPTION:
Mapping XS 6a4cfa76
END DESCRIPTION:
XS GIS Cut Line= 3
      2745680.21      6895570.52      2746057.82      6895377.37
      2746270.48      6895082.25
#Sta/Elev= 30
  4553.8  484.35  4698.1  480.55  4714.7  479.24  4759.1  478.91  4781.3  477.51
  4825.7  476.22  4914.6  473.97  4934.9  473.85  4977.9   473.7  4987.7  473.02
  4996.2  471.86  5002.4  467.99  5008.4  465.51  5008.7  465.01  5012.2  465.01
  5012.4  465.51  5017.1  467.45  5023.3  472.25  5031.8  473.97  5082.1  474.62
  5088.2  475.41  5117.7  475.74  5123.9  474.96  5132.4  474.97  5138.6  475.93
  5159.5     477  5239.2  479.64  5245.4  480.24  5310.4  482.72  5341.7  483.48
#Mann= 5 ,-1 , 0
  4553.8     .05       0  4934.9      .1       0  5008.4     .07       0
  5012.4      .1       0  5088.2     .05       0
Bank Sta=5008.4,5012.4
XS Rating Curve= 0 ,0
Exp/Cntr=0.3,0.1

Type RM Length L Ch R = 1 ,1457    ,314,314,314
BEGIN DESCRIPTION:
Mapping XS fa94e830
END DESCRIPTION:
XS GIS Cut Line= 3
      2745712.78      6895689.87       2746211.9      6895529.28
      2746381.06      6895256.02
#Sta/Elev= 30
  4460.1  484.58  4572.2   481.8    4579   481.2  4636.4  479.87  4663.1     479
  4668.5  478.53  4705.8     478  4789.1  474.86  4810.1  474.51  4852.2  473.05
    4861  472.48  4900.1     472  4915.2  471.97  4930.4  471.13  4962.5  470.29
  4967.7     468  4981.9  463.85  4982.2  463.35  4985.7  463.35  4985.9  463.85
  4994.2  468.34  5000.9  470.86  5011.7  472.15  5037.5  473.37    5080  473.59
  5116.7  474.78  5153.3  476.93    5190  478.57  5211.2  479.13  5305.8  483.02
#Mann= 5 ,-1 , 0
  4460.1     .05       0  4900.1      .1       0  4981.9     .07       0
  4985.9      .1       0  5011.7     .05       0
Bank Sta=4981.9,4985.9
XS Rating Curve= 0 ,0
Exp/Cntr=0.3,0.1

Type RM Length L Ch R = 1 ,1143    ,154,154,154
BEGIN DESCRIPTION:
Mapping XS 0d1421ca
END DESCRIPTION:
XS GIS Cut Line= 3
      2745643.27      6895756.72      2746387.68      6895687.27
      2746564.68      6895374.29
#Sta/Elev= 30
  4241.5  486.81  4314.5  484.52  4404.9  482.77  4571.4  477.48  4625.9  476.36
  4706.2  473.47  4776.5  472.07  4816.7  470.49  4893.6  468.89  4927.2  468.68
  4950.3   467.8  4977.4  466.95  4993.2  467.12  5007.8  464.91  5012.9  462.18
  5013.1  461.68  5016.6  461.68  5016.9  462.18  5020.6  463.83  5030.8  467.13
  5052.4  469.23  5058.2  468.85  5079.8  469.65  5095.7  471.81  5101.4   471.8
  5117.4  473.69  5241.5  475.81    5279   476.9  5284.8  476.68  5348.7  478.62
#Mann= 5 ,-1 , 0
  4241.5     .05       0  4950.3     .12       0  5012.9     .07       0
  5016.9     .12       0  5101.4     .05       0
Bank Sta=5012.9,5016.9
XS Rating Curve= 0 ,0
Exp/Cntr=0.3,0.1

Type RM Length L Ch R = 1 ,989     ,192,192,192
BEGIN DESCRIPTION:
Mapping XS 2b7b31fe
END DESCRIPTION:
XS GIS Cut Line= 3
      2745775.75      6895943.34      2746487.51      6895810.97
      2746638.69      6895564.74
#Sta/Elev= 30
  4247.6  486.95  4285.6  485.96  4343.5  483.31  4420.8  480.73  4675.4  473.19
    4723  470.93  4833.7  467.72  4944.3  466.15  4968.3  465.16  4977.2  465.32
  4983.7  464.93  4993.2   465.2  4999.1  464.19  5004.7  461.47    5005  460.97
  5008.5  460.97  5008.7  461.47  5014.5  462.34  5020.4  465.37    5030  466.04
  5035.8  467.13  5051.2  467.48  5057.1  468.47  5072.5  469.57  5078.4  470.68
  5093.8  470.79  5130.5  472.56  5138.7  471.73    5204  473.44  5260.5  475.91
#Mann= 5 ,-1 , 0
  4247.6     .05       0  4977.2     .12       0  5004.7     .07       0
  5008.7     .12       0  5138.7     .05       0
Bank Sta=5004.7,5008.7
XS Rating Curve= 0 ,0
Exp/Cntr=0.3,0.1

Type RM Length L Ch R = 1 ,797     ,419,419,419
BEGIN DESCRIPTION:
Mapping XS 3f5b024e
END DESCRIPTION:
XS GIS Cut Line= 3
      2745953.61      6896114.79      2746513.55      6895986.75
      2746687.15      6895750.21
#Sta/Elev= 30
  4405.7  484.58  4551.8  478.45  4592.8  477.23  4603.1  476.45  4695.4  474.45
  4712.5  473.43    4839  469.86  4859.5  468.53  4894.6  467.83  4922.6  466.33
  4931.3  466.17  4942.6  465.13  4951.8  465.11  4962.1  463.79  4970.3  459.17
  4970.6  458.67  4974.1  458.67  4974.3  459.17  4978.8  462.41  4993.1  463.21
  4999.6  462.96  5013.9  463.59  5022.4  463.09  5049.4  465.24  5072.5  466.03
  5078.7  466.99  5093.4  467.49  5122.7  467.39  5171.9  468.31  5273.5  471.41
#Mann= 5 ,-1 , 0
  4405.7     .05       0  4922.6      .1       0  4970.3     .05       0
  4974.3      .1       0  5171.9     .05       0
Bank Sta=4970.3,4974.3
XS Rating Curve= 0 ,0
Exp/Cntr=0.3,0.1

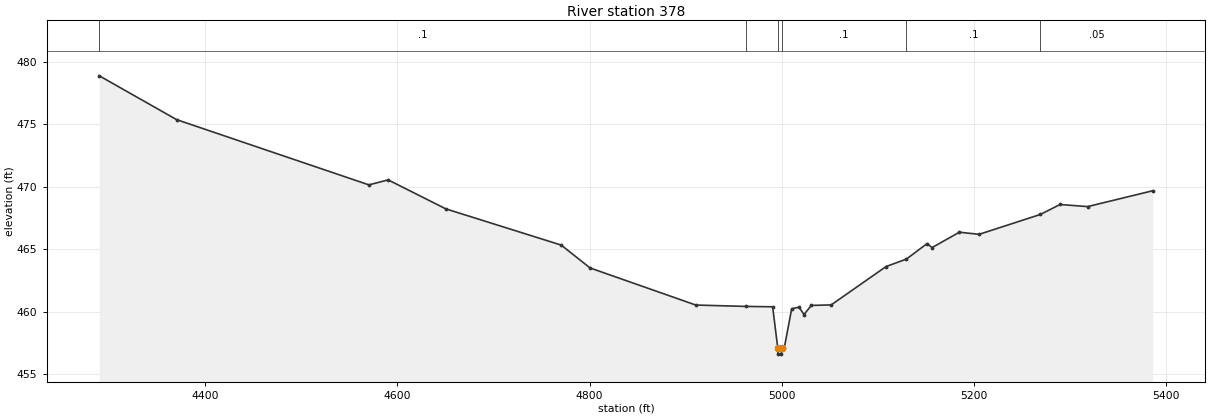
Type RM Length L Ch R = 1 ,378     ,0,0,0
BEGIN DESCRIPTION:
Dawson T4 1.0
END DESCRIPTION:
XS GIS Cut Line= 3
      2746105.53      6896214.61       2746815.6      6896200.93
      2746728.62      6895824.97
#Sta/Elev= 30
  4289.8  478.87  4370.3  475.36  4570.3  470.14  4590.3  470.54  4650.3  468.22
  4770.4  465.32  4800.4  463.49  4910.4  460.52  4962.3  460.41  4990.4  460.38
  4995.7  457.09    4996  456.59  4999.5  456.59  4999.7  457.09  5002.5  457.09
  5010.2  460.22  5017.9  460.35    5023  459.76  5030.7  460.49  5051.3  460.53
  5108.4   463.6  5129.6   464.2  5151.1  465.44  5156.3  465.12  5184.7  466.35
  5205.2  466.18  5268.9  467.77  5289.5  468.57  5318.1   468.4  5385.9  469.67
#Mann= 6 ,-1 , 0
  4289.8      .1       0  4962.3      .1       0  4995.7     .05       0
  4999.7      .1       0  5129.6      .1       0  5268.9     .05       0
Bank Sta=4995.7,4999.7
XS Rating Curve= 0 ,0
Exp/Cntr=0.3,0.1

Chan Stop Cuts=-1
Use User Specified Reach Order=0
Composite Channel Slope=5