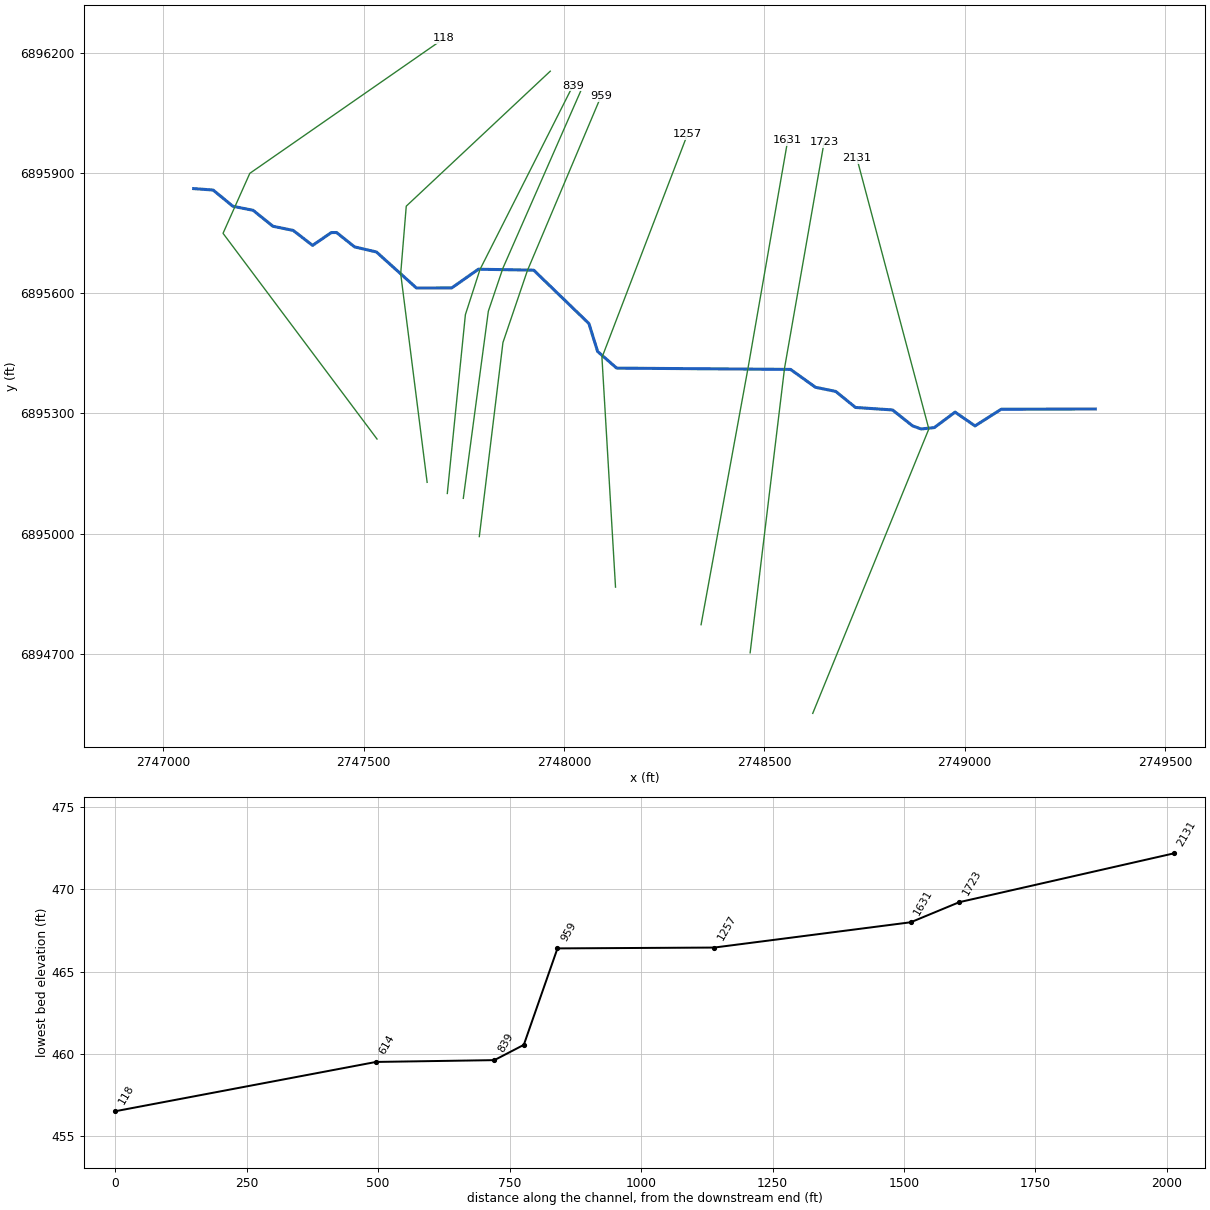
--- Dawson T5.prj (project) ---

Proj Title=Dawson T5 Base Level Engineering
Current Plan=p01
Default Exp/Contr=0.3,0.1
English Units
Geom File=g01
Flow File=f01
Plan File=p01
BEGIN DESCRIPTION:
Dawson T5
END DESCRIPTION:

--- Dawson T5.p01 (plan) ---

Plan Title=Multiple Run
Short Identifier=Multiple
Geom File=g01
Flow File=f01
Subcritical Flow
K Sum by GR= 0
Std Step Tol= 0.01
Critical Tol= 0.01
Num of Std Step Trials= 20
Max Error Tol= 0.3
Flow Tol Ratio= 0.001
Split Flow NTrial= 30
Split Flow Tol= 0.02
Split Flow Ratio= 0.02
Log Output Level= 0
Friction Slope Method= 1
Unsteady Friction Slope Method= 2
Unsteady Bridges Friction Slope Method= 1
Parabolic Critical Depth
Global Vel Dist=  1 , 1 , 1
Global Log Level= 0
CheckData=True
Encroach Param= -1, 0, 0, 0
BEGIN DESCRIPTION:
Multiple Run
END DESCRIPTION:

--- Dawson T5.f01 (steady flow) ---

Flow Title=Multiple
Number of Profiles=7
Profile Names=10-year,25-year,50-year,1pct_min,100-year,1pct_plu,500-year
River Rch & RM= Dawson T5,Reach-1,2131
     385     500     592     348     694    1385     957
Boundary for River Rch & Prof#=Dawson T5,Reach-1,1
Up Type=0
Dn Type=3
Dn Slope=0.005
Boundary for River Rch & Prof#=Dawson T5,Reach-1,2
Up Type=0
Dn Type=3
Dn Slope=0.005
Boundary for River Rch & Prof#=Dawson T5,Reach-1,3
Up Type=0
Dn Type=3
Dn Slope=0.005
Boundary for River Rch & Prof#=Dawson T5,Reach-1,4
Up Type=0
Dn Type=3
Dn Slope=0.005
Boundary for River Rch & Prof#=Dawson T5,Reach-1,5
Up Type=0
Dn Type=3
Dn Slope=0.005
Boundary for River Rch & Prof#=Dawson T5,Reach-1,6
Up Type=0
Dn Type=3
Dn Slope=0.005
Boundary for River Rch & Prof#=Dawson T5,Reach-1,7
Up Type=0
Dn Type=3
Dn Slope=0.005

--- Dawson T5.g01 (geometry) ---

Geom Title=Existing Conditions

River Reach=Dawson T5,Reach-1
Reach XY= 30
      2749326.00      6895311.00      2749091.16      6895310.35
      2749025.90      6895268.79      2748976.08      6895303.17
      2748924.37      6895264.59      2748891.42      6895261.15
      2748870.09      6895268.83      2748820.03      6895308.62
      2748727.58      6895314.83      2748678.18      6895354.89
      2748627.74      6895365.19      2748565.50      6895409.80
      2748131.67      6895412.98      2748084.02      6895454.62
      2748062.36      6895524.20      2747924.53      6895657.47
      2747786.51      6895659.79      2747720.02      6895613.16
      2747631.89      6895612.97      2747532.04      6895702.86
      2747477.65      6895715.44      2747432.55      6895751.42
      2747419.28      6895751.25      2747372.77      6895719.24
      2747324.37      6895756.59      2747273.81      6895767.05
      2747224.28      6895806.86      2747173.75      6895816.95
      2747124.51      6895857.40      2747076.00      6895861.00

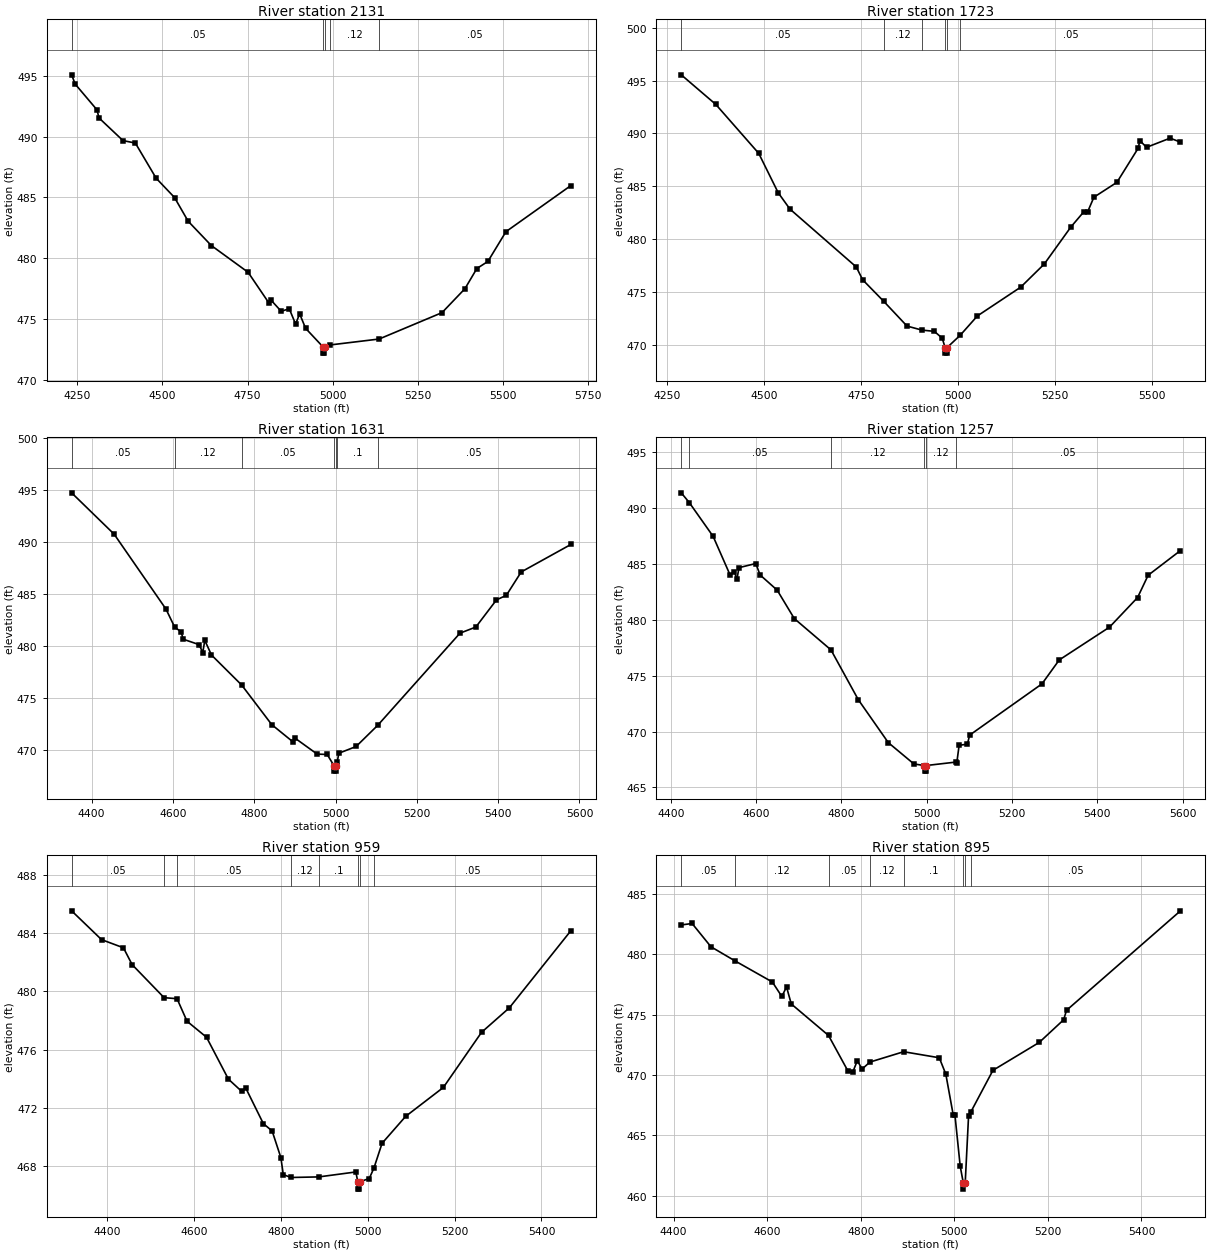
Type RM Length L Ch R = 1,2131,408,408,408
BEGIN DESCRIPTION:
Dawson T5 5.0
END DESCRIPTION:
XS GIS Cut Line= 3
      2748620.90      6894551.39      2748910.66      6895261.22
      2748731.10      6895936.35
#Sta/Elev= 30
  4233.3  495.08  4243.7  494.32  4308.0  492.19  4313.4  491.54  4384.1  489.67
  4420.3  489.47  4481.3  486.58  4535.3  484.99  4575.3  483.04  4643.3  481.04
  4751.3  478.84  4813.2  476.28  4818.6  476.55  4848.5  475.63  4872.1  475.84
  4890.7  474.58  4902.6  475.42  4920.1  474.23  4971.6  472.69  4971.8  472.19
  4975.3  472.19  4975.6  472.69  4991.1  472.86  5135.9  473.35  5320.5  475.52
  5387.8  477.49  5422.8  479.15  5455.1  479.73  5508.2  482.18  5698.6  485.97
#Mann=5,-1,0
  4233.3    0.05       0  4971.6    0.07       0  4975.6    0.05       0
  4991.1    0.12       0  5135.9    0.05       0
Bank Sta=4971.6,4975.6
Exp/Cntr=0.3,0.1

Type RM Length L Ch R = 1,1723,92,92,92
BEGIN DESCRIPTION:
Mapping XS 8790f441
END DESCRIPTION:
XS GIS Cut Line= 3
      2748464.66      6894702.49      2748550.60      6895413.39
      2748649.34      6895977.24
#Sta/Elev= 30
  4286.1  495.55  4375.3  492.75  4486.1  488.12  4536.4  484.39  4566.6  482.85
  4737.9  477.37  4754.3  476.16  4809.0  474.11  4868.8  471.78  4907.2  471.40
  4939.3  471.28  4959.5  470.64  4967.5  469.72  4967.8  469.22  4971.3  469.22
  4971.5  469.72  5006.1  470.91  5050.5  472.74  5162.2  475.46  5223.1  477.65
  5291.7  481.15  5324.6  482.57  5334.8  482.57  5351.2  483.97  5410.6  485.38
  5465.0  488.58  5470.1  489.32  5487.0  488.69  5548.0  489.56  5574.6  489.18
#Mann=6,-1,0
  4286.1    0.05       0  4809.0    0.12       0  4907.2     0.1       0
  4967.5    0.07       0  4971.5     0.1       0  5006.1    0.05       0
Bank Sta=4967.5,4971.5
Exp/Cntr=0.3,0.1

Type RM Length L Ch R = 1,1631,374,374,374
BEGIN DESCRIPTION:
Mapping XS 58984528
END DESCRIPTION:
XS GIS Cut Line= 3
      2748342.26      6894772.73      2748459.45      6895413.39
      2748558.42      6895981.14
#Sta/Elev= 30
  4351.1  494.77  4455.7  490.79  4583.2  483.58  4604.4  481.86  4620.4  481.39
  4625.4  480.69  4664.5  480.17  4673.6  479.41  4678.6  480.58  4695.0  479.17
  4769.3  476.28  4843.3  472.47  4896.5  470.78  4901.6  471.14  4954.8  469.64
  4979.6  469.60  4996.6  468.50  4996.9  468.00  5000.4  468.00  5000.6  468.50
  5004.2  468.88  5008.2  469.72  5050.7  470.37  5103.9  472.41  5306.1  481.27
  5345.1  481.86  5395.8  484.47  5420.1  484.91  5456.7  487.16  5578.7  489.80
#Mann=7,-1,0
  4351.1    0.05       0  4604.4    0.12       0  4769.3    0.05       0
  4996.6    0.05       0  5000.6    0.05       0  5004.2     0.1       0
  5103.9    0.05       0
Bank Sta=4996.6,5000.6
Exp/Cntr=0.3,0.1

Type RM Length L Ch R = 1,1257,298,298,298
BEGIN DESCRIPTION:
Mapping XS 79cab304
END DESCRIPTION:
XS GIS Cut Line= 3
      2748128.72      6894866.47      2748094.87      6895439.43
      2748308.28      6895996.39
#Sta/Elev= 30
  4424.7  491.34  4443.5  490.47  4499.4  487.45  4539.4  483.98  4549.4  484.28
  4555.1  483.60  4560.1  484.65  4599.5  485.02  4609.5  484.00  4649.6  482.64
  4689.7  480.10  4775.7  477.30  4839.9  472.84  4910.1  469.01  4970.2  467.10
  4994.9  466.96  4995.2  466.46  4998.7  466.46  4998.9  466.96  5068.8  467.27
  5070.8  467.23  5076.2  468.77  5095.5  468.87  5100.9  469.68  5270.4  474.26
  5310.9  476.40  5428.7  479.33  5494.6  481.98  5519.3  483.97  5595.1  486.18
#Mann=6,-1,0
  4424.7    0.12       0  4443.5    0.05       0  4775.7    0.12       0
  4994.9    0.07       0  4998.9    0.12       0  5068.8    0.05       0
Bank Sta=4994.9,4998.9
Exp/Cntr=0.3,0.1

Type RM Length L Ch R = 1,959,64,64,64
BEGIN DESCRIPTION:
Mapping XS f958c5f8
END DESCRIPTION:
XS GIS Cut Line= 4
      2747788.80      6894992.60      2747847.82      6895476.93
      2747908.58      6895655.75      2748092.61      6896091.51
#Sta/Elev= 30
  4317.9  485.54  4386.8  483.56  4437.2  483.00  4457.3  481.84  4530.9  479.57
  4560.7  479.50  4583.7  477.95  4628.6  476.85  4679.0  473.97  4709.2  473.14
  4719.3  473.34  4759.5  470.91  4779.7  470.41  4799.8  468.58  4805.4  467.41
  4823.0  467.21  4887.1  467.25  4972.5  467.59  4977.1  466.91  4977.4  466.41
  4980.9  466.41  4981.1  466.91  5003.4  467.14  5014.2  467.86  5032.9  469.56
  5087.2  471.41  5174.1  473.40  5262.1  477.19  5326.0  478.87  5467.7  484.17
#Mann=8,-1,0
  4317.9    0.05       0  4530.9    0.12       0  4560.7    0.05       0
  4823.0    0.12       0  4887.1     0.1       0  4977.1    0.07       0
  4981.1     0.1       0  5014.2    0.05       0
Bank Sta=4977.1,4981.1
Exp/Cntr=0.3,0.1

Type RM Length L Ch R = 1,895,56,56,56
BEGIN DESCRIPTION:
Mapping XS eb6d6c12
END DESCRIPTION:
XS GIS Cut Line= 4
      2747748.86      6895088.02      2747811.36      6895555.06
      2747847.82      6895662.70      2748041.63      6896103.96
#Sta/Elev= 30
  4416.5  482.44  4439.7  482.56  4480.0  480.63  4532.3  479.44  4611.2  477.71
  4631.4  476.51  4641.5  477.30  4651.6  475.89  4731.2  473.28  4772.6  470.34
  4782.7  470.21  4792.8  471.19  4802.9  470.49  4819.5  471.07  4891.8  471.93
  4967.9  471.43  4981.9  470.07  4997.8  466.67  5001.4  466.67  5012.6  462.45
  5019.3  461.04  5019.6  460.54  5023.3  461.04  5030.5  466.61  5035.8  466.97
  5082.6  470.39  5181.5  472.70  5233.7  474.58  5239.8  475.36  5483.3  483.61
#Mann=8,-1,0
  4416.5    0.05       0  4532.3    0.12       0  4731.2    0.05       0
  4819.5    0.12       0  4891.8     0.1       0  5019.3    0.07       0
  5023.3     0.1       0  5035.8    0.05       0
Bank Sta=5019.3,5023.3
Exp/Cntr=0.3,0.1

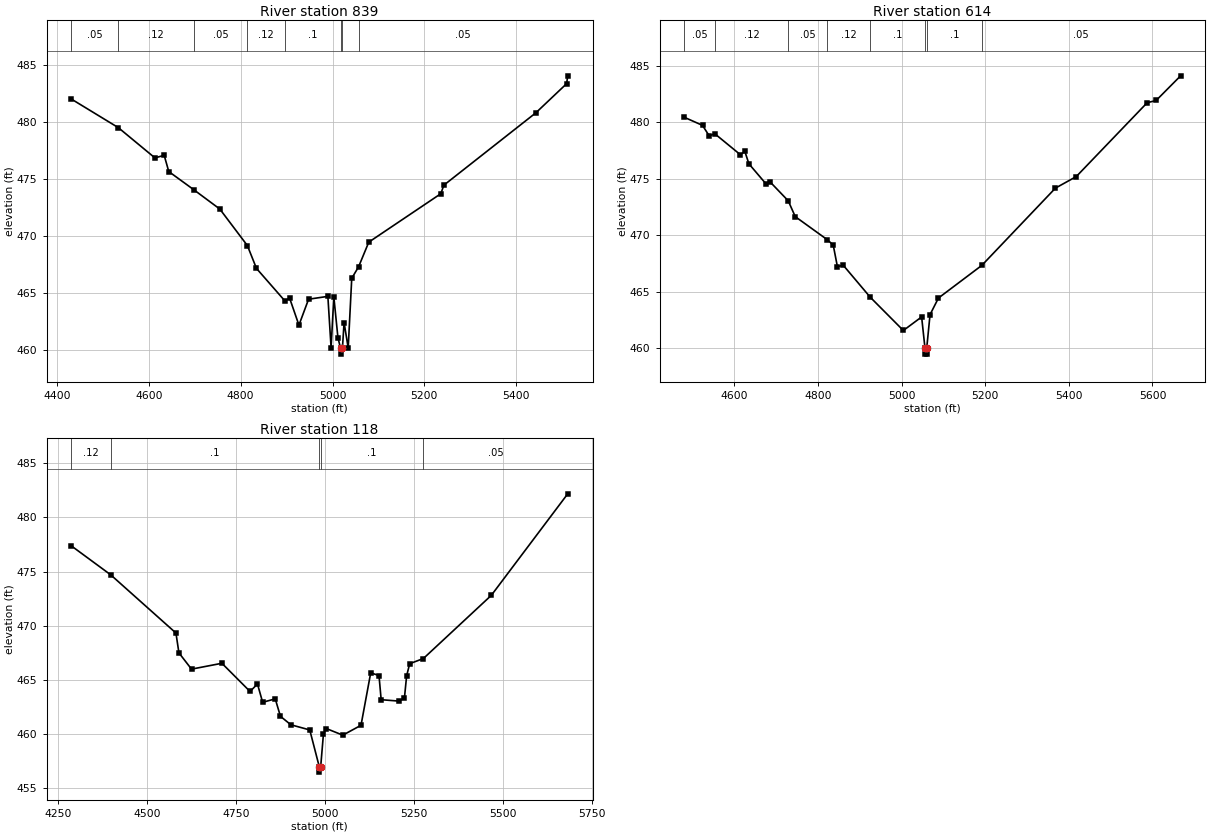
Type RM Length L Ch R = 1,839,225,225,225
BEGIN DESCRIPTION:
Mapping XS 94db770e
END DESCRIPTION:
XS GIS Cut Line= 4
      2747708.93      6895100.16      2747754.07      6895546.38
      2747790.53      6895659.23      2748022.34      6896117.66
#Sta/Elev= 30
  4431.5  482.04  4533.6  479.53  4613.3  476.87  4633.4  477.10  4643.4  475.67
  4697.6  474.08  4754.6  472.37  4814.6  469.16  4834.4  467.15  4895.9  464.31
  4906.8  464.51  4926.9  462.16  4947.9  464.44  4989.9  464.69  4996.9  460.18
  5002.9  464.64  5011.8  461.07  5017.6  460.11  5017.8  459.61  5021.6  460.11
  5025.2  462.39  5034.2  460.15  5041.9  466.28  5056.8  467.29  5079.0  469.46
  5235.9  473.72  5242.5  474.47  5443.0  480.84  5509.9  483.40  5512.3  484.09
#Mann=8,-1,0
  4431.5    0.05       0  4533.6    0.12       0  4697.6    0.05       0
  4814.6    0.12       0  4895.9     0.1       0  5017.6    0.07       0
  5021.6     0.1       0  5056.8    0.05       0
Bank Sta=5017.6,5021.6
Exp/Cntr=0.3,0.1

Type RM Length L Ch R = 1,614,496,496,496
BEGIN DESCRIPTION:
Mapping XS 7b15d4e6
END DESCRIPTION:
XS GIS Cut Line= 4
      2747658.59      6895127.96      2747592.61      6895648.81
      2747606.50      6895817.21      2747965.86      6896154.00
#Sta/Elev= 30
  4480.7  480.44  4524.1  479.73  4540.1  478.80  4553.4  478.99  4614.8  477.13
  4625.3  477.43  4635.0  476.33  4675.3  474.58  4685.4  474.74  4729.0  473.06
  4745.8  471.66  4822.0  469.63  4836.6  469.15  4846.6  467.24  4860.6  467.36
  4925.2  464.53  5004.3  461.59  5048.0  462.79  5056.1  460.00  5056.3  459.50
  5059.8  459.50  5060.1  460.00  5068.1  462.99  5088.2  464.46  5192.0  467.35
  5367.9  474.18  5417.7  475.20  5587.2  481.73  5608.7  481.93  5667.2  484.11
#Mann=8,-1,0
  4480.7    0.05       0  4553.4    0.12       0  4729.0    0.05       0
  4822.0    0.12       0  4925.2     0.1       0  5056.1    0.07       0
  5060.1     0.1       0  5192.0    0.05       0
Bank Sta=5056.1,5060.1
Exp/Cntr=0.3,0.1

Type RM Length L Ch R = 1,118,0,0,0
BEGIN DESCRIPTION:
Dawson T5 1.0
END DESCRIPTION:
XS GIS Cut Line= 4
      2747533.56      6895236.04      2747149.26      6895749.39
      2747216.05      6895899.07      2747701.02      6896236.01
#Sta/Elev= 30
  4287.1  477.36  4397.4  474.70  4580.9  469.33  4589.3  467.50  4624.7  466.00
  4710.2  466.54  4789.3  463.94  4810.2  464.63  4824.8  462.94  4860.2  463.26
  4874.8  461.65  4904.0  460.87  4957.3  460.39  4984.0  457.00  4984.3  456.50
  4988.0  457.00  4995.8  460.04  5003.8  460.52  5050.2  459.91  5101.4  460.82
  5128.7  465.66  5152.0  465.41  5158.1  463.18  5208.7  463.05  5223.6  463.36
  5229.7  465.38  5238.3  466.50  5276.9  466.98  5468.0  472.81  5682.8  482.17
#Mann=5,-1,0
  4287.1    0.12       0  4397.4     0.1       0  4984.0    0.07       0
  4988.0     0.1       0  5276.9    0.05       0
Bank Sta=4984,4988
Exp/Cntr=0.3,0.1

Chan Stop Cuts=-1