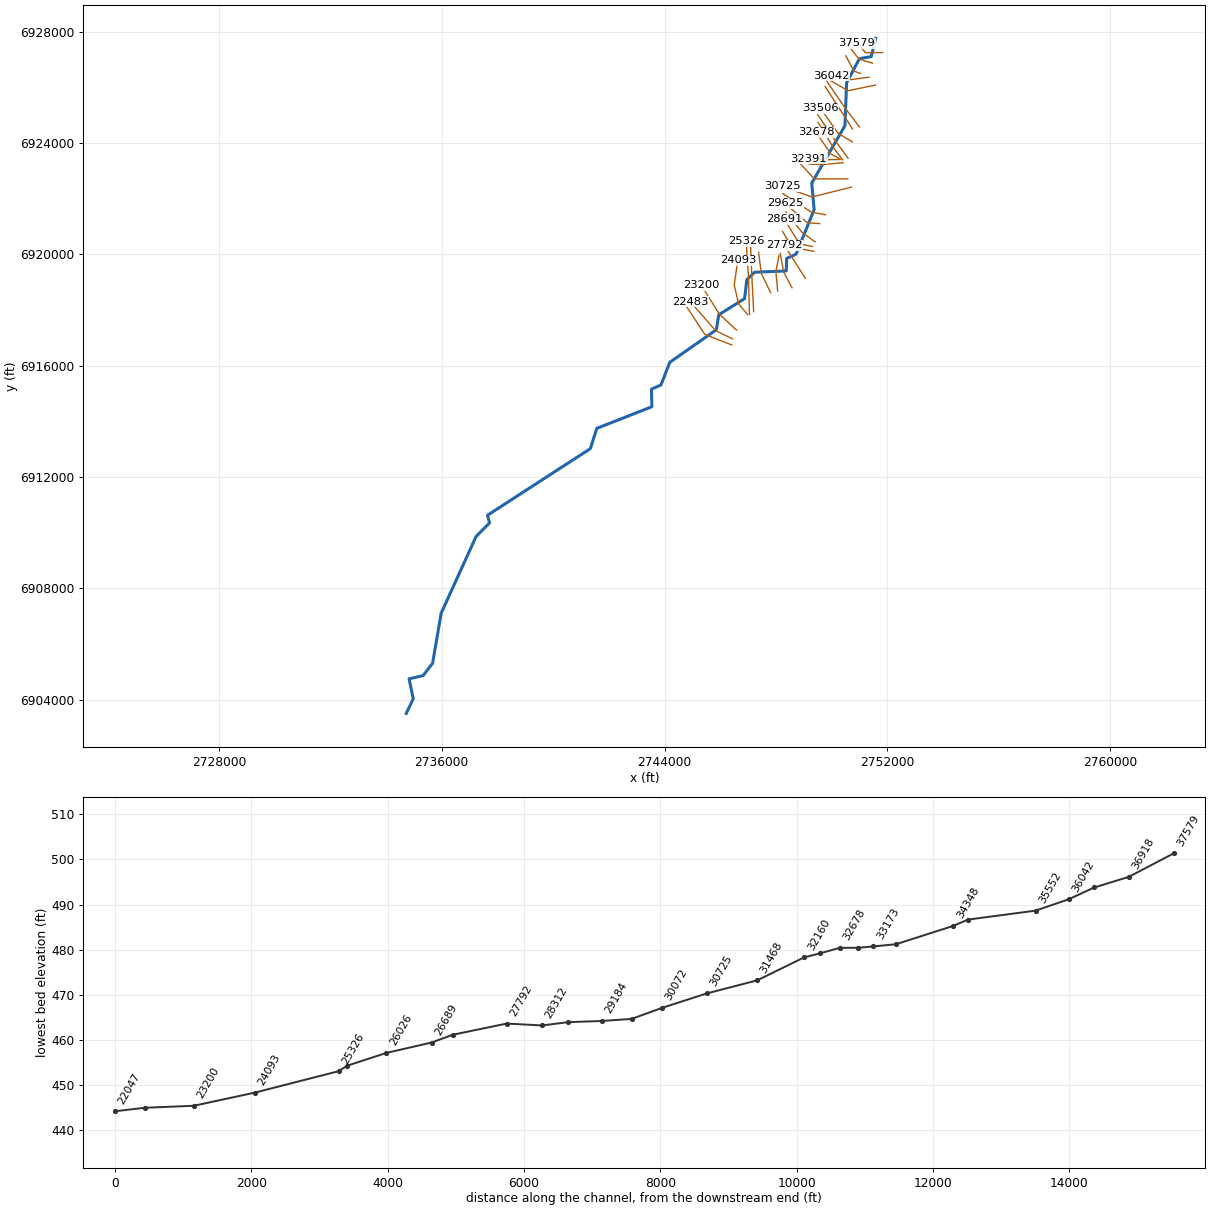
--- Flat Creek.prj (project) ---

Proj Title=Flat Creek Base Level Engineering
Current Plan=p01
Default Exp/Contr=0.3,0.1
English Units
Geom File=g01
Flow File=f01
Plan File=p01
Y Axis Title=Elevation
X Axis Title(PF)=Main Channel Distance
X Axis Title(XS)=Station
BEGIN DESCRIPTION:
Flat Creek
END DESCRIPTION:
DSS Export Rating Curves= 0
DSS Export Rating Curve Sorted= 0
DSS Export Volume Flow Curves= 0
DXF OffsetX= 0
DXF OffsetY= 0
DXF ScaleX= 1
DXF ScaleY= 10

--- Flat Creek.p01 (plan) ---

Plan Title=Multiple Run
Short Identifier=Multiple
Geom File=g01
Flow File=f01
Subcritical Flow
K Sum by GR= 0
Std Step Tol= 0.01
Critical Tol= 0.01
Num of Std Step Trials= 20
Max Error Tol= 0.3
Flow Tol Ratio= 0.001
Split Flow NTrial= 30
Split Flow Tol= 0.02
Split Flow Ratio= 0.02
Log Output Level= 0
Friction Slope Method= 1
Unsteady Friction Slope Method= 2
Unsteady Bridges Friction Slope Method= 1
Parabolic Critical Depth
Global Vel Dist=  1 , 1 , 1
Global Log Level= 0
CheckData=True
Encroach Param= -1, 0, 0, 0
BEGIN DESCRIPTION:
Multiple Run
END DESCRIPTION:

--- Flat Creek.f01 (steady flow) ---

Flow Title=Multiple
Program Version=4.10
Number of Profiles= 7
Profile Names=10-year,25-year,50-year,1pct_min,100-year,1pct_plu,500-year
River Rch & RM=Flat Creek,Reach-1         ,37579
     484     642     770     459     916    1829    1300
River Rch & RM=Flat Creek,Reach-1         ,33506
     730     989    1200     724    1444    2881    2094
River Rch & RM=Flat Creek,Reach-1         ,27792
    1594    2245    2800    1729    3451    6885    5257
River Rch & RM=Flat Creek,Reach-1         ,23200
    1795    2538    3172    1963    3916    7813    5986
River Rch & RM=Flat Creek,Reach-1         ,19472
    1864    2633    3289    2033    4057    8095    6193
River Rch & RM=Flat Creek,Reach-1         ,15129
    2059    2918    3652    2262    4513    9005    6914
River Rch & RM=Flat Creek,Reach-1         ,12652
    2717    3890    4903    3056    6097   12165    9454
River Rch & RM=Flat Creek,Reach-1         ,6935
    4465    6491    8260    5182   10339   20629   16197
River Rch & RM=Flat Creek,Reach-1         ,4849
    4557    6621    8422    5280   10536   21021   16487
River Rch & RM=Flat Creek,Reach-1         ,287
    4712    6851    8720    5469   10913   21774   17091
Boundary for River Rch & Prof#=Flat Creek,Reach-1         , 1
Up Type= 0
Dn Type= 3
Dn Slope=0.0028
Boundary for River Rch & Prof#=Flat Creek,Reach-1         , 2
Up Type= 0
Dn Type= 3
Dn Slope=0.0028
Boundary for River Rch & Prof#=Flat Creek,Reach-1         , 3
Up Type= 0
Dn Type= 3
Dn Slope=0.0028
Boundary for River Rch & Prof#=Flat Creek,Reach-1         , 4
Up Type= 0
Dn Type= 3
Dn Slope=0.0028
Boundary for River Rch & Prof#=Flat Creek,Reach-1         , 5
Up Type= 0
Dn Type= 3
Dn Slope=0.0028
Boundary for River Rch & Prof#=Flat Creek,Reach-1         , 6
Up Type= 0
Dn Type= 3
Dn Slope=0.0028
Boundary for River Rch & Prof#=Flat Creek,Reach-1         , 7
Up Type= 0
Dn Type= 3
Dn Slope=0.0028
DSS Import GetInterval= 0
DSS Import GetPeak= 0
DSS Import FillOption= 0

--- Flat Creek.g01 (geometry) ---

Geom Title=Existing Conditions
Program Version=4.10

River Reach=Flat Creek      ,Reach-1
Reach XY= 30
        2751576.        6927761.      2751417.86      6927104.91
       2750995.4      6927031.66      2750533.53      6926164.57
       2750474.5      6924622.53      2749283.85      6922564.23
      2749368.39      6921607.67      2748720.95      6920008.72
      2748378.93      6919853.03      2748368.64      6919404.68
      2747231.49      6919359.04      2746952.26      6919087.89
      2746871.03      6918408.42      2745945.08      6917831.52
      2745856.77      6917290.42      2744186.18      6916120.71
      2743867.96      6915304.67      2743529.43      6915159.78
      2743543.05      6914526.97      2741565.98      6913749.77
       2741335.7      6913021.72      2737642.64      6910628.53
      2737717.23       6910354.2      2737231.46      6909863.66
      2735979.75      6907109.45      2735672.18      6905312.58
       2735332.5      6904868.62      2734828.46      6904752.91
      2734976.62      6904035.67        2734726.        6903511.

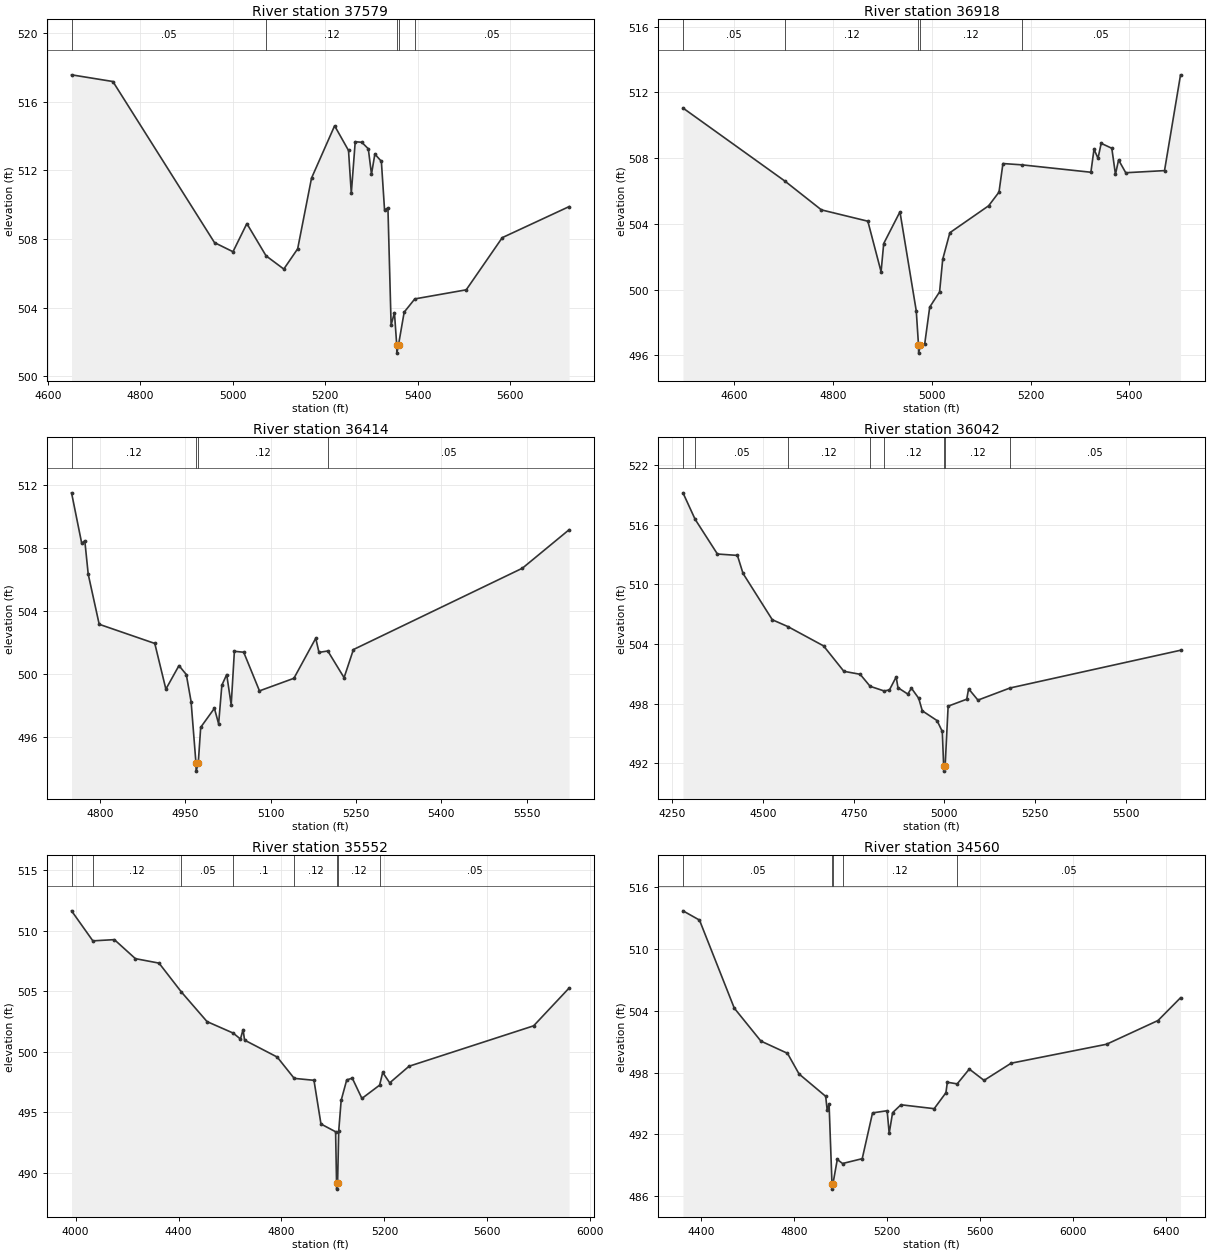
Type RM Length L Ch R = 1 ,37579   ,661,661,661
BEGIN DESCRIPTION:
Flat Creek 65.0
END DESCRIPTION:
XS GIS Cut Line= 3
      2751825.53      6927247.88      2751218.88      6927243.54
      2750894.96      6927584.69
#Sta/Elev= 30
  4650.9  517.57  4740.4  517.18  4960.4  507.79  5000.4  507.26  5030.4   508.9
    5072  507.02  5110.4  506.25  5140.4  507.43  5170.4  511.55  5220.4   514.6
  5250.5  513.16  5256.5  510.66    5265  513.67  5279.1  513.64  5293.3  513.26
  5300.2  511.78  5307.5  512.95  5321.6  512.53  5328.5  509.69  5335.8  509.82
  5342.7  502.99  5349.9  503.71  5354.8  501.85  5355.1  501.35  5358.8  501.85
    5371  503.74    5394  504.51  5505.3  505.04  5583.3  508.08    5728  509.89
#Mann= 5 ,-1 , 0
  4650.9     .05       0    5072     .12       0  5354.8     .04       0
  5358.8     .12       0    5394     .05       0
Bank Sta=5354.8,5358.8
XS Rating Curve= 0 ,0
Exp/Cntr=0.3,0.1

Type RM Length L Ch R = 1 ,36918   ,504,504,504
BEGIN DESCRIPTION:
Mapping XS b2938f8c
END DESCRIPTION:
XS GIS Cut Line= 3
      2751464.16      6926869.83      2750981.47      6927015.68
        2750670.      6927410.21
#Sta/Elev= 30
  4496.7  511.05  4702.6  506.61  4776.8  504.85  4870.8  504.16  4897.6  501.08
  4902.9   502.8  4935.8  504.73  4968.8   498.7  4973.3  496.63  4973.6  496.13
  4977.3  496.63  4985.8  496.67    4996  498.93    5016  499.86  5022.3  501.84
  5036.8  503.46  5115.3   505.1  5136.2  505.93  5144.2  507.67  5182.8  507.59
  5322.2  507.14  5328.5  508.54  5336.6  507.99    5343   508.9  5364.5   508.6
  5371.9  507.01  5378.2  507.89  5392.7  507.11  5471.2  507.24  5503.6  513.07
#Mann= 5 ,-1 , 0
  4496.7     .05       0  4702.6     .12       0  4973.3     .07       0
  4977.3     .12       0  5182.8     .05       0
Bank Sta=4973.3,4977.3
XS Rating Curve= 0 ,0
Exp/Cntr=0.3,0.1

Type RM Length L Ch R = 1 ,36414   ,372,372,372
BEGIN DESCRIPTION:
Mapping XS 8b80e938
END DESCRIPTION:
XS GIS Cut Line= 3
      2751033.55      6926498.32      2750793.97      6926585.12
      2750505.78      6927133.72
#Sta/Elev= 30
  4749.9  511.52  4767.8   508.3  4773.2  508.47  4779.2  506.34  4798.5  503.15
  4896.2  501.93  4915.7  499.02  4938.7  500.52  4951.6  499.95    4960  498.23
  4968.6   494.3  4968.9   493.8  4972.6   494.3  4976.9  496.59    5001   497.8
  5008.4  496.81  5014.1  499.27  5022.6  499.95  5030.5  498.02  5036.1  501.43
  5052.5  501.37  5080.2  498.91  5140.7  499.71  5179.1  502.26  5184.8  501.36
  5200.3  501.45  5228.9  499.75  5245.3  501.54  5542.3  506.72  5624.4  509.17
#Mann= 4 ,-1 , 0
  4749.9     .12       0  4968.6     .07       0  4972.6     .12       0
  5200.3     .05       0
Bank Sta=4968.6,4972.6
XS Rating Curve= 0 ,0
Exp/Cntr=0.3,0.1

Type RM Length L Ch R = 1 ,36042   ,490,490,490
BEGIN DESCRIPTION:
Mapping XS 1f30d862
END DESCRIPTION:
XS GIS Cut Line= 3
      2751340.01      6926366.38      2750631.65      6926269.15
      2749992.76      6926421.93
#Sta/Elev= 30
  4279.2  519.22  4312.6  516.56  4374.1  513.06  4429.3  512.92  4444.7  511.11
  4525.5  506.44  4568.6  505.75  4666.8  503.81  4722.8  501.25  4767.7  500.95
  4795.2  499.74    4834  499.27  4848.5  499.38    4867  500.68    4872   499.6
    4899  498.96  4909.1  499.55  4929.2  498.53  4939.1  497.27  4979.7  496.29
  4994.2  495.19    4998   491.7  4998.3   491.2    5002   491.7  5010.3  497.74
  5061.6  498.44  5066.7  499.49  5092.5  498.35  5180.9  499.57  5651.1  503.37
#Mann= 8 ,-1 , 0
  4279.2     .12       0  4312.6     .05       0  4568.6     .12       0
  4795.2      .1       0    4834     .12       0    4998     .07       0
    5002     .12       0  5180.9     .05       0
Bank Sta=4998,5002
XS Rating Curve= 0 ,0
Exp/Cntr=0.3,0.1

Type RM Length L Ch R = 1 ,35552   ,992,992,992
BEGIN DESCRIPTION:
Mapping XS 514d8c9e
END DESCRIPTION:
XS GIS Cut Line= 3
      2751569.12      6926081.65      2750589.98      6925880.26
      2749777.49      6926342.06
#Sta/Elev= 30
  3983.9  511.65  4066.7  509.17  4150.4  509.27  4232.1   507.7    4324  507.33
  4411.1  504.94  4510.6   502.5  4612.3  501.55  4640.5  501.06  4650.7  501.84
  4656.5  500.97  4783.4  499.57  4849.5  497.81  4926.3  497.65  4953.5  494.04
  5010.4   493.4  5014.1  489.16  5014.4  488.66  5018.1  489.16  5022.6  493.48
    5032  495.99  5053.6  497.68  5075.2  497.83  5112.7  496.15  5181.5  497.25
  5193.5   498.3  5220.8  497.44  5295.8  498.81  5780.2  502.15  5918.1  505.27
#Mann= 8 ,-1 , 0
  3983.9     .05       0  4066.7     .12       0  4411.1     .05       0
  4612.3      .1       0  4849.5     .12       0  5014.1     .07       0
  5018.1     .12       0  5181.5     .05       0
Bank Sta=5014.1,5018.1
XS Rating Curve= 0 ,0
Exp/Cntr=0.3,0.1

Type RM Length L Ch R = 1 ,34560   ,212,212,212
BEGIN DESCRIPTION:
Mapping XS f76498ea
END DESCRIPTION:
XS GIS Cut Line= 4
      2750992.78      6924578.15      2750586.51       6925112.9
      2750235.81       6925612.9      2749753.19      6926321.21
#Sta/Elev= 30
  4322.7  513.72  4393.6  512.82  4543.3  504.26  4657.7  501.06    4772  499.87
  4821.9  497.86  4936.3  495.69  4942.6  494.37  4950.9  494.94  4963.4  487.17
  4963.7  486.67  4967.4  487.17  4986.2  489.55  5008.9  489.16  5093.4  489.63
  5137.8  494.08  5200.6  494.29  5209.3  492.09    5224   494.1  5259.8  494.87
  5402.8  494.49  5453.3  496.04  5459.4  497.06  5501.7   496.9  5553.8  498.34
  5617.2  497.24  5733.8  498.91  6143.8  500.75  6365.3  503.06  6462.1  505.27
#Mann= 5 ,-1 , 0
  4322.7     .05       0  4963.4     .04       0  4967.4     .05       0
  5008.9     .12       0  5501.7     .05       0
Bank Sta=4963.4,4967.4
XS Rating Curve= 0 ,0
Exp/Cntr=0.3,0.1

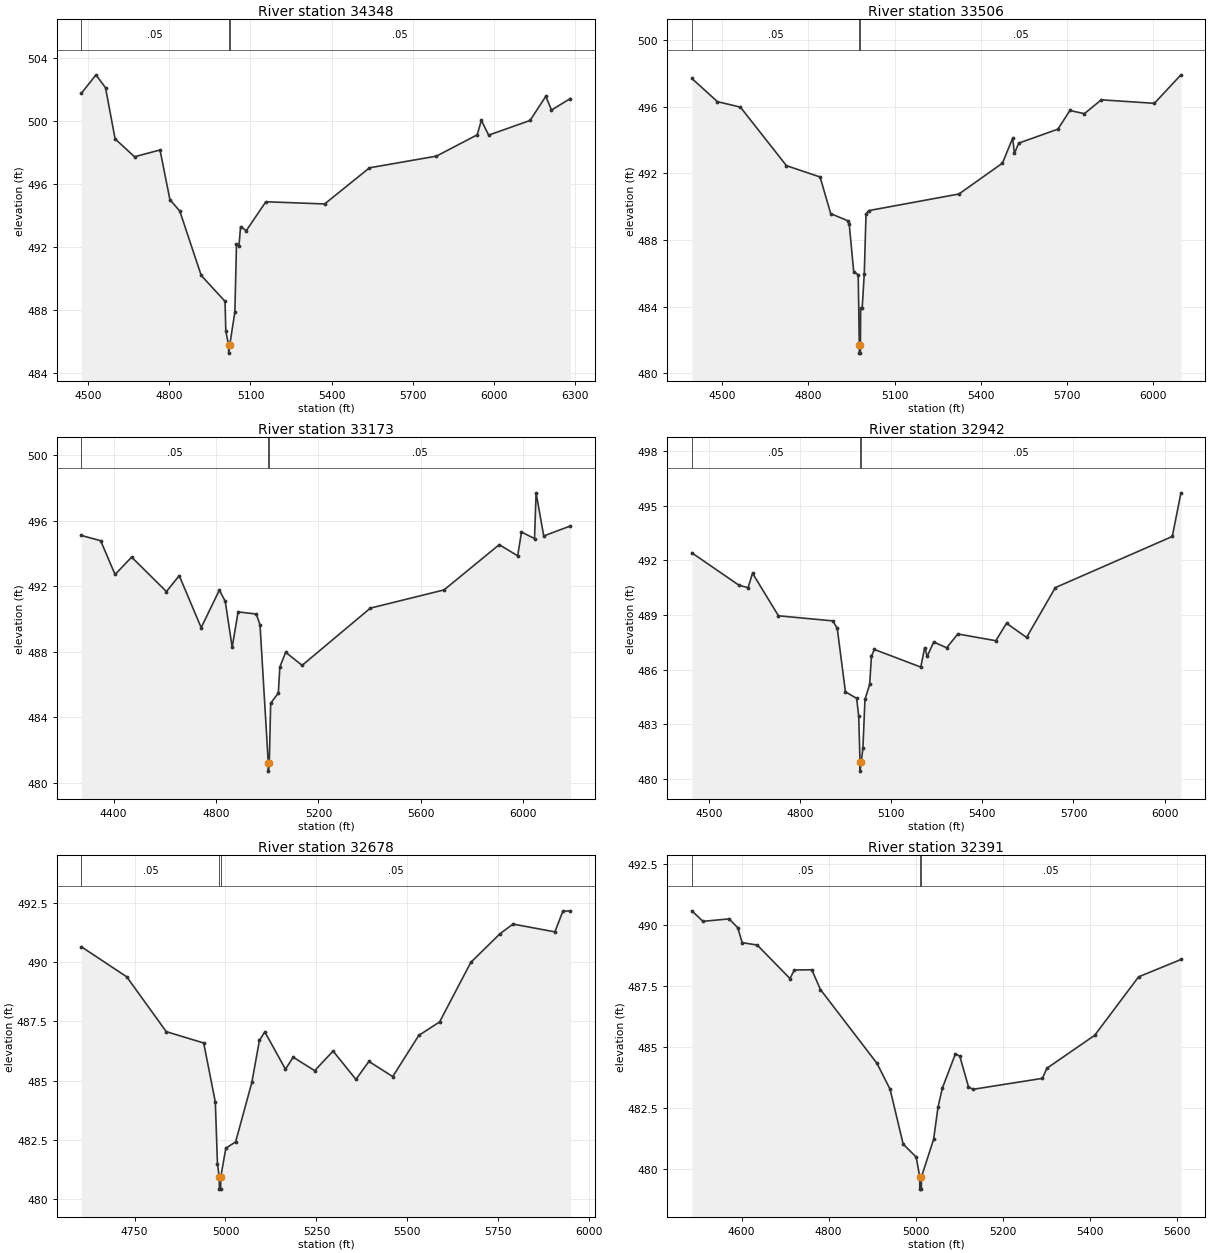
Type RM Length L Ch R = 1 ,34348   ,842,842,842
BEGIN DESCRIPTION:
Mapping XS d654c980
END DESCRIPTION:
XS GIS Cut Line= 3
      2750742.77      6924505.25      2750458.03      6924960.12
      2749763.62      6926026.04
#Sta/Elev= 30
  4474.5  501.75  4528.5  502.92  4563.9   502.1  4599.3  498.86  4671.1  497.73
  4765.4  498.16    4802  495.01  4838.5  494.29  4917.8  490.21  5005.9  488.57
  5008.7  486.69  5019.1  485.79  5019.3  485.29  5023.1  485.79  5042.2   487.9
  5048.2  492.18  5057.3  492.07  5063.3   493.3  5084.4  493.05  5156.8  494.88
  5374.2  494.74  5540.1  497.03  5787.7  497.77  5938.6  499.12  5953.7  500.04
  5980.8   499.1  6134.1  500.03  6192.1  501.56  6213.2  500.69  6283.3  501.42
#Mann= 3 ,-1 , 0
  4474.5     .05       0  5019.1     .05       0  5023.1     .05       0
Bank Sta=5019.1,5023.1
XS Rating Curve= 0 ,0
Exp/Cntr=0.3,0.1

Type RM Length L Ch R = 1 ,33506   ,333,333,333
BEGIN DESCRIPTION:
Mapping XS d0178353
END DESCRIPTION:
XS GIS Cut Line= 3
      2750746.26      6924039.97      2750239.28       6924338.6
      2749594.29      6925247.14
#Sta/Elev= 30
  4394.2   497.7  4483.2  496.31  4563.2  495.98  4723.3  492.47  4840.4  491.79
  4877.5  489.59  4936.1  489.17  4941.9  488.96  4957.6   486.1  4973.2  485.93
    4977  481.72  4977.3  481.22  4980.8  481.22    4981  481.72  4981.6  483.94
  4987.1  483.94  4994.3  485.99  5000.4  489.55  5009.1  489.77    5324  490.77
  5475.3  492.62  5510.9  494.12  5517.1   493.2  5531.8  493.82  5668.4  494.66
  5710.2  495.78  5760.6  495.59  5819.5  496.42  6004.2  496.21  6096.8  497.92
#Mann= 3 ,-1 , 0
  4394.2     .05       0    4977     .05       0    4981     .05       0
Bank Sta=4977,4981
XS Rating Curve= 0 ,0
Exp/Cntr=0.3,0.1

Type RM Length L Ch R = 1 ,33173   ,231,231,231
BEGIN DESCRIPTION:
Mapping XS ca7fded4
END DESCRIPTION:
XS GIS Cut Line= 3
      2750586.51      6923456.64      2750152.48      6924046.93
      2749492.75      6925022.64
#Sta/Elev= 30
    4274  495.09  4349.3  494.77  4405.6  492.71  4470.4  493.77  4606.2  491.67
  4656.3  492.64    4742  489.47  4813.1  491.76  4836.1  491.07  4863.1  488.27
  4886.2  490.43  4957.2   490.3  4971.9  489.64  5004.1  481.22  5004.4  480.72
  5008.1  481.22  5013.5  484.86  5043.4  485.48  5049.4  487.07    5072  487.97
  5136.3  487.17    5403  490.66  5690.7  491.77  5906.4  494.53  5978.4  493.85
  5993.3   495.3  6044.2   494.9  6050.3  497.69  6080.2  495.06  6184.5  495.67
#Mann= 3 ,-1 , 0
    4274     .05       0  5004.1     .05       0  5008.1     .05       0
Bank Sta=5004.1,5008.1
XS Rating Curve= 0 ,0
Exp/Cntr=0.3,0.1

Type RM Length L Ch R = 1 ,32942   ,264,264,264
BEGIN DESCRIPTION:
Mapping XS 70d2dfd3
END DESCRIPTION:
XS GIS Cut Line= 3
      2750392.07      6923397.61      2750051.78      6923849.01
      2749506.64      6924741.38
#Sta/Elev= 30
  4443.1  492.42  4599.1  490.63  4628.3  490.51  4642.8   491.3  4728.2  488.96
  4907.2  488.68  4921.8  488.28  4948.9  484.78  4985.8  484.42  4992.6  483.44
  4996.9  480.92  4997.1  480.42  5000.9  480.92  5006.5   481.7  5013.2  484.36
  5028.7  485.19  5034.6  486.74  5044.1  487.11    5197  486.14  5209.9  487.21
  5218.3  486.73  5239.7  487.52  5282.3   487.2    5319  487.96  5444.3  487.59
  5479.5  488.55  5545.5  487.77  5640.3  490.51  6025.5  493.32  6054.1  495.72
#Mann= 3 ,-1 , 0
  4443.1     .05       0  4996.9     .05       0  5000.9     .05       0
Bank Sta=4996.9,5000.9
XS Rating Curve= 0 ,0
Exp/Cntr=0.3,0.1

Type RM Length L Ch R = 1 ,32678   ,287,287,287
BEGIN DESCRIPTION:
Mapping XS bf669c13
END DESCRIPTION:
XS GIS Cut Line= 3
      2750319.15      6923414.98       2749975.4      6923605.96
      2749431.05      6924386.07
#Sta/Elev= 30
  4603.8  490.66  4728.5  489.39  4837.2  487.07  4940.1  486.59  4972.1  484.09
  4977.9  481.48  4982.9  480.91  4983.2  480.41  4986.7  480.41  4986.9  480.91
  5000.9  482.14  5027.9  482.41  5072.4  484.92  5093.4  486.71  5108.2  487.06
  5164.9  485.48  5186.1  485.99  5245.2  485.42  5295.8  486.25  5358.6  485.05
  5394.3  485.81  5459.8  485.17  5531.3  486.91  5588.5  487.48  5674.4     490
  5754.6  491.21  5790.4  491.62  5905.5  491.29  5927.4  492.16  5948.3  492.18
#Mann= 3 ,-1 , 0
  4603.8     .05       0  4982.9     .04       0  4986.9     .05       0
Bank Sta=4982.9,4986.9
XS Rating Curve= 0 ,0
Exp/Cntr=0.3,0.1

Type RM Length L Ch R = 1 ,32391   ,231,231,231
BEGIN DESCRIPTION:
Mapping XS fb7bde04
END DESCRIPTION:
XS GIS Cut Line= 4
      2750291.35      6923408.04      2749780.95       6923401.1
      2749280.95      6923404.57      2749173.27       6923439.3
#Sta/Elev= 30
  4485.9  490.57  4511.3  490.14  4571.3  490.24  4591.3  489.88  4601.3  489.27
  4636.1  489.17  4711.3   487.8  4721.3  488.15  4761.3  488.16  4781.3  487.35
  4911.3  484.33  4941.3  483.27  4971.3  481.03  5001.3   480.5  5009.3  479.69
  5009.5  479.19    5013  479.19  5013.3  479.69  5041.3  481.23  5051.3  482.54
  5061.3  483.32  5091.3  484.72  5101.3  484.63  5121.3  483.38  5131.3  483.27
  5291.3  483.72  5301.3  484.13  5411.3  485.48  5512.1  487.87  5609.5  488.58
#Mann= 3 ,-1 , 0
  4485.9     .05       0  5009.3     .05       0  5013.3     .05       0
Bank Sta=5009.3,5013.3
XS Rating Curve= 0 ,0
Exp/Cntr=0.3,0.1

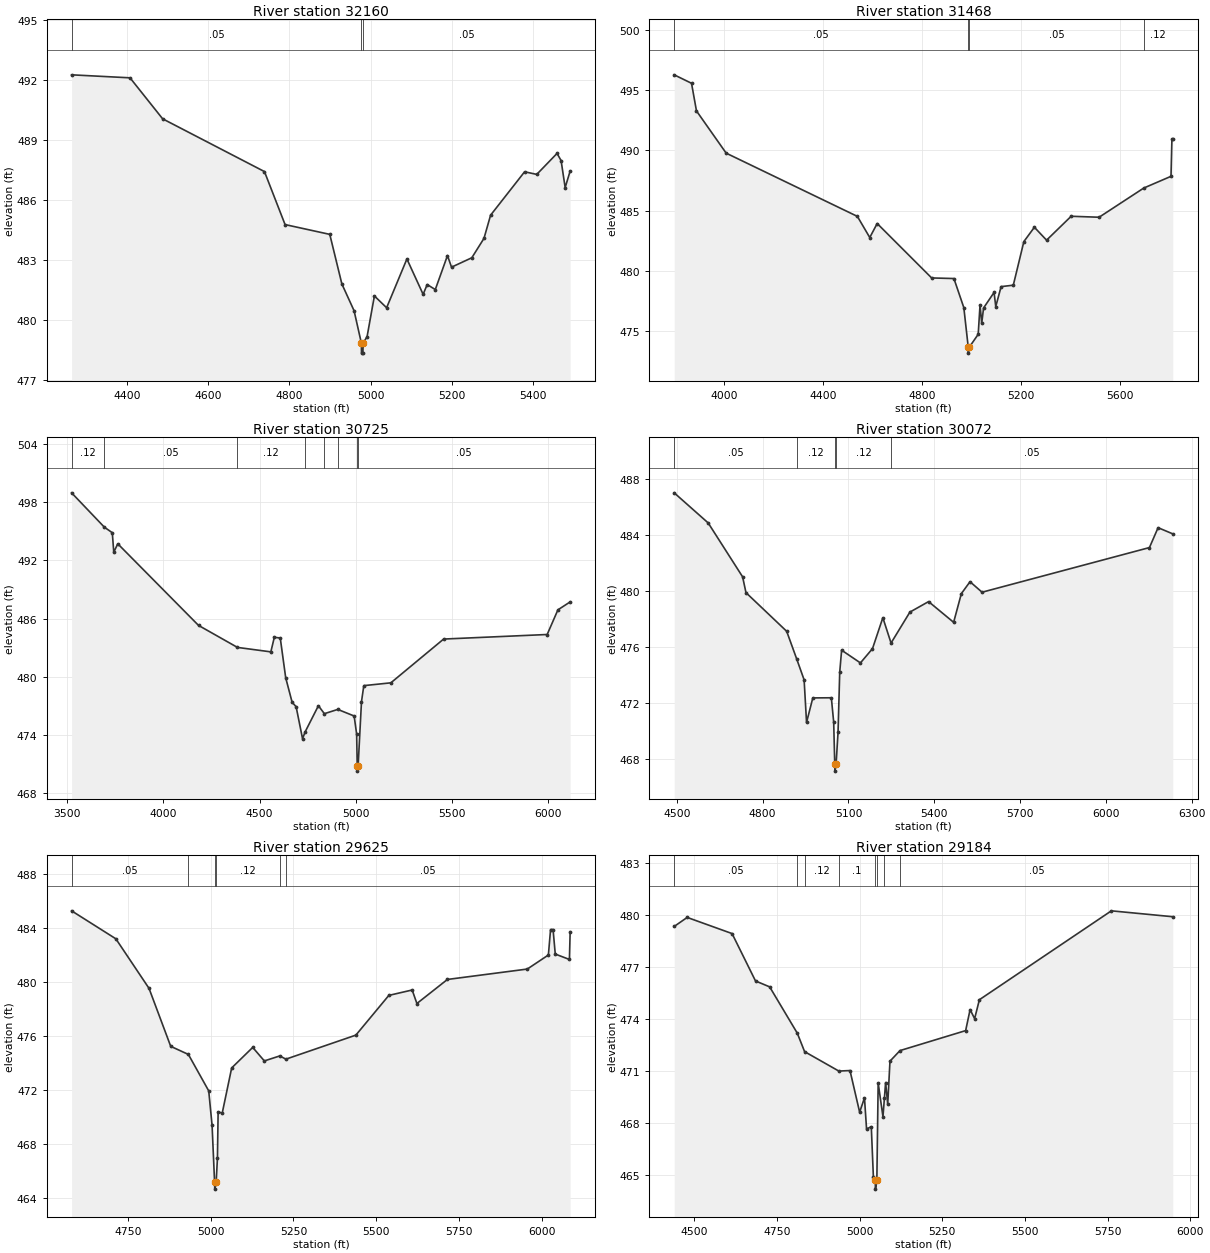
Type RM Length L Ch R = 1 ,32160   ,692,692,692
BEGIN DESCRIPTION:
Mapping XS 5c3e6ced
END DESCRIPTION:
XS GIS Cut Line= 3
      2750409.42      6923293.46       2749687.2      6923227.48
      2749183.72      6923241.37
#Sta/Elev= 30
    4263  492.24    4407  492.09  4487.4  490.04  4738.4   487.4  4789.2  484.75
  4899.4  484.26  4929.2  481.78  4959.3  480.44  4977.3  478.82  4977.6  478.32
  4981.1  478.32  4981.4  478.82  4991.3  479.14  5009.4  481.18  5039.5  480.59
  5089.5  483.03  5129.5  481.26  5139.5  481.75  5159.5   481.5  5189.5   483.2
  5199.5  482.62  5249.5  483.09  5279.5  484.06  5295.8  485.22  5379.6  487.39
  5409.6  487.26  5459.6  488.31  5469.6  487.95  5479.6   486.6  5491.9  487.43
#Mann= 3 ,-1 , 0
    4263     .05       0  4977.3     .04       0  4981.4     .05       0
Bank Sta=4977.3,4981.4
XS Rating Curve= 0 ,0
Exp/Cntr=0.3,0.1

Type RM Length L Ch R = 1 ,31468   ,743,743,743
BEGIN DESCRIPTION:
Flat Creek 52.0
END DESCRIPTION:
XS GIS Cut Line= 3
      2750576.05        6922711.        2749376.        6922711.
      2748825.99      6923311.01
#Sta/Elev= 30
  3799.5  496.26  3869.5  495.56  3889.5  493.27  4009.5  489.77  4539.5  484.53
  4589.5  482.78  4619.5  483.94  4839.5  479.43  4929.5  479.38  4969.5  476.97
  4987.3   473.7  4987.7   473.2  4991.8   473.7  5027.6  474.76    5035   477.2
  5041.8  475.67  5049.2  476.94  5091.7  478.23  5098.5  477.06  5120.1  478.71
  5169.4  478.83    5212  482.44  5254.5  483.63  5303.8  482.56  5403.1  484.54
    5516  484.46  5696.5  486.88  5806.4  487.85  5810.1  490.91  5813.5  490.91
#Mann= 4 ,-1 , 0
  3799.5     .05       0  4987.3     .04       0  4991.8     .05       0
  5696.5     .12       0
Bank Sta=4987.3,4991.8
XS Rating Curve= 0 ,0
Exp/Cntr=0.3,0.1

Type RM Length L Ch R = 1 ,30725   ,653,653,653
BEGIN DESCRIPTION:
Mapping XS a2048764
END DESCRIPTION:
XS GIS Cut Line= 3
      2750708.89      6922416.72      2749285.29      6922060.82
      2748227.76      6922446.56
#Sta/Elev= 30
  3522.6  498.97    3693  495.43  3734.3  494.86    3742  492.85  3762.7  493.72
  4182.7  485.31  4385.2  483.04  4558.9  482.58    4577  484.08  4607.9  484.01
  4636.2  479.91  4669.7  477.38  4690.4  476.93  4723.8  473.63  4737.4  474.34
  4806.3  477.03  4837.3  476.21  4907.2  476.65  4992.3  475.97  5005.2   474.1
  5008.2  470.79  5008.7  470.29  5012.8  470.79  5030.4  477.45  5042.5   479.1
  5183.2  479.39  5457.6   483.9  5996.2  484.37    6052  486.91  6115.7  487.73
#Mann= 8 ,-1 , 0
  3522.6     .12       0    3693     .05       0  4385.2     .12       0
  4737.4      .1       0  4837.3     .12       0  4907.2     .05       0
  5008.2     .04       0  5012.8     .05       0
Bank Sta=5008.2,5012.8
XS Rating Curve= 0 ,0
Exp/Cntr=0.3,0.1

Type RM Length L Ch R = 1 ,30072   ,447,447,447
BEGIN DESCRIPTION:
Mapping XS 3c168a63
END DESCRIPTION:
XS GIS Cut Line= 3
      2749782.93       6921422.6      2749267.35      6921516.34
      2748246.49      6922183.03
#Sta/Elev= 30
  4490.6  486.98  4609.4  484.83  4729.8  480.98  4741.6  479.85  4883.9  477.09
    4919  475.11  4944.9  473.62  4953.4  470.58  4975.3  472.33  5040.1  472.34
  5048.3   470.6    5052   467.6  5052.5   467.1  5056.7   467.6  5063.5  469.86
  5069.4  474.16    5076  475.74  5141.8  474.83    5184  475.85  5220.2  478.06
  5248.9  476.25  5314.8  478.46  5380.1  479.21  5467.7  477.73  5494.7  479.78
    5525  480.63  5567.1  479.88  6152.4  483.07  6182.6  484.49  6233.9  484.05
#Mann= 5 ,-1 , 0
  4490.6     .05       0    4919     .12       0    5052     .07       0
  5056.7     .12       0  5248.9     .05       0
Bank Sta=5052,5056.7
XS Rating Curve= 0 ,0
Exp/Cntr=0.3,0.1

Type RM Length L Ch R = 1 ,29625   ,441,441,441
BEGIN DESCRIPTION:
Mapping XS 6fe64a05
END DESCRIPTION:
XS GIS Cut Line= 3
      2749569.41      6921104.89      2749126.73      6921136.14
      2748320.22      6921828.17
#Sta/Elev= 30
  4579.6  485.25  4713.3  483.18  4813.6  479.51  4879.1  475.22  4932.5  474.62
    4994  471.92  5004.1  469.37  5011.7  465.15  5012.2  464.65  5016.4  465.15
  5020.3  466.94  5022.4  470.38  5034.7  470.27  5063.3  473.62  5126.9  475.14
    5162  474.14  5208.8  474.51  5227.1  474.27  5438.6  476.05  5538.2  478.99
  5608.7  479.39    5623  478.39  5715.2  480.17  5956.6  480.94  6020.3  481.98
  6026.9  483.86  6034.5  483.86  6041.1  482.05  6083.9  481.65  6086.1   483.7
#Mann= 6 ,-1 , 0
  4579.6     .05       0  4932.5     .12       0  5011.7     .07       0
  5016.4     .12       0  5208.8      .1       0  5227.1     .05       0
Bank Sta=5011.7,5016.4
XS Rating Curve= 0 ,0
Exp/Cntr=0.3,0.1

Type RM Length L Ch R = 1 ,29184   ,493,493,493
BEGIN DESCRIPTION:
Mapping XS 7bae813b
END DESCRIPTION:
XS GIS Cut Line= 3
      2749397.55      6920448.65      2748928.81      6920797.59
      2748355.89      6921521.56
#Sta/Elev= 30
  4439.4  479.32  4478.7  479.84  4614.4  478.91  4685.3  476.18  4728.1  475.84
  4811.7  473.17  4833.7  472.11  4937.3  470.99    4971  471.02  5000.2  468.62
  5014.8  469.45  5021.1  467.65  5035.4  467.79  5041.8  464.86  5047.4  464.69
    5048  464.19  5052.2  464.69  5056.2  470.31  5070.7  468.36  5075.1  469.44
  5078.7  470.33  5085.1  469.09  5091.9  471.56  5122.2  472.17  5320.7  473.32
  5334.2  474.53  5347.9  474.01  5362.3   475.1  5761.4  480.22    5947  479.88
#Mann= 8 ,-1 , 0
  4439.4     .05       0  4811.7      .1       0  4833.7     .12       0
  4937.3      .1       0  5047.4     .07       0  5052.2      .1       0
  5075.1     .12       0  5122.2     .05       0
Bank Sta=5047.4,5052.2
XS Rating Curve= 0 ,0
Exp/Cntr=0.3,0.1

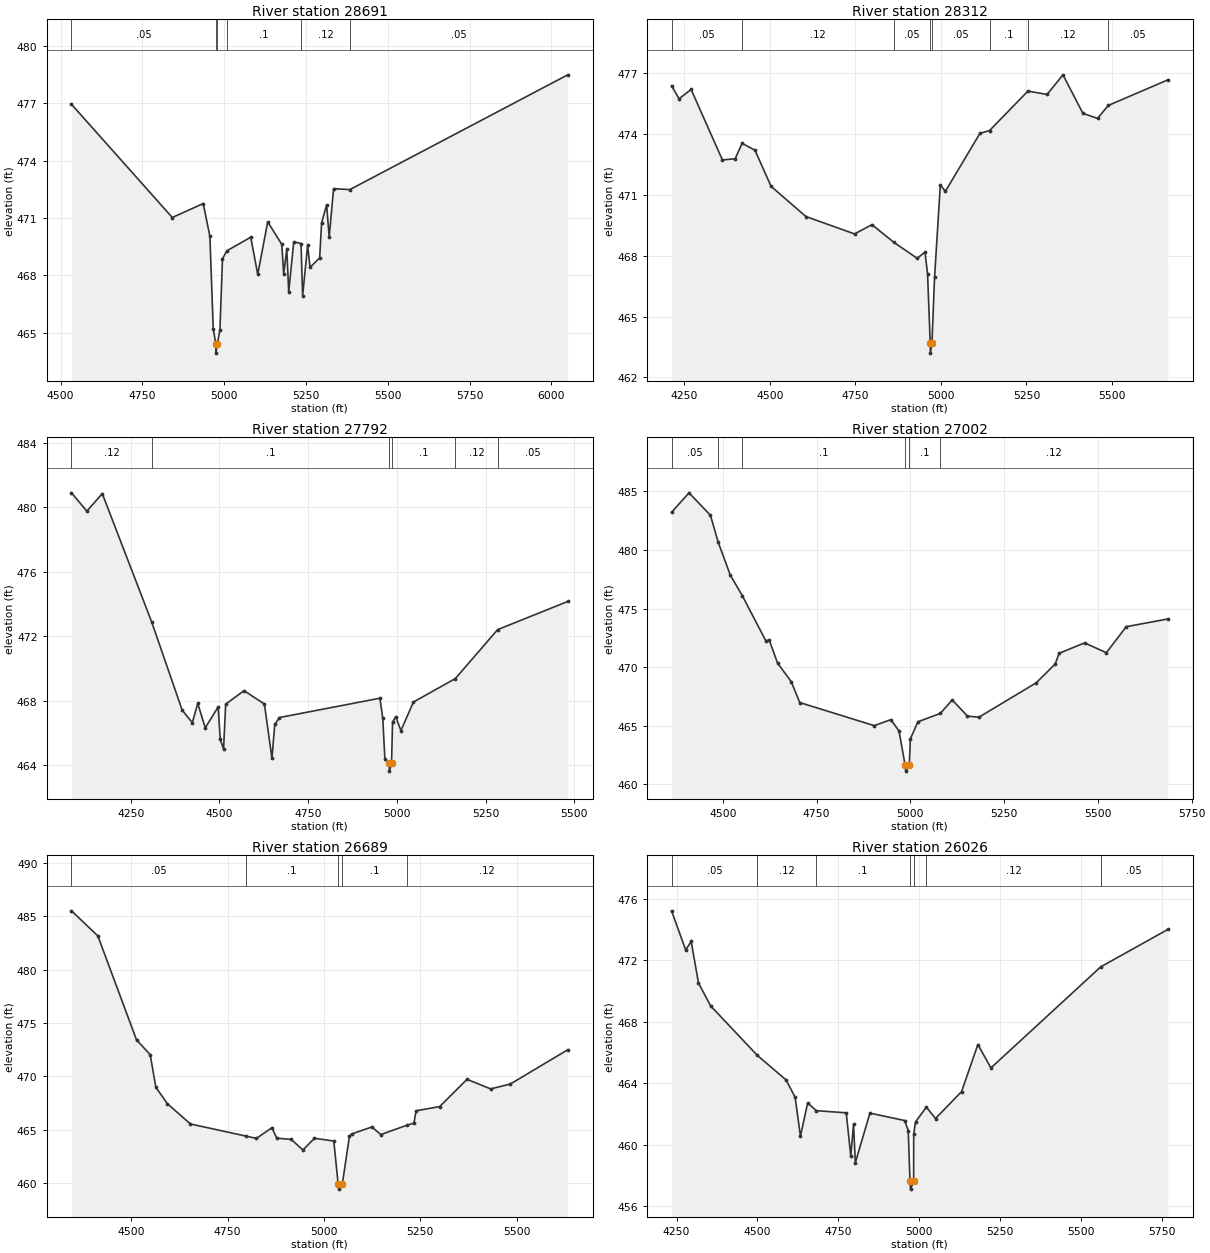
Type RM Length L Ch R = 1 ,28691   ,379,379,379
BEGIN DESCRIPTION:
Mapping XS be84138c
END DESCRIPTION:
XS GIS Cut Line= 3
        2749301.        6920286.      2748845.48      6920375.72
      2748293.38      6921271.58
#Sta/Elev= 30
  4533.1  476.94  4841.2  471.02  4935.7  471.75  4956.1  470.04  4966.3  465.21
  4974.1  464.43  4974.6  463.93  4978.9  464.43  4986.7  465.13  4994.6  468.86
    5008  469.28    5081  469.99  5102.3  468.05  5132.8  470.79  5175.7  469.62
  5181.6  468.08  5191.1  469.36    5197  467.13  5212.4  469.75  5234.6  469.66
  5239.5  466.94  5254.9  469.57    5262  468.41  5291.6  468.91  5297.5  470.75
  5312.9  471.68  5320.7  469.99  5334.1  472.53  5383.8  472.48  6049.7  478.48
#Mann= 6 ,-1 , 0
  4533.1     .05       0  4974.1     .04       0  4978.9     .05       0
    5008      .1       0  5234.6     .12       0  5383.8     .05       0
Bank Sta=4974.1,4978.9
XS Rating Curve= 0 ,0
Exp/Cntr=0.3,0.1

Type RM Length L Ch R = 1 ,28312   ,520,520,520
BEGIN DESCRIPTION:
Flat Creek 44.0
END DESCRIPTION:
XS GIS Cut Line= 3
      2749352.21      6920111.92      2748577.79      6920254.89
       2748236.1      6920823.64
#Sta/Elev= 30
  4212.5  476.39  4234.5  475.75  4269.7  476.21  4361.2  472.73  4398.5  472.79
  4418.8  473.55  4456.5  473.21  4503.5  471.43  4605.2  469.94  4747.6  469.08
  4798.4  469.54  4862.1  468.67  4930.6  467.88  4953.6  468.18  4961.1   467.1
  4968.8   463.7  4969.4   463.2  4973.9   463.7  4981.5  466.94  4998.4   471.5
  5013.1  471.18  5114.1  474.04  5142.2  474.18  5254.7  476.13  5310.4  475.96
    5357  476.93  5415.3  475.03    5458  474.78  5489.6  475.42  5663.5  476.68
#Mann= 8 ,-1 , 0
  4212.5     .05       0  4418.8     .12       0  4862.1     .05       0
  4968.8     .04       0  4973.9     .05       0  5142.2      .1       0
  5254.7     .12       0  5489.6     .05       0
Bank Sta=4968.8,4973.9
XS Rating Curve= 0 ,0
Exp/Cntr=0.3,0.1

Type RM Length L Ch R = 1 ,27792   ,790,790,790
BEGIN DESCRIPTION:
Flat Creek 43.0
END DESCRIPTION:
XS GIS Cut Line= 3
      2749053.26      6919137.74      2748560.94      6919911.13
      2748310.17      6920322.41
#Sta/Elev= 30
  4083.2  480.91  4126.6  479.77    4170  480.86    4309   472.9  4395.3   467.4
  4423.8  466.63    4439  467.83  4460.2  466.31  4496.6  467.61  4502.5  465.59
  4511.8  464.99  4517.7  467.78  4569.4  468.62  4626.9  467.79  4648.1  464.42
  4656.1  466.52  4669.3  466.95  4952.4  468.15  4960.5   466.9  4966.4  464.37
  4978.1  464.12  4979.2  463.62  4985.2  464.12    4988  466.67  4996.9     467
  5011.6  466.14  5046.7  467.91    5165  469.37  5284.1  472.41  5481.7  474.16
#Mann= 6 ,-1 , 0
  4083.2     .12       0    4309      .1       0  4978.1     .07       0
  4985.2      .1       0    5165     .12       0  5284.1     .05       0
Bank Sta=4978.1,4985.2
XS Rating Curve= 0 ,0
Exp/Cntr=0.3,0.1

Type RM Length L Ch R = 1 ,27002   ,313,313,313
BEGIN DESCRIPTION:
Flat Creek 42.0
END DESCRIPTION:
XS GIS Cut Line= 3
      2748575.29      6918799.39      2748275.95      6919361.11
      2748150.99      6920036.04
#Sta/Elev= 30
  4363.5  483.22  4410.1  484.88  4467.3  482.96  4487.5   480.7  4519.9  477.88
    4552  476.11  4614.6  472.27    4624  472.32    4646  470.36  4682.6  468.77
  4705.3  466.99  4903.9  465.02  4947.8  465.53  4969.8  464.58  4986.2  461.64
  4987.7  461.14  4997.3  461.64    5000  463.88  5020.2  465.35  5079.8  466.06
  5111.8  467.21  5152.4  465.83  5182.9  465.74  5335.5  468.67  5386.3  470.28
  5396.5  471.19  5464.6  472.08  5522.6  471.24  5575.5  473.46  5686.4  474.12
#Mann= 6 ,-1 , 0
  4363.5     .05       0  4487.5     .12       0    4552      .1       0
  4986.2     .07       0  4997.3      .1       0  5079.8     .12       0
Bank Sta=4986.2,4997.3
XS Rating Curve= 0 ,0
Exp/Cntr=0.3,0.1

Type RM Length L Ch R = 1 ,26689   ,663,663,663
BEGIN DESCRIPTION:
Mapping XS 95d7d046
END DESCRIPTION:
XS GIS Cut Line= 3
      2748059.86      6918682.89      2747995.45      6919379.22
      2748106.27      6919957.59
#Sta/Elev= 30
  4344.7  485.51  4413.1  483.16  4513.5  473.41  4549.1  472.02  4563.7  468.96
  4593.9  467.41  4653.6  465.52  4796.8  464.39  4824.9  464.17    4865  465.17
  4877.6  464.19  4915.2  464.07  4945.4  463.08  4975.5  464.18  5025.7  463.92
  5036.8  459.91  5038.3  459.41  5047.9  459.91  5066.2  464.38  5072.4  464.59
  5124.4  465.24  5147.6  464.53  5214.5  465.39  5233.6   465.6  5239.3  466.76
  5300.4  467.15  5371.6  469.71  5432.7  468.81  5483.6  469.26  5632.9  472.48
#Mann= 5 ,-1 , 0
  4344.7     .05       0  4796.8      .1       0  5036.8     .07       0
  5047.9      .1       0  5214.5     .12       0
Bank Sta=5036.8,5047.9
XS Rating Curve= 0 ,0
Exp/Cntr=0.3,0.1

Type RM Length L Ch R = 1 ,26026   ,576,576,576
BEGIN DESCRIPTION:
Mapping XS fb47c4da
END DESCRIPTION:
XS GIS Cut Line= 3
      2747807.96      6918622.25      2747471.14      6919316.72
      2747373.92      6920073.67
#Sta/Elev= 30
  4234.5   475.2  4278.2  472.66  4295.3  473.21  4317.8  470.51  4355.4  469.02
    4500   465.8  4588.7  464.21  4616.8  463.08  4633.2  460.55  4655.4  462.71
  4682.5  462.21  4774.8  462.07  4788.8  459.28  4797.4  461.33    4803  458.83
  4848.1  462.05  4955.4  461.57  4966.6  460.92  4972.1  457.61  4973.7  457.11
  4983.3  457.61  4983.5  460.67  4989.1  461.48  5022.7  462.44    5051   461.7
  5131.6  463.45    5182  466.51  5222.4  464.99  5562.1  471.56  5769.5  473.99
#Mann= 7 ,-1 , 0
  4234.5     .05       0    4500     .12       0  4682.5      .1       0
  4972.1     .07       0  4983.3      .1       0  5022.7     .12       0
  5562.1     .05       0
Bank Sta=4972.1,4983.3
XS Rating Curve= 0 ,0
Exp/Cntr=0.3,0.1

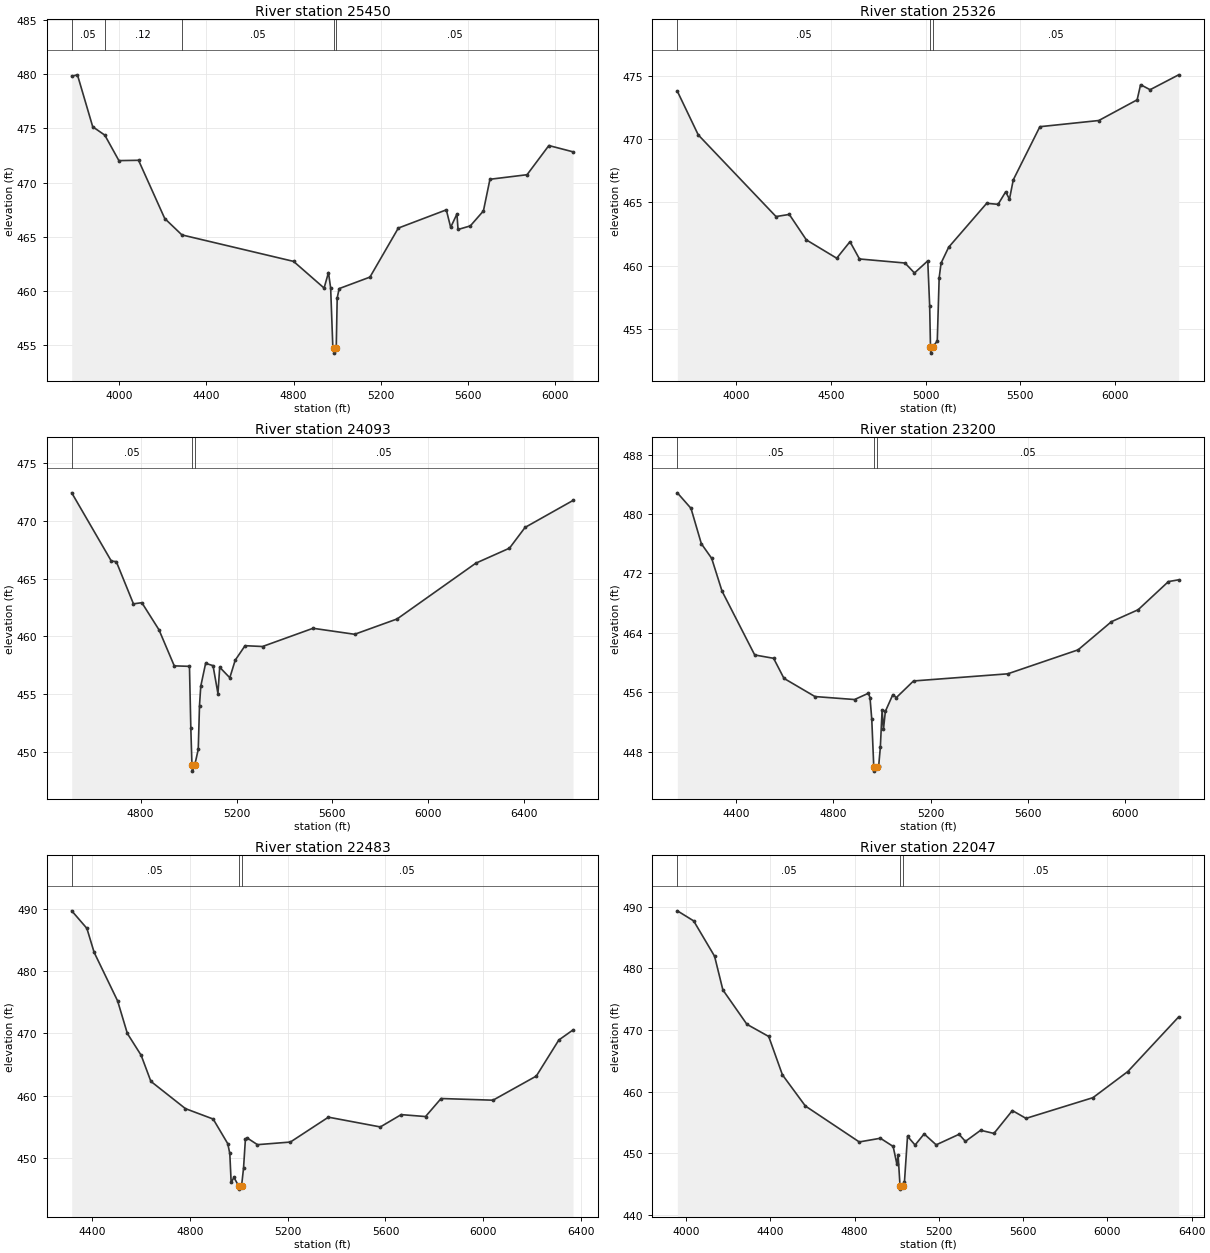
Type RM Length L Ch R = 1 ,25450   ,124,124,124
BEGIN DESCRIPTION:
Mapping XS 2a255611
END DESCRIPTION:
XS GIS Cut Line= 3
      2747197.18      6917944.86      2747134.68      6919174.01
      2747087.81      6920241.74
#Sta/Elev= 30
  3782.4   479.8  3808.6  479.93  3878.7  475.14  3934.1  474.37  3998.8  472.02
  4088.9  472.05  4209.1  466.68  4287.8  465.17  4799.9  462.73    4940  460.27
  4960.1   461.7  4970.1  460.27  4980.1   454.8  4984.5  454.77    4986  454.27
  4995.7  454.77  5000.1  459.36  5009.1  460.22  5150.3  461.28  5280.4   465.8
  5500.6  467.48  5520.6  465.87  5549.4   467.1  5554.4  465.67  5610.7     466
  5670.8  467.38  5700.8   470.3    5871  470.72    5971  473.41  6081.9  472.83
#Mann= 5 ,-1 , 0
  3782.4     .05       0  3934.1     .12       0  4287.8     .05       0
  4984.5     .05       0  4995.7     .05       0
Bank Sta=4984.5,4995.7
XS Rating Curve= 0 ,0
Exp/Cntr=0.3,0.1

Type RM Length L Ch R = 1 ,25326   ,1233,1233,1233
BEGIN DESCRIPTION:
Mapping XS 316987dc
END DESCRIPTION:
XS GIS Cut Line= 3
      2747046.14      6917840.72      2747014.89      6919142.76
      2746926.35      6920481.32
#Sta/Elev= 30
  3691.2  473.81  3801.5  470.35  4211.6  463.88  4281.6  464.05  4371.7  462.03
  4531.7  460.58  4601.7  461.89  4651.8  460.52  4891.8   460.2  4941.8  459.41
  5011.9  460.37  5021.9  456.82  5026.3  453.56  5027.9  453.06  5037.5  453.56
    5062  454.01    5072  459.02    5082  460.19  5122.1  461.45  5322.6  464.93
  5382.7  464.85  5422.8  465.84  5442.8  465.26  5462.9  466.79  5603.2     471
  5913.9  471.49  6116.2  473.13  6134.3  474.33  6184.5  473.93  6335.1  475.11
#Mann= 3 ,-1 , 0
  3691.2     .05       0  5026.3     .04       0  5037.5     .05       0
Bank Sta=5026.3,5037.5
XS Rating Curve= 0 ,0
Exp/Cntr=0.3,0.1

Type RM Length L Ch R = 1 ,24093   ,893,893,893
BEGIN DESCRIPTION:
Mapping XS 87f966b9
END DESCRIPTION:
XS GIS Cut Line= 4
      2746978.41       6917840.7      2746660.73      6918215.68
      2746499.27      6918892.76      2746629.29      6919787.33
#Sta/Elev= 30
  4512.4  472.44  4677.6  466.52  4698.4  466.47  4769.9  462.81    4805  462.91
  4876.4  460.56  4940.2  457.43  5003.6  457.39  5009.3  452.02    5014   448.8
  5015.5   448.3  5025.3   448.8  5040.2  450.18  5045.5  453.99  5050.7  455.66
    5071  457.65  5101.9  457.45  5122.4  455.03  5129.8  457.31  5171.9   456.4
  5194.4  457.92  5235.5  459.18  5308.5  459.11  5519.1  460.69  5692.7  460.17
  5869.9   461.5  6198.5  466.34  6338.8  467.64  6403.8  469.44  6603.9  471.78
#Mann= 3 ,-1 , 0
  4512.4     .05       0    5014     .04       0  5025.3     .05       0
Bank Sta=5014,5025.3
XS Rating Curve= 0 ,0
Exp/Cntr=0.3,0.1

Type RM Length L Ch R = 1 ,23200   ,717,717,717
BEGIN DESCRIPTION:
Mapping XS 6bbf6874
END DESCRIPTION:
XS GIS Cut Line= 3
      2746582.57       6917278.2      2745962.81       6917856.3
      2745322.69      6918886.74
#Sta/Elev= 30
  4158.8  482.86  4214.9  480.77  4257.4  476.01  4299.9  474.04  4342.4  469.63
  4476.8  461.03  4554.5  460.58    4597  457.88  4724.5  455.43  4887.2  455.03
  4943.8  455.87  4950.7   455.3    4958  452.35  4966.3  445.89  4967.9  445.39
    4978  445.89  4986.3  446.06  4993.2  448.61  5000.5  453.64  5006.1  451.04
  5013.8  453.43  5044.5  455.69  5058.9  455.29  5129.6  457.53  5516.8  458.49
  5806.1  461.72  5943.1  465.51  6052.9  467.12  6177.3  470.91  6219.4  471.15
#Mann= 3 ,-1 , 0
  4158.8     .05       0  4966.3     .04       0    4978     .05       0
Bank Sta=4966.3,4978
XS Rating Curve= 0 ,0
Exp/Cntr=0.3,0.1

Type RM Length L Ch R = 1 ,22483   ,436,436,436
BEGIN DESCRIPTION:
Mapping XS 3f8da92a
END DESCRIPTION:
XS GIS Cut Line= 3
      2746441.97      6916965.68      2745843.02      6917252.14
      2744926.35       6918293.8
#Sta/Elev= 30
  4316.2   489.7  4378.2  486.88  4407.8  483.03    4504  475.21  4543.8  469.98
  4600.3  466.47  4640.1  462.28  4781.7  457.89    4895  456.22  4954.7  452.26
  4963.1  450.68  4968.6  446.02  4980.1  446.83  4999.4  445.45    5001  444.95
  5011.2  445.45  5019.3  448.34  5026.9  452.96  5033.6  453.19  5076.3   452.1
    5211  452.52  5366.6  456.52  5579.1  454.95  5664.5  456.93  5764.1  456.62
  5827.7  459.52  6040.2  459.25  6217.4  463.13  6309.6  468.93  6367.7  470.55
#Mann= 3 ,-1 , 0
  4316.2     .05       0  4999.4     .04       0  5011.2     .05       0
Bank Sta=4999.4,5011.2
XS Rating Curve= 0 ,0
Exp/Cntr=0.3,0.1

Type RM Length L Ch R = 1 ,22047   ,246,246,246
BEGIN DESCRIPTION:
Mapping XS e2eaca34
END DESCRIPTION:
XS GIS Cut Line= 3
      2746410.69      6916746.94      2745447.18      6917121.93
      2744707.89      6918246.48
#Sta/Elev= 30
  3958.7   489.3  4036.1  487.67  4135.4  481.94  4174.8  476.48    4289   470.9
  4392.4  468.93  4457.5  462.71  4566.3  457.66  4822.2  451.83  4922.6  452.43
  4983.1   451.1  5000.7  448.25  5006.7  449.65  5015.8  444.68  5017.5  444.18
  5027.6  444.68  5036.8  445.35  5051.3  452.75  5087.2  451.33  5130.2  453.13
  5187.4  451.36  5295.9  453.07  5326.1  451.92  5398.4  453.72  5461.6  453.21
    5549  456.92  5613.8  455.65  5931.6  459.01  6097.3  463.25  6338.4   472.1
#Mann= 3 ,-1 , 0
  3958.7     .05       0  5015.8     .04       0  5027.6     .05       0
Bank Sta=5015.8,5027.6
XS Rating Curve= 0 ,0
Exp/Cntr=0.3,0.1