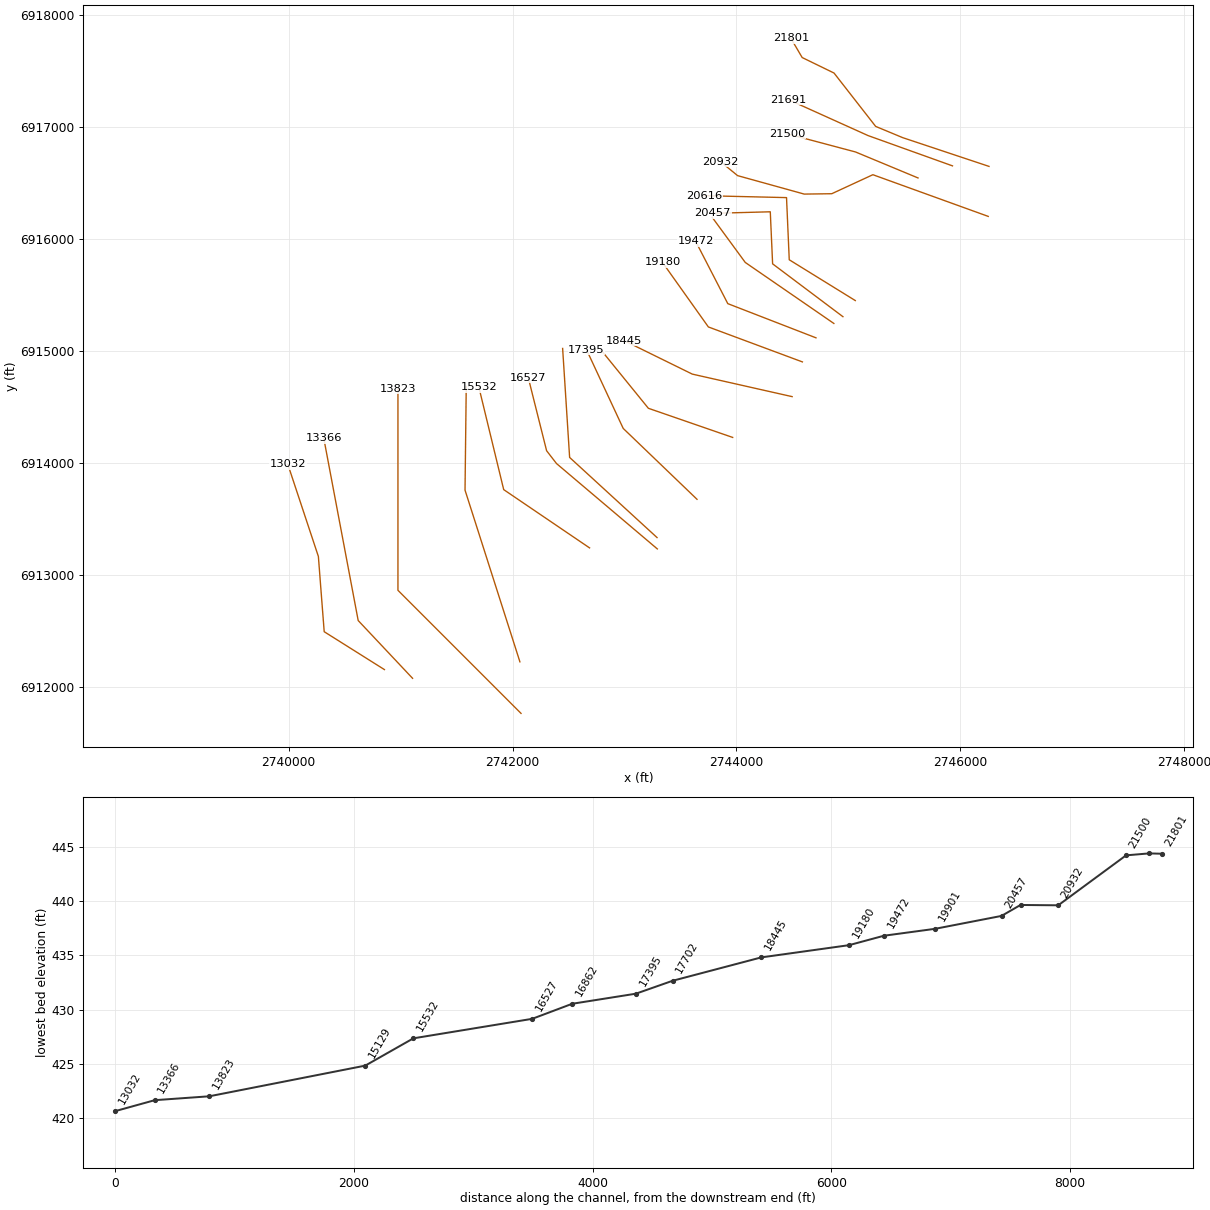
HEC-RAS study Flat Creek.prj: Flat Creek Base Level Engineering

--- Flat Creek.g01 (geometry) --- (continued)

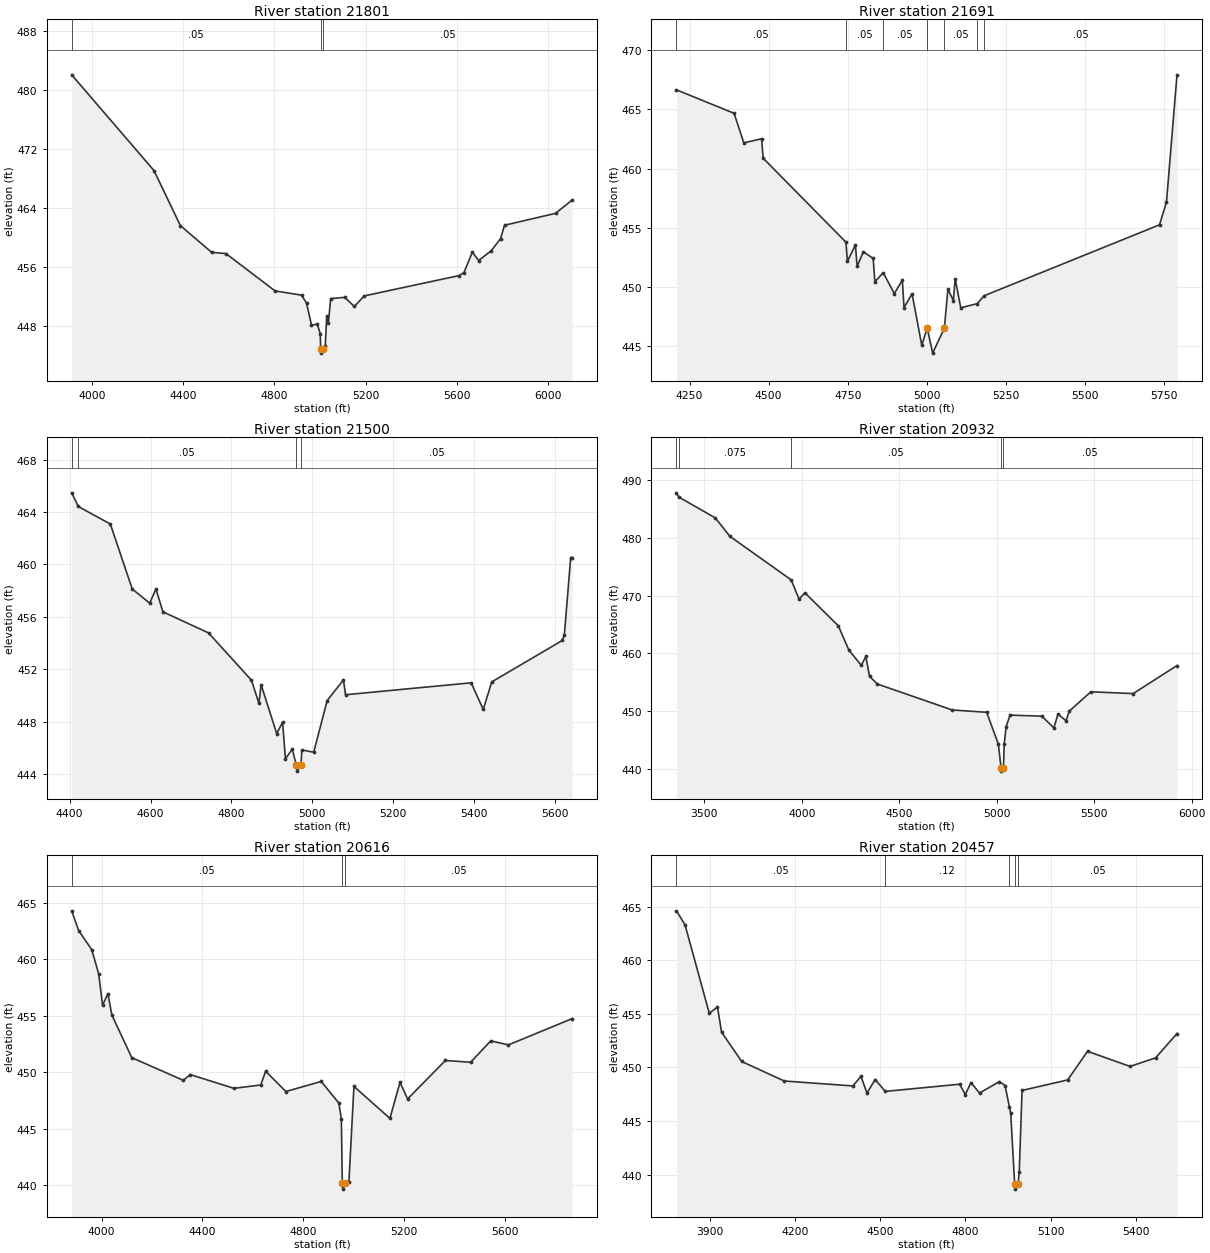
Type RM Length L Ch R = 1 ,21801   ,110,110,110
BEGIN DESCRIPTION:
Mapping XS fafb2c8b
END DESCRIPTION:
XS GIS Cut Line= 6
       2746258.8      6916649.69       2745487.6      6916906.49
      2745245.55      6917007.18      2744873.55      6917484.02
      2744588.83      6917622.65        2744488.      6917794.24
#Sta/Elev= 30
  3909.7  482.03    4271  469.08  4386.9  461.63    4524  458.02  4587.2  457.84
  4802.4   452.8  4919.2  452.22  4940.9  451.12  4962.5  448.16  4987.7  448.31
    5001  447.02  5002.8  444.88  5004.5  444.38  5014.6  444.88    5023  445.41
  5029.6  449.45  5036.8  448.51  5046.8  451.76  5108.3  451.92  5150.8  450.69
  5193.8  452.12  5610.2  454.87  5631.8  455.28  5668.5  458.03  5696.7  456.91
  5752.3  458.26  5792.4  459.86  5809.9  461.68  6033.9  463.29  6107.2   465.1
#Mann= 3 ,-1 , 0
  3909.7     .05       0  5002.8     .04       0  5014.6     .05       0
Bank Sta=5002.8,5014.6
XS Rating Curve= 0 ,0
Exp/Cntr=0.3,0.1

Type RM Length L Ch R = 1 ,21691   ,191,191,191
BEGIN DESCRIPTION:
Mapping XS 7e2d702f
END DESCRIPTION:
XS GIS Cut Line= 3
      2745932.26      6916654.38      2745177.35      6916925.23
       2744465.6      6917246.45
#Sta/Elev= 30
  4208.4  466.65  4390.6  464.67  4421.4  462.17  4477.5  462.52  4482.8  460.87
  4744.4  453.78  4748.9  452.16  4774.3  453.55  4779.6  451.73  4799.4  452.97
  4830.5  452.41  4835.8  450.44  4862.2   451.2  4897.3  449.44  4922.7  450.58
    4928  448.26  4953.5  449.42  4984.2  445.06  5001.2  446.54  5018.6  444.41
  5055.6  446.52  5066.8  449.81  5084.2  448.85  5089.7   450.7  5107.4  448.24
  5159.3  448.59  5181.6  449.26    5736  455.25    5758  457.17  5791.3  467.92
#Mann= 7 ,-1 , 0
  4208.4     .05       0  4744.4     .05       0  4862.2     .05       0
  5001.2     .04       0  5055.6     .05       0  5159.3     .05       0
  5181.6     .05       0
Bank Sta=5001.2,5055.6
XS Rating Curve= 0 ,0
Exp/Cntr=0.3,0.1

Type RM Length L Ch R = 1 ,21500   ,568,568,568
BEGIN DESCRIPTION:
Mapping XS 06c754c2
END DESCRIPTION:
XS GIS Cut Line= 3
       2745624.3      6916546.32      2745065.76      6916778.59
      2744453.65       6916941.4
#Sta/Elev= 30
    4405  465.47  4421.1  464.43  4500.6  463.09  4554.8  458.13  4598.1  457.05
  4613.4  458.14  4630.6  456.39  4743.5  454.78  4849.7  451.17  4868.2   449.4
  4873.6  450.83  4912.2  447.09  4926.7  447.96  4933.8  445.17  4950.6  445.91
  4960.4  444.73    4962  444.23  4972.3  444.73  4974.4  445.85  5003.7  445.67
  5037.1  449.62  5077.3  451.19  5082.4  450.06  5393.3  450.97  5423.1  448.94
  5444.3  451.04  5618.6   454.2  5623.8  454.62  5639.5  460.53  5643.3  460.53
#Mann= 4 ,-1 , 0
    4405    .075       0  4421.1     .05       0  4960.4     .04       0
  4972.3     .05       0
Bank Sta=4960.4,4972.3
XS Rating Curve= 0 ,0
Exp/Cntr=0.3,0.1

Type RM Length L Ch R = 1 ,20932   ,316,316,316
BEGIN DESCRIPTION:
Mapping XS 800184d0
END DESCRIPTION:
XS GIS Cut Line= 6
        2746252.      6916202.71      2745220.75      6916575.37
      2744853.28      6916405.48      2744607.13      6916402.17
      2744011.77      6916567.13      2743857.07      6916693.29
#Sta/Elev= 30
  3356.6  487.82  3368.5  487.09  3555.7  483.48  3630.7  480.29  3945.3  472.74
  3985.5  469.42  4016.1  470.49  4187.4  464.77  4240.9   460.6  4305.2  457.93
  4328.2  459.49  4347.1  456.04  4387.9   454.7  4771.5  450.21  4948.3  449.81
  5008.3  444.29  5022.4  440.12    5024  439.62  5034.3  440.12  5038.3  444.31
  5048.3  447.34  5068.4  449.32  5231.5  449.14  5293.1  447.11  5314.1   449.5
  5355.6  448.34  5371.9  450.01    5483  453.36    5700  453.05  5924.9  457.91
#Mann= 5 ,-1 , 0
  3356.6     .05       0  3368.5    .075       0  3945.3     .05       0
  5022.4     .04       0  5034.3     .05       0
Bank Sta=5022.4,5034.3
XS Rating Curve= 0 ,0
Exp/Cntr=0.3,0.1

Type RM Length L Ch R = 1 ,20616   ,159,159,159
BEGIN DESCRIPTION:
Mapping XS 0eea6e31
END DESCRIPTION:
XS GIS Cut Line= 4
      2745063.51      6915450.58      2744473.27      6915815.14
      2744448.96      6916370.69      2743712.81      6916388.05
#Sta/Elev= 30
  3881.6  464.31  3909.5  462.55  3960.9  460.88  3988.7  458.73  4004.1  455.95
  4025.4  456.97  4040.8  455.09    4120   451.3  4324.5  449.29  4351.7   449.8
  4525.5  448.58  4631.8  448.88  4651.3   450.1  4731.4   448.3  4871.5  449.19
  4941.6  447.28  4951.6  445.87  4955.5  440.15  4957.2  439.65  4967.6  440.15
  4981.6  440.29  5001.6  448.75  5144.4  445.92  5184.4  449.11  5214.4  447.64
  5364.5  451.05  5464.5  450.89  5544.5  452.79  5614.5  452.43  5867.8  454.76
#Mann= 3 ,-1 , 0
  3881.6     .05       0  4955.5     .03       0  4967.6     .05       0
Bank Sta=4955.5,4967.6
XS Rating Curve= 0 ,0
Exp/Cntr=0.3,0.1

Type RM Length L Ch R = 1 ,20457   ,556,556,556
BEGIN DESCRIPTION:
Mapping XS db79695d
END DESCRIPTION:
XS GIS Cut Line= 4
      2744953.17      6915306.43      2744324.66      6915778.68
      2744303.82      6916243.96      2743790.51      6916230.08
#Sta/Elev= 30
  3780.7  464.61  3810.9   463.3  3896.3  455.06  3925.4  455.63  3939.8  453.29
  4010.8  450.55  4160.8  448.73  4402.6  448.27  4431.5  449.16  4452.6   447.6
  4481.5  448.87  4517.1  447.76  4779.4  448.43  4799.4  447.47  4819.4  448.58
  4849.5  447.61  4919.5  448.67  4939.6  448.31  4954.6  446.35  4959.6  445.72
  4973.5  439.14  4975.2  438.64  4985.6  439.14  4989.6  440.21  4999.6  447.85
  5160.5  448.83  5230.5   451.5  5380.6  450.09  5470.6  450.89  5546.1  453.16
#Mann= 5 ,-1 , 0
  3780.7     .05       0  4517.1     .12       0  4954.6     .05       0
  4973.5     .05       0  4985.6     .05       0
Bank Sta=4973.5,4985.6
XS Rating Curve= 0 ,0
Exp/Cntr=0.3,0.1

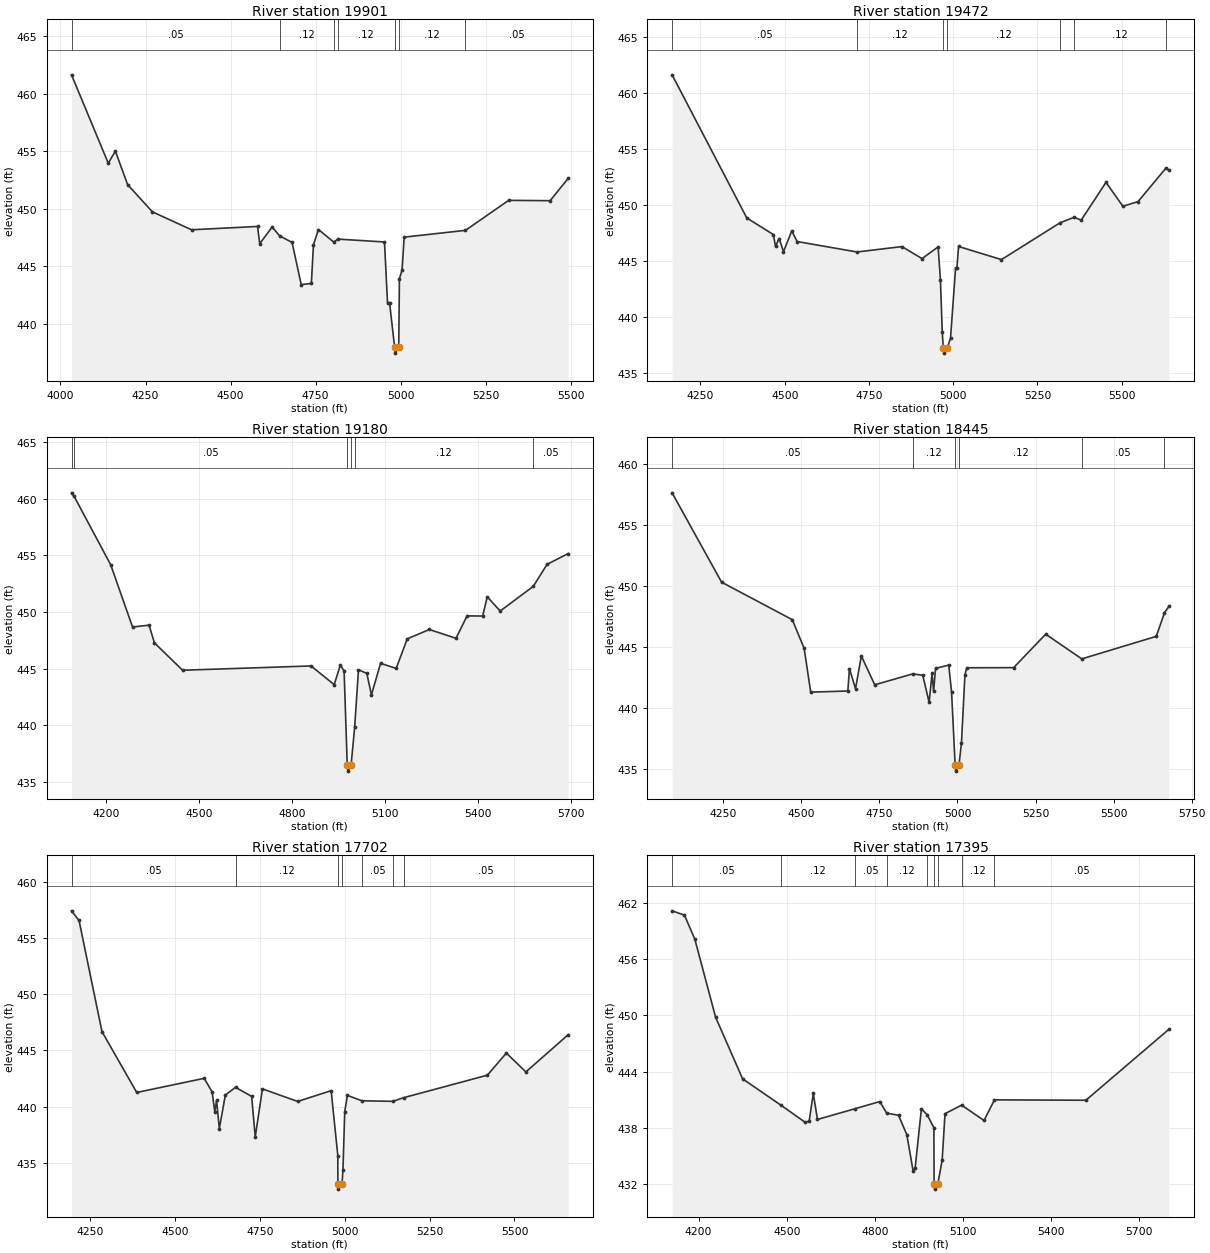
Type RM Length L Ch R = 1 ,19901   ,429,429,429
BEGIN DESCRIPTION:
Mapping XS 628aa912
END DESCRIPTION:
XS GIS Cut Line= 3
       2744871.9      6915246.02      2744080.21      6915791.18
      2743785.06      6916193.98
#Sta/Elev= 30
  4032.4  461.66  4140.5  453.97  4161.4  455.02  4197.4  452.11  4270.3  449.74
  4385.3  448.18  4579.4  448.47  4585.9  446.97  4622.4  448.42    4644  447.66
  4680.9  447.08  4707.9  443.41  4737.7  443.51  4743.8  446.87  4758.6   448.2
  4803.5  447.11  4815.5  447.37  4952.7  447.12  4961.6  441.84  4967.6  441.84
  4982.5  437.95  4984.2  437.45  4994.6  437.95  4996.6  443.93  5004.4  444.68
  5010.6  447.54  5190.8  448.13  5317.8  450.74  5439.7  450.71    5493  452.66
#Mann= 7 ,-1 , 0
  4032.4     .05       0    4644     .12       0  4803.5     .05       0
  4815.5     .12       0  4982.5     .07       0  4994.6     .12       0
  5190.8     .05       0
Bank Sta=4982.5,4994.6
XS Rating Curve= 0 ,0
Exp/Cntr=0.3,0.1

Type RM Length L Ch R = 1 ,19472   ,292,292,292
BEGIN DESCRIPTION:
Mapping XS 9d385d8f
END DESCRIPTION:
XS GIS Cut Line= 3
      2744712.12      6915117.58      2743923.96      6915423.12
      2743635.75      6915982.19
#Sta/Elev= 30
  4165.8   461.6  4387.5  448.85  4466.5  447.37  4472.7  446.31  4483.4  447.02
  4496.4  445.85    4521  447.69    4537  446.75  4714.5  445.82  4847.9   446.3
  4907.7  445.23  4955.3  446.27  4962.2  443.34  4967.6  438.67  4970.7  437.31
  4972.4  436.81  4982.8  437.31  4992.1  438.13  5007.3  444.42  5011.1  444.42
    5016  446.31  5143.3  445.14  5317.2  448.42    5359  448.91    5380  448.66
  5453.6  452.02  5503.8  449.89  5548.8  450.31  5631.5  453.29  5640.1  453.13
#Mann= 7 ,-1 , 0
  4165.8     .05       0  4714.5     .12       0  4970.7     .07       0
  4982.8     .12       0  5317.2     .05       0    5359     .12       0
  5631.5     .05       0
Bank Sta=4970.7,4982.8
XS Rating Curve= 0 ,0
Exp/Cntr=0.3,0.1

Type RM Length L Ch R = 1 ,19180   ,735,735,735
BEGIN DESCRIPTION:
Mapping XS b893b7bb
END DESCRIPTION:
XS GIS Cut Line= 3
      2744590.67      6914902.28      2743750.35      6915214.79
      2743340.82      6915790.92
#Sta/Elev= 30
  4088.5  460.52  4097.2   460.2  4215.1  454.16  4285.5  448.67  4338.9  448.83
  4356.1  447.27  4447.2  444.85  4861.7  445.23  4936.4  443.58  4956.1  445.29
  4968.4  444.79  4978.6  436.44  4980.3  435.94  4990.8  436.44  5002.5  439.81
  5014.8  444.89  5041.8  444.57  5056.6  442.67  5086.1  445.46  5136.5  445.01
  5172.2  447.62  5243.5  448.45  5329.6  447.67  5365.3  449.65  5415.7  449.64
  5430.5  451.34  5472.2  450.08  5579.1  452.26  5623.5   454.2  5691.9  455.16
#Mann= 6 ,-1 , 0
  4088.5     .12       0  4097.2     .05       0  4978.6     .05       0
  4990.8     .05       0  5002.5     .12       0  5579.1     .05       0
Bank Sta=4978.6,4990.8
XS Rating Curve= 0 ,0
Exp/Cntr=0.3,0.1

Type RM Length L Ch R = 1 ,18445   ,743,743,743
BEGIN DESCRIPTION:
Mapping XS 8ef3a202
END DESCRIPTION:
XS GIS Cut Line= 3
      2744499.01      6914591.86       2743606.6      6914793.26
      2742999.95      6915091.39
#Sta/Elev= 30
  4086.1  457.67  4244.6  450.33    4471  447.25    4509  444.89    4530   441.3
  4648.9  441.39  4654.1  443.23  4673.5  441.58  4692.2  444.27    4735   441.9
    4857   442.8  4888.8  442.68  4909.3  440.45  4918.5  442.86  4923.6  441.37
  4929.8  443.25    4972  443.52  4981.1   441.3  4992.6  435.31  4994.3  434.81
  5004.8  435.31  5012.8  437.14  5023.9  442.72  5029.7   443.3  5179.9  443.31
  5282.5  446.06  5398.1  444.03  5636.6  445.88  5662.7   447.8  5676.9  448.34
#Mann= 6 ,-1 , 0
  4086.1     .05       0    4857     .12       0  4992.6     .07       0
  5004.8     .12       0  5398.1     .05       0  5662.7     .12       0
Bank Sta=4992.6,5004.8
XS Rating Curve= 0 ,0
Exp/Cntr=0.3,0.1

Type RM Length L Ch R = 1 ,17702   ,307,307,307
BEGIN DESCRIPTION:
Mapping XS 7e84e1d2
END DESCRIPTION:
XS GIS Cut Line= 3
       2743967.7       6914227.3      2743214.24      6914487.71
      2742794.07       6915005.1
#Sta/Elev= 30
  4194.8  457.44    4217  456.58  4284.6  446.68    4387  441.26  4585.8  442.52
  4609.2   441.3    4617  439.54  4622.3  440.56  4630.4  438.04  4648.1  441.03
  4678.1  441.72  4725.6  440.91  4736.2   437.3  4757.4  441.58  4861.1  440.46
  4959.9  441.42  4979.5  435.64  4979.7  433.15  4981.4  432.65    4992  433.15
  4994.6  434.31  4999.9  439.55  5007.8     441  5050.4  440.52  5141.8  440.47
  5174.1   440.8  5420.2   442.8  5476.2  444.77  5533.7  443.09  5658.5  446.41
#Mann= 7 ,-1 , 0
  4194.8     .05       0  4678.1     .12       0  4979.7     .07       0
    4992     .12       0  5050.4     .05       0  5141.8     .12       0
  5174.1     .05       0
Bank Sta=4979.7,4992
XS Rating Curve= 0 ,0
Exp/Cntr=0.3,0.1

Type RM Length L Ch R = 1 ,17395   ,533,533,533
BEGIN DESCRIPTION:
Mapping XS cb6be221
END DESCRIPTION:
XS GIS Cut Line= 3
      2743648.83      6913674.35      2742989.13      6914308.02
      2742661.42      6915011.17
#Sta/Elev= 30
  4109.9  461.14    4152  460.68  4187.3  458.11    4258  449.79  4349.9  443.22
  4480.9   440.4  4562.1   438.6  4576.3   438.7  4590.4  441.66  4604.6  438.89
    4734  440.05  4816.8   440.8  4840.1  439.56  4880.4  439.34  4908.7  437.27
    4930  433.42    4937   433.7  4958.3  440.01    4978   439.4  5000.8     438
  5001.6  431.96  5003.3  431.46  5013.9  431.96    5029  434.56  5038.7  439.51
  5095.3  440.42  5171.4  438.78    5207  440.98  5518.1  440.94  5800.4   448.5
#Mann= 9 ,-1 , 0
  4109.9     .05       0  4480.9     .12       0    4734     .05       0
  4840.1     .12       0    4978     .12       0  5001.6     .07       0
  5013.9     .12       0  5095.3     .12       0    5207     .05       0
Bank Sta=5001.6,5013.9
XS Rating Curve= 0 ,0
Exp/Cntr=0.3,0.1

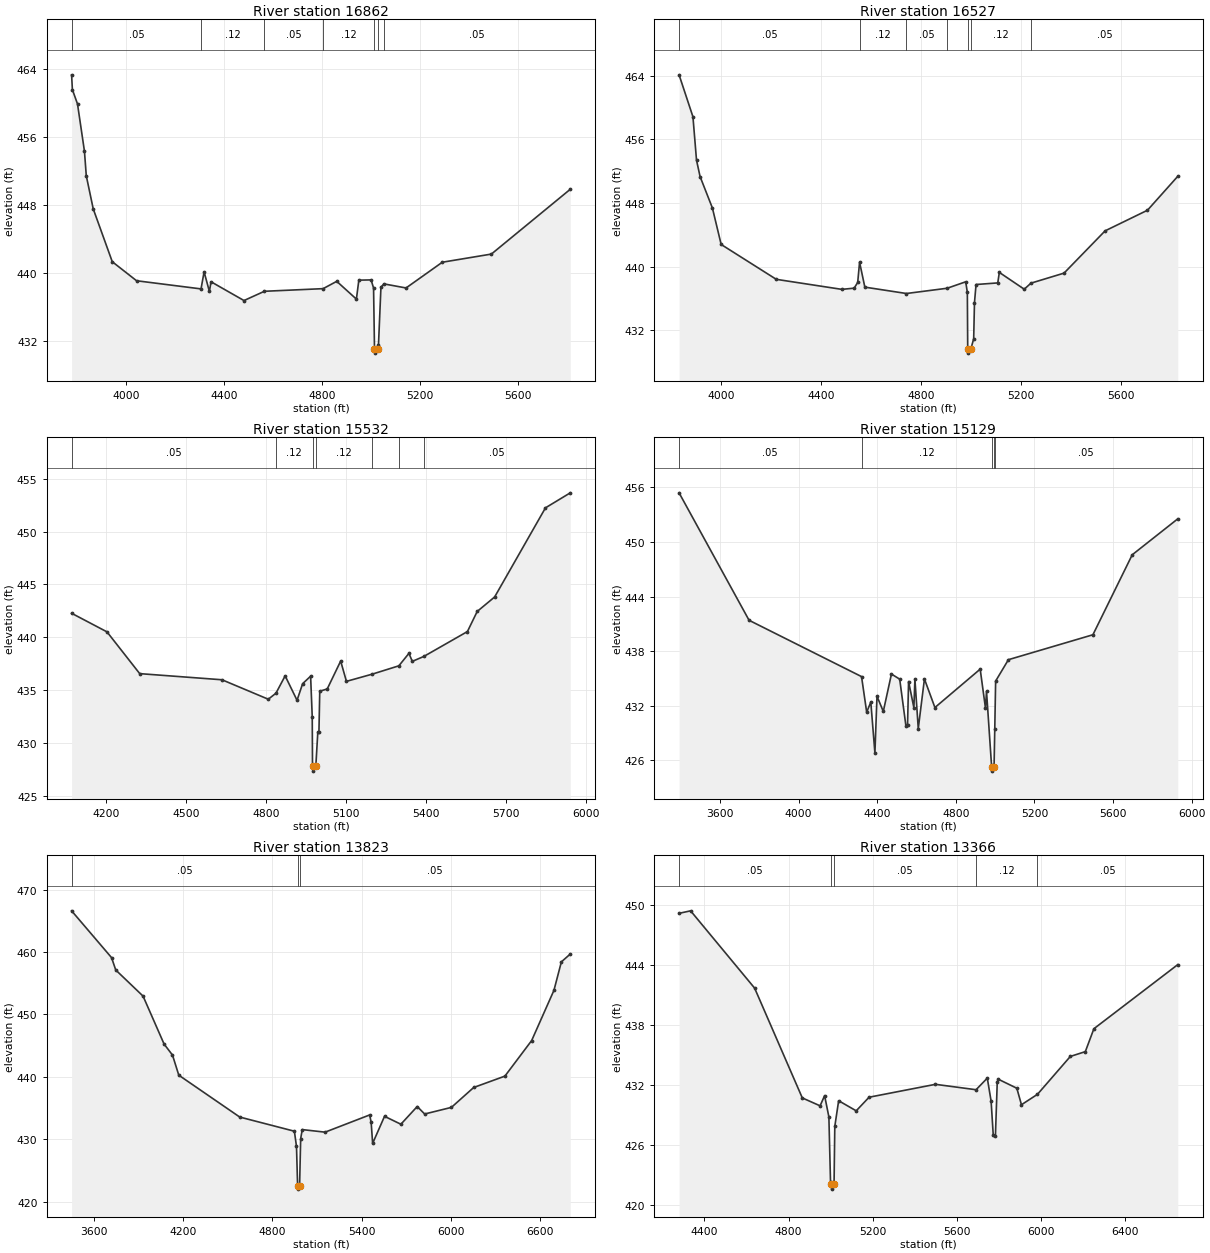
Type RM Length L Ch R = 1 ,16862   ,335,335,335
BEGIN DESCRIPTION:
Mapping XS d1ef0404
END DESCRIPTION:
XS GIS Cut Line= 3
      2743291.66      6913332.31      2742510.39      6914048.47
      2742447.89      6915022.43
#Sta/Elev= 30
  3777.3  463.29  3780.5  461.55  3801.4  459.86  3829.8  454.29  3837.2  451.41
  3865.6  447.51  3943.3  441.29  4042.5  439.05  4305.7  438.09  4318.2   440.1
  4339.8  437.79  4346.5  438.93    4481  436.72  4564.4  437.81    4804  438.12
  4859.7  438.98  4939.9  436.89  4949.9  439.12    5000  439.15    5010  438.19
  5013.8  431.03  5015.6  430.53  5026.2  431.03  5030.1  431.51  5040.1  438.28
  5052.3  438.68  5142.6   438.2  5290.6  441.23    5491  442.19  5813.1  449.82
#Mann= 7 ,-1 , 0
  3777.3     .05       0  4305.7     .12       0  4564.4     .05       0
    4804     .12       0  5013.8     .07       0  5026.2     .12       0
  5052.3     .05       0
Bank Sta=5013.8,5026.2
XS Rating Curve= 0 ,0
Exp/Cntr=0.3,0.1

Type RM Length L Ch R = 1 ,16527   ,995,995,995
BEGIN DESCRIPTION:
Mapping XS ad2acab2
END DESCRIPTION:
XS GIS Cut Line= 4
      2743294.25      6913230.76       2742393.2      6913993.78
      2742304.66      6914108.37       2742140.8       6914761.2
#Sta/Elev= 30
  3830.9   464.1  3886.5  458.83  3900.8  453.38  3915.1  451.32  3964.5  447.37
  3999.6  442.79  4220.5  438.41  4483.1  437.15  4532.5   437.3  4546.8  438.02
  4554.3  440.56  4575.4  437.43  4742.1  436.63  4905.3  437.29  4979.6   438.1
  4986.2  436.77  4987.7  429.64  4989.5  429.14  5000.1  429.64  5011.6  430.94
  5014.8  435.48  5021.1  437.76  5108.1  437.96  5114.4  439.28  5214.2  437.17
  5241.2  437.93  5373.7  439.19  5538.3   444.5  5708.1  447.09  5829.5  451.35
#Mann= 7 ,-1 , 0
  3830.9     .05       0  4554.3     .12       0  4742.1     .05       0
  4905.3     .12       0  4987.7     .07       0  5000.1     .12       0
  5241.2     .05       0
Bank Sta=4987.7,5000.1
XS Rating Curve= 0 ,0
Exp/Cntr=0.3,0.1

Type RM Length L Ch R = 1 ,15532   ,403,403,403
BEGIN DESCRIPTION:
Mapping XS 253c94f4
END DESCRIPTION:
XS GIS Cut Line= 3
      2742688.55      6913239.97      2741921.16      6913760.82
      2741699.12      6914676.74
#Sta/Elev= 30
  4070.6  442.27  4203.3  440.51    4326  436.56  4634.5  435.98  4808.1  434.14
  4836.9  434.71  4871.3  436.35  4915.9  434.04  4936.9  435.61  4966.8  436.32
  4972.9  432.47  4973.9  427.84  4975.6  427.34  4986.4  427.84  4993.8  431.03
    4998  431.03  5001.1   434.9  5029.1  435.11  5079.5  437.75  5101.1  435.83
  5197.6  436.51  5297.7   437.3  5335.5  438.48  5348.1  437.72  5391.6  438.19
  5554.8  440.54  5591.4  442.44  5656.8  443.81  5847.4  452.24  5940.5  453.66
#Mann= 7 ,-1 , 0
  4070.6     .05       0  4836.9     .12       0  4973.9     .07       0
  4986.4     .12       0  5197.6     .05       0  5297.7     .12       0
  5391.6     .05       0
Bank Sta=4973.9,4986.4
XS Rating Curve= 0 ,0
Exp/Cntr=0.3,0.1

Type RM Length L Ch R = 1 ,15129   ,1306,1306,1306
BEGIN DESCRIPTION:
Mapping XS 6421adc5
END DESCRIPTION:
XS GIS Cut Line= 3
      2742065.99      6912221.73      2741575.53      6913756.04
      2741586.38      6914682.69
#Sta/Elev= 30
    3392  455.41  3748.2   441.4  4320.5  435.21  4346.6   431.3  4367.6  432.41
  4388.5  426.81  4399.1  433.05  4431.2  431.38  4472.6  435.49  4514.6  434.93
  4546.1  429.82  4554.6  429.93  4559.8  434.67  4586.8  431.79    4592  434.93
  4609.1   429.5  4640.5  434.95  4693.8  431.81  4924.2  436.03  4951.1  431.74
  4956.4  433.59  4982.3  425.32    4984  424.82  4994.8  425.32  4998.4  429.48
  5002.8  434.72  5067.8  437.07  5497.8  439.81  5697.8   448.6  5929.5  452.55
#Mann= 5 ,-1 , 0
    3392     .05       0  4320.5     .12       0  4982.3     .05       0
  4994.8     .12       0  4998.4     .05       0
Bank Sta=4982.3,4994.8
XS Rating Curve= 0 ,0
Exp/Cntr=0.3,0.1

Type RM Length L Ch R = 1 ,13823   ,457,457,457
BEGIN DESCRIPTION:
Flat Creek 17.0
END DESCRIPTION:
XS GIS Cut Line= 3
      2742076.04      6911760.96        2740976.        6912861.
        2740976.      6914661.02
#Sta/Elev= 30
  3448.6  466.59  3717.4  459.09  3745.6  457.11  3929.5  452.92  4070.9  445.24
  4127.5  443.47  4169.9  440.25    4580  433.54  4947.7  431.27  4961.9  428.83
  4969.4  422.49  4971.3  421.99  4982.7  422.49  4990.1  430.09  5000.7  431.53
  5154.3  431.12  5454.3  433.88  5464.3  432.69  5474.3  429.32  5554.3  433.66
  5664.3  432.39  5774.3  435.23  5824.3  434.03  6004.3  435.09  6154.3  438.28
  6364.3   440.1  6544.3   445.8  6694.3  453.85  6744.3  458.41  6804.3  459.67
#Mann= 3 ,-1 , 0
  3448.6     .05       0  4969.4     .04       0  4982.7     .05       0
Bank Sta=4969.4,4982.7
XS Rating Curve= 0 ,0
Exp/Cntr=0.3,0.1

Type RM Length L Ch R = 1 ,13366   ,334,334,334
BEGIN DESCRIPTION:
Mapping XS 332a337c
END DESCRIPTION:
XS GIS Cut Line= 3
      2741106.79      6912074.17      2740620.67      6912590.68
      2740312.51      6914222.65
#Sta/Elev= 30
  4279.7  449.21  4334.5  449.46  4638.8  441.73  4865.4  430.75  4949.9  429.96
  4971.4  430.98  4991.7  428.85  4999.5  422.33    5003  422.13  5004.9  421.63
  5016.3  422.13  5019.8   427.9  5038.1  430.47  5121.6  429.46  5182.7  430.82
  5498.2  432.11  5691.2  431.57  5744.6  432.73  5762.7  430.43  5772.9  427.02
  5783.1   426.9  5791.9  432.34    5797  432.62  5884.9  431.72  5906.9  430.07
    5983  431.11  6139.3   434.9  6210.5  435.38  6251.2  437.67  6649.8  444.08
#Mann= 5 ,-1 , 0
  4279.7     .05       0    5003     .04       0  5016.3     .05       0
  5691.2     .12       0    5983     .05       0
Bank Sta=5003,5016.3
XS Rating Curve= 0 ,0
Exp/Cntr=0.3,0.1

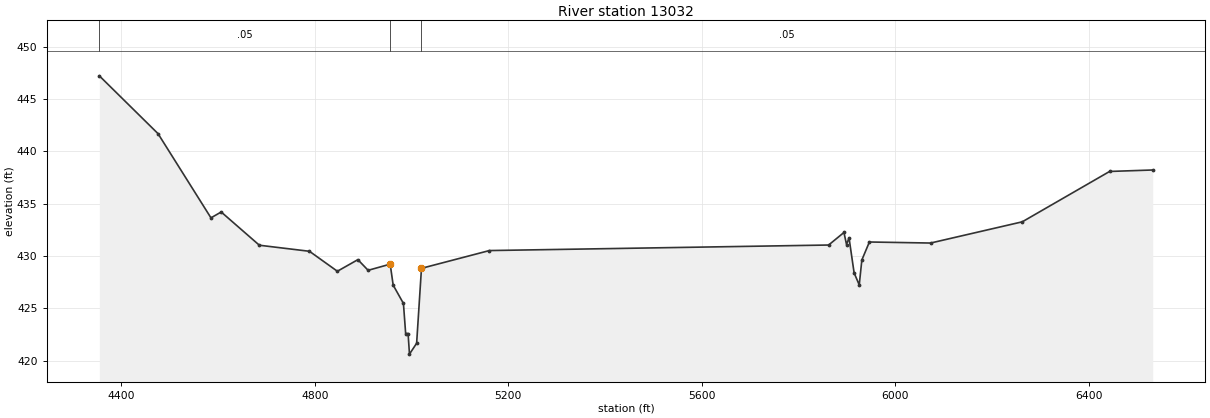
Type RM Length L Ch R = 1 ,13032   ,380,380,380
BEGIN DESCRIPTION:
Mapping XS 5bf91edd
END DESCRIPTION:
XS GIS Cut Line= 4
      2740855.08      6912152.29      2740316.85      6912490.85
      2740264.77       6913163.6      2739991.71       6913987.1
#Sta/Elev= 30
  4354.5  447.24  4475.8  441.71  4585.3  433.65  4606.5  434.21  4685.4  431.03
    4789  430.45  4846.7  428.54  4889.1  429.65  4910.3  428.63  4955.9  429.22
  4962.1  427.21  4983.3  425.46  4987.9  422.58  4992.9  422.58  4995.8  420.61
  5010.6  421.65  5020.6  428.82    5161  430.52  5862.5  431.05  5894.2  432.25
  5899.5   431.1  5904.7  431.73  5915.2  428.39  5925.8  427.23  5931.2  429.62
  5946.8  431.34  6073.3  431.24  6262.9  433.27  6443.5  438.09  6532.7  438.23
#Mann= 3 ,-1 , 0
  4354.5     .05       0  4955.9     .04       0  5020.6     .05       0
Bank Sta=4955.9,5020.6
XS Rating Curve= 0 ,0
Exp/Cntr=0.3,0.1