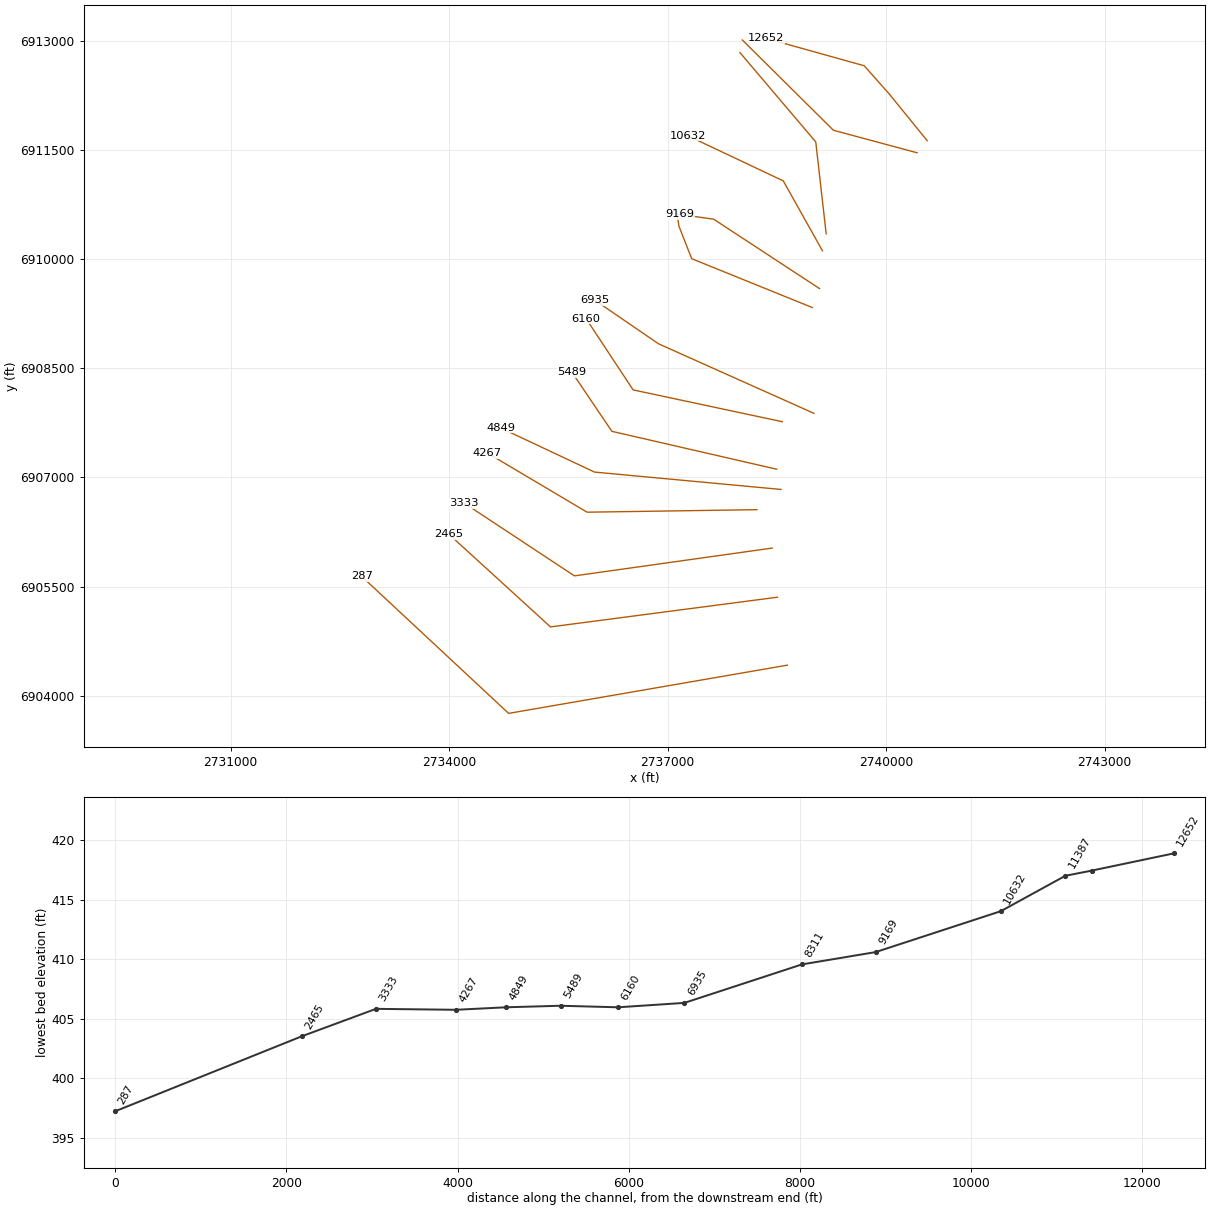
HEC-RAS study Flat Creek.prj: Flat Creek Base Level Engineering

--- Flat Creek.g01 (geometry) --- (continued)

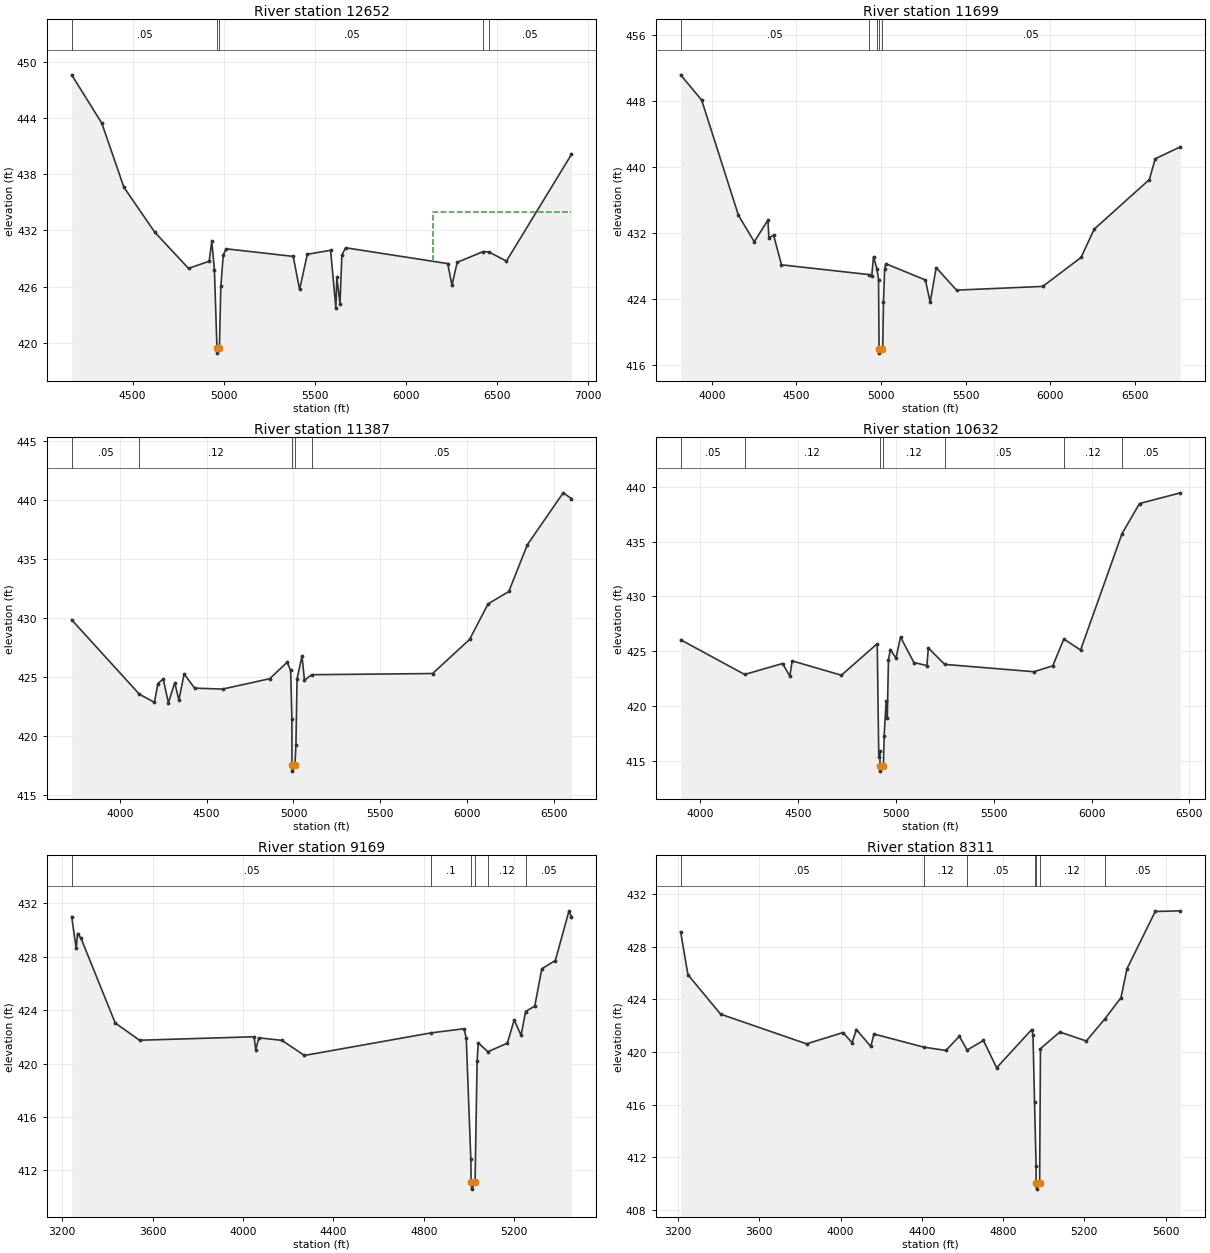
Type RM Length L Ch R = 1 ,12652   ,953,953,953
BEGIN DESCRIPTION:
Flat Creek 14.0
END DESCRIPTION:
XS GIS Cut Line= 4
      2740565.11      6911627.15      2740039.19      6912274.68
      2739700.53      6912656.36      2738351.59      6913033.38
#Sta/Elev= 30
  4165.8  448.59  4331.4  443.43  4452.8  436.59  4622.3   431.8  4807.6  427.94
  4921.1   428.7  4935.5  430.84  4949.9  427.77    4964   419.4  4965.9   418.9
  4977.3   419.4    4985  426.01  4998.6  429.36  5013.7  430.03  5382.6  429.22
  5417.7  425.69  5460.3  429.45    5588  429.87    5617  423.72  5622.2  427.01
  5639.6  424.17    5650  429.36  5670.7  430.14  6231.4  428.45  6254.6  426.14
  6283.3  428.59  6427.1  429.74  6457.2  429.69  6553.8  428.72  6910.9   440.1
#Mann= 5 ,-1 , 0
  4165.8     .05       0    4964     .04       0  4977.3     .05       0
  6427.1     .12       0  6457.2     .05       0
#XS Ineff= 2 , 0
       0                    6150       0     434
Permanent Ineff=
       F       F
Bank Sta=4964,4977.3
XS Rating Curve= 0 ,0
Exp/Cntr=0.3,0.1

Type RM Length L Ch R = 1 ,11699   ,312,312,312
BEGIN DESCRIPTION:
Flat Creek 13.0
END DESCRIPTION:
XS GIS Cut Line= 3
      2740425.97      6911461.01      2739277.15      6911770.48
      2738025.98      6913011.02
#Sta/Elev= 30
  3815.8  451.21    3940  448.15  4157.5  434.16  4250.7  430.97  4331.6   433.6
  4336.8  431.44  4364.7  431.77  4411.5  428.17  4926.2  426.99  4944.6  426.84
    4955  429.17  4975.4  427.66  4984.6  426.37  4987.8  417.96  4989.8  417.46
    5005  417.96  5009.5  418.09  5013.8  423.62  5020.9   427.7    5028   428.3
  5261.3  426.33  5289.6  423.64    5325  427.83  5445.1   425.1  5954.3  425.55
  6180.6  429.06  6258.4   432.5  6583.6   438.5    6619  441.03  6767.5  442.48
#Mann= 5 ,-1 , 0
  3815.8     .05       0  4926.2     .12       0  4975.4     .05       0
  4987.8     .05       0    5005     .05       0
Bank Sta=4987.8,5005
XS Rating Curve= 0 ,0
Exp/Cntr=0.3,0.1

Type RM Length L Ch R = 1 ,11387   ,755,755,755
BEGIN DESCRIPTION:
Flat Creek 11.0
END DESCRIPTION:
XS GIS Cut Line= 3
      2739178.08      6910347.05      2739034.85      6911610.12
      2737994.21      6912837.21
#Sta/Elev= 30
  3721.9  429.86  4112.5  423.54  4198.9  422.86    4219  424.45  4249.2  424.84
  4279.4  422.82  4315.9  424.52  4339.8  423.05    4370  425.27  4430.4  424.06
  4591.4  423.98  4863.1  424.86  4963.8  426.26  4983.9  425.56    4991  421.43
  4991.3  417.52  4993.3  417.02  5008.5  417.52  5014.2  419.24  5020.7  424.84
  5049.3  426.79  5063.6  424.73  5105.3   425.2  5801.8   425.3  6014.9  428.19
  6121.5  431.21  6241.1  432.26  6347.7  436.22  6554.3  440.63    6602  440.14
#Mann= 5 ,-1 , 0
  3721.9     .05       0  4112.5     .12       0  4991.3     .07       0
  5008.5     .12       0  5105.3     .05       0
Bank Sta=4991.3,5008.5
XS Rating Curve= 0 ,0
Exp/Cntr=0.3,0.1

Type RM Length L Ch R = 1 ,10632   ,1463,1463,1463
BEGIN DESCRIPTION:
Mapping XS 1ebdc0ed
END DESCRIPTION:
XS GIS Cut Line= 3
      2739127.17      6910113.57      2738588.97      6911074.75
      2737273.94      6911696.48
#Sta/Elev= 30
  3898.4  426.04  4225.7  422.87  4419.8  423.87    4457  422.72    4469  424.11
  4720.6   422.8    4904  425.68  4911.9  415.31  4917.6  415.89  4918.3  414.54
  4920.3  414.04  4935.5  414.54  4939.3  417.29  4949.5  420.45  4955.3  418.89
  4961.3  424.22  4971.2  425.14    5000  424.36  5023.1  426.29  5091.4  423.96
  5158.1  423.68  5165.2  425.29    5249  423.79  5705.2  423.12  5801.8  423.66
  5858.3  426.11  5943.9   425.1  6155.8  435.73  6245.3  438.48  6454.6  439.46
#Mann= 7 ,-1 , 0
  3898.4     .05       0  4225.7     .12       0  4918.3     .07       0
  4935.5     .12       0    5249     .05       0  5858.3     .12       0
  6155.8     .05       0
Bank Sta=4918.3,4935.5
XS Rating Curve= 0 ,0
Exp/Cntr=0.3,0.1

Type RM Length L Ch R = 1 ,9169    ,858,858,858
BEGIN DESCRIPTION:
Mapping XS 0c853ede
END DESCRIPTION:
XS GIS Cut Line= 3
      2739087.19      6909594.52       2737634.1      6910547.62
      2737165.35      6910615.33
#Sta/Elev= 30
  3241.9  431.01  3262.1  428.63    3268  429.74  3283.1  429.39  3434.7  423.04
  3542.3  421.75  4048.7  422.01  4056.6  421.04  4069.8  421.93  4172.3  421.74
  4271.8  420.61  4831.9   422.3  4978.2  422.61  4987.9  421.89  5008.1  412.83
  5009.5   411.1  5011.5   410.6  5026.8   411.1  5035.8  420.17  5040.9  421.55
  5083.7  420.89  5169.7  421.53    5200  423.27  5230.4  422.12  5250.4   423.9
    5291  424.31  5322.2   427.1  5381.9  427.72  5442.5  431.44  5453.3  430.97
#Mann= 6 ,-1 , 0
  3241.9     .05       0  4831.9      .1       0  5009.5     .07       0
  5026.8      .1       0  5083.7     .12       0  5250.4     .05       0
Bank Sta=5009.5,5026.8
XS Rating Curve= 0 ,0
Exp/Cntr=0.3,0.1

Type RM Length L Ch R = 1 ,8311    ,1376,1376,1376
BEGIN DESCRIPTION:
Mapping XS 614b8fea
END DESCRIPTION:
XS GIS Cut Line= 4
      2738988.27      6909334.08      2737331.32      6910005.44
      2737155.84      6910453.35      2737127.54       6910643.6
#Sta/Elev= 30
  3212.2  429.15  3248.2  425.88    3409  422.88  3832.4  420.62  4011.9  421.48
  4056.2  420.71  4077.8  421.71  4148.7  420.42  4164.1  421.37  4409.8  420.37
  4518.5  420.12  4584.9   421.2  4623.1  420.15  4703.4  420.88  4768.4   418.8
    4941  421.71  4947.3  421.33    4955  416.21  4962.6  411.34  4962.7  410.07
  4964.7  409.57  4980.1  410.07  4984.2  420.26  5079.4  421.52    5210  420.84
  5302.4  422.54  5380.6  424.13  5410.4  426.34  5549.4  430.69  5673.4  430.74
#Mann= 7 ,-1 , 0
  3212.2     .05       0  4409.8     .12       0  4623.1     .05       0
    4955     .12       0  4962.7     .07       0  4980.1     .12       0
  5302.4     .05       0
Bank Sta=4962.7,4980.1
XS Rating Curve= 0 ,0
Exp/Cntr=0.3,0.1

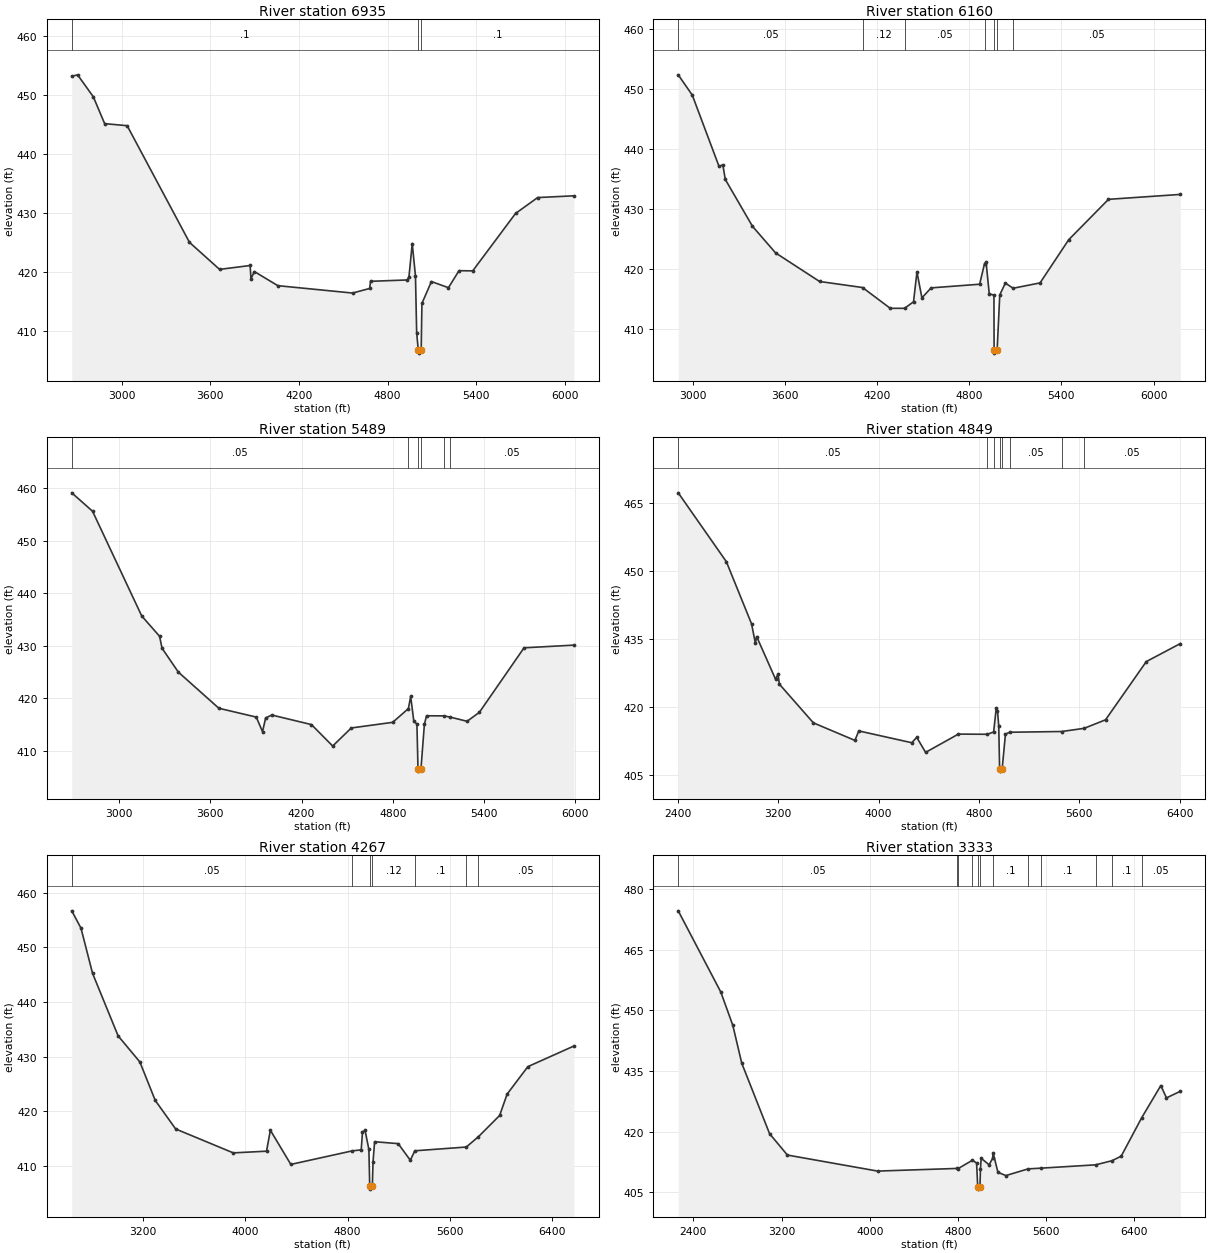
Type RM Length L Ch R = 1 ,6935    ,775,775,775
BEGIN DESCRIPTION:
Flat Creek 7.0
END DESCRIPTION:
XS GIS Cut Line= 3
      2739009.09      6907880.96      2736876.21      6908835.91
      2736000.98      6909436.01
#Sta/Elev= 30
  2663.1  453.24  2702.4  453.49  2808.9  449.77  2885.6  445.22    3038  444.87
  3459.7   425.1  3663.5  420.52  3870.4  421.18  3875.9  418.92    3899  420.15
    4058  417.76  4563.6  416.51  4679.5  417.29    4685   418.5  4934.5  418.73
  4945.4  419.29  4967.4   424.9  4989.3   419.4  4997.4  409.81  5008.3  406.83
  5010.3  406.33    5028  406.83    5033  414.76  5097.3  418.46  5212.4  417.42
  5284.1   420.3  5376.8  420.27  5666.6     430  5816.1  432.69  6061.2  432.99
#Mann= 3 ,-1 , 0
  2663.1      .1       0  5008.3     .07       0    5028      .1       0
Bank Sta=5008.3,5028
XS Rating Curve= 0 ,0
Exp/Cntr=0.3,0.1

Type RM Length L Ch R = 1 ,6160    ,671,671,671
BEGIN DESCRIPTION:
Mapping XS 3e86c279
END DESCRIPTION:
XS GIS Cut Line= 3
       2738575.5      6907765.51      2736526.89      6908203.01
      2735881.04       6909182.2
#Sta/Elev= 30
    2906  452.41  2997.5  449.02  3171.3  437.14  3196.3  437.38  3212.3  434.95
  3389.2  427.13  3539.5  422.69  3825.8  417.92  4105.6  416.91  4285.9  413.44
  4379.2  413.44  4437.4  414.53  4459.8  419.51    4492  415.18  4551.8  416.85
  4867.6  417.46  4899.6   420.9  4909.7  421.12  4930.1  415.89  4960.8  415.62
  4961.9  406.46  4963.9  405.96  4981.6  406.46  4998.7  415.67    5035  417.65
    5086  416.79  5260.9  417.68  5447.5  424.89  5706.4  431.63  6173.8  432.45
#Mann= 7 ,-1 , 0
    2906     .05       0  4105.6     .12       0  4379.2     .05       0
  4899.6     .12       0  4961.9     .07       0  4981.6     .12       0
    5086     .05       0
Bank Sta=4961.9,4981.6
XS Rating Curve= 0 ,0
Exp/Cntr=0.3,0.1

Type RM Length L Ch R = 1 ,5489    ,640,640,640
BEGIN DESCRIPTION:
Mapping XS 7546ce3f
END DESCRIPTION:
XS GIS Cut Line= 3
      2738499.12      6907112.73      2736235.23      6907633.56
      2735686.62      6908446.06
#Sta/Elev= 30
  2688.1  459.08  2824.7  455.58  3148.3  435.64  3265.9  431.76  3281.9   429.5
  3389.1  424.95  3655.9  418.06    3902  416.38  3943.2   413.6  3963.7  416.22
  4004.7  416.77  4265.1  414.95  4404.9  410.87  4527.2  414.31  4799.5  415.38
    4903     418    4918  420.32  4938.5  415.61    4959  415.05  4966.1  406.59
  4968.1  406.09  4985.8  406.59  5008.2  415.02  5022.4  416.63  5136.5  416.61
  5174.5   416.4  5289.2  415.58    5370  417.29  5663.8  429.57  5991.5  430.08
#Mann= 6 ,-1 , 0
  2688.1     .05       0    4903     .12       0  4966.1     .07       0
  4985.8     .12       0  5136.5      .1       0  5174.5     .05       0
Bank Sta=4966.1,4985.8
XS Rating Curve= 0 ,0
Exp/Cntr=0.3,0.1

Type RM Length L Ch R = 1 ,4849    ,582,582,582
BEGIN DESCRIPTION:
Mapping XS e0f128b1
END DESCRIPTION:
XS GIS Cut Line= 3
       2738557.7      6906834.95      2735996.94      6907073.67
      2734705.73      6907681.29
#Sta/Elev= 30
  2404.7  467.29  2788.1  452.11  2988.9   438.4  3019.1  434.15  3029.1  435.62
  3179.7  426.22  3199.8  427.34  3209.9  425.14    3481   416.6    3812  412.73
  3842.6  414.82  4264.4  412.22  4304.6   413.4  4374.9  410.09    4636  414.12
  4866.9  414.08  4916.8  414.59  4937.3  419.77  4947.4  419.27  4957.4  415.92
  4964.4  406.46  4966.4  405.96  4984.7  406.46  5010.9  414.12  5045.4  414.53
  5458.8  414.69  5637.5  415.39    5808  417.27  6132.7   430.1  6403.6  434.07
#Mann= 8 ,-1 , 0
  2404.7     .05       0  4866.9     .12       0  4916.8      .1       0
  4964.4     .07       0  4984.7      .1       0  5045.4     .05       0
  5458.8      .1       0  5637.5     .05       0
Bank Sta=4964.4,4984.7
XS Rating Curve= 0 ,0
Exp/Cntr=0.3,0.1

Type RM Length L Ch R = 1 ,4267    ,934,934,934
BEGIN DESCRIPTION:
Mapping XS d1fd4e0e
END DESCRIPTION:
XS GIS Cut Line= 3
      2738228.24      6906557.17      2735894.95      6906522.45
      2734526.89      6907334.95
#Sta/Elev= 30
  2644.1  456.65  2716.3  453.47  2806.4  445.23  3006.4  433.78  3176.4  429.01
  3296.4  421.98  3456.4  416.75  3906.5  412.38  4166.5  412.69  4196.5  416.52
  4356.5  410.27    4837  412.75  4906.6  412.93  4916.6  416.18  4936.6   416.5
  4966.6  413.02  4973.3  406.25  4975.3  405.75  4993.6  406.25    4999  410.71
  5011.3  414.42  5195.8  414.07  5290.5  411.03  5325.6  412.76  5728.2  413.45
    5823  415.34  5988.7  419.22  6047.2  423.13  6209.3  428.15  6568.8  431.92
#Mann= 7 ,-1 , 0
  2644.1     .05       0    4837     .12       0  4973.3     .07       0
  4993.6     .12       0  5325.6      .1       0  5728.2     .12       0
    5823     .05       0
Bank Sta=4973.3,4993.6
XS Rating Curve= 0 ,0
Exp/Cntr=0.3,0.1

Type RM Length L Ch R = 1 ,3333    ,868,868,868
BEGIN DESCRIPTION:
Mapping XS dcb1e61b
END DESCRIPTION:
XS GIS Cut Line= 3
      2738436.66       6906029.4      2735721.34      6905647.45
      2734208.53      6906646.73
#Sta/Elev= 30
  2262.6   474.6    2649  454.52  2758.1  446.27  2838.9  436.94  3091.3  419.53
  3252.9  414.25  4070.9  410.29  4788.3  410.94    4801  410.89  4932.3  412.98
  4969.6  412.27  4979.7  406.33  4981.7  405.83    5000  406.33  5004.7  410.89
    5011  413.45    5083  411.85  5114.7  413.42  5118.9  414.84  5163.1  409.99
  5235.3  409.18  5436.5  410.83  5552.4  411.01  6048.5  411.83  6196.3  412.84
  6281.4  413.97  6468.3  423.52    6641  431.43  6692.1  428.37  6817.7  430.01
#Mann= 12 ,-1 , 0
  2262.6     .05       0  4788.3      .1       0    4801     .05       0
  4932.3     .12       0  4979.7     .07       0    5000     .12       0
  5114.7      .1       0  5436.5     .12       0  5552.4      .1       0
  6048.5     .12       0  6196.3      .1       0  6468.3     .05       0
Bank Sta=4979.7,5000
XS Rating Curve= 0 ,0
Exp/Cntr=0.3,0.1

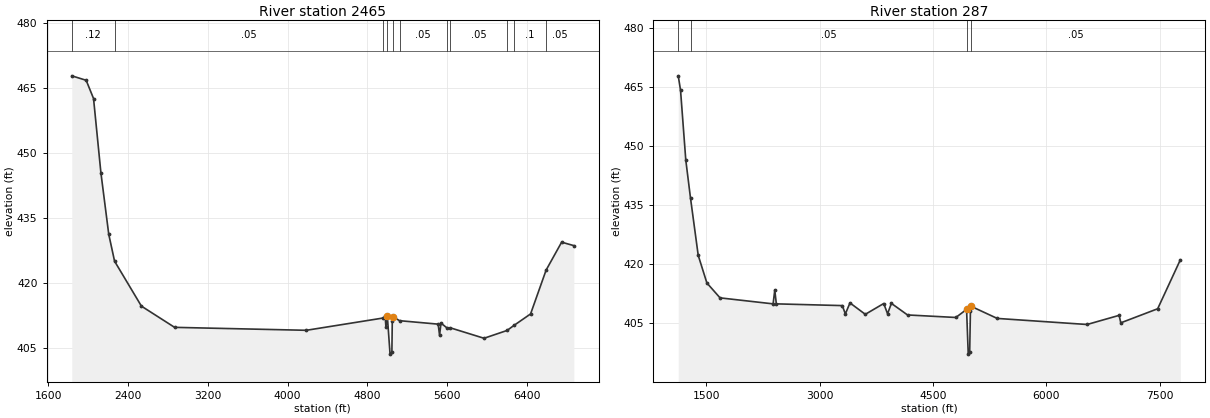
Type RM Length L Ch R = 1 ,2465    ,2178,2178,2178
BEGIN DESCRIPTION:
Mapping XS 1594e05b
END DESCRIPTION:
XS GIS Cut Line= 3
      2738508.53      6905354.19      2735392.24      6904946.21
      2733994.64      6906222.27
#Sta/Elev= 30
  1835.2  467.75  1979.6  466.72  2053.5  462.51  2127.3  445.39  2206.1  431.17
  2264.4  424.97  2533.6   414.6  2866.5   409.7  4187.6  409.02  4954.2  411.84
  4978.1  412.22  4986.2  409.72  5000.1  412.29  5027.4  403.52  5045.7  404.02
  5049.7  411.26  5056.5  412.16  5122.3  411.24  5509.8  410.44    5524  407.85
  5538.1  410.68  5598.7  409.56  5633.3  409.58  5969.9  407.18  6200.5  408.98
  6270.4  410.15  6436.7   412.8  6592.6  422.92  6748.2  429.36  6870.6  428.56
#Mann= 11 ,-1 , 0
  1835.2     .12       0  2264.4     .05       0  4954.2      .1       0
  5000.1     .05       0  5056.5      .1       0  5122.3     .05       0
  5598.7     .12       0  5633.3     .05       0  6200.5     .12       0
  6270.4      .1       0  6592.6     .05       0
Bank Sta=5000.1,5056.5
XS Rating Curve= 0 ,0
Exp/Cntr=0.3,0.1

Type RM Length L Ch R = 1 ,287     ,0,0,0
BEGIN DESCRIPTION:
Flat Creek 1.0
END DESCRIPTION:
XS GIS Cut Line= 3
      2738644.45      6904420.61      2734817.21      6903758.11
      2732800.86      6905639.16
#Sta/Elev= 30
  1129.4  467.76  1159.9  464.11  1229.3   446.4  1291.7  436.77  1393.8  422.25
  1508.3  415.26  1682.5  411.48  2384.4  409.96  2406.6  413.47  2426.9  409.96
  3299.7  409.52  3340.3  407.41  3401.1   410.2  3604.1  407.31  3847.7  410.05
  3898.4  407.45  3949.2  410.08  4162.3  407.15  4801.7  406.51  4943.7  408.55
  4965.7  397.22  4984.8  397.72  4994.5  408.06  5004.6  409.33    5349  406.27
  6537.6  404.73  6962.1  407.05  6983.6  405.15  7471.7  408.72  7771.1  421.11
#Mann= 4 ,-1 , 0
  1129.4     .12       0  1291.7     .05       0  4943.7     .04       0
  5004.6     .05       0
Bank Sta=4943.7,5004.6
XS Rating Curve= 0 ,0
Exp/Cntr=0.3,0.1

Chan Stop Cuts=-1
Use User Specified Reach Order=0
Composite Channel Slope=5