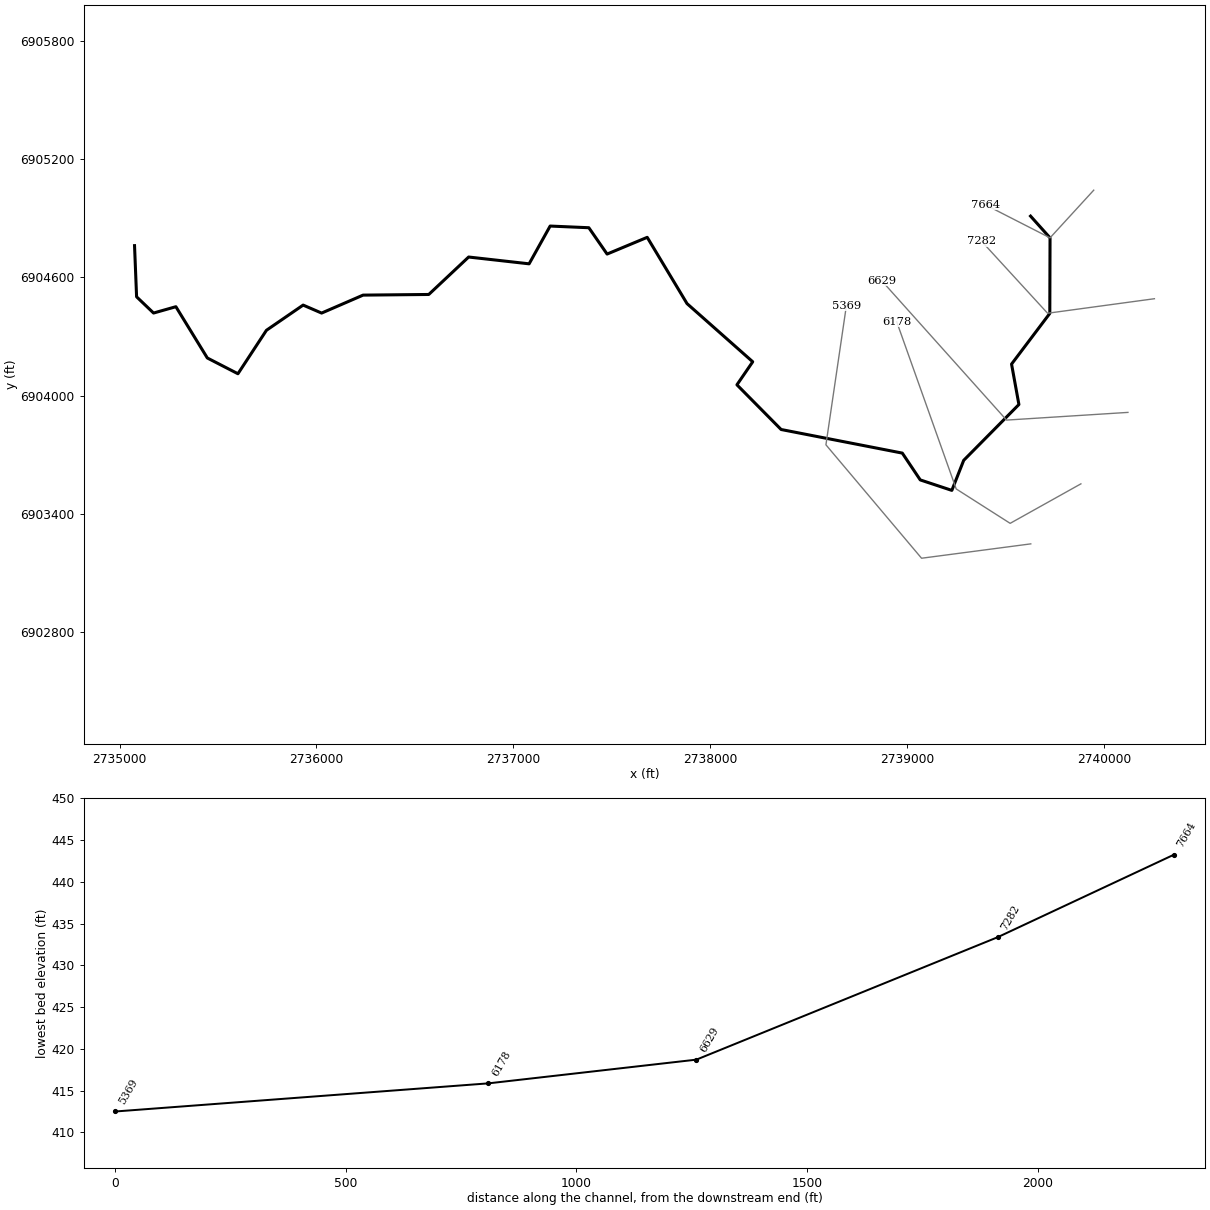
--- Flat T1.prj (project) ---

Proj Title=Flat T1 Base Level Engineering
Current Plan=p01
Default Exp/Contr=0.3,0.1
English Units
Geom File=g01
Flow File=f01
Plan File=p01
Y Axis Title=Elevation
X Axis Title(PF)=Main Channel Distance
X Axis Title(XS)=Station
BEGIN DESCRIPTION:
Flat T1
END DESCRIPTION:
DSS Export Rating Curves= 0
DSS Export Rating Curve Sorted= 0
DSS Export Volume Flow Curves= 0
DXF OffsetX= 0
DXF OffsetY= 0
DXF ScaleX= 1
DXF ScaleY= 10

--- Flat T1.p01 (plan) ---

Plan Title=Multiple Run
Short Identifier=Multiple
Geom File=g01
Flow File=f01
Subcritical Flow
K Sum by GR= 0
Std Step Tol= 0.01
Critical Tol= 0.01
Num of Std Step Trials= 20
Max Error Tol= 0.3
Flow Tol Ratio= 0.001
Split Flow NTrial= 30
Split Flow Tol= 0.02
Split Flow Ratio= 0.02
Log Output Level= 0
Friction Slope Method= 1
Unsteady Friction Slope Method= 2
Unsteady Bridges Friction Slope Method= 1
Parabolic Critical Depth
Global Vel Dist=  1 , 1 , 1
Global Log Level= 0
CheckData=True
Encroach Param= -1, 0, 0, 0
BEGIN DESCRIPTION:
Multiple Run
END DESCRIPTION:

--- Flat T1.f01 (steady flow) ---

Flow Title=Multiple
Number of Profiles=7
Profile Names=10-year,25-year,50-year,1pct_min,100-year,1pct_plu,500-year
River Rch & RM= Flat T1,Reach-1,7664
     614     817     980     583    1163    2321    1637
Boundary for River Rch & Prof#=Flat T1,Reach-1,1
Up Type=0
Dn Type=3
Dn Slope=0.005
Boundary for River Rch & Prof#=Flat T1,Reach-1,2
Up Type=0
Dn Type=3
Dn Slope=0.005
Boundary for River Rch & Prof#=Flat T1,Reach-1,3
Up Type=0
Dn Type=3
Dn Slope=0.005
Boundary for River Rch & Prof#=Flat T1,Reach-1,4
Up Type=0
Dn Type=3
Dn Slope=0.005
Boundary for River Rch & Prof#=Flat T1,Reach-1,5
Up Type=0
Dn Type=3
Dn Slope=0.005
Boundary for River Rch & Prof#=Flat T1,Reach-1,6
Up Type=0
Dn Type=3
Dn Slope=0.005
Boundary for River Rch & Prof#=Flat T1,Reach-1,7
Up Type=0
Dn Type=3
Dn Slope=0.005

--- Flat T1.g01 (geometry) ---

Geom Title=Existing Conditions
Program Version=4.10

River Reach=Flat T1         ,Reach-1
Reach XY= 30
        2739626.        6904911.      2739724.98      6904800.58
      2739723.76      6904416.93      2739529.53      6904159.53
      2739566.87      6903954.26      2739286.52      6903670.78
      2739226.34      6903518.21       2739065.9      6903571.39
      2738974.75      6903707.55      2738359.33      6903827.39
      2738134.97      6904054.33      2738215.17      6904171.32
      2737881.59      6904466.61      2737679.43      6904803.21
      2737475.69      6904718.23      2737383.01      6904851.97
      2737186.45      6904860.47      2737079.69       6904668.7
      2736772.58       6904703.2      2736570.15      6904513.06
       2736236.5      6904509.78      2736025.99      6904418.59
      2735932.12      6904459.16      2735745.77      6904331.13
      2735601.12      6904110.46      2735445.63      6904190.52
        2735286.      6904450.93      2735172.58      6904418.81
      2735086.44      6904501.17        2735076.        6904761.

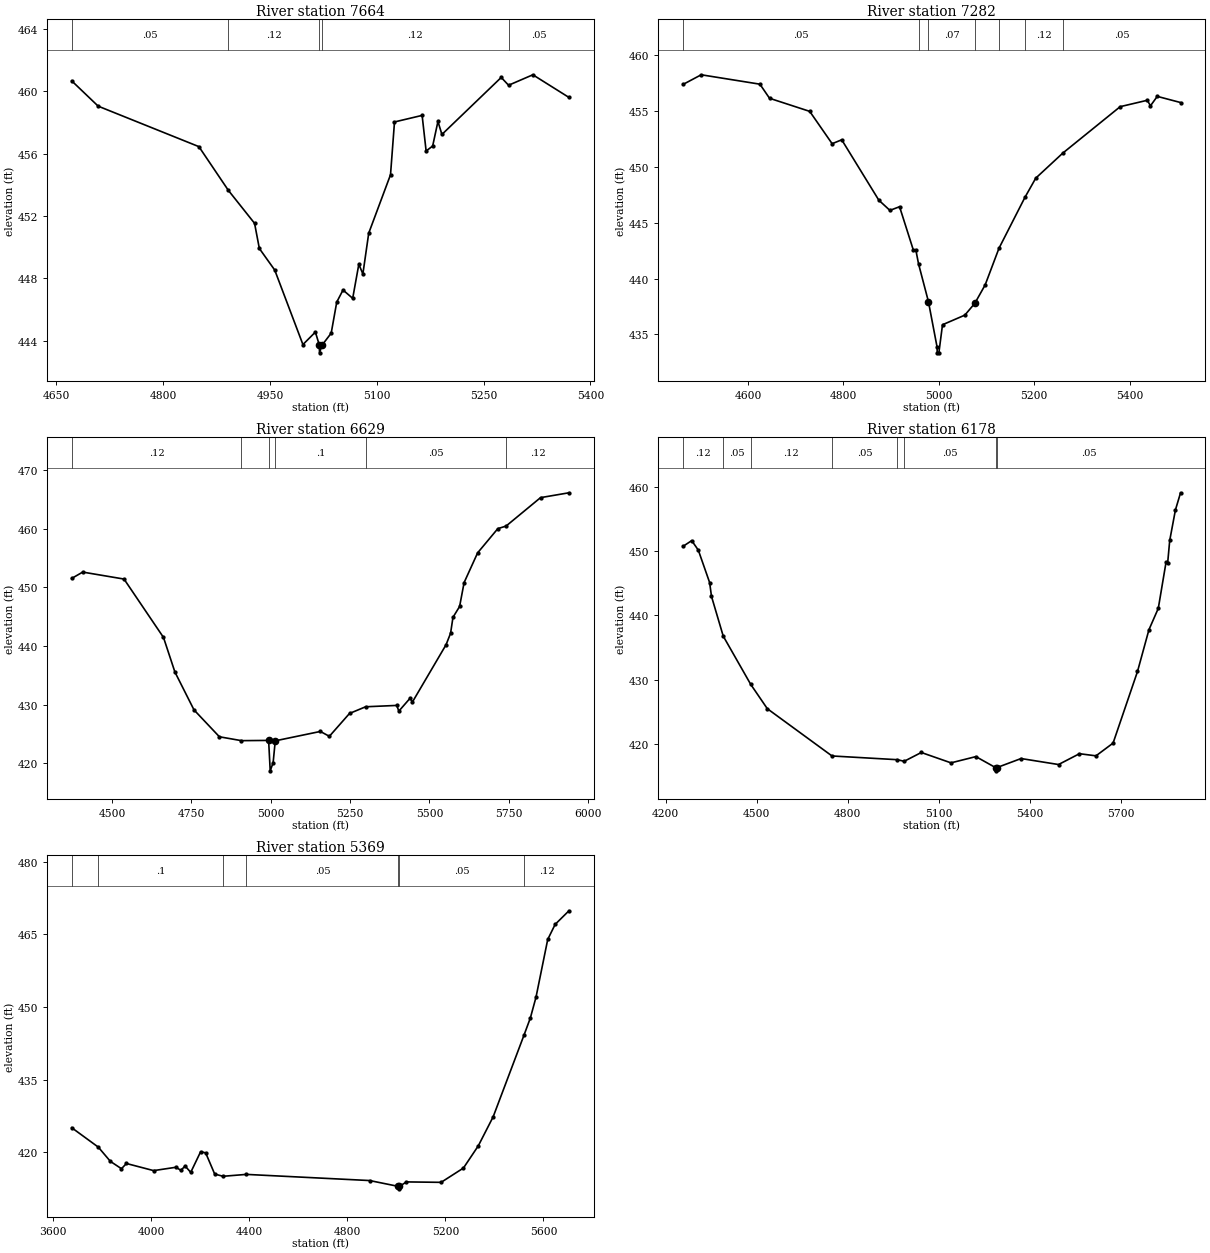
Type RM Length L Ch R = 1 ,7664    ,382,382,382
BEGIN DESCRIPTION:
Flat T1 3.0
END DESCRIPTION:
XS GIS Cut Line= 3
      2739946.84       6905042.7      2739724.98      6904800.58
      2739395.61      6904968.94
#Sta/Elev= 30
  4671.6  460.65  4708.8  459.03  4850.2  456.44  4891.6  453.64  4928.4  451.53
  4935.1  449.92  4956.7  448.54  4996.3  443.77  5013.8  444.57  5019.3  443.74
  5019.6  443.24  5023.3  443.74    5036   444.5  5043.8  446.49  5052.6  447.26
  5066.2  446.73  5074.8  448.91  5080.5  448.29  5088.7   450.9  5119.3  454.64
  5124.9  458.02  5163.7  458.44  5169.3  456.16  5178.5  456.48  5185.9  458.05
  5191.5  457.22  5274.8  460.87  5285.1  460.37  5319.2  461.04  5369.9  459.59
#Mann= 5 ,-1 , 0
  4671.6     .05       0  4891.6     .12       0  5019.3     .07       0
  5023.3     .12       0  5285.1     .05       0
Bank Sta=5019.3,5023.3
XS Rating Curve= 0 ,0
Exp/Cntr=0.3,0.1

Type RM Length L Ch R = 1 ,7282    ,653,653,653
BEGIN DESCRIPTION:
Mapping XS 2e2c5893
END DESCRIPTION:
XS GIS Cut Line= 3
      2740255.02      6904491.49      2739712.48      6904417.71
      2739378.29      6904782.28
#Sta/Elev= 30
  4464.4  457.36  4501.9  458.21  4624.9  457.37  4645.1  456.11  4729.3  454.94
  4776.3  452.05  4796.4   452.4  4874.2     447  4897.4  446.09  4917.6  446.42
  4946.6  442.53  4951.6  442.58  4957.4  441.31  4978.1  437.94  4996.3  433.86
  4996.5  433.36    5000  433.36  5007.6  435.87  5054.4  436.73  5075.4  437.79
    5097  439.43    5126  442.71  5180.3  447.25    5203  448.97  5259.7  451.21
    5380  455.36  5436.7  455.93  5443.5  455.44  5457.7  456.28  5506.5  455.73
#Mann= 7 ,-1 , 0
  4464.4     .05       0  4957.4     .12       0  4978.1     .07       0
  5075.4     .12       0    5126     .05       0  5180.3     .12       0
  5259.7     .05       0
Bank Sta=4978.1,5075.4
XS Rating Curve= 0 ,0
Exp/Cntr=0.3,0.1

Type RM Length L Ch R = 1 ,6629    ,451,451,451
BEGIN DESCRIPTION:
Mapping XS e9ac277a
END DESCRIPTION:
XS GIS Cut Line= 3
      2740120.49      6903914.24      2739504.15      6903875.17
      2738870.76       6904582.3
#Sta/Elev= 30
  4372.6  451.53  4407.2  452.61  4537.4  451.42  4661.8  441.46  4697.7  435.57
  4757.9   429.1    4838  424.51  4907.4  423.85  4993.1  423.89  4998.1   418.7
  5007.3  420.09    5014  423.82  5156.1  425.42  5184.5  424.59    5248  428.49
  5298.8  429.63  5396.8  429.86  5403.5  428.89  5439.4  431.12  5446.1  430.43
  5552.3  440.22  5566.5  442.18    5574  444.89  5594.9  446.74  5609.1  450.82
  5651.7  455.89  5715.3  460.02  5741.3  460.46  5849.9  465.31  5939.5  466.14
#Mann= 6 ,-1 , 0
  4372.6     .12       0  4907.4      .1       0  4993.1     .07       0
    5014      .1       0  5298.8     .05       0  5741.3     .12       0
Bank Sta=4993.1,5014
XS Rating Curve= 0 ,0
Exp/Cntr=0.3,0.1

Type RM Length L Ch R = 1 ,6178    ,809,809,809
BEGIN DESCRIPTION:
Mapping XS fbab3ab2
END DESCRIPTION:
XS GIS Cut Line= 4
      2739881.66      6903551.42      2739522.42      6903350.87
      2739248.36      6903525.63      2738946.27      6904374.61
#Sta/Elev= 30
  4258.6  450.76  4286.3  451.62    4308  450.14  4345.3   445.1  4351.4  442.96
  4390.1  436.78  4480.6  429.29  4535.3  425.51  4748.3  418.17  4963.8  417.59
  4985.9  417.34  5042.4  418.71  5140.2   417.1  5222.1  418.07  5287.1  416.36
  5287.3  415.86  5291.1  416.36    5371  417.77  5494.3  416.84  5563.3  418.52
  5617.7  418.19    5674  420.17  5754.4  431.29  5792.1  437.78  5822.9   441.1
  5848.4  448.26  5853.7  448.12  5860.5  451.64  5879.3  456.38  5896.2  459.05
#Mann= 8 ,-1 , 0
  4258.6     .12       0  4390.1     .05       0  4480.6     .12       0
  4748.3     .05       0  4963.8     .12       0  4985.9     .05       0
  5287.1     .04       0  5291.1     .05       0
Bank Sta=5287.1,5291.1
XS Rating Curve= 0 ,0
Exp/Cntr=0.3,0.1

Type RM Length L Ch R = 1 ,5369    ,0,0,0
BEGIN DESCRIPTION:
Mapping XS 133d1a05
END DESCRIPTION:
XS GIS Cut Line= 4
      2739627.18      6903246.63      2739072.52      6903173.67
       2738586.9      6903749.59      2738690.89      6904456.72
#Sta/Elev= 30
  3676.4   425.1  3784.7   421.1  3834.2  418.15  3879.3  416.64  3899.5  417.72
  4010.4  416.25  4101.2  416.94  4121.4  416.32  4138.9  417.19  4161.7  415.89
  4202.1  420.15  4222.6  419.91  4259.4  415.54  4293.5  415.08  4388.5  415.47
  4891.3   414.2  5008.8  412.99  5009.1  412.49  5012.8  412.99  5041.1  413.92
  5182.6  413.83  5273.6  416.78  5334.2  421.36  5394.9  427.36  5520.3  444.16
  5546.5  447.74  5569.5  452.02  5617.3  463.94  5647.6  467.05  5703.9  469.86
#Mann= 7 ,-1 , 0
  3676.4     .12       0  3784.7      .1       0  4293.5     .12       0
  4388.5     .05       0  5008.8     .04       0  5012.8     .05       0
  5520.3     .12       0
Bank Sta=5008.8,5012.8
XS Rating Curve= 0 ,0
Exp/Cntr=0.3,0.1

Chan Stop Cuts=-1
Use User Specified Reach Order=0
Composite Channel Slope=5