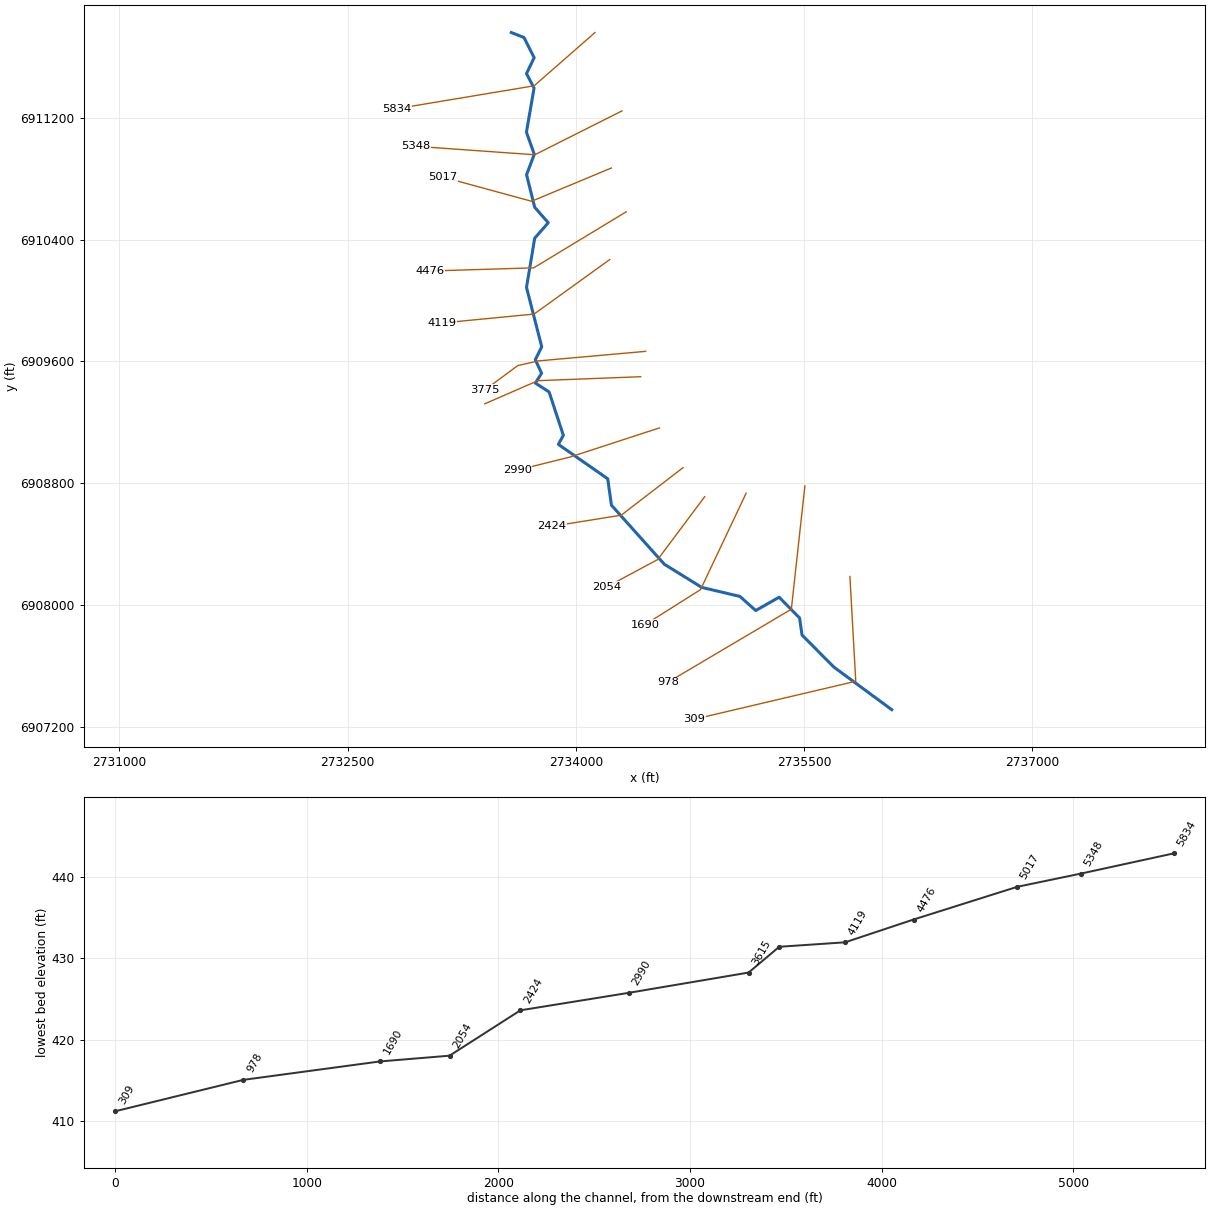
--- Flat T2.prj (project) ---

Proj Title=Flat T2 Base Level Engineering
Current Plan=p01
Default Exp/Contr=0.3,0.1
English Units
Geom File=g01
Flow File=f01
Plan File=p01
BEGIN DESCRIPTION:
Flat T2
END DESCRIPTION:

--- Flat T2.p01 (plan) ---

Plan Title=Multiple Run
Short Identifier=Multiple
Geom File=g01
Flow File=f01
Subcritical Flow
K Sum by GR= 0
Std Step Tol= 0.01
Critical Tol= 0.01
Num of Std Step Trials= 20
Max Error Tol= 0.3
Flow Tol Ratio= 0.001
Split Flow NTrial= 30
Split Flow Tol= 0.02
Split Flow Ratio= 0.02
Log Output Level= 0
Friction Slope Method= 1
Unsteady Friction Slope Method= 2
Unsteady Bridges Friction Slope Method= 1
Parabolic Critical Depth
Global Vel Dist=  1 , 1 , 1
Global Log Level= 0
CheckData=True
Encroach Param= -1, 0, 0, 0
BEGIN DESCRIPTION:
Multiple Run
END DESCRIPTION:

--- Flat T2.f01 (steady flow) ---

Flow Title=Multiple
Number of Profiles=7
Profile Names=10-year,25-year,50-year,1pct_min,100-year,1pct_plu,500-year
River Rch & RM= Flat T2,Reach-1,5834
     580     769     920     547    1091    2176    1529
Boundary for River Rch & Prof#=Flat T2,Reach-1,1
Up Type=0
Dn Type=3
Dn Slope=0.005
Boundary for River Rch & Prof#=Flat T2,Reach-1,2
Up Type=0
Dn Type=3
Dn Slope=0.005
Boundary for River Rch & Prof#=Flat T2,Reach-1,3
Up Type=0
Dn Type=3
Dn Slope=0.005
Boundary for River Rch & Prof#=Flat T2,Reach-1,4
Up Type=0
Dn Type=3
Dn Slope=0.005
Boundary for River Rch & Prof#=Flat T2,Reach-1,5
Up Type=0
Dn Type=3
Dn Slope=0.005
Boundary for River Rch & Prof#=Flat T2,Reach-1,6
Up Type=0
Dn Type=3
Dn Slope=0.005
Boundary for River Rch & Prof#=Flat T2,Reach-1,7
Up Type=0
Dn Type=3
Dn Slope=0.005

--- Flat T2.g01 (geometry) ---

Geom Title=Existing Conditions

River Reach=Flat T2,Reach-1
Reach XY= 30
      2733576.00      6911761.00      2733659.63      6911728.04
      2733725.92      6911595.61      2733675.73      6911490.83
      2733725.46      6911395.79      2733675.19      6911105.97
      2733726.81      6910961.00      2733676.09      6910826.39
      2733729.57      6910612.47      2733818.90      6910511.00
      2733729.63      6910409.50      2733675.69      6910085.96
      2733775.85      6909695.58      2733733.62      6909611.00
      2733775.01      6909521.63      2733733.75      6909457.36
      2733824.22      6909399.13      2733917.71      6909114.22
      2733885.29      6909054.31      2734209.72      6908828.14
      2734233.82      6908654.81      2734581.61      6908266.59
      2734827.47      6908114.55      2735078.29      6908055.15
      2735182.05      6907962.59      2735336.00      6908050.04
      2735470.48      6907913.43      2735486.52      6907801.21
      2735695.84      6907590.62      2736076.00      6907311.00

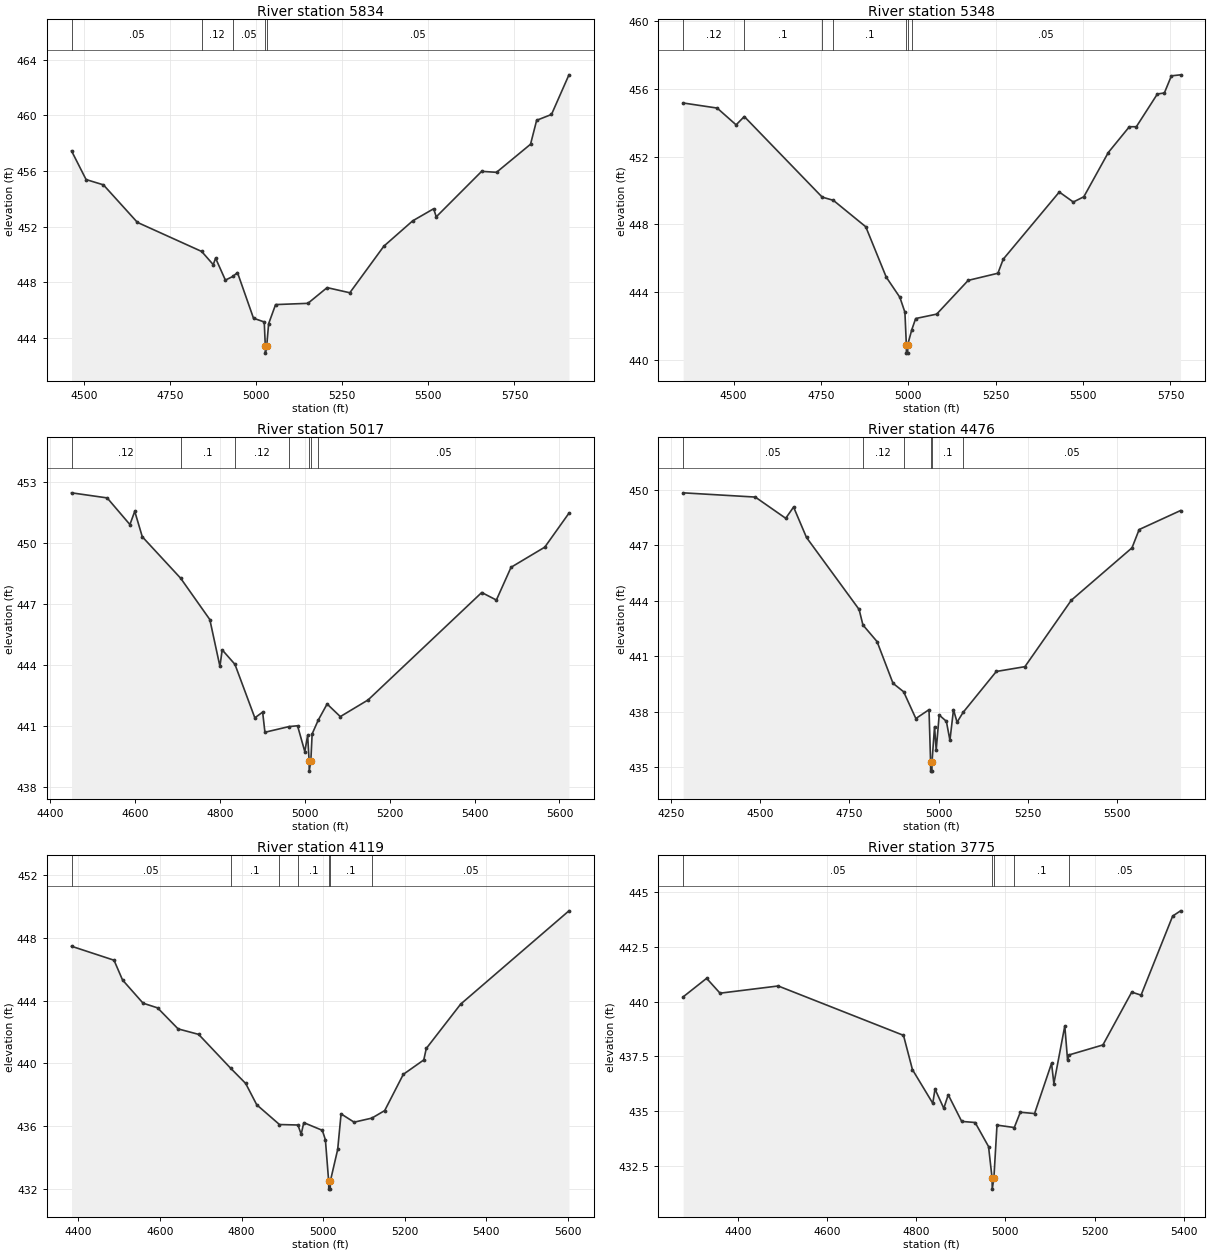
Type RM Length L Ch R = 1,5834,486,486,486
BEGIN DESCRIPTION:
Flat T2 11.0
END DESCRIPTION:
XS GIS Cut Line= 3
      2734126.00      6911761.00      2733726.00      6911411.00
      2732826.02      6911261.00
#Sta/Elev= 30
  4464.2  457.44  4506.4  455.38  4556.7  455.00  4655.4  452.30  4842.0  450.21
  4875.6  449.26  4882.3  449.73  4910.8  448.15  4932.1  448.41  4945.9  448.69
  4992.4  445.41  5023.6  445.14  5026.7  443.40  5026.9  442.90  5030.7  443.40
  5036.3  445.01  5056.5  446.39  5150.3  446.48  5206.1  447.61  5272.0  447.24
  5370.8  450.59  5454.4  452.41  5515.3  453.28  5522.9  452.70  5654.7  455.97
  5697.8  455.90  5796.6  457.92  5814.3  459.64  5857.4  460.06  5908.1  462.91
#Mann=5,-1,0
  4464.2    0.05       0  4842.0    0.12       0  4932.1    0.05       0
  5026.7    0.04       0  5030.7    0.05       0
Bank Sta=5026.7,5030.7
Exp/Cntr=0.3,0.1

Type RM Length L Ch R = 1,5348,331,331,331
BEGIN DESCRIPTION:
Flat T2 10.0
END DESCRIPTION:
XS GIS Cut Line= 3
      2734302.98      6911245.84      2733730.03      6910957.62
      2732949.86      6911013.10
#Sta/Elev= 30
  4355.4  455.16  4452.8  454.86  4507.0  453.87  4530.4  454.36  4753.3  449.61
  4785.3  449.42  4878.1  447.86  4936.7  444.89  4975.7  443.70  4990.1  442.82
  4994.2  440.91  4994.5  440.41  4998.0  440.41  4998.2  440.91  5009.6  441.78
  5020.9  442.45  5081.0  442.71  5171.2  444.70  5256.2  445.12  5271.5  445.95
  5431.9  449.91  5472.0  449.32  5502.1  449.63  5572.2  452.24  5632.4  453.76
  5652.4  453.76  5712.6  455.69  5732.6  455.75  5752.7  456.76  5778.9  456.82
#Mann=7,-1,0
  4355.4    0.12       0  4530.4     0.1       0  4753.3    0.12       0
  4785.3     0.1       0  4994.2    0.07       0  4998.2     0.1       0
  5009.6    0.05       0
Bank Sta=4994.2,4998.2
Exp/Cntr=0.3,0.1

Type RM Length L Ch R = 1,5017,541,541,541
BEGIN DESCRIPTION:
Flat T2 9.0
END DESCRIPTION:
XS GIS Cut Line= 3
      2734233.53      6910870.83      2733709.19      6910652.07
      2733126.00      6910811.00
#Sta/Elev= 30
  4449.7  452.47  4533.7  452.22  4587.3  450.91  4598.7  451.56  4616.5  450.31
  4707.0  448.27  4775.7  446.24  4799.5  443.94  4804.9  444.75  4834.9  444.04
  4881.8  441.41  4900.2  441.69  4905.6  440.70  4962.4  440.98  4982.5  441.02
  4999.6  439.75  5006.3  440.55  5009.8  439.29  5010.0  438.79  5013.8  439.29
  5016.9  440.62  5031.1  441.29  5052.2  442.09  5083.3  441.47  5148.8  442.29
  5416.7  447.57  5451.2  447.20  5485.8  448.81  5565.3  449.80  5622.3  451.47
#Mann=7,-1,0
  4449.7    0.12       0  4707.0     0.1       0  4834.9    0.12       0
  4962.4     0.1       0  5009.8    0.07       0  5013.8     0.1       0
  5031.1    0.05       0
Bank Sta=5009.8,5013.8
Exp/Cntr=0.3,0.1

Type RM Length L Ch R = 1,4476,357,357,357
BEGIN DESCRIPTION:
Mapping XS 2ab30f60
END DESCRIPTION:
XS GIS Cut Line= 3
      2734330.76      6910582.65      2733723.08      6910214.57
      2733040.06      6910193.76
#Sta/Elev= 30
  4284.1  449.85  4486.3  449.62  4571.6  448.47  4593.6  449.08  4629.8  447.43
  4777.2  443.53  4787.9  442.69  4827.5  441.79  4872.2  439.53  4902.0  439.07
  4936.2  437.62  4973.1  438.10  4977.5  435.27  4977.7  434.77  4981.2  434.77
  4981.5  435.27  4988.6  437.18  4993.2  435.91  5001.6  437.81  5021.7  437.47
  5031.7  436.44  5041.7  438.10  5051.7  437.42  5068.5  437.95  5161.7  440.17
  5241.8  440.43  5371.8  444.03  5541.9  446.87  5561.9  447.86  5677.9  448.89
#Mann=6,-1,0
  4284.1    0.05       0  4787.9    0.12       0  4902.0     0.1       0
  4977.5    0.07       0  4981.5     0.1       0  5068.5    0.05       0
Bank Sta=4977.5,4981.5
Exp/Cntr=0.3,0.1

Type RM Length L Ch R = 1,4119,344,344,344
BEGIN DESCRIPTION:
Flat T2 7.0
END DESCRIPTION:
XS GIS Cut Line= 3
      2734222.61      6910268.91      2733726.00      6909911.00
      2733121.90      6909852.24
#Sta/Elev= 30
  4383.3  447.46  4487.4  446.57  4508.3  445.31  4558.6  443.83  4594.2  443.53
  4644.5  442.19  4694.8  441.84  4772.9  439.69  4810.1  438.71  4837.2  437.35
  4892.9  436.09  4938.2  436.06  4946.1  435.47  4952.5  436.21  4998.0  435.72
  5005.5  435.11  5013.5  432.47  5013.8  431.97  5017.3  431.97  5017.5  432.47
  5035.6  434.50  5043.9  436.77  5075.8  436.24  5119.4  436.50  5150.8  436.98
  5196.4  439.29  5246.6  440.21  5252.7  440.94  5337.0  443.77  5602.4  449.72
#Mann=7,-1,0
  4383.3    0.05       0  4772.9     0.1       0  4892.9    0.12       0
  4938.2     0.1       0  5013.5    0.07       0  5017.5     0.1       0
  5119.4    0.05       0
Bank Sta=5013.5,5017.5
Exp/Cntr=0.3,0.1

Type RM Length L Ch R = 1,3775,160,160,160
BEGIN DESCRIPTION:
Mapping XS 08a3dea1
END DESCRIPTION:
XS GIS Cut Line= 4
      2734458.49      6909665.81      2733753.17      6909602.88
      2733618.63      6909572.49      2733401.63      6909411.92
#Sta/Elev= 30
  4277.0  440.22  4329.7  441.07  4359.8  440.39  4490.3  440.72  4771.4  438.46
  4791.5  436.89  4837.1  435.35  4842.1  436.00  4861.8  435.12  4871.8  435.74
  4902.0  434.52  4932.1  434.47  4962.2  433.37  4970.2  431.92  4970.5  431.42
  4974.2  431.92  4981.2  434.35  5020.0  434.24  5033.5  434.94  5065.5  434.88
  5103.6  437.18  5108.8  436.25  5133.3  438.89  5139.5  437.34  5142.3  437.56
  5218.8  438.02  5283.5  440.44  5304.4  440.30  5375.3  443.92  5393.0  444.16
#Mann=5,-1,0
  4277.0    0.05       0  4970.2    0.05       0  4974.2    0.05       0
  5020.0     0.1       0  5142.3    0.05       0
Bank Sta=4970.2,4974.2
Exp/Cntr=0.3,0.1

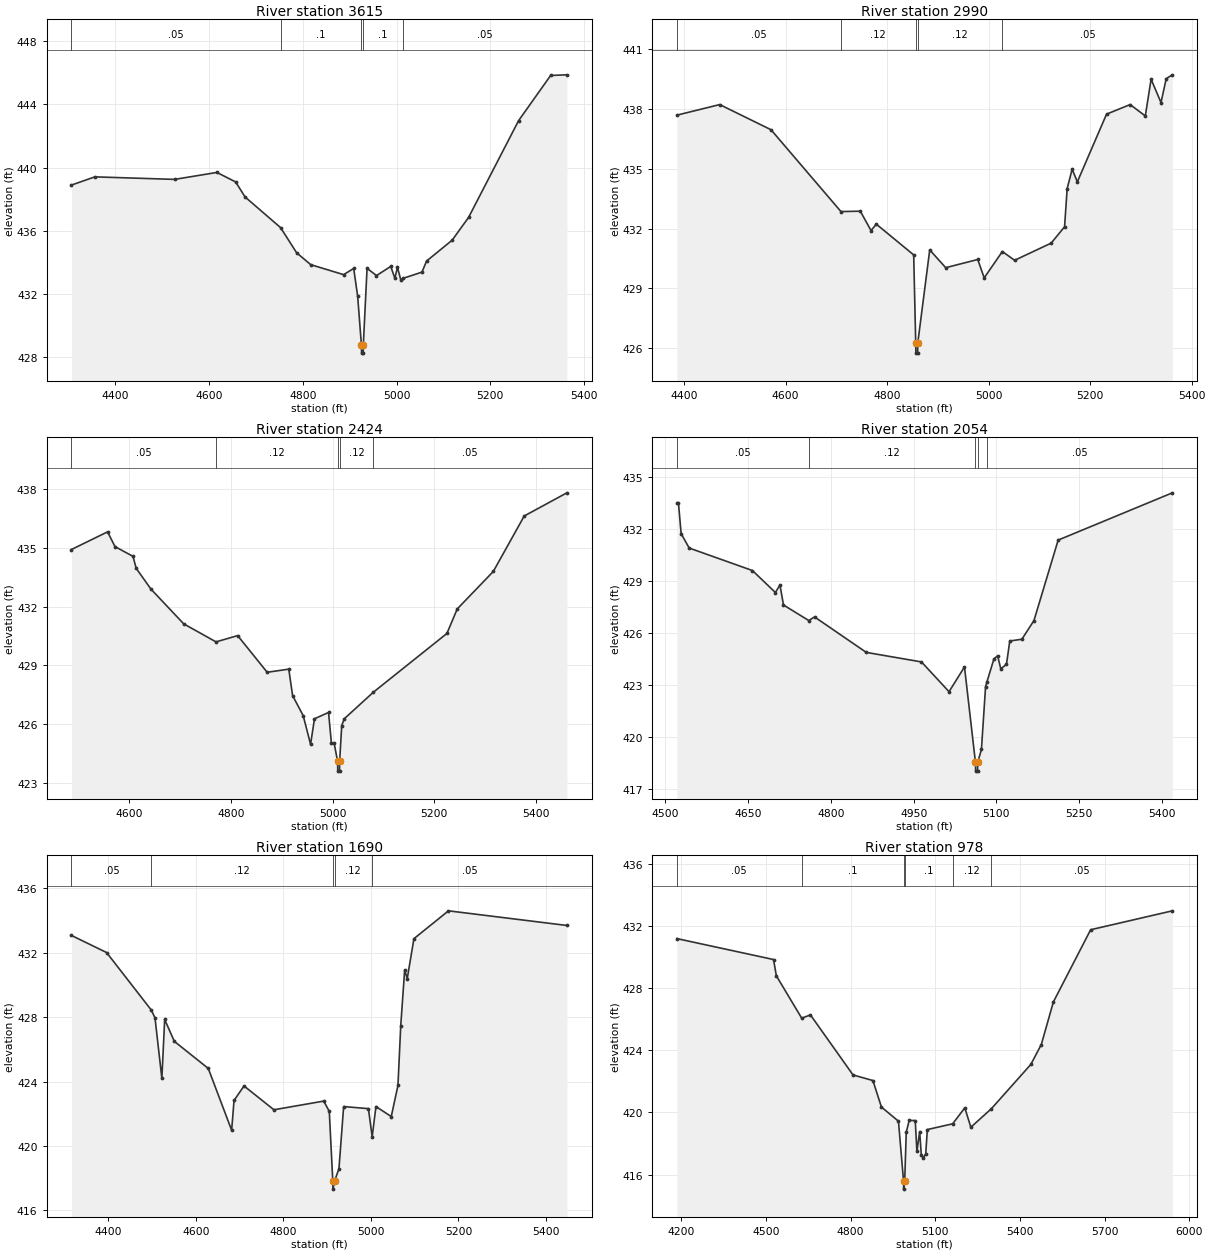
Type RM Length L Ch R = 1,3615,625,625,625
BEGIN DESCRIPTION:
Mapping XS 050d19ec
END DESCRIPTION:
XS GIS Cut Line= 3
      2734425.87      6909499.07      2733751.00      6909473.03
      2733401.57      6909321.10
#Sta/Elev= 30
  4306.8  438.89  4356.7  439.41  4526.8  439.25  4616.9  439.69  4656.9  439.09
  4676.9  438.14  4752.6  436.20  4787.0  434.60  4817.1  433.85  4887.1  433.22
  4908.6  433.61  4917.1  431.84  4925.1  428.75  4925.4  428.25  4928.9  428.25
  4929.1  428.75  4937.1  433.62  4957.2  433.16  4987.6  433.74  4996.4  432.99
  5001.9  433.68  5009.4  432.85  5013.4  432.98  5054.2  433.38  5064.0  434.08
  5118.5  435.40  5153.5  436.84  5260.2  442.97  5328.5  445.83  5363.2  445.87
#Mann=5,-1,0
  4306.8    0.05       0  4752.6     0.1       0  4925.1    0.07       0
  4929.1     0.1       0  5013.4    0.05       0
Bank Sta=4925.1,4929.1
Exp/Cntr=0.3,0.1

Type RM Length L Ch R = 1,2990,566,566,566
BEGIN DESCRIPTION:
Mapping XS 09ad0510
END DESCRIPTION:
XS GIS Cut Line= 3
      2734549.63      6909162.71      2733963.68      6908971.73
      2733614.29      6908884.92
#Sta/Elev= 30
  4385.7  437.68  4470.1  438.21  4571.1  436.95  4709.0  432.85  4747.1  432.87
  4768.2  431.90  4778.7  432.22  4852.3  430.68  4856.3  426.26  4856.6  425.76
  4860.1  425.76  4860.3  426.26  4883.9  430.93  4915.4  430.04  4978.5  430.45
  4991.2  429.53  5027.0  430.85  5051.1  430.41  5123.2  431.27  5149.6  432.09
  5154.7  434.00  5164.5  434.97  5174.8  434.34  5232.3  437.73  5278.8  438.21
  5308.7  437.64  5320.1  439.48  5339.6  438.31  5349.9  439.51  5362.0  439.70
#Mann=5,-1,0
  4385.7    0.05       0  4709.0    0.12       0  4856.3    0.07       0
  4860.3    0.12       0  5027.0    0.05       0
Bank Sta=4856.3,4860.3
Exp/Cntr=0.3,0.1

Type RM Length L Ch R = 1,2424,370,370,370
BEGIN DESCRIPTION:
Mapping XS e1defdf8
END DESCRIPTION:
XS GIS Cut Line= 3
      2734704.38      6908901.53      2734298.17      6908589.06
      2733843.27      6908516.14
#Sta/Elev= 30
  4487.2  434.91  4558.2  435.81  4572.7  435.06  4608.1  434.56  4614.4  433.95
  4643.4  432.89  4707.7  431.12  4771.2  430.20  4813.7  430.52  4871.7  428.65
  4914.1  428.81  4921.6  427.46  4942.4  426.44  4956.9  424.98  4964.6  426.28
  4992.2  426.60  4997.9  425.02  5003.3  425.02  5010.0  424.11  5010.3  423.61
  5013.8  423.61  5014.0  424.11  5018.1  425.93  5023.1  426.28  5080.5  427.64
  5224.7  430.63  5245.0  431.88  5315.8  433.79  5376.6  436.62  5460.4  437.80
#Mann=5,-1,0
  4487.2    0.05       0  4771.2    0.12       0  5010.0    0.07       0
  5014.0    0.12       0  5080.5    0.05       0
Bank Sta=5010,5014
Exp/Cntr=0.3,0.1

Type RM Length L Ch R = 1,2054,364,364,364
BEGIN DESCRIPTION:
Mapping XS 1a4694b9
END DESCRIPTION:
XS GIS Cut Line= 3
      2734846.80      6908710.61      2734537.75      6908297.39
      2734200.99      6908116.86
#Sta/Elev= 30
  4520.8  433.50  4523.7  433.50  4528.5  431.75  4543.1  430.92  4657.7  429.62
  4699.4  428.35  4707.6  428.79  4714.0  427.63  4759.9  426.73  4770.3  426.94
  4864.1  424.89  4964.1  424.34  5014.1  422.62  5042.1  424.05  5062.0  418.53
  5062.3  418.03  5065.8  418.03  5066.0  418.53  5072.8  419.28  5080.3  422.90
  5082.8  423.19  5095.5  424.52  5102.2  424.69  5107.9  423.94  5118.2  424.20
  5124.2  425.55  5146.1  425.65  5168.0  426.73  5211.9  431.38  5418.9  434.11
#Mann=5,-1,0
  4520.8    0.05       0  4759.9    0.12       0  5062.0    0.07       0
  5066.0    0.12       0  5082.8    0.05       0
Bank Sta=5062,5066
Exp/Cntr=0.3,0.1

Type RM Length L Ch R = 1,1690,712,712,712
BEGIN DESCRIPTION:
Mapping XS d42221fe
END DESCRIPTION:
XS GIS Cut Line= 3
      2735118.93      6908733.59      2734819.44      6908099.87
      2734454.86      6907869.84
#Sta/Elev= 30
  4315.8  433.08  4396.1  432.02  4498.1  428.45  4506.7  427.96  4522.4  424.20
  4528.8  427.86  4550.9  426.50  4628.4  424.82  4681.8  420.98  4687.3  422.83
  4710.1  423.73  4778.4  422.25  4892.2  422.79  4904.9  422.15  4912.9  417.82
  4913.2  417.32  4916.9  417.82  4927.0  418.59  4937.7  422.45  4994.3  422.32
  5002.9  420.57  5011.5  422.45  5046.5  421.83  5061.8  423.76  5068.1  427.45
  5077.1  430.93  5083.0  430.40  5098.3  432.88  5177.2  434.61  5447.8  433.70
#Mann=5,-1,0
  4315.8    0.05       0  4498.1    0.12       0  4912.9    0.07       0
  4916.9    0.12       0  5002.9    0.05       0
Bank Sta=4912.9,4916.9
Exp/Cntr=0.3,0.1

Type RM Length L Ch R = 1,978,669,669,669
BEGIN DESCRIPTION:
Mapping XS 5f684b79
END DESCRIPTION:
XS GIS Cut Line= 3
      2735505.20      6908781.33      2735416.14      6907971.11
      2734606.79      6907492.25
#Sta/Elev= 30
  4184.9  431.21  4527.3  429.86  4537.3  428.81  4627.1  426.08  4658.1  426.29
  4809.0  422.42  4879.4  422.06  4909.6  420.35  4969.9  419.44  4988.0  415.56
  4988.3  415.06  4992.0  415.56  4997.5  418.72  5008.0  419.49  5029.4  419.48
  5035.3  417.49  5045.1  418.77  5050.9  417.27  5058.3  417.07  5066.5  417.33
  5072.3  418.90  5161.9  419.27  5205.0  420.30  5226.4  419.05  5299.5  420.25
  5439.0  423.10  5476.0  424.38  5518.9  427.13  5650.8  431.78  5940.4  433.00
#Mann=6,-1,0
  4184.9    0.05       0  4627.1     0.1       0  4988.0    0.07       0
  4992.0     0.1       0  5161.9    0.12       0  5299.5    0.05       0
Bank Sta=4988,4992
Exp/Cntr=0.3,0.1

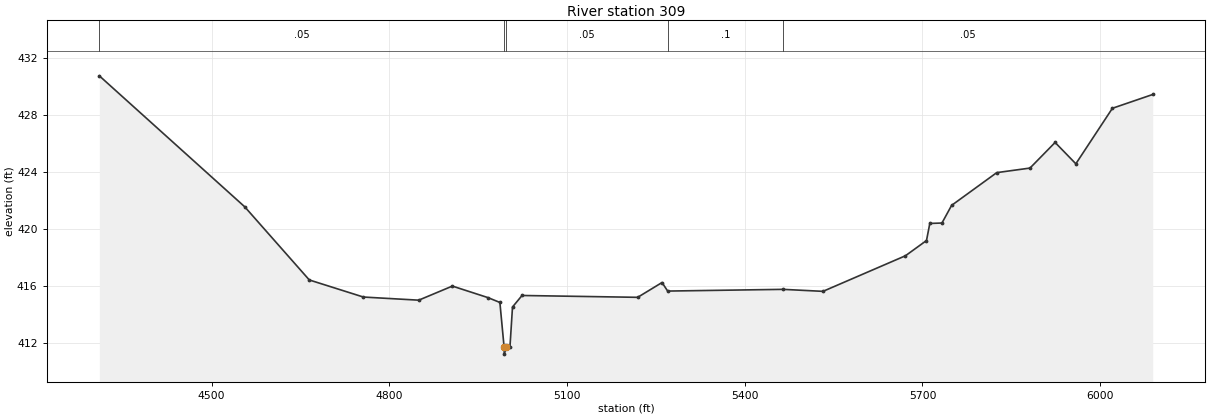
Type RM Length L Ch R = 1,309,0,0,0
BEGIN DESCRIPTION:
Flat T2 1.0
END DESCRIPTION:
XS GIS Cut Line= 3
      2735801.00      6908186.00      2735839.49      6907497.67
      2734779.69      6907248.48
#Sta/Elev= 30
  4310.6  430.75  4556.0  421.55  4665.0  416.41  4756.3  415.21  4849.7  414.99
  4906.5  415.98  4966.6  415.17  4986.7  414.83  4993.8  411.70  4994.1  411.20
  4997.8  411.70  5003.7  411.70  5008.0  414.51  5024.1  415.32  5219.3  415.19
  5260.4  416.23  5269.9  415.63  5464.6  415.75  5532.1  415.61  5671.3  418.11
  5706.8  419.18  5712.4  420.38  5732.9  420.41  5749.2  421.65  5825.4  423.95
  5881.5  424.27  5923.9  426.07  5958.9  424.57  6020.6  428.47  6088.7  429.44
#Mann=5,-1,0
  4310.6    0.05       0  4993.8    0.04       0  4997.8    0.05       0
  5269.9     0.1       0  5464.6    0.05       0
Bank Sta=4993.8,4997.8
Exp/Cntr=0.3,0.1

Chan Stop Cuts=-1