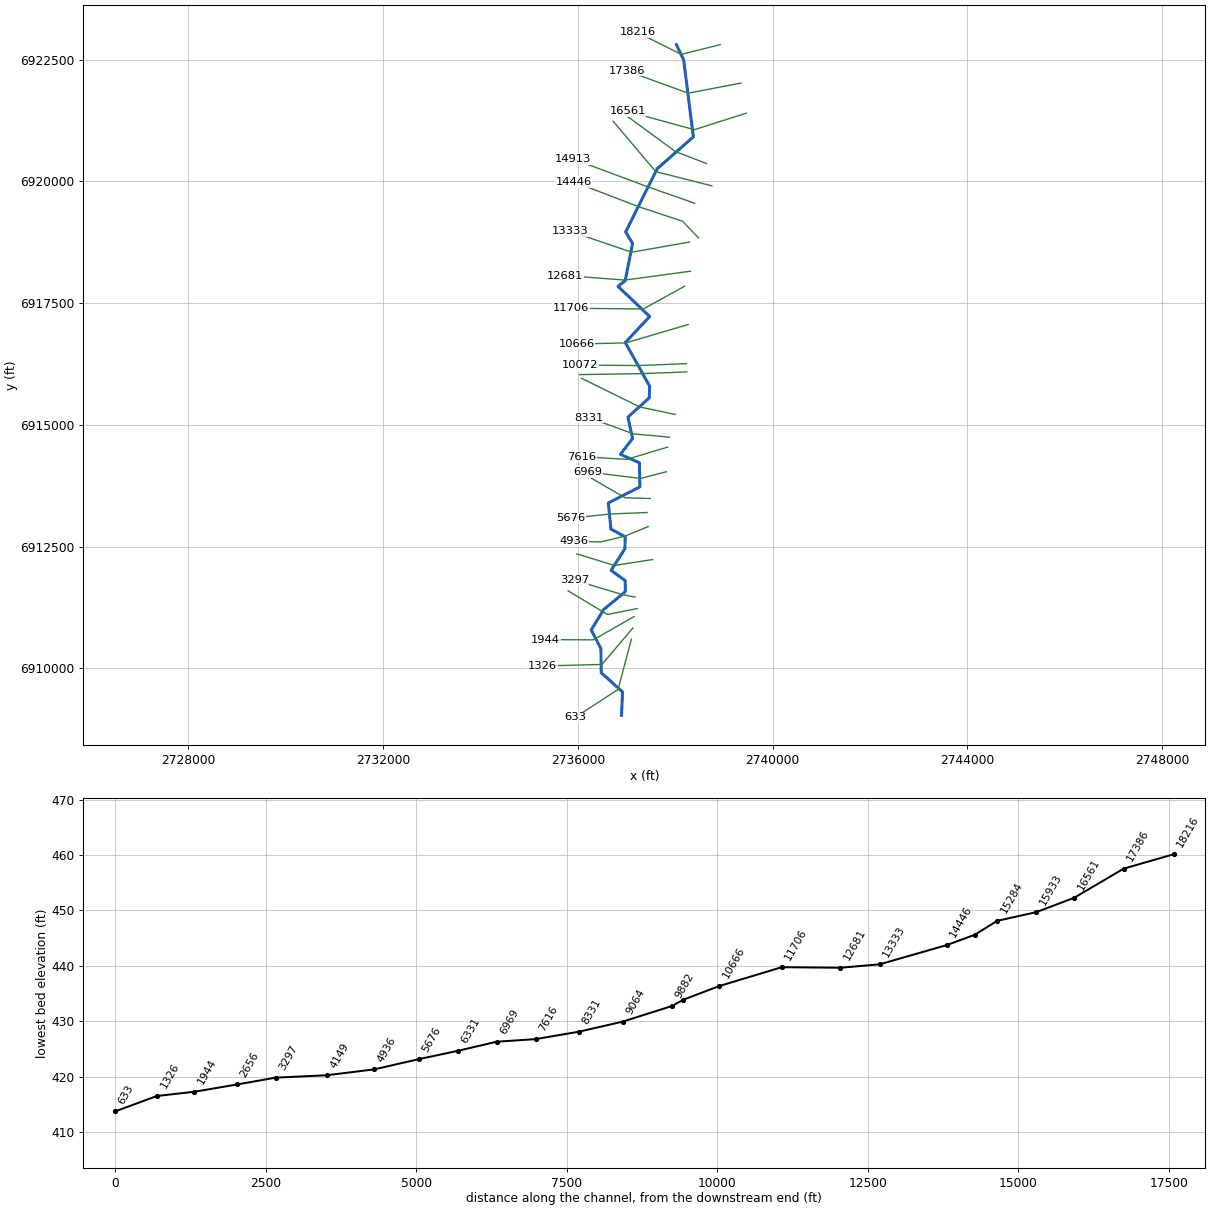
--- Flat T3.prj (project) ---

Proj Title=Flat T3 Base Level Engineering
Current Plan=p01
Default Exp/Contr=0.3,0.1
English Units
Geom File=g01
Flow File=f01
Plan File=p01
Y Axis Title=Elevation
X Axis Title(PF)=Main Channel Distance
X Axis Title(XS)=Station
BEGIN DESCRIPTION:
Flat T3
END DESCRIPTION:
DSS Export Rating Curves= 0
DSS Export Rating Curve Sorted= 0
DSS Export Volume Flow Curves= 0
DXF OffsetX= 0
DXF OffsetY= 0
DXF ScaleX= 1
DXF ScaleY= 10

--- Flat T3.p01 (plan) ---

Plan Title=Multiple Run
Short Identifier=Multiple
Geom File=g01
Flow File=f01
Subcritical Flow
K Sum by GR= 0
Std Step Tol= 0.01
Critical Tol= 0.01
Num of Std Step Trials= 20
Max Error Tol= 0.3
Flow Tol Ratio= 0.001
Split Flow NTrial= 30
Split Flow Tol= 0.02
Split Flow Ratio= 0.02
Log Output Level= 0
Friction Slope Method= 1
Unsteady Friction Slope Method= 2
Unsteady Bridges Friction Slope Method= 1
Parabolic Critical Depth
Global Vel Dist=  1 , 1 , 1
Global Log Level= 0
CheckData=True
Encroach Param= -1, 0, 0, 0
BEGIN DESCRIPTION:
Multiple Run
END DESCRIPTION:

--- Flat T3.f01 (steady flow) ---

Flow Title=Multiple
Number of Profiles=7
Profile Names=10-year,25-year,50-year,1pct_min,100-year,1pct_plu,500-year
River Rch & RM= Flat T3,Reach-1,18216
     526     693     825     488     974    1943    1353
River Rch & RM= Flat T3,Reach-1,17386
     836    1131    1371     824    1644    3280    2360
River Rch & RM= Flat T3,Reach-1,14446
    1144    1565    1911    1155    2304    4597    3347
River Rch & RM= Flat T3,Reach-1,5676
    1319    1814    2222    1345    2685    5356    3919
Boundary for River Rch & Prof#=Flat T3,Reach-1,1
Up Type=0
Dn Type=3
Dn Slope=0.005
Boundary for River Rch & Prof#=Flat T3,Reach-1,2
Up Type=0
Dn Type=3
Dn Slope=0.005
Boundary for River Rch & Prof#=Flat T3,Reach-1,3
Up Type=0
Dn Type=3
Dn Slope=0.005
Boundary for River Rch & Prof#=Flat T3,Reach-1,4
Up Type=0
Dn Type=3
Dn Slope=0.005
Boundary for River Rch & Prof#=Flat T3,Reach-1,5
Up Type=0
Dn Type=3
Dn Slope=0.005
Boundary for River Rch & Prof#=Flat T3,Reach-1,6
Up Type=0
Dn Type=3
Dn Slope=0.005
Boundary for River Rch & Prof#=Flat T3,Reach-1,7
Up Type=0
Dn Type=3
Dn Slope=0.005

--- Flat T3.g01 (geometry) ---

Geom Title=Existing Conditions
Program Version=4.10

River Reach=Flat T3         ,Reach-1
Reach XY= 30
        2738026.        6922811.      2738175.04      6922495.04
      2738374.02      6920916.67      2737631.83      6920263.31
      2736983.78       6918964.4      2737125.97      6918726.42
      2736972.96      6917962.42      2736825.84      6917845.76
      2737476.79      6917226.07      2736975.53      6916690.84
      2737475.48      6915795.78      2737468.19      6915554.81
      2737029.67      6915159.42      2737124.94      6914721.44
      2736875.74       6914395.3      2737265.06      6914221.44
      2737275.46      6913726.54      2736626.25      6913396.02
       2736681.4      6912858.56      2736975.07      6912700.53
      2736966.57      6912454.38        2736683.      6912010.78
      2736973.06      6911803.03      2736975.02      6911571.26
      2736531.08      6911205.96      2736275.85      6910786.11
      2736474.38      6910404.97      2736481.36       6909908.3
      2736918.31      6909514.67      2736898.12      6909033.09

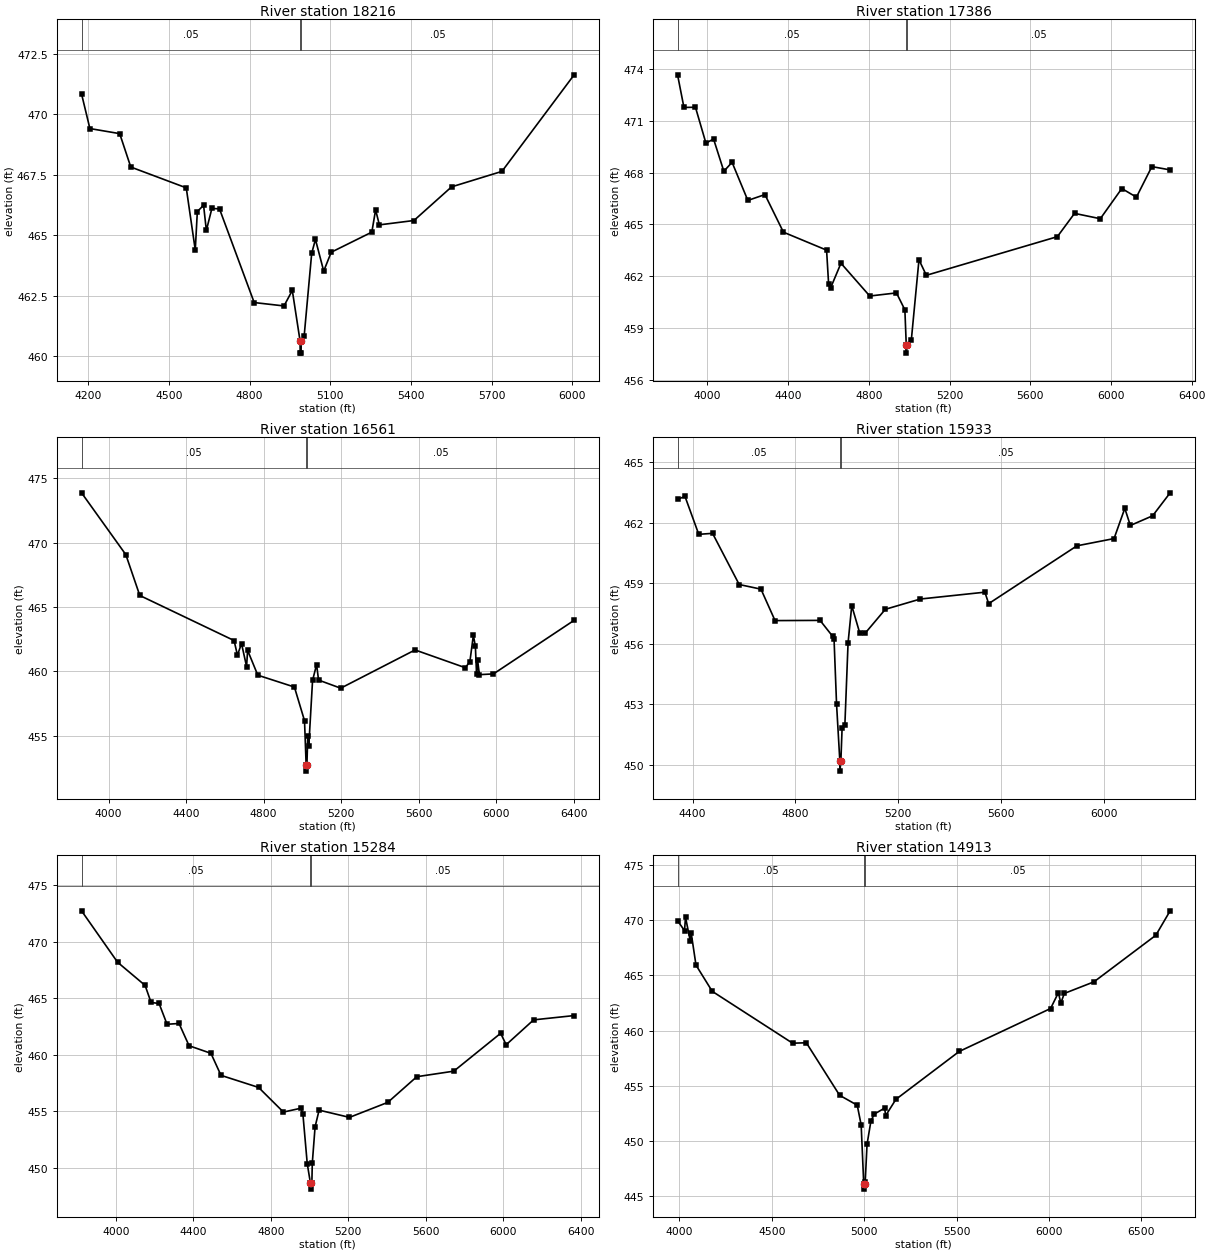
Type RM Length L Ch R = 1 ,18216   ,830,830,830
BEGIN DESCRIPTION:
Flat T3 24.0
END DESCRIPTION:
XS GIS Cut Line= 3
      2738926.03      6922811.01        2738126.        6922611.
      2737225.99      6923061.01
#Sta/Elev= 30
  4175.3  470.84  4206.3  469.41  4317.1   469.2  4358.3  467.82  4564.5  466.96
    4598  464.39  4605.7  465.98  4628.9  466.24  4639.2   465.2  4659.8  466.11
  4688.1  466.09    4817  462.22  4927.8  462.08  4958.7  462.72  4987.6  460.63
  4987.9  460.13  4991.4  460.13  4991.6  460.63  5002.8  460.84  5030.7  464.25
  5044.7  464.83  5075.4  463.52  5103.4   464.3  5254.3  465.13  5268.3  466.05
  5282.3  465.43  5410.8  465.61  5550.6     467  5737.9  467.64  6006.2  471.63
#Mann= 3 ,-1 , 0
  4175.3     .05       0  4987.6     .04       0  4991.6     .05       0
Bank Sta=4987.6,4991.6
XS Rating Curve= 0 ,0
Exp/Cntr=0.3,0.1

Type RM Length L Ch R = 1 ,17386   ,825,825,825
BEGIN DESCRIPTION:
Mapping XS 7de88c24
END DESCRIPTION:
XS GIS Cut Line= 3
      2739351.24      6922022.14      2738267.89       6921813.8
      2737010.95      6922272.13
#Sta/Elev= 30
  3852.2  473.67  3883.8  471.78  3940.9  471.79  3992.8  469.71  4030.6  469.95
  4081.6  468.08  4122.3   468.6  4200.5  466.39  4285.2  466.73  4376.9  464.55
  4590.7  463.51  4600.9  461.53  4611.1  461.33    4662  462.75  4804.6  460.85
    4937  461.03  4978.7  460.05  4985.5  458.04  4985.8  457.54  4989.5  458.04
  5010.6  458.29  5048.6  462.95  5085.1  462.05  5734.4  464.29  5819.6  465.64
  5947.3  465.33  6053.8  467.08  6126.2  466.58  6202.8  468.35  6293.3  468.16
#Mann= 3 ,-1 , 0
  3852.2     .05       0  4985.5     .04       0  4989.5     .05       0
Bank Sta=4985.5,4989.5
XS Rating Curve= 0 ,0
Exp/Cntr=0.3,0.1

Type RM Length L Ch R = 1 ,16561   ,628,628,628
BEGIN DESCRIPTION:
Mapping XS 84759cf6
END DESCRIPTION:
XS GIS Cut Line= 3
       2739462.3      6921404.07      2738392.89       6921063.8
       2737024.8      6921438.81
#Sta/Elev= 30
  3860.7  473.87  4089.1  469.07  4161.1   465.9  4647.5   462.4  4664.9  461.26
  4685.8  462.17    4712  460.38  4717.3  461.64  4769.8  459.71  4958.7  458.79
  5010.8  456.18  5019.2  452.76  5019.4  452.26  5023.2  452.76  5027.7  455.01
  5032.9  454.22  5052.3   459.3    5073  460.53  5083.4  459.33  5197.5   458.7
  5581.1  461.67  5840.3  460.29  5863.8  460.76  5881.8  462.81  5892.2  461.94
  5898.2  459.83  5903.4   460.9  5912.9  459.75  5985.5  459.81  6401.5  463.97
#Mann= 3 ,-1 , 0
  3860.7     .05       0  5019.2     .05       0  5023.2     .05       0
Bank Sta=5019.2,5023.2
XS Rating Curve= 0 ,0
Exp/Cntr=0.3,0.1

Type RM Length L Ch R = 1 ,15933   ,649,649,649
BEGIN DESCRIPTION:
Mapping XS a72f28d8
END DESCRIPTION:
XS GIS Cut Line= 3
      2738642.94      6920369.34      2738010.95      6920612.41
      2737010.98      6921341.56
#Sta/Elev= 30
  4341.9  463.17  4370.8  463.31  4424.3  461.43  4477.9  461.48  4581.5  458.94
  4666.1  458.71  4720.8  457.15  4895.8  457.16  4944.7  456.37  4950.1  456.25
    4960  452.99  4972.7  450.18    4973  449.68  4976.7  450.18  4981.5  451.82
  4992.2  451.95  5004.7  456.05    5019  457.89  5049.9  456.54  5072.2  456.54
  5149.5  457.71  5285.5  458.22  5536.5  458.56  5551.2  457.99  5894.2  460.86
  6038.6  461.22  6080.4  462.72  6101.9  461.87  6188.5  462.35  6256.6  463.49
#Mann= 3 ,-1 , 0
  4341.9     .05       0  4972.7     .04       0  4976.7     .05       0
Bank Sta=4972.7,4976.7
XS Rating Curve= 0 ,0
Exp/Cntr=0.3,0.1

Type RM Length L Ch R = 1 ,15284   ,371,371,371
BEGIN DESCRIPTION:
Mapping XS 35285cc1
END DESCRIPTION:
XS GIS Cut Line= 3
      2738754.05      6919911.01      2737601.22      6920202.69
      2736726.83      6921236.69
#Sta/Elev= 30
  3823.4  472.74  4009.5  468.19  4151.5  466.14  4182.4  464.63  4223.7  464.54
  4264.9   462.7  4326.8  462.77  4378.6   460.8  4491.4  460.13  4543.4  458.18
  4737.5  457.11  4865.7  454.93    4956  455.27  4966.4  454.74  4988.7  450.37
  5005.5  448.61  5005.8  448.11  5009.5  448.61  5012.5  448.61  5014.9  450.43
  5029.2  453.62    5050   455.1  5206.8  454.46  5404.9  455.79  5554.4  458.06
  5745.5  458.55  5987.3   461.9  6015.9  460.89  6157.6  463.09  6366.7  463.47
#Mann= 3 ,-1 , 0
  3823.4     .05       0  5005.5     .04       0  5009.5     .05       0
Bank Sta=5005.5,5009.5
XS Rating Curve= 0 ,0
Exp/Cntr=0.3,0.1

Type RM Length L Ch R = 1 ,14913   ,467,467,467
BEGIN DESCRIPTION:
Mapping XS f48a988a
END DESCRIPTION:
XS GIS Cut Line= 3
      2738403.53       6919552.5      2737450.36      6919885.85
      2735899.62      6920463.47
#Sta/Elev= 30
  3990.3  469.97    4028  469.07  4033.3  470.29    4059  468.13  4064.3  468.83
    4090  465.94  4177.9  463.56  4612.7  458.85  4686.9  458.89    4867  454.12
  4962.3  453.22  4983.5  451.43  4997.4   446.1  4997.9   445.6    5002   446.1
  5005.3  446.25  5015.4  449.68  5036.7  451.82  5055.3  452.42  5110.6  452.96
  5115.9  452.27  5171.3  453.75  5513.9   458.1  6008.2     462  6050.5  463.44
  6063.5  462.49  6082.5  463.37  6242.6  464.42  6577.5  468.65  6654.9  470.87
#Mann= 3 ,-1 , 0
  3990.3     .05       0  4997.4     .05       0    5002     .05       0
Bank Sta=4997.4,5002
XS Rating Curve= 0 ,0
Exp/Cntr=0.3,0.1

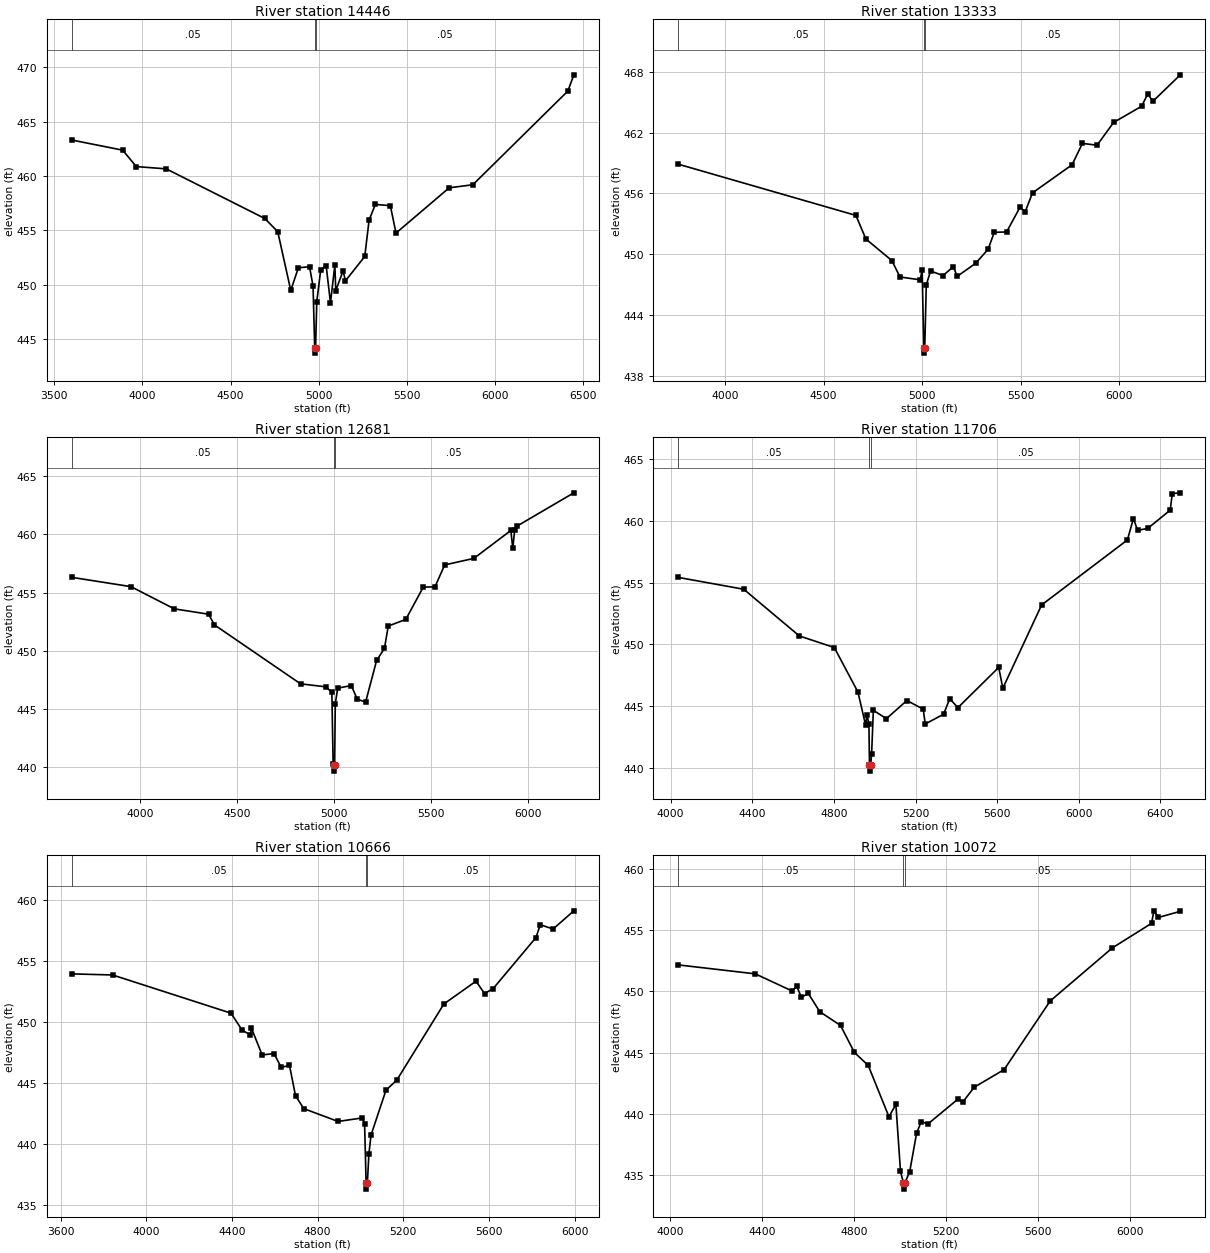
Type RM Length L Ch R = 1 ,14446   ,1113,1113,1113
BEGIN DESCRIPTION:
Mapping XS a2a8909c
END DESCRIPTION:
XS GIS Cut Line= 4
      2738481.59      6918838.99      2738153.48      6919182.72
      2737257.65       6919479.6      2735924.34      6919990.01
#Sta/Elev= 30
    3600  463.31  3888.3  462.38    3966  460.87  4135.7  460.66  4694.5   456.1
  4767.8  454.89  4841.6  449.49  4884.7  451.57  4948.1  451.67    4968  449.88
  4977.3  444.23  4977.9  443.73  4982.2  444.23  4989.1  448.46  5011.4  451.38
  5042.2  451.78  5066.8  448.35  5091.5  451.81  5096.9  449.48  5138.5   451.3
  5151.6  450.37  5261.1  452.61  5285.8  455.96  5321.2  457.39  5406.2  457.28
  5438.3  454.76  5739.8  458.92    5874   459.2  6412.7  467.81  6446.6   469.3
#Mann= 3 ,-1 , 0
    3600     .05       0  4977.3    .035       0  4982.2     .05       0
Bank Sta=4977.3,4982.2
XS Rating Curve= 0 ,0
Exp/Cntr=0.3,0.1

Type RM Length L Ch R = 1 ,13333   ,652,652,652
BEGIN DESCRIPTION:
Mapping XS 3fa90194
END DESCRIPTION:
XS GIS Cut Line= 3
      2738294.07      6918755.63      2737106.61      6918547.31
      2735835.81      6918979.59
#Sta/Elev= 30
    3762  458.89  4663.6  453.84  4714.4  451.51  4846.4  449.38    4887  447.77
  4989.3  447.49  4999.9  448.43    5008  440.76  5008.6  440.26    5013  440.76
  5020.7  446.97  5042.2  448.36  5105.6  447.91  5158.4  448.78  5177.6  447.83
  5271.7  449.12  5334.4   450.5  5365.8  452.17  5428.5  452.21  5496.5  454.65
  5522.6  454.19  5559.8  456.06  5760.4  458.83  5813.3  460.94  5887.2  460.76
  5971.7  463.01  6113.4   464.6  6144.7  465.81  6170.8  465.09  6309.9   467.7
#Mann= 3 ,-1 , 0
    3762     .05       0    5008     .05       0    5013     .05       0
Bank Sta=5008,5013
XS Rating Curve= 0 ,0
Exp/Cntr=0.3,0.1

Type RM Length L Ch R = 1 ,12681   ,975,975,975
BEGIN DESCRIPTION:
Mapping XS e11e6452
END DESCRIPTION:
XS GIS Cut Line= 3
      2738314.96      6918156.69      2736965.98      6917974.39
      2735742.01      6918068.14
#Sta/Elev= 30
  3648.9  456.31  3954.2  455.51  4177.2   453.6  4354.2  453.14  4384.5  452.22
  4828.5  447.15  4959.7  446.89  4989.9  446.41  4996.6  440.25    4999  440.14
  4999.7  439.64  5004.2  440.14  5007.6  445.44  5020.2  446.78  5090.4     447
  5120.4  445.84  5163.9  445.57  5220.7  449.16  5260.9  450.19  5280.9  452.12
  5371.2  452.69  5461.4  455.47  5521.6  455.49  5571.8  457.38  5722.2  457.94
  5912.8  460.34  5922.8   458.8  5932.8   460.4  5942.8   460.7  6237.7  463.58
#Mann= 3 ,-1 , 0
  3648.9     .05       0    4999     .05       0  5004.2     .05       0
Bank Sta=4999,5004.2
XS Rating Curve= 0 ,0
Exp/Cntr=0.3,0.1

Type RM Length L Ch R = 1 ,11706   ,1040,1040,1040
BEGIN DESCRIPTION:
Mapping XS 24a5a53b
END DESCRIPTION:
XS GIS Cut Line= 3
      2738195.19      6917849.41      2737346.19      6917380.64
      2735856.59      6917396.27
#Sta/Elev= 30
  4037.7  455.43  4358.7  454.47  4630.8  450.69  4802.1  449.75  4917.9  446.15
  4955.7  443.46    4962  444.31  4971.7  443.57  4974.6  440.24  4975.5  439.74
  4980.4  440.24  4984.9   441.1  4993.5  444.66  5057.7  443.99  5157.7  445.46
  5237.7  444.76  5247.7  443.56  5337.7  444.35  5367.7  445.61  5407.7  444.88
  5607.7  448.14  5627.7  446.45  5817.8   453.2  6237.8  458.46  6267.8   460.2
  6287.8  459.24  6337.8   459.4  6447.8  460.88  6457.8  462.22  6497.2  462.28
#Mann= 3 ,-1 , 0
  4037.7     .05       0  4974.6     .05       0  4980.4     .05       0
Bank Sta=4974.6,4980.4
XS Rating Curve= 0 ,0
Exp/Cntr=0.3,0.1

Type RM Length L Ch R = 1 ,10666   ,594,594,594
BEGIN DESCRIPTION:
Mapping XS bff7749d
END DESCRIPTION:
XS GIS Cut Line= 3
      2738269.11      6917060.97      2736980.09      6916683.38
      2735979.21      6916661.71
#Sta/Elev= 30
  3652.2  453.98  3842.8  453.89  4395.3  450.76  4447.3  449.38  4485.9  448.97
  4491.2  449.52  4541.2  447.33  4596.6  447.45    4630  446.31  4668.7  446.48
  4696.9  443.99  4735.5  442.93  4895.5  441.88  5009.5  442.17  5019.5  441.68
  5026.5  436.83  5027.5  436.33  5032.4  436.83  5039.5  439.22  5049.5  440.76
  5119.5  444.45  5169.5  445.26  5389.6  451.51  5539.6  453.38  5579.6  452.37
  5619.6  452.77  5819.7  456.96  5839.7  458.01  5899.7  457.66  5996.5  459.15
#Mann= 3 ,-1 , 0
  3652.2     .05       0  5026.5    .035       0  5032.4     .05       0
Bank Sta=5026.5,5032.4
XS Rating Curve= 0 ,0
Exp/Cntr=0.3,0.1

Type RM Length L Ch R = 1 ,10072   ,190,190,190
BEGIN DESCRIPTION:
Mapping XS 6dcdbbb2
END DESCRIPTION:
XS GIS Cut Line= 3
      2738230.12      6916258.03      2737249.19      6916218.97
      2736051.23      6916227.65
#Sta/Elev= 30
    4037  452.16  4371.4  451.43  4531.5  450.03  4551.5  450.43  4571.5  449.51
  4601.6  449.83  4651.6  448.34  4741.7  447.22  4801.7  445.02  4861.8  443.96
  4951.8  439.77  4981.9  440.78  5001.9  435.32  5014.8  434.37  5015.8  433.87
  5020.9  434.37  5041.9   435.3  5071.9  438.44  5091.9  439.36  5121.9   439.2
  5251.9  441.22  5271.9  440.96  5321.9  442.18  5451.9  443.62  5651.9  449.22
  5921.9  453.55  6091.9  455.55  6101.9  456.57  6121.9  456.03  6216.7  456.53
#Mann= 3 ,-1 , 0
    4037     .05       0  5014.8     .03       0  5020.9     .05       0
Bank Sta=5014.8,5020.9
XS Rating Curve= 0 ,0
Exp/Cntr=0.3,0.1

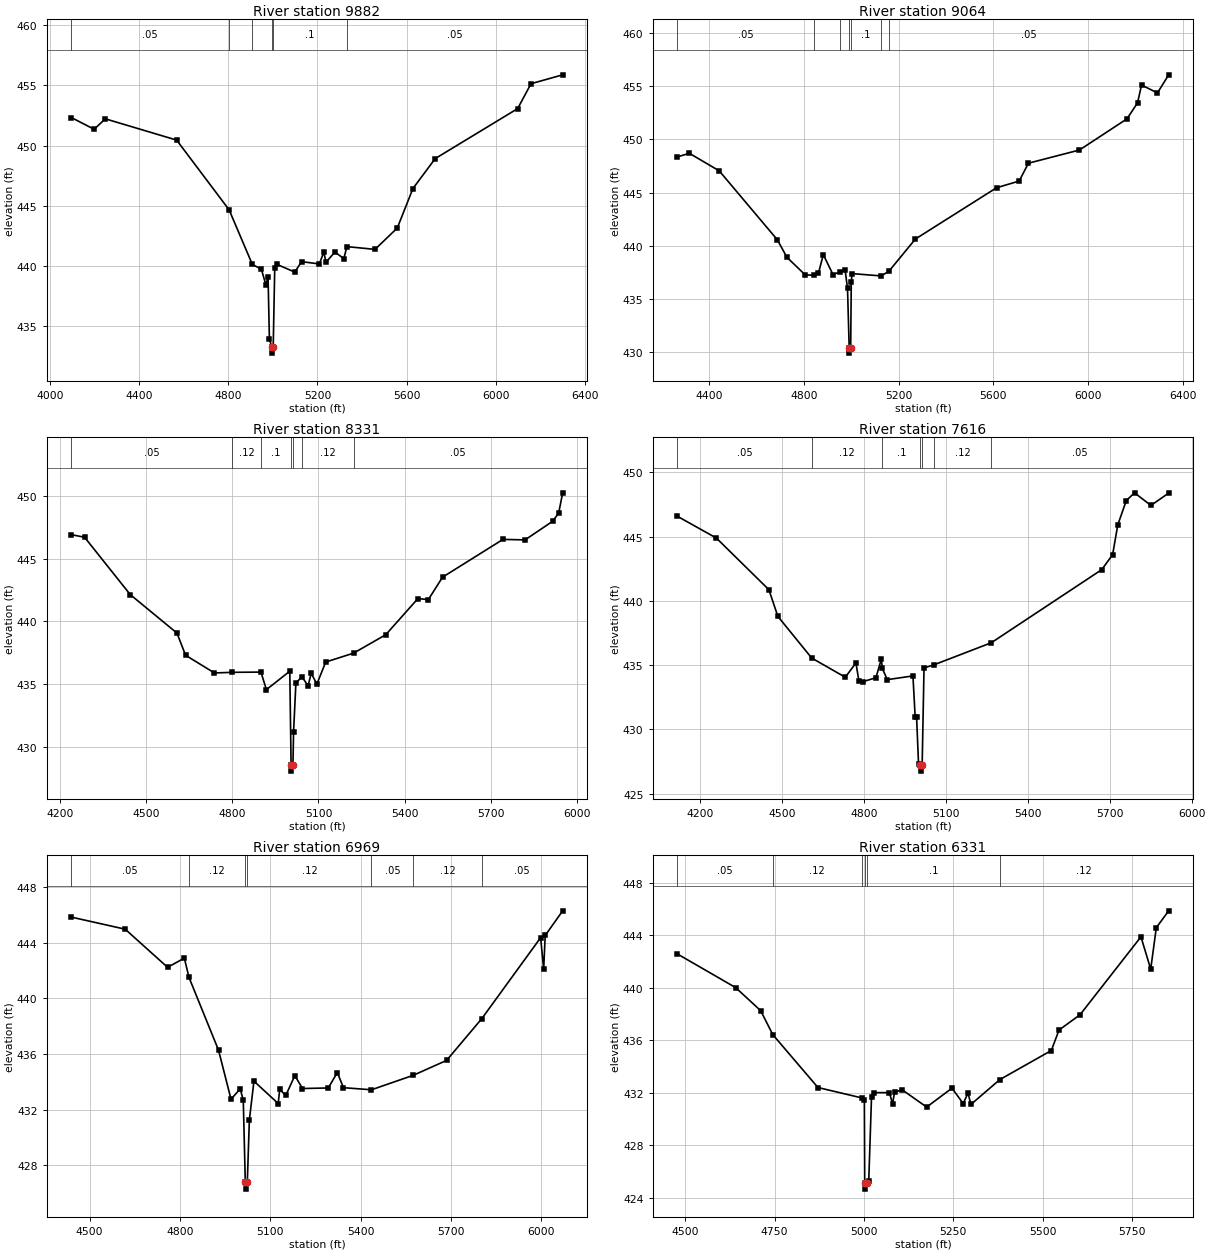
Type RM Length L Ch R = 1 ,9882    ,818,818,818
BEGIN DESCRIPTION:
Mapping XS 71dc4e88
END DESCRIPTION:
XS GIS Cut Line= 3
      2738238.77      6916088.76      2737349.01      6916054.03
      2736033.92      6916032.33
#Sta/Elev= 30
  4095.2  452.33    4198  451.35  4248.1  452.22  4568.3  450.45  4803.8  444.65
    4908  440.11  4948.6  439.71  4968.6  438.42  4978.6  439.08  4984.6  433.91
  4995.6  433.23  4996.6  432.73  5001.7  433.23  5008.6  439.85  5018.6  440.11
  5098.7  439.47  5128.7  440.34  5208.7  440.15  5228.7  441.13  5238.7  440.29
  5278.7  441.14  5318.7  440.59  5332.4  441.59  5458.7  441.36  5558.7  443.14
  5628.7  446.42  5728.7  448.91  6098.8  453.07  6158.8  455.14  6300.9  455.88
#Mann= 6 ,-1 , 0
  4095.2     .05       0  4803.8     .12       0    4908      .1       0
  4995.6     .07       0  5001.7      .1       0  5332.4     .05       0
Bank Sta=4995.6,5001.7
XS Rating Curve= 0 ,0
Exp/Cntr=0.3,0.1

Type RM Length L Ch R = 1 ,9064    ,733,733,733
BEGIN DESCRIPTION:
Mapping XS 11348ff5
END DESCRIPTION:
XS GIS Cut Line= 3
      2737999.43      6915215.18      2737274.59       6915367.1
      2736078.05       6915956.7
#Sta/Elev= 30
    4266  448.36  4317.1   448.7  4443.2  447.05  4688.4  440.57  4729.3  438.91
  4806.1  437.27    4844  437.23  4862.1  437.44  4882.5  439.17  4923.4   437.3
  4952.2  437.55  4974.5  437.73  4984.7     436  4991.8  430.41  4992.8  429.91
  4998.1  430.41  5000.6  436.63  5003.9  437.39  5126.4  437.17  5159.1   437.6
  5271.3  440.64  5613.8  445.46  5709.2  446.09  5748.5  447.77  5963.8  449.01
  6164.4  451.94    6209  453.44  6225.8  455.12  6293.1  454.38  6340.5  456.08
#Mann= 7 ,-1 , 0
    4266     .05       0    4844     .12       0  4952.2      .1       0
  4991.8     .07       0  4998.1      .1       0  5126.4     .12       0
  5159.1     .05       0
Bank Sta=4991.8,4998.1
XS Rating Curve= 0 ,0
Exp/Cntr=0.3,0.1

Type RM Length L Ch R = 1 ,8331    ,715,715,715
BEGIN DESCRIPTION:
Mapping XS b3dd66be
END DESCRIPTION:
XS GIS Cut Line= 3
      2737882.26      6914746.43      2737144.39      6914815.88
      2736232.88      6915145.76
#Sta/Elev= 30
  4239.4  446.92  4285.9  446.71  4444.9  442.14  4607.3  439.08  4637.4  437.31
  4737.9   435.9  4798.3  435.95  4899.7  435.97  4918.7  434.57  5000.1  436.04
  5004.6  428.58  5005.6  428.08  5011.1  428.58  5013.2  431.18  5021.4  435.11
  5042.6  435.59  5063.8  434.87  5074.5  435.87  5094.5  435.02  5125.1  436.77
  5222.2  437.48  5334.3  438.95  5446.2  441.83  5482.2  441.74  5531.8  443.53
  5742.1  446.54    5819   446.5  5914.7  447.98  5935.9  448.63  5949.9  450.25
#Mann= 7 ,-1 , 0
  4239.4     .05       0  4798.3     .12       0  4899.7      .1       0
  5004.6     .07       0  5011.1      .1       0  5042.6     .12       0
  5222.2     .05       0
Bank Sta=5004.6,5011.1
XS Rating Curve= 0 ,0
Exp/Cntr=0.3,0.1

Type RM Length L Ch R = 1 ,7616    ,647,647,647
BEGIN DESCRIPTION:
Mapping XS cf27674e
END DESCRIPTION:
XS GIS Cut Line= 3
      2737843.19      6914542.45       2737005.5      6914290.71
      2736081.02      6914347.13
#Sta/Elev= 30
  4114.9  446.59  4258.2  444.89  4450.7  440.87  4483.7  438.79  4607.7  435.55
  4730.6  434.06  4769.8  435.17  4780.2   433.8  4796.7  433.72  4842.9  434.02
  4862.8  435.47  4866.3  434.74  4884.7  433.87  4978.6  434.16  4986.7  430.98
  4991.9  430.98  4999.1  427.31  5005.8  427.25  5006.9  426.75  5012.4  427.25
  5019.2  434.78  5055.1  435.02  5265.6  436.74  5670.4  442.43  5710.4   443.6
  5729.3  445.92  5760.5  447.81  5790.6  448.41  5850.7  447.43  5915.8  448.39
#Mann= 7 ,-1 , 0
  4114.9     .05       0  4607.7     .12       0  4866.3      .1       0
  5005.8     .07       0  5012.4      .1       0  5055.1     .12       0
  5265.6     .05       0
Bank Sta=5005.8,5012.4
XS Rating Curve= 0 ,0
Exp/Cntr=0.3,0.1

Type RM Length L Ch R = 1 ,6969    ,638,638,638
BEGIN DESCRIPTION:
Mapping XS 2d64fd76
END DESCRIPTION:
XS GIS Cut Line= 3
      2737819.32      6914037.53      2737289.78      6913898.63
       2736213.4      6914033.18
#Sta/Elev= 30
    4439  445.83  4618.2  444.96    4759  442.22  4814.6  442.88  4830.2  441.49
  4928.3  436.26  4969.7  432.74  5000.3  433.49  5010.4  432.66  5017.1  426.78
  5018.2  426.28  5023.8  426.78  5030.6  431.24  5045.8  434.04  5126.4  432.43
  5131.4  433.45  5151.5  433.01  5181.7  434.44    5207  433.51  5292.7  433.55
  5322.8  434.66    5343  433.57  5436.2  433.42  5574.9  434.46  5685.6  435.53
  5802.9  438.54    5998  444.35  6008.1  442.09  6013.2  444.51  6071.2  446.28
#Mann= 7 ,-1 , 0
    4439     .05       0  4830.2     .12       0  5017.1     .07       0
  5023.8     .12       0  5436.2     .05       0  5574.9     .12       0
  5802.9     .05       0
Bank Sta=5017.1,5023.8
XS Rating Curve= 0 ,0
Exp/Cntr=0.3,0.1

Type RM Length L Ch R = 1 ,6331    ,655,655,655
BEGIN DESCRIPTION:
Mapping XS 81a8c6c3
END DESCRIPTION:
XS GIS Cut Line= 3
      2737489.39      6913486.31       2736968.6      6913503.67
      2736230.86       6913933.3
#Sta/Elev= 30
  4477.7  442.57  4641.2     440  4711.2  438.24  4744.9  436.42  4871.3  432.39
  4993.7   431.6  5001.1  431.46  5002.1  425.15  5003.2  424.65  5008.8  425.15
  5013.4  425.29  5021.2   431.7    5027     432  5071.2     432    5080  431.15
  5085.7  432.04  5107.2  432.21  5175.4   430.9  5246.2  432.34  5277.7  431.17
  5291.1  431.97  5299.2   431.1  5379.9  432.99  5524.2  435.21  5545.7  436.77
  5604.4  437.93  5774.9  443.87  5802.2  441.41  5817.9  444.57  5852.5  445.85
#Mann= 6 ,-1 , 0
  4477.7     .05       0  4744.9     .12       0  4993.7      .1       0
  5002.1     .07       0  5008.8      .1       0  5379.9     .12       0
Bank Sta=5002.1,5008.8
XS Rating Curve= 0 ,0
Exp/Cntr=0.3,0.1

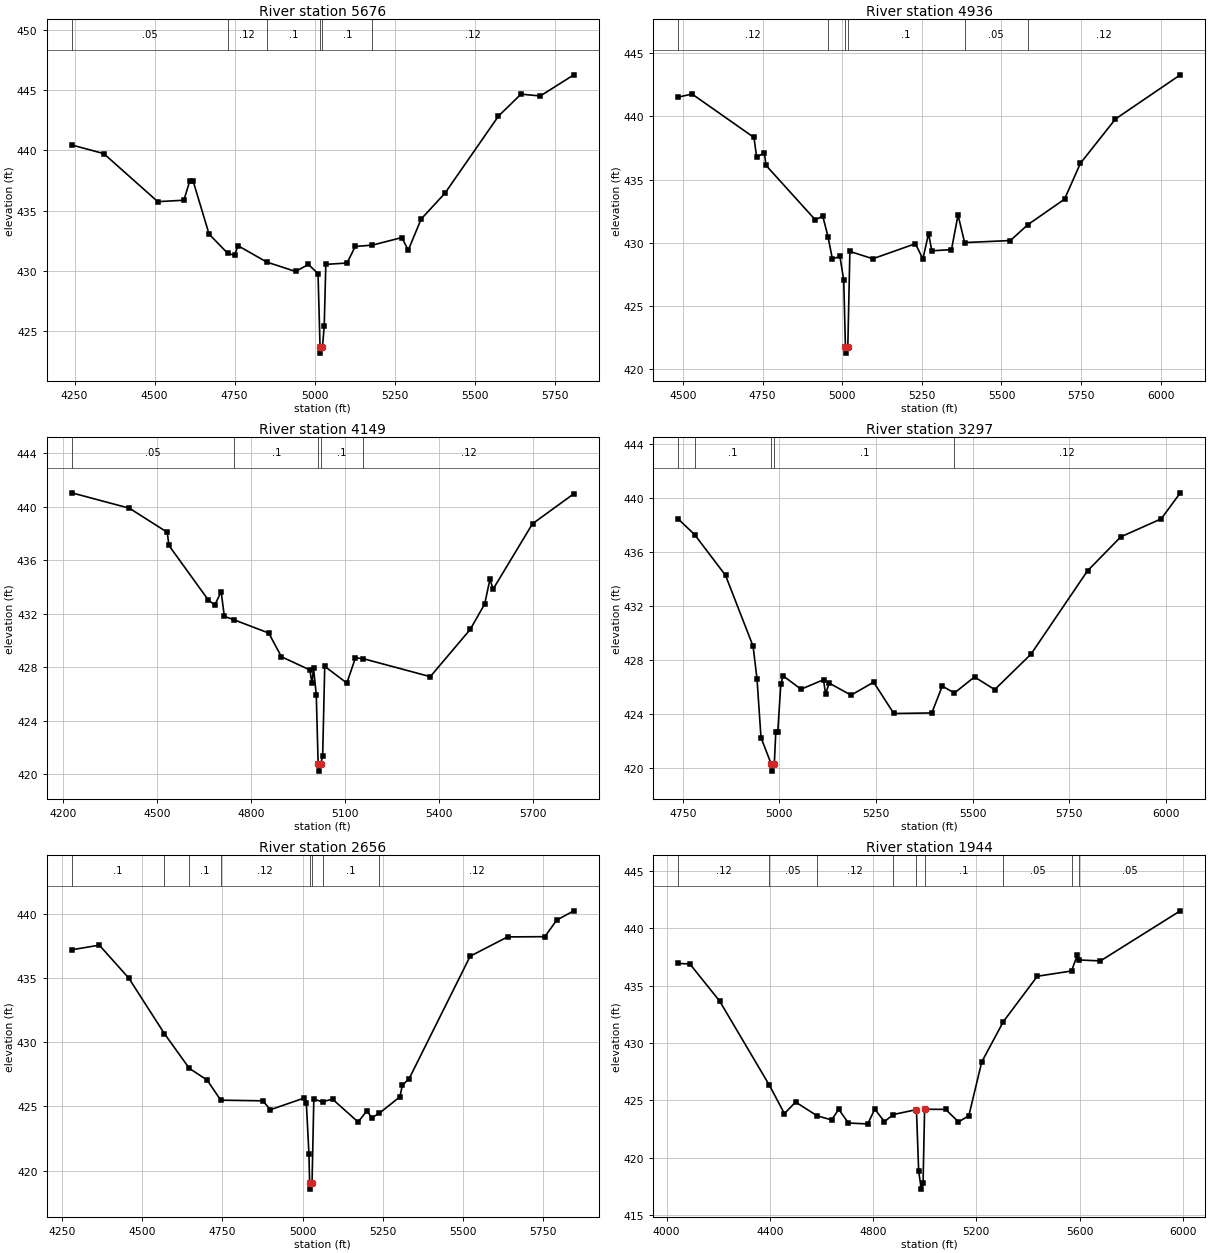
Type RM Length L Ch R = 1 ,5676    ,740,740,740
BEGIN DESCRIPTION:
Mapping XS 0481ab8f
END DESCRIPTION:
XS GIS Cut Line= 3
      2737424.38      6913199.85      2736664.78      6913169.47
      2735861.87      6913082.67
#Sta/Elev= 30
  4241.3  440.46  4341.2  439.74  4509.9  435.74  4591.4  435.86    4610  437.49
    4620  437.48    4670  433.04  4728.6  431.43  4750.1  431.28  4760.1  432.08
  4850.2  430.71  4940.2  429.93  4980.3  430.51  5010.3  429.75  5016.6  423.63
  5017.8  423.13  5024.1  423.63  5029.6  425.38  5034.6  430.52  5100.9  430.63
  5126.4  432.01  5179.6  432.12  5271.9  432.75    5292   431.7  5332.2  434.29
  5406.8  436.45  5573.6  442.86    5644  444.69  5704.4  444.54  5809.1   446.3
#Mann= 6 ,-1 , 0
  4241.3     .05       0  4728.6     .12       0  4850.2      .1       0
  5016.6     .07       0  5024.1      .1       0  5179.6     .12       0
Bank Sta=5016.6,5024.1
XS Rating Curve= 0 ,0
Exp/Cntr=0.3,0.1

Type RM Length L Ch R = 1 ,4936    ,787,787,787
BEGIN DESCRIPTION:
Mapping XS c060c449
END DESCRIPTION:
XS GIS Cut Line= 4
      2737446.07      6912910.51       2736968.6      6912715.19
      2736469.47      6912593.66      2735922.59      6912615.36
#Sta/Elev= 30
  4484.9  441.53  4528.4  441.77  4722.7  438.34  4731.3  436.76  4755.1  437.14
  4760.7  436.13  4915.6  431.82  4938.8  432.13  4955.4  430.48    4969  428.74
  4992.8  428.93  5004.7  427.04    5010  421.79  5011.2  421.29  5017.5  421.79
    5024  429.33  5096.1  428.75  5229.9  429.94  5253.3  428.73  5271.1  430.74
  5281.3  429.38  5343.1  429.47  5363.7  432.21  5384.3  430.03    5528  430.19
  5582.3  431.43  5698.1  433.46  5748.1   436.3  5858.2   439.8  6061.8  443.29
#Mann= 6 ,-1 , 0
  4484.9     .12       0  4955.4      .1       0    5010     .07       0
  5017.5      .1       0  5384.3     .05       0  5582.3     .12       0
Bank Sta=5010,5017.5
XS Rating Curve= 0 ,0
Exp/Cntr=0.3,0.1

Type RM Length L Ch R = 1 ,4149    ,852,852,852
BEGIN DESCRIPTION:
Mapping XS 891d9d74
END DESCRIPTION:
XS GIS Cut Line= 3
      2737537.19      6912233.42      2736751.59      6912111.89
      2735980.02      6912350.29
#Sta/Elev= 30
  4227.5  441.03  4411.4  439.88  4532.3  438.08  4537.5   437.1  4663.6  433.01
  4684.1  432.65  4704.3  433.64  4714.4   431.8  4746.4  431.53  4856.1  430.55
  4896.6  428.78  4987.6  427.79  4994.1  426.78  4999.2  427.91  5007.9  425.95
  5013.9  420.73  5015.1  420.23  5021.5  420.73  5028.3  421.38  5034.9  428.06
  5105.5  426.81  5132.9   428.7  5158.5  428.63  5371.8  427.29  5499.3  430.82
  5545.4  432.72  5562.1  434.56  5572.5  433.84  5698.1  438.72    5830  440.96
#Mann= 5 ,-1 , 0
  4227.5     .05       0  4746.4      .1       0  5013.9     .07       0
  5021.5      .1       0  5158.5     .12       0
Bank Sta=5013.9,5021.5
XS Rating Curve= 0 ,0
Exp/Cntr=0.3,0.1

Type RM Length L Ch R = 1 ,3297    ,641,641,641
BEGIN DESCRIPTION:
Flat T3 2.0
END DESCRIPTION:
XS GIS Cut Line= 3
      2737175.97      6911461.01        2736926.        6911511.
      2735926.05      6911810.99
#Sta/Elev= 30
  4738.4  438.47  4780.6  437.32  4860.7   434.3  4932.1  429.04  4942.3  426.58
  4952.5  422.28  4979.3  420.29  4980.5  419.79  4986.9  420.29  4990.8   422.7
  4995.9   422.7  5003.8  426.25  5009.8  426.85    5056  425.86  5114.3  426.56
  5119.5  425.51    5129  426.31  5185.6  425.42  5243.9  426.38  5296.1  424.06
  5394.4   424.1  5421.4  426.09  5452.9  425.58  5504.9  426.77  5557.1  425.83
  5651.1  428.46  5797.2  434.63  5883.4  437.15  5987.8  438.48  6037.3  440.41
#Mann= 5 ,-1 , 0
  4738.4     .12       0  4780.6      .1       0  4979.3     .07       0
  4986.9      .1       0  5452.9     .12       0
Bank Sta=4979.3,4986.9
XS Rating Curve= 0 ,0
Exp/Cntr=0.3,0.1

Type RM Length L Ch R = 1 ,2656    ,712,712,712
BEGIN DESCRIPTION:
Mapping XS 6d0385c0
END DESCRIPTION:
XS GIS Cut Line= 3
      2737220.33      6911226.47      2736608.36      6911104.94
      2735801.04      6911591.07
#Sta/Elev= 30
  4279.9  437.18  4365.9  437.54  4457.6  434.98  4568.8  430.66  4646.4  427.96
  4702.3  427.04  4744.6  425.48  4875.6  425.43  4899.8  424.74  5004.3  425.64
  5011.6  425.29  5019.8  421.29  5021.9  419.06    5023  418.56  5029.5  419.06
    5035  425.54  5062.8  425.36  5093.3  425.56  5173.2  423.78  5200.4  424.65
    5216  424.11  5239.6  424.47  5303.5  425.74  5311.1  426.63  5332.5  427.16
  5522.8  436.68  5639.3  438.18  5755.8   438.2  5792.7  439.49  5846.2  440.21
#Mann= 8 ,-1 , 0
  4279.9      .1       0  4568.8     .12       0  4646.4      .1       0
  4744.6     .12       0  5021.9     .07       0  5029.5     .12       0
  5062.8      .1       0  5239.6     .12       0
Bank Sta=5021.9,5029.5
XS Rating Curve= 0 ,0
Exp/Cntr=0.3,0.1

Type RM Length L Ch R = 1 ,1944    ,618,618,618
BEGIN DESCRIPTION:
Mapping XS 9861b87c
END DESCRIPTION:
XS GIS Cut Line= 3
       2737155.2      6911061.52      2736317.56      6910584.11
       2735336.7      6910588.45
#Sta/Elev= 30
  4045.2  436.94  4090.3  436.89  4205.4  433.66  4398.5   426.3  4456.6  423.83
  4499.8  424.84  4583.2  423.64  4639.5  423.28  4666.9  424.21  4704.3  423.01
  4779.3  422.93  4806.6  424.22  4844.1  423.13  4878.1  423.75    4968  424.18
  4976.6  418.82  4986.7  417.24  4993.6  417.74  4999.6  424.21  5080.9   424.2
  5130.9  423.11  5170.9  423.64  5220.9  428.34  5304.7  431.86  5436.3  435.82
  5568.8  436.28  5590.9  437.65  5596.9  437.24  5680.9  437.16  5990.2  441.53
#Mann= 9 ,-1 , 0
  4045.2     .12       0  4398.5     .05       0  4583.2     .12       0
  4878.1      .1       0    4968     .07       0  4999.6      .1       0
  5304.7     .05       0  5568.8     .12       0  5596.9     .05       0
Bank Sta=4968,4999.6
XS Rating Curve= 0 ,0
Exp/Cntr=0.3,0.1

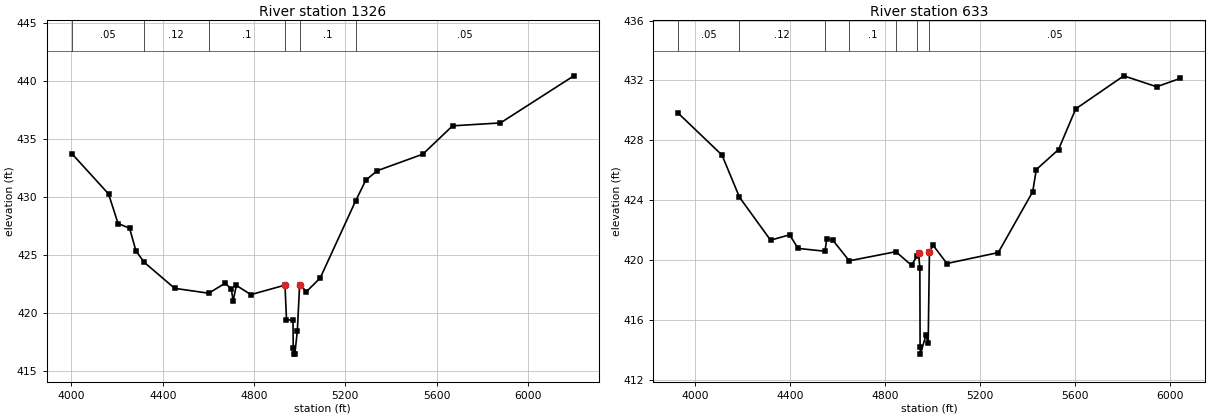
Type RM Length L Ch R = 1 ,1326    ,693,693,693
BEGIN DESCRIPTION:
Mapping XS 8e3d5587
END DESCRIPTION:
XS GIS Cut Line= 3
       2737128.7      6910824.82      2736496.79      6910078.32
      2735274.53      6910047.07
#Sta/Elev= 30
  4001.2  433.77  4162.4  430.29  4204.1  427.74  4254.7  427.33  4282.1   425.4
  4317.3  424.42  4452.4  422.15  4601.5  421.73  4673.2  422.59  4700.6   422.1
  4708.4  421.07  4722.7   422.4  4786.4  421.61  4935.8  422.43  4942.4  419.45
    4971  419.39  4971.9  416.98  4973.1  416.48  4978.9  416.48    4990   418.5
    5000  422.48    5030  421.87  5090.1  423.04  5245.2  429.68  5290.1  431.48
  5340.2  432.29  5540.2  433.72  5670.3  436.16  5880.3  436.41  6201.9  440.47
#Mann= 6 ,-1 , 0
  4001.2     .05       0  4317.3     .12       0  4601.5      .1       0
  4935.8     .07       0    5000      .1       0  5245.2     .05       0
Bank Sta=4935.8,5000
XS Rating Curve= 0 ,0
Exp/Cntr=0.3,0.1

Type RM Length L Ch R = 1 ,633     ,0,0,0
BEGIN DESCRIPTION:
Flat T3 1.0
END DESCRIPTION:
XS GIS Cut Line= 3
      2737100.96       6910599.2      2736827.77      6909565.18
      2735952.42      6908995.49
#Sta/Elev= 30
  3930.5  429.81  4114.8  427.01  4188.4  424.19  4319.2  421.32  4399.7  421.68
  4434.8  420.77  4548.4  420.58  4555.6  421.39  4580.3  421.34  4650.5  419.94
    4847  420.55  4912.7  419.64    4937  420.29  4942.3  420.47  4947.8  419.44
  4948.8   414.2    4950   413.7  4973.3  414.96  4982.9  414.46  4988.1  420.54
    5004  420.97  5061.8  419.76    5278  420.49  5422.9  424.56    5438  426.04
  5531.6  427.38  5604.1   430.1  5806.3  432.31  5944.7  431.58  6044.4  432.14
#Mann= 7 ,-1 , 0
  3930.5     .05       0  4188.4     .12       0  4548.4      .1       0
  4650.5      .1       0    4847     .07       0    4937     .05       0
  4988.1     .05       0
Bank Sta=4942.3,4988.1
XS Rating Curve= 0 ,0
Exp/Cntr=0.3,0.1

Chan Stop Cuts=-1
Use User Specified Reach Order=0
Composite Channel Slope=5