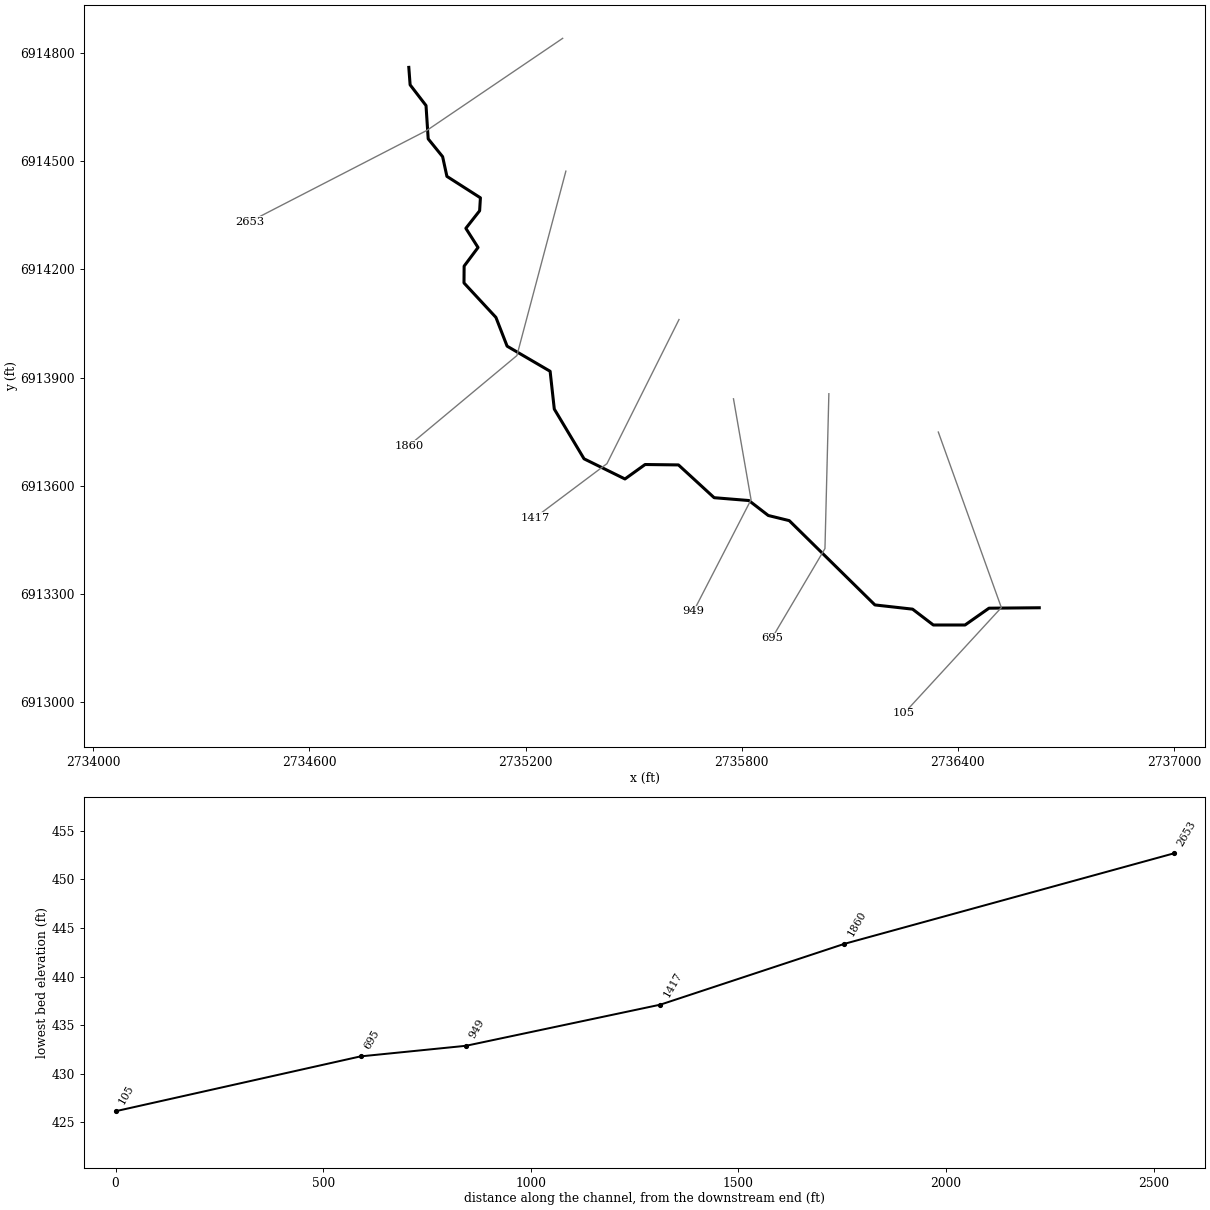
--- Flat T3_1.prj (project) ---

Proj Title=Flat T3_1 Base Level Engineering
Current Plan=p01
Default Exp/Contr=0.3,0.1
English Units
Geom File=g01
Flow File=f01
Plan File=p01
BEGIN DESCRIPTION:
Flat T3_1
END DESCRIPTION:

--- Flat T3_1.p01 (plan) ---

Plan Title=Multiple Run
Short Identifier=Multiple
Geom File=g01
Flow File=f01
Subcritical Flow
K Sum by GR= 0
Std Step Tol= 0.01
Critical Tol= 0.01
Num of Std Step Trials= 20
Max Error Tol= 0.3
Flow Tol Ratio= 0.001
Split Flow NTrial= 30
Split Flow Tol= 0.02
Split Flow Ratio= 0.02
Log Output Level= 0
Friction Slope Method= 1
Unsteady Friction Slope Method= 2
Unsteady Bridges Friction Slope Method= 1
Parabolic Critical Depth
Global Vel Dist=  1 , 1 , 1
Global Log Level= 0
CheckData=True
Encroach Param= -1, 0, 0, 0
BEGIN DESCRIPTION:
Multiple Run
END DESCRIPTION:

--- Flat T3_1.f01 (steady flow) ---

Flow Title=Multiple
Number of Profiles=7
Profile Names=10-year,25-year,50-year,1pct_min,100-year,1pct_plu,500-year
River Rch & RM= Flat T3_1,Reach-1,2653
     263     332     384     222     443     883     584
Boundary for River Rch & Prof#=Flat T3_1,Reach-1,1
Up Type=0
Dn Type=3
Dn Slope=0.005
Boundary for River Rch & Prof#=Flat T3_1,Reach-1,2
Up Type=0
Dn Type=3
Dn Slope=0.005
Boundary for River Rch & Prof#=Flat T3_1,Reach-1,3
Up Type=0
Dn Type=3
Dn Slope=0.005
Boundary for River Rch & Prof#=Flat T3_1,Reach-1,4
Up Type=0
Dn Type=3
Dn Slope=0.005
Boundary for River Rch & Prof#=Flat T3_1,Reach-1,5
Up Type=0
Dn Type=3
Dn Slope=0.005
Boundary for River Rch & Prof#=Flat T3_1,Reach-1,6
Up Type=0
Dn Type=3
Dn Slope=0.005
Boundary for River Rch & Prof#=Flat T3_1,Reach-1,7
Up Type=0
Dn Type=3
Dn Slope=0.005

--- Flat T3_1.g01 (geometry) ---

Geom Title=Existing Conditions

River Reach=Flat T3_1,Reach-1
Reach XY= 30
      2734876.00      6914761.00      2734879.64      6914712.51
      2734923.77      6914655.08      2734929.82      6914562.58
      2734969.85      6914513.15      2734981.77      6914458.47
      2735074.76      6914398.96      2735072.58      6914363.01
      2735034.33      6914314.27      2735068.17      6914261.08
      2735029.56      6914209.35      2735029.17      6914162.65
      2735117.81      6914067.02      2735148.87      6913987.17
      2735268.25      6913917.45      2735279.83      6913812.59
      2735362.44      6913674.46      2735475.99      6913618.53
      2735531.90      6913658.64      2735624.50      6913657.53
      2735723.58      6913566.54      2735820.03      6913558.67
      2735873.83      6913517.14      2735932.06      6913502.86
      2736169.83      6913268.86      2736274.40      6913257.14
      2736331.97      6913213.17      2736420.03      6913213.17
      2736486.48      6913259.83      2736626.00      6913261.00

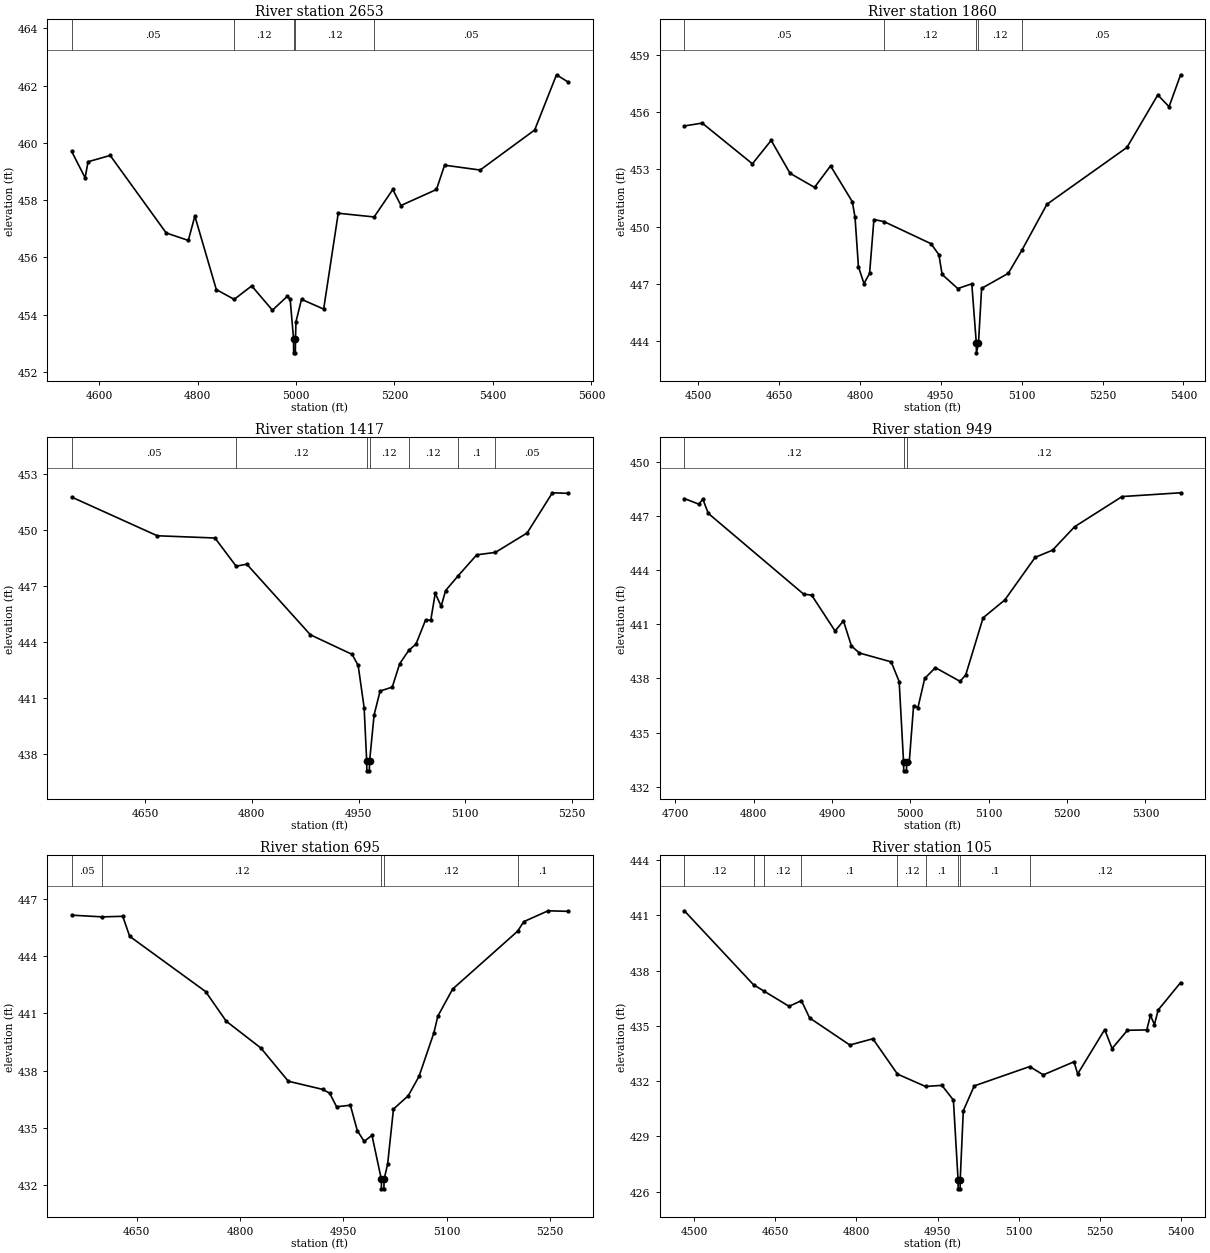
Type RM Length L Ch R = 1,2653,793,793,793
BEGIN DESCRIPTION:
Flat T3_1 5.0
END DESCRIPTION:
XS GIS Cut Line= 3
      2735303.10      6914841.64      2734925.98      6914585.99
      2734435.05      6914332.96
#Sta/Elev= 30
  4544.4  459.70  4571.7  458.78  4577.7  459.34  4622.6  459.56  4736.4  456.85
  4781.3  456.59  4794.6  457.44  4838.2  454.87  4874.5  454.53  4910.1  455.00
  4952.1  454.15  4982.0  454.63  4988.1  454.55  4995.0  453.16  4995.2  452.66
  4998.7  452.66  4999.0  453.16  5000.0  453.75  5011.2  454.53  5056.2  454.19
  5085.8  457.54  5158.7  457.41  5196.6  458.37  5213.2  457.81  5285.3  458.37
  5301.8  459.22  5374.0  459.05  5484.8  460.45  5529.1  462.38  5552.3  462.13
#Mann=5,-1,0
  4544.4    0.05       0  4874.5    0.12       0  4995.0    0.07       0
  4999.0    0.12       0  5158.7    0.05       0
Bank Sta=4995,4999
Exp/Cntr=0.3,0.1

Type RM Length L Ch R = 1,1860,443,443,443
BEGIN DESCRIPTION:
Flat T3_1 4.0
END DESCRIPTION:
XS GIS Cut Line= 3
      2735311.97      6914472.97      2735176.00      6913961.00
      2734876.03      6913711.02
#Sta/Elev= 30
  4474.5  455.29  4507.6  455.44  4600.7  453.30  4635.5  454.53  4670.5  452.80
  4715.9  452.06  4745.6  453.19  4785.9  451.31  4791.0  450.49  4797.3  447.89
  4807.6  447.00  4818.0  447.54  4826.0  450.37  4844.8  450.26  4931.8  449.10
  4946.5  448.52  4952.5  447.48  4981.5  446.74  5007.5  446.99  5015.9  443.86
  5016.1  443.36  5019.9  443.86  5025.7  446.75  5075.2  447.54  5100.9  448.78
  5146.8  451.17  5295.2  454.16  5352.4  456.92  5373.3  456.30  5394.7  457.98
#Mann=5,-1,0
  4474.5    0.05       0  4844.8    0.12       0  5015.9    0.07       0
  5019.9    0.12       0  5100.9    0.05       0
Bank Sta=5015.9,5019.9
Exp/Cntr=0.3,0.1

Type RM Length L Ch R = 1,1417,468,468,468
BEGIN DESCRIPTION:
Flat T3_1 3.0
END DESCRIPTION:
XS GIS Cut Line= 3
      2735626.01      6914061.02      2735426.00      6913661.00
      2735226.03      6913511.02
#Sta/Elev= 30
  4547.0  451.76  4667.2  449.69  4748.3  449.57  4778.1  448.06  4793.0  448.17
  4882.4  444.39  4941.1  443.34  4949.5  442.75  4957.9  440.49  4961.5  437.61
  4961.7  437.11  4965.2  437.11  4965.5  437.61  4971.9  440.10  4980.3  441.38
  4997.4  441.59  5007.8  442.84  5020.7  443.56  5030.7  443.89  5044.2  445.18
  5051.5  445.17  5057.8  446.61  5066.1  445.92  5072.4  446.76  5089.8  447.54
  5116.1  448.67  5142.3  448.80  5186.9  449.84  5222.4  451.99  5244.2  451.96
#Mann=7,-1,0
  4547.0    0.05       0  4778.1    0.12       0  4961.5    0.07       0
  4965.5    0.12       0  5020.7    0.12       0  5089.8     0.1       0
  5142.3    0.05       0
Bank Sta=4961.5,4965.5
Exp/Cntr=0.3,0.1

Type RM Length L Ch R = 1,949,254,254,254
BEGIN DESCRIPTION:
Flat T3_1 2.0
END DESCRIPTION:
XS GIS Cut Line= 3
      2735777.25      6913841.01      2735826.00      6913561.00
      2735666.15      6913250.78
#Sta/Elev= 30
  4711.6  447.97  4730.1  447.66  4735.2  447.94  4742.1  447.15  4863.9  442.67
  4874.0  442.62  4903.9  440.63  4914.6  441.19  4924.8  439.80  4934.9  439.41
  4975.5  438.92  4985.7  437.83  4991.3  433.38  4991.5  432.88  4995.0  432.88
  4995.3  433.38  4998.6  433.38  5004.1  436.49  5009.7  436.39  5018.3  438.00
  5031.9  438.60  5063.3  437.84  5070.6  438.19  5092.8  441.36  5120.5  442.35
  5159.2  444.71  5181.4  445.11  5209.6  446.41  5270.1  448.08  5344.8  448.29
#Mann=3,-1,0
  4711.6    0.12       0  4991.3    0.07       0  4995.3    0.12       0
Bank Sta=4991.3,4995.3
Exp/Cntr=0.3,0.1

Type RM Length L Ch R = 1,695,590,590,590
BEGIN DESCRIPTION:
Mapping XS ccd1040a
END DESCRIPTION:
XS GIS Cut Line= 3
      2736042.00      6913855.11      2736031.15      6913425.39
      2735883.63      6913175.90
#Sta/Elev= 30
  4555.9  446.16  4600.3  446.07  4630.0  446.10  4640.0  445.05  4750.1  442.15
  4780.1  440.59  4830.1  439.19  4870.1  437.44  4920.1  437.01  4930.1  436.81
  4940.1  436.10  4960.1  436.18  4970.1  434.85  4980.1  434.28  4991.4  434.60
  5005.0  432.29  5005.2  431.79  5008.7  431.79  5009.0  432.29  5014.1  433.08
  5022.6  435.98  5044.1  436.68  5059.7  437.70  5081.1  439.97  5087.0  440.86
  5108.4  442.28  5202.7  445.32  5211.6  445.82  5246.9  446.39  5275.6  446.36
#Mann=5,-1,0
  4555.9    0.05       0  4600.3    0.12       0  5005.0    0.07       0
  5009.0    0.12       0  5202.7     0.1       0
Bank Sta=5005,5009
Exp/Cntr=0.3,0.1

Type RM Length L Ch R = 1,105,0,0,0
BEGIN DESCRIPTION:
Flat T3_1 1.0
END DESCRIPTION:
XS GIS Cut Line= 3
      2736345.81      6913748.76      2736520.78      6913261.52
      2736250.67      6912967.85
#Sta/Elev= 30
  4482.3  441.25  4610.2  437.23  4629.9  436.88  4675.8  436.06  4698.5  436.37
  4713.7  435.43  4788.0  433.96  4830.5  434.30  4876.0  432.38  4927.8  431.71
  4958.1  431.77  4979.3  430.97  4987.9  426.65  4988.2  426.15  4991.7  426.15
  4991.9  426.65  4997.6  430.39  5017.8  431.74  5120.2  432.79  5145.4  432.34
  5202.1  433.05  5208.9  432.39  5258.8  434.80  5272.4  433.77  5300.8  434.76
  5336.5  434.78  5343.3  435.57  5350.7  435.07  5357.5  435.86  5399.0  437.35
#Mann=9,-1,0
  4482.3    0.12       0  4610.2     0.1       0  4629.9    0.12       0
  4698.5     0.1       0  4876.0    0.12       0  4927.8     0.1       0
  4987.9    0.07       0  4991.9     0.1       0  5120.2    0.12       0
Bank Sta=4987.9,4991.9
Exp/Cntr=0.3,0.1

Chan Stop Cuts=-1