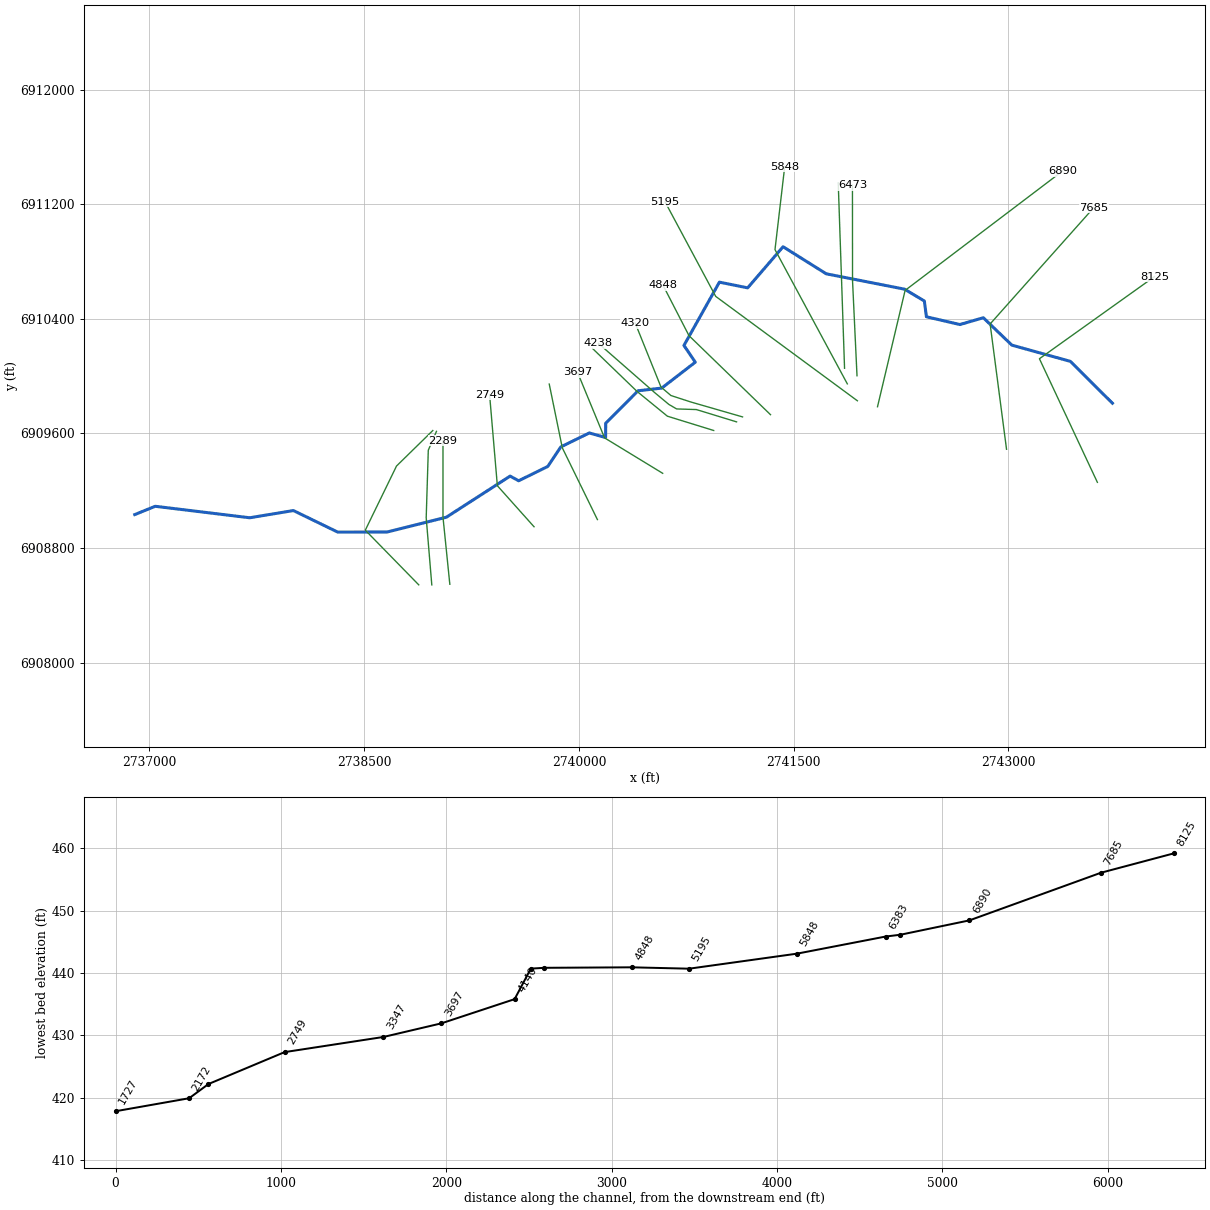
--- Flat T4.prj (project) ---

Proj Title=Flat T4 Base Level Engineering
Current Plan=p01
Default Exp/Contr=0.3,0.1
English Units
Geom File=g01
Flow File=f01
Plan File=p01
Y Axis Title=Elevation
X Axis Title(PF)=Main Channel Distance
X Axis Title(XS)=Station
BEGIN DESCRIPTION:
Flat T4
END DESCRIPTION:
DSS Export Rating Curves= 0
DSS Export Rating Curve Sorted= 0
DSS Export Volume Flow Curves= 0
DXF OffsetX= 0
DXF OffsetY= 0
DXF ScaleX= 1
DXF ScaleY= 10

--- Flat T4.p01 (plan) ---

Plan Title=Multiple Run
Short Identifier=Multiple
Geom File=g01
Flow File=f01
Subcritical Flow
K Sum by GR= 0
Std Step Tol= 0.01
Critical Tol= 0.01
Num of Std Step Trials= 20
Max Error Tol= 0.3
Flow Tol Ratio= 0.001
Split Flow NTrial= 30
Split Flow Tol= 0.02
Split Flow Ratio= 0.02
Log Output Level= 0
Friction Slope Method= 1
Unsteady Friction Slope Method= 2
Unsteady Bridges Friction Slope Method= 1
Parabolic Critical Depth
Global Vel Dist=  1 , 1 , 1
Global Log Level= 0
CheckData=True
Encroach Param= -1, 0, 0, 0
BEGIN DESCRIPTION:
Multiple Run
END DESCRIPTION:

--- Flat T4.f01 (steady flow) ---

Flow Title=Multiple
Program Version=4.10
Number of Profiles= 7
Profile Names=10-year,25-year,50-year,1pct_min,100-year,1pct_plu,500-year
River Rch & RM=Flat T4,Reach-1         ,8125
     282     361     423     247     493     983     668
River Rch & RM=Flat T4,Reach-1         ,4238
     468     619     740     440     878    1752    1238
Boundary for River Rch & Prof#=Flat T4,Reach-1         , 1
Up Type= 0
Dn Type= 3
Dn Slope=0.0092
Boundary for River Rch & Prof#=Flat T4,Reach-1         , 2
Up Type= 0
Dn Type= 3
Dn Slope=0.0092
Boundary for River Rch & Prof#=Flat T4,Reach-1         , 3
Up Type= 0
Dn Type= 3
Dn Slope=0.0092
Boundary for River Rch & Prof#=Flat T4,Reach-1         , 4
Up Type= 0
Dn Type= 3
Dn Slope=0.0092
Boundary for River Rch & Prof#=Flat T4,Reach-1         , 5
Up Type= 0
Dn Type= 3
Dn Slope=0.0092
Boundary for River Rch & Prof#=Flat T4,Reach-1         , 6
Up Type= 0
Dn Type= 3
Dn Slope=0.0092
Boundary for River Rch & Prof#=Flat T4,Reach-1         , 7
Up Type= 0
Dn Type= 3
Dn Slope=0.0092
DSS Import GetInterval= 0
DSS Import GetPeak= 0
DSS Import FillOption= 0

--- Flat T4.g01 (geometry) ---

Geom Title=Existing Conditions
Program Version=4.10

River Reach=Flat T4         ,Reach-1
Reach XY= 30
        2743726.        6909811.      2743432.19      6910103.19
      2743023.57      6910216.52      2742824.37      6910407.87
      2742660.94      6910360.29        2742427.      6910414.54
      2742412.49      6910524.68      2742274.45      6910607.24
      2741727.47      6910714.55       2741425.9      6910903.72
      2741178.43       6910616.4      2740981.25      6910656.38
      2740733.62      6910214.33      2740812.73      6910097.32
      2740578.45      6909916.47      2740412.68      6909897.63
      2740187.25      6909670.99      2740186.39       6909571.2
       2740072.6      6909603.16      2739873.33      6909505.58
      2739782.34      6909369.03      2739579.23      6909269.25
      2739519.33       6909301.7      2739074.44      6909014.76
      2738660.78      6908911.52      2738315.81      6908910.55
      2738005.95      6909061.21      2737700.92       6909010.8
      2737040.79      6909090.96      2736898.12      6909033.09

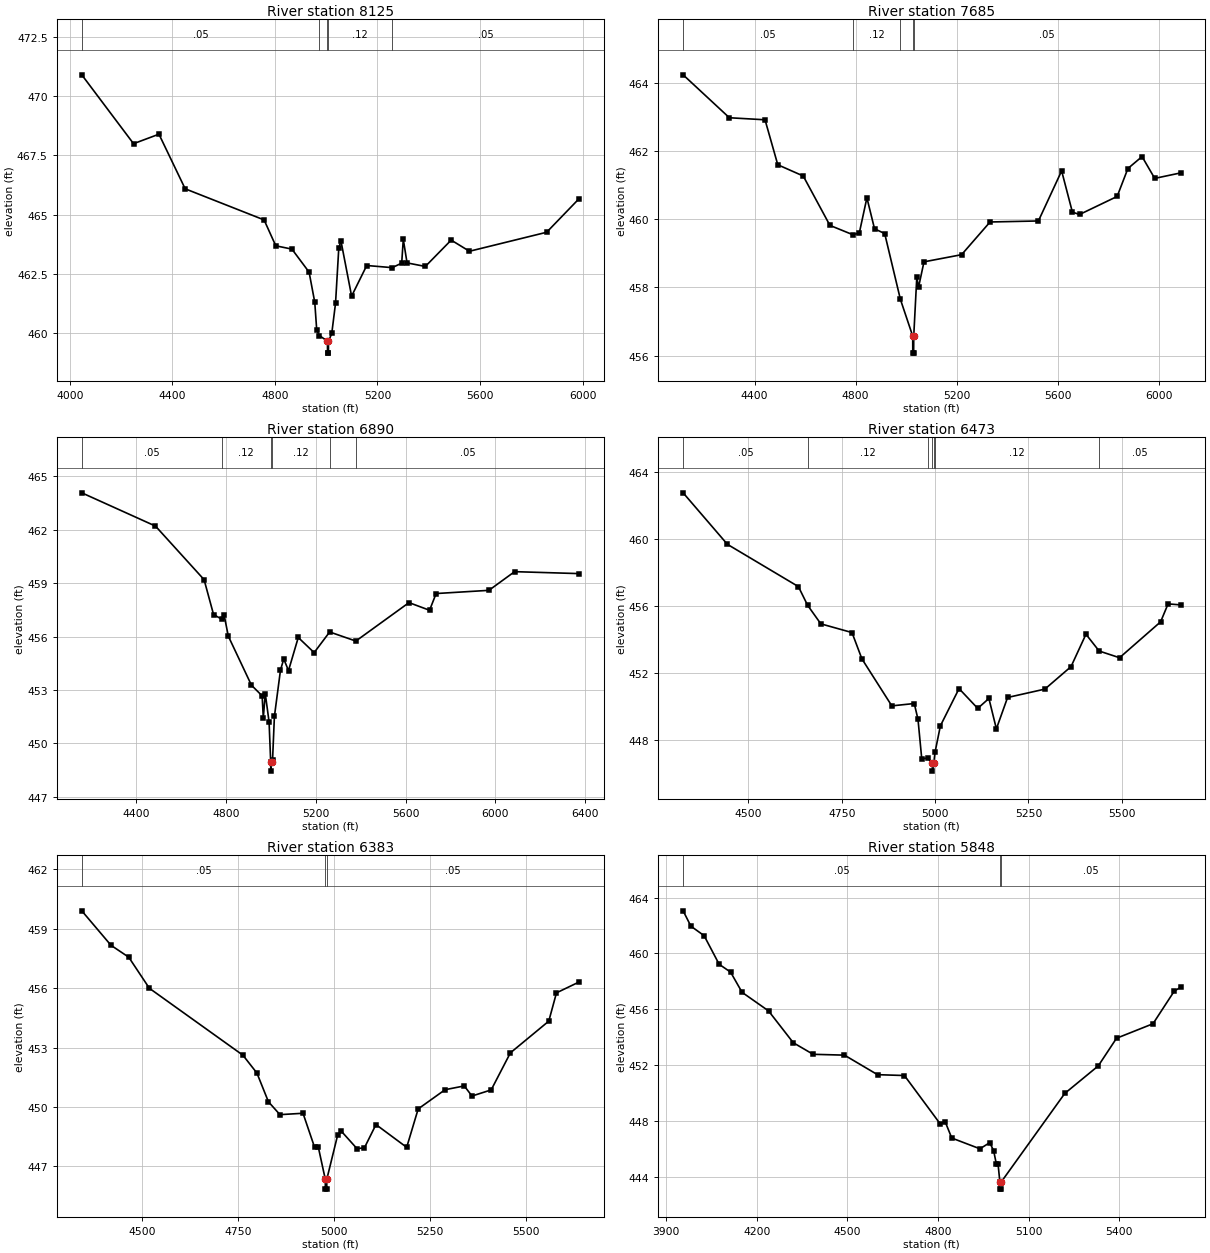
Type RM Length L Ch R = 1 ,8125    ,440,440,440
BEGIN DESCRIPTION:
Flat T4 15.0
END DESCRIPTION:
XS GIS Cut Line= 3
      2743620.99      6909258.18      2743216.21       6910121.5
      2744019.41      6910694.77
#Sta/Elev= 30
  4046.5  470.89  4248.4  467.99  4347.5  468.39  4449.8  466.09  4757.6  464.78
  4803.2  463.69  4866.2  463.55  4933.2  462.58  4955.3  461.31    4963  460.13
  4973.7  459.91  5004.8  459.67  5005.1  459.17  5008.6  459.17  5008.8  459.67
  5021.6     460  5036.3  461.27  5048.9  463.58  5057.2  463.91    5099  461.57
    5158  462.86  5257.3  462.77  5294.4  462.96  5300.6  463.96  5315.3  462.97
  5386.6  462.82  5487.4  463.93  5558.7  463.46  5859.8  464.26  5986.8  465.68
#Mann= 5 ,-1 , 0
  4046.5     .05       0  4973.7     .12       0  5004.8     .07       0
  5008.8     .12       0  5257.3     .05       0
Bank Sta=5004.8,5008.8
XS Rating Curve= 0 ,0
Exp/Cntr=0.3,0.1

Type RM Length L Ch R = 1 ,7685    ,795,795,795
BEGIN DESCRIPTION:
Mapping XS 7d0a576b
END DESCRIPTION:
XS GIS Cut Line= 3
      2742986.46      6909489.31      2742871.87      6910364.35
      2743595.46      6911176.44
#Sta/Elev= 30
  4116.6  464.24  4299.8  462.98    4441  462.92  4491.5   461.6  4592.3  461.27
    4698  459.82  4787.6  459.55  4814.2  459.59  4844.5  460.63  4874.7  459.72
    4915  459.58  4977.1  457.65    5026  456.57  5026.2  456.07  5029.7  456.07
    5030  456.57  5042.2  458.31  5048.9     458  5070.6  458.75  5219.5  458.96
  5332.3  459.92  5523.8  459.95  5615.8  461.42  5658.4  460.21  5686.8  460.14
  5835.7  460.67  5878.3  461.49  5934.3  461.84  5984.5   461.2  6086.8  461.36
#Mann= 5 ,-1 , 0
  4116.6     .05       0  4787.6     .12       0  4977.1     .05       0
    5026     .04       0    5030     .05       0
Bank Sta=5026,5030
XS Rating Curve= 0 ,0
Exp/Cntr=0.3,0.1

Type RM Length L Ch R = 1 ,6890    ,417,417,417
BEGIN DESCRIPTION:
Mapping XS 9f575ef1
END DESCRIPTION:
XS GIS Cut Line= 3
      2742085.41      6909786.21      2742278.12      6910598.73
      2743377.04      6911432.03
#Sta/Elev= 30
    4159  464.08  4487.1  462.21  4703.4   459.2  4745.6  457.24  4781.7  456.98
  4792.9  457.19  4811.4  456.02  4914.2  453.27  4961.8  452.67    4967  451.44
  4975.8  452.79  4992.7  451.21  4999.9  448.94  5000.1  448.44  5003.9  448.94
  5008.2  449.07  5016.4  451.51  5043.5  454.12  5058.1  454.74  5079.2  454.09
  5122.6  455.95  5193.3   455.1  5262.4  456.26    5379  455.75  5615.5  457.91
  5707.1  457.48  5736.2  458.42  5971.3   458.6  6085.7  459.65  6373.2  459.54
#Mann= 6 ,-1 , 0
    4159     .05       0  4781.7     .12       0  4999.9     .07       0
  5003.9     .12       0  5262.4     .12       0    5379     .05       0
Bank Sta=4999.9,5003.9
XS Rating Curve= 0 ,0
Exp/Cntr=0.3,0.1

Type RM Length L Ch R = 1 ,6473    ,90,90,90
BEGIN DESCRIPTION:
Mapping XS 8a23c1e6
END DESCRIPTION:
XS GIS Cut Line= 3
       2741942.2      6910002.49      2741910.92      6910666.79
      2741910.35      6911334.36
#Sta/Elev= 30
  4324.9  462.73  4443.5  459.66  4633.7  457.14  4658.3  456.03  4693.8  454.92
  4777.3   454.4  4803.9  452.83    4884  450.03  4944.1  450.17  4954.1  449.23
  4964.1  446.89  4980.2  446.91  4992.5  446.64  4992.8  446.14  4996.5  446.64
  4999.8  447.27  5014.1  448.84  5064.1  451.06  5114.1  449.88  5144.1  450.47
  5164.1  448.66  5194.1  450.53  5294.1  451.03  5364.1  452.37  5404.1   454.3
  5439.4   453.3  5494.1   452.9  5604.1  455.04  5624.1  456.11  5657.5  456.05
#Mann= 7 ,-1 , 0
  4324.9     .05       0  4658.3     .12       0  4980.2     .05       0
  4992.5     .07       0  4996.5     .05       0  4999.8     .12       0
  5439.4     .05       0
Bank Sta=4992.5,4996.5
XS Rating Curve= 0 ,0
Exp/Cntr=0.3,0.1

Type RM Length L Ch R = 1 ,6383    ,535,535,535
BEGIN DESCRIPTION:
Mapping XS 67d68acf
END DESCRIPTION:
XS GIS Cut Line= 3
      2741855.19      6910054.96      2741832.82      6910714.28
      2741811.02      6911350.21
#Sta/Elev= 30
  4343.2   459.9  4419.3  458.16  4465.5  457.56  4519.3  455.99  4763.1  452.61
  4799.5  451.71  4829.5  450.26  4859.5  449.61  4919.6  449.68  4949.6  447.97
  4959.6  447.96  4977.6  446.35  4977.9  445.85  4981.4  445.85  4981.6  446.35
  5009.6  448.56  5019.6  448.77  5060.4  447.89  5079.7  447.94  5109.7  449.11
  5189.7  447.96  5219.7   449.9  5289.8  450.87  5339.8  451.06  5359.8  450.55
  5409.9  450.86  5459.9  452.73  5559.9  454.33    5580  455.76  5639.2  456.31
#Mann= 3 ,-1 , 0
  4343.2     .05       0  4977.6     .05       0  4981.6     .05       0
Bank Sta=4977.6,4981.6
XS Rating Curve= 0 ,0
Exp/Cntr=0.3,0.1

Type RM Length L Ch R = 1 ,5848    ,653,653,653
BEGIN DESCRIPTION:
Mapping XS 4f3806f9
END DESCRIPTION:
XS GIS Cut Line= 3
      2741874.59      6909945.97      2741369.39      6910883.45
       2741437.1      6911461.56
#Sta/Elev= 30
  3955.9  463.05  3981.6  461.95  4025.4  461.27  4075.2  459.22    4113  458.66
  4151.1  457.21  4238.7  455.88  4320.6   453.6  4386.3  452.77  4490.1  452.71
  4599.6  451.31  4688.6  451.25  4807.3  447.78  4823.5  447.94  4845.4  446.77
  4938.7     446  4971.1  446.44    4984  445.87    4993  444.91  4998.7   444.9
  5004.7  443.61  5004.9  443.11  5008.4  443.11  5008.7  443.61  5219.7  449.97
  5330.5  451.94  5390.9  453.92  5511.7  454.96  5582.2   457.3  5602.9  457.57
#Mann= 3 ,-1 , 0
  3955.9     .05       0  5004.7     .04       0  5008.7     .05       0
Bank Sta=5004.7,5008.7
XS Rating Curve= 0 ,0
Exp/Cntr=0.3,0.1

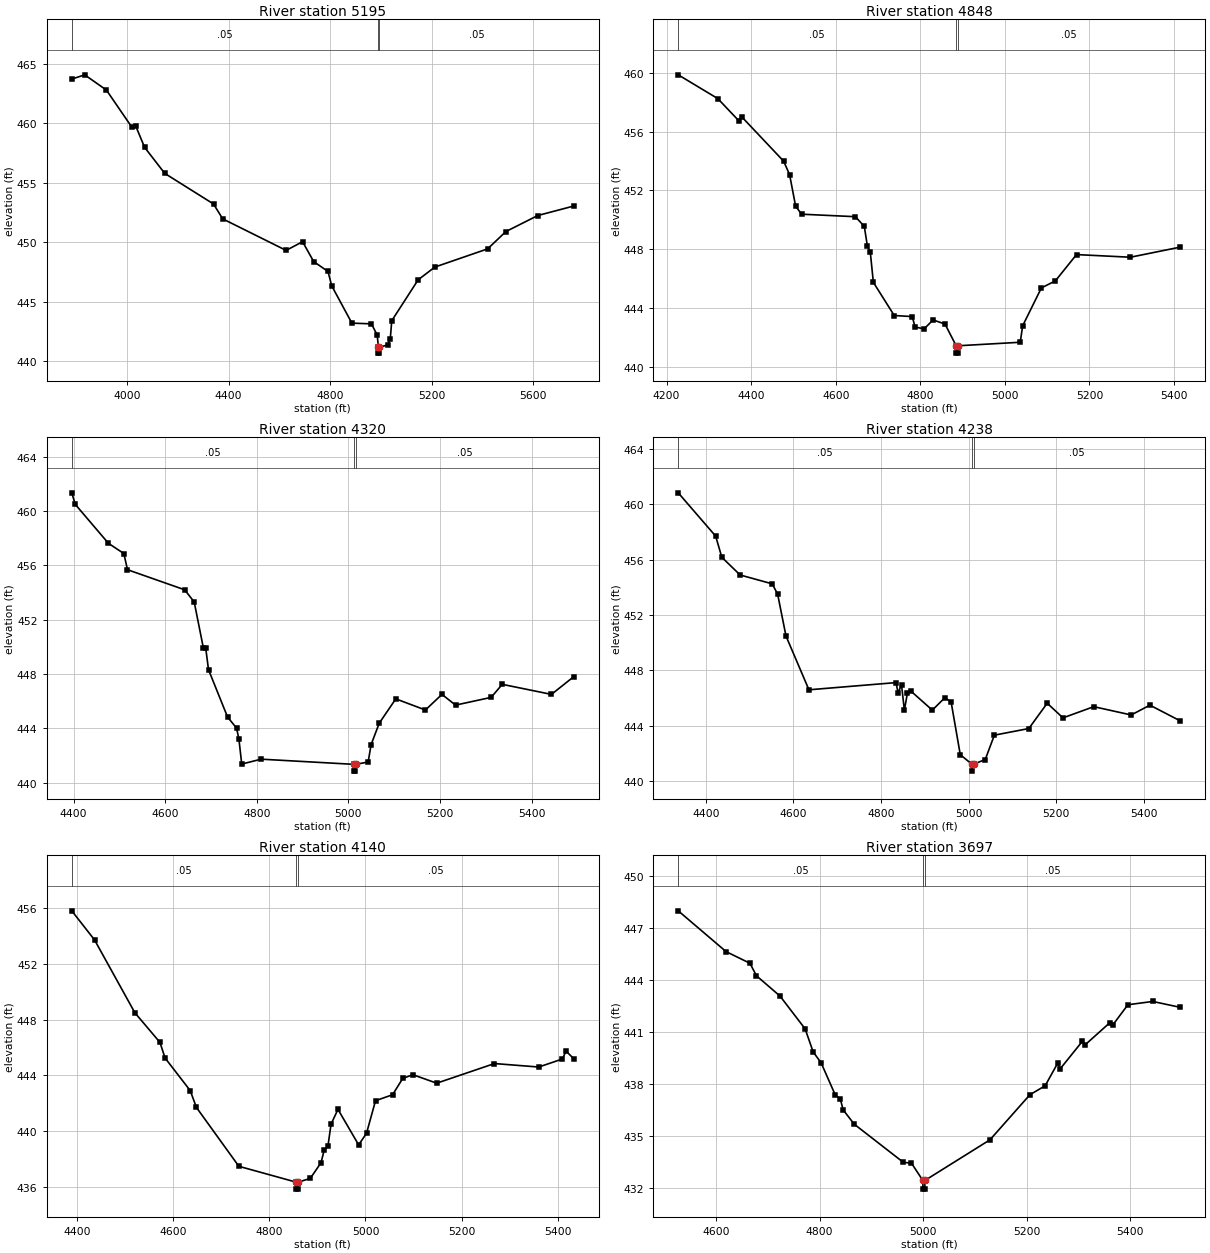
Type RM Length L Ch R = 1 ,5195    ,347,347,347
BEGIN DESCRIPTION:
Mapping XS 4b5056cc
END DESCRIPTION:
XS GIS Cut Line= 3
      2741944.77       6909827.9       2740955.2      6910557.06
      2740601.69      6911217.28
#Sta/Elev= 30
  3782.1  463.72    3833  464.08  3918.6   462.8  4018.8  459.68  4033.5  459.81
    4069  457.99  4148.4   455.8  4340.5  453.23  4376.8  451.98  4626.6  449.33
  4691.4  450.06  4735.3  448.39  4791.6  447.56  4806.3  446.35  4885.7  443.22
  4962.9  443.16  4985.5  442.21  4990.2   441.2  4990.4   440.7  4993.9   440.7
  4994.2   441.2  5027.1  441.39  5037.1  441.92  5042.7  443.42  5146.8  446.86
  5212.6  447.93  5420.6  449.46  5492.2  450.91    5618  452.26  5760.2  453.06
#Mann= 3 ,-1 , 0
  3782.1     .05       0  4990.2     .04       0  4994.2     .05       0
Bank Sta=4990.2,4994.2
XS Rating Curve= 0 ,0
Exp/Cntr=0.3,0.1

Type RM Length L Ch R = 1 ,4848    ,528,528,528
BEGIN DESCRIPTION:
Mapping XS b94f98ee
END DESCRIPTION:
XS GIS Cut Line= 3
      2741338.11       6909730.7       2740768.7      6910282.75
      2740588.16      6910633.42
#Sta/Elev= 30
  4227.5  459.87  4321.1  458.25  4370.5  456.75  4377.7  457.01  4476.8  453.99
  4490.9  453.07  4505.1  450.93  4519.2  450.38  4646.5  450.21  4667.6  449.55
  4674.8  448.22  4681.8  447.78    4689  445.74  4738.4  443.48  4780.8  443.41
  4787.8   442.7  4809.1  442.57  4830.2  443.18  4858.5   442.9  4884.8  441.42
  4885.1  440.92  4888.6  440.92  4888.8  441.42  5036.4  441.66  5042.1  442.78
  5086.4  445.36  5119.5  445.84  5169.5  447.63  5296.9  447.45    5415  448.14
#Mann= 3 ,-1 , 0
  4227.5     .05       0  4884.8     .03       0  4888.8     .05       0
Bank Sta=4884.8,4888.8
XS Rating Curve= 0 ,0
Exp/Cntr=0.3,0.1

Type RM Length L Ch R = 1 ,4320    ,82,82,82
BEGIN DESCRIPTION:
Mapping XS 192bfa25
END DESCRIPTION:
XS GIS Cut Line= 5
      2741142.81      6909715.22      2740781.66      6909819.39
      2740642.77      6909864.53      2740573.33      6909923.56
      2740392.77      6910371.48
#Sta/Elev= 30
  4396.1  461.33  4403.7  460.48  4476.2  457.61  4509.8  456.86  4517.7  455.67
  4642.6  454.19  4663.4  453.29  4683.3  449.92  4688.5   449.9  4694.6  448.31
  4736.2  444.82  4755.8  444.01    4761  443.19  4767.1  441.36  4809.5  441.72
  5011.6  441.34  5011.8  440.84  5015.3  440.84  5015.6  441.34  5043.1  441.51
  5049.5  442.79  5067.3  444.37  5103.4  446.16  5168.1  445.34  5204.2  446.49
  5233.8   445.7  5311.6  446.27  5335.8  447.23  5443.2  446.49  5492.1   447.8
#Mann= 3 ,-1 , 0
  4396.1     .05       0  5011.6     .04       0  5015.6     .05       0
Bank Sta=5011.6,5015.6
XS Rating Curve= 0 ,0
Exp/Cntr=0.3,0.1

Type RM Length L Ch R = 1 ,4238    ,98,98,98
BEGIN DESCRIPTION:
Mapping XS 6f88a37e
END DESCRIPTION:
XS GIS Cut Line= 6
      2741101.09      6909680.51      2740820.41      6909766.51
       2740682.6      6909770.85      2740628.35      6909802.32
      2740531.78      6909882.62      2740135.83      6910229.11
#Sta/Elev= 30
  4337.1  460.83  4422.5   457.7  4436.6  456.17  4478.4  454.89  4551.6  454.25
    4564   453.5    4583  450.48  4635.4  446.59  4834.1  447.11  4838.9  446.37
  4846.7  446.95  4853.2  445.11  4860.3  446.38  4867.6  446.51    4917  445.12
  4945.7  446.02  4959.9  445.71  4980.8   441.9  5007.3  441.21  5007.5  440.71
  5011.3  441.21  5037.8  441.55  5058.6  443.31  5137.3  443.79  5179.2  445.62
  5215.2  444.56  5285.5  445.37  5370.9  444.77  5413.6  445.48    5483  444.34
#Mann= 3 ,-1 , 0
  4337.1     .05       0  5007.3     .04       0  5011.3     .05       0
Bank Sta=5007.3,5011.3
XS Rating Curve= 0 ,0
Exp/Cntr=0.3,0.1

Type RM Length L Ch R = 1 ,4140    ,443,443,443
BEGIN DESCRIPTION:
Mapping XS 67145b05
END DESCRIPTION:
XS GIS Cut Line= 4
      2740941.33      6909620.38      2740617.95      6909720.22
      2740405.28      6909893.83      2740094.98      6910193.27
#Sta/Elev= 30
  4389.2  455.81  4436.6  453.72  4520.4  448.49  4572.6  446.36  4583.2  445.24
  4635.5   442.9  4648.4  441.69  4736.7  437.46    4856  436.32  4856.3  435.82
  4859.8  435.82    4860  436.32  4885.3  436.59  4907.6  437.72    4914   438.6
  4921.9  438.89  4928.4  440.48  4942.8  441.55  4985.8     439  5002.2  439.83
  5020.9  442.17  5056.4   442.6  5077.5  443.77  5098.6  444.04  5148.2  443.43
  5268.3  444.84  5360.4  444.59  5409.8  445.17    5417  445.74  5433.4  445.18
#Mann= 3 ,-1 , 0
  4389.2     .05       0    4856     .04       0    4860     .05       0
Bank Sta=4856,4860
XS Rating Curve= 0 ,0
Exp/Cntr=0.3,0.1

Type RM Length L Ch R = 1 ,3697    ,350,350,350
BEGIN DESCRIPTION:
Mapping XS 917c02e4
END DESCRIPTION:
XS GIS Cut Line= 3
      2740584.92      6909321.39      2740179.11      6909568.78
      2739990.79      6910025.51
#Sta/Elev= 30
  4527.1  447.97  4619.5  445.62  4665.5  444.95  4678.1  444.23  4723.6  443.06
  4772.1  441.17  4787.5  439.85    4803  439.21  4830.3  437.36  4839.8  437.15
  4845.6   436.5  4866.9  435.68  4961.8  433.48  4977.3  433.44  4999.3  432.44
  4999.5  431.94    5003  431.94  5003.3  432.44  5128.9  434.78  5206.1  437.38
  5235.4  437.89  5259.4  439.18  5264.8  438.88  5307.2  440.45  5312.6  440.25
  5360.5  441.53  5365.9  441.39  5395.2  442.56  5443.1  442.75  5496.4  442.41
#Mann= 3 ,-1 , 0
  4527.1     .05       0  4999.3     .04       0  5003.3     .05       0
Bank Sta=4999.3,5003.3
XS Rating Curve= 0 ,0
Exp/Cntr=0.3,0.1

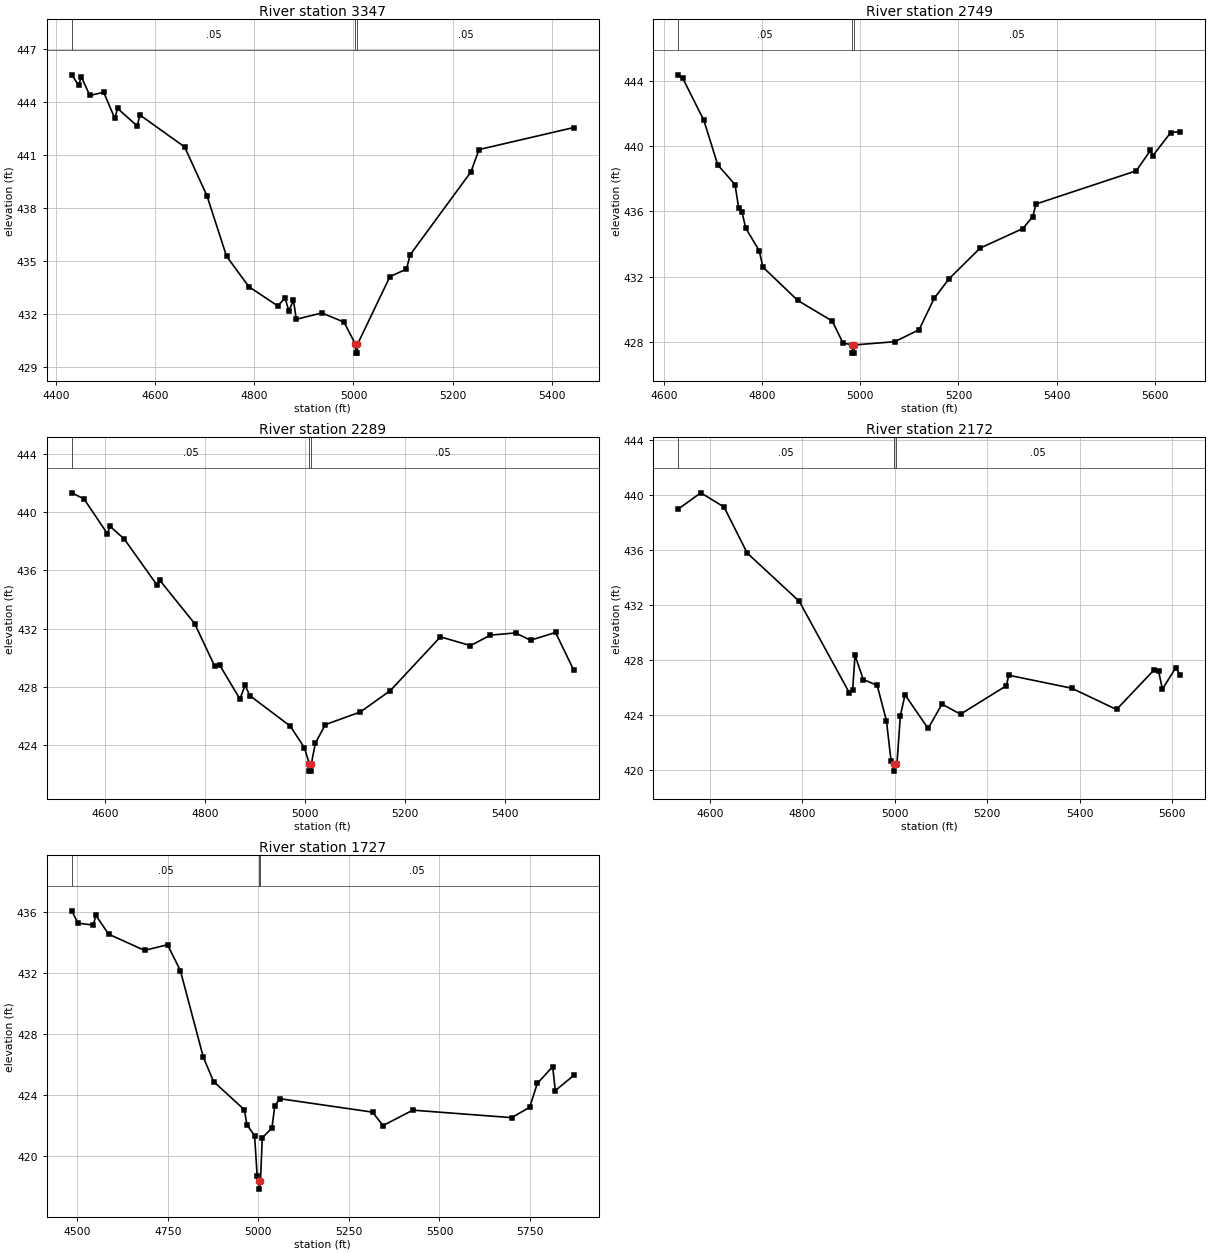
Type RM Length L Ch R = 1 ,3347    ,598,598,598
BEGIN DESCRIPTION:
Mapping XS fc0ade5a
END DESCRIPTION:
XS GIS Cut Line= 3
      2740129.19      6908998.05      2739883.97      6909499.33
      2739792.82      6909944.24
#Sta/Elev= 30
  4432.1  445.55  4445.8  444.96  4451.4  445.44  4468.4  444.38  4496.4  444.56
  4518.9  443.08  4524.5  443.64    4564  442.65  4569.5  443.27  4659.6  441.46
  4704.6  438.69  4744.1  435.26  4789.1  433.53  4847.3  432.44  4862.2  432.89
  4869.6  432.16  4879.1  432.75  4884.7  431.68  4936.3  432.04  4980.9  431.52
  5004.1  430.26  5004.3  429.76  5007.8  429.76  5008.1  430.26  5073.5   434.1
  5106.9  434.53  5114.3  435.34  5236.8  440.04  5253.1  441.31  5444.3  442.56
#Mann= 3 ,-1 , 0
  4432.1     .05       0  5004.1     .04       0  5008.1     .05       0
Bank Sta=5004.1,5008.1
XS Rating Curve= 0 ,0
Exp/Cntr=0.3,0.1

Type RM Length L Ch R = 1 ,2749    ,460,460,460
BEGIN DESCRIPTION:
Mapping XS b1bcfd0c
END DESCRIPTION:
XS GIS Cut Line= 3
      2739686.51       6908948.1      2739430.41      6909234.58
      2739376.16      6909870.41
#Sta/Elev= 30
  4629.4  444.35  4638.8  444.13  4681.5  441.57  4709.9  438.84    4745  437.64
  4752.5   436.2  4759.2  435.97  4766.7  434.98  4794.3   433.6  4801.8  432.59
  4872.9  430.55  4943.1  429.29  4964.8  427.95  4983.8  427.83    4984  427.33
  4987.5  427.33  4987.8  427.83  5070.3  428.03  5119.9  428.76  5150.6  430.68
  5180.7  431.87    5244  433.75  5331.2  434.95  5351.3  435.68    5358  436.45
  5562.1  438.48    5591  439.73    5596  439.41  5632.3  440.82  5651.8  440.87
#Mann= 3 ,-1 , 0
  4629.4     .05       0  4983.8     .04       0  4987.8     .05       0
Bank Sta=4983.8,4987.8
XS Rating Curve= 0 ,0
Exp/Cntr=0.3,0.1

Type RM Length L Ch R = 1 ,2289    ,117,117,117
BEGIN DESCRIPTION:
Mapping XS 7a84828c
END DESCRIPTION:
XS GIS Cut Line= 3
      2739098.39      6908546.62      2739050.64      6909015.39
      2739050.64      6909547.59
#Sta/Elev= 30
  4533.4  441.31  4557.9  440.89  4604.7   438.5  4609.7  439.02  4638.3  438.14
  4704.3  434.96  4709.3  435.31    4779  432.34  4819.3   429.4  4829.3  429.48
  4869.5  427.16  4879.6   428.1  4889.6  427.39    4970  425.31  4998.1  423.84
  5008.2  422.72  5008.5  422.22    5012  422.22  5012.2  422.72  5020.2  424.14
  5040.2  425.41  5110.2  426.28  5170.2  427.75  5270.2  431.43  5330.2  430.83
  5370.2  431.55  5420.2   431.7  5450.2   431.2  5500.2  431.73  5536.8  429.13
#Mann= 3 ,-1 , 0
  4533.4     .05       0  5008.2     .05       0  5012.2     .05       0
Bank Sta=5008.2,5012.2
XS Rating Curve= 0 ,0
Exp/Cntr=0.3,0.1

Type RM Length L Ch R = 1 ,2172    ,445,445,445
BEGIN DESCRIPTION:
Mapping XS 4be5172a
END DESCRIPTION:
XS GIS Cut Line= 4
      2738972.51      6908542.33      2738933.45      6909011.05
      2738948.08      6909482.68      2739005.24      6909614.19
#Sta/Elev= 30
  4531.6  438.99  4580.4  440.17  4630.6  439.14  4680.8  435.79  4793.4  432.28
  4901.6  425.63  4908.8  425.86  4913.8  428.36  4931.7   426.6  4961.8  426.17
  4981.8   423.6  4991.9  420.64  4997.4  420.44  4997.7  419.94  5001.4  420.44
  5004.4  420.44  5011.9  423.96  5021.9  425.49  5071.9  423.04  5101.9  424.81
    5142  424.08  5241.2  426.15  5246.2  426.91  5382.1  425.97  5479.3  424.42
  5560.5   427.3  5570.1  427.24  5578.5   425.9  5607.4  427.46  5617.2   426.9
#Mann= 3 ,-1 , 0
  4531.6     .05       0  4997.4     .04       0  5001.4     .05       0
Bank Sta=4997.4,5001.4
XS Rating Curve= 0 ,0
Exp/Cntr=0.3,0.1

Type RM Length L Ch R = 1 ,1727    ,0,0,0
BEGIN DESCRIPTION:
Mapping XS 904406e0
END DESCRIPTION:
XS GIS Cut Line= 4
      2738881.38      6908542.29      2738508.11      6908924.25
      2738726.18      6909372.19      2738979.47      6909620.11
#Sta/Elev= 30
  4484.5  436.08  4501.5  435.27  4543.9  435.15  4551.1  435.78  4586.4  434.55
  4685.4  433.49    4749  433.86  4784.4  432.17    4848  426.48  4876.3   424.9
  4961.1  423.06  4968.3  422.07  4989.4  421.36  4996.6  418.71  5001.6  418.36
  5001.8  417.86  5005.6  418.36  5010.7  421.22  5037.2  421.85  5045.4  423.32
  5059.4  423.78  5315.3   422.9    5344  422.02  5426.5  423.03  5699.6  422.54
  5749.2  423.22  5770.3  424.78  5812.8  425.88  5819.9  424.31  5871.2  425.31
#Mann= 3 ,-1 , 0
  4484.5     .05       0  5001.6     .03       0  5005.6     .05       0
Bank Sta=5001.6,5005.6
XS Rating Curve= 0 ,0
Exp/Cntr=0.3,0.1

Chan Stop Cuts=-1
Use User Specified Reach Order=0
Composite Channel Slope=5