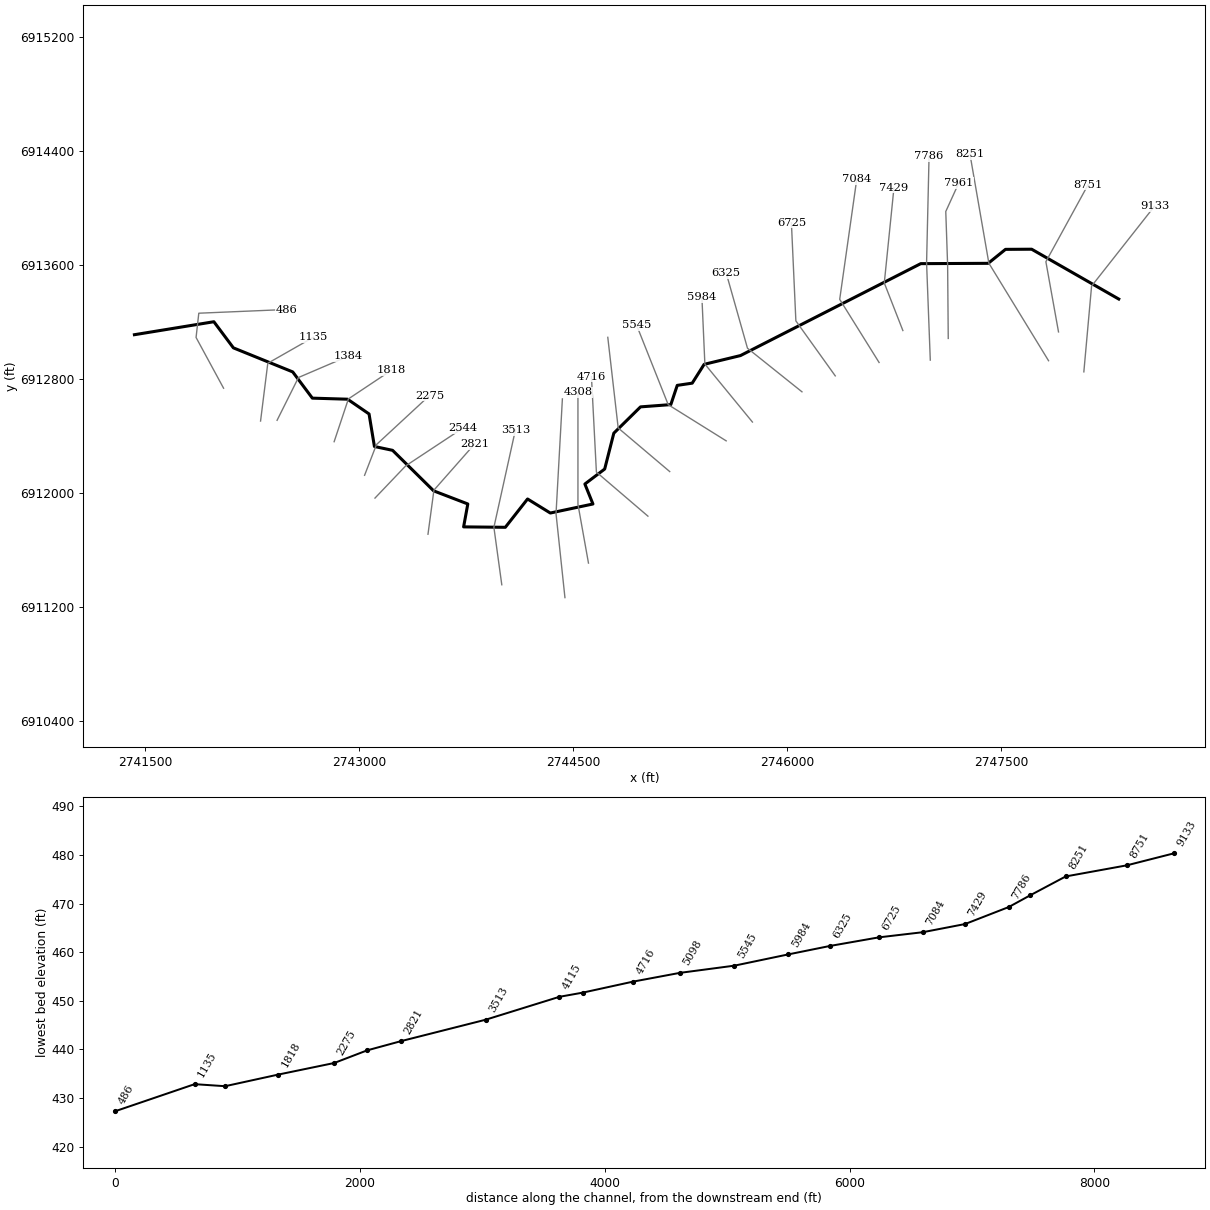
--- Flat T5.prj (project) ---

Proj Title=Flat T5 Base Level Engineering
Current Plan=p01
Default Exp/Contr=0.3,0.1
English Units
Geom File=g01
Flow File=f01
Plan File=p01
Y Axis Title=Elevation
X Axis Title(PF)=Main Channel Distance
X Axis Title(XS)=Station
BEGIN DESCRIPTION:
Flat T5
END DESCRIPTION:
DSS Export Rating Curves= 0
DSS Export Rating Curve Sorted= 0
DSS Export Volume Flow Curves= 0
DXF OffsetX= 0
DXF OffsetY= 0
DXF ScaleX= 1
DXF ScaleY= 10

--- Flat T5.p01 (plan) ---

Plan Title=Multiple Run
Short Identifier=Multiple
Geom File=g01
Flow File=f01
Subcritical Flow
K Sum by GR= 0
Std Step Tol= 0.01
Critical Tol= 0.01
Num of Std Step Trials= 20
Max Error Tol= 0.3
Flow Tol Ratio= 0.001
Split Flow NTrial= 30
Split Flow Tol= 0.02
Split Flow Ratio= 0.02
Log Output Level= 0
Friction Slope Method= 1
Unsteady Friction Slope Method= 2
Unsteady Bridges Friction Slope Method= 1
Parabolic Critical Depth
Global Vel Dist=  1 , 1 , 1
Global Log Level= 0
CheckData=True
Encroach Param= -1, 0, 0, 0
BEGIN DESCRIPTION:
Multiple Run
END DESCRIPTION:

--- Flat T5.f01 (steady flow) ---

Flow Title=Multiple
Number of Profiles=7
Profile Names=10-year,25-year,50-year,1pct_min,100-year,1pct_plu,500-year
River Rch & RM= Flat T5,Reach-1,9133
     376     491     583     344     686    1369     953
River Rch & RM= Flat T5,Reach-1,3513
     520     693     833     498     993    1982    1415
Boundary for River Rch & Prof#=Flat T5,Reach-1,1
Up Type=0
Dn Type=3
Dn Slope=0.005
Boundary for River Rch & Prof#=Flat T5,Reach-1,2
Up Type=0
Dn Type=3
Dn Slope=0.005
Boundary for River Rch & Prof#=Flat T5,Reach-1,3
Up Type=0
Dn Type=3
Dn Slope=0.005
Boundary for River Rch & Prof#=Flat T5,Reach-1,4
Up Type=0
Dn Type=3
Dn Slope=0.005
Boundary for River Rch & Prof#=Flat T5,Reach-1,5
Up Type=0
Dn Type=3
Dn Slope=0.005
Boundary for River Rch & Prof#=Flat T5,Reach-1,6
Up Type=0
Dn Type=3
Dn Slope=0.005
Boundary for River Rch & Prof#=Flat T5,Reach-1,7
Up Type=0
Dn Type=3
Dn Slope=0.005

--- Flat T5.g01 (geometry) ---

Geom Title=Existing Conditions
Program Version=4.10

River Reach=Flat T5         ,Reach-1
Reach XY= 30
        2748326.        6913361.      2747715.36      6913710.35
      2747532.05      6913709.33      2747410.84      6913611.39
      2746938.02      6913609.15      2745674.42      6912964.83
      2745419.55      6912903.25      2745336.06      6912771.41
      2745231.12      6912755.88      2745186.05      6912621.06
      2744973.71      6912605.19      2744786.48       6912420.8
      2744722.49      6912169.48       2744583.6      6912064.35
      2744640.15       6911924.4      2744341.36      6911861.02
      2744181.85       6911959.5        2744026.        6911761.
      2743733.58      6911763.97      2743763.02      6911924.57
      2743523.56      6912016.52      2743235.78      6912300.48
      2743108.39      6912327.46      2743070.74      6912555.53
      2742920.15      6912658.94       2742673.3      6912666.36
      2742535.71      6912850.25      2742119.81      6913018.86
      2741983.01      6913201.97        2741426.        6913111.

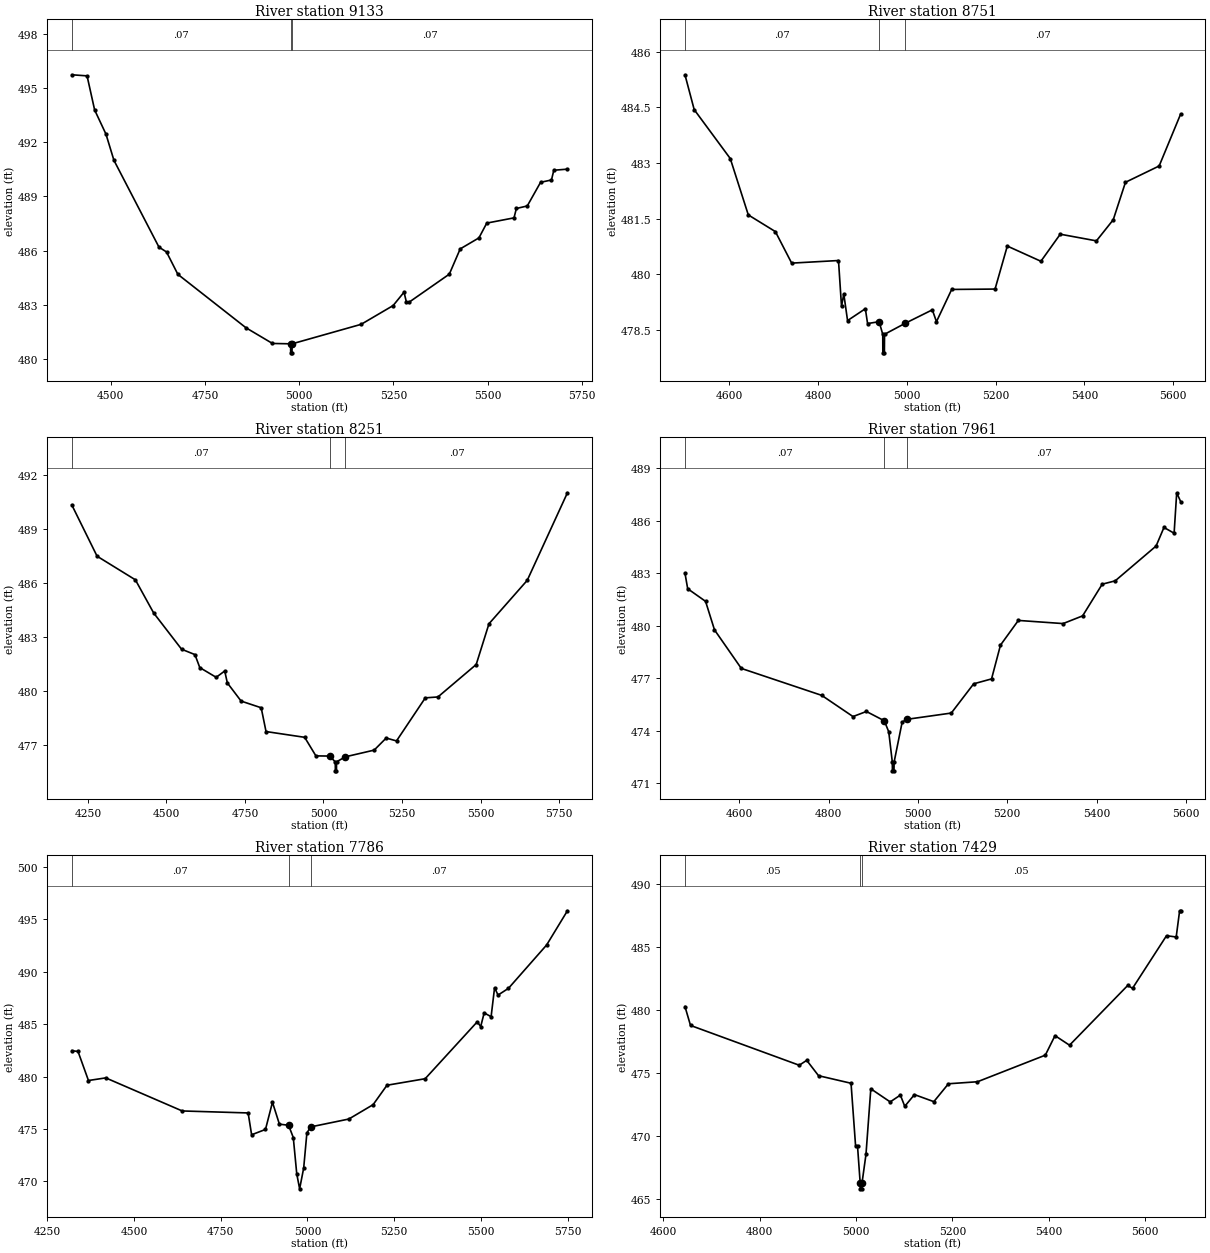
Type RM Length L Ch R = 1 ,9133    ,382,382,382
BEGIN DESCRIPTION:
Flat T5 18.0
END DESCRIPTION:
XS GIS Cut Line= 3
      2748081.31      6912850.56      2748135.48      6913451.72
      2748575.98      6914010.97
#Sta/Elev= 30
  4396.4  495.74    4437  495.68  4457.1  493.79  4487.2  492.45  4508.3     491
  4627.8  486.19  4647.9  485.92    4678  484.68  4858.7  481.72    4929  480.85
  4977.2  480.83  4977.4  480.33  4980.9  480.33  4981.2  480.83  5164.4  481.91
  5249.3  482.95  5278.2  483.69  5284.6  483.14  5291.9  483.14  5398.4  484.69
  5427.3  486.09    5477   486.7  5497.8  487.52  5570.1  487.81  5576.4  488.33
  5605.3  488.47  5640.6  489.78  5669.5  489.91  5675.8  490.45  5711.9  490.51
#Mann= 3 ,-1 , 0
  4396.4     .07       0  4977.2     .04       0  4981.2     .07       0
Bank Sta=4977.2,4981.2
XS Rating Curve= 0 ,0
Exp/Cntr=0.3,0.1

Type RM Length L Ch R = 1 ,8751    ,500,500,500
BEGIN DESCRIPTION:
Mapping XS 3f935226
END DESCRIPTION:
XS GIS Cut Line= 3
      2747903.75      6913130.52       2747815.2      6913622.71
      2748111.56      6914163.43
#Sta/Elev= 30
  4499.9  485.38  4520.7  484.44    4602  483.12  4642.6   481.6  4703.6  481.15
  4740.3   480.3  4845.8  480.37  4852.6  479.13  4857.7  479.47  4866.2  478.75
  4906.3  479.07  4911.3  478.67  4937.3  478.72  4945.5  478.38  4945.7  477.88
  4949.2  477.88  4949.5  478.38  4996.6  478.68  5057.2  479.04  5066.5  478.72
  5100.8  479.59  5198.5   479.6  5226.1  480.76  5301.8  480.35  5345.4  481.08
  5426.9   480.9  5464.8  481.47  5492.3  482.48  5568.2  482.92  5616.6  484.32
#Mann= 3 ,-1 , 0
  4499.9     .07       0  4937.3     .04       0  4996.6     .07       0
Bank Sta=4937.3,4996.6
XS Rating Curve= 0 ,0
Exp/Cntr=0.3,0.1

Type RM Length L Ch R = 1 ,8251    ,290,290,290
BEGIN DESCRIPTION:
Flat T5 16.0
END DESCRIPTION:
XS GIS Cut Line= 3
      2747833.92      6912928.64      2747415.56      6913612.06
       2747282.9      6914377.14
#Sta/Elev= 30
  4198.7  490.35  4279.3   487.5  4401.2  486.19  4459.4  484.35  4548.2  482.34
  4590.8  482.04  4606.2  481.32  4658.4  480.78  4685.6  481.13  4693.9  480.47
  4737.8  479.46  4801.7  479.09  4817.1  477.77  4940.1  477.45  4975.8  476.42
  5019.2  476.41  5037.5  476.09  5037.8  475.59  5041.3  475.59  5041.5  476.09
    5070  476.37  5161.3  476.74  5199.6  477.41  5232.4  477.25  5324.1  479.64
  5364.3  479.69  5486.1  481.49  5526.7  483.75  5648.5  486.16  5776.5  491.02
#Mann= 3 ,-1 , 0
  4198.7     .07       0  5019.2     .04       0    5070     .07       0
Bank Sta=5019.2,5070
XS Rating Curve= 0 ,0
Exp/Cntr=0.3,0.1

Type RM Length L Ch R = 1 ,7961    ,175,175,175
BEGIN DESCRIPTION:
Mapping XS d52da3cf
END DESCRIPTION:
XS GIS Cut Line= 4
      2747130.79      6913084.92      2747126.45      6913597.05
      2747113.43      6913974.65      2747204.55      6914174.26
#Sta/Elev= 30
  4478.6     483  4484.7  482.11  4524.7  481.39  4544.7  479.76  4604.7  477.56
  4784.7  476.02  4854.7  474.81  4884.7   475.1  4924.7  474.57  4934.7  473.94
  4942.7  472.21  4942.9  471.71  4946.4  471.71  4946.7  472.21  4964.7  474.49
  4974.7  474.65  5074.7  475.01  5124.8  476.68  5164.8  476.96  5184.8  478.89
  5224.8   480.3  5324.9  480.12  5368.6  480.56  5412.5  482.37  5441.5  482.56
  5533.1  484.55  5550.7  485.61  5573.4  485.28  5579.2  487.59    5588  487.09
#Mann= 3 ,-1 , 0
  4478.6     .07       0  4924.7     .04       0  4974.7     .07       0
Bank Sta=4924.7,4974.7
XS Rating Curve= 0 ,0
Exp/Cntr=0.3,0.1

Type RM Length L Ch R = 1 ,7786    ,357,357,357
BEGIN DESCRIPTION:
Mapping XS 840cc498
END DESCRIPTION:
XS GIS Cut Line= 3
      2747004.92      6912932.97      2746978.88      6913614.41
      2746996.24      6914360.97
#Sta/Elev= 30
  4320.6  482.46  4338.6  482.39  4368.7  479.62  4418.5  479.87  4638.9  476.72
    4829  476.53    4839  474.45    4879  474.96  4899.1  477.55  4919.1  475.46
  4945.5  475.36  4959.1  474.19  4969.1  470.73  4977.4   469.3  4989.1  471.29
  4998.3  474.62  5009.1   475.2  5119.2  475.95  5189.2  477.32  5229.2  479.17
  5339.2  479.79  5489.3  485.21  5499.3  484.76  5509.3  486.06  5529.3   485.7
  5539.3  488.46  5549.3  487.76  5579.3   488.4  5689.3  492.53  5749.3  495.79
#Mann= 3 ,-1 , 0
  4320.6     .07       0  4945.5     .04       0  5009.1     .07       0
Bank Sta=4945.5,5009.1
XS Rating Curve= 0 ,0
Exp/Cntr=0.3,0.1

Type RM Length L Ch R = 1 ,7429    ,345,345,345
BEGIN DESCRIPTION:
Mapping XS 38cc368a
END DESCRIPTION:
XS GIS Cut Line= 3
      2746812.64      6913140.25      2746682.44      6913473.57
      2746750.14      6914140.19
#Sta/Elev= 30
  4645.3  480.27  4656.8  478.77  4882.3  475.61  4897.8     476  4922.3  474.78
  4989.7  474.18  4999.1  469.22  5003.1  469.22  5008.6   466.3  5008.9   465.8
  5012.4   465.8  5012.6   466.3  5020.7  468.54  5030.7  473.74  5070.9   472.7
    5092  473.24  5101.1  472.35  5121.2  473.28  5161.4  472.72  5191.7  474.14
  5251.9   474.3  5392.6  476.41  5412.7  477.96  5442.8   477.2  5563.4  481.94
  5573.5  481.72  5643.9  485.89    5664  485.79  5671.1  487.87  5673.2  487.87
#Mann= 3 ,-1 , 0
  4645.3     .05       0  5008.6     .04       0  5012.6     .05       0
Bank Sta=5008.6,5012.6
XS Rating Curve= 0 ,0
Exp/Cntr=0.3,0.1

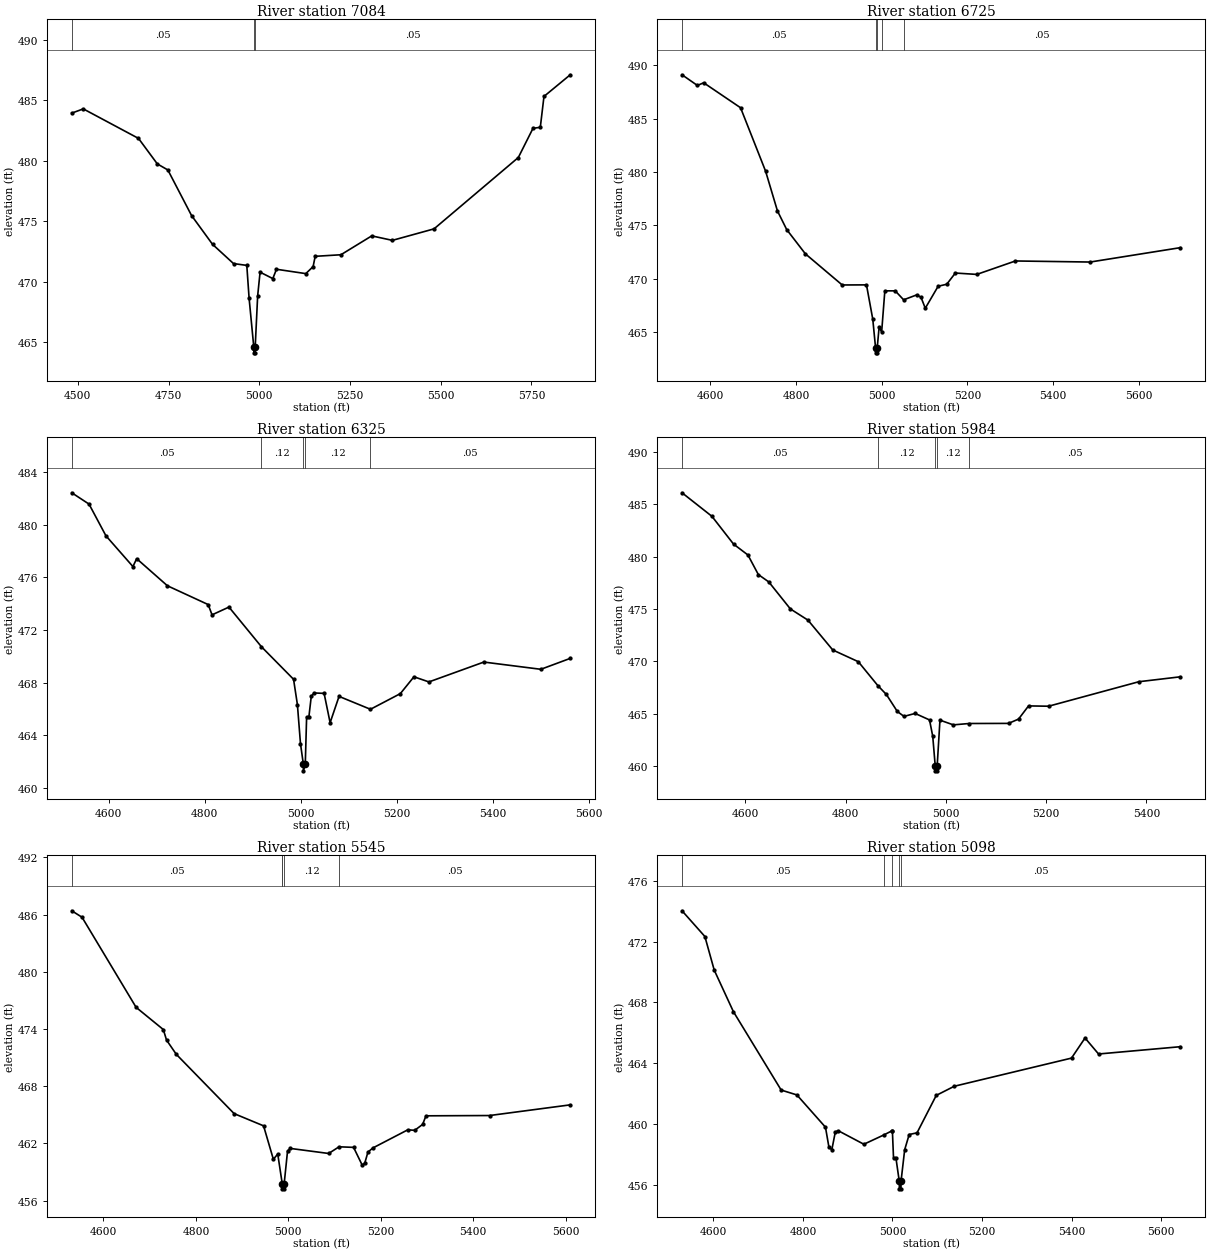
Type RM Length L Ch R = 1 ,7084    ,359,359,359
BEGIN DESCRIPTION:
Mapping XS 918cf1f1
END DESCRIPTION:
XS GIS Cut Line= 3
      2746645.98      6912916.28      2746369.94      6913358.98
      2746489.72      6914202.71
#Sta/Elev= 30
  4483.2  483.94  4514.9  484.29  4667.1  481.85    4719  479.74    4748  479.24
  4813.4  475.47  4871.2  473.09    4929   471.5  4965.6  471.35  4971.9  468.65
  4984.8  464.62  4985.1  464.12  4988.6  464.12  4988.8  464.62  4995.5  468.82
  5002.2  470.79  5037.3  470.26  5047.4  471.03  5128.2  470.67  5148.4  471.25
  5154.1   472.1    5225  472.23    5310  473.79  5366.9  473.42  5481.7  474.37
    5714  480.27  5754.4  482.68  5774.6  482.77  5784.7  485.32  5857.1  487.11
#Mann= 3 ,-1 , 0
  4483.2     .05       0  4984.8     .04       0  4988.8     .05       0
Bank Sta=4984.8,4988.8
XS Rating Curve= 0 ,0
Exp/Cntr=0.3,0.1

Type RM Length L Ch R = 1 ,6725    ,400,400,400
BEGIN DESCRIPTION:
Mapping XS 7e10adc2
END DESCRIPTION:
XS GIS Cut Line= 3
      2746338.67      6912822.54      2746062.64      6913207.94
      2746031.39      6913895.48
#Sta/Elev= 30
  4534.4  489.12  4570.2  488.12  4584.9  488.37  4670.9  486.03  4729.3  480.08
  4756.9  476.36  4778.5  474.61    4822  472.34  4907.9  469.42  4964.5  469.43
  4979.2  466.21  4985.6  463.56  4985.9  463.06  4989.4  463.06  4989.6  463.56
  4993.9  465.44  4999.9  465.03  5007.3  468.87  5031.5  468.87  5051.1  468.03
  5081.6  468.49  5091.6  468.27  5101.6  467.24  5131.6   469.3  5151.7  469.49
  5171.7  470.54  5221.7  470.41  5311.8  471.67  5486.1  471.57  5696.7  472.92
#Mann= 5 ,-1 , 0
  4534.4     .05       0  4985.6     .07       0  4989.6     .05       0
  4999.9     .12       0  5051.1     .05       0
Bank Sta=4985.6,4989.6
XS Rating Curve= 0 ,0
Exp/Cntr=0.3,0.1

Type RM Length L Ch R = 1 ,6325    ,341,341,341
BEGIN DESCRIPTION:
Mapping XS bbd7c9d6
END DESCRIPTION:
XS GIS Cut Line= 3
      2746105.38       6912710.7      2745723.41      6913016.27
      2745574.09       6913544.1
#Sta/Elev= 30
  4523.3  482.43  4559.2  481.57  4594.4  479.16  4650.6  476.82  4658.4  477.42
  4722.4  475.36  4807.3  473.93  4815.3  473.15  4850.5  473.74    4918  470.73
    4985  468.25    4993  466.33  4999.4  463.36  5005.4  461.79  5005.6  461.29
  5009.4  461.79  5012.2  465.39  5016.9  465.39  5021.9  466.96  5027.8  467.21
  5048.6  467.18  5061.1  464.95  5079.7  466.95  5145.1  465.97  5207.3  467.16
  5235.6  468.44  5266.8  468.05  5381.1  469.56  5499.8  469.01    5561  469.84
#Mann= 5 ,-1 , 0
  4523.3     .05       0    4918     .12       0  5005.4     .07       0
  5009.4     .12       0  5145.1     .05       0
Bank Sta=5005.4,5009.4
XS Rating Curve= 0 ,0
Exp/Cntr=0.3,0.1

Type RM Length L Ch R = 1 ,5984    ,439,439,439
BEGIN DESCRIPTION:
Mapping XS ebeaba7c
END DESCRIPTION:
XS GIS Cut Line= 3
      2745758.13      6912498.91       2745424.8      6912905.16
      2745403.96       6913373.9
#Sta/Elev= 30
  4473.4   486.1  4533.1  483.85  4576.2   481.2  4604.9  480.16  4625.7  478.29
  4646.5  477.59  4689.6  475.01  4724.7  473.94  4774.2  471.09  4825.2  469.97
  4864.3  467.68  4881.2  466.84    4903  465.22  4916.3  464.75  4938.6  465.03
  4967.3  464.41  4973.7  462.85  4978.6  460.05  4978.8  459.55  4982.3  459.55
  4982.6  460.05  4988.1  464.39  5014.8  463.94  5046.5  464.07  5124.9  464.08
  5144.9  464.49  5164.9  465.75  5204.9  465.72  5385.1  468.06  5468.1  468.53
#Mann= 5 ,-1 , 0
  4473.4     .05       0  4864.3     .12       0  4978.6     .07       0
  4982.6     .12       0  5046.5     .05       0
Bank Sta=4978.6,4982.6
XS Rating Curve= 0 ,0
Exp/Cntr=0.3,0.1

Type RM Length L Ch R = 1 ,5545    ,447,447,447
BEGIN DESCRIPTION:
Mapping XS c2ad0cab
END DESCRIPTION:
XS GIS Cut Line= 3
      2745574.11      6912366.96      2745167.85      6912620.44
      2744946.31      6913177.77
#Sta/Elev= 30
  4531.4  486.41  4553.6  485.73  4670.6  476.28  4729.5  473.95  4736.4  472.85
  4757.6  471.35  4882.7  465.13  4946.4  463.85  4967.6  460.34  4977.1  460.89
  4986.6  457.84  4986.9  457.74  4987.1  457.24  4990.6  457.24  4990.9  457.74
  4998.3  461.21  5004.2  461.48  5087.3  460.95  5109.7  461.65  5141.2  461.59
  5160.1   459.7  5165.5  459.96  5172.3   461.1    5183  461.53  5258.4  463.43
  5273.5  463.38  5290.6     464  5297.8   464.9  5435.4  464.93    5610  466.05
#Mann= 5 ,-1 , 0
  4531.4     .05       0  4986.6     .12       0  4986.9     .07       0
  4990.9     .12       0  5109.7     .05       0
Bank Sta=4986.9,4990.9
XS Rating Curve= 0 ,0
Exp/Cntr=0.3,0.1

Type RM Length L Ch R = 1 ,5098    ,382,382,382
BEGIN DESCRIPTION:
Mapping XS 80c4bada
END DESCRIPTION:
XS GIS Cut Line= 3
      2745178.31      6912151.66      2744817.16      6912457.25
      2744744.24      6913092.69
#Sta/Elev= 30
  4530.2  474.02  4581.2  472.33  4602.1  470.12  4644.9  467.39  4751.5  462.24
  4786.6  461.92  4850.4   459.8  4858.1  458.49  4864.6  458.32  4872.4  459.49
  4878.9  459.57  4936.1  458.68  4980.6  459.29    4998  459.55  4999.8  459.55
  5002.3  457.78  5007.7  457.78  5015.1  456.25  5015.4  455.75  5018.9  455.75
  5019.1  456.25  5027.2  458.32  5037.3  459.32  5054.8  459.43  5097.7  461.89
  5137.9  462.49  5399.6  464.34  5429.8  465.66    5460  464.61  5642.9  465.09
#Mann= 5 ,-1 , 0
  4530.2     .05       0  4980.6     .12       0    4998     .05       0
  5015.1     .04       0  5019.1     .05       0
Bank Sta=5015.1,5019.1
XS Rating Curve= 0 ,0
Exp/Cntr=0.3,0.1

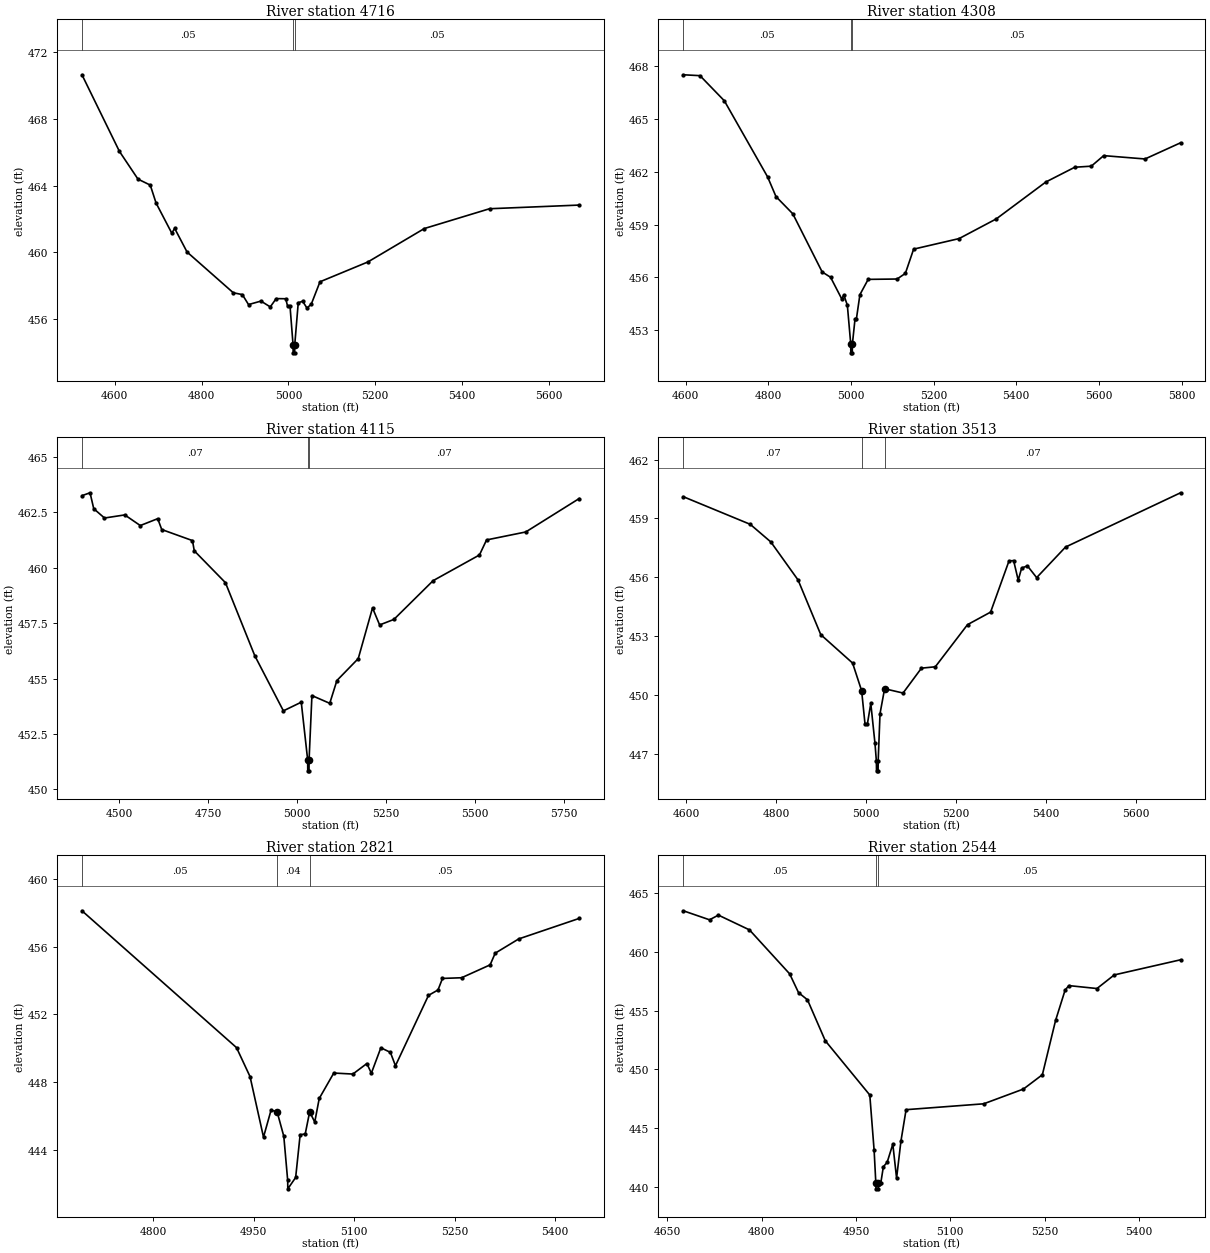
Type RM Length L Ch R = 1 ,4716    ,408,408,408
BEGIN DESCRIPTION:
Mapping XS b38a1d16
END DESCRIPTION:
XS GIS Cut Line= 3
      2745025.52      6911839.17      2744664.38      6912148.22
      2744629.72       6912817.2
#Sta/Elev= 30
  4524.5  470.66  4610.7  466.06  4653.5  464.39  4681.8  464.03  4695.2  462.95
  4731.4  461.14    4738  461.43  4766.5  460.01    4873  457.56  4893.9  457.45
  4908.1  456.85  4936.7  457.06  4958.2  456.71  4971.8  457.21  4993.8   457.2
  4998.1  456.75  5003.7  456.75  5010.6  454.45  5010.9  453.95  5014.4  453.95
  5014.6  454.45  5022.6  456.96  5032.7  457.05  5042.7  456.64  5052.7  456.88
  5072.7  458.22  5182.9  459.41    5313  461.42  5463.2  462.61  5669.7  462.83
#Mann= 3 ,-1 , 0
  4524.5     .05       0  5010.6     .04       0  5014.6     .05       0
Bank Sta=5010.6,5014.6
XS Rating Curve= 0 ,0
Exp/Cntr=0.3,0.1

Type RM Length L Ch R = 1 ,4308    ,193,193,193
BEGIN DESCRIPTION:
Mapping XS d806f107
END DESCRIPTION:
XS GIS Cut Line= 3
      2744608.83      6911510.18      2744535.04      6911922.52
      2744535.04      6912707.03
#Sta/Elev= 30
  4594.2  467.52  4634.6  467.47  4693.5  466.04  4798.2  461.71  4818.5  460.59
  4859.2  459.61  4930.3   456.3  4950.6     456  4977.6  454.77  4982.7  454.99
  4991.2  454.41  4999.4   452.2  4999.6   451.7  5003.1   451.7  5003.4   452.2
  5009.8  453.63  5013.1  453.63  5021.6  455.01  5041.6  455.88  5111.6   455.9
  5131.6  456.22  5151.6   457.6  5261.6   458.2  5351.6  459.32  5471.6  461.42
  5541.6  462.26  5581.6  462.32  5611.6  462.92  5711.6  462.73  5797.6  463.65
#Mann= 3 ,-1 , 0
  4594.2     .05       0  4999.4     .05       0  5003.4     .05       0
Bank Sta=4999.4,5003.4
XS Rating Curve= 0 ,0
Exp/Cntr=0.3,0.1

Type RM Length L Ch R = 1 ,4115    ,602,602,602
BEGIN DESCRIPTION:
Flat T5 8.0
END DESCRIPTION:
XS GIS Cut Line= 3
      2744443.89      6911268.05      2744381.39      6911856.55
        2744426.        6912661.
#Sta/Elev= 30
  4395.6  463.26  4418.3  463.39  4428.7  462.67  4458.9  462.25  4515.9  462.39
  4559.5  461.91  4608.5  462.22  4619.8  461.73  4706.2  461.23  4711.2  460.77
  4798.8  459.33  4881.3  456.03  4961.7  453.54  5011.9  453.93  5029.9  451.33
  5030.2  450.83  5033.7  450.83  5033.9  451.33  5041.9  454.23    5092  453.88
  5112.1  454.91  5172.1   455.9  5212.2  458.19  5232.2  457.42  5272.3  457.67
  5382.5  459.42  5512.7  460.58  5532.7  461.26  5642.9  461.62  5793.1  463.13
#Mann= 3 ,-1 , 0
  4395.6     .07       0  5029.9     .04       0  5033.9     .07       0
Bank Sta=5029.9,5033.9
XS Rating Curve= 0 ,0
Exp/Cntr=0.3,0.1

Type RM Length L Ch R = 1 ,3513    ,692,692,692
BEGIN DESCRIPTION:
Flat T5 7.0
END DESCRIPTION:
XS GIS Cut Line= 3
      2744001.19      6911358.24      2743945.87      6911760.96
      2744096.68       6912443.4
#Sta/Elev= 30
  4593.5  460.11  4742.3   458.7  4788.1   457.8  4848.6  455.86  4899.1  453.07
  4969.8  451.62  4989.9  450.21  4997.5   448.5  5002.6   448.5  5010.3  449.56
  5019.6  447.52  5022.7  446.62    5023  446.12  5026.5  446.12  5026.7  446.62
  5030.8  449.04    5041  450.31    5082  450.09  5122.9  451.36  5153.7  451.43
  5225.3  453.58  5276.6  454.22  5317.5  456.83  5327.8  456.85    5338  455.85
  5345.7  456.47  5358.5  456.58    5379  455.98  5443.2  457.54  5698.9  460.31
#Mann= 3 ,-1 , 0
  4593.5     .07       0  4989.9     .04       0    5041     .07       0
Bank Sta=4989.9,5041
XS Rating Curve= 0 ,0
Exp/Cntr=0.3,0.1

Type RM Length L Ch R = 1 ,2821    ,277,277,277
BEGIN DESCRIPTION:
Mapping XS 815b0fb4
END DESCRIPTION:
XS GIS Cut Line= 3
      2743483.83      6911712.38      2743525.49      6912021.37
      2743810.22      6912344.29
#Sta/Elev= 30
  4693.7  458.11  4924.4  450.04  4944.6  448.33  4964.7  444.76  4975.9  446.34
  4984.9  446.27    4995  444.81  5000.8  442.21    5001  441.71  5012.7  442.38
  5019.4   444.9    5027  444.95  5033.6  446.25  5041.2  445.65  5047.9  447.04
  5069.6  448.54  5098.1  448.48    5119   449.1  5125.7  448.53  5139.9  450.03
  5154.1  449.76  5161.7  448.97    5211  453.12  5225.2  453.44  5231.9  454.12
  5260.4  454.16    5303  454.92  5310.6  455.61  5345.7  456.45    5436  457.66
#Mann= 3 ,-1 , 0
  4693.7     .05       0  4984.9     .04       0  5033.6     .05       0
Bank Sta=4984.9,5033.6
XS Rating Curve= 0 ,0
Exp/Cntr=0.3,0.1

Type RM Length L Ch R = 1 ,2544    ,269,269,269
BEGIN DESCRIPTION:
Mapping XS 300eef4e
END DESCRIPTION:
XS GIS Cut Line= 3
      2743112.27      6911965.78      2743327.57      6912191.51
      2743726.91      6912455.41
#Sta/Elev= 30
  4675.4  463.52  4717.1  462.75  4731.2  463.15  4780.6  461.89  4844.5  458.14
  4858.6  456.54  4872.8  455.93  4901.1  452.44  4971.9  447.81  4978.8  443.08
  4981.5  440.31  4981.8  439.81  4985.3  439.81  4985.5  440.31  4989.4  440.31
  4993.5   441.7  4999.5  442.07  5008.5  443.62  5014.5  440.72  5021.4  443.87
  5029.6  446.56    5153  447.06  5216.2  448.32  5246.3  449.54  5267.3  454.17
  5282.4  456.75  5288.4  457.14  5333.1  456.89  5360.6  458.05    5466  459.34
#Mann= 3 ,-1 , 0
  4675.4     .05       0  4981.5     .04       0  4985.5     .05       0
Bank Sta=4981.5,4985.5
XS Rating Curve= 0 ,0
Exp/Cntr=0.3,0.1

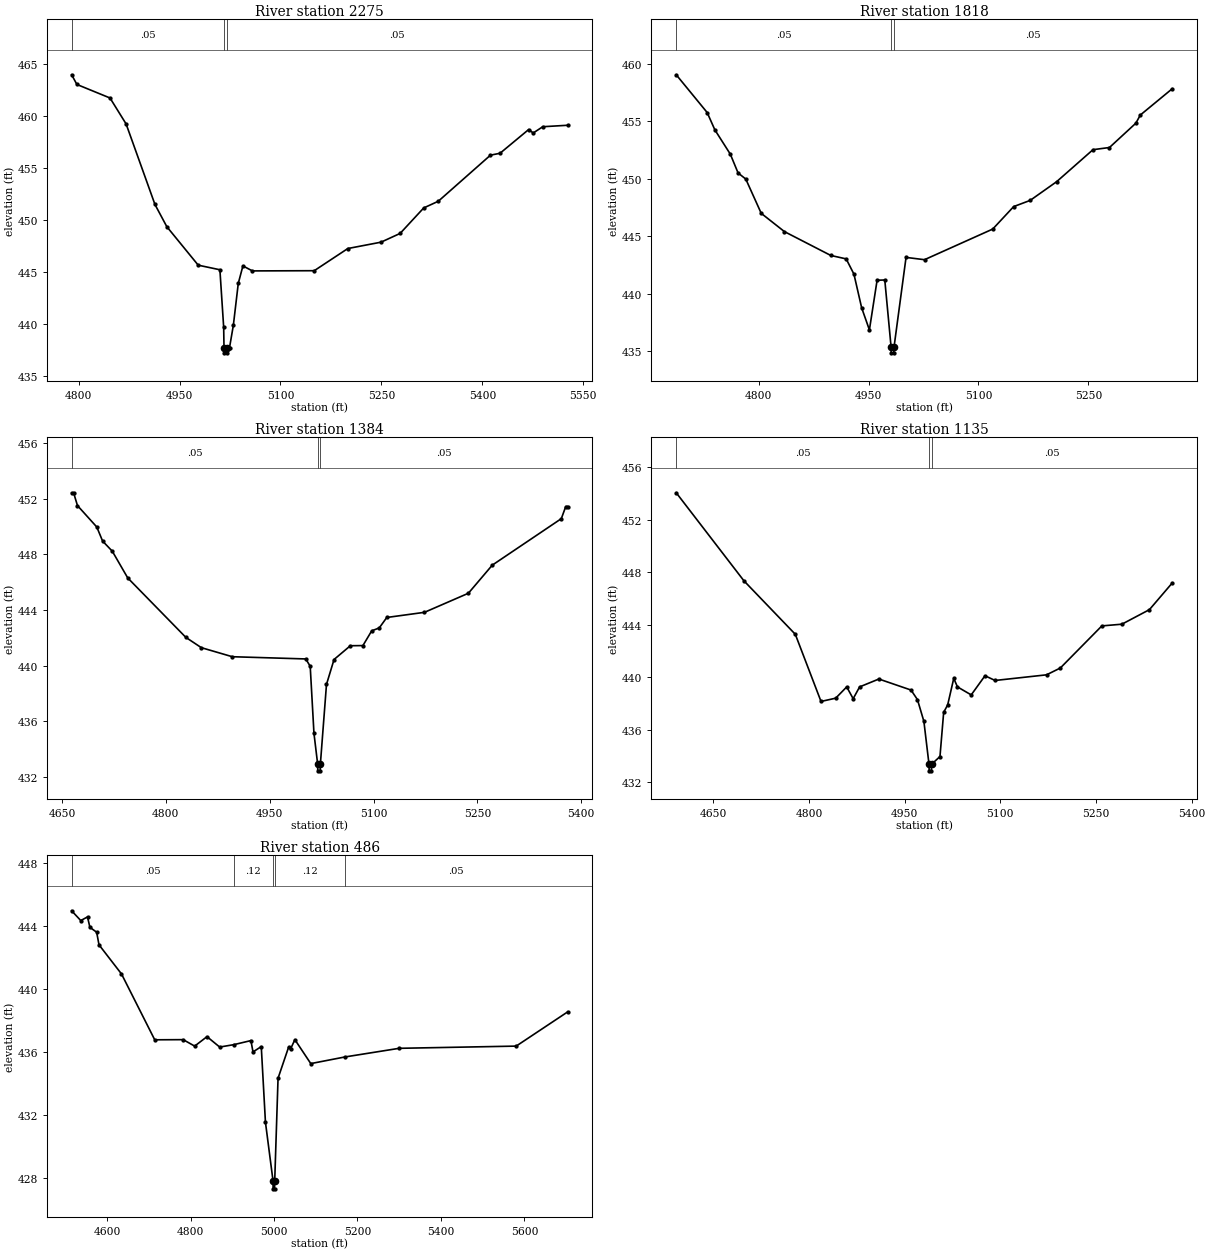
Type RM Length L Ch R = 1 ,2275    ,457,457,457
BEGIN DESCRIPTION:
Mapping XS 773ceba1
END DESCRIPTION:
XS GIS Cut Line= 3
      2743039.39      6912125.56      2743122.71      6912340.81
      2743494.26      6912684.58
#Sta/Elev= 30
  4789.7  463.92  4797.5  462.99  4846.7  461.69  4870.6   459.2  4913.5  451.46
  4931.1  449.33  4977.8  445.63    5010  445.19  5015.6  439.67  5016.1  437.71
  5016.4  437.21  5019.9  437.21  5020.1  437.71  5024.3  437.71    5030  439.86
  5037.3  443.88  5044.2  445.56  5058.3  445.08  5150.2   445.1  5200.1  447.23
  5249.4  447.84  5277.8  448.68  5312.9  451.13  5334.5  451.77  5412.1   456.2
  5426.3  456.38  5468.8  458.66  5475.6  458.33  5489.8  458.93  5526.7  459.07
#Mann= 3 ,-1 , 0
  4789.7     .05       0  5016.1     .04       0  5020.1     .05       0
Bank Sta=5016.1,5020.1
XS Rating Curve= 0 ,0
Exp/Cntr=0.3,0.1

Type RM Length L Ch R = 1 ,1818    ,434,434,434
BEGIN DESCRIPTION:
Flat T5 3.0
END DESCRIPTION:
XS GIS Cut Line= 3
      2742825.99      6912360.96        2742926.        6912661.
      2743225.98      6912860.99
#Sta/Elev= 30
  4687.6  459.07  4729.8  455.78  4740.3  454.27  4761.4  452.15    4772  450.51
  4782.5  449.98  4803.6  446.99  4835.2   445.4  4898.5  443.32  4919.5  443.02
  4930.1  441.69  4940.6  438.76  4951.2  436.83  4961.7  441.16  4972.2  441.18
  4980.8  435.33    4981  434.83  4984.5  434.83  4984.8  435.33  5001.2  443.15
  5026.4  442.95  5119.5  445.62  5148.1  447.58  5170.6  448.12  5206.7  449.75
  5256.3  452.54  5278.8  452.73  5314.8  454.85  5320.9  455.56  5364.4  457.85
#Mann= 3 ,-1 , 0
  4687.6     .05       0  4980.8     .04       0  4984.8     .05       0
Bank Sta=4980.8,4984.8
XS Rating Curve= 0 ,0
Exp/Cntr=0.3,0.1

Type RM Length L Ch R = 1 ,1384    ,249,249,249
BEGIN DESCRIPTION:
Flat T5 2.0
END DESCRIPTION:
XS GIS Cut Line= 3
        2742426.      6912511.01        2742576.        6912811.
      2742926.01        6912961.
#Sta/Elev= 30
  4664.1  452.42  4666.9  452.42  4672.5   451.5  4700.4  449.96  4708.8  448.95
  4722.8  448.22  4745.1   446.3    4829  442.03  4851.4  441.29  4896.1  440.64
  5002.2  440.48  5008.6  439.95    5014  435.14  5019.3  432.94  5019.5  432.44
    5023  432.44  5023.3  432.94  5032.1  438.65    5043  440.44  5066.6  441.43
  5084.7  441.44  5097.4   442.5  5108.3  442.71  5119.2  443.46  5173.6  443.83
    5237   445.2  5271.5  447.22  5371.2  450.56  5377.6  451.43  5380.3  451.43
#Mann= 3 ,-1 , 0
  4664.1     .05       0  5019.3     .04       0  5023.3     .05       0
Bank Sta=5019.3,5023.3
XS Rating Curve= 0 ,0
Exp/Cntr=0.3,0.1

Type RM Length L Ch R = 1 ,1135    ,649,649,649
BEGIN DESCRIPTION:
Mapping XS 5d511e91
END DESCRIPTION:
XS GIS Cut Line= 3
      2742310.21      6912505.75      2742360.91      6912910.79
      2742681.79      6913093.81
#Sta/Elev= 30
  4591.8  454.06  4697.9  447.35  4778.5  443.27  4818.8  438.15  4841.8   438.4
  4859.1  439.26  4869.2  438.36  4879.3  439.26  4909.5  439.86  4959.9  439.02
    4970  438.29  4980.1  436.63  4988.1  433.36  4988.4  432.86  4991.9  432.86
  4992.1  433.36  5005.3  433.95  5011.1  437.32  5017.4  437.89  5026.9  439.91
  5032.7  439.26  5054.3  438.65  5075.9  440.11  5091.7  439.75  5172.4  440.18
    5194   440.7  5259.1  443.91  5290.5  444.04  5333.7  445.15  5369.4  447.18
#Mann= 3 ,-1 , 0
  4591.8     .05       0  4988.1     .04       0  4992.1     .05       0
Bank Sta=4988.1,4992.1
XS Rating Curve= 0 ,0
Exp/Cntr=0.3,0.1

Type RM Length L Ch R = 1 ,486     ,0,0,0
BEGIN DESCRIPTION:
Flat T5 1.0
END DESCRIPTION:
XS GIS Cut Line= 4
      2742050.98      6912736.04      2741858.17      6913091.57
      2741877.27      6913261.71      2742489.07      6913287.65
#Sta/Elev= 30
  4515.3  444.94  4537.1  444.32  4553.3  444.55    4559  443.89  4575.2  443.58
  4580.8  442.78  4634.7  440.93  4714.3  436.75  4782.4  436.76    4810  436.35
  4839.5  436.95  4869.9  436.29  4903.4  436.44  4944.7   436.7  4949.7  435.98
  4969.5  436.32  4979.5  431.52  4997.7  427.79  4997.9  427.29  5001.4  427.29
  5001.7  427.79  5009.7  434.31  5034.8  436.27  5039.9  436.18    5050  436.76
  5088.1  435.24  5169.7  435.66  5299.9  436.21  5580.1  436.35  5703.3  438.52
#Mann= 5 ,-1 , 0
  4515.3     .05       0  4903.4     .12       0  4997.7     .07       0
  5001.7     .12       0  5169.7     .05       0
Bank Sta=4997.7,5001.7
XS Rating Curve= 0 ,0
Exp/Cntr=0.3,0.1

Chan Stop Cuts=-1
Use User Specified Reach Order=0
Composite Channel Slope=5