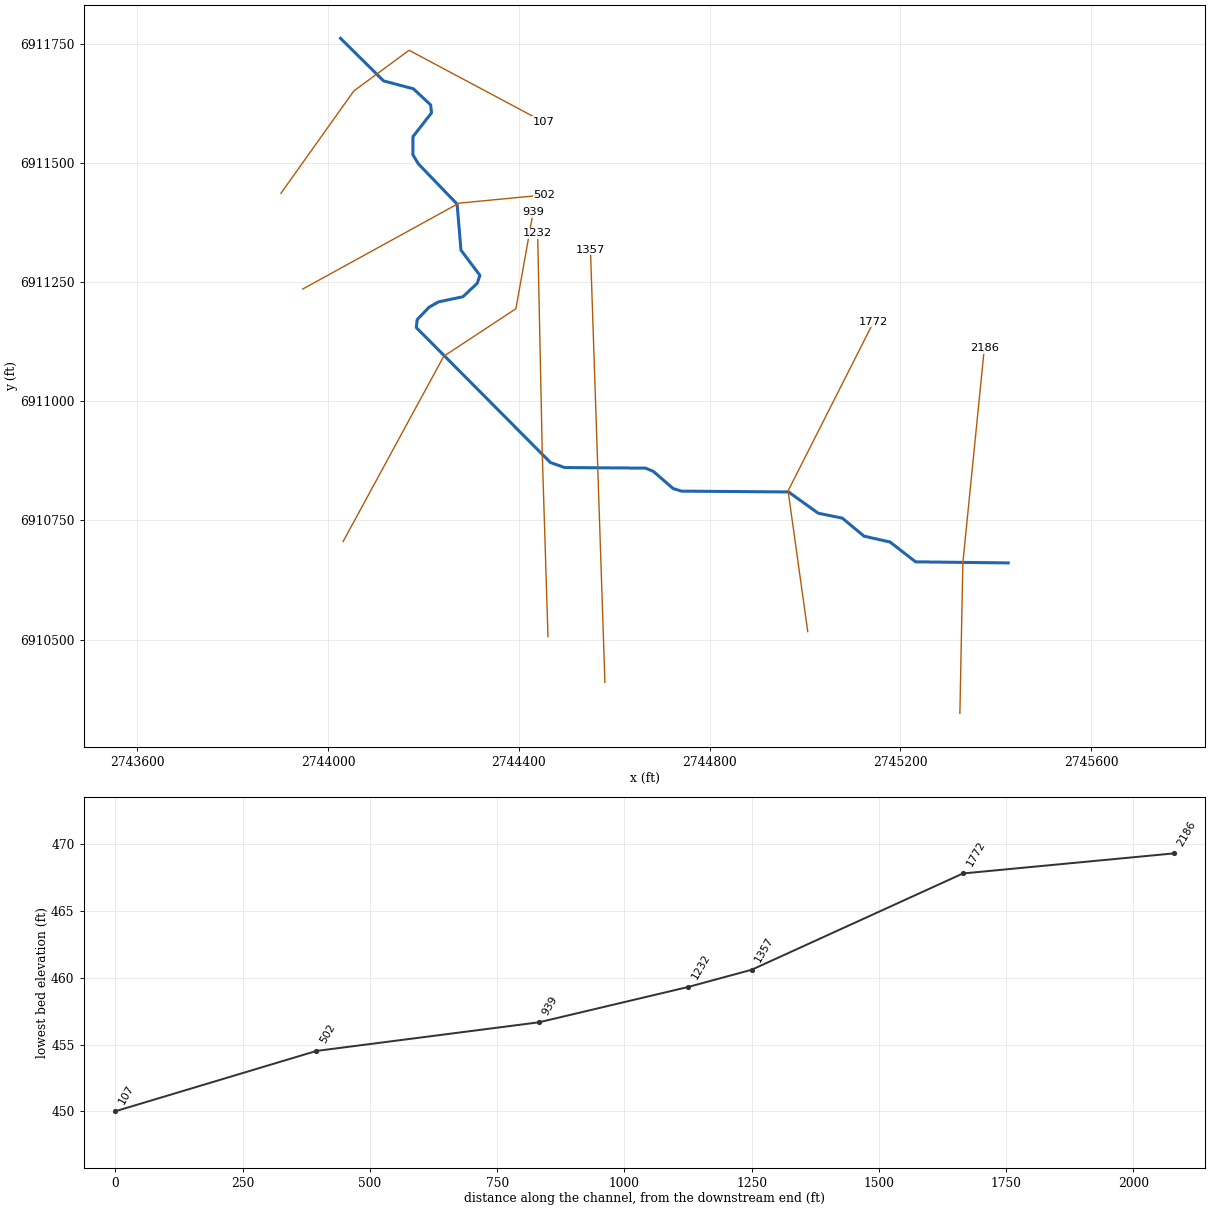
--- Flat T5_1.prj (project) ---

Proj Title=Flat T5_1 Base Level Engineering
Current Plan=p01
Default Exp/Contr=0.3,0.1
English Units
Geom File=g01
Flow File=f01
Plan File=p01
Y Axis Title=Elevation
X Axis Title(PF)=Main Channel Distance
X Axis Title(XS)=Station
BEGIN DESCRIPTION:
Flat T5_1
END DESCRIPTION:
DSS Export Rating Curves= 0
DSS Export Rating Curve Sorted= 0
DSS Export Volume Flow Curves= 0
DXF OffsetX= 0
DXF OffsetY= 0
DXF ScaleX= 1
DXF ScaleY= 10

--- Flat T5_1.p01 (plan) ---

Plan Title=Multiple Run
Short Identifier=Multiple
Geom File=g01
Flow File=f01
Subcritical Flow
K Sum by GR= 0
Std Step Tol= 0.01
Critical Tol= 0.01
Num of Std Step Trials= 20
Max Error Tol= 0.3
Flow Tol Ratio= 0.001
Split Flow NTrial= 30
Split Flow Tol= 0.02
Split Flow Ratio= 0.02
Log Output Level= 0
Friction Slope Method= 1
Unsteady Friction Slope Method= 2
Unsteady Bridges Friction Slope Method= 1
Parabolic Critical Depth
Global Vel Dist=  1 , 1 , 1
Global Log Level= 0
CheckData=True
Encroach Param= -1, 0, 0, 0
BEGIN DESCRIPTION:
Multiple Run
END DESCRIPTION:

--- Flat T5_1.f01 (steady flow) ---

Flow Title=Multiple
Program Version=4.10
Number of Profiles= 7
Profile Names=10-year,25-year,50-year,1pct_min,100-year,1pct_plu,500-year
River Rch & RM=Flat T5_1,Reach-1         ,2186
     179     222     255     146     292     582     382
Boundary for River Rch & Prof#=Flat T5_1,Reach-1         , 1
Up Type= 0
Dn Type= 3
Dn Slope=0.0112
Boundary for River Rch & Prof#=Flat T5_1,Reach-1         , 2
Up Type= 0
Dn Type= 3
Dn Slope=0.0112
Boundary for River Rch & Prof#=Flat T5_1,Reach-1         , 3
Up Type= 0
Dn Type= 3
Dn Slope=0.0112
Boundary for River Rch & Prof#=Flat T5_1,Reach-1         , 4
Up Type= 0
Dn Type= 3
Dn Slope=0.0112
Boundary for River Rch & Prof#=Flat T5_1,Reach-1         , 5
Up Type= 0
Dn Type= 3
Dn Slope=0.0112
Boundary for River Rch & Prof#=Flat T5_1,Reach-1         , 6
Up Type= 0
Dn Type= 3
Dn Slope=0.0112
Boundary for River Rch & Prof#=Flat T5_1,Reach-1         , 7
Up Type= 0
Dn Type= 3
Dn Slope=0.0112
DSS Import GetInterval= 0
DSS Import GetPeak= 0
DSS Import FillOption= 0

--- Flat T5_1.g01 (geometry) ---

Geom Title=Existing Conditions
Program Version=4.10

River Reach=Flat T5_1       ,Reach-1
Reach XY= 30
        2745426.        6910661.      2745231.92      6910663.23
      2745178.18      6910704.88       2745123.8      6910717.08
       2745078.2      6910754.92      2745027.74      6910765.19
       2744965.5       6910809.8      2744741.22      6910811.52
      2744723.67      6910816.75      2744682.06      6910852.86
      2744665.49      6910859.78      2744495.98      6910860.96
       2744466.2      6910871.48      2744184.89      6911154.49
      2744186.82      6911171.32      2744211.97      6911197.37
      2744231.72      6911208.46      2744282.65      6911219.15
      2744312.61      6911247.27       2744318.2      6911264.03
      2744278.57      6911316.88      2744270.46      6911413.42
      2744189.16       6911497.8      2744177.67      6911517.06
      2744177.99      6911554.96      2744216.73       6911604.6
      2744215.02      6911621.37      2744178.85      6911655.16
      2744116.33      6911671.72        2744026.        6911761.

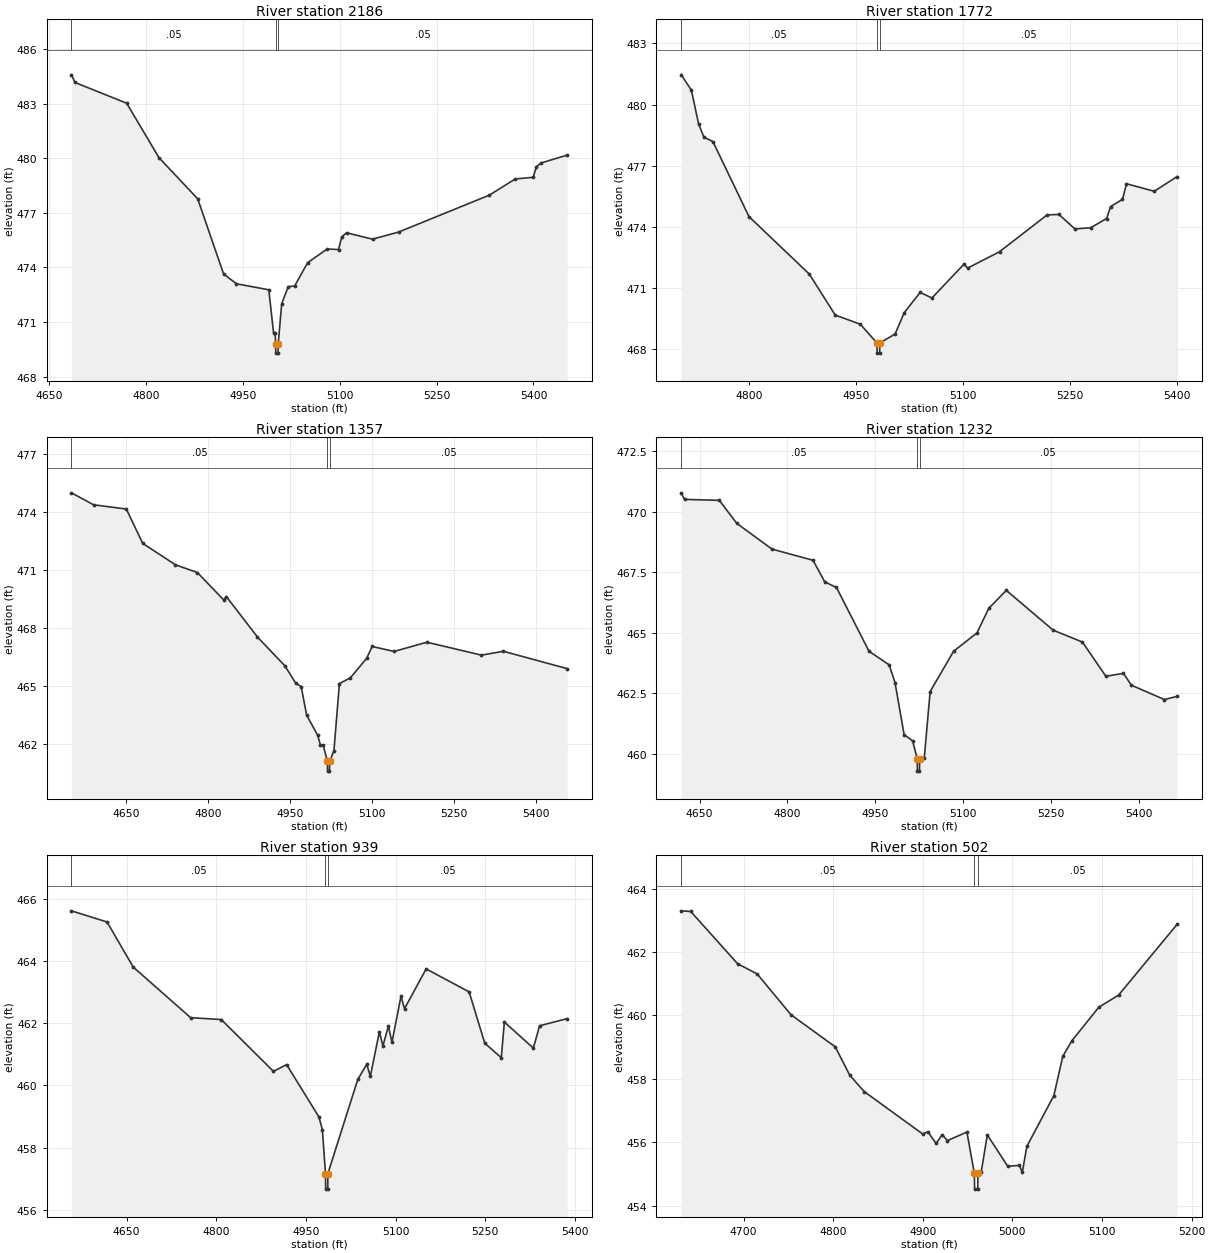
Type RM Length L Ch R = 1 ,2186    ,414,414,414
BEGIN DESCRIPTION:
Flat T5_1 4.0
END DESCRIPTION:
XS GIS Cut Line= 3
      2745324.75      6910345.49      2745330.97      6910660.93
        2745376.      6911110.98
#Sta/Elev= 30
  4684.5  484.58    4690  484.16    4770  483.02    4820  480.03    4880  477.77
  4920.1  473.64  4940.1   473.1  4990.1  472.77  4997.5  470.41    5000  470.41
  5000.7  469.79  5000.9  469.29  5004.4  469.29  5004.7  469.79  5010.1     472
  5020.2  472.94  5030.2  472.98  5050.3  474.26  5080.5  475.01  5098.1  474.98
  5103.2  475.68  5110.6   475.9  5150.8  475.55    5191  475.94  5331.7  477.97
  5371.9  478.86  5399.6  478.95  5404.6  479.53  5412.1  479.74  5452.3  480.17
#Mann= 3 ,-1 , 0
  4684.5     .05       0  5000.7     .04       0  5004.7     .05       0
Bank Sta=5000.7,5004.7
XS Rating Curve= 0 ,0
Exp/Cntr=0.3,0.1

Type RM Length L Ch R = 1 ,1772    ,415,415,415
BEGIN DESCRIPTION:
Mapping XS ef94e394
END DESCRIPTION:
XS GIS Cut Line= 3
      2745005.74      6910516.95      2744964.51      6910812.07
      2745144.15      6911167.01
#Sta/Elev= 30
  4704.2  481.46  4718.4  480.71  4728.5  479.06    4736   478.4  4748.7  478.18
  4799.2   474.5    4884  471.67  4920.3  469.66  4955.5  469.21  4978.9  468.29
  4979.2  467.79  4982.7  467.79  4982.9  468.29  5004.4  468.73  5017.2  469.78
  5039.5  470.77  5056.1   470.5  5100.7  472.15  5106.3  471.97  5150.9  472.77
  5217.7  474.58  5234.4   474.6  5256.7  473.89  5278.9  473.95  5301.2   474.4
  5306.8  474.99  5323.5  475.34  5329.1  476.11  5368.1  475.74    5400  476.46
#Mann= 3 ,-1 , 0
  4704.2     .05       0  4978.9     .04       0  4982.9     .05       0
Bank Sta=4978.9,4982.9
XS Rating Curve= 0 ,0
Exp/Cntr=0.3,0.1

Type RM Length L Ch R = 1 ,1357    ,125,125,125
BEGIN DESCRIPTION:
Mapping XS 3df1750d
END DESCRIPTION:
XS GIS Cut Line= 3
       2744580.4      6910410.56       2744565.2      6910866.32
      2744550.08      6911317.95
#Sta/Elev= 30
  4549.4  475.01  4589.9  474.39  4649.9  474.17  4679.9  472.39  4739.9  471.28
    4780  470.88  4828.2  469.46  4833.2  469.63    4890  467.54  4940.1  466.05
  4960.1  465.15  4970.1  464.97  4980.1  463.49  5000.1  462.46  5005.3  461.95
  5010.3  461.95  5018.1  461.09  5018.4  460.59  5021.9  460.59  5022.1  461.09
  5030.1  461.65  5040.1  465.13  5060.1  465.42  5090.1  466.44  5100.1  467.05
  5140.2  466.79  5200.2  467.27  5300.3   466.6  5340.3   466.8  5457.3   465.9
#Mann= 3 ,-1 , 0
  4549.4     .05       0  5018.1     .05       0  5022.1     .05       0
Bank Sta=5018.1,5022.1
XS Rating Curve= 0 ,0
Exp/Cntr=0.3,0.1

Type RM Length L Ch R = 1 ,1232    ,293,293,293
BEGIN DESCRIPTION:
Mapping XS 702b9b26
END DESCRIPTION:
XS GIS Cut Line= 3
      2744461.04      6910506.05      2744449.13      6910887.17
      2744439.34      6911352.46
#Sta/Elev= 30
  4618.7  470.77  4624.3   470.5  4683.7  470.46  4713.7  469.51  4773.7  468.45
  4843.8  467.99  4863.8   467.1  4883.8  466.87  4939.4  464.24  4973.8  463.68
  4983.8  462.95  4999.4   460.8  5013.8  460.55  5021.8   459.8  5022.1   459.3
  5025.6   459.3  5025.8   459.8  5033.8  459.85  5043.8  462.58  5083.9  464.24
  5123.9     465  5143.9  466.01  5173.9  466.75  5253.9  465.11  5303.9  464.62
  5343.9  463.21  5373.9  463.33  5387.6  462.84  5443.9  462.25  5465.4  462.38
#Mann= 3 ,-1 , 0
  4618.7     .05       0  5021.8     .04       0  5025.8     .05       0
Bank Sta=5021.8,5025.8
XS Rating Curve= 0 ,0
Exp/Cntr=0.3,0.1

Type RM Length L Ch R = 1 ,939     ,437,437,437
BEGIN DESCRIPTION:
Mapping XS 97cb20d8
END DESCRIPTION:
XS GIS Cut Line= 4
      2744031.37      6910705.77      2744242.46      6911094.34
      2744393.76      6911194.01      2744429.97      6911396.83
#Sta/Elev= 30
  4557.8  465.62  4617.4  465.26  4661.1  463.81  4757.2  462.18  4808.4  462.12
  4895.8  460.45  4917.7  460.67  4971.9  458.98  4977.6  458.57  4982.8  457.16
  4983.1  456.66  4986.6  456.66  4986.8  457.16  5036.8  460.19  5051.8  460.68
  5057.8  460.29  5072.9  461.72  5078.9  461.27    5088  461.91    5094  461.39
  5109.1  462.87    5115  462.47  5151.2  463.75  5223.1  463.01  5249.2  461.36
  5276.9  460.89    5282  462.04  5330.5   461.2    5341  461.92  5387.2  462.15
#Mann= 3 ,-1 , 0
  4557.8     .05       0  4982.8     .04       0  4986.8     .05       0
Bank Sta=4982.8,4986.8
XS Rating Curve= 0 ,0
Exp/Cntr=0.3,0.1

Type RM Length L Ch R = 1 ,502     ,395,395,395
BEGIN DESCRIPTION:
Mapping XS 1dfdb398
END DESCRIPTION:
XS GIS Cut Line= 3
      2743946.74      6911235.26      2744274.41      6911415.37
      2744452.78      6911432.56
#Sta/Elev= 30
  4630.5   463.3  4641.1  463.28  4693.4  461.63  4715.2  461.31    4753  460.02
  4802.3  459.01  4818.4  458.12  4834.5   457.6  4899.9  456.26  4905.6  456.33
  4914.9  455.96  4921.7  456.24  4927.4  456.05  4949.2  456.32  4957.5  455.02
  4957.8  454.52  4961.3  454.52  4961.5  455.02  4965.2  455.07    4972  456.23
  4994.8  455.24  5007.7  455.27    5011  455.05  5016.1  455.87  5046.2  457.47
  5056.2  458.71  5066.3   459.2  5096.4  460.26  5118.4  460.64  5183.6  462.87
#Mann= 3 ,-1 , 0
  4630.5     .05       0  4957.5     .04       0  4961.5     .05       0
Bank Sta=4957.5,4961.5
XS Rating Curve= 0 ,0
Exp/Cntr=0.3,0.1

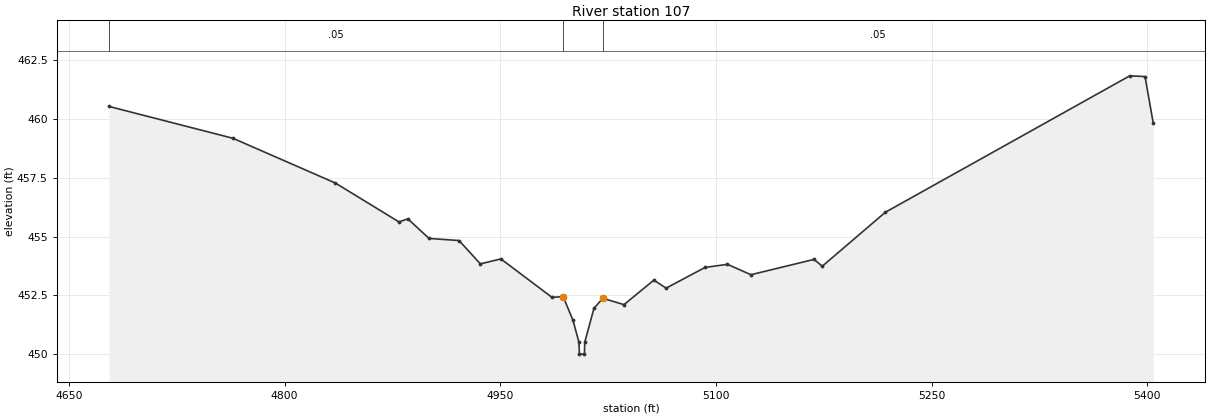
Type RM Length L Ch R = 1 ,107     ,0,0,0
BEGIN DESCRIPTION:
Flat  T5_1 1.0
END DESCRIPTION:
XS GIS Cut Line= 4
        2743901.        6911436.      2744053.83       6911650.6
      2744169.72        6911736.      2744451.01        6911586.
#Sta/Elev= 30
  4677.9  460.52    4764  459.17  4835.3  457.27  4879.5  455.62  4885.7  455.75
  4900.4  454.92  4921.3  454.83  4936.1  453.84  4950.4  454.05  4985.9  452.42
  4993.7  452.45  5000.5  451.45  5004.7  450.51    5005  450.01  5008.5  450.01
  5008.7  450.51  5015.1  451.95  5021.3  452.38    5036  452.11  5056.8  453.15
  5065.3  452.81  5092.4  453.69    5108  453.82  5124.3  453.38  5168.2  454.03
  5173.9  453.74  5217.8  456.03  5387.8  461.82  5398.4  461.79  5404.1  459.82
#Mann= 3 ,-1 , 0
  4677.9     .05       0  4993.7     .04       0  5021.3     .05       0
Bank Sta=4993.7,5021.3
XS Rating Curve= 0 ,0
Exp/Cntr=0.3,0.1

Chan Stop Cuts=-1
Use User Specified Reach Order=0
Composite Channel Slope=5