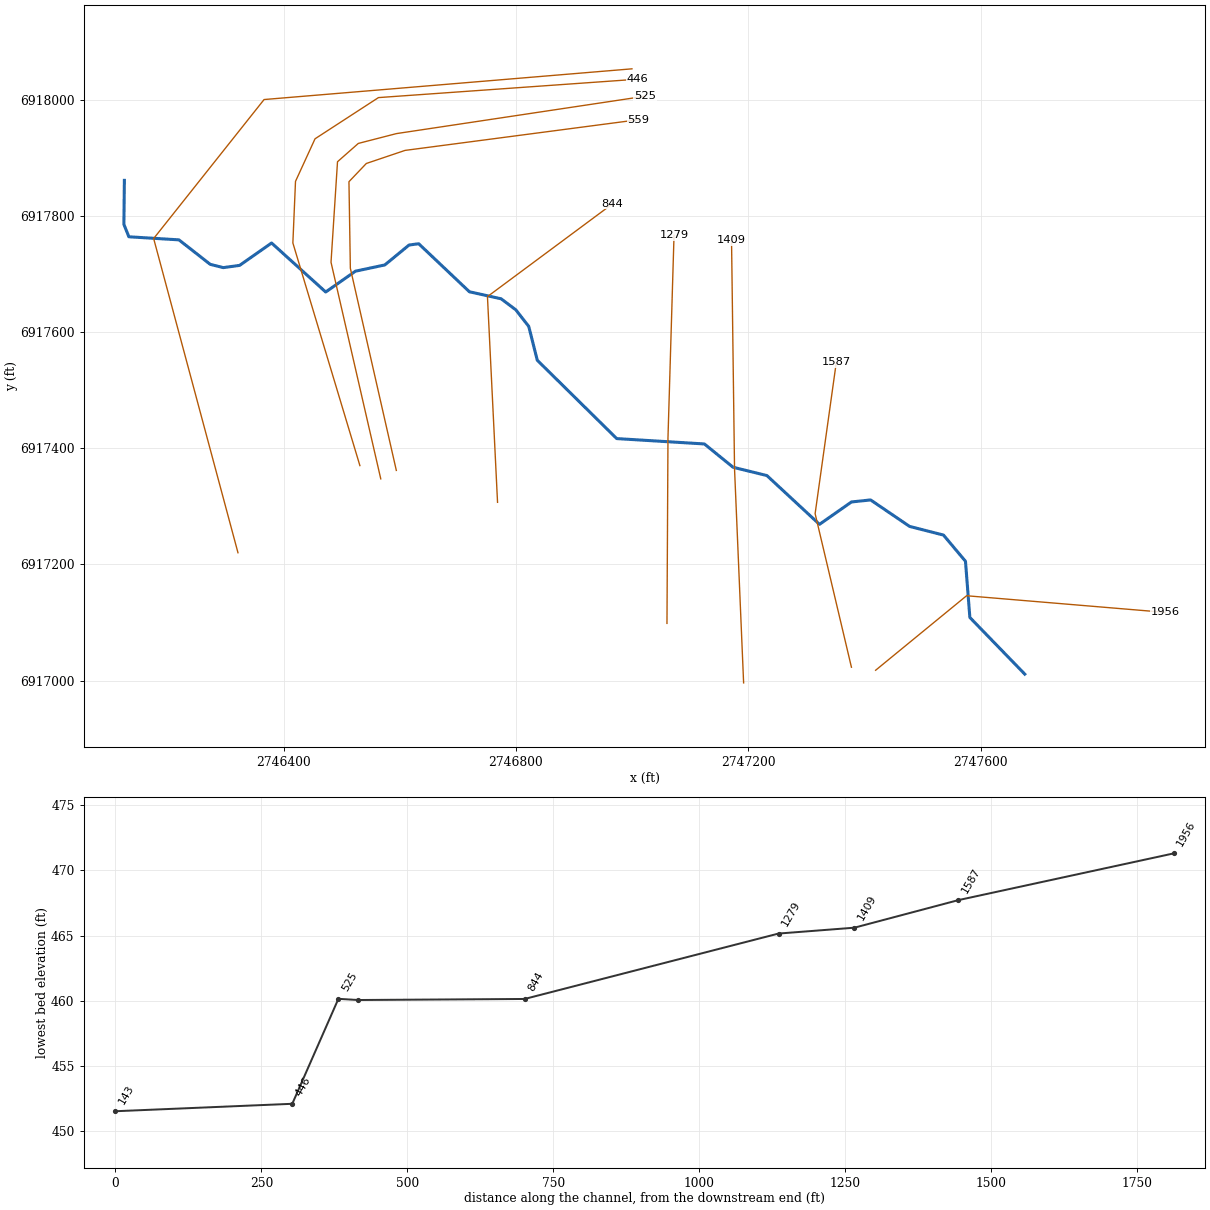
--- Flat T6.prj (project) ---

Proj Title=Flat T6 Base Level Engineering
Current Plan=p01
Default Exp/Contr=0.3,0.1
English Units
Geom File=g01
Flow File=f01
Plan File=p01
BEGIN DESCRIPTION:
Flat T6
END DESCRIPTION:

--- Flat T6.p01 (plan) ---

Plan Title=Multiple Run
Short Identifier=Multiple
Geom File=g01
Flow File=f01
Subcritical Flow
K Sum by GR= 0
Std Step Tol= 0.01
Critical Tol= 0.01
Num of Std Step Trials= 20
Max Error Tol= 0.3
Flow Tol Ratio= 0.001
Split Flow NTrial= 30
Split Flow Tol= 0.02
Split Flow Ratio= 0.02
Log Output Level= 0
Friction Slope Method= 1
Unsteady Friction Slope Method= 2
Unsteady Bridges Friction Slope Method= 1
Parabolic Critical Depth
Global Vel Dist=  1 , 1 , 1
Global Log Level= 0
CheckData=True
Encroach Param= -1, 0, 0, 0
BEGIN DESCRIPTION:
Multiple Run
END DESCRIPTION:

--- Flat T6.f01 (steady flow) ---

Flow Title=Multiple
Number of Profiles=7
Profile Names=10-year,25-year,50-year,1pct_min,100-year,1pct_plu,500-year
River Rch & RM= Flat T6,Reach-1,1956
     209     262     303     175     350     698     464
Boundary for River Rch & Prof#=Flat T6,Reach-1,1
Up Type=0
Dn Type=3
Dn Slope=0.005
Boundary for River Rch & Prof#=Flat T6,Reach-1,2
Up Type=0
Dn Type=3
Dn Slope=0.005
Boundary for River Rch & Prof#=Flat T6,Reach-1,3
Up Type=0
Dn Type=3
Dn Slope=0.005
Boundary for River Rch & Prof#=Flat T6,Reach-1,4
Up Type=0
Dn Type=3
Dn Slope=0.005
Boundary for River Rch & Prof#=Flat T6,Reach-1,5
Up Type=0
Dn Type=3
Dn Slope=0.005
Boundary for River Rch & Prof#=Flat T6,Reach-1,6
Up Type=0
Dn Type=3
Dn Slope=0.005
Boundary for River Rch & Prof#=Flat T6,Reach-1,7
Up Type=0
Dn Type=3
Dn Slope=0.005

--- Flat T6.g01 (geometry) ---

Geom Title=Existing Conditions

River Reach=Flat T6,Reach-1
Reach XY= 30
      2747676.00      6917011.00      2747581.46      6917108.55
      2747573.92      6917205.29      2747536.06      6917250.39
      2747477.77      6917265.26      2747410.59      6917310.86
      2747377.64      6917307.39      2747322.60      6917268.83
      2747232.06      6917352.82      2747173.83      6917367.14
      2747124.44      6917407.24      2746973.55      6917416.47
      2746836.79      6917551.34      2746822.11      6917609.57
      2746799.84      6917638.14      2746774.57      6917657.11
      2746719.97      6917669.21      2746632.72      6917751.87
      2746616.13      6917749.72      2746574.35      6917715.40
      2746523.71      6917704.62      2746472.59      6917668.80
      2746379.41      6917753.15      2746324.37      6917714.62
      2746296.21      6917710.79      2746273.83      6917716.40
      2746219.95      6917758.59      2746133.80      6917763.86
      2746125.17      6917785.19      2746126.00      6917861.00

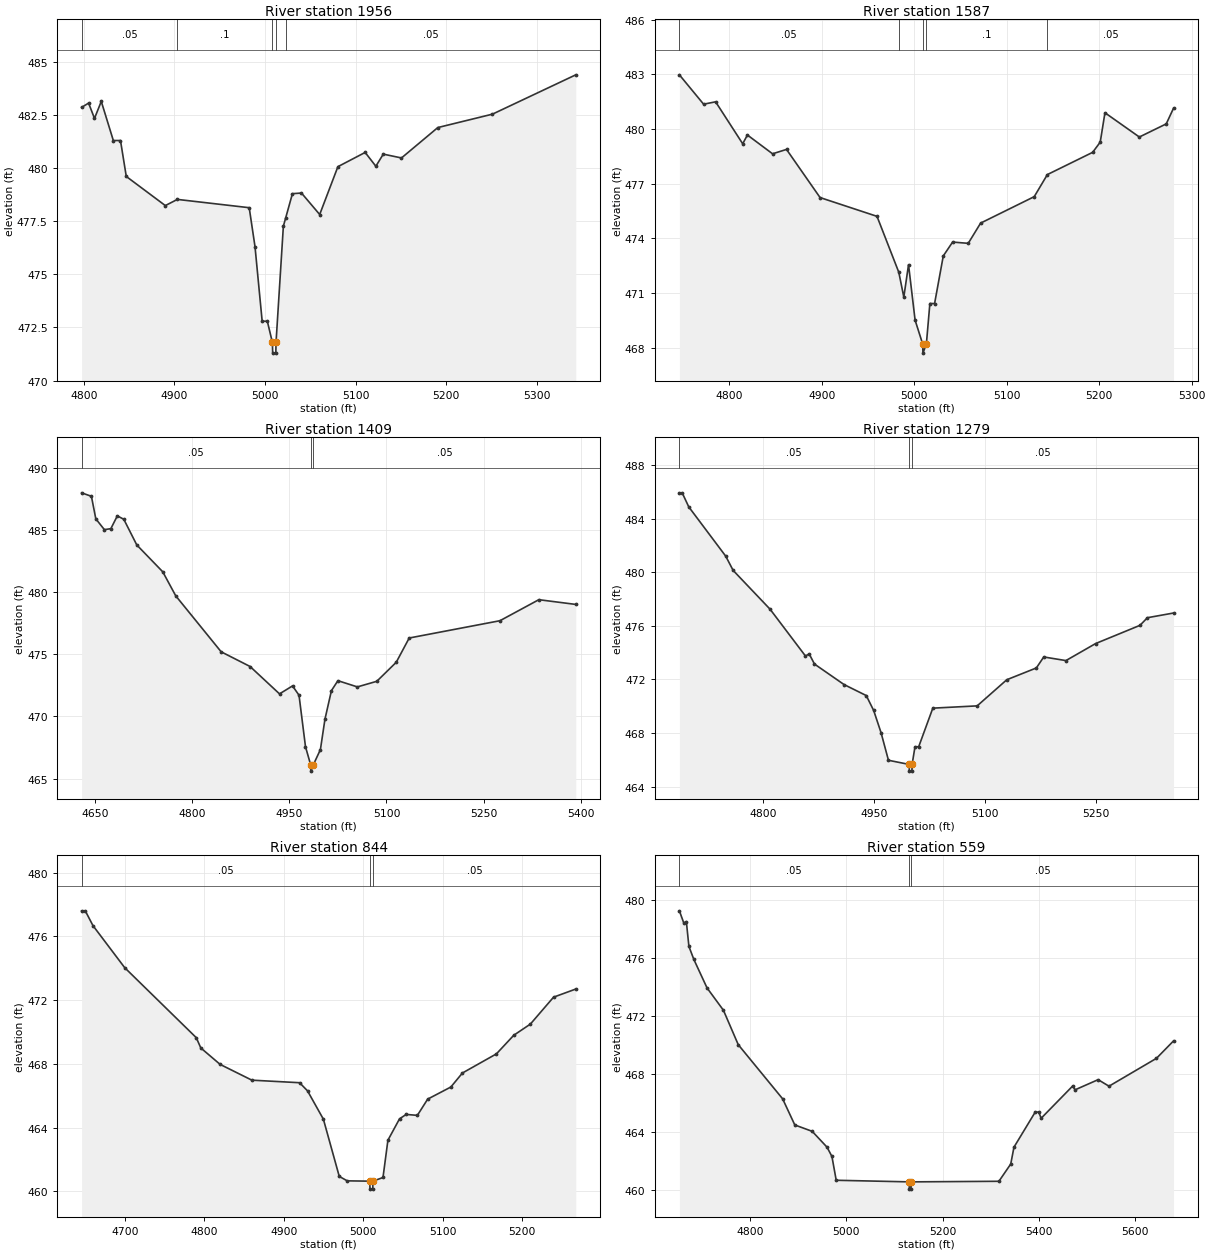
Type RM Length L Ch R = 1,1956,369,369,369
BEGIN DESCRIPTION:
Flat T6 3.0
END DESCRIPTION:
XS GIS Cut Line= 3
      2747419.24      6917017.68      2747575.82      6917145.94
      2747917.72      6917117.31
#Sta/Elev= 30
  4797.6  482.85  4805.3  483.05  4811.8  482.33  4819.3  483.13  4832.6  481.29
  4840.5  481.29  4846.9  479.60  4890.0  478.23  4903.3  478.52  4982.6  478.13
  4989.0  476.30  4996.9  472.79  5002.6  472.79  5008.2  471.79  5008.5  471.29
  5012.0  471.29  5012.2  471.79  5020.3  477.26  5022.8  477.64  5030.3  478.79
  5040.3  478.82  5060.4  477.81  5080.5  480.06  5110.6  480.73  5122.4  480.08
  5130.6  480.65  5150.7  480.47  5190.8  481.90  5251.1  482.53  5343.1  484.38
#Mann=5,-1,0
  4797.6    0.05       0  4903.3     0.1       0  5008.2    0.07       0
  5012.2     0.1       0  5022.8    0.05       0
Bank Sta=5008.2,5012.2
Exp/Cntr=0.3,0.1

Type RM Length L Ch R = 1,1587,178,178,178
BEGIN DESCRIPTION:
Mapping XS 964c0644
END DESCRIPTION:
XS GIS Cut Line= 3
      2747377.60      6917022.89      2747315.09      6917287.23
      2747351.55      6917547.66
#Sta/Elev= 30
  4745.8  482.97  4772.0  481.36  4785.0  481.49  4814.3  479.19  4819.4  479.67
  4846.6  478.64  4861.7  478.88  4898.0  476.24  4959.6  475.21  4983.2  472.14
  4988.6  470.78  4993.7  472.56  5000.8  469.52  5009.0  468.21  5009.3  467.71
  5013.0  468.21  5016.8  470.43  5021.9  470.43  5031.3  473.04  5041.4  473.80
  5058.3  473.73  5071.7  474.84  5129.7  476.29  5143.9  477.50  5192.9  478.72
  5201.1  479.28  5206.2  480.89  5243.4  479.56  5272.5  480.28  5280.4  481.14
#Mann=5,-1,0
  4745.8    0.05       0  4983.2     0.1       0  5009.0    0.07       0
  5013.0     0.1       0  5143.9    0.05       0
Bank Sta=5009,5013
Exp/Cntr=0.3,0.1

Type RM Length L Ch R = 1,1409,130,130,130
BEGIN DESCRIPTION:
Mapping XS 53f45e27
END DESCRIPTION:
XS GIS Cut Line= 3
      2747192.00      6916995.93      2747176.38      6917364.01
      2747171.19      6917757.97
#Sta/Elev= 30
  4629.7  487.97  4644.8  487.69  4651.6  485.88  4664.8  485.01  4674.8  485.09
  4684.8  486.12  4694.8  485.84  4714.8  483.78  4754.9  481.62  4774.9  479.69
  4845.0  475.19  4889.6  474.01  4935.0  471.81  4955.1  472.45  4965.1  471.70
  4975.1  467.56  4983.1  466.10  4983.3  465.60  4987.1  466.10  4998.1  467.33
  5005.1  469.77  5015.1  472.07  5025.1  472.87  5055.1  472.37  5085.1  472.82
  5115.1  474.35  5135.1  476.30  5275.1  477.69  5335.1  479.38  5392.1  479.00
#Mann=3,-1,0
  4629.7    0.05       0  4983.1    0.05       0  4987.1    0.05       0
Bank Sta=4983.1,4987.1
Exp/Cntr=0.3,0.1

Type RM Length L Ch R = 1,1279,435,435,435
BEGIN DESCRIPTION:
Mapping XS 1ffea006
END DESCRIPTION:
XS GIS Cut Line= 3
      2747060.06      6917098.35      2747061.79      6917417.83
      2747072.20      6917766.39
#Sta/Elev= 30
  4687.2  485.92  4691.0  485.92  4699.9  484.87  4749.9  481.19  4759.9  480.13
  4809.9  477.23  4857.7  473.74  4862.7  473.90  4869.9  473.14  4909.9  471.61
  4939.9  470.79  4949.9  469.68  4959.9  468.02  4969.9  465.96  4997.9  465.65
  4998.1  465.15  5001.6  465.15  5001.9  465.65  5005.8  466.97  5010.8  466.97
  5029.9  469.85  5089.9  470.02  5129.9  471.97  5169.9  472.85  5179.9  473.67
  5209.9  473.40  5250.0  474.67  5310.0  476.03  5320.1  476.60  5355.4  476.95
#Mann=3,-1,0
  4687.2    0.05       0  4997.9    0.05       0  5001.9    0.05       0
Bank Sta=4997.9,5001.9
Exp/Cntr=0.3,0.1

Type RM Length L Ch R = 1,844,285,285,285
BEGIN DESCRIPTION:
Mapping XS 3a744fd3
END DESCRIPTION:
XS GIS Cut Line= 3
      2746768.39      6917306.75      2746751.03      6917660.89
      2746966.29      6917820.60
#Sta/Elev= 30
  4645.2  477.61  4649.8  477.61  4659.5  476.68  4699.5  474.04  4789.6  469.65
  4795.4  469.00  4819.7  467.97  4859.7  466.98  4919.8  466.82  4929.8  466.31
  4949.8  464.53  4969.8  460.94  4979.8  460.66  5008.3  460.64  5008.5  460.14
  5012.0  460.14  5012.3  460.64  5024.9  460.87  5031.1  463.21  5045.7  464.55
  5054.1  464.83  5068.2  464.77  5081.2  465.79  5110.4  466.55  5125.0  467.43
  5167.8  468.63  5189.7  469.80  5210.6  470.50  5239.8  472.19  5267.8  472.70
#Mann=3,-1,0
  4645.2    0.05       0  5008.3    0.04       0  5012.3    0.05       0
Bank Sta=5008.3,5012.3
Exp/Cntr=0.3,0.1

Type RM Length L Ch R = 1,559,34,34,34
BEGIN DESCRIPTION:
Mapping XS 44656a5c
END DESCRIPTION:
XS GIS Cut Line= 6
      2746594.15      6917361.68      2746515.01      6917709.62
      2746512.60      6917858.69      2746542.51      6917890.07
      2746609.20      6917912.58      2747011.17      6917965.45
#Sta/Elev= 30
  4652.9  479.23  4662.2  478.38  4667.4  478.49  4672.7  476.78  4683.0  475.88
  4710.4  473.92  4744.5  472.38  4775.3  470.01  4867.6  466.28  4892.9  464.48
  4929.1  464.04  4959.9  462.95  4970.1  462.31  4979.0  460.67  5130.8  460.56
  5131.0  460.06  5134.5  460.06  5134.8  460.56  5317.3  460.60  5341.9  461.79
  5348.6  462.95  5392.3  465.34  5400.0  465.38  5405.1  464.94  5470.6  467.16
  5475.6  466.90  5523.6  467.60  5546.2  467.15  5644.9  469.07  5680.4  470.27
#Mann=3,-1,0
  4652.9    0.05       0  5130.8    0.04       0  5134.8    0.05       0
Bank Sta=5130.8,5134.8
Exp/Cntr=0.3,0.1

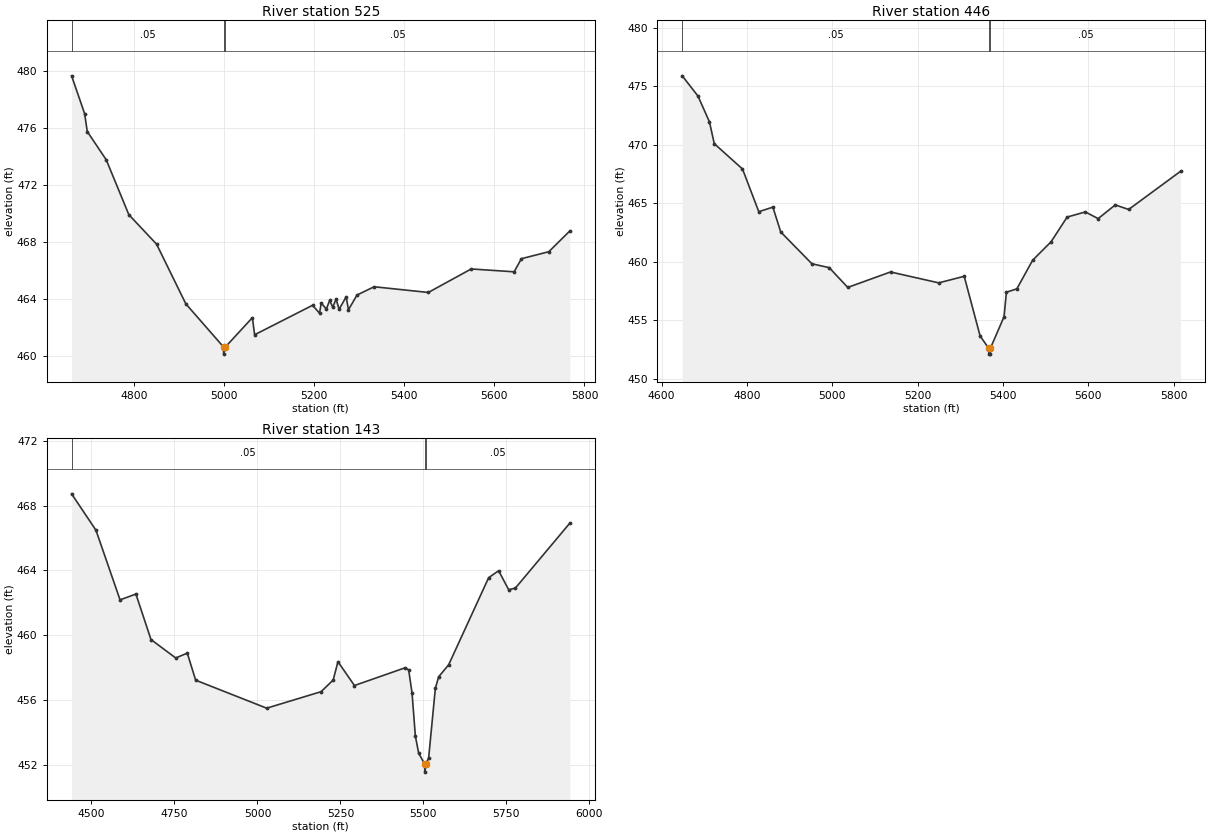
Type RM Length L Ch R = 1,525,79,79,79
BEGIN DESCRIPTION:
Mapping XS 91075476
END DESCRIPTION:
XS GIS Cut Line= 6
      2746567.37      6917347.13      2746481.73      6917719.97
      2746492.90      6917893.06      2746528.71      6917924.58
      2746594.35      6917941.50      2747022.13      6918005.82
#Sta/Elev= 30
  4661.7  479.69  4690.7  477.03  4696.5  475.78  4738.7  473.79  4788.8  469.94
  4850.4  467.87  4915.3  463.68  4999.0  460.65  4999.2  460.15  5003.0  460.65
  5063.0  462.71  5068.0  461.51  5196.6  463.58  5212.1  463.02  5215.8  463.75
  5227.0  463.31  5234.6  463.92  5241.3  463.45  5248.8  464.01  5255.5  463.30
  5271.1  464.17  5276.3  463.27  5295.3  464.30  5333.2  464.88  5453.5  464.48
  5548.7  466.13  5644.0  465.93  5660.1  466.85  5720.9  467.34  5767.6  468.80
#Mann=3,-1,0
  4661.7    0.05       0  4999.0    0.04       0  5003.0    0.05       0
Bank Sta=4999,5003
Exp/Cntr=0.3,0.1

Type RM Length L Ch R = 1,446,303,303,303
BEGIN DESCRIPTION:
Mapping XS ca91e2e7
END DESCRIPTION:
XS GIS Cut Line= 6
      2746531.43      6917369.98      2746416.06      6917753.24
      2746420.59      6917859.27      2746454.21      6917932.55
      2746563.37      6918003.47      2747008.49      6918035.09
#Sta/Elev= 30
  4648.3  475.89  4685.2  474.16  4712.0  471.96  4723.4  470.09  4789.5  467.93
  4827.7  464.28  4860.7  464.67  4879.1  462.55  4952.2  459.83  4992.7  459.50
  5036.2  457.81  5136.4  459.13  5249.4  458.20  5309.1  458.76  5346.4  453.66
  5366.5  452.61  5366.8  452.11  5370.3  452.11  5370.5  452.61  5402.5  455.31
  5408.0  457.40  5432.5  457.69  5469.4  460.13  5512.7  461.71  5550.3  463.82
  5592.9  464.26  5623.0  463.69  5663.1  464.86  5694.5  464.47  5816.0  467.73
#Mann=3,-1,0
  4648.3    0.05       0  5366.5    0.04       0  5370.5    0.05       0
Bank Sta=5366.5,5370.5
Exp/Cntr=0.3,0.1

Type RM Length L Ch R = 1,143,0,0,0
BEGIN DESCRIPTION:
Flat T6 1.0
END DESCRIPTION:
XS GIS Cut Line= 4
      2746321.55      6917219.98      2746176.41      6917760.85
      2746366.48      6918000.12      2746999.79      6918053.00
#Sta/Elev= 30
  4440.0  468.73  4513.5  466.48  4586.0  462.18  4633.8  462.54  4679.2  459.73
  4753.8  458.59  4788.6  458.89  4813.8  457.22  5027.8  455.49  5191.8  456.51
  5228.1  457.23  5242.5  458.36  5292.2  456.89  5445.6  457.99  5455.6  457.85
  5465.7  456.43  5475.7  453.77  5485.7  452.71  5503.8  452.04  5504.0  451.54
  5507.8  452.04  5515.8  452.43  5535.9  456.71  5545.9  457.43  5576.0  458.17
  5696.5  463.55  5726.6  463.98  5756.7  462.81  5776.7  462.90  5941.1  466.92
#Mann=3,-1,0
  4440.0    0.05       0  5503.8    0.04       0  5507.8    0.05       0
Bank Sta=5503.8,5507.8
Exp/Cntr=0.3,0.1

Chan Stop Cuts=-1