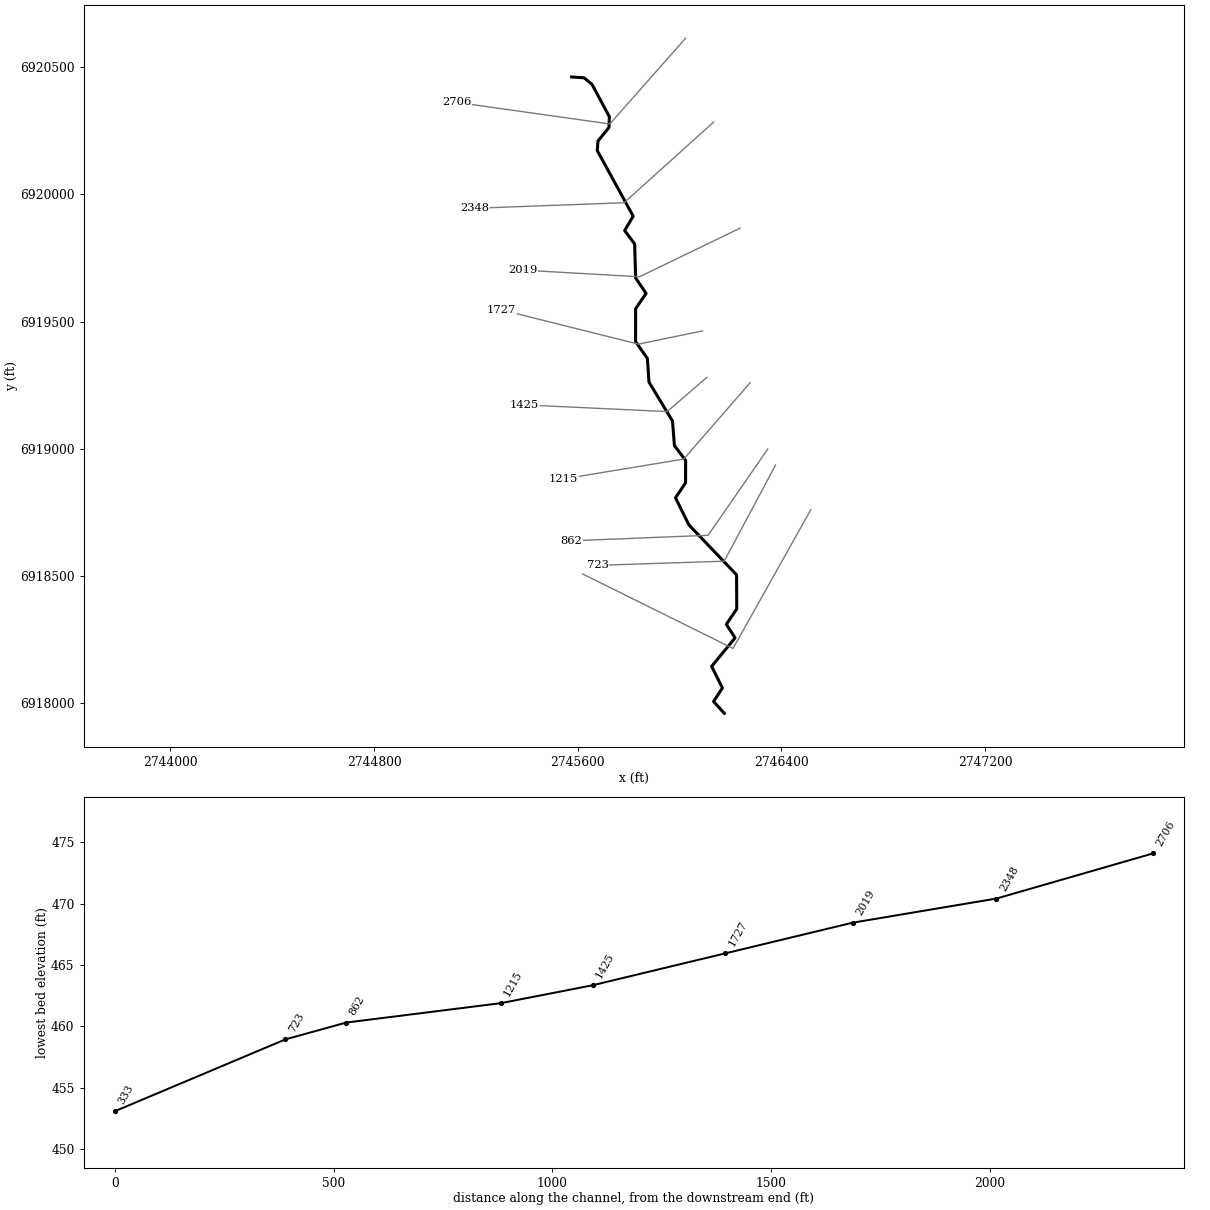
--- Flat T7.prj (project) ---

Proj Title=Flat T7 Base Level Engineering
Current Plan=p01
Default Exp/Contr=0.3,0.1
English Units
Geom File=g01
Flow File=f01
Plan File=p01
BEGIN DESCRIPTION:
Flat T7
END DESCRIPTION:

--- Flat T7.p01 (plan) ---

Plan Title=Multiple Run
Short Identifier=Multiple
Geom File=g01
Flow File=f01
Subcritical Flow
K Sum by GR= 0
Std Step Tol= 0.01
Critical Tol= 0.01
Num of Std Step Trials= 20
Max Error Tol= 0.3
Flow Tol Ratio= 0.001
Split Flow NTrial= 30
Split Flow Tol= 0.02
Split Flow Ratio= 0.02
Log Output Level= 0
Friction Slope Method= 1
Unsteady Friction Slope Method= 2
Unsteady Bridges Friction Slope Method= 1
Parabolic Critical Depth
Global Vel Dist=  1 , 1 , 1
Global Log Level= 0
CheckData=True
Encroach Param= -1, 0, 0, 0
BEGIN DESCRIPTION:
Multiple Run
END DESCRIPTION:

--- Flat T7.f01 (steady flow) ---

Flow Title=Multiple
Number of Profiles=7
Profile Names=10-year,25-year,50-year,1pct_min,100-year,1pct_plu,500-year
River Rch & RM= Flat T7,Reach-1,2706
     168     207     237     136     271     540     352
Boundary for River Rch & Prof#=Flat T7,Reach-1,1
Up Type=0
Dn Type=3
Dn Slope=0.005
Boundary for River Rch & Prof#=Flat T7,Reach-1,2
Up Type=0
Dn Type=3
Dn Slope=0.005
Boundary for River Rch & Prof#=Flat T7,Reach-1,3
Up Type=0
Dn Type=3
Dn Slope=0.005
Boundary for River Rch & Prof#=Flat T7,Reach-1,4
Up Type=0
Dn Type=3
Dn Slope=0.005
Boundary for River Rch & Prof#=Flat T7,Reach-1,5
Up Type=0
Dn Type=3
Dn Slope=0.005
Boundary for River Rch & Prof#=Flat T7,Reach-1,6
Up Type=0
Dn Type=3
Dn Slope=0.005
Boundary for River Rch & Prof#=Flat T7,Reach-1,7
Up Type=0
Dn Type=3
Dn Slope=0.005

--- Flat T7.g01 (geometry) ---

Geom Title=Existing Conditions

River Reach=Flat T7,Reach-1
Reach XY= 30
      2745576.00      6920461.00      2745624.97      6920457.86
      2745656.50      6920431.47      2745724.20      6920304.89
      2745722.60      6920262.72      2745679.40      6920209.28
      2745676.75      6920171.69      2745817.76      6919914.23
      2745784.28      6919857.78      2745823.54      6919805.14
      2745827.39      6919671.44      2745868.44      6919611.00
      2745827.37      6919550.56      2745827.20      6919421.51
      2745873.64      6919355.02      2745879.83      6919262.58
      2745972.17      6919109.42      2745979.86      6919012.60
      2746023.83      6918955.02      2746023.63      6918866.89
      2745984.04      6918807.68      2746036.75      6918701.32
      2746223.95      6918505.14      2746224.64      6918371.44
      2746183.81      6918310.90      2746217.99      6918257.67
      2746126.02      6918145.64      2746168.33      6918060.91
      2746133.51      6918007.66      2746176.00      6917961.00

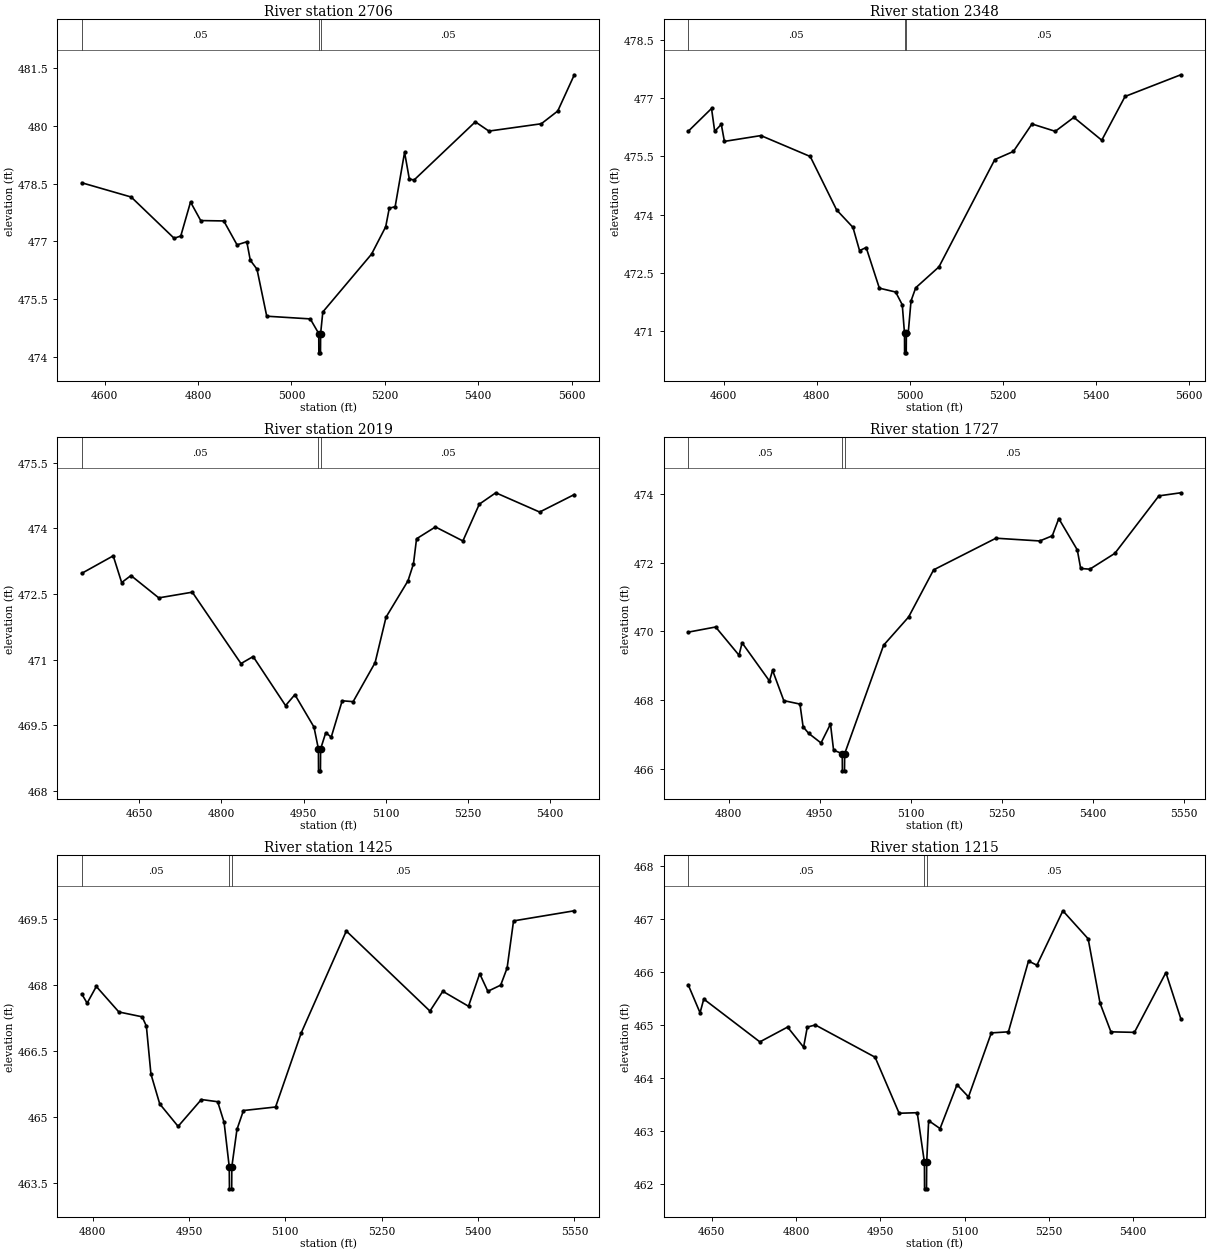
Type RM Length L Ch R = 1,2706,358,358,358
BEGIN DESCRIPTION:
Flat T7 1.0
END DESCRIPTION:
XS GIS Cut Line= 3
      2746023.40      6920612.82      2745725.90      6920276.39
      2745126.04      6920361.00
#Sta/Elev= 30
  4550.9  478.52  4656.8  478.15  4748.8  477.08  4763.0  477.14  4783.9  478.02
  4805.7  477.54  4855.1  477.53  4883.5  476.91  4904.4  476.99  4911.9  476.51
  4926.2  476.28  4947.1  475.06  5040.3  474.99  5058.5  474.61  5058.7  474.11
  5062.2  474.11  5062.5  474.61  5067.2  475.17  5171.6  476.67  5201.9  477.38
  5209.5  477.86  5222.1  477.90  5242.3  479.31  5252.4  478.62  5262.5  478.59
  5393.8  480.10  5422.9  479.86  5535.1  480.05  5570.3  480.38  5605.8  481.32
#Mann=3,-1,0
  4550.9    0.05       0  5058.5    0.05       0  5062.5    0.05       0
Bank Sta=5058.5,5062.5
Exp/Cntr=0.3,0.1

Type RM Length L Ch R = 1,2348,329,329,329
BEGIN DESCRIPTION:
Mapping XS 557e3224
END DESCRIPTION:
XS GIS Cut Line= 3
      2746133.64      6920283.83      2745782.09      6919967.00
      2745196.14      6919945.30
#Sta/Elev= 30
  4523.6  476.15  4573.8  476.74  4580.6  476.15  4594.8  476.33  4601.5  475.89
  4680.0  476.04  4786.1  475.50  4842.9  474.12  4878.0  473.67  4892.2  473.07
  4906.4  473.15  4934.8  472.10  4969.9  472.00  4984.1  471.67  4988.9  470.93
  4989.1  470.43  4992.6  470.43  4992.9  470.93  4996.8  470.93  5002.9  471.77
  5013.0  472.11  5063.0  472.65  5183.1  475.42  5223.1  475.63  5263.1  476.34
  5313.2  476.15  5353.2  476.51  5413.2  475.92  5463.3  477.05  5583.2  477.61
#Mann=3,-1,0
  4523.6    0.05       0  4988.9   0.035       0  4992.9    0.05       0
Bank Sta=4988.9,4992.9
Exp/Cntr=0.3,0.1

Type RM Length L Ch R = 1,2019,292,292,292
BEGIN DESCRIPTION:
Mapping XS 42c3e850
END DESCRIPTION:
XS GIS Cut Line= 3
      2746237.81      6919867.17      2745842.85      6919676.21
      2745382.79      6919702.25
#Sta/Elev= 30
  4545.0  472.97  4602.5  473.37  4617.9  472.76  4634.9  472.92  4685.7  472.41
  4746.9  472.54  4835.8  470.91  4858.0  471.07  4917.2  469.95  4934.2  470.20
  4969.1  469.46  4977.2  468.96  4977.4  468.46  4980.9  468.46  4981.2  468.96
  4990.6  469.33  5000.6  469.23  5020.6  470.06  5040.6  470.04  5080.7  470.93
  5100.7  471.97  5140.8  472.80  5150.8  473.19  5156.4  473.76  5190.9  474.03
  5241.0  473.71  5271.0  474.55  5301.1  474.81  5381.2  474.37  5444.5  474.77
#Mann=3,-1,0
  4545.0    0.05       0  4977.2   0.035       0  4981.2    0.05       0
Bank Sta=4977.2,4981.2
Exp/Cntr=0.3,0.1

Type RM Length L Ch R = 1,1727,302,302,302
BEGIN DESCRIPTION:
Mapping XS 5449910c
END DESCRIPTION:
XS GIS Cut Line= 3
      2746090.25      6919463.53      2745838.51      6919411.45
      2745300.64      6919545.92
#Sta/Elev= 30
  4733.5  469.98  4778.7  470.13  4817.2  469.31  4822.3  469.67  4867.4  468.56
  4872.5  468.87  4891.0  467.99  4917.6  467.89  4922.8  467.23  4931.9  467.04
  4952.3  466.76  4967.9  467.31  4973.0  466.55  4987.3  466.45  4987.5  465.95
  4991.0  465.95  4991.3  466.45  5055.4  469.60  5096.6  470.42  5137.8  471.79
  5240.5  472.71  5312.7  472.63  5333.3  472.78  5344.0  473.28  5374.5  472.37
  5380.1  471.83  5395.2  471.81  5436.4  472.27  5508.9  473.94  5545.0  474.03
#Mann=3,-1,0
  4733.5    0.05       0  4987.3    0.04       0  4991.3    0.05       0
Bank Sta=4987.3,4991.3
Exp/Cntr=0.3,0.1

Type RM Length L Ch R = 1,1425,210,210,210
BEGIN DESCRIPTION:
Mapping XS c95ad848
END DESCRIPTION:
XS GIS Cut Line= 3
      2746107.65      6919281.27      2745951.36      6919146.69
      2745391.51      6919172.73
#Sta/Elev= 30
  4783.1  467.79  4791.5  467.58  4805.8  467.96  4840.9  467.38  4877.1  467.27
  4883.7  467.06  4890.8  465.97  4904.5  465.29  4933.1  464.78  4969.3  465.39
  4994.7  465.34  5004.7  464.87  5012.7  463.86  5013.0  463.36  5016.5  463.36
  5016.7  463.86  5024.7  464.71  5034.8  465.14  5084.8  465.22  5124.9  466.91
  5194.9  469.22  5325.1  467.40  5345.1  467.85  5385.1  467.51  5402.5  468.25
  5415.2  467.85  5435.2  467.99  5445.2  468.38  5455.2  469.45  5549.8  469.68
#Mann=3,-1,0
  4783.1    0.05       0  5012.7   0.035       0  5016.7    0.05       0
Bank Sta=5012.7,5016.7
Exp/Cntr=0.3,0.1

Type RM Length L Ch R = 1,1215,353,353,353
BEGIN DESCRIPTION:
Mapping XS e49669f4
END DESCRIPTION:
XS GIS Cut Line= 3
      2746276.90      6919259.57      2746016.47      6918960.06
      2745543.38      6918881.94
#Sta/Elev= 30
  4608.3  465.76  4629.4  465.23  4636.0  465.49  4735.8  464.68  4785.1  464.96
  4813.6  464.58  4820.2  464.96  4834.5  465.00  4940.8  464.39  4983.6  463.33
  5015.8  463.34  5028.6  462.40  5028.8  461.90  5032.3  461.90  5032.6  462.40
  5036.1  463.19  5056.4  463.04  5086.6  463.87  5107.0  463.64  5147.6  464.85
  5178.0  464.87  5213.8  466.21  5228.7  466.13  5274.9  467.16  5319.9  466.63
  5341.1  465.41  5360.4  464.87  5402.2  464.86  5458.2  465.99  5484.7  465.12
#Mann=3,-1,0
  4608.3    0.05       0  5028.6    0.04       0  5032.6    0.05       0
Bank Sta=5028.6,5032.6
Exp/Cntr=0.3,0.1

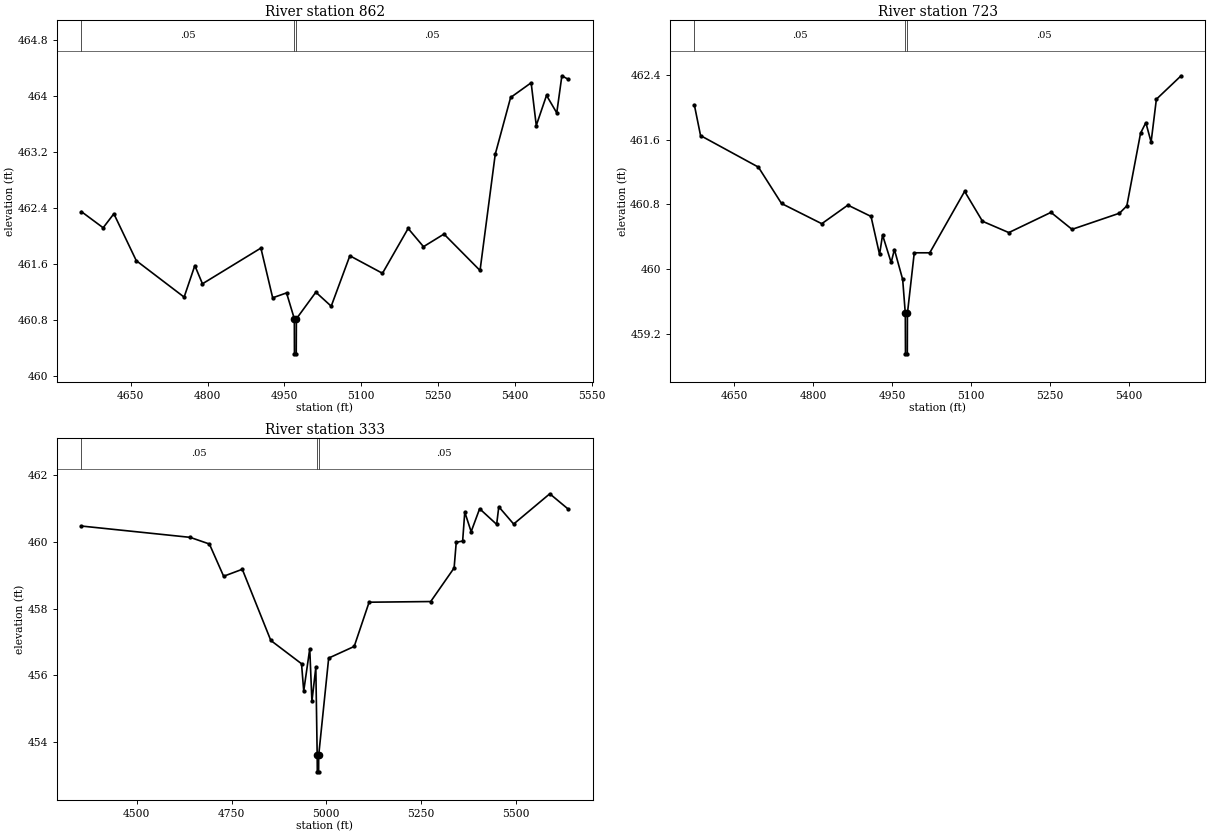
Type RM Length L Ch R = 1,862,139,139,139
BEGIN DESCRIPTION:
Mapping XS 4708c9ed
END DESCRIPTION:
XS GIS Cut Line= 3
      2746346.31      6918999.09      2746111.95      6918660.58
      2745573.71      6918638.88
#Sta/Elev= 30
  4553.8  462.35  4596.2  462.12  4617.1  462.32  4660.9  461.65  4754.3  461.13
  4775.2  461.58  4790.1  461.32  4904.2  461.83  4927.2  461.12  4954.3  461.19
  4969.5  460.82  4969.7  460.32  4973.2  460.32  4973.5  460.82  5011.5  461.20
  5041.5  461.00  5077.9  461.72  5141.6  461.47  5191.7  462.11  5221.7  461.85
  5261.7  462.03  5332.1  461.51  5361.8  463.17  5391.8  463.98  5431.9  464.19
  5441.9  463.58  5461.9  464.01  5481.9  463.76  5491.9  464.29  5504.2  464.24
#Mann=3,-1,0
  4553.8    0.05       0  4969.5    0.04       0  4973.5    0.05       0
Bank Sta=4969.5,4973.5
Exp/Cntr=0.3,0.1

Type RM Length L Ch R = 1,723,390,390,390
BEGIN DESCRIPTION:
Mapping XS 1d824939
END DESCRIPTION:
XS GIS Cut Line= 3
      2746376.83      6918936.00      2746175.24      6918558.83
      2745679.16      6918542.59
#Sta/Elev= 30
  4574.8  462.03  4586.6  461.65  4696.4  461.26  4740.3  460.81  4816.7  460.56
  4866.3  460.79  4910.2  460.65  4926.4  460.18  4932.1  460.42  4948.4  460.08
  4954.6  460.24  4970.3  459.87  4975.3  459.45  4975.6  458.95  4979.1  458.95
  4979.3  459.45  4992.3  460.20  5021.7  460.20  5087.9  460.96  5121.8  460.59
  5171.8  460.45  5251.8  460.70  5291.8  460.49  5381.9  460.69  5395.8  460.78
  5421.9  461.68  5431.9  461.81  5441.9  461.57  5451.9  462.10  5498.8  462.39
#Mann=3,-1,0
  4574.8    0.05       0  4975.3    0.04       0  4979.3    0.05       0
Bank Sta=4975.3,4979.3
Exp/Cntr=0.3,0.1

Type RM Length L Ch R = 1,333,0,0,0
BEGIN DESCRIPTION:
Flat T7 0.0
END DESCRIPTION:
XS GIS Cut Line= 3
      2746515.59      6918761.01      2746210.04      6918216.14
      2745619.54      6918508.48
#Sta/Elev= 30
  4354.2  460.48  4640.8  460.14  4691.6  459.94  4729.2  458.97  4778.4  459.18
  4853.6  457.04  4934.6  456.34  4940.4  455.52  4956.3  456.79  4962.0  455.21
  4972.3  456.23  4975.9  453.59  4976.2  453.09  4979.7  453.09  4979.9  453.59
  5006.2  456.51  5073.5  456.86  5112.8  458.19  5275.3  458.21  5337.0  459.22
  5342.6  459.99  5359.5  460.03  5365.1  460.90  5381.9  460.31  5404.3  461.00
  5449.2  460.53  5454.8  461.06  5494.0  460.54  5589.3  461.45  5637.8  460.99
#Mann=3,-1,0
  4354.2    0.05       0  4975.9    0.04       0  4979.9    0.05       0
Bank Sta=4975.9,4979.9
Exp/Cntr=0.3,0.1

Chan Stop Cuts=-1