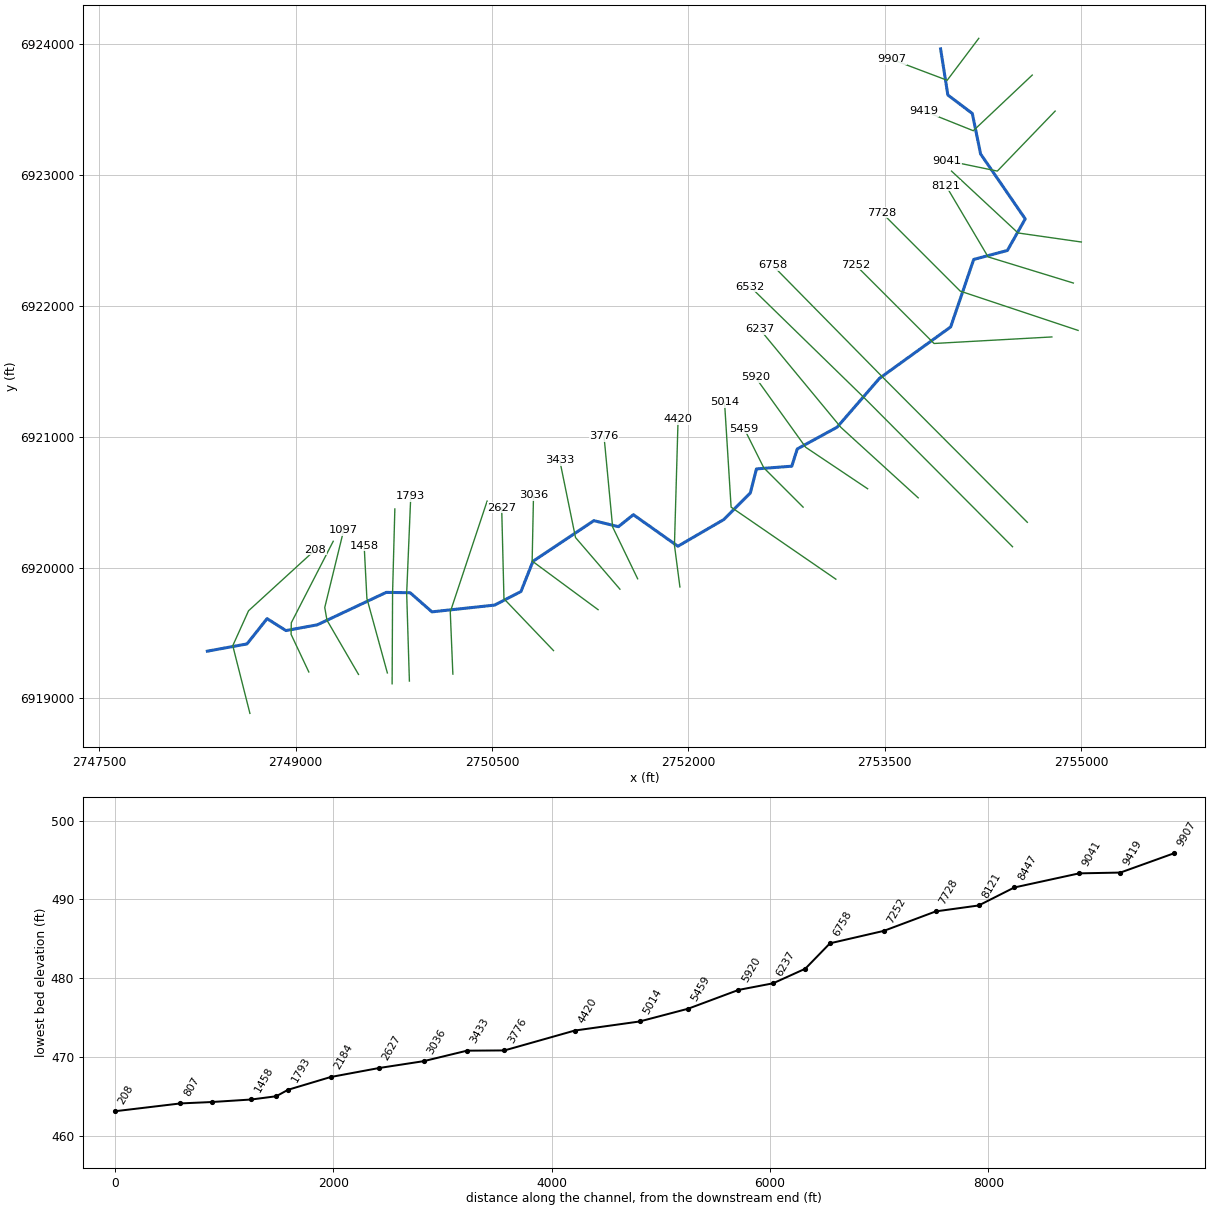
--- Flat T8.prj (project) ---

Proj Title=Flat T8 Base Level Engineering
Current Plan=p01
Default Exp/Contr=0.3,0.1
English Units
Geom File=g01
Flow File=f01
Plan File=p01
Y Axis Title=Elevation
X Axis Title(PF)=Main Channel Distance
X Axis Title(XS)=Station
BEGIN DESCRIPTION:
Flat T8
END DESCRIPTION:
DSS Export Rating Curves= 0
DSS Export Rating Curve Sorted= 0
DSS Export Volume Flow Curves= 0
DXF OffsetX= 0
DXF OffsetY= 0
DXF ScaleX= 1
DXF ScaleY= 10

--- Flat T8.p01 (plan) ---

Plan Title=Multiple Run
Short Identifier=Multiple
Geom File=g01
Flow File=f01
Subcritical Flow
K Sum by GR= 0
Std Step Tol= 0.01
Critical Tol= 0.01
Num of Std Step Trials= 20
Max Error Tol= 0.3
Flow Tol Ratio= 0.001
Split Flow NTrial= 30
Split Flow Tol= 0.02
Split Flow Ratio= 0.02
Log Output Level= 0
Friction Slope Method= 1
Unsteady Friction Slope Method= 2
Unsteady Bridges Friction Slope Method= 1
Parabolic Critical Depth
Global Vel Dist=  1 , 1 , 1
Global Log Level= 0
CheckData=True
Encroach Param= -1, 0, 0, 0
BEGIN DESCRIPTION:
Multiple Run
END DESCRIPTION:

--- Flat T8.f01 (steady flow) ---

Flow Title=Multiple
Program Version=4.10
Number of Profiles= 7
Profile Names=10-year,25-year,50-year,1pct_min,100-year,1pct_plu,500-year
River Rch & RM=Flat T8,Reach-1         ,9907
     264     337     393     229     457     911     616
River Rch & RM=Flat T8,Reach-1         ,8447
     474     627     750     447     891    1778    1259
River Rch & RM=Flat T8,Reach-1         ,6758
     741    1002    1216     733    1462    2917    2118
River Rch & RM=Flat T8,Reach-1         ,4420
     844    1148    1398     844    1685    3361    2453
River Rch & RM=Flat T8,Reach-1         ,2184
     954    1305    1594     965    1926    3843    2821
Boundary for River Rch & Prof#=Flat T8,Reach-1         , 1
Up Type= 0
Dn Type= 3
Dn Slope=0.005
Boundary for River Rch & Prof#=Flat T8,Reach-1         , 2
Up Type= 0
Dn Type= 3
Dn Slope=0.005
Boundary for River Rch & Prof#=Flat T8,Reach-1         , 3
Up Type= 0
Dn Type= 3
Dn Slope=0.005
Boundary for River Rch & Prof#=Flat T8,Reach-1         , 4
Up Type= 0
Dn Type= 3
Dn Slope=0.005
Boundary for River Rch & Prof#=Flat T8,Reach-1         , 5
Up Type= 0
Dn Type= 3
Dn Slope=0.005
Boundary for River Rch & Prof#=Flat T8,Reach-1         , 6
Up Type= 0
Dn Type= 3
Dn Slope=0.005
Boundary for River Rch & Prof#=Flat T8,Reach-1         , 7
Up Type= 0
Dn Type= 3
Dn Slope=0.005
DSS Import GetInterval= 0
DSS Import GetPeak= 0
DSS Import FillOption= 0

--- Flat T8.g01 (geometry) ---

Geom Title=Existing Conditions
Program Version=4.10

River Reach=Flat T8         ,Reach-1
Reach XY= 30
        2753926.        6923961.      2753981.46      6923608.54
       2754168.3      6923467.47      2754231.52      6923158.57
       2754572.4      6922662.49      2754436.11      6922421.38
      2754179.03      6922352.99      2754002.99      6921837.53
      2753459.07      6921444.59      2753135.68      6921071.76
      2752831.26      6920905.53      2752789.63      6920773.96
      2752519.61        6920753.      2752472.92      6920569.31
      2752270.49      6920366.44      2751919.57      6920162.44
      2751579.57      6920403.47      2751465.52      6920311.95
      2751277.64      6920357.86      2750812.76      6920047.39
      2750720.82      6919816.41      2750519.74      6919712.95
      2750041.16      6919661.38      2749874.53      6919807.46
      2749691.96      6919810.04       2749165.5      6919562.22
       2748925.9      6919518.33      2748782.04      6919609.42
      2748628.67      6919416.42        2748326.        6919361.

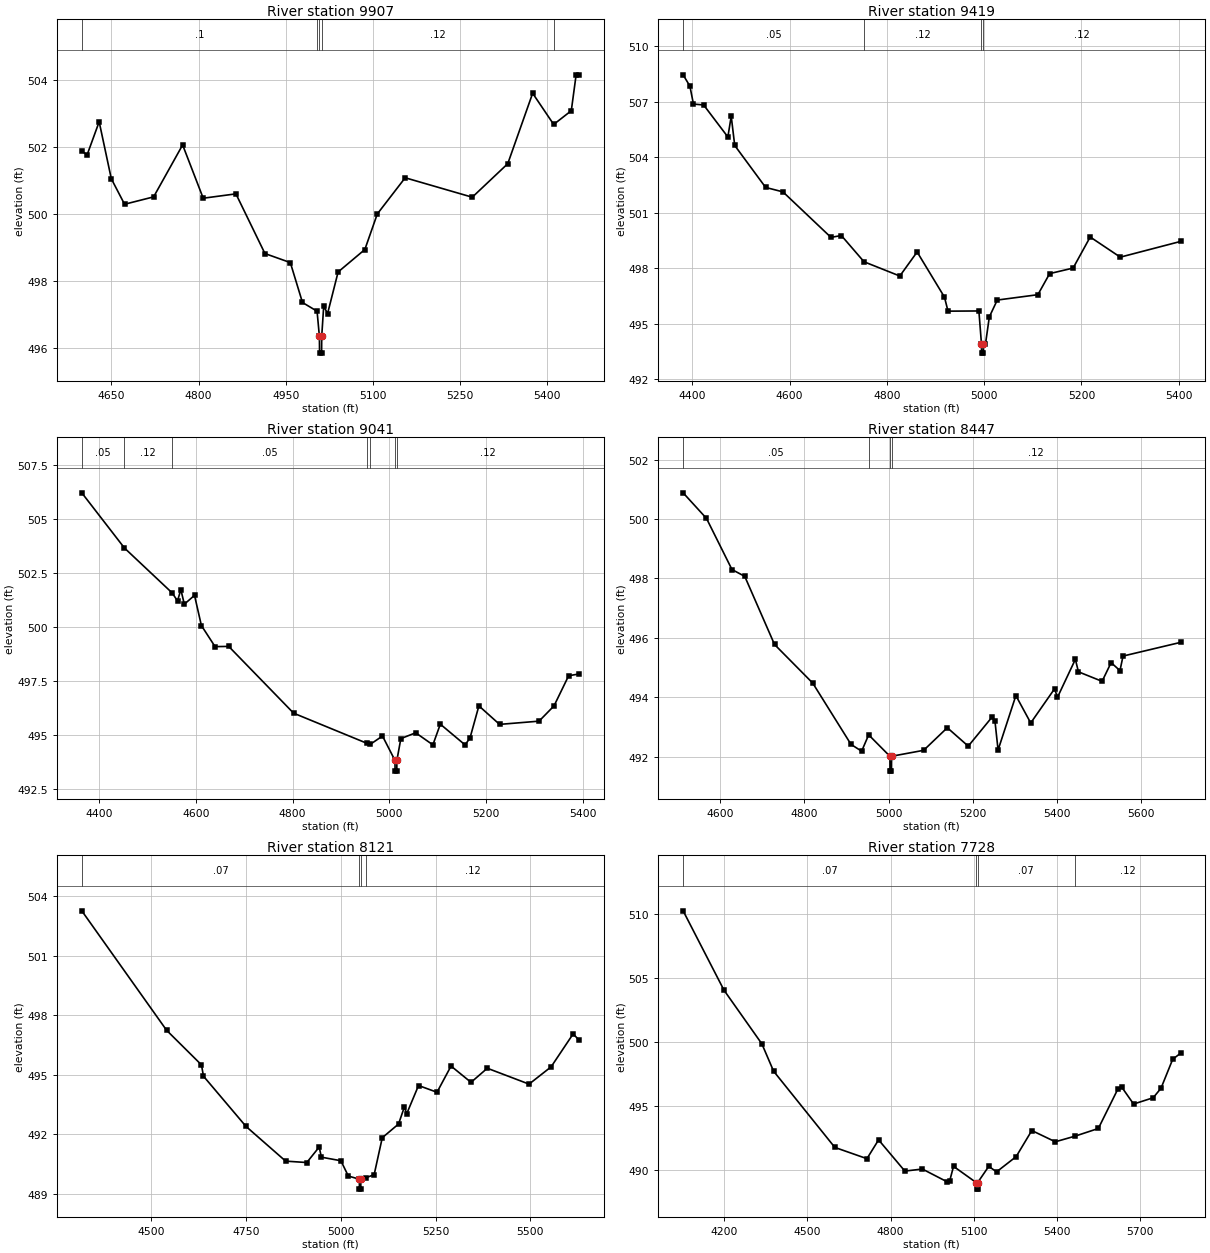
Type RM Length L Ch R = 1 ,9907    ,488,488,488
BEGIN DESCRIPTION:
Flat T8 17.0
END DESCRIPTION:
XS GIS Cut Line= 3
      2754217.71      6924041.56      2753976.39      6923721.17
      2753551.03      6923881.84
#Sta/Elev= 30
  4598.9  501.87    4608  501.75  4628.8  502.74  4649.7  501.04  4672.5  500.28
  4722.5   500.5  4772.4  502.05  4807.8  500.46  4864.1  500.59    4914  498.81
  4957.7  498.54  4978.6  497.35  5003.7  497.09  5007.7  496.34    5008  495.84
  5011.5  495.84  5011.7  496.34  5015.1  497.24  5021.8  497.02  5039.9  498.26
  5085.9  498.93  5107.3  499.99  5155.3  501.07  5270.7  500.49  5331.8  501.49
  5374.6  503.59  5410.8  502.66  5441.1  503.07  5449.4  504.14  5454.7  504.14
#Mann= 5 ,-1 , 0
  4598.9      .1       0  5003.7     .12       0  5007.7     .07       0
  5011.7     .12       0  5410.8     .05       0
Bank Sta=5007.7,5011.7
XS Rating Curve= 0 ,0
Exp/Cntr=0.3,0.1

Type RM Length L Ch R = 1 ,9419    ,378,378,378
BEGIN DESCRIPTION:
Flat T8 16.0
END DESCRIPTION:
XS GIS Cut Line= 3
      2754625.96      6923760.97      2754175.82      6923335.93
      2753800.95      6923486.02
#Sta/Elev= 30
  4380.9  508.46  4394.8  507.85  4402.1  506.88  4423.1  506.83  4472.9   505.1
  4479.8  506.22    4487  504.64  4550.6  502.37  4586.2  502.13  4684.9  499.67
  4706.3  499.77  4752.9  498.35  4826.5  497.58  4862.1  498.88  4918.3  496.44
  4925.6  495.68  4989.1  495.69  4994.4  493.91  4994.6  493.41  4998.1  493.41
  4998.4  493.91  5002.7  493.91  5010.6  495.37  5026.9  496.28  5110.4  496.57
  5134.6  497.71  5182.9  498.01    5218  499.69  5279.9   498.6  5403.8  499.45
#Mann= 4 ,-1 , 0
  4380.9     .05       0  4752.9     .12       0  4994.4     .07       0
  4998.4     .12       0
Bank Sta=4994.4,4998.4
XS Rating Curve= 0 ,0
Exp/Cntr=0.3,0.1

Type RM Length L Ch R = 1 ,9041    ,594,594,594
BEGIN DESCRIPTION:
Flat T8 15.0
END DESCRIPTION:
XS GIS Cut Line= 3
      2754800.99      6923485.99      2754359.43      6923027.71
      2753974.62      6923107.53
#Sta/Elev= 30
  4363.6  506.23  4451.8  503.67  4550.8  501.58  4561.7  501.21  4568.6  501.74
  4575.8  501.06  4596.9  501.47  4611.1  500.07  4639.4  499.09  4667.7   499.1
    4802     496  4953.9   494.6    4961  494.56  4985.9  494.94  5011.7  493.81
    5012  493.31  5015.5  493.31  5015.7  493.81  5023.9  494.82  5054.6  495.09
  5090.2  494.53  5105.6  495.49  5156.7  494.53  5166.9  494.84  5185.4  496.34
  5228.2  495.48  5309.9  495.63  5340.9  496.34  5371.2  497.74    5393  497.82
#Mann= 7 ,-1 , 0
  4363.6     .05       0  4451.8     .12       0  4550.8     .05       0
  4953.9      .1       0    4961     .12       0  5011.7     .07       0
  5015.7     .12       0
Bank Sta=5011.7,5015.7
XS Rating Curve= 0 ,0
Exp/Cntr=0.3,0.1

Type RM Length L Ch R = 1 ,8447    ,326,326,326
BEGIN DESCRIPTION:
Flat T8 14.0
END DESCRIPTION:
XS GIS Cut Line= 3
      2755000.98        6922486.      2754517.59      6922555.06
      2754009.38      6923027.66
#Sta/Elev= 30
  4511.7  500.88  4567.2  500.02  4627.8   498.3  4658.2  498.07  4728.9  495.78
  4819.8  494.48  4910.7  492.42    4936  492.19  4952.7  492.74  5003.2  492.02
  5003.4  491.52  5006.9  491.52  5007.2  492.02  5083.4  492.22  5139.6  492.98
  5189.4  492.36  5246.1  493.34  5252.9   493.2  5260.3  492.23  5302.6  494.06
  5337.9  493.14  5394.6  494.29  5401.4     494    5444  495.28  5451.3  494.86
  5507.5  494.54    5529  495.17    5550   494.9  5557.3  495.39    5694  495.85
#Mann= 4 ,-1 , 0
  4511.7     .05       0  4952.7     .12       0  5003.2     .07       0
  5007.2     .12       0
Bank Sta=5003.2,5007.2
XS Rating Curve= 0 ,0
Exp/Cntr=0.3,0.1

Type RM Length L Ch R = 1 ,8121    ,393,393,393
BEGIN DESCRIPTION:
Mapping XS 3acd033a
END DESCRIPTION:
XS GIS Cut Line= 3
      2754939.92      6922172.64      2754288.89      6922372.29
      2753967.72       6922914.8
#Sta/Elev= 30
  4317.2  503.26  4540.9  497.24  4632.7   495.5    4638  494.93  4750.1   492.4
  4854.7  490.65  4910.4  490.58  4943.1  491.36  4948.9  490.85  5000.3  490.67
  5019.9   489.9  5048.9  489.74  5049.2  489.24  5052.7  489.24  5052.9  489.74
  5065.9  489.81    5088  489.97  5109.4  491.83  5152.3  492.52  5167.9  493.39
  5173.7  493.03    5205  494.46  5253.7  494.12  5290.7  495.44  5343.4  494.62
  5386.3  495.33  5496.4  494.53  5554.5   495.4  5612.6  497.06  5628.6  496.74
#Mann= 4 ,-1 , 0
  4317.2     .07       0  5048.9     .05       0  5052.9     .07       0
  5065.9     .12       0
Bank Sta=5048.9,5052.9
XS Rating Curve= 0 ,0
Exp/Cntr=0.3,0.1

Type RM Length L Ch R = 1 ,7728    ,476,476,476
BEGIN DESCRIPTION:
Flat T8 13.0
END DESCRIPTION:
XS GIS Cut Line= 3
      2754976.01        6921811.        2754076.        6922111.
      2753476.01      6922710.99
#Sta/Elev= 30
  4050.7  510.24  4198.3  504.04  4335.3  499.84  4377.5  497.71  4598.8  491.75
  4714.8  490.87  4756.9  492.34  4851.8   489.9  4915.1  490.06  5002.9  489.08
  5013.5  489.11  5027.7  490.27  5110.5  488.99  5110.8  488.49  5114.3  488.49
  5114.5  488.99    5155  490.27  5183.2  489.84  5253.9  491.03  5310.5  493.07
  5395.4  492.19  5466.7  492.63  5550.9  493.23  5621.6  496.32  5635.8  496.45
  5678.2  495.14  5748.9  495.63  5777.2  496.37  5819.6  498.64  5847.9  499.11
#Mann= 4 ,-1 , 0
  4050.7     .07       0  5110.5     .05       0  5114.5     .07       0
  5466.7     .12       0
Bank Sta=5110.5,5114.5
XS Rating Curve= 0 ,0
Exp/Cntr=0.3,0.1

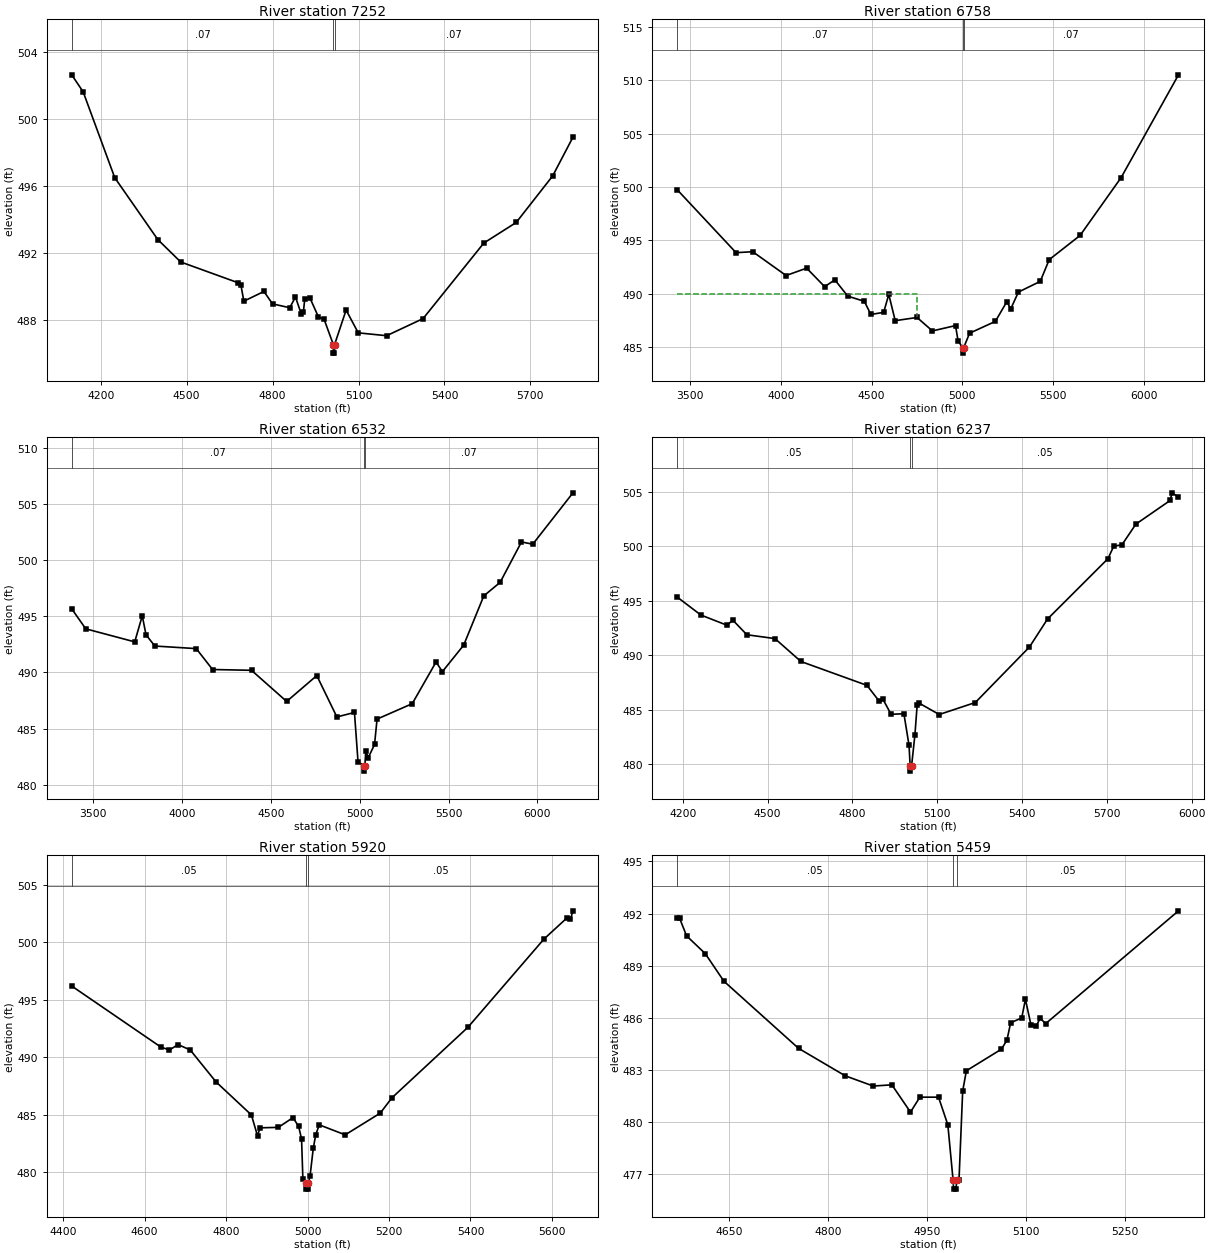
Type RM Length L Ch R = 1 ,7252    ,494,494,494
BEGIN DESCRIPTION:
Flat T8 12.0
END DESCRIPTION:
XS GIS Cut Line= 3
      2754775.95        6921761.        2753876.        6921711.
      2753275.98      6922311.02
#Sta/Elev= 30
  4098.7  502.63  4138.7  501.61  4248.9  496.49  4399.1   492.8  4479.2  491.46
  4679.5  490.22  4689.6  490.06  4699.6  489.12  4769.7   489.7  4799.7  488.96
  4859.8  488.73  4879.9  489.37  4899.9  488.36  4907.4  488.45  4912.4  489.28
  4929.9  489.33    4960  488.18    4980  488.03  5012.2  486.52  5012.4  486.02
  5015.9  486.02  5016.2  486.52  5056.6  488.59    5099  487.23    5198  487.06
  5325.3  488.08  5537.4  492.59  5650.6  493.82  5777.9   496.6  5848.6  498.91
#Mann= 3 ,-1 , 0
  4098.7     .07       0  5012.2     .05       0  5016.2     .07       0
Bank Sta=5012.2,5016.2
XS Rating Curve= 0 ,0
Exp/Cntr=0.3,0.1

Type RM Length L Ch R = 1 ,6758    ,226,226,226
BEGIN DESCRIPTION:
Flat T8 11.0
END DESCRIPTION:
XS GIS Cut Line= 3
      2754588.38      6920345.36        2753501.        6921436.
      2752644.48      6922306.61
#Sta/Elev= 30
  3429.4  499.74  3753.3  493.85  3845.2  493.94    4029  491.71  4142.2   492.4
  4241.2  490.67  4297.8   491.3  4368.5  489.78  4460.4  489.29  4495.7  488.06
  4566.5  488.26  4594.7  489.94  4630.1  487.48  4750.3  487.78  4835.2  486.52
  4962.4  487.02  4976.5  485.58  5002.8  484.94    5003  484.44  5006.8  484.94
  5040.2  486.31  5181.6  487.41  5245.2  489.26  5266.5  488.58  5308.9  490.16
  5429.1  491.16  5478.7   493.2  5648.4  495.46  5874.6  500.88  6190.8  510.51
#Mann= 3 ,-1 , 0
  3429.4     .07       0  5002.8     .05       0  5006.8     .07       0
#XS Ineff= 2 , 0
       0  4750.3     490               0
Permanent Ineff=
       F       F
Bank Sta=5002.8,5006.8
XS Rating Curve= 0 ,0
Exp/Cntr=0.3,0.1

Type RM Length L Ch R = 1 ,6532    ,295,295,295
BEGIN DESCRIPTION:
Mapping XS 03922ed1
END DESCRIPTION:
XS GIS Cut Line= 3
      2754475.49      6920158.77      2753334.03      6921304.58
      2752470.94      6922145.98
#Sta/Elev= 30
  3377.9  495.66  3456.9  493.88  3732.7  492.72  3775.1  495.04  3796.3  493.35
  3845.8  492.35  4079.1  492.12  4171.1  490.26  4390.3  490.19  4588.3  487.42
    4758  489.72  4871.1  486.04  4970.1  486.44  4990.3  482.03  5024.4  481.72
  5024.9  481.22  5028.9  481.72  5033.8  483.01    5048  482.42  5083.2  483.59
  5097.4  485.85  5295.4  487.22  5429.7  490.93  5465.2  490.07  5585.3  492.43
  5698.5  496.81  5790.3  498.01  5910.7  501.61  5974.2  501.41  6200.6  505.98
#Mann= 3 ,-1 , 0
  3377.9     .07       0  5024.4     .05       0  5028.9     .07       0
Bank Sta=5024.4,5028.9
XS Rating Curve= 0 ,0
Exp/Cntr=0.3,0.1

Type RM Length L Ch R = 1 ,6237    ,317,317,317
BEGIN DESCRIPTION:
Mapping XS 36cf3ba7
END DESCRIPTION:
XS GIS Cut Line= 3
        2753755.      6920532.04      2753164.76       6921070.2
      2752544.12      6921821.04
#Sta/Elev= 30
  4180.6  495.32    4264  493.68  4355.8  492.75  4377.5   493.2  4426.8  491.87
  4526.1  491.52    4618  489.42  4851.7  487.23  4894.3   485.8  4908.5  485.94
  4936.9  484.58  4982.3  484.63  5000.4  481.73  5004.3  479.87    5005  479.37
  5009.5  479.87  5021.2  482.69  5029.1  485.41  5035.6  485.61  5107.2  484.56
  5234.9  485.66  5426.4  490.75  5490.2  493.31  5703.9  498.84  5724.7     500
  5753.3  500.11  5802.8  502.01    5924  504.18  5930.5  504.88  5953.5   504.5
#Mann= 3 ,-1 , 0
  4180.6     .05       0  5004.3     .04       0  5009.5     .05       0
Bank Sta=5004.3,5009.5
XS Rating Curve= 0 ,0
Exp/Cntr=0.3,0.1

Type RM Length L Ch R = 1 ,5920    ,461,461,461
BEGIN DESCRIPTION:
Mapping XS 8cfcc431
END DESCRIPTION:
XS GIS Cut Line= 3
      2753368.74      6920601.46      2752895.66      6920918.29
      2752510.34      6921455.15
#Sta/Elev= 30
  4421.3  496.19  4640.2  490.88  4661.2  490.63  4682.2   491.1  4712.2  490.63
  4775.3  487.86  4862.3  484.98  4877.3  483.16  4883.3  483.86  4928.4   483.9
  4964.4  484.75  4978.2  483.98  4985.4  482.89  4988.6  479.45  4996.8  479.03
  4997.5  478.53  5001.3  478.53    5002  479.03  5006.3  479.69  5014.1  482.07
  5020.3  483.28  5028.9  484.12  5092.5  483.25  5178.6  485.14  5206.9  486.46
  5393.6   492.6  5580.2  500.27  5636.7  502.11  5645.3  501.99  5651.5  502.73
#Mann= 3 ,-1 , 0
  4421.3     .05       0  4996.8     .04       0    5002     .05       0
Bank Sta=4996.8,5002
XS Rating Curve= 0 ,0
Exp/Cntr=0.3,0.1

Type RM Length L Ch R = 1 ,5459    ,445,445,445
BEGIN DESCRIPTION:
Flat T8 8.0
END DESCRIPTION:
XS GIS Cut Line= 3
      2752875.99      6920461.01        2752576.        6920761.
      2752425.98      6921061.04
#Sta/Elev= 30
  4571.1  491.74  4574.6  491.74  4585.2  490.72  4613.5   489.7  4641.8  488.11
  4754.9  484.25  4825.6  482.67  4868.1  482.08  4896.4  482.15  4924.6  480.58
  4938.8  481.44  4967.1  481.44  4981.2  479.85  4989.2  476.65  4989.9  476.15
  4993.7  476.15  4994.5  476.65  4998.1  476.65  5003.7  481.79  5009.3  482.96
  5062.4   484.2  5070.8  484.72  5076.4  485.72  5093.2     486  5098.8  487.07
  5107.2   485.6  5115.5  485.56  5121.1  485.98  5129.5  485.67  5330.8  492.16
#Mann= 3 ,-1 , 0
  4571.1     .05       0  4989.2     .04       0  4994.5     .05       0
Bank Sta=4989.2,4994.5
XS Rating Curve= 0 ,0
Exp/Cntr=0.3,0.1

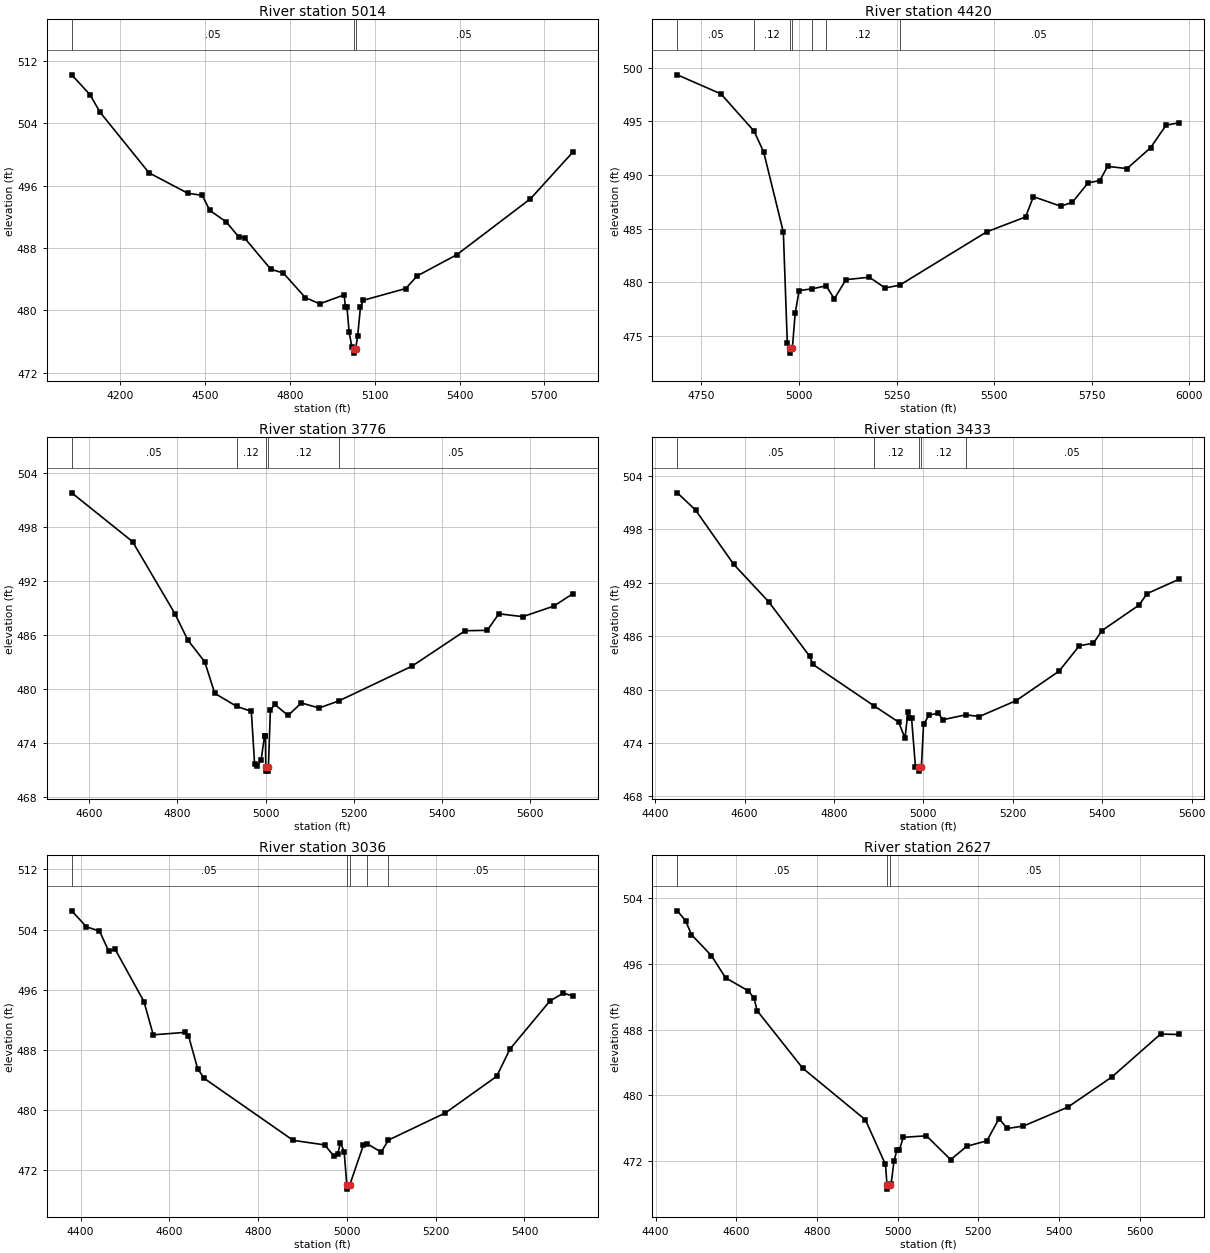
Type RM Length L Ch R = 1 ,5014    ,594,594,594
BEGIN DESCRIPTION:
Flat T8 7.0
END DESCRIPTION:
XS GIS Cut Line= 3
        2753126.        6919911.        2752326.        6920461.
        2752276.      6921261.01
#Sta/Elev= 30
  4028.9  510.19  4093.2  507.66    4129   505.4  4302.2  497.63  4439.6  495.01
    4490  494.75  4517.4  492.81    4575  491.35  4618.8  489.45  4639.8  489.29
  4732.8  485.28  4777.2  484.79  4854.9  481.64  4905.7  480.85  4992.3  481.99
  4996.7  480.39  5002.2  480.39  5009.7  477.22  5019.8  475.26  5027.1  475.03
  5027.9  474.53  5032.4  475.03  5039.8  476.69  5049.8  480.42  5059.8   481.3
  5210.1  482.81  5250.2  484.42  5390.5  487.14    5651  494.31  5801.3  500.31
#Mann= 3 ,-1 , 0
  4028.9     .05       0  5027.1     .04       0  5032.4     .05       0
Bank Sta=5027.1,5032.4
XS Rating Curve= 0 ,0
Exp/Cntr=0.3,0.1

Type RM Length L Ch R = 1 ,4420    ,644,644,644
BEGIN DESCRIPTION:
Mapping XS d85002da
END DESCRIPTION:
XS GIS Cut Line= 3
      2751935.01      6919851.56      2751893.34      6920171.01
      2751921.12      6921132.85
#Sta/Elev= 30
  4688.1  499.33    4800  497.55  4884.8  494.08  4909.4  492.13  4959.8  484.66
  4969.9  474.36    4977  473.88    4978  473.38    4983  473.88  4990.1  477.09
  5000.2  479.21  5033.9  479.38  5069.6  479.65  5090.3  478.44  5120.3  480.23
  5180.3  480.46  5220.3  479.46  5257.7  479.71  5480.4  484.68  5580.5  486.08
  5600.5  487.97  5670.5  487.08  5700.5  487.45  5740.6  489.26  5770.6  489.47
  5790.6  490.79  5840.6  490.59  5900.6  492.53  5940.6  494.64  5972.5  494.85
#Mann= 7 ,-1 , 0
  4688.1     .05       0  4884.8     .12       0    4977     .07       0
    4983     .12       0  5033.9      .1       0  5069.6     .12       0
  5257.7     .05       0
Bank Sta=4977,4983
XS Rating Curve= 0 ,0
Exp/Cntr=0.3,0.1

Type RM Length L Ch R = 1 ,3776    ,343,343,343
BEGIN DESCRIPTION:
Mapping XS 13de0e70
END DESCRIPTION:
XS GIS Cut Line= 3
      2751612.09      6919914.08      2751421.12       6920309.9
      2751355.15      6921004.39
#Sta/Elev= 30
  4560.2  501.76  4698.2  496.34  4794.2  488.35  4823.3  485.43    4862  482.99
  4884.6   479.5  4934.3  478.05  4967.6   477.5    4975  471.69  4980.6  471.39
  4989.8  472.09  4997.5  474.76  4999.7  474.76  5000.3  471.36  5001.3  470.86
  5005.4  470.86  5006.4  471.36  5010.8  477.63  5020.9  478.26    5051  477.04
  5081.1  478.43  5121.3  477.87  5165.8  478.65  5332.3  482.52  5452.8  486.45
    5503  486.49  5528.9  488.33  5583.4  488.01  5653.7  489.18  5697.3  490.57
#Mann= 5 ,-1 , 0
  4560.2     .05       0  4934.3     .12       0  5000.3     .07       0
  5006.4     .12       0  5165.8     .05       0
Bank Sta=5000.3,5006.4
XS Rating Curve= 0 ,0
Exp/Cntr=0.3,0.1

Type RM Length L Ch R = 1 ,3433    ,397,397,397
BEGIN DESCRIPTION:
Mapping XS 0b526842
END DESCRIPTION:
XS GIS Cut Line= 3
      2751476.99      6919834.51      2751137.67      6920228.96
      2751017.46       6920817.6
#Sta/Elev= 30
  4449.7  502.12  4490.4  500.19    4576  494.07  4653.9  489.88    4746  483.73
  4752.6  482.84  4889.7  478.17  4944.7  476.34  4958.9  474.54  4965.5  477.45
  4968.1  476.79  4973.6  476.79  4982.3  471.33  4989.5  471.33  4990.5  470.83
  4995.6  471.33  5000.5  476.12  5012.9  477.12  5033.3  477.36  5043.5  476.61
  5095.1  477.16  5125.2  476.97  5207.6  478.76  5303.5  482.07  5348.9  484.93
  5380.3  485.21  5399.4  486.63  5482.4   489.5  5500.4  490.79  5570.8  492.38
#Mann= 5 ,-1 , 0
  4449.7     .05       0  4889.7     .12       0  4989.5     .07       0
  4995.6     .12       0  5095.1     .05       0
Bank Sta=4989.5,4995.6
XS Rating Curve= 0 ,0
Exp/Cntr=0.3,0.1

Type RM Length L Ch R = 1 ,3036    ,409,409,409
BEGIN DESCRIPTION:
Mapping XS 6ca45177
END DESCRIPTION:
XS GIS Cut Line= 3
        2751310.      6919677.97      2750806.54      6920049.48
      2750816.96      6920552.98
#Sta/Elev= 30
  4380.1  506.49  4413.3  504.36  4442.6  503.81  4463.4  501.14  4478.1  501.36
  4542.8  494.43  4563.7  490.01  4634.6  490.33    4643  489.91  4663.9  485.49
  4678.5  484.22    4879  475.98    4950  475.38  4970.8  473.89  4979.2  474.14
  4985.5  475.66  4993.9  474.46  4999.9     470    5001   469.5  5006.1     470
  5037.3  475.36  5045.4  475.54  5077.3  474.42  5093.6  476.02  5221.9  479.63
  5337.4  484.49  5367.4  488.12  5457.4  494.51  5487.4  495.54  5509.4  495.18
#Mann= 5 ,-1 , 0
  4380.1     .05       0  4999.9     .04       0  5006.1     .05       0
  5045.4     .12       0  5093.6     .05       0
Bank Sta=4999.9,5006.1
XS Rating Curve= 0 ,0
Exp/Cntr=0.3,0.1

Type RM Length L Ch R = 1 ,2627    ,443,443,443
BEGIN DESCRIPTION:
Mapping XS 0e196031
END DESCRIPTION:
XS GIS Cut Line= 3
      2750969.73      6919365.46      2750591.26      6919761.29
       2750573.9      6920455.72
#Sta/Elev= 30
  4453.9  502.41  4474.7  501.19  4488.9  499.52  4538.3  496.98  4573.5  494.28
  4630.1  492.69  4644.3  491.79  4651.5   490.3  4764.7  483.31  4920.1  477.04
  4969.8  471.62  4973.6  469.13  4974.6  468.63  4979.8  469.13  4983.9  469.29
  4990.8     472  4997.9  473.34  5003.9  473.34  5014.1  474.92  5071.3   475.1
  5131.3  472.21  5171.3  473.83  5221.3   474.5  5251.3   477.2  5271.3  475.99
  5311.4  476.28  5421.4  478.57  5531.4  482.26  5651.5  487.45  5696.2   487.4
#Mann= 3 ,-1 , 0
  4453.9     .05       0  4973.6     .04       0  4979.8     .05       0
Bank Sta=4973.6,4979.8
XS Rating Curve= 0 ,0
Exp/Cntr=0.3,0.1

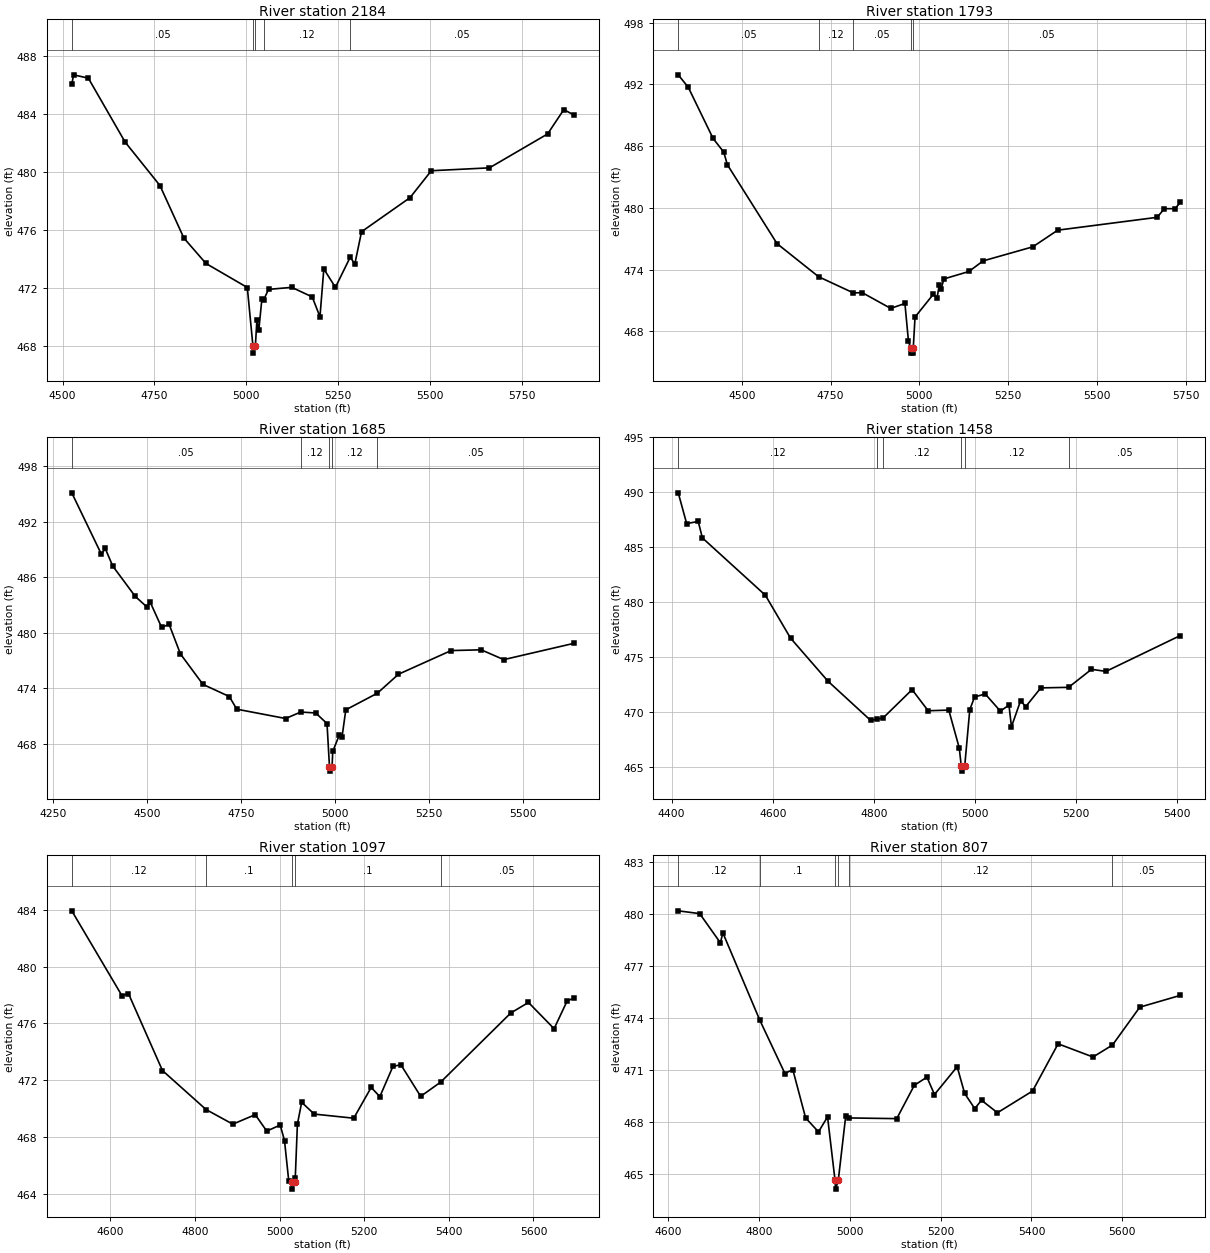
Type RM Length L Ch R = 1 ,2184    ,391,391,391
BEGIN DESCRIPTION:
Flat T8 2.0
END DESCRIPTION:
XS GIS Cut Line= 3
        2750201.      6919185.97      2750181.18      6919660.55
      2750462.49      6920506.93
#Sta/Elev= 30
    4525  486.05    4530   486.7  4570.1  486.47  4670.2  482.06    4765  479.06
  4830.3  475.43  4890.3  473.68  5002.9  472.02  5018.2  467.99  5019.2  467.49
  5024.9  467.99    5029  469.77  5034.2  469.07  5042.6  471.24  5047.4  471.16
  5060.6  471.89    5124  472.03  5179.6  471.37  5200.7     470  5211.2   473.3
  5242.8  472.03  5283.2  474.12  5295.5  473.63  5313.9  475.87  5445.8  478.22
  5503.9  480.08  5662.2  480.28  5820.5  482.62  5864.6   484.3  5891.9  483.93
#Mann= 5 ,-1 , 0
    4525     .05       0  5018.2     .04       0  5024.9     .05       0
  5047.4     .12       0  5283.2     .05       0
Bank Sta=5018.2,5024.9
XS Rating Curve= 0 ,0
Exp/Cntr=0.3,0.1

Type RM Length L Ch R = 1 ,1793    ,108,108,108
BEGIN DESCRIPTION:
Mapping XS 084de129
END DESCRIPTION:
XS GIS Cut Line= 3
      2749869.04       6919132.8      2749848.21      6919802.96
      2749879.46      6920546.02
#Sta/Elev= 30
  4321.1  492.94  4349.3  491.73  4419.3  486.75  4449.4  485.42  4459.4   484.2
  4599.4  476.52  4716.5   473.3  4814.3  471.73  4839.5  471.75  4919.6  470.22
  4959.6   470.7  4969.6  467.02  4976.1  466.37  4977.2  465.87    4982  465.87
  4983.1  466.37  4988.1  469.38  5039.7   471.6  5049.7  471.19  5056.4  472.47
  5061.4  472.13  5069.7  473.09  5139.8  473.81  5179.8  474.84  5319.9  476.21
    5390  477.83  5670.2  479.08  5690.2  479.92  5720.3  479.92  5735.3  480.53
#Mann= 5 ,-1 , 0
  4321.1     .05       0  4716.5     .12       0  4814.3     .05       0
  4976.1     .05       0  4983.1     .05       0
Bank Sta=4976.1,4983.1
XS Rating Curve= 0 ,0
Exp/Cntr=0.3,0.1

Type RM Length L Ch R = 1 ,1685    ,227,227,227
BEGIN DESCRIPTION:
Mapping XS 6b503e91
END DESCRIPTION:
XS GIS Cut Line= 3
      2749737.09        6919112.      2749740.57      6919806.43
      2749757.89      6920447.36
#Sta/Elev= 30
  4300.6  495.15  4379.6  488.49  4389.6  489.13  4409.6  487.23  4469.6  483.94
  4499.6  482.84  4509.6  483.29  4539.6   480.6  4559.6  480.92  4589.6  477.73
  4649.6  474.43  4719.6  473.12  4739.6  471.75  4869.6  470.74  4909.6  471.44
  4949.6  471.34  4979.6  470.19  4986.1  465.55  4987.2  465.05  4993.1  465.55
  4994.8  467.18  5012.8     469  5019.6  468.76  5029.6  471.68  5113.6  473.48
  5169.7  475.53  5309.7  478.09  5389.8  478.17  5449.8  477.11  5636.2  478.87
#Mann= 5 ,-1 , 0
  4300.6     .05       0  4909.6     .12       0  4986.1     .07       0
  4993.1     .12       0  5113.6     .05       0
Bank Sta=4986.1,4993.1
XS Rating Curve= 0 ,0
Exp/Cntr=0.3,0.1

Type RM Length L Ch R = 1 ,1458    ,361,361,361
BEGIN DESCRIPTION:
Mapping XS b4ce7f12
END DESCRIPTION:
XS GIS Cut Line= 3
      2749700.63      6919194.87      2749544.39      6919764.26
      2749523.59      6920166.48
#Sta/Elev= 30
  4413.1  489.95  4429.8  487.15  4452.6  487.35  4460.9  485.85  4585.4  480.64
  4635.2  476.74  4709.3  472.82  4793.8  469.25  4806.4  469.36  4818.2  469.47
  4875.7  472.05  4907.5  470.13  4948.3  470.19    4969  466.75  4972.9  465.14
    4974  464.64  4979.9  465.14  4989.8  470.22  4999.3  471.38  5020.3  471.66
  5050.3   470.1  5067.3  470.64  5072.3  468.68  5090.4  471.05  5100.4   470.5
  5130.4  472.21  5185.3  472.26  5230.6   473.9  5259.2  473.71  5406.3  476.97
#Mann= 6 ,-1 , 0
  4413.1     .12       0  4806.4      .1       0  4818.2     .12       0
  4972.9     .07       0  4979.9     .12       0  5185.3     .05       0
Bank Sta=4972.9,4979.9
XS Rating Curve= 0 ,0
Exp/Cntr=0.3,0.1

Type RM Length L Ch R = 1 ,1097    ,290,290,290
BEGIN DESCRIPTION:
Mapping XS 2bfd727e
END DESCRIPTION:
XS GIS Cut Line= 4
      2749480.32      6919183.39      2749239.52      6919597.51
      2749222.52      6919694.51      2749367.49      6920286.39
#Sta/Elev= 30
  4508.5  483.94  4626.9  477.97  4642.6   478.1  4722.9  472.68    4826  469.93
  4889.2   468.9  4942.2  469.57  4969.5  468.41  5001.2  468.84  5011.4  467.74
  5021.5  464.88  5028.1  464.82  5029.2  464.32  5035.2  464.82  5036.8  465.07
  5041.9   468.9    5052  470.44  5081.7  469.61  5175.1  469.32  5216.3  471.49
  5236.8  470.84  5267.7  472.97  5286.5  473.09  5333.3  470.86  5380.8  471.87
  5546.4  476.74  5588.1  477.48  5648.7  475.63  5679.6  477.59  5695.4  477.79
#Mann= 5 ,-1 , 0
  4508.5     .12       0    4826      .1       0  5028.1     .07       0
  5035.2      .1       0  5380.8     .05       0
Bank Sta=5028.1,5035.2
XS Rating Curve= 0 ,0
Exp/Cntr=0.3,0.1

Type RM Length L Ch R = 1 ,807     ,599,599,599
BEGIN DESCRIPTION:
Mapping XS c5298dbe
END DESCRIPTION:
XS GIS Cut Line= 4
      2749100.68      6919202.31      2748965.51      6919489.15
      2748967.03      6919577.94      2749287.22      6920200.42
#Sta/Elev= 30
    4622  480.17  4669.2  480.01  4714.8  478.33  4720.3   478.9  4801.7  473.87
    4857   470.8  4874.3  471.03  4902.6  468.24  4930.9  467.44  4950.9   468.3
  4967.4  464.64  4968.5  464.14  4974.5  464.64    4991  468.37  4998.9  468.24
  5103.3   468.2    5142  470.12  5169.8  470.59  5186.4  469.59  5236.4  471.19
  5252.9  469.65  5275.1  468.78    5290  469.26  5325.1  468.54  5402.4  469.79
  5458.7  472.51  5535.6  471.75  5578.5  472.44  5638.6  474.62  5727.9   475.3
#Mann= 6 ,-1 , 0
    4622     .12       0  4801.7      .1       0  4967.4     .07       0
  4974.5      .1       0  4998.9     .12       0  5578.5     .05       0
Bank Sta=4967.4,4974.5
XS Rating Curve= 0 ,0
Exp/Cntr=0.3,0.1

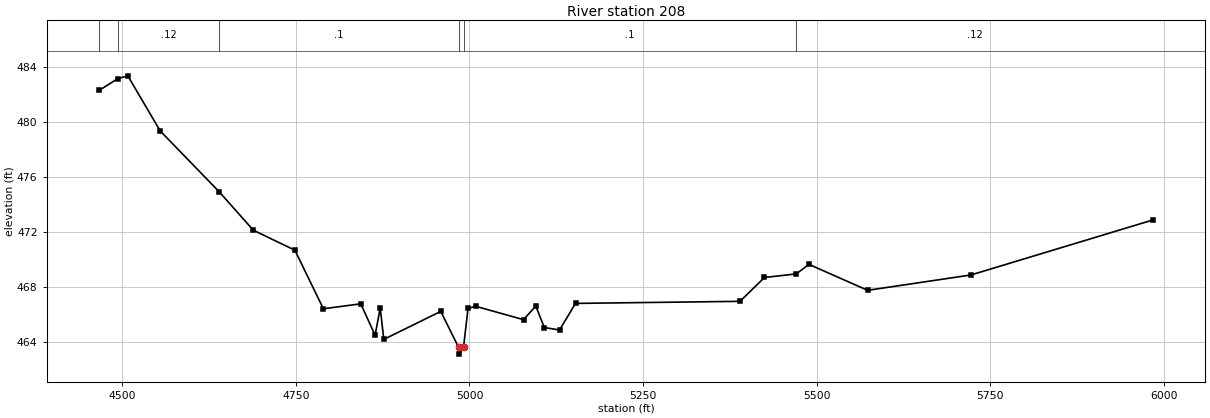
Type RM Length L Ch R = 1 ,208     ,0,0,0
BEGIN DESCRIPTION:
Flat T8 1.0
END DESCRIPTION:
XS GIS Cut Line= 4
      2748651.01      6918885.96      2748519.97      6919402.81
      2748640.57      6919669.64      2749150.99      6920135.99
#Sta/Elev= 30
  4466.8  482.29  4493.5  483.14  4507.8  483.34  4554.5  479.34  4639.6  474.92
  4688.6  472.14  4748.5  470.69  4789.5  466.44  4843.4   466.8    4864  464.52
  4871.4  466.49  4876.6  464.22  4958.6  466.25  4984.2  463.65  4985.4  463.15
  4991.4  463.65  4997.9  466.47    5009  466.62  5077.8  465.65  5095.5  466.64
  5107.8  465.08  5129.7   464.9  5152.7  466.83  5389.7  466.98  5424.9  468.71
  5470.7  468.97    5489  469.66  5573.5  467.78  5722.1  468.89  5984.2  472.88
#Mann= 6 ,-1 , 0
  4466.8     .05       0  4493.5     .12       0  4639.6      .1       0
  4984.2     .07       0  4991.4      .1       0  5470.7     .12       0
Bank Sta=4984.2,4991.4
XS Rating Curve= 0 ,0
Exp/Cntr=0.3,0.1

Chan Stop Cuts=-1
Use User Specified Reach Order=0
Composite Channel Slope=5