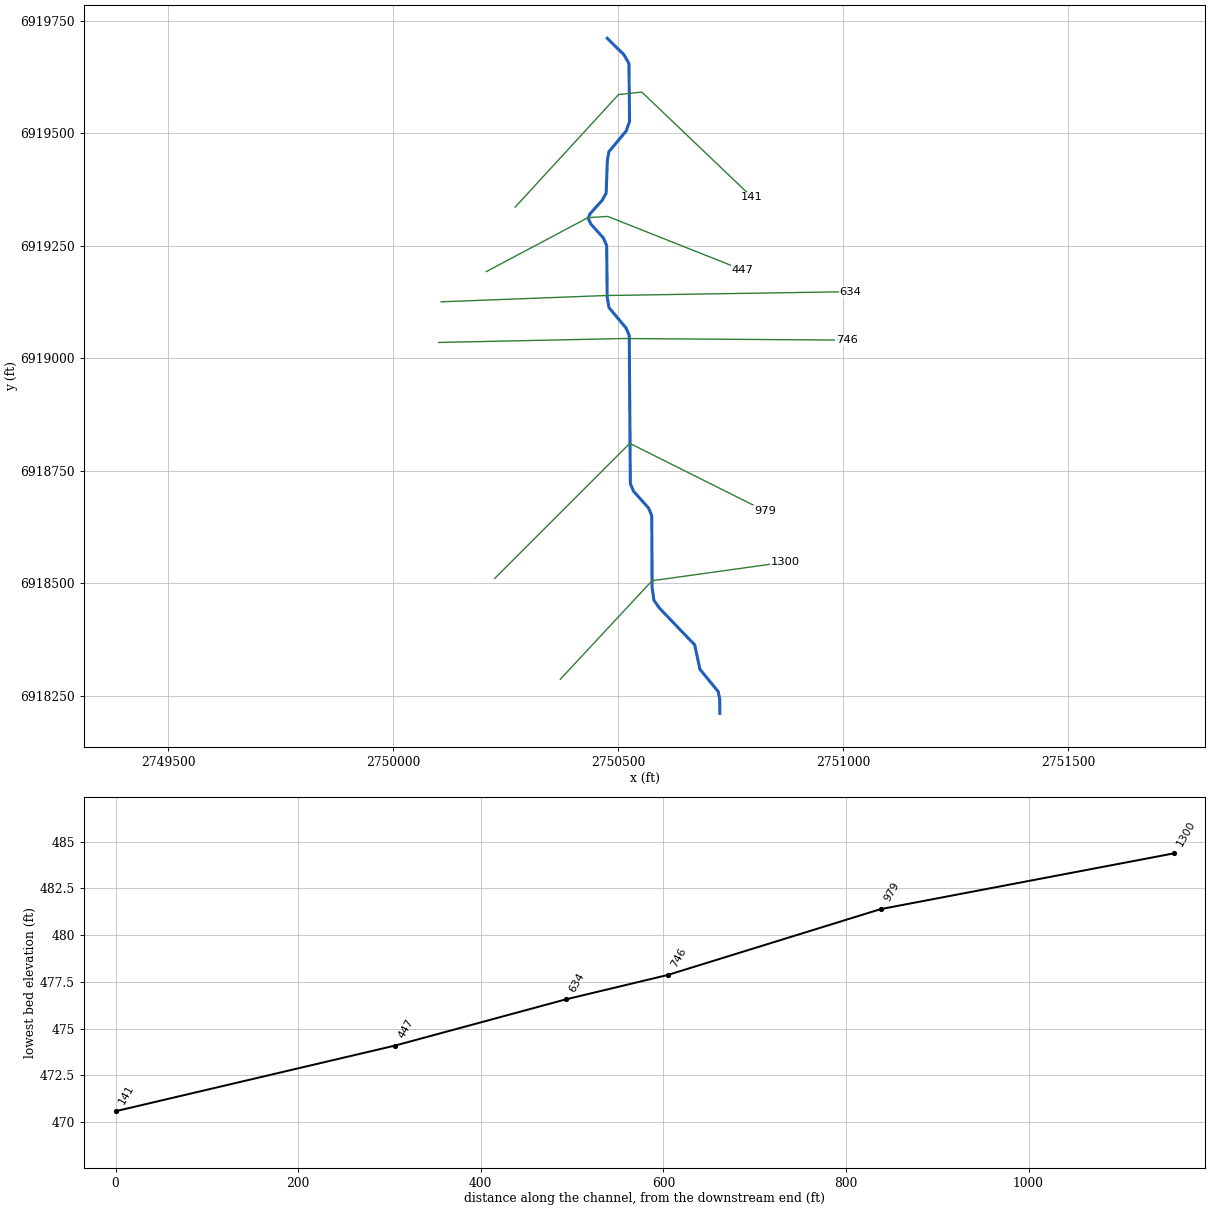
--- Flat T8_1.prj (project) ---

Proj Title=Flat T8_1 Base Level Engineering
Current Plan=p01
Default Exp/Contr=0.3,0.1
English Units
Geom File=g01
Flow File=f01
Plan File=p01
BEGIN DESCRIPTION:
Flat T8_1
END DESCRIPTION:

--- Flat T8_1.p01 (plan) ---

Plan Title=Multiple Run
Short Identifier=Multiple
Geom File=g01
Flow File=f01
Subcritical Flow
K Sum by GR= 0
Std Step Tol= 0.01
Critical Tol= 0.01
Num of Std Step Trials= 20
Max Error Tol= 0.3
Flow Tol Ratio= 0.001
Split Flow NTrial= 30
Split Flow Tol= 0.02
Split Flow Ratio= 0.02
Log Output Level= 0
Friction Slope Method= 1
Unsteady Friction Slope Method= 2
Unsteady Bridges Friction Slope Method= 1
Parabolic Critical Depth
Global Vel Dist=  1 , 1 , 1
Global Log Level= 0
CheckData=True
Encroach Param= -1, 0, 0, 0
BEGIN DESCRIPTION:
Multiple Run
END DESCRIPTION:

--- Flat T8_1.f01 (steady flow) ---

Flow Title=Multiple
Number of Profiles=7
Profile Names=10-year,25-year,50-year,1pct_min,100-year,1pct_plu,500-year
River Rch & RM= Flat T8_1,Reach-1,1300
     187     234     270     155     310     619     409
Boundary for River Rch & Prof#=Flat T8_1,Reach-1,1
Up Type=0
Dn Type=3
Dn Slope=0.005
Boundary for River Rch & Prof#=Flat T8_1,Reach-1,2
Up Type=0
Dn Type=3
Dn Slope=0.005
Boundary for River Rch & Prof#=Flat T8_1,Reach-1,3
Up Type=0
Dn Type=3
Dn Slope=0.005
Boundary for River Rch & Prof#=Flat T8_1,Reach-1,4
Up Type=0
Dn Type=3
Dn Slope=0.005
Boundary for River Rch & Prof#=Flat T8_1,Reach-1,5
Up Type=0
Dn Type=3
Dn Slope=0.005
Boundary for River Rch & Prof#=Flat T8_1,Reach-1,6
Up Type=0
Dn Type=3
Dn Slope=0.005
Boundary for River Rch & Prof#=Flat T8_1,Reach-1,7
Up Type=0
Dn Type=3
Dn Slope=0.005

--- Flat T8_1.g01 (geometry) ---

Geom Title=Existing Conditions

River Reach=Flat T8_1,Reach-1
Reach XY= 30
      2750726.00      6918211.00      2750725.90      6918242.81
      2750722.40      6918259.51      2750681.97      6918308.76
      2750670.17      6918363.30      2750592.46      6918444.25
      2750579.55      6918462.47      2750575.57      6918490.82
      2750574.78      6918650.49      2750567.86      6918667.06
      2750534.14      6918704.94      2750527.22      6918721.50
      2750524.78      6919050.50      2750517.86      6919067.06
      2750479.79      6919112.57      2750475.82      6919135.93
      2750474.60      6919250.56      2750467.54      6919267.18
      2750439.95      6919297.79      2750433.56      6919311.00
      2750437.47      6919320.91      2750464.75      6919351.22
      2750473.45      6919366.89      2750476.23      6919440.90
      2750479.85      6919459.40      2750517.87      6919504.94
      2750525.50      6919526.22      2750524.12      6919655.21
      2750513.09      6919674.50      2750476.00      6919711.00

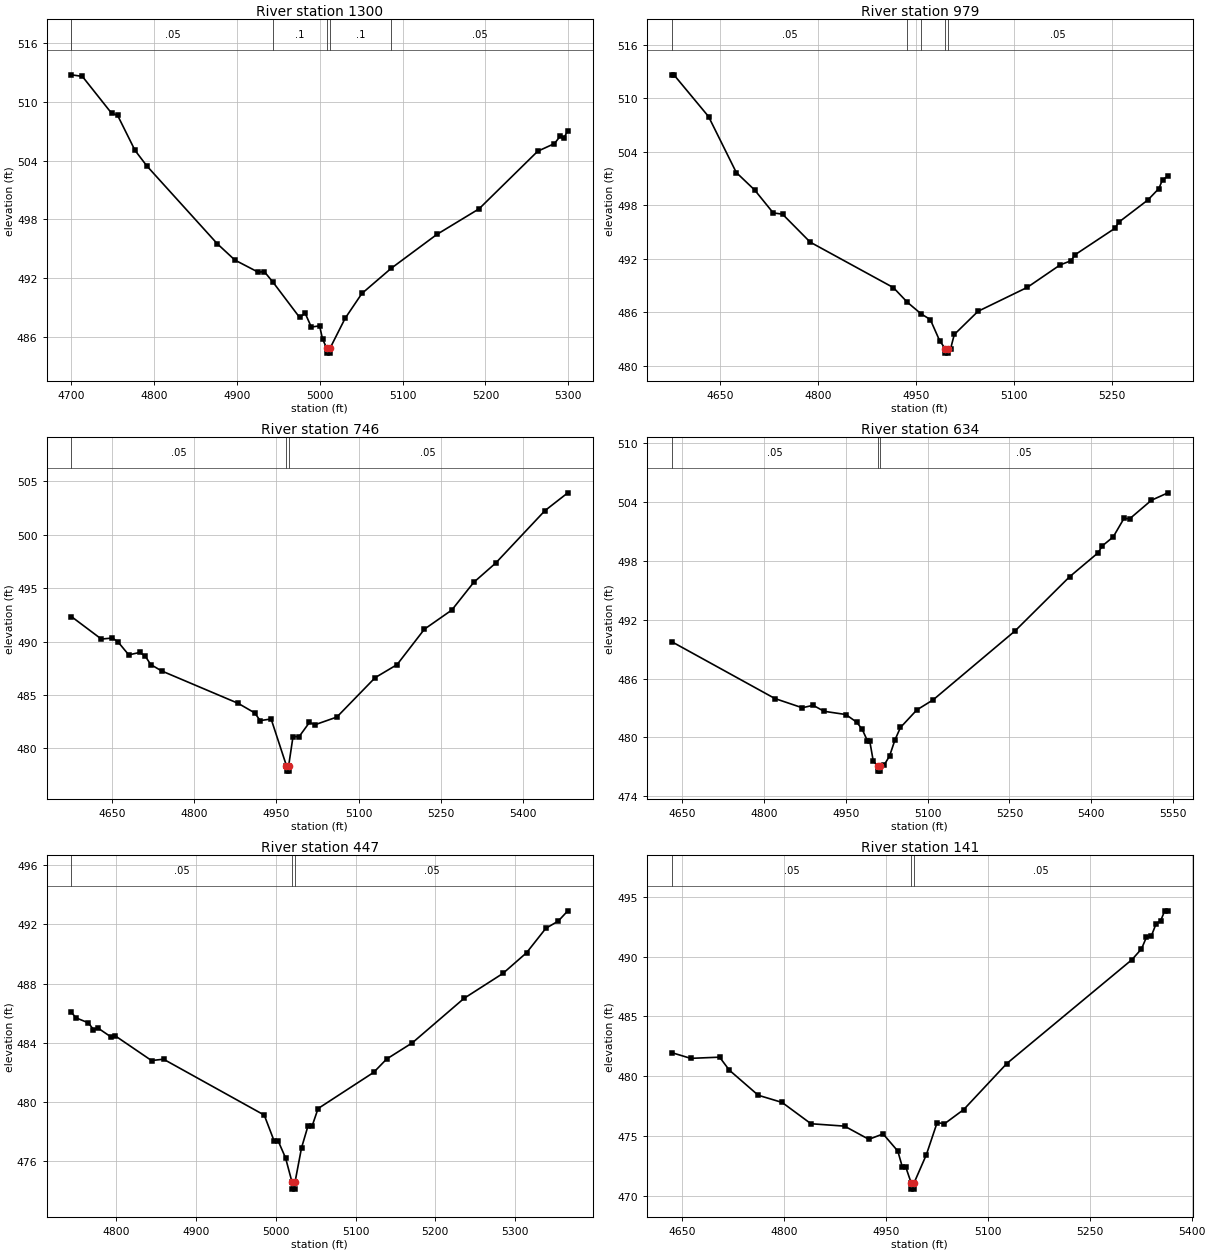
Type RM Length L Ch R = 1,1300,321,321,321
BEGIN DESCRIPTION:
Flat T8_1 3.0
END DESCRIPTION:
XS GIS Cut Line= 3
      2750371.65      6918286.82      2750575.53      6918505.80
      2750871.97      6918547.07
#Sta/Elev= 30
  4700.8  512.74  4713.9  512.58  4749.1  508.83  4756.4  508.61  4777.4  505.04
  4791.6  503.46  4876.6  495.52  4897.8  493.86  4926.0  492.62  4933.3  492.68
  4944.1  491.57  4975.8  488.02  4982.6  488.43  4990.0  487.03  5000.0  487.15
  5003.5  485.82  5008.6  484.87  5008.8  484.37  5012.3  484.37  5012.6  484.87
  5030.8  487.92  5051.0  490.45  5086.4  493.02  5141.6  496.48  5192.3  499.08
  5263.0  504.95  5283.2  505.73  5289.9  506.46  5294.9  506.34  5299.3  507.06
#Mann=5,-1,0
  4700.8    0.05       0  4944.1     0.1       0  5008.6    0.07       0
  5012.6     0.1       0  5086.4    0.05       0
Bank Sta=5008.6,5012.6
Exp/Cntr=0.3,0.1

Type RM Length L Ch R = 1,979,233,233,233
BEGIN DESCRIPTION:
Flat T8_1 2.0
END DESCRIPTION:
XS GIS Cut Line= 3
      2750226.03      6918511.03      2750526.00      6918811.00
      2750825.97      6918661.02
#Sta/Elev= 30
  4575.9  512.61  4579.4  512.61  4632.4  507.93  4674.9  501.65  4703.1  499.68
  4731.4  497.12  4745.6  496.98  4788.0  493.84  4915.3  488.74  4936.9  487.08
  4958.0  485.78  4971.8  485.16  4986.0  482.80  4994.6  481.89  4994.8  481.39
  4998.3  481.39  4998.6  481.89  5002.9  481.89  5008.5  483.48  5044.8  486.08
  5120.3  488.77  5170.6  491.29  5187.4  491.76  5193.0  492.41  5254.5  495.40
  5260.1  496.07  5304.8  498.57  5321.6  499.85  5327.2  500.84  5335.5  501.24
#Mann=5,-1,0
  4575.9    0.05       0  4936.9     0.1       0  4958.0    0.05       0
  4994.6    0.04       0  4998.6    0.05       0
Bank Sta=4994.6,4998.6
Exp/Cntr=0.3,0.1

Type RM Length L Ch R = 1,746,112,112,112
BEGIN DESCRIPTION:
Mapping XS 9f33e37b
END DESCRIPTION:
XS GIS Cut Line= 3
      2750101.45      6919035.23      2750512.93      6919043.91
      2751007.75      6919040.43
#Sta/Elev= 30
  4575.7  492.33  4630.3  490.23  4650.3  490.33  4660.3  489.99  4680.3  488.75
  4700.3  488.98  4710.3  488.65  4720.3  487.85  4740.3  487.25  4880.3  484.21
  4910.3  483.32  4920.3  482.60  4940.3  482.75  4968.3  478.37  4968.6  477.87
  4972.1  477.87  4972.3  478.37  4980.3  481.11  4991.3  481.09  5010.3  482.43
  5020.3  482.21  5060.3  482.93  5130.3  486.62  5170.3  487.84  5220.3  491.16
  5270.3  492.95  5310.3  495.54  5350.3  497.34  5440.3  502.25  5482.1  503.92
#Mann=3,-1,0
  4575.7    0.05       0  4968.3    0.04       0  4972.3    0.05       0
Bank Sta=4968.3,4972.3
Exp/Cntr=0.3,0.1

Type RM Length L Ch R = 1,634,187,187,187
BEGIN DESCRIPTION:
Mapping XS e2bf9775
END DESCRIPTION:
XS GIS Cut Line= 3
      2750106.71      6919125.51      2750469.53      6919139.39
      2751016.38      6919148.07
#Sta/Elev= 30
  4630.7  489.76  4820.1  483.96  4870.2  483.02  4890.2  483.27  4910.2  482.66
  4950.2  482.33  4970.2  481.54  4980.2  480.81  4989.5  479.68  4993.8  479.68
  5000.3  477.62  5008.3  477.06  5008.5  476.56  5012.0  476.56  5012.3  477.06
  5020.3  477.18  5030.3  478.10  5040.3  479.76  5050.3  481.01  5080.3  482.80
  5110.3  483.83  5260.3  490.85  5360.3  496.37  5412.7  498.82  5420.3  499.52
  5440.3  500.43  5460.3  502.34  5470.3  502.27  5510.3  504.17  5540.7  504.93
#Mann=3,-1,0
  4630.7    0.05       0  5008.3    0.04       0  5012.3    0.05       0
Bank Sta=5008.3,5012.3
Exp/Cntr=0.3,0.1

Type RM Length L Ch R = 1,447,306,306,306
BEGIN DESCRIPTION:
Mapping XS 6179f39f
END DESCRIPTION:
XS GIS Cut Line= 4
      2750207.30      6919192.75      2750432.99      6919312.49
      2750476.89      6919315.28      2750777.25      6919196.14
#Sta/Elev= 30
  4743.7  486.05  4749.3  485.68  4764.9  485.34  4771.2  484.89  4776.9  484.99
  4793.2  484.39  4798.9  484.45  4844.1  482.79  4859.2  482.88  4985.5  479.10
  4998.1  477.32  5003.2  477.32  5012.2  476.21  5020.2  474.59  5020.5  474.09
  5024.0  474.09  5024.2  474.59  5032.3  476.89  5040.2  478.33  5045.4  478.33
  5053.0  479.54  5122.8  481.99  5139.0  482.89  5171.3  483.99  5236.2  487.00
  5284.8  488.68  5314.5  490.08  5338.8  491.74  5354.2  492.22  5366.3  492.92
#Mann=3,-1,0
  4743.7    0.05       0  5020.2    0.04       0  5024.2    0.05       0
Bank Sta=5020.2,5024.2
Exp/Cntr=0.3,0.1

Type RM Length L Ch R = 1,141,0,0,0
BEGIN DESCRIPTION:
Flat T8_1 1.0
END DESCRIPTION:
XS GIS Cut Line= 4
      2750271.35      6919336.02      2750501.00      6919586.00
      2750552.65      6919591.61      2750797.72      6919357.84
#Sta/Elev= 30
  4635.0  481.98  4663.1  481.50  4705.6  481.60  4719.8  480.52  4762.4  478.42
  4797.5  477.82  4840.0  476.04  4889.4  475.84  4925.1  474.74  4946.1  475.19
  4967.7  473.76  4974.5  472.41  4979.5  472.41  4987.5  471.08  4987.8  470.58
  4991.3  470.58  4991.5  471.08  5009.7  473.45  5025.6  476.14  5036.2  476.03
  5064.6  477.22  5128.1  481.07  5312.1  489.74  5326.2  490.64  5333.5  491.62
  5340.4  491.68  5347.6  492.73  5354.5  493.01  5360.4  493.82  5365.1  493.82
#Mann=3,-1,0
  4635.0    0.05       0  4987.5    0.04       0  4991.5    0.05       0
Bank Sta=4987.5,4991.5
Exp/Cntr=0.3,0.1

Chan Stop Cuts=-1