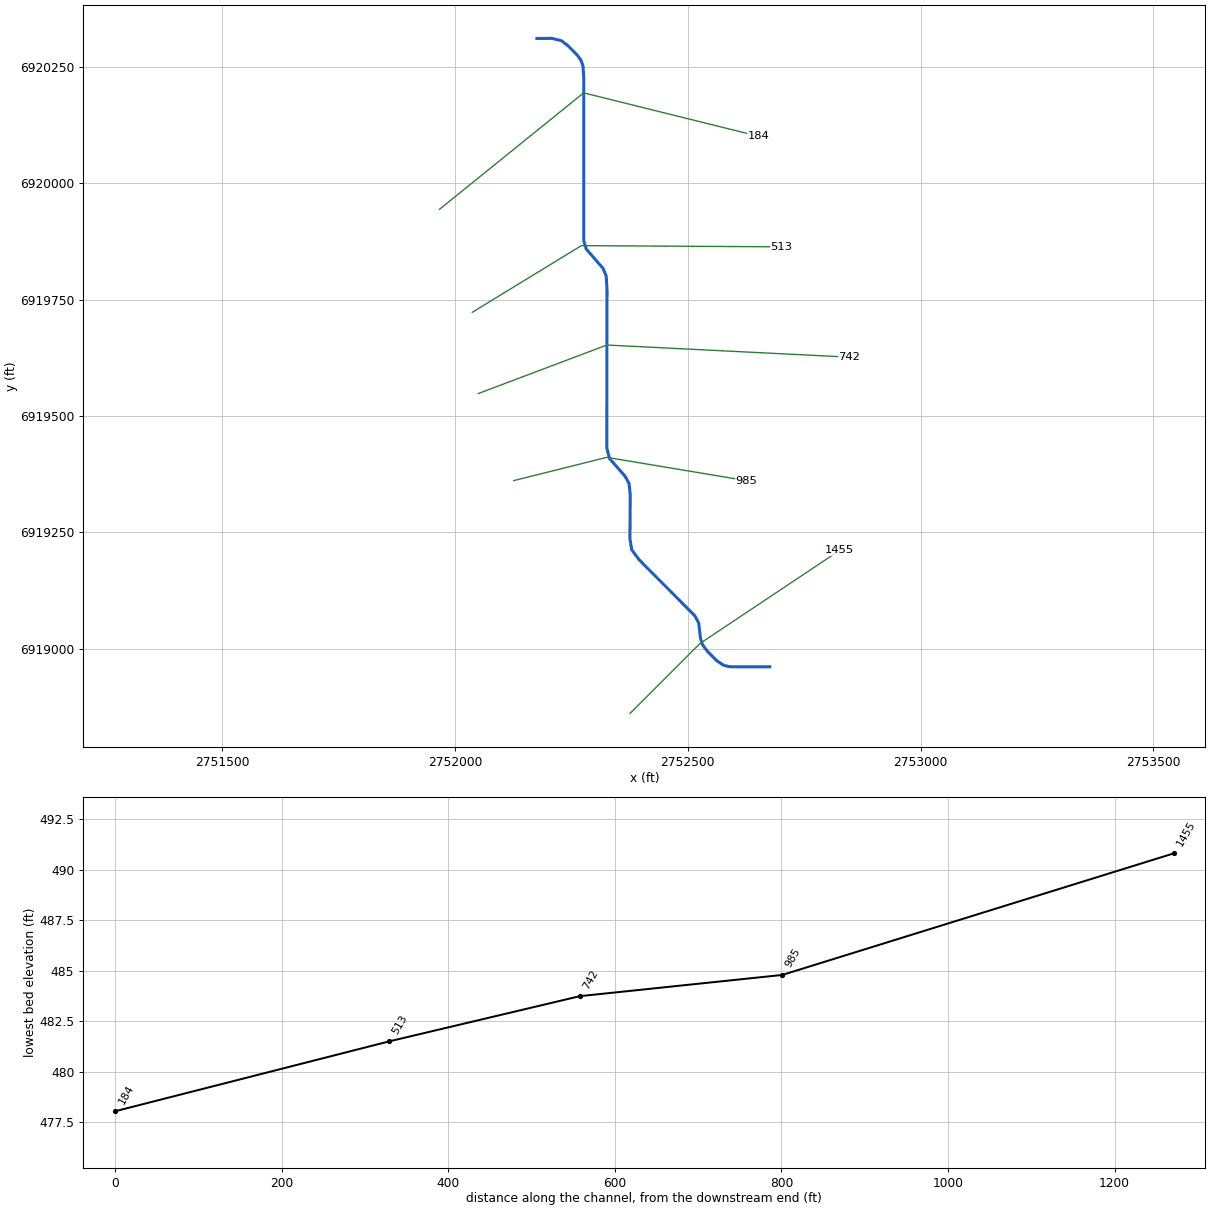
--- Flat T8_2.prj (project) ---

Proj Title=Flat T8_2 Base Level Engineering
Current Plan=p01
Default Exp/Contr=0.3,0.1
English Units
Geom File=g01
Flow File=f01
Plan File=p01
BEGIN DESCRIPTION:
Flat T8_2
END DESCRIPTION:

--- Flat T8_2.p01 (plan) ---

Plan Title=Multiple Run
Short Identifier=Multiple
Geom File=g01
Flow File=f01
Subcritical Flow
K Sum by GR= 0
Std Step Tol= 0.01
Critical Tol= 0.01
Num of Std Step Trials= 20
Max Error Tol= 0.3
Flow Tol Ratio= 0.001
Split Flow NTrial= 30
Split Flow Tol= 0.02
Split Flow Ratio= 0.02
Log Output Level= 0
Friction Slope Method= 1
Unsteady Friction Slope Method= 2
Unsteady Bridges Friction Slope Method= 1
Parabolic Critical Depth
Global Vel Dist=  1 , 1 , 1
Global Log Level= 0
CheckData=True
Encroach Param= -1, 0, 0, 0
BEGIN DESCRIPTION:
Multiple Run
END DESCRIPTION:

--- Flat T8_2.f01 (steady flow) ---

Flow Title=Multiple
Number of Profiles=7
Profile Names=10-year,25-year,50-year,1pct_min,100-year,1pct_plu,500-year
River Rch & RM= Flat T8_2,Reach-1,1455
     226     285     330     191     381     760     507
Boundary for River Rch & Prof#=Flat T8_2,Reach-1,1
Up Type=0
Dn Type=3
Dn Slope=0.005
Boundary for River Rch & Prof#=Flat T8_2,Reach-1,2
Up Type=0
Dn Type=3
Dn Slope=0.005
Boundary for River Rch & Prof#=Flat T8_2,Reach-1,3
Up Type=0
Dn Type=3
Dn Slope=0.005
Boundary for River Rch & Prof#=Flat T8_2,Reach-1,4
Up Type=0
Dn Type=3
Dn Slope=0.005
Boundary for River Rch & Prof#=Flat T8_2,Reach-1,5
Up Type=0
Dn Type=3
Dn Slope=0.005
Boundary for River Rch & Prof#=Flat T8_2,Reach-1,6
Up Type=0
Dn Type=3
Dn Slope=0.005
Boundary for River Rch & Prof#=Flat T8_2,Reach-1,7
Up Type=0
Dn Type=3
Dn Slope=0.005

--- Flat T8_2.g01 (geometry) ---

Geom Title=Existing Conditions

River Reach=Flat T8_2,Reach-1
Reach XY= 30
      2752676.00      6918961.00      2752590.89      6918961.05
      2752577.15      6918964.28      2752562.28      6918974.19
      2752542.44      6918993.87      2752531.73      6919008.43
      2752527.48      6919021.48      2752523.45      6919054.91
      2752515.21      6919070.66      2752395.61      6919190.84
      2752379.54      6919212.47      2752375.73      6919235.89
      2752376.32      6919331.13      2752373.73      6919355.06
      2752365.14      6919370.64      2752331.75      6919408.67
      2752326.07      6919431.03      2752326.45      6919771.19
      2752324.78      6919800.50      2752317.86      6919817.06
      2752281.75      6919858.67      2752276.52      6919876.22
      2752276.50      6920226.24      2752275.04      6920250.70
      2752270.74      6920263.69      2752262.92      6920274.67
      2752243.35      6920294.69      2752228.95      6920305.87
      2752208.08      6920311.16      2752176.00      6920311.00

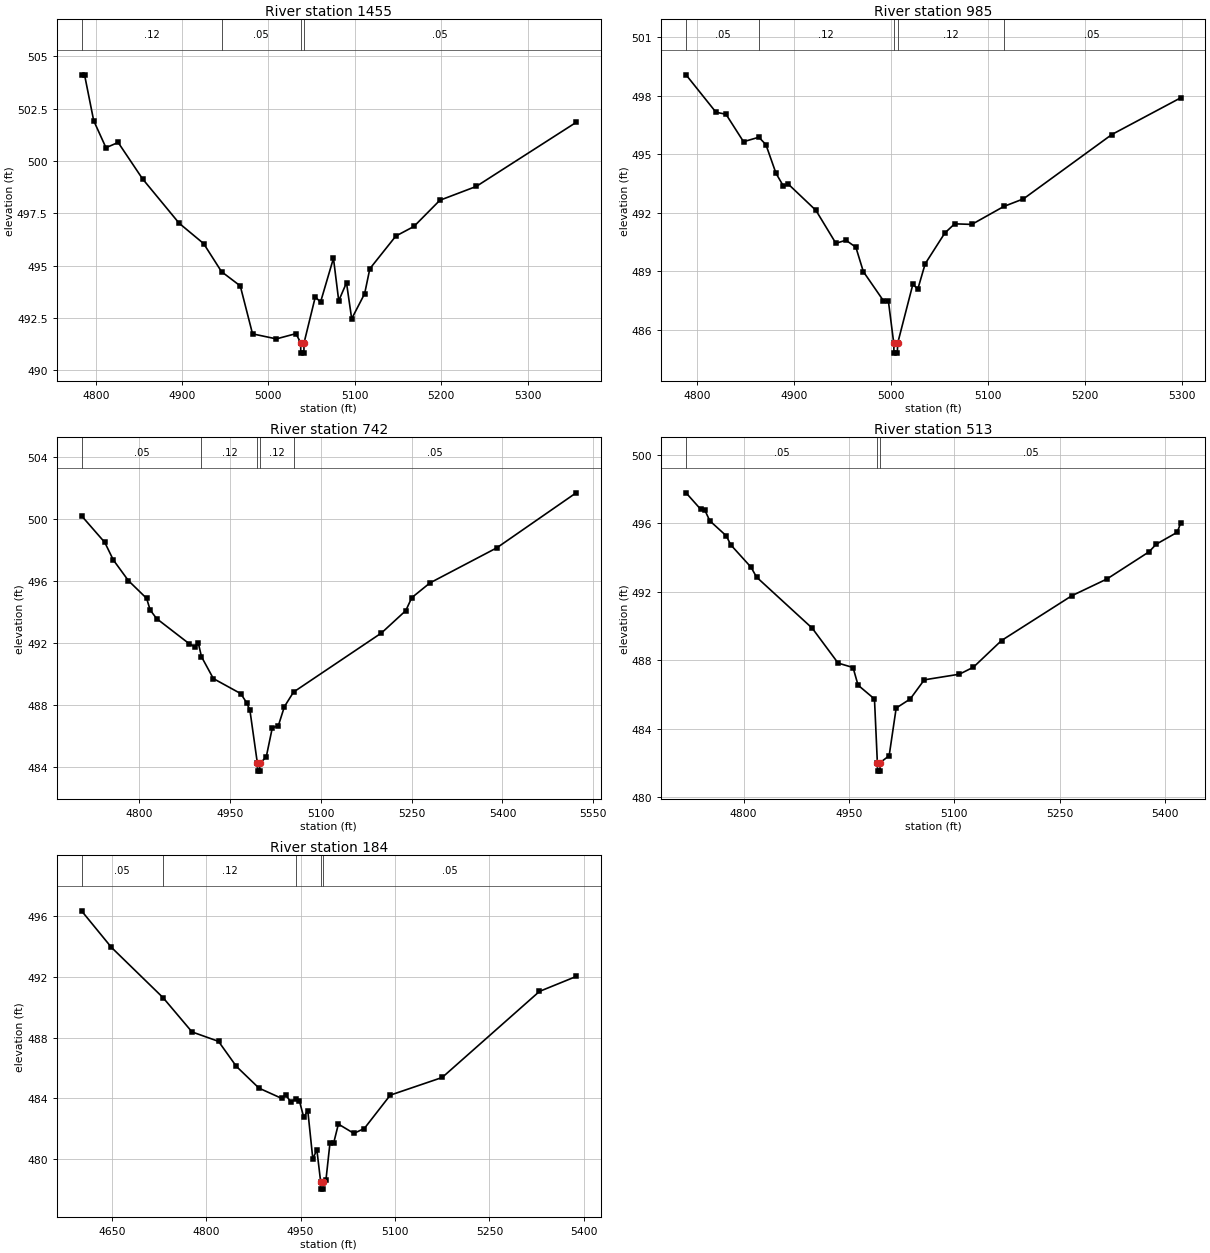
Type RM Length L Ch R = 1,1455,470,470,470
BEGIN DESCRIPTION:
Flat T8_2 3.0
END DESCRIPTION:
XS GIS Cut Line= 3
      2752376.01      6918861.01      2752526.00      6919011.00
      2752826.02      6919211.01
#Sta/Elev= 30
  4783.6  504.11  4787.1  504.11  4797.7  501.92  4811.9  500.63  4826.0  500.88
  4854.3  499.14  4896.7  497.02  4925.0  496.05  4945.7  494.71  4967.4  494.03
  4981.6  491.74  5009.2  491.50  5031.8  491.75  5037.3  491.32  5037.5  490.82
  5041.0  490.82  5041.3  491.32  5054.3  493.51  5060.3  493.25  5075.3  495.35
  5081.4  493.32  5090.4  494.18  5096.4  492.46  5111.4  493.66  5117.4  494.85
  5147.5  496.41  5168.5  496.87  5198.5  498.12  5240.6  498.78  5356.3  501.84
#Mann=4,-1,0
  4783.6    0.12       0  4945.7    0.05       0  5037.3    0.04       0
  5041.3    0.05       0
Bank Sta=5037.3,5041.3
Exp/Cntr=0.3,0.1

Type RM Length L Ch R = 1,985,243,243,243
BEGIN DESCRIPTION:
Flat T8_2 2.0
END DESCRIPTION:
XS GIS Cut Line= 3
      2752126.01      6919361.00      2752326.00      6919411.00
      2752626.02      6919361.00
#Sta/Elev= 30
  4788.8  499.07  4819.7  497.15  4830.0  497.05  4848.1  495.64  4863.9  495.87
  4871.2  495.49  4881.6  494.02  4889.3  493.36  4894.4  493.46  4922.8  492.12
  4943.4  490.43  4953.7  490.59  4964.0  490.23  4971.7  488.98  4992.4  487.49
  4997.5  487.49  5003.1  485.30  5003.3  484.80  5006.8  484.80  5007.1  485.30
  5022.8  488.33  5027.9  488.08  5035.5  489.38  5055.8  490.96  5065.9  491.43
  5083.6  491.40  5116.6  492.32  5136.9  492.71  5228.1  496.01  5299.1  497.89
#Mann=5,-1,0
  4788.8    0.05       0  4863.9    0.12       0  5003.1    0.07       0
  5007.1    0.12       0  5116.6    0.05       0
Bank Sta=5003.1,5007.1
Exp/Cntr=0.3,0.1

Type RM Length L Ch R = 1,742,229,229,229
BEGIN DESCRIPTION:
Mapping XS db70c72a
END DESCRIPTION:
XS GIS Cut Line= 3
      2752050.11      6919548.15      2752326.12      6919652.31
      2752846.96      6919626.27
#Sta/Elev= 30
  4705.1  500.22  4743.5  498.50  4757.6  497.37  4782.4  496.04  4812.6  494.89
  4818.3  494.15  4829.0  493.59  4882.4  491.98  4892.5  491.76  4897.9  492.01
  4903.1  491.13  4922.7  489.72  4967.9  488.75  4977.7  488.16  4983.1  487.67
  4995.4  484.25  4995.6  483.75  4999.1  483.75  4999.4  484.25  5010.0  484.66
  5020.0  486.54  5030.0  486.68  5040.0  487.91  5055.1  488.85  5200.2  492.66
  5240.3  494.10  5250.3  494.94  5280.3  495.89  5390.5  498.15  5521.6  501.70
#Mann=5,-1,0
  4705.1    0.05       0  4903.1    0.12       0  4995.4    0.07       0
  4999.4    0.12       0  5055.1    0.05       0
Bank Sta=4995.4,4999.4
Exp/Cntr=0.3,0.1

Type RM Length L Ch R = 1,513,329,329,329
BEGIN DESCRIPTION:
Mapping XS c57b4f43
END DESCRIPTION:
XS GIS Cut Line= 3
      2752037.06      6919722.62      2752271.44      6919865.85
      2752701.05      6919863.25
#Sta/Elev= 30
  4718.1  497.79  4739.1  496.82  4745.0  496.76  4752.0  496.15  4775.5  495.27
  4781.7  494.75  4810.6  493.44  4818.5  492.86  4897.8  489.87  4934.6  487.83
  4955.9  487.57  4963.0  486.54  4986.4  485.73  4990.5  482.01  4990.8  481.51
  4994.3  481.51  4994.5  482.01  5007.3  482.41  5017.3  485.20  5037.3  485.73
  5057.3  486.85  5107.3  487.18  5127.3  487.59  5167.3  489.15  5267.4  491.77
  5317.4  492.75  5377.4  494.34  5387.4  494.78  5417.4  495.48  5422.4  496.02
#Mann=3,-1,0
  4718.1    0.05       0  4990.5    0.04       0  4994.5    0.05       0
Bank Sta=4990.5,4994.5
Exp/Cntr=0.3,0.1

Type RM Length L Ch R = 1,184,0,0,0
BEGIN DESCRIPTION:
Flat T8_2 1.0
END DESCRIPTION:
XS GIS Cut Line= 3
      2751966.71      6919943.94      2752276.30      6920194.06
      2752652.58      6920100.64
#Sta/Elev= 30
  4602.0  496.32  4649.5  493.92  4731.5  490.62  4777.5  488.37  4819.6  487.75
  4847.9  486.11  4883.9  484.68  4919.8  484.01  4926.2  484.24  4934.2  483.79
  4942.6  483.95  4948.2  483.82  4955.0  482.77  4961.4  483.21  4969.4  480.03
  4975.8  480.64  4981.8  478.55  4982.0  478.05  4985.5  478.05  4985.8  478.55
  4990.2  478.63  4996.6  481.06  5002.4  481.06  5010.0  482.32  5034.6  481.71
  5051.2  482.03  5092.4  484.22  5174.9  485.38  5329.4  491.03  5387.7  492.01
#Mann=5,-1,0
  4602.0    0.05       0  4731.5    0.12       0  4942.6    0.05       0
  4981.8    0.04       0  4985.8    0.05       0
Bank Sta=4981.8,4985.8
Exp/Cntr=0.3,0.1

Chan Stop Cuts=-1