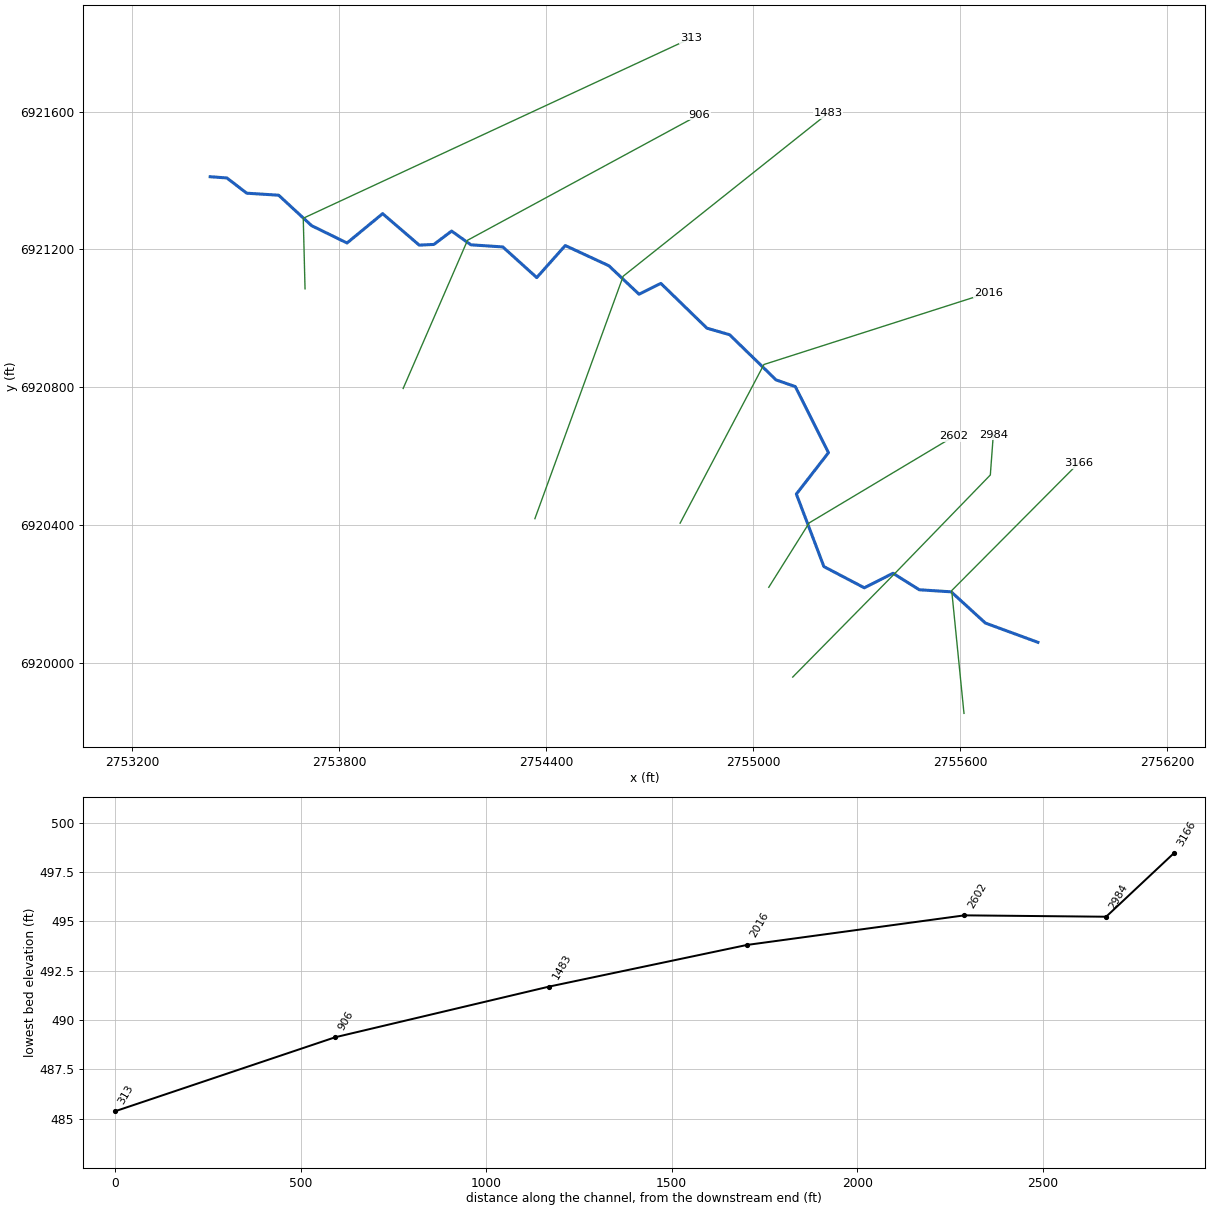
--- Flat T8_3.prj (project) ---

Proj Title=Flat T8_3 Base Level Engineering
Current Plan=p01
Default Exp/Contr=0.3,0.1
English Units
Geom File=g01
Flow File=f01
Plan File=p01
Y Axis Title=Elevation
X Axis Title(PF)=Main Channel Distance
X Axis Title(XS)=Station
BEGIN DESCRIPTION:
Flat T8_3
END DESCRIPTION:
DSS Export Rating Curves= 0
DSS Export Rating Curve Sorted= 0
DSS Export Volume Flow Curves= 0
DXF OffsetX= 0
DXF OffsetY= 0
DXF ScaleX= 1
DXF ScaleY= 10

--- Flat T8_3.p01 (plan) ---

Plan Title=Multiple Run
Short Identifier=Multiple
Geom File=g01
Flow File=f01
Subcritical Flow
K Sum by GR= 0
Std Step Tol= 0.01
Critical Tol= 0.01
Num of Std Step Trials= 20
Max Error Tol= 0.3
Flow Tol Ratio= 0.001
Split Flow NTrial= 30
Split Flow Tol= 0.02
Split Flow Ratio= 0.02
Log Output Level= 0
Friction Slope Method= 1
Unsteady Friction Slope Method= 2
Unsteady Bridges Friction Slope Method= 1
Parabolic Critical Depth
Global Vel Dist=  1 , 1 , 1
Global Log Level= 0
CheckData=True
Encroach Param= -1, 0, 0, 0
BEGIN DESCRIPTION:
Multiple Run
END DESCRIPTION:

--- Flat T8_3.f01 (steady flow) ---

Flow Title=Multiple
Program Version=4.10
Number of Profiles= 7
Profile Names=10-year,25-year,50-year,1pct_min,100-year,1pct_plu,500-year
River Rch & RM=Flat T8_3,Reach-1         ,3166
     256     323     375     217     433     864     576
Boundary for River Rch & Prof#=Flat T8_3,Reach-1         , 1
Up Type= 0
Dn Type= 3
Dn Slope=0.0065
Boundary for River Rch & Prof#=Flat T8_3,Reach-1         , 2
Up Type= 0
Dn Type= 3
Dn Slope=0.0065
Boundary for River Rch & Prof#=Flat T8_3,Reach-1         , 3
Up Type= 0
Dn Type= 3
Dn Slope=0.0065
Boundary for River Rch & Prof#=Flat T8_3,Reach-1         , 4
Up Type= 0
Dn Type= 3
Dn Slope=0.0065
Boundary for River Rch & Prof#=Flat T8_3,Reach-1         , 5
Up Type= 0
Dn Type= 3
Dn Slope=0.0065
Boundary for River Rch & Prof#=Flat T8_3,Reach-1         , 6
Up Type= 0
Dn Type= 3
Dn Slope=0.0065
Boundary for River Rch & Prof#=Flat T8_3,Reach-1         , 7
Up Type= 0
Dn Type= 3
Dn Slope=0.0065
DSS Import GetInterval= 0
DSS Import GetPeak= 0
DSS Import FillOption= 0

--- Flat T8_3.g01 (geometry) ---

Geom Title=Existing Conditions
Program Version=4.10

River Reach=Flat T8_3       ,Reach-1
Reach XY= 30
        2755826.        6920061.       2755673.7      6920116.83
       2755574.5      6920207.38      2755481.97      6920213.38
      2755405.79      6920261.21      2755322.69      6920219.07
      2755205.43      6920280.58      2755125.61      6920490.87
       2755218.7      6920610.92      2755122.49      6920802.52
      2755066.59      6920821.89      2754932.05      6920952.84
      2754866.32      6920971.78      2754732.67       6921101.7
      2754669.34      6921070.32      2754582.05      6921152.83
      2754455.54      6921211.46      2754372.85      6921118.55
       2754274.5      6921207.37       2754181.9      6921213.55
      2754125.99      6921253.41      2754074.35      6921214.58
      2754032.05      6921212.67        2753926.      6921303.89
      2753822.77      6921218.85      2753719.96      6921269.14
       2753624.5      6921357.38      2753531.92      6921363.23
      2753474.49      6921407.36        2753426.        6921411.

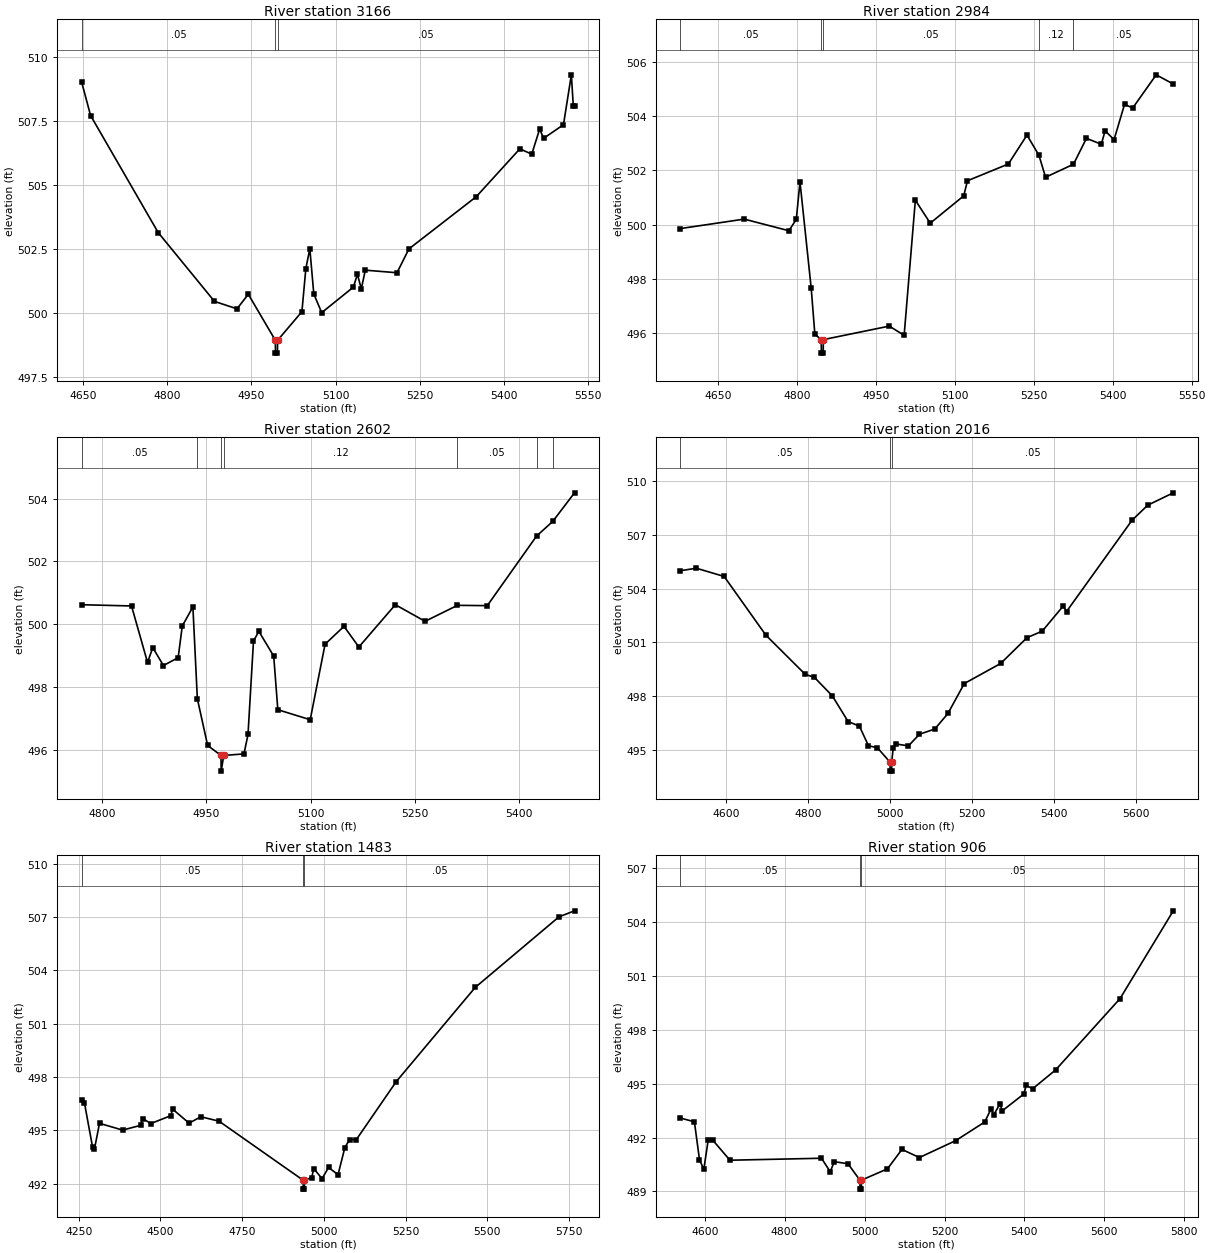
Type RM Length L Ch R = 1 ,3166    ,182,182,182
BEGIN DESCRIPTION:
Flat T8_3 6.0
END DESCRIPTION:
XS GIS Cut Line= 3
       2755611.6      6919854.97        2755576.        6920211.
      2755944.05      6920580.88
#Sta/Elev= 30
  4646.8  509.05  4662.9  507.73  4783.5  503.16    4884  500.47  4924.2  500.18
  4944.3  500.75  4992.6  498.95  4992.8  498.45  4996.3  498.45  4996.6  498.95
    5040  500.07    5047  501.75  5054.1  502.53  5061.2  500.76  5075.3  500.03
  5131.9  501.03    5139  501.53    5146  500.96  5153.1  501.69  5209.7  501.59
  5230.9  502.52  5351.1  504.56  5428.9  506.43  5450.1  506.22  5464.2   507.2
  5471.3  506.84  5506.7  507.37  5520.8  509.32  5524.2  508.12  5526.4  508.12
#Mann= 3 ,-1 , 0
  4646.8     .05       0  4992.6     .04       0  4996.6     .05       0
Bank Sta=4992.6,4996.6
XS Rating Curve= 0 ,0
Exp/Cntr=0.3,0.1

Type RM Length L Ch R = 1 ,2984    ,382,382,382
BEGIN DESCRIPTION:
Mapping XS 749c4bde
END DESCRIPTION:
XS GIS Cut Line= 4
      2755115.09      6919960.25      2755410.21      6920259.72
      2755687.99      6920546.17      2755696.67      6920663.38
#Sta/Elev= 30
  4578.1  499.85  4699.5   500.2  4784.4  499.77  4798.5  500.19  4805.5  501.58
  4826.8  497.65  4833.8  495.94  4845.9  495.74  4846.2  495.24  4849.7  495.24
  4849.9  495.74  4975.2  496.24  5003.5   495.9  5024.8   500.9  5053.1  500.05
  5116.7  501.06  5123.9  501.62  5201.6  502.24    5237  503.31  5259.8  502.56
  5272.3  501.75  5325.4  502.23    5350  503.19  5378.3  502.97  5385.5  503.47
  5402.5  503.14  5422.5  504.45  5437.9  504.31  5482.6  505.54  5515.1   505.2
#Mann= 5 ,-1 , 0
  4578.1     .05       0  4845.9     .04       0  4849.9     .05       0
  5259.8     .12       0  5325.4     .05       0
Bank Sta=4845.9,4849.9
XS Rating Curve= 0 ,0
Exp/Cntr=0.3,0.1

Type RM Length L Ch R = 1 ,2602    ,586,586,586
BEGIN DESCRIPTION:
Mapping XS 87ee051a
END DESCRIPTION:
XS GIS Cut Line= 3
      2755045.61      6920220.62      2755162.81      6920407.29
      2755582.41      6920658.18
#Sta/Elev= 30
  4770.3  500.62  4842.2  500.58  4865.2  498.78  4872.8  499.25  4888.1  498.68
  4909.3  498.93  4915.2  499.94  4930.5  500.55  4936.9  497.62  4951.7  496.13
  4970.9  495.81  4971.2  495.31  4974.9  495.81    5004  495.86  5009.8  496.48
  5017.7  499.46  5025.4  499.77  5046.8  498.98  5052.7  497.27  5099.3  496.95
  5120.7  499.36  5147.9  499.93  5169.3  499.27  5221.8  500.62  5264.6  500.09
  5311.2   500.6  5354.1  500.59    5425  502.81  5448.4  503.28  5479.6  504.19
#Mann= 7 ,-1 , 0
  4770.3     .05       0  4936.9     .12       0  4970.9     .07       0
  4974.9     .12       0  5311.2     .05       0    5425     .12       0
  5448.4     .05       0
Bank Sta=4970.9,4974.9
XS Rating Curve= 0 ,0
Exp/Cntr=0.3,0.1

Type RM Length L Ch R = 1 ,2016    ,533,533,533
BEGIN DESCRIPTION:
Mapping XS 39f7d894
END DESCRIPTION:
XS GIS Cut Line= 3
      2754788.47      6920406.42      2755031.52      6920866.49
      2755681.82      6921074.58
#Sta/Elev= 30
    4488     505  4527.1  505.14  4594.9  504.68  4696.8   501.4    4793  499.21
    4815  499.05    4859  498.01  4897.4  496.58  4925.1  496.32  4947.1  495.23
  4969.1  495.11  4999.8  494.31  5000.1  493.81  5003.6  493.81  5003.8  494.31
  5007.5   495.1  5013.3  495.33  5044.7  495.22  5071.6  495.87    5109  496.16
  5141.1  497.03    5181   498.7  5269.7  499.82    5334  501.26  5371.4  501.63
  5422.5  503.03  5430.5  502.72  5590.5  507.82  5628.7  508.66  5691.1  509.35
#Mann= 3 ,-1 , 0
    4488     .05       0  4999.8     .04       0  5003.8     .05       0
Bank Sta=4999.8,5003.8
XS Rating Curve= 0 ,0
Exp/Cntr=0.3,0.1

Type RM Length L Ch R = 1 ,1483    ,577,577,577
BEGIN DESCRIPTION:
Mapping XS 83a86192
END DESCRIPTION:
XS GIS Cut Line= 3
      2754367.46      6920419.45      2754623.53      6921122.56
      2755218.19      6921595.68
#Sta/Elev= 30
  4258.8  496.73  4267.5  496.56  4292.4  494.07    4298  493.93  4313.7   495.4
  4384.4  495.02  4440.3  495.29  4445.6  495.67  4470.8  495.39    4532  495.83
  4537.3   496.2  4587.8  495.41  4623.7  495.77  4679.5  495.52  4936.8   492.2
    4937   491.7  4940.5   491.7  4940.8   492.2  4962.9  492.35  4969.3  492.85
  4994.6  492.29  5014.6  492.92  5043.5  492.51  5064.3  494.03  5078.7  494.49
  5099.7  494.49  5221.3  497.74  5463.1  503.04  5719.4  507.01    5767  507.35
#Mann= 3 ,-1 , 0
  4258.8     .05       0  4936.8     .04       0  4940.8     .05       0
Bank Sta=4936.8,4940.8
XS Rating Curve= 0 ,0
Exp/Cntr=0.3,0.1

Type RM Length L Ch R = 1 ,906     ,593,593,593
BEGIN DESCRIPTION:
Mapping XS 6fbd6713
END DESCRIPTION:
XS GIS Cut Line= 3
      2753985.52      6920797.05      2754172.15      6921226.73
      2754844.85      6921591.29
#Sta/Elev= 30
  4538.9  493.09  4574.1  492.88  4586.8  490.77  4597.6  490.23  4608.6  491.86
  4619.5  491.87  4663.1  490.74  4892.1  490.85  4913.9   490.1  4924.3  490.66
  4958.6  490.54  4988.2  489.63  4988.5  489.13    4992  489.13  4992.2  489.63
  5057.2  490.26  5093.4  491.34  5137.2  490.89  5227.9  491.83  5300.7  492.87
  5316.9  493.62  5322.6  493.25  5338.8  493.87  5344.5  493.49  5398.5  494.43
  5404.4  494.91  5420.6  494.72  5478.1  495.77  5639.2  499.74  5772.5  504.63
#Mann= 3 ,-1 , 0
  4538.9     .05       0  4988.2     .03       0  4992.2     .05       0
Bank Sta=4988.2,4992.2
XS Rating Curve= 0 ,0
Exp/Cntr=0.3,0.1

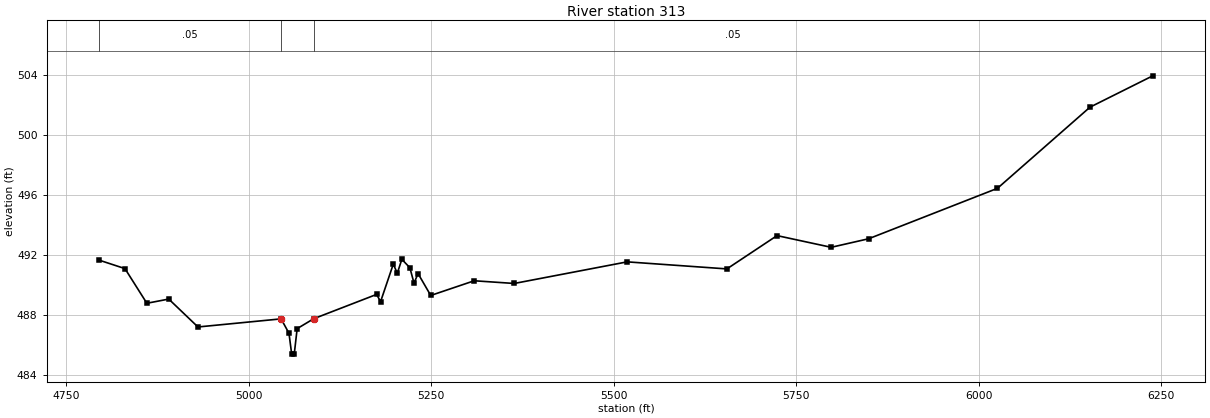
Type RM Length L Ch R = 1 ,313     ,0,0,0
BEGIN DESCRIPTION:
Flat T8_3 1.0
END DESCRIPTION:
XS GIS Cut Line= 3
        2753701.      6921085.95      2753695.84      6921290.57
      2754819.02      6921812.23
#Sta/Elev= 30
  4795.2  491.64  4830.3  491.08  4860.3  488.77  4890.3  489.05  4930.3  487.19
  5044.2  487.73    5055  486.77  5058.7  485.38  5062.2  485.38  5066.2  487.08
  5088.9  487.74    5175  489.36  5180.5  488.88  5197.9  491.38  5203.4  490.77
  5209.6   491.7  5220.6  491.14  5226.3  490.11  5231.8  490.75  5249.2  489.29
  5308.8  490.27  5363.6  490.09  5518.3  491.53  5654.9  491.06  5723.6  493.28
  5797.8   492.5  5849.1  493.07  6025.5  496.43  6152.3  501.84  6238.3  503.93
#Mann= 3 ,-1 , 0
  4795.2     .05       0  5044.2     .03       0  5088.9     .05       0
Bank Sta=5044.2,5088.9
XS Rating Curve= 0 ,0
Exp/Cntr=0.3,0.1

Chan Stop Cuts=-1
Use User Specified Reach Order=0
Composite Channel Slope=5