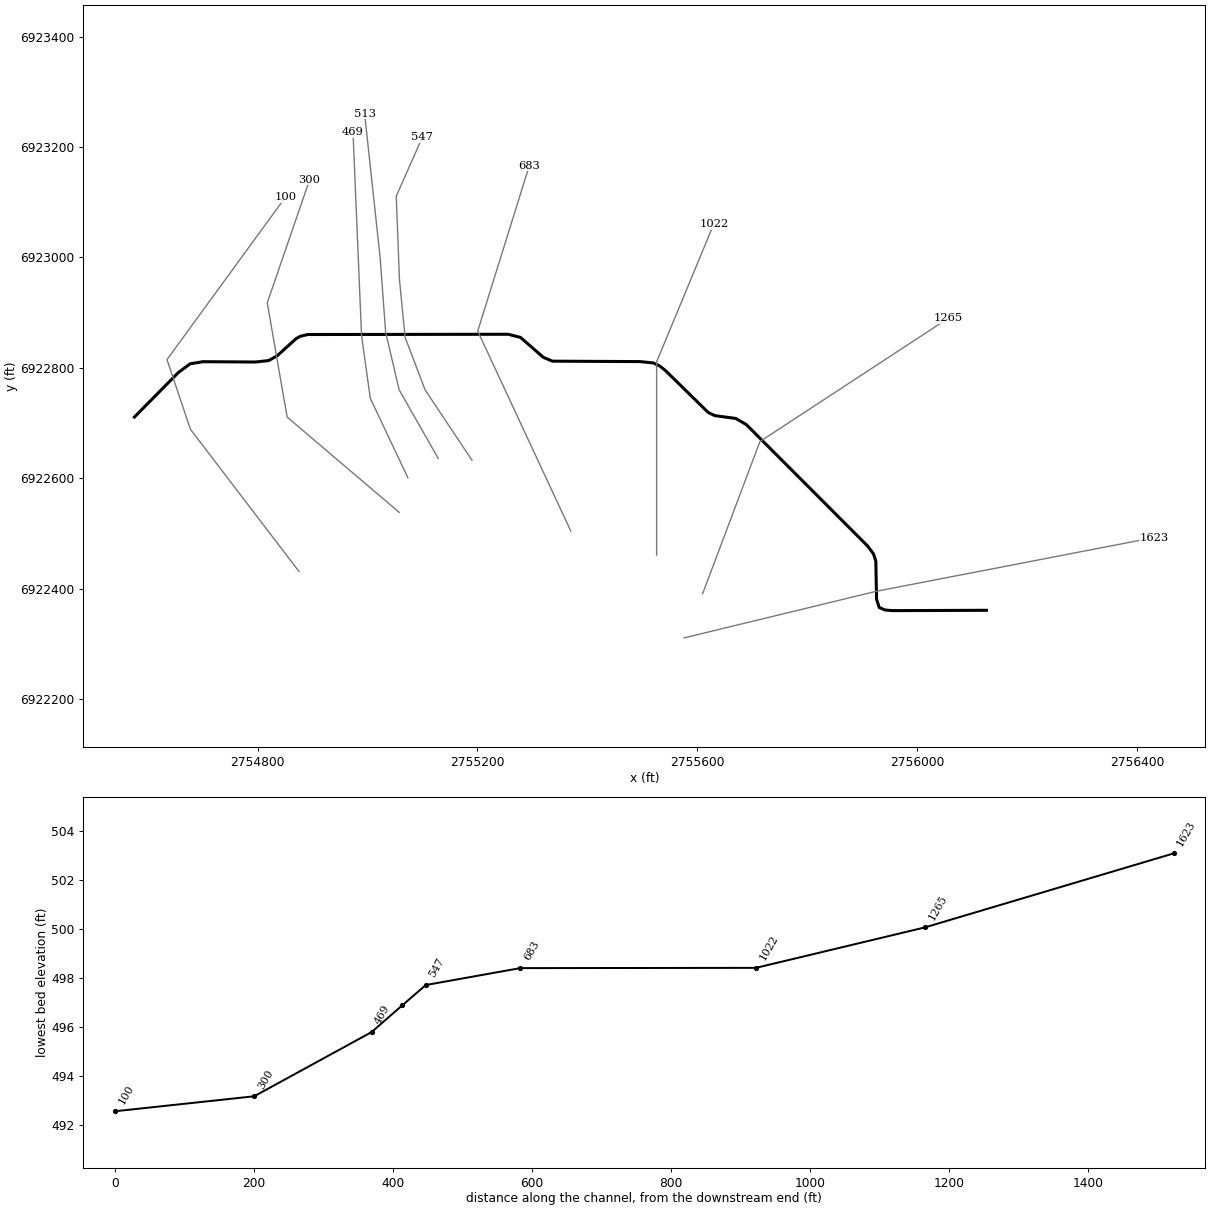
--- Flat T8_4.prj (project) ---

Proj Title=Flat T8_4 Base Level Engineering
Current Plan=p01
Default Exp/Contr=0.3,0.1
English Units
Geom File=g01
Flow File=f01
Plan File=p01
Y Axis Title=Elevation
X Axis Title(PF)=Main Channel Distance
X Axis Title(XS)=Station
BEGIN DESCRIPTION:
Flat T8_4
END DESCRIPTION:
DSS Export Rating Curves= 0
DSS Export Rating Curve Sorted= 0
DSS Export Volume Flow Curves= 0
DXF OffsetX= 0
DXF OffsetY= 0
DXF ScaleX= 1
DXF ScaleY= 10

--- Flat T8_4.p01 (plan) ---

Plan Title=Multiple Run
Short Identifier=Multiple
Geom File=g01
Flow File=f01
Subcritical Flow
K Sum by GR= 0
Std Step Tol= 0.01
Critical Tol= 0.01
Num of Std Step Trials= 20
Max Error Tol= 0.3
Flow Tol Ratio= 0.001
Split Flow NTrial= 30
Split Flow Tol= 0.02
Split Flow Ratio= 0.02
Log Output Level= 0
Friction Slope Method= 1
Unsteady Friction Slope Method= 2
Unsteady Bridges Friction Slope Method= 1
Parabolic Critical Depth
Global Vel Dist=  1 , 1 , 1
Global Log Level= 0
CheckData=True
Encroach Param= -1, 0, 0, 0
BEGIN DESCRIPTION:
Multiple Run
END DESCRIPTION:

--- Flat T8_4.f01 (steady flow) ---

Flow Title=Multiple
Number of Profiles=7
Profile Names=10-year,25-year,50-year,1pct_min,100-year,1pct_plu,500-year
River Rch & RM= Flat T8_4,Reach-1,1623
     206     259     299     172     343     685     453
Boundary for River Rch & Prof#=Flat T8_4,Reach-1,1
Up Type=0
Dn Type=3
Dn Slope=0.005
Boundary for River Rch & Prof#=Flat T8_4,Reach-1,2
Up Type=0
Dn Type=3
Dn Slope=0.005
Boundary for River Rch & Prof#=Flat T8_4,Reach-1,3
Up Type=0
Dn Type=3
Dn Slope=0.005
Boundary for River Rch & Prof#=Flat T8_4,Reach-1,4
Up Type=0
Dn Type=3
Dn Slope=0.005
Boundary for River Rch & Prof#=Flat T8_4,Reach-1,5
Up Type=0
Dn Type=3
Dn Slope=0.005
Boundary for River Rch & Prof#=Flat T8_4,Reach-1,6
Up Type=0
Dn Type=3
Dn Slope=0.005
Boundary for River Rch & Prof#=Flat T8_4,Reach-1,7
Up Type=0
Dn Type=3
Dn Slope=0.005

--- Flat T8_4.g01 (geometry) ---

Geom Title=Existing Conditions
Program Version=4.10

River Reach=Flat T8_4       ,Reach-1
Reach XY= 30
        2756126.        6922361.      2755955.39      6922360.38
      2755941.56      6922361.54      2755931.07      6922366.02
      2755926.11      6922381.01      2755924.78       6922450.4
      2755920.45      6922463.36      2755909.53      6922477.73
      2755689.21      6922697.37      2755669.95      6922708.47
      2755632.05      6922713.54      2755619.96      6922719.18
      2755542.75      6922794.54      2755532.19      6922803.17
      2755520.14      6922808.93      2755496.18      6922811.43
      2755336.51      6922812.22      2755319.94      6922819.14
      2755278.33      6922855.25      2755255.97      6922860.93
      2754891.22      6922860.48      2754877.57      6922857.22
      2754869.94      6922852.86      2754835.64      6922821.86
      2754820.06      6922813.27      2754796.13      6922810.68
      2754700.89      6922811.27      2754677.45      6922807.51
      2754655.79       6922791.5        2754576.        6922711.

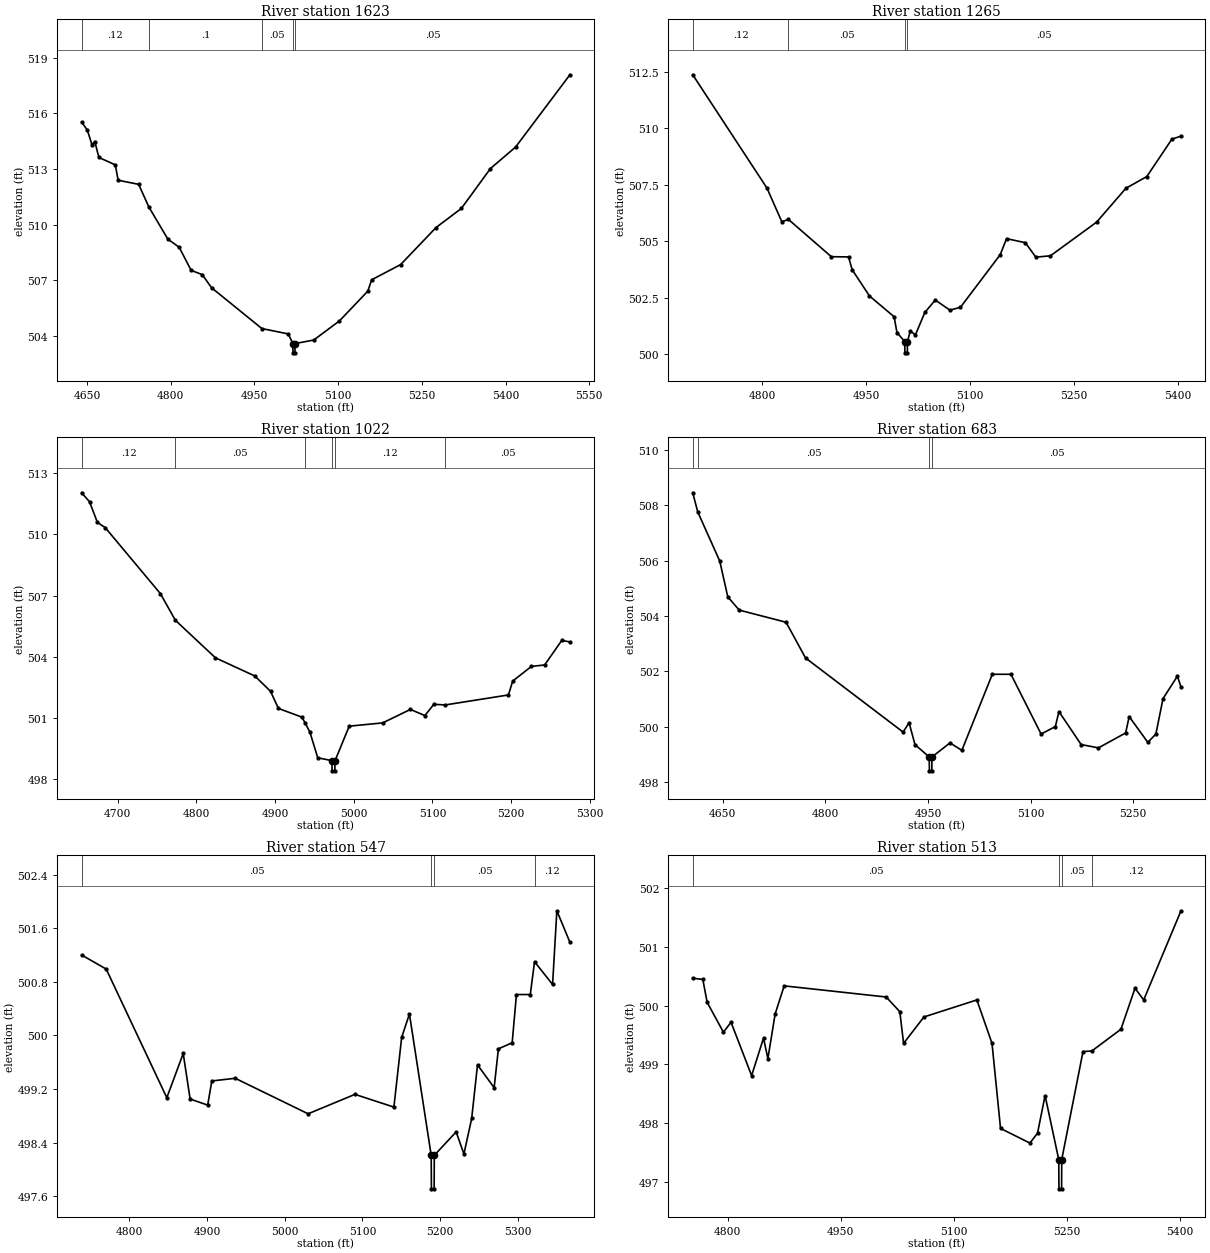
Type RM Length L Ch R = 1 ,1623    ,358,358,358
BEGIN DESCRIPTION:
Flat T8_4 3.0
END DESCRIPTION:
XS GIS Cut Line= 3
      2755575.95      6922310.99       2755925.6      6922395.43
      2756431.61      6922492.82
#Sta/Elev= 30
  4640.3  515.53  4650.6  515.09  4658.7  514.31  4663.9  514.48  4671.2  513.62
  4700.6  513.22  4705.7  512.39  4742.5  512.17  4760.7  510.95  4794.7  509.22
  4815.2  508.77  4836.5  507.53  4856.4   507.3  4873.2  506.59  4963.3  504.39
  5010.6   504.1  5018.8  503.58    5019  503.08  5022.5  503.08  5022.8  503.58
  5056.2  503.77  5102.2   504.8  5153.2  506.41    5160  507.02  5211.9  507.84
  5275.4  509.84  5320.8  510.87  5372.8  513.02  5417.9  514.18  5515.3  518.08
#Mann= 5 ,-1 , 0
  4640.3     .12       0  4760.7      .1       0  4963.3     .05       0
  5018.8     .04       0  5022.8     .05       0
Bank Sta=5018.8,5022.8
XS Rating Curve= 0 ,0
Exp/Cntr=0.3,0.1

Type RM Length L Ch R = 1 ,1265    ,243,243,243
BEGIN DESCRIPTION:
Mapping XS 5688cc59
END DESCRIPTION:
XS GIS Cut Line= 3
       2755609.7      6922390.93      2755713.86      6922666.54
      2756056.71      6922890.04
#Sta/Elev= 30
  4700.3  512.38  4807.3  507.36  4828.7  505.87  4838.3  505.97  4900.1  504.32
  4924.9  504.31  4930.2  503.74  4955.1  502.58  4990.6  501.66  4994.7  500.96
  5005.9  500.56  5006.1  500.06  5009.6  500.06  5009.9  500.56  5013.8  501.02
  5021.4  500.86  5034.9  501.85    5050   502.4  5071.1  501.95  5086.3  502.08
  5143.6  504.41  5152.7  505.12  5179.8  504.94  5194.9   504.3    5216  504.36
  5282.5  505.85  5324.7  507.35  5354.9  507.87  5391.1  509.53  5404.2  509.66
#Mann= 4 ,-1 , 0
  4700.3     .12       0  4838.3     .05       0  5005.9     .04       0
  5009.9     .05       0
Bank Sta=5005.9,5009.9
XS Rating Curve= 0 ,0
Exp/Cntr=0.3,0.1

Type RM Length L Ch R = 1 ,1022    ,339,339,339
BEGIN DESCRIPTION:
Flat T8_4 2.0
END DESCRIPTION:
XS GIS Cut Line= 3
        2755526.      6922461.03        2755526.        6922811.
      2755630.01      6923060.63
#Sta/Elev= 30
  4654.3  512.04  4664.3   511.6  4674.3  510.59  4684.3  510.33  4754.3   507.1
  4773.4  505.79  4824.3  503.95  4874.3  503.06  4894.3  502.31  4904.3  501.47
  4934.3  501.04  4938.2  500.76  4944.3  500.31  4954.3  499.05  4972.3  498.91
  4972.5  498.41    4976  498.41  4976.3  498.91  4994.3   500.6  5036.8  500.76
    5072  501.42  5090.4  501.12  5101.8  501.67  5116.3  501.64  5196.6  502.13
    5202  502.81  5225.8  503.53  5242.6   503.6  5264.3   504.8  5274.7  504.73
#Mann= 6 ,-1 , 0
  4654.3     .12       0  4773.4     .05       0  4938.2     .12       0
  4972.3     .07       0  4976.3     .12       0  5116.3     .05       0
Bank Sta=4972.3,4976.3
XS Rating Curve= 0 ,0
Exp/Cntr=0.3,0.1

Type RM Length L Ch R = 1 ,683     ,136,136,136
BEGIN DESCRIPTION:
Mapping XS 43aae532
END DESCRIPTION:
XS GIS Cut Line= 3
      2755369.82      6922504.62      2755200.55      6922866.59
       2755294.3      6923166.07
#Sta/Elev= 30
  4606.3  508.45  4613.6  507.76  4645.8  505.98  4657.5  504.69  4674.2  504.21
  4742.7  503.77  4771.1  502.48  4913.7   499.8  4922.4  500.14    4931  499.35
  4951.8   498.9  4952.1   498.4  4955.6   498.4  4955.8   498.9  4982.2  499.41
  4999.5  499.14    5044  501.89  5071.2  501.89  5115.3  499.73  5136.1     500
  5141.4  500.54  5173.8  499.35  5199.1  499.23  5238.8  499.77    5244  500.36
  5271.2  499.43    5283  499.73  5293.4  501.01  5314.4  501.82  5319.7  501.43
#Mann= 4 ,-1 , 0
  4606.3     .12       0  4613.6     .05       0  4951.8     .04       0
  4955.8     .05       0
Bank Sta=4951.8,4955.8
XS Rating Curve= 0 ,0
Exp/Cntr=0.3,0.1

Type RM Length L Ch R = 1 ,547     ,34,34,34
BEGIN DESCRIPTION:
Mapping XS 82a5aaaf
END DESCRIPTION:
XS GIS Cut Line= 6
      2755190.34      6922632.44      2755104.79      6922760.26
       2755068.4      6922855.49      2755058.15      6922960.45
      2755052.29      6923110.97      2755099.65      6923217.35
#Sta/Elev= 30
  4738.7   501.2  4770.3  500.99  4848.3  499.07  4869.4  499.73  4878.3  499.05
  4900.9  498.96  4906.2  499.32  4936.3  499.36  5030.1  498.83  5090.4  499.12
  5140.5  498.93  5150.5  499.97  5160.5  500.32  5188.5  498.21  5188.8  497.71
  5192.3  497.71  5192.5  498.21  5220.6  498.56  5230.6  498.23  5240.6  498.76
  5248.1  499.56  5269.5  499.22    5275   499.8  5292.7  499.89  5298.2  500.61
    5316  500.61  5321.5   501.1  5344.7  500.76  5350.2  501.86    5367  501.39
#Mann= 4 ,-1 , 0
  4738.7     .05       0  5188.5     .05       0  5192.5     .05       0
  5321.5     .12       0
Bank Sta=5188.5,5192.5
XS Rating Curve= 0 ,0
Exp/Cntr=0.3,0.1

Type RM Length L Ch R = 1 ,513     ,44,44,44
BEGIN DESCRIPTION:
Mapping XS cf43bad9
END DESCRIPTION:
XS GIS Cut Line= 5
      2755128.67      6922636.19      2755057.52      6922760.41
        2755033.      6922865.02      2755023.15      6922998.56
      2754994.81      6923260.23
#Sta/Elev= 30
  4753.5  500.47  4766.9  500.45  4772.6  500.06  4794.2  499.55  4804.3  499.72
  4831.6  498.81  4847.4  499.45  4853.2   499.1  4862.8  499.86  4874.8  500.34
  5010.1  500.15  5028.2   499.9  5033.2  499.36  5060.2  499.81  5130.4   500.1
  5150.5  499.36  5161.8  497.91  5200.8  497.66  5210.9  497.83  5220.9  498.47
    5239  497.38  5239.3  496.88  5242.8  496.88    5243  497.38  5271.2  499.22
  5282.9  499.23  5321.5   499.6  5340.2   500.3  5351.7   500.1  5401.2  501.62
#Mann= 4 ,-1 , 0
  4753.5     .05       0    5239     .05       0    5243     .05       0
  5282.9     .12       0
Bank Sta=5239,5243
XS Rating Curve= 0 ,0
Exp/Cntr=0.3,0.1

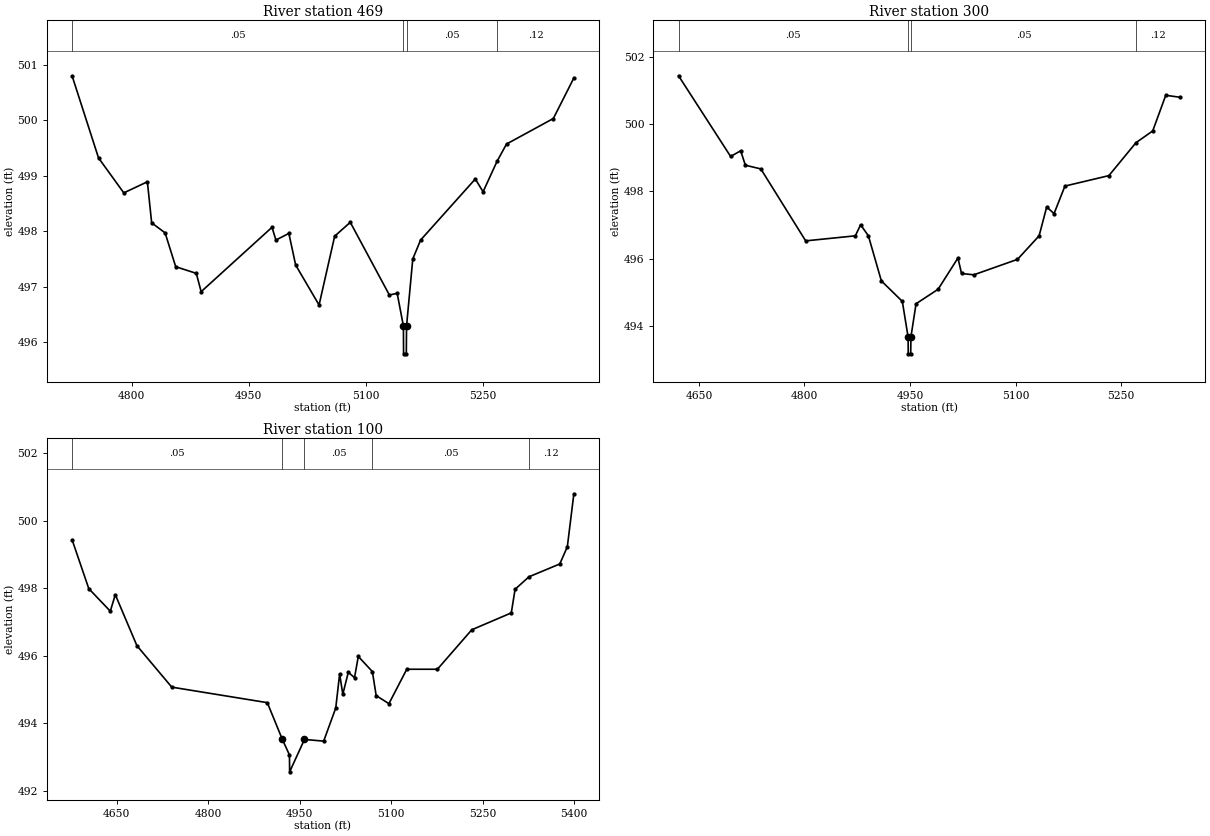
Type RM Length L Ch R = 1 ,469     ,169,169,169
BEGIN DESCRIPTION:
Mapping XS 12b4141a
END DESCRIPTION:
XS GIS Cut Line= 4
      2755073.47      6922601.08      2755005.15      6922744.85
      2754989.19      6922858.76      2754973.65      6923227.23
#Sta/Elev= 30
  4723.5   500.8  4757.4  499.32  4789.8  498.69    4820  498.89  4825.5  498.15
  4842.7  497.97  4856.3  497.36  4882.7  497.24  4888.9  496.91  4979.7  498.07
  4984.7  497.84  5001.3  497.96    5010  497.39    5040  496.67    5060  497.91
    5080  498.16  5130.1  496.85  5140.1  496.88  5148.1  496.29  5148.3  495.79
  5151.8  495.79  5152.1  496.29  5160.1   497.5  5170.1  497.84  5240.2  498.94
  5250.2  498.71  5268.1  499.26  5280.2  499.57  5340.2  500.03  5366.5  500.76
#Mann= 4 ,-1 , 0
  4723.5     .05       0  5148.1     .05       0  5152.1     .05       0
  5268.1     .12       0
Bank Sta=5148.1,5152.1
XS Rating Curve= 0 ,0
Exp/Cntr=0.3,0.1

Type RM Length L Ch R = 1 ,300     ,200,200,200
BEGIN DESCRIPTION:
Mapping XS 2430b835
END DESCRIPTION:
XS GIS Cut Line= 4
      2755057.74      6922538.38      2754853.84      6922710.97
      2754817.67      6922917.91      2754894.67      6923140.56
#Sta/Elev= 30
  4621.1  501.44  4695.1  499.04  4709.4  499.21    4716  498.78    4738  498.67
  4801.7  496.53  4872.3  496.68  4879.7  497.01  4890.8  496.68  4909.2  495.34
    4939  494.73  4947.2  493.67  4947.4  493.17  4950.9  493.17  4951.2  493.67
  4958.5  494.66  4989.8  495.09    5018  496.02  5023.1  495.56  5040.5  495.52
  5102.6  495.98  5133.3  496.68  5144.1  497.54  5154.5  497.34    5170  498.16
  5232.4  498.47  5270.9  499.45  5294.7   499.8  5313.2  500.86  5333.9   500.8
#Mann= 4 ,-1 , 0
  4621.1     .05       0  4947.2     .04       0  4951.2     .05       0
  5270.9     .12       0
Bank Sta=4947.2,4951.2
XS Rating Curve= 0 ,0
Exp/Cntr=0.3,0.1

Type RM Length L Ch R = 1 ,100     ,0,0,0
BEGIN DESCRIPTION:
Flat T8_4 1.0
END DESCRIPTION:
XS GIS Cut Line= 4
      2754875.38      6922431.28      2754677.89      6922688.83
      2754635.26      6922815.08        2754851.      6923109.61
#Sta/Elev= 30
  4576.9  499.44  4604.3  497.99  4639.6  497.32  4647.8  497.81  4683.2   496.3
  4740.4  495.07  4897.1  494.61  4921.3  493.54  4933.4  493.06  4933.7  492.56
    4958  493.52  4989.5  493.47  5009.3  494.45  5015.7  495.46  5020.9  494.86
  5029.9  495.51  5040.1  495.35  5046.3  495.98  5069.4  495.53  5075.6  494.82
  5096.5  494.58  5125.8   495.6    5176   495.6  5232.4  496.77  5297.2  497.27
  5303.4  497.97  5326.2  498.34  5376.7  498.72  5389.1  499.23  5399.8   500.8
#Mann= 5 ,-1 , 0
  4576.9     .05       0  4921.3     .04       0    4958     .05       0
  5069.4     .05       0  5326.2     .12       0
Bank Sta=4921.3,4958
XS Rating Curve= 0 ,0
Exp/Cntr=0.3,0.1

Chan Stop Cuts=-1
Use User Specified Reach Order=0
Composite Channel Slope=5