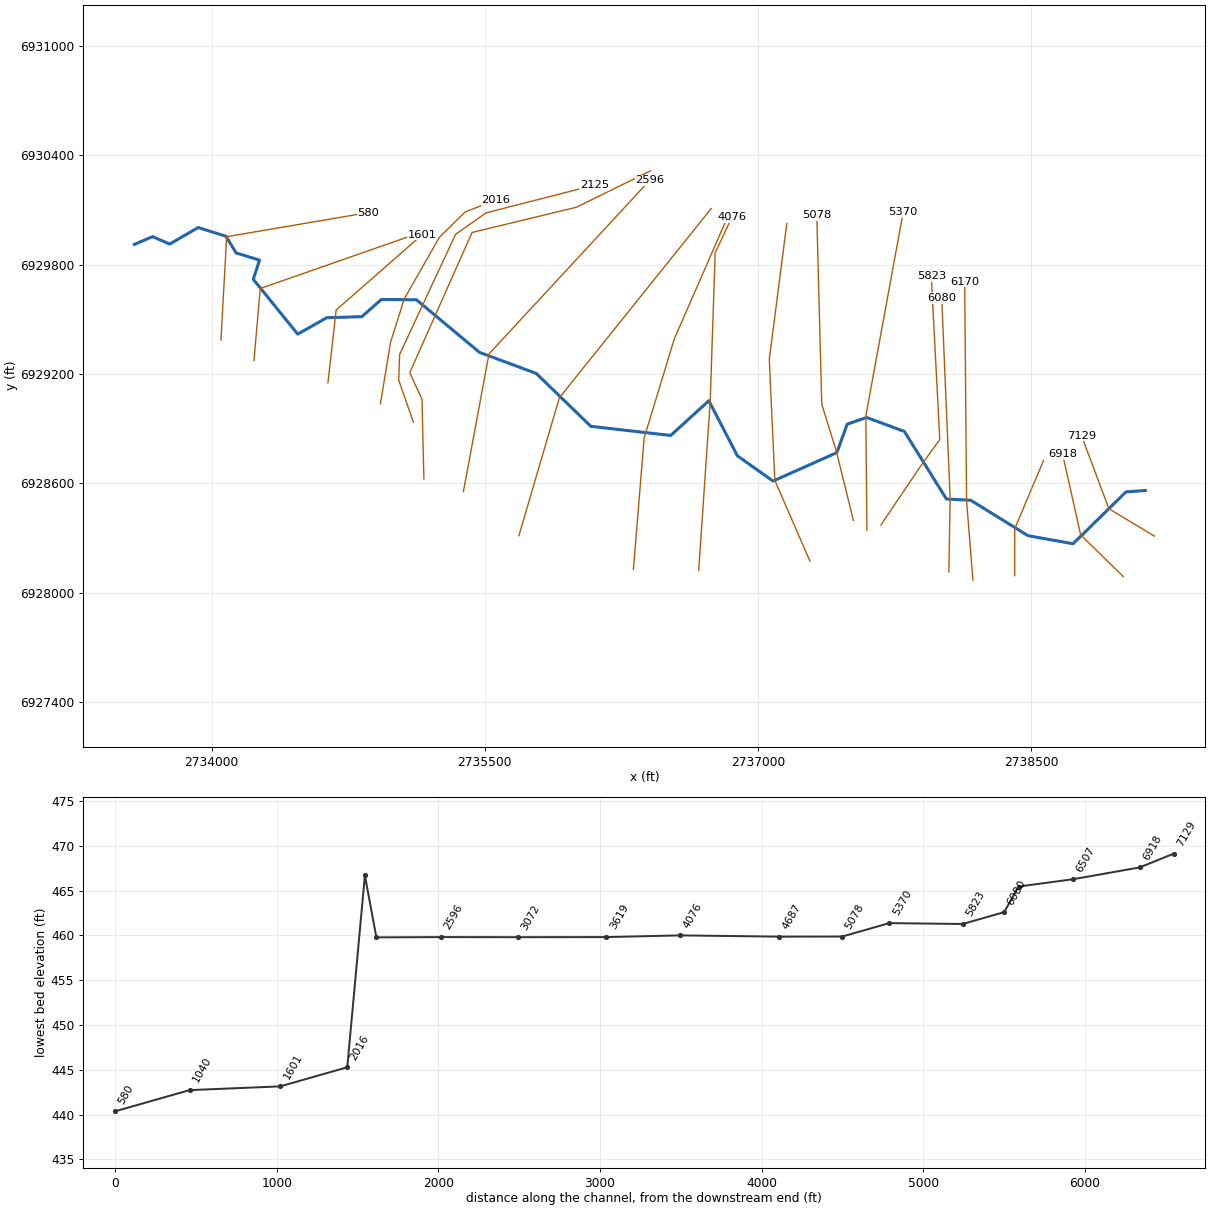
--- Graveyard Branch.prj (project) ---

Proj Title=Graveyard Branch Base Level Engineering
Current Plan=p01
Default Exp/Contr=0.3,0.1
English Units
Geom File=g01
Flow File=f01
Plan File=p01
Y Axis Title=Elevation
X Axis Title(PF)=Main Channel Distance
X Axis Title(XS)=Station
BEGIN DESCRIPTION:
Graveyard Branch
END DESCRIPTION:
DSS Export Rating Curves= 0
DSS Export Rating Curve Sorted= 0
DSS Export Volume Flow Curves= 0
DXF OffsetX= 0
DXF OffsetY= 0
DXF ScaleX= 1
DXF ScaleY= 10

--- Graveyard Branch.p01 (plan) ---

Plan Title=Multiple Run
Short Identifier=Multiple
Geom File=g01
Flow File=f01
Subcritical Flow
K Sum by GR= 0
Std Step Tol= 0.01
Critical Tol= 0.01
Num of Std Step Trials= 20
Max Error Tol= 0.3
Flow Tol Ratio= 0.001
Split Flow NTrial= 30
Split Flow Tol= 0.02
Split Flow Ratio= 0.02
Log Output Level= 0
Friction Slope Method= 1
Unsteady Friction Slope Method= 2
Unsteady Bridges Friction Slope Method= 1
Parabolic Critical Depth
Global Vel Dist=  1 , 1 , 1
Global Log Level= 0
CheckData=True
Encroach Param= -1, 0, 0, 0
BEGIN DESCRIPTION:
Multiple Run
END DESCRIPTION:

--- Graveyard Branch.f01 (steady flow) ---

Flow Title=Multiple
Number of Profiles=7
Profile Names=10-year,25-year,50-year,1pct_min,100-year,1pct_plu,500-year
River Rch & RM= Graveyard Branch,Reach-1,7129
     474     630     756     452     902    1799    1283
River Rch & RM= Graveyard Branch,Reach-1,4687
     723     972    1174     703    1403    2799    2001
River Rch & RM= Graveyard Branch,Reach-1,2016
     805    1091    1324     798    1592    3176    2296
Boundary for River Rch & Prof#=Graveyard Branch,Reach-1,1
Up Type=0
Dn Type=3
Dn Slope=0.005
Boundary for River Rch & Prof#=Graveyard Branch,Reach-1,2
Up Type=0
Dn Type=3
Dn Slope=0.005
Boundary for River Rch & Prof#=Graveyard Branch,Reach-1,3
Up Type=0
Dn Type=3
Dn Slope=0.005
Boundary for River Rch & Prof#=Graveyard Branch,Reach-1,4
Up Type=0
Dn Type=3
Dn Slope=0.005
Boundary for River Rch & Prof#=Graveyard Branch,Reach-1,5
Up Type=0
Dn Type=3
Dn Slope=0.005
Boundary for River Rch & Prof#=Graveyard Branch,Reach-1,6
Up Type=0
Dn Type=3
Dn Slope=0.005
Boundary for River Rch & Prof#=Graveyard Branch,Reach-1,7
Up Type=0
Dn Type=3
Dn Slope=0.005

--- Graveyard Branch.g01 (geometry) ---

Geom Title=Existing Conditions
Program Version=4.10

River Reach=Graveyard Branch,Reach-1
Reach XY= 30
        2739126.        6928561.      2739019.78      6928553.26
      2738729.42      6928268.79      2738481.94      6928313.26
      2738167.55      6928507.59      2738034.31      6928514.08
      2737803.19      6928884.95      2737596.03      6928961.61
      2737489.23      6928924.73       2737432.5      6928768.73
      2737082.11      6928612.79      2736886.51      6928751.19
      2736729.66      6929053.33      2736520.33      6928862.98
      2736081.86      6928913.07      2735782.17      6929203.14
      2735469.94      6929319.14      2735124.45      6929607.25
      2734931.86      6929608.94      2734824.53      6929514.55
      2734631.93      6929508.76      2734472.58      6929418.76
       2734228.7      6929719.51      2734262.62      6929824.78
      2734134.36      6929864.19      2734078.66      6929955.54
      2733925.99      6930003.47      2733769.88      6929912.84
      2733675.97      6929953.65        2733576.        6929911.

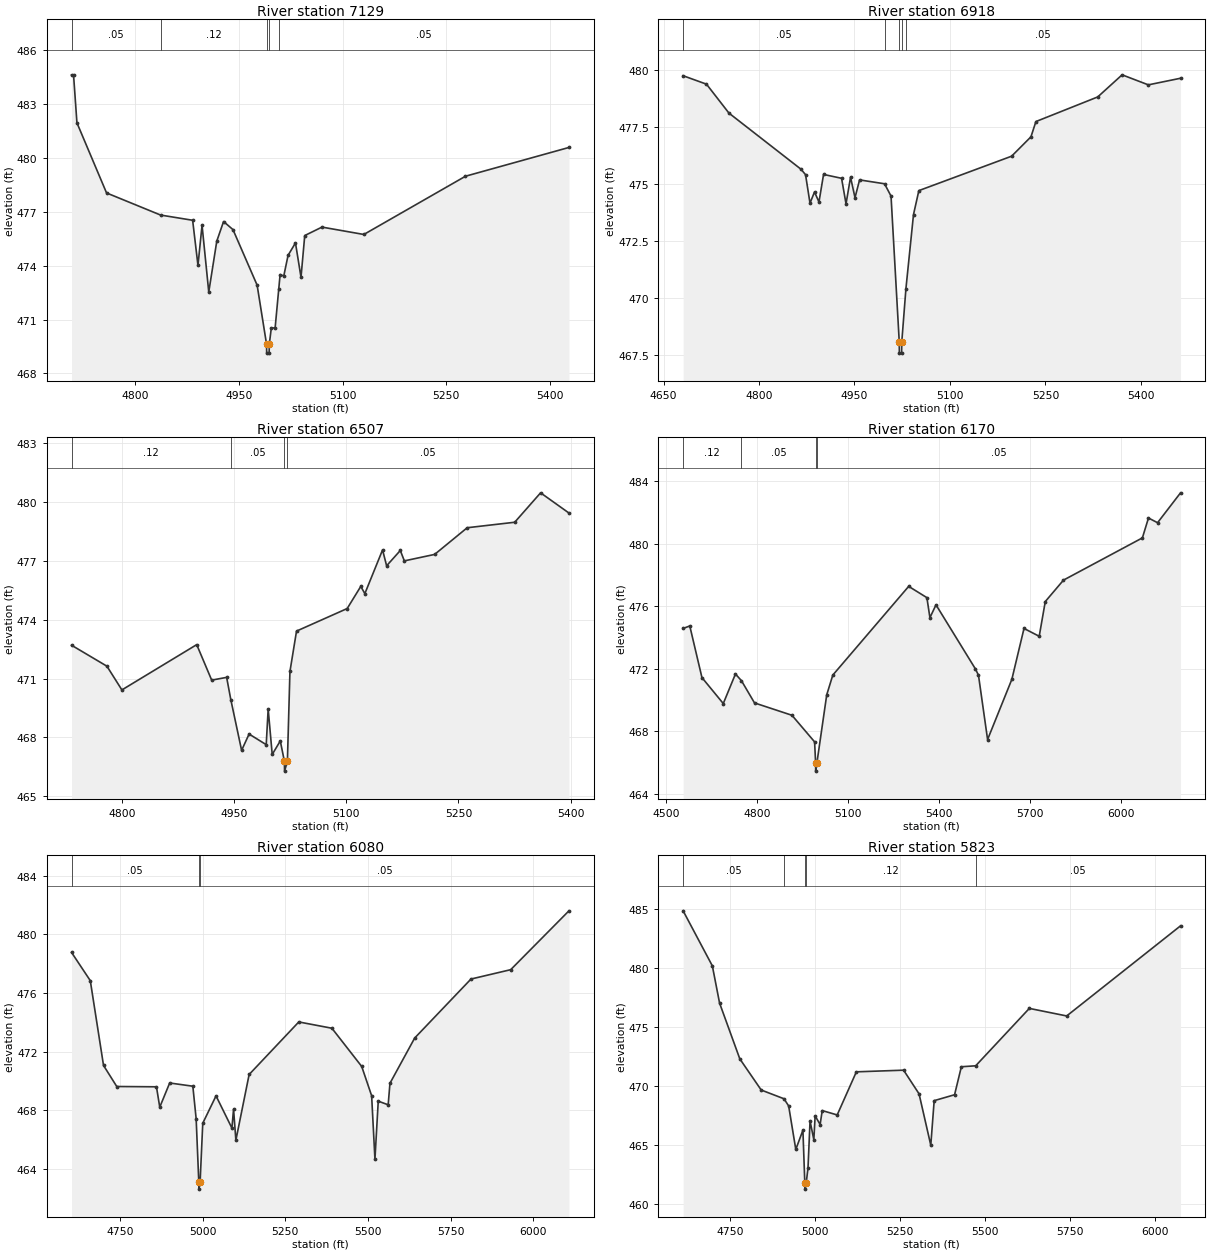
Type RM Length L Ch R = 1 ,7129    ,211,211,211
BEGIN DESCRIPTION:
Graveyard Branch 14.0
END DESCRIPTION:
XS GIS Cut Line= 3
      2739176.02      6928310.99        2738926.        6928461.
      2738775.99      6928861.03
#Sta/Elev= 30
  4708.4  484.61  4711.3  484.61  4716.2  481.94    4759  478.04  4837.1  476.81
  4883.4  476.52  4891.1  474.01    4897  476.24  4906.7  472.53  4918.3  475.36
  4928.1  476.45  4941.7     476  4976.6  472.91  4990.2  469.63  4990.4  469.13
  4993.9  469.13  4994.2  469.63  4997.1  470.53  5002.6  470.53  5007.9  472.72
  5009.8   473.5  5015.1  473.42  5021.3  474.57    5032  475.26    5040  473.35
  5045.4  475.67  5070.3  476.14  5130.8  475.73  5277.7  478.97  5427.2  480.57
#Mann= 5 ,-1 , 0
  4708.4     .05       0  4837.1     .12       0  4990.2     .07       0
  4994.2     .12       0  5007.9     .05       0
Bank Sta=4990.2,4994.2
XS Rating Curve= 0 ,0
Exp/Cntr=0.3,0.1

Type RM Length L Ch R = 1 ,6918    ,411,411,411
BEGIN DESCRIPTION:
Mapping XS f3efb5cf
END DESCRIPTION:
XS GIS Cut Line= 3
      2739005.36      6928088.49        2738771.      6928317.64
      2738672.04      6928760.35
#Sta/Elev= 30
  4680.8  479.76  4717.5  479.39  4752.8  478.12  4865.9  475.66  4873.1  475.42
  4880.1  474.17  4887.2  474.66  4894.2  474.22  4901.4  475.43  4929.7  475.26
  4936.7  474.14  4943.8  475.31  4950.8  474.41    4958  475.19  4997.2  475.02
  5007.4  474.48  5020.3  468.09  5020.5  467.59    5024  467.59  5024.3  468.09
  5030.8  470.42  5042.7  473.67  5051.1  474.72  5196.8  476.23  5227.2  477.08
    5235  477.75  5332.1  478.83  5370.4   479.8  5411.6  479.36  5462.2  479.65
#Mann= 5 ,-1 , 0
  4680.8     .05       0  4997.2     .12       0  5020.3     .07       0
  5024.3     .12       0  5030.8     .05       0
Bank Sta=5020.3,5024.3
XS Rating Curve= 0 ,0
Exp/Cntr=0.3,0.1

Type RM Length L Ch R = 1 ,6507    ,337,337,337
BEGIN DESCRIPTION:
Mapping XS c46b32fe
END DESCRIPTION:
XS GIS Cut Line= 3
      2738409.03       6928093.7      2738409.03      6928351.49
      2738567.78      6928726.26
#Sta/Elev= 30
  4732.9   472.7  4780.2  471.63  4800.2  470.42  4900.2  472.73  4920.2  470.92
  4940.2  471.06  4945.8  469.92  4960.2  467.34  4970.2  468.17  4993.1  467.63
  4995.7  469.45  5001.1  467.13  5011.9  467.82  5017.4  466.78  5017.6  466.28
  5021.4  466.78  5024.8  471.36  5033.6  473.42  5101.3  474.57  5119.5   475.7
  5124.9  475.33  5148.6  477.56    5154  476.75  5172.3  477.53  5177.7     477
  5218.2  477.33  5261.7  478.69  5325.2  478.97  5359.8  480.47  5397.7  479.44
#Mann= 4 ,-1 , 0
  4732.9     .12       0  4945.8     .05       0  5017.4     .04       0
  5021.4     .05       0
Bank Sta=5017.4,5021.4
XS Rating Curve= 0 ,0
Exp/Cntr=0.3,0.1

Type RM Length L Ch R = 1 ,6170    ,90,90,90
BEGIN DESCRIPTION:
Mapping XS c767ef5f
END DESCRIPTION:
XS GIS Cut Line= 3
      2738179.43      6928069.15       2738144.7      6928506.67
      2738134.27      6929706.73
#Sta/Elev= 30
  4556.4  474.58  4578.3  474.74  4618.4  471.44  4688.7  469.78  4728.8  471.67
  4748.6  471.24  4791.6  469.82    4915  469.03  4989.6  467.33    4993  465.96
  4993.2  465.46    4997  465.96  5029.6  470.34  5049.6   471.6  5299.6  477.27
  5359.6  476.55  5369.6  475.27  5389.6  476.09  5519.6  471.99  5529.6  471.59
  5559.6  467.48  5639.6  471.33  5679.6  474.58  5729.7  474.08  5749.7   476.3
  5809.7  477.67  6069.7  480.37  6089.7  481.64  6119.7  481.34  6195.4  483.25
#Mann= 4 ,-1 , 0
  4556.4     .12       0  4748.6     .05       0    4993     .04       0
    4997     .05       0
Bank Sta=4993,4997
XS Rating Curve= 0 ,0
Exp/Cntr=0.3,0.1

Type RM Length L Ch R = 1 ,6080    ,257,257,257
BEGIN DESCRIPTION:
Mapping XS a27c7e47
END DESCRIPTION:
XS GIS Cut Line= 3
      2738047.48      6928114.32      2738054.42      6928520.56
      2738008.25      6929616.99
#Sta/Elev= 30
  4603.7  478.77  4660.4  476.84  4700.4  471.05  4740.4  469.61  4860.4  469.59
  4870.4   468.2  4900.4  469.85  4970.4  469.63  4980.4  467.41  4988.4   463.1
  4988.7   462.6  4992.4   463.1  5000.4   467.1  5040.5  468.97  5088.5  466.77
  5093.5  468.06  5100.5  465.94  5140.6  470.43  5290.7  474.02  5390.8  473.59
  5480.9  470.98  5510.9  468.98  5520.9  464.64  5530.9  468.61  5560.9  468.36
  5566.3  469.83    5641  472.92  5811.2  476.95  5931.3  477.59  6107.4  481.61
#Mann= 3 ,-1 , 0
  4603.7     .05       0  4988.4     .05       0  4992.4     .05       0
Bank Sta=4988.4,4992.4
XS Rating Curve= 0 ,0
Exp/Cntr=0.3,0.1

Type RM Length L Ch R = 1 ,5823    ,453,453,453
BEGIN DESCRIPTION:
Mapping XS c7dc97d3
END DESCRIPTION:
XS GIS Cut Line= 4
      2737674.63      6928371.95      2737889.93      6928691.42
      2737997.57      6928840.73        2737951.      6929736.02
#Sta/Elev= 30
  4610.7  484.84  4696.8  480.18  4718.1  477.03  4777.7  472.31  4840.8  469.67
  4907.9  468.93  4921.7  468.32  4942.7  464.64  4963.7  466.27  4969.3  461.78
  4969.6  461.28  4973.3  461.78  4978.7  463.08  4984.7  467.05  4995.9  465.46
  4999.7  467.48  5014.4  466.75  5020.6  467.93  5064.7  467.56  5121.2  471.21
  5260.4  471.35  5305.9  469.35  5340.5     465  5350.5  468.77  5410.6  469.27
  5430.6  471.64  5472.8  471.72  5630.9  476.58    5741  475.94  6076.5  483.57
#Mann= 5 ,-1 , 0
  4610.7     .05       0  4907.9     .12       0  4969.3     .07       0
  4973.3     .12       0  5472.8     .05       0
Bank Sta=4969.3,4973.3
XS Rating Curve= 0 ,0
Exp/Cntr=0.3,0.1

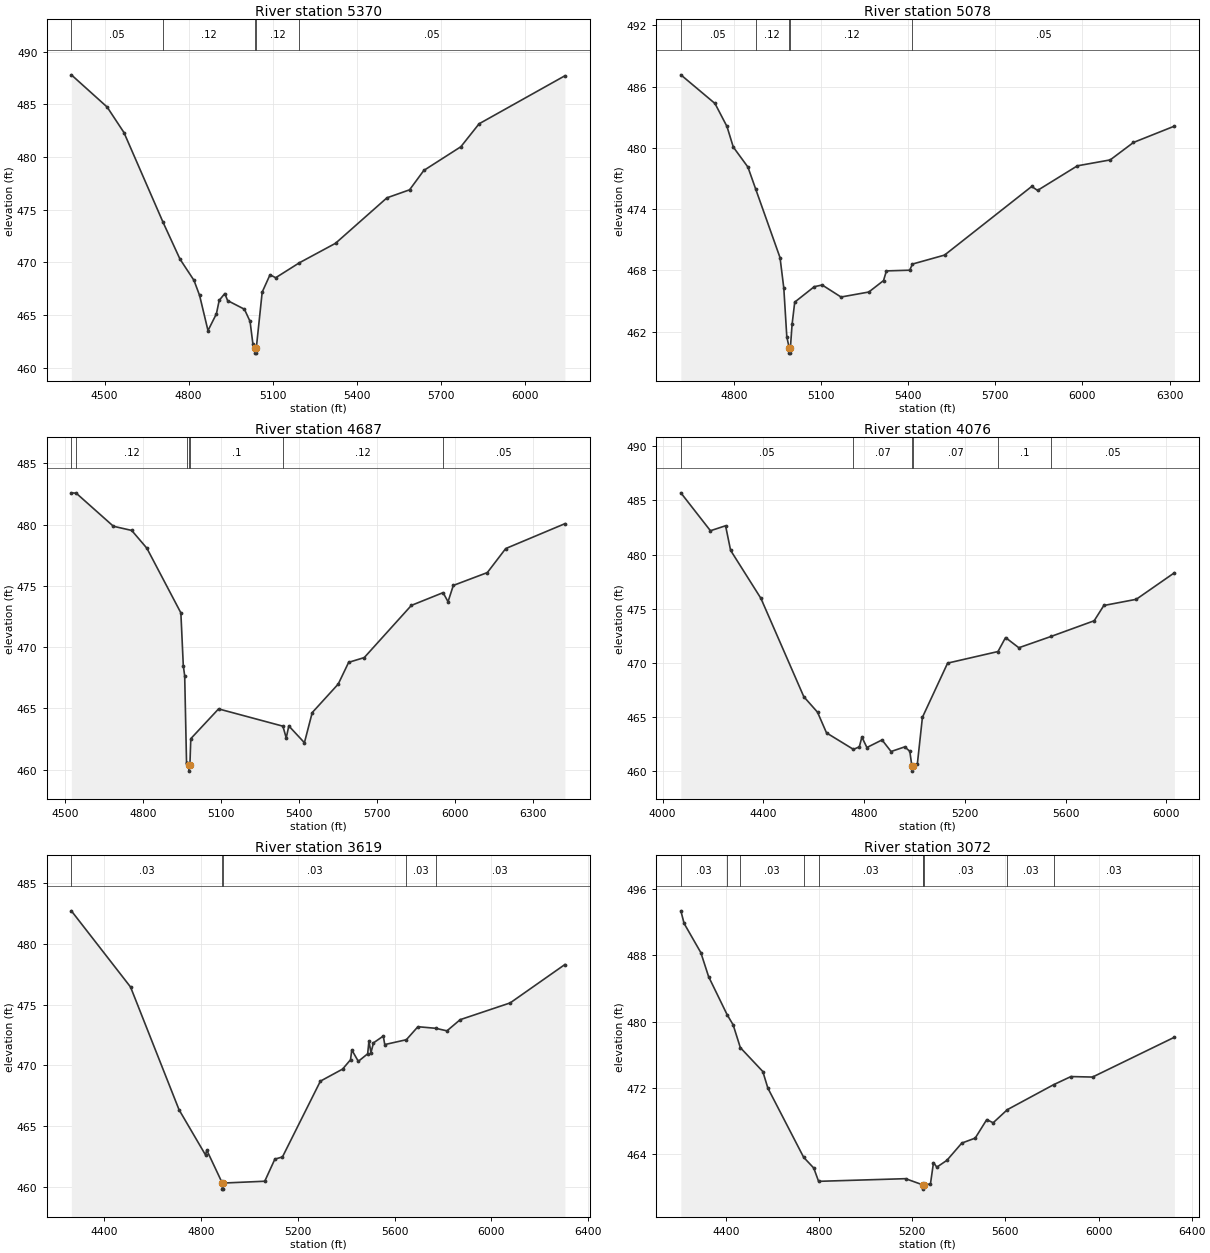
Type RM Length L Ch R = 1 ,5370    ,292,292,292
BEGIN DESCRIPTION:
Mapping XS 5526b99c
END DESCRIPTION:
XS GIS Cut Line= 3
      2737597.71      6928343.21      2737591.59      6928969.94
      2737796.44      6930086.34
#Sta/Elev= 30
  4381.5  487.81  4509.3  484.75  4569.3  482.33  4708.8  473.81  4769.3  470.31
  4819.3  468.29  4839.3  466.86  4869.3  463.52  4899.3  465.11  4909.3  466.39
  4929.3  467.04  4939.3  466.37  4999.3  465.55  5019.5  464.39  5029.7  462.22
  5037.8  461.88  5038.1  461.38  5041.6  461.38  5041.8  461.88  5062.8  467.18
  5090.7  468.82  5110.9  468.54  5195.5  469.96  5324.5  471.81  5508.1  476.13
  5588.9  476.89  5639.7  478.73  5771.9  480.98    5837  483.16  6143.3  487.72
#Mann= 5 ,-1 , 0
  4381.5     .05       0  4708.8     .12       0  5037.8     .07       0
  5041.8     .12       0  5195.5     .05       0
Bank Sta=5037.8,5041.8
XS Rating Curve= 0 ,0
Exp/Cntr=0.3,0.1

Type RM Length L Ch R = 1 ,5078    ,391,391,391
BEGIN DESCRIPTION:
Mapping XS 1e1b3886
END DESCRIPTION:
XS GIS Cut Line= 4
      2737523.17      6928396.86      2737429.11      6928779.05
       2737349.8      6929033.46      2737322.17      6930071.91
#Sta/Elev= 30
  4617.5  487.16    4735  484.35  4776.2   482.1    4798  480.08  4848.3  478.12
  4874.5  476.01  4958.9  469.24  4971.9  466.25  4982.2  461.49  4990.5  460.38
  4990.8  459.88  4994.3  459.88  4994.5  460.38  5000.4   462.7  5009.5  464.88
  5076.6  466.39  5103.9  466.56  5168.9  465.38  5264.5  465.87  5315.1  466.99
  5325.1  467.94  5405.2  468.01  5414.7  468.61  5525.2  469.49  5825.3  476.22
  5845.3  475.83  5982.4  478.24  6095.4  478.82  6175.4  480.53  6316.4  482.13
#Mann= 5 ,-1 , 0
  4617.5     .05       0  4874.5     .12       0  4990.5     .07       0
  4994.5     .12       0  5414.7     .05       0
Bank Sta=4990.5,4994.5
XS Rating Curve= 0 ,0
Exp/Cntr=0.3,0.1

Type RM Length L Ch R = 1 ,4687    ,611,611,611
BEGIN DESCRIPTION:
Mapping XS b0d6528d
END DESCRIPTION:
XS GIS Cut Line= 4
      2737284.21      6928174.45      2737092.04      6928616.64
       2737061.6      6929280.92      2737157.98       6930026.9
#Sta/Elev= 30
  4524.2  482.59    4543  482.56  4686.1  479.86  4756.5  479.52  4814.8  478.07
  4945.7  472.79    4955  468.49  4960.4  467.64  4967.5  460.54  4968.7  460.52
  4976.4  460.37  4976.6  459.87  4980.4  460.37  4983.9  462.52  5090.8  464.95
  5338.3  463.54  5351.1  462.58  5361.1  463.56  5421.1  462.19  5451.2  464.65
  5551.3  466.98  5591.3  468.75  5651.4  469.14  5832.7   473.4  5954.7  474.44
  5973.8   473.7  5994.1  475.03  6125.1  476.08  6195.7  478.04  6423.5  480.07
#Mann= 7 ,-1 , 0
  4524.2     .05       0    4543     .12       0  4968.7      .1       0
  4976.4     .07       0  4980.4      .1       0  5338.3     .12       0
  5954.7     .05       0
Bank Sta=4976.4,4980.4
XS Rating Curve= 0 ,0
Exp/Cntr=0.3,0.1

Type RM Length L Ch R = 1 ,4076    ,457,457,457
BEGIN DESCRIPTION:
Mapping XS ade7d31c
END DESCRIPTION:
XS GIS Cut Line= 4
      2736674.04      6928123.82      2736737.08       6929046.6
      2736764.52      6929864.66      2736856.55      6930060.79
#Sta/Elev= 30
  4072.2   485.7  4189.7   482.2  4249.8  482.66  4269.8  480.39  4390.1  475.96
  4560.5  466.88    4615  465.45  4650.7  463.54  4757.5  462.02    4781  462.25
  4791.1  463.15  4811.1  462.19  4871.2  462.89  4907.1  461.82  4961.4  462.25
  4981.5  461.84  4989.5  460.51  4989.8  460.01  4993.5  460.51  5011.5  460.68
  5031.6  464.98  5131.6  469.98  5331.7  471.05  5361.7  472.34  5414.5   471.4
  5542.2  472.44  5713.7  473.89    5752   475.3  5880.7  475.87  6032.3  478.32
#Mann= 6 ,-1 , 0
  4072.2     .05       0  4757.5     .07       0  4989.5      .5       0
  4993.5     .07       0  5331.7      .1       0  5542.2     .05       0
Bank Sta=4989.5,4993.5
XS Rating Curve= 0 ,0
Exp/Cntr=0.3,0.1

Type RM Length L Ch R = 1 ,3619    ,547,547,547
BEGIN DESCRIPTION:
Mapping XS 70c1e2de
END DESCRIPTION:
XS GIS Cut Line= 4
      2736315.45      6928127.15      2736374.48      6928848.96
      2736540.29      6929393.22      2736839.73       6930077.6
#Sta/Elev= 30
  4263.3  482.73    4508  476.46  4708.6  466.35    4818  462.63  4823.1  463.03
  4887.2  460.32  4887.5  459.82    4891  459.82  4891.2  460.32  5062.8  460.47
  5104.6  462.29    5136  462.47  5292.8  468.71  5384.5   469.7  5417.3  470.47
  5422.6  471.28  5449.6  470.34  5488.2  470.96  5493.5  472.01  5501.9  471.06
  5512.3  471.86  5552.7  472.42  5558.9  471.72  5648.2  472.12  5695.9  473.19
  5769.4  473.06    5816  472.85  5870.6  473.77  6077.3  475.15  6303.5  478.31
#Mann= 5 ,-1 , 0
  4263.3     .03       0  4887.2     .03       0  4891.2     .03       0
  5648.2     .03       0  5769.4     .03       0
Bank Sta=4887.2,4891.2
XS Rating Curve= 0 ,0
Exp/Cntr=0.3,0.1

Type RM Length L Ch R = 1 ,3072    ,476,476,476
BEGIN DESCRIPTION:
Mapping XS 6d076d5b
END DESCRIPTION:
XS GIS Cut Line= 3
       2735686.9      6928313.13       2735909.2      6929069.97
      2736743.03      6930108.04
#Sta/Elev= 30
  4205.6  493.36  4219.6  491.84  4291.5  488.32  4324.9  485.42  4404.2  480.85
  4430.3  479.61  4461.1  476.87  4557.7  473.99  4579.4  471.99  4733.1  463.65
  4776.6  462.35  4797.3  460.75  5170.9  461.07  5246.4  460.31  5247.3  460.31
  5247.6  459.81  5251.3  460.31  5277.9  460.44  5290.9     463  5305.3  462.46
  5348.5  463.28  5412.5  465.36  5470.1  465.96  5519.7  468.19  5547.3  467.81
  5608.2  469.39    5807   472.4  5881.4  473.38  5974.2  473.32  6325.9  478.12
#Mann= 10 ,-1 , 0
  4205.6     .03       0  4404.2     .03       0  4461.1     .03       0
  4733.1     .03       0  4797.3     .03       0  5246.4     .03       0
  5247.3     .03       0  5251.3     .03       0  5608.2     .03       0
    5807     .03       0
Bank Sta=5247.3,5251.3
XS Rating Curve= 0 ,0
Exp/Cntr=0.3,0.1

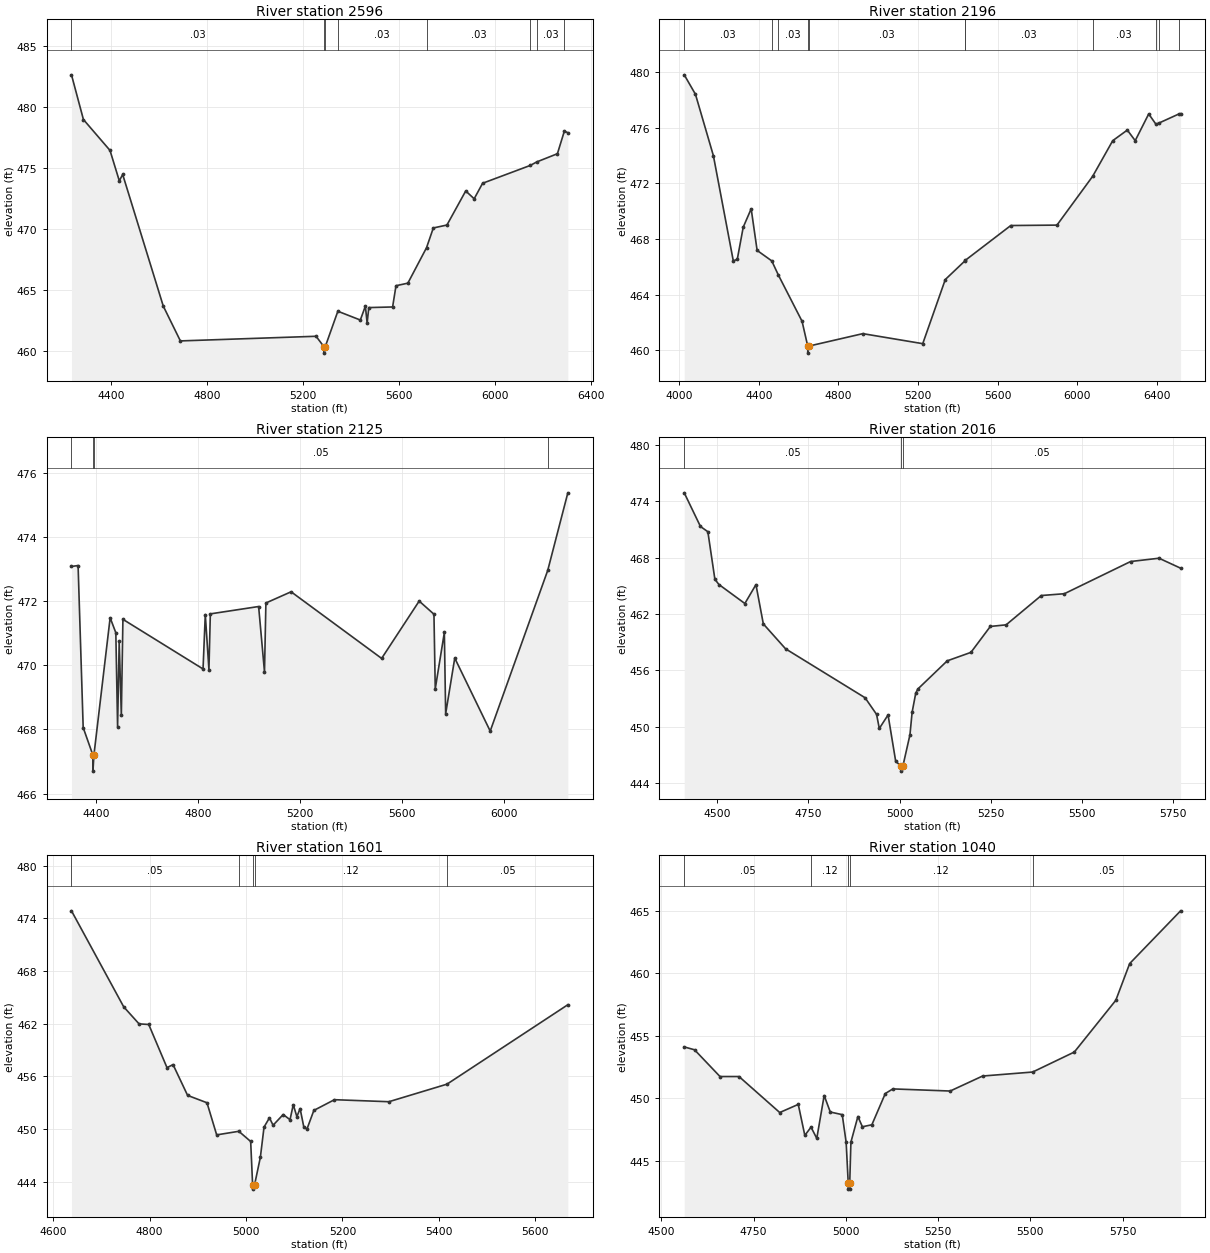
Type RM Length L Ch R = 1 ,2596    ,400,400,400
BEGIN DESCRIPTION:
Mapping XS c884a552
END DESCRIPTION:
XS GIS Cut Line= 3
      2735382.26      6928555.22      2735522.58      6929310.17
      2736405.38      6930262.86
#Sta/Elev= 30
  4234.8  482.61  4284.5  478.95  4395.2  476.42  4433.9  473.93    4448  474.45
    4617  463.67  4688.2  460.82  5253.2   461.2  5286.9  460.32  5287.2  459.82
  5290.9  460.32  5343.9  463.25  5437.5  462.53  5458.5  463.67  5465.8  462.28
  5472.7  463.55  5571.9   463.6    5586  465.34  5635.4  465.55  5713.1  468.45
  5741.4  470.07  5798.1  470.31  5876.3   473.1  5911.5  472.46  5946.6  473.73
    6145  475.19  6172.4  475.48  6258.1  476.15    6287     478  6301.5  477.87
#Mann= 8 ,-1 , 0
  4234.8     .03       0  5286.9     .03       0  5290.9     .03       0
  5343.9     .03       0  5713.1     .03       0    6145     .03       0
  6172.4     .03       0    6287     .03       0
Bank Sta=5286.9,5290.9
XS Rating Curve= 0 ,0
Exp/Cntr=0.3,0.1

Type RM Length L Ch R = 1 ,2196    ,71,71,71
BEGIN DESCRIPTION:
Mapping XS 9d3a01bc
END DESCRIPTION:
XS GIS Cut Line= 6
      2735165.25      6928624.57       2735154.9      6929060.73
       2735087.7      6929207.21      2735429.85      6929976.44
      2736002.33      6930114.72       2736408.5      6930313.98
#Sta/Elev= 30
  4024.8  479.79  4081.2  478.39  4171.3  473.98  4271.3  466.43  4291.3  466.52
  4321.3  468.84  4361.3  470.16  4391.3  467.17  4464.7  466.42  4498.1   465.4
  4617.1  462.08  4645.7  460.29  4645.9  459.79  4649.7  460.29  4922.6  461.19
  5223.9  460.47  5337.3  465.08  5436.8  466.43  5437.9  466.46  5666.5  468.96
  5898.7  468.99  6078.3   472.5  6179.2  475.06  6252.4  475.82  6292.1  475.06
    6360  476.98  6395.8  476.25  6409.2  476.31  6512.2  476.98  6520.3     477
#Mann= 11 ,-1 , 0
  4024.8     .03       0  4464.7     .03       0  4498.1     .03       0
  4645.7     .03       0  4649.7     .03       0  5436.8     .03       0
  5437.9     .03       0  6078.3     .03       0  6395.8     .03       0
  6409.2     .03       0  6512.2     .03       0
Bank Sta=4645.7,4649.7
XS Rating Curve= 0 ,0
Exp/Cntr=0.3,0.1

Type RM Length L Ch R = 1 ,2125    ,109,109,109
BEGIN DESCRIPTION:
Mapping XS 2a0a9cd5
END DESCRIPTION:
XS GIS Cut Line= 6
      2735107.64      6928935.19      2735026.91        6929167.
      2735032.12      6929307.63      2735339.41      6929966.48
      2735506.07      6930083.67      2736101.05      6930236.01
#Sta/Elev= 30
  4302.8  473.09  4328.7  473.12  4348.7  468.06  4386.8   467.2    4387   466.7
  4390.8   467.2  4454.5  471.49  4476.8  471.02  4483.7  468.09    4490  470.75
  4498.4  468.45  4504.6  471.44    4819  469.89  4827.8  471.59  4842.1  469.87
  4847.6  471.61  5037.1  471.84  5060.1   469.8  5065.6  471.95  5164.5   472.3
  5519.7  470.22    5667  472.01    5725   471.6  5730.1  469.27  5765.8  471.03
  5770.9  468.49  5806.6  470.23  5945.7  467.95  6171.5  472.97  6250.3  475.39
#Mann= 4 ,-1 , 0
  4302.8     .05       0  4386.8     .04       0  4390.8     .05       0
  6171.5     .12       0
Bank Sta=4386.8,4390.8
XS Rating Curve= 0 ,0
Exp/Cntr=0.3,0.1

Type RM Length L Ch R = 1 ,2016    ,415,415,415
BEGIN DESCRIPTION:
Mapping XS f0a151a0
END DESCRIPTION:
XS GIS Cut Line= 6
      2734926.65      6929037.15       2734982.2      6929373.94
      2735057.06      6929611.28      2735250.87      6929950.84
       2735391.3      6930088.53      2735561.05      6930154.87
#Sta/Elev= 30
  4409.8  474.91  4454.2  471.33  4474.5  470.77  4493.8   465.7  4504.9  465.15
  4575.9  463.13  4606.3  465.14  4626.5  460.96  4687.4  458.31  4905.3   453.1
  4936.8  451.33  4944.3  449.83  4968.3  451.27  4989.2  446.34  5004.6  445.79
  5004.9  445.29  5008.7  445.79  5028.3  449.16  5034.2  451.55  5044.1  453.58
  5049.9  454.03  5130.5  457.03  5195.4  457.93  5248.6  460.69  5291.8  460.86
  5388.2  463.98  5451.3  464.17    5633   467.6  5710.8  467.95  5769.9  466.89
#Mann= 3 ,-1 , 0
  4409.8     .05       0  5004.6     .04       0  5008.7     .05       0
Bank Sta=5004.6,5008.7
XS Rating Curve= 0 ,0
Exp/Cntr=0.3,0.1

Type RM Length L Ch R = 1 ,1601    ,561,561,561
BEGIN DESCRIPTION:
Mapping XS c8e12a36
END DESCRIPTION:
XS GIS Cut Line= 3
      2734638.46      6929151.77      2734683.59      6929551.03
      2735155.83      6929964.24
#Sta/Elev= 30
  4638.1  474.87  4746.4  463.93  4778.2  461.99  4798.3  461.92  4836.2     457
  4848.7  457.35  4878.9  453.84  4919.1     453  4939.2  449.34  4985.1  449.75
  5009.7  448.59  5013.7  443.66    5014  443.16  5017.8  443.66  5029.8  446.79
  5037.4  450.23  5048.6  451.28  5056.2  450.44  5077.1  451.66  5091.3  451.07
    5098  452.78  5105.5  451.42  5112.2  452.34  5119.8  450.26  5126.4     450
  5140.7  452.13  5183.4  453.35  5296.3  453.12  5416.8  455.12  5667.4  464.17
#Mann= 5 ,-1 , 0
  4638.1     .05       0  4985.1     .12       0  5013.7     .07       0
  5017.8     .12       0  5416.8     .05       0
Bank Sta=5013.7,5017.8
XS Rating Curve= 0 ,0
Exp/Cntr=0.3,0.1

Type RM Length L Ch R = 1 ,1040    ,460,460,460
BEGIN DESCRIPTION:
Mapping XS 88df4345
END DESCRIPTION:
XS GIS Cut Line= 3
       2734232.2      6929273.21      2734266.92      6929669.08
      2735161.84      6929981.26
#Sta/Elev= 30
    4562  454.12  4589.9  453.89  4658.9  451.75  4710.4  451.75  4820.8  448.87
    4871  449.52  4888.8  447.04  4905.6   447.7  4921.2   446.8  4941.2  450.23
  4957.8  448.91  4990.2   448.7  5000.8  446.48  5006.4  443.24  5006.7  442.74
  5010.2  442.74  5010.5  443.24  5013.7   446.5  5032.6  448.55  5044.8  447.73
  5070.5  447.89  5106.9  450.39  5127.4  450.76  5282.7  450.59  5370.6  451.79
  5506.3  452.11  5619.2  453.71  5731.6  457.85  5769.2  460.79  5907.2  465.01
#Mann= 5 ,-1 , 0
    4562     .05       0  4905.6     .12       0  5006.4     .07       0
  5010.5     .12       0  5506.3     .05       0
Bank Sta=5006.4,5010.5
XS Rating Curve= 0 ,0
Exp/Cntr=0.3,0.1

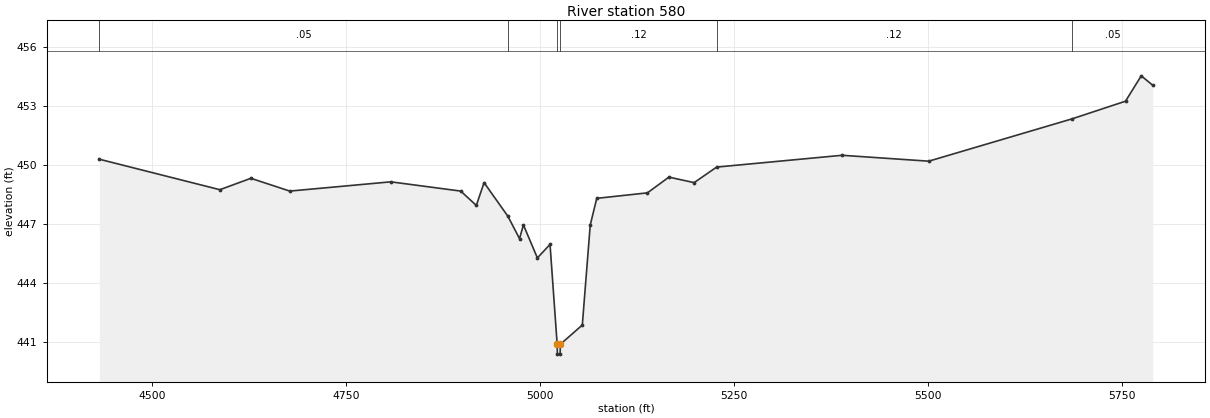
Type RM Length L Ch R = 1 ,580     ,0,0,0
BEGIN DESCRIPTION:
Graveyard Branch 1.0
END DESCRIPTION:
XS GIS Cut Line= 3
        2734051.      6929385.98      2734082.43      6929953.21
      2734860.63      6930085.74
#Sta/Elev= 30
  4431.9  450.29  4587.2  448.74  4627.2  449.32  4677.3  448.67  4807.5  449.14
  4897.6  448.67  4917.7  447.94  4927.7   449.1  4958.4  447.39  4973.4  446.25
  4978.4  446.95  4996.4  445.27  5012.7  445.96  5021.9  440.88  5022.2  440.38
  5025.7  440.38    5026  440.88  5054.3  441.86  5064.5  446.94  5072.9   448.3
  5138.2  448.58  5165.9  449.38  5198.4   449.1  5227.4  449.89  5389.1  450.49
  5500.7  450.19  5685.2  452.34  5754.3  453.24  5774.6  454.53  5789.4  454.05
#Mann= 6 ,-1 , 0
  4431.9     .05       0  4958.4     .12       0  5021.9     .07       0
    5026     .12       0  5227.4     .12       0  5685.2     .05       0
Bank Sta=5021.9,5026
XS Rating Curve= 0 ,0
Exp/Cntr=0.3,0.1

Chan Stop Cuts=-1
Use User Specified Reach Order=0
Composite Channel Slope=5