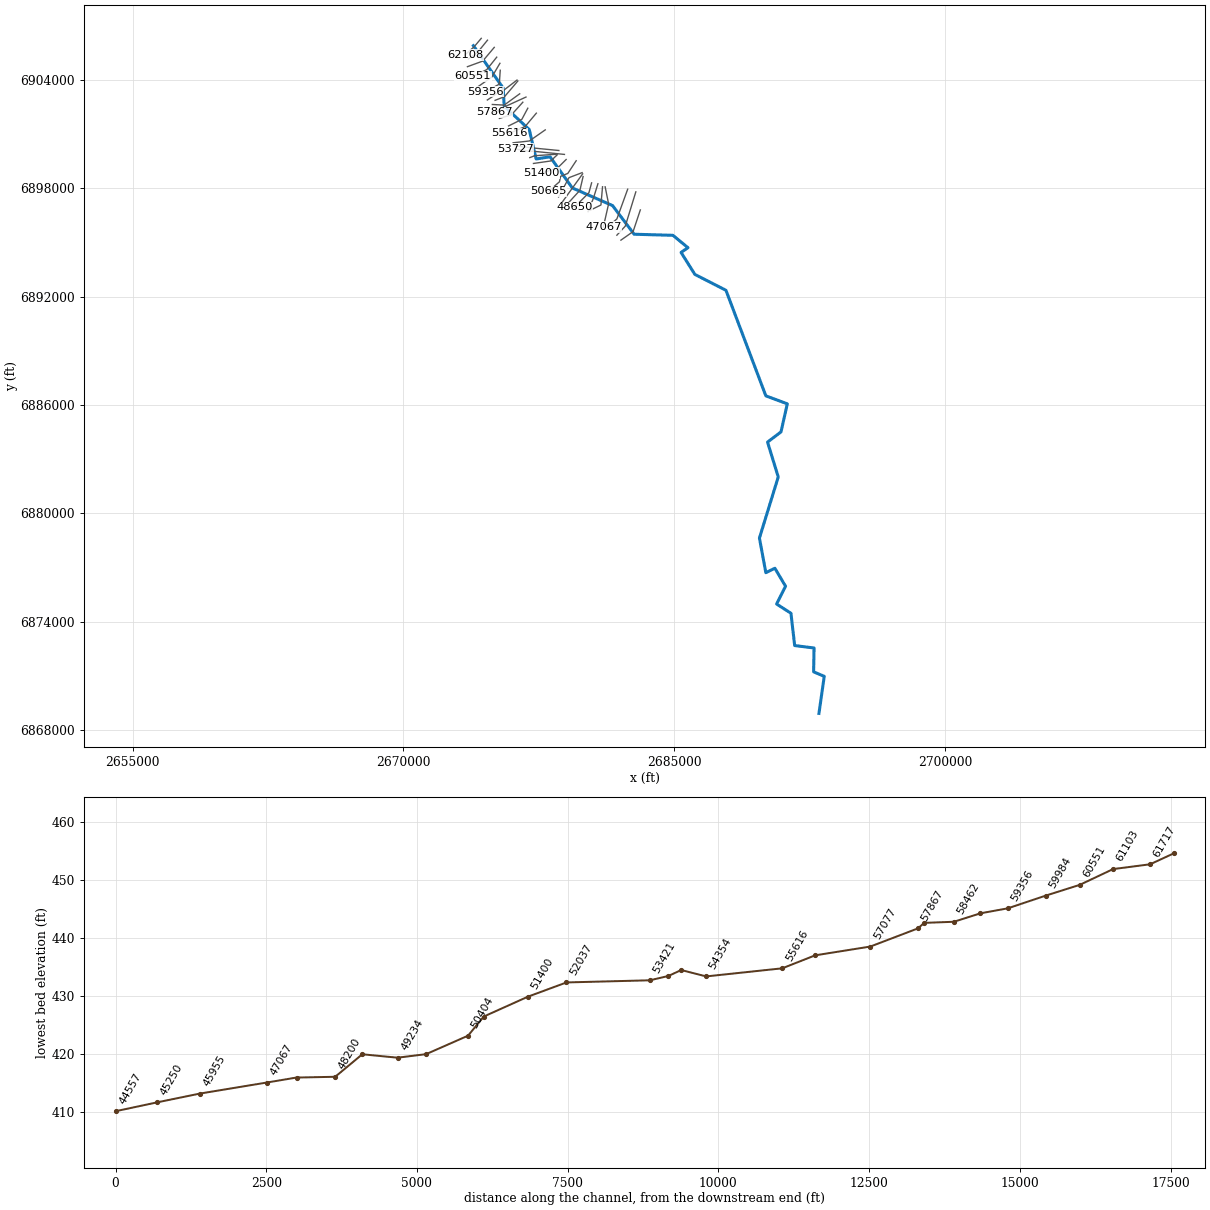
--- Jones Creek.prj (project) ---

Proj Title=Jones Creek Base Level Engineering
Current Plan=p01
Default Exp/Contr=0.3,0.1
English Units
Geom File=g01
Flow File=f01
Plan File=p01
Y Axis Title=Elevation
X Axis Title(PF)=Main Channel Distance
X Axis Title(XS)=Station
BEGIN DESCRIPTION:
Jones Creek
END DESCRIPTION:
DSS Export Rating Curves= 0
DSS Export Rating Curve Sorted= 0
DSS Export Volume Flow Curves= 0
DXF OffsetX= 0
DXF OffsetY= 0
DXF ScaleX= 1
DXF ScaleY= 10

--- Jones Creek.p01 (plan) ---

Plan Title=Multiple Run
Short Identifier=Multiple
Geom File=g01
Flow File=f01
Subcritical Flow
K Sum by GR= 0
Std Step Tol= 0.01
Critical Tol= 0.01
Num of Std Step Trials= 20
Max Error Tol= 0.3
Flow Tol Ratio= 0.001
Split Flow NTrial= 30
Split Flow Tol= 0.02
Split Flow Ratio= 0.02
Log Output Level= 0
Friction Slope Method= 1
Unsteady Friction Slope Method= 2
Unsteady Bridges Friction Slope Method= 1
Parabolic Critical Depth
Global Vel Dist=  1 , 1 , 1
Global Log Level= 0
CheckData=True
Encroach Param= -1, 0, 0, 0
BEGIN DESCRIPTION:
Multiple Run
END DESCRIPTION:

--- Jones Creek.f01 (steady flow) ---

Flow Title=Multiple
Program Version=4.10
Number of Profiles= 7
Profile Names=10-year,25-year,50-year,1pct_min,100-year,1pct_plu,500-year
River Rch & RM=Jones Creek,Reach-1         ,62108
     583     783     944     565    1127    2249    1607
River Rch & RM=Jones Creek,Reach-1         ,61103
     668     902    1093     656    1309    2612    1878
River Rch & RM=Jones Creek,Reach-1         ,58903
    1110    1542    1904    1163    2320    4630    3450
River Rch & RM=Jones Creek,Reach-1         ,57867
    1308    1828    2265    1388    2769    5525    4142
River Rch & RM=Jones Creek,Reach-1         ,54354
    1443    2022    2509    1539    3070    6126    4603
River Rch & RM=Jones Creek,Reach-1         ,50665
    2011    2857    3577    2212    4413    8804    6724
River Rch & RM=Jones Creek,Reach-1         ,45955
    2104    2990    3745    2315    4620    9218    7039
River Rch & RM=Jones Creek,Reach-1         ,43035
    2319    3306    4150    2571    5129   10234    7845
River Rch & RM=Jones Creek,Reach-1         ,40545
    2281    3241    4059    2508    5004    9984    7615
River Rch & RM=Jones Creek,Reach-1         ,35410
    2515    3588    4506    2791    5568   11110    8515
River Rch & RM=Jones Creek,Reach-1         ,33992
    2589    3688    4625    2860    5707   11387    8701
River Rch & RM=Jones Creek,Reach-1         ,27899
    2982    4272    5379    3338    6661   13290   10229
River Rch & RM=Jones Creek,Reach-1         ,23203
    3158    4533    5714    3551    7085   14136   10904
River Rch & RM=Jones Creek,Reach-1         ,20766
    3291    4729    5965    3708    7398   14761   11395
River Rch & RM=Jones Creek,Reach-1         ,16810
    3310    4746    5979    3711    7404   14773   11368
River Rch & RM=Jones Creek,Reach-1         ,9496
    3473    4987    6288    3906    7794   15552   11988
River Rch & RM=Jones Creek,Reach-1         ,5978
    3501    5021    6326    3926    7833   15629   12024
Boundary for River Rch & Prof#=Jones Creek,Reach-1         , 1
Up Type= 0
Dn Type= 3
Dn Slope=0.00123
Boundary for River Rch & Prof#=Jones Creek,Reach-1         , 2
Up Type= 0
Dn Type= 3
Dn Slope=0.00123
Boundary for River Rch & Prof#=Jones Creek,Reach-1         , 3
Up Type= 0
Dn Type= 3
Dn Slope=0.00123
Boundary for River Rch & Prof#=Jones Creek,Reach-1         , 4
Up Type= 0
Dn Type= 3
Dn Slope=0.00123
Boundary for River Rch & Prof#=Jones Creek,Reach-1         , 5
Up Type= 0
Dn Type= 3
Dn Slope=0.00123
Boundary for River Rch & Prof#=Jones Creek,Reach-1         , 6
Up Type= 0
Dn Type= 3
Dn Slope=0.00123
Boundary for River Rch & Prof#=Jones Creek,Reach-1         , 7
Up Type= 0
Dn Type= 3
Dn Slope=0.00123
DSS Import GetInterval= 0
DSS Import GetPeak= 0
DSS Import FillOption= 0

--- Jones Creek.g01 (geometry) ---

Geom Title=Existing Conditions
Program Version=4.10

River Reach=Jones Creek     ,Reach-1
Reach XY= 30
        2673876.        6905911.        2675526.        6903561.
      2675583.64      6902554.54      2676970.91      6901263.84
      2677352.48      6899633.99      2678120.96      6899756.08
      2679358.34      6898027.41      2681586.18      6897050.68
      2682784.17      6895463.46      2684932.47       6895403.3
      2685767.12      6894717.53       2685383.4      6894457.63
      2686148.31      6893237.17      2687871.34      6892355.89
      2690080.97      6886508.41      2691270.94      6886063.83
      2690921.01      6884508.38      2690176.51      6883945.67
      2690768.68       6882011.1      2689726.38      6878626.16
      2690081.82      6876708.68      2690582.17      6876953.24
      2691173.83      6875955.03      2690677.19      6874971.48
      2691472.49      6874459.75      2691678.91      6872669.67
       2692753.7      6872534.73      2692729.04      6871212.36
      2693318.34      6870964.69        2693026.        6868911.

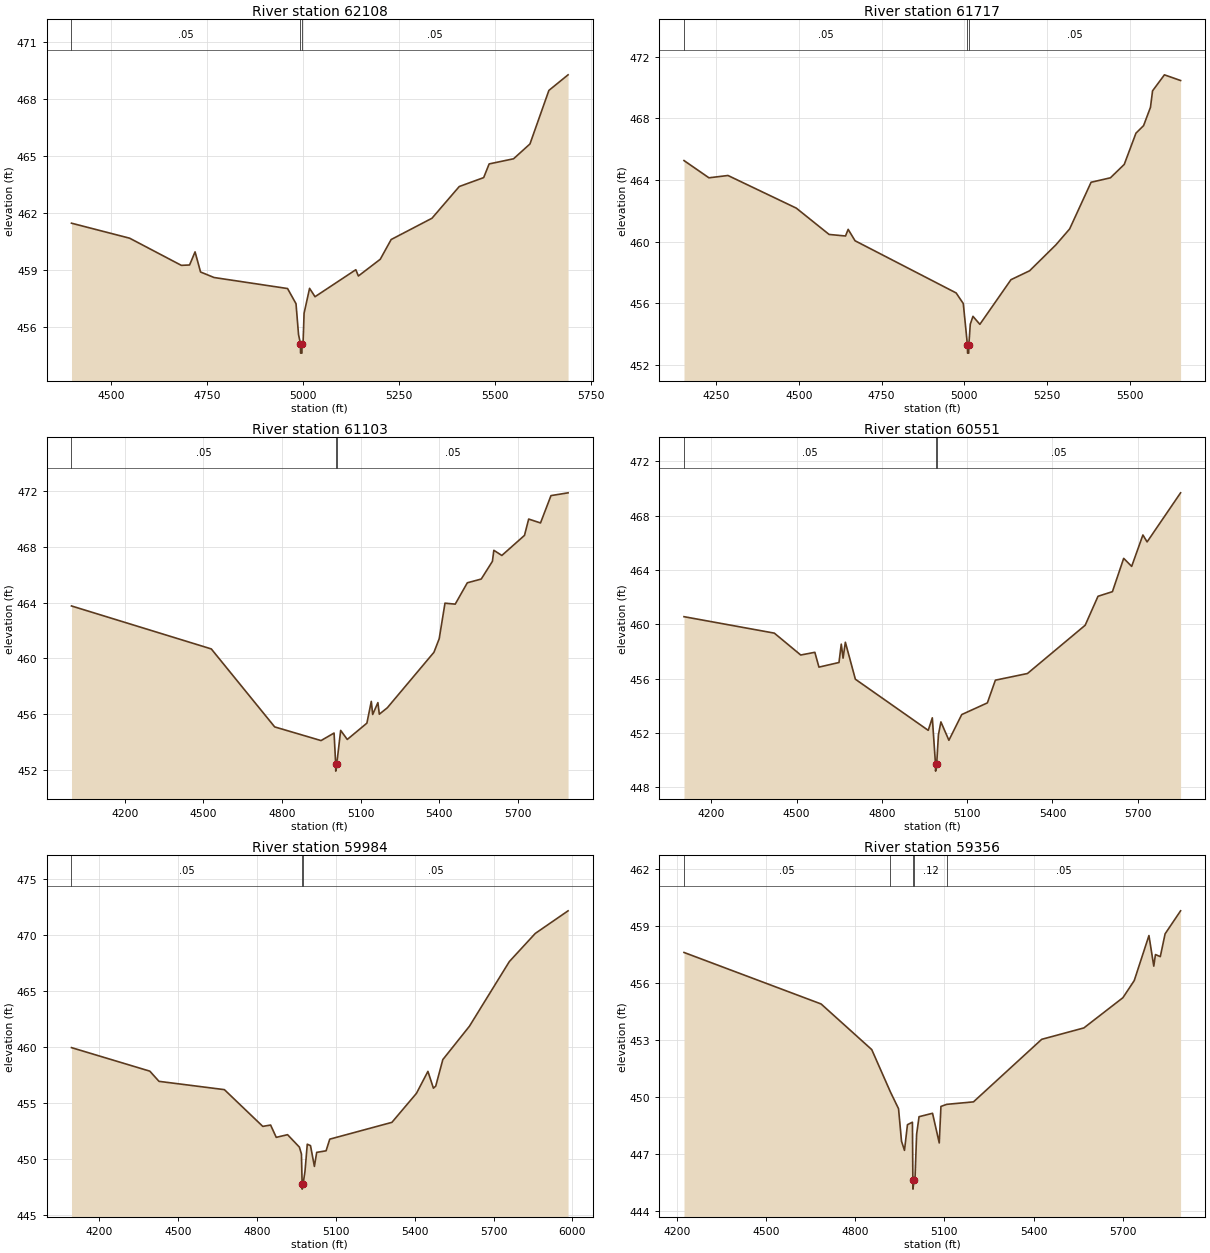
Type RM Length L Ch R = 1 ,62108   ,391,391,391
BEGIN DESCRIPTION:
Jones Creek 101.0
END DESCRIPTION:
XS GIS Cut Line= 3
      2674310.22      6906319.65      2673921.88      6905858.87
      2673407.42       6905399.5
#Sta/Elev= 30
  4397.4  461.47  4548.7  460.68  4683.3  459.25  4704.7  459.27    4719  459.96
  4733.3   458.9  4768.5  458.61  4959.7  458.03  4981.7  457.23  4988.3   455.6
  4993.3  455.13  4993.6  454.63  4997.1  454.63  4997.3  455.13    5000  455.13
  5002.7  456.73    5017  458.04  5031.2   457.6  5137.3  459.02    5144  458.69
  5200.9  459.57  5229.3  460.61  5335.5  461.73  5406.5   463.4  5470.1  463.87
  5484.3  464.59  5547.8  464.86  5590.5  465.64  5639.8  468.46  5689.7  469.28
#Mann= 3 ,-1 , 0
  4397.4     .05       0  4993.3     .04       0  4997.3     .05       0
Bank Sta=4993.3,4997.3
XS Rating Curve= 0 ,0
Exp/Cntr=0.3,0.1

Type RM Length L Ch R = 1 ,61717   ,614,614,614
BEGIN DESCRIPTION:
Mapping XS 54de92eb
END DESCRIPTION:
XS GIS Cut Line= 3
      2674655.87      6906217.73      2674128.09      6905568.43
      2673596.88      6905172.63
#Sta/Elev= 30
  4153.7  465.26    4229  464.14  4286.5  464.29  4492.7  462.17  4591.8  460.46
  4641.3  460.36  4649.3  460.79  4670.1  460.05  4975.3  456.66  4996.9  455.97
  5009.5  453.25  5009.8  452.75  5013.3  452.75  5013.5  453.25    5018  454.63
  5026.1  455.14  5046.9  454.62  5140.8  457.52  5197.1   458.1  5276.3  459.78
    5318  460.82  5382.7  463.85  5441.1  464.14  5482.8  465.01  5518.2  467.04
  5541.2  467.53    5562  468.72  5568.3  469.79  5604.1  470.83  5652.9  470.46
#Mann= 3 ,-1 , 0
  4153.7     .05       0  5009.5     .03       0  5013.5     .05       0
Bank Sta=5009.5,5013.5
XS Rating Curve= 0 ,0
Exp/Cntr=0.3,0.1

Type RM Length L Ch R = 1 ,61103   ,552,552,552
BEGIN DESCRIPTION:
Mapping XS b7d8ab4a
END DESCRIPTION:
XS GIS Cut Line= 3
      2675030.87      6905818.43      2674391.98      6905058.01
      2673544.76      6904748.99
#Sta/Elev= 30
  3996.8  463.76  4530.3  460.68  4772.2  455.09  4949.1  454.11  4998.8  454.65
    5005  452.42  5005.2  451.92    5009  452.42    5024  454.84  5049.2  454.19
  5124.1  455.36  5140.9  456.92  5146.2  455.98  5166.1  456.83  5171.5     456
    5202  456.46    5380  460.44    5400  461.41  5422.1  463.96  5461.1  463.89
  5507.3  465.42  5560.5  465.69  5603.1  466.96  5608.5  467.75  5639.1  467.38
  5725.5  468.82  5741.5  469.99  5786.6  469.71  5826.6  471.67  5891.8  471.87
#Mann= 3 ,-1 , 0
  3996.8     .05       0    5005     .04       0    5009     .05       0
Bank Sta=5005,5009
XS Rating Curve= 0 ,0
Exp/Cntr=0.3,0.1

Type RM Length L Ch R = 1 ,60551   ,567,567,567
BEGIN DESCRIPTION:
Mapping XS 7938bf43
END DESCRIPTION:
XS GIS Cut Line= 3
      2675167.53      6905276.28      2674616.29      6904586.14
      2673840.17      6904208.92
#Sta/Elev= 30
  4104.3  460.56  4421.9  459.35  4514.8  457.74  4564.4  457.94  4578.8  456.85
  4649.3  457.19  4657.3  458.54  4663.7  457.51  4671.7  458.68  4706.9  455.96
  4963.1   452.2  4977.5  453.12  4988.7   449.7  4988.9   449.2  4992.7   449.7
    4999  451.88  5007.7  452.82  5035.8  451.47  5080.9  453.36  5171.1  454.22
  5199.2  455.89    5312  456.38    5515  459.93  5560.1  462.06  5610.8   462.4
  5650.4  464.85  5678.5  464.26    5718  466.57  5732.8  466.06  5850.5  469.67
#Mann= 3 ,-1 , 0
  4104.3     .05       0  4988.7     .03       0  4992.7     .05       0
Bank Sta=4988.7,4992.7
XS Rating Curve= 0 ,0
Exp/Cntr=0.3,0.1

Type RM Length L Ch R = 1 ,59984   ,628,628,628
BEGIN DESCRIPTION:
Mapping XS 35cbdef0
END DESCRIPTION:
XS GIS Cut Line= 3
      2675345.44      6904937.68       2674898.4      6904178.15
      2674073.78      6903600.92
#Sta/Elev= 30
  4095.5  459.96  4393.3  457.86  4428.2  456.95  4676.8  456.21  4822.7  452.93
  4852.5  453.05    4874  451.95  4916.9  452.19  4961.9  451.08  4969.7  450.47
  4972.3  447.83  4972.5  447.33  4976.3  447.83  4983.2  448.92  4991.9  451.34
  5004.2  451.21    5019  449.36  5027.7  450.61  5063.4  450.75  5077.4  451.79
  5313.7  453.29    5407  455.88  5450.6  457.84  5471.5  456.34  5480.2  456.52
  5507.2  458.89  5608.4  461.87  5760.1  467.64  5858.6  470.15  5983.4  472.17
#Mann= 3 ,-1 , 0
  4095.5     .05       0  4972.3     .03       0  4976.3     .05       0
Bank Sta=4972.3,4976.3
XS Rating Curve= 0 ,0
Exp/Cntr=0.3,0.1

Type RM Length L Ch R = 1 ,59356   ,453,453,453
BEGIN DESCRIPTION:
Mapping XS 2b1e645f
END DESCRIPTION:
XS GIS Cut Line= 3
      2675362.82      6904551.44      2675310.73      6903778.85
       2674520.9      6903353.56
#Sta/Elev= 30
  4223.5  457.59    4685  454.88  4855.4  452.48  4918.3  450.25  4945.6  449.37
  4955.6  447.66  4965.6  447.18  4975.6  448.53  4992.3  448.66  4993.8  445.64
  4994.1  445.14  4997.9  445.64  5000.9  445.64  5006.4  448.02  5014.6  448.95
    5060  449.13  5082.6  447.57  5088.3  449.49  5107.7   449.6  5197.8  449.73
  5427.4  453.02  5569.4  453.62  5700.8  455.21  5738.9  456.11  5788.4  458.48
  5804.7  456.87  5810.3  457.48  5826.6  457.37  5842.8  458.57  5894.9  459.78
#Mann= 5 ,-1 , 0
  4223.5     .05       0  4918.3     .12       0  4993.8     .07       0
  4997.9     .12       0  5107.7     .05       0
Bank Sta=4993.8,4997.9
XS Rating Curve= 0 ,0
Exp/Cntr=0.3,0.1

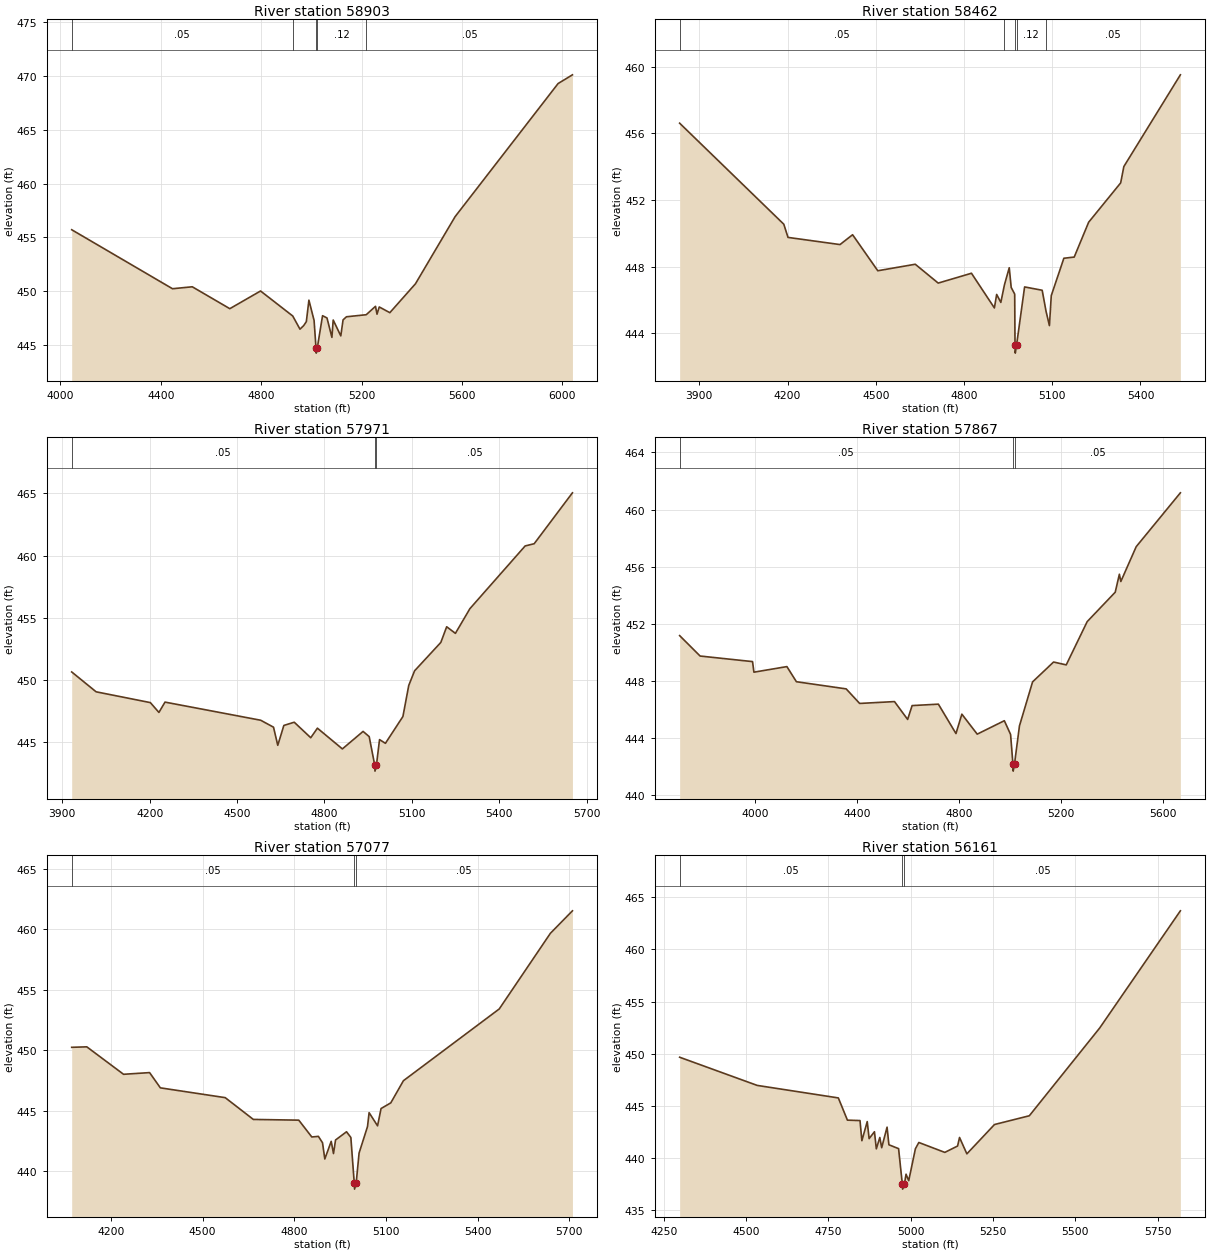
Type RM Length L Ch R = 1 ,58903   ,441,441,441
BEGIN DESCRIPTION:
Mapping XS 57cb03a5
END DESCRIPTION:
XS GIS Cut Line= 4
      2676292.09      6904008.52      2675575.96      6903457.32
       2675428.4       6903422.6      2674647.18      6902901.78
#Sta/Elev= 30
  4045.5  455.72  4446.9  450.25  4525.7  450.43  4675.2   448.4  4797.6  450.04
  4925.9  447.72  4954.6   446.5  4969.7  446.84    4980   447.2  4990.2  449.19
  5010.8  447.31  5018.4  444.78  5019.2  444.28  5023.7  444.78  5044.5  447.75
  5062.2  447.54  5081.8  445.74  5086.9  447.35  5117.2  445.88  5126.2  447.36
  5139.7  447.65  5218.5  447.84  5255.4  448.62  5261.4  447.89  5270.4  448.56
  5312.5  448.03  5414.6  450.71  5572.4  456.93  5982.5  469.27  6039.7  470.08
#Mann= 5 ,-1 , 0
  4045.5     .05       0  4925.9     .12       0  5018.4     .07       0
  5023.7     .12       0  5218.5     .05       0
Bank Sta=5018.4,5023.7
XS Rating Curve= 0 ,0
Exp/Cntr=0.3,0.1

Type RM Length L Ch R = 1 ,58462   ,491,491,491
BEGIN DESCRIPTION:
Mapping XS 4e1d3f17
END DESCRIPTION:
XS GIS Cut Line= 3
      2676339.87      6903956.47      2675602.01       6903088.4
      2675076.83       6902884.4
#Sta/Elev= 30
    3833  456.61  4187.2  450.55  4201.5  449.76  4378.3  449.33  4421.1  449.92
  4506.8  447.76  4634.2  448.15  4712.2  447.02  4825.3  447.61  4903.3  445.53
    4911  446.34  4925.2  445.86  4937.5  446.92  4953.8  447.94  4960.4  446.76
  4972.3  446.36  4973.4  443.32  4974.2  442.82  4978.8  443.32    5006  446.79
  5065.8  446.59  5078.8  445.34  5090.4  444.47  5096.7  446.27  5139.5  448.51
  5174.7  448.58  5223.8  450.67  5332.7  453.03  5343.5  454.01  5535.7  459.51
#Mann= 5 ,-1 , 0
    3833     .05       0  4937.5     .12       0  4973.4     .07       0
  4978.8     .12       0  5078.8     .05       0
Bank Sta=4973.4,4978.8
XS Rating Curve= 0 ,0
Exp/Cntr=0.3,0.1

Type RM Length L Ch R = 1 ,57971   ,104,104,104
BEGIN DESCRIPTION:
Mapping XS c2c24b2a
END DESCRIPTION:
XS GIS Cut Line= 3
      2676439.65      6903244.62      2675580.31      6902619.65
       2674924.9      6902654.37
#Sta/Elev= 30
  3932.3  450.62  4016.1  449.02  4202.3  448.15  4231.7  447.36  4252.6  448.19
    4581  446.73  4625.1  446.17  4639.7  444.71  4660.6  446.31  4696.2  446.57
  4752.9  445.32  4775.8  446.09  4861.5  444.42  4932.6  445.83  4953.5  445.41
  4972.4  443.13  4973.4  442.63  4978.5  443.13    4989  445.17  5009.2  444.87
  5069.3  447.03  5089.3  449.53  5109.3  450.71  5199.5     453  5219.5  454.26
  5249.5  453.73  5299.3  455.72  5488.9  460.77  5519.9  460.95  5651.2  465.05
#Mann= 3 ,-1 , 0
  3932.3     .05       0  4972.4     .03       0  4978.5     .05       0
Bank Sta=4972.4,4978.5
XS Rating Curve= 0 ,0
Exp/Cntr=0.3,0.1

Type RM Length L Ch R = 1 ,57867   ,790,790,790
BEGIN DESCRIPTION:
Mapping XS 0f0120bf
END DESCRIPTION:
XS GIS Cut Line= 3
      2676789.15      6903065.74      2675606.87      6902526.68
      2675017.44      6902215.08
#Sta/Elev= 30
  3702.7  451.17  3783.1  449.74  3988.9  449.35  3994.4  448.61  4123.8     449
  4161.2  447.94  4356.5  447.44  4409.5  446.42  4546.3  446.55  4597.9   445.3
  4615.5  446.27  4718.6  446.37  4787.7  444.31  4810.8  445.67  4871.1  444.27
  4977.6  445.21  5002.1  444.25  5011.3  442.18  5012.3  441.68  5017.5  442.18
    5037  444.85  5088.5  447.93  5170.9  449.32  5220.6  449.12  5302.9  452.15
    5413  454.21  5429.3  455.47    5435  454.96  5495.4   457.4  5668.8  461.17
#Mann= 3 ,-1 , 0
  3702.7     .05       0  5011.3     .03       0  5017.5     .05       0
Bank Sta=5011.3,5017.5
XS Rating Curve= 0 ,0
Exp/Cntr=0.3,0.1

Type RM Length L Ch R = 1 ,57077   ,916,916,916
BEGIN DESCRIPTION:
Mapping XS c6a1f2d3
END DESCRIPTION:
XS GIS Cut Line= 3
      2676615.55      6902781.02      2675990.55      6902086.57
       2675316.9       6901881.7
#Sta/Elev= 30
  4071.7  450.26  4121.1   450.3  4241.4  448.03  4326.6  448.17  4361.8  446.91
    4574   446.1    4666   444.3  4814.7  444.24  4857.3  442.85  4878.9   442.9
  4892.4  442.37  4899.9  441.03  4920.8  442.49  4928.3  441.48    4935   442.6
  4970.9  443.28  4985.1  442.81  4996.2  439.04  4997.2  438.54  5002.5  439.04
    5012  441.52  5039.6  443.71  5044.8  444.86  5072.5  443.77  5083.9   445.2
  5115.8  445.67  5157.1   447.5  5470.6  453.43  5637.9  459.68  5710.1  461.54
#Mann= 3 ,-1 , 0
  4071.7     .05       0  4996.2     .03       0  5002.5     .05       0
Bank Sta=4996.2,5002.5
XS Rating Curve= 0 ,0
Exp/Cntr=0.3,0.1

Type RM Length L Ch R = 1 ,56161   ,545,545,545
BEGIN DESCRIPTION:
Mapping XS 7324ca2b
END DESCRIPTION:
XS GIS Cut Line= 3
      2676889.83      6902447.64      2676559.99      6901829.63
      2675824.84      6901465.52
#Sta/Elev= 30
  4298.4  449.66  4533.9  446.96  4780.4  445.76    4808  443.63  4846.2  443.59
  4851.9  441.66  4868.2  443.49  4873.9  441.86  4890.1  442.52  4895.8  440.88
  4906.4  441.97  4912.1  440.99  4928.4  442.96    4934  441.27  4963.4   440.9
  4974.7  437.52  4975.7  437.02  4981.3  437.52    4986  438.45  4994.2  437.83
  5014.5  440.89  5024.9  441.49  5103.8  440.54  5142.6  441.15  5148.5  441.97
  5170.8   440.4  5254.7  443.21  5360.5  444.05  5574.2  452.46  5819.3  463.69
#Mann= 3 ,-1 , 0
  4298.4     .05       0  4974.7     .03       0  4981.3     .05       0
Bank Sta=4974.7,4981.3
XS Rating Curve= 0 ,0
Exp/Cntr=0.3,0.1

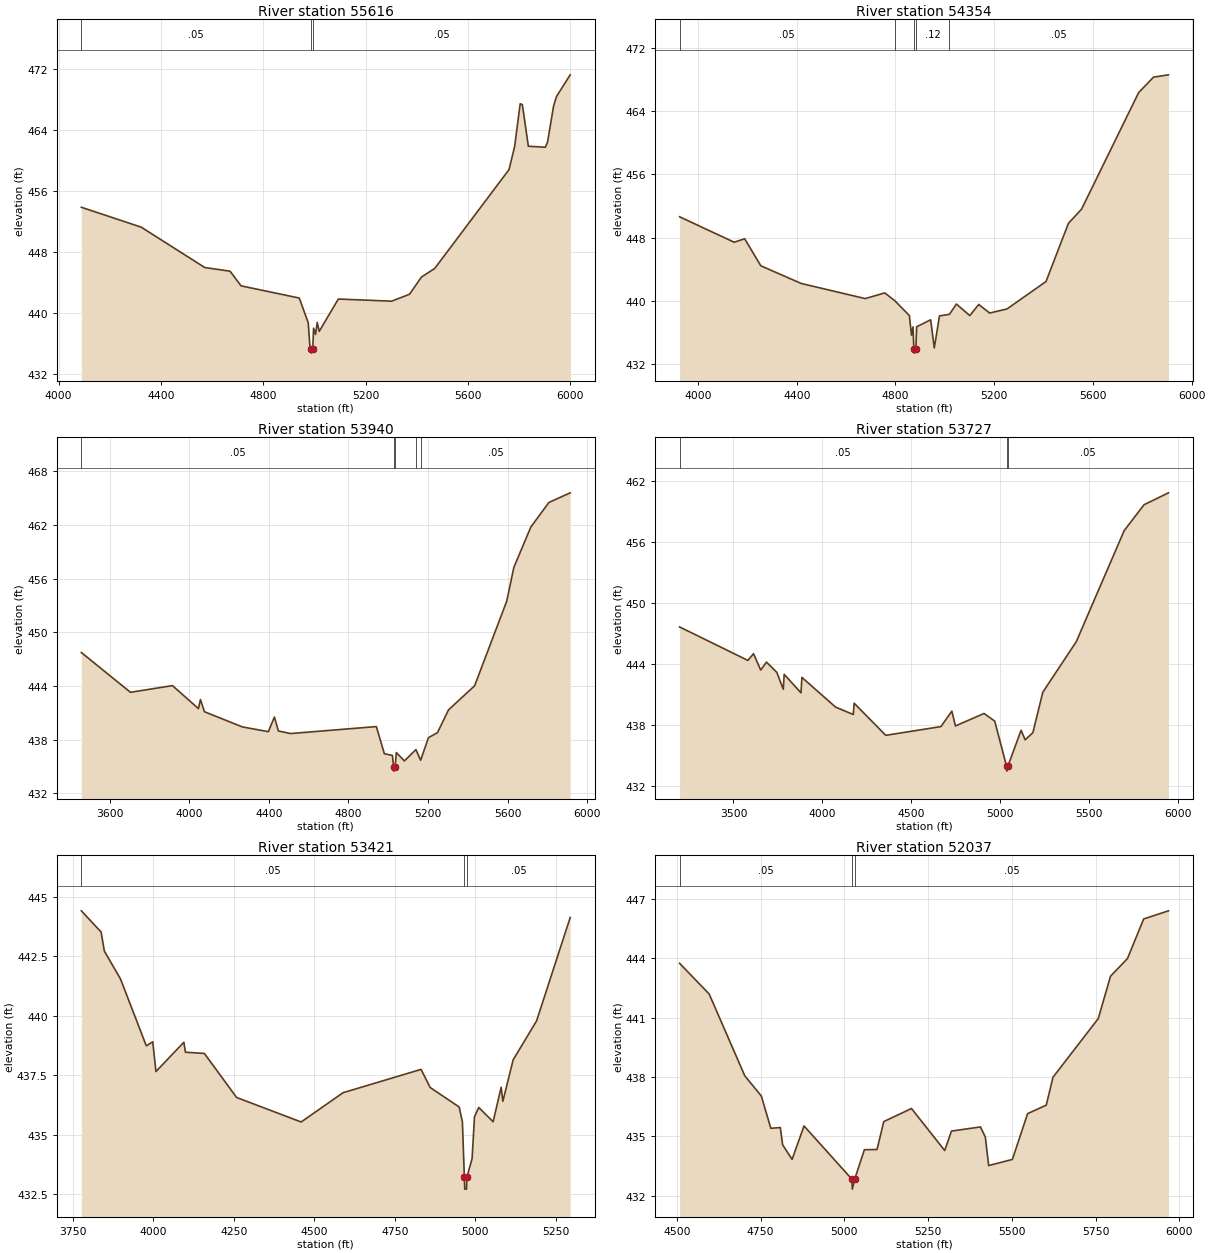
Type RM Length L Ch R = 1 ,55616   ,1262,1262,1262
BEGIN DESCRIPTION:
Mapping XS 7fcafe52
END DESCRIPTION:
XS GIS Cut Line= 3
      2677363.32      6902173.23      2676741.76      6901433.62
      2675877.17      6901051.67
#Sta/Elev= 30
  4088.9   453.9    4323  451.29  4571.5     446  4670.3  445.52  4713.3   443.6
  4940.9     442    4976  438.76  4982.5  435.66  4986.9  435.28    4988  434.78
  4993.6  435.28  4996.8  438.05  5004.6  437.23  5011.1  438.81  5018.9  437.63
  5093.6  441.87  5301.9  441.59  5371.8  442.49  5418.5  444.75  5470.5  445.88
    5761  458.84  5782.8  461.85  5804.7  467.47  5813.2  467.34  5836.5   461.9
  5903.1  461.77  5911.9  462.48  5935.2  467.17  5946.8  468.43  6000.2  471.26
#Mann= 3 ,-1 , 0
  4088.9     .05       0  4986.9     .03       0  4993.6     .05       0
Bank Sta=4986.9,4993.6
XS Rating Curve= 0 ,0
Exp/Cntr=0.3,0.1

Type RM Length L Ch R = 1 ,54354   ,414,414,414
BEGIN DESCRIPTION:
Mapping XS 56760afb
END DESCRIPTION:
XS GIS Cut Line= 3
      2677857.18      6901246.96      2676976.46      6900631.25
      2676075.95      6900531.71
#Sta/Elev= 30
  3925.4  450.63  4146.5  447.41    4189  447.85  4254.4  444.43  4418.4  442.19
  4677.4  440.28  4756.5     441  4797.3  440.01  4856.2  438.14  4864.9  435.65
    4871   436.7  4874.6  433.88  4875.8  433.38  4882.4  433.88  4885.8  436.71
  4942.5   437.6  4957.3  434.04  4978.3  438.09  5018.7  438.29  5046.8  439.59
  5101.1  438.13  5137.5  439.54  5181.6  438.45    5252  438.97  5409.9  442.44
  5500.7   449.8  5553.8  451.59  5785.2  466.34  5845.6   468.3    5906  468.59
#Mann= 5 ,-1 , 0
  3925.4     .05       0  4797.3     .12       0  4874.6     .07       0
  4882.4     .12       0  5018.7     .05       0
Bank Sta=4874.6,4882.4
XS Rating Curve= 0 ,0
Exp/Cntr=0.3,0.1

Type RM Length L Ch R = 1 ,53940   ,213,213,213
BEGIN DESCRIPTION:
Mapping XS bb1217bc
END DESCRIPTION:
XS GIS Cut Line= 3
      2678611.71      6900103.82      2677062.25      6900255.73
      2676169.57      6900372.73
#Sta/Elev= 30
  3457.3  447.74  3704.2  443.29  3915.2  444.04  4045.8  441.47  4055.9  442.48
    4076  441.12  4266.9  439.42  4397.3  438.89  4427.6  440.53  4447.7  438.97
  4508.8  438.68  4940.1  439.46  4980.3  436.43  5020.9  436.23  5026.6  434.98
  5027.8  434.48  5034.5  434.98  5040.7  436.55    5081  435.62    5139  436.89
  5162.6  435.69    5202  438.22  5247.3  438.78  5302.9  441.33    5434  444.02
  5595.4  453.48  5631.3  457.26  5716.4  461.76  5807.2  464.51  5914.5  465.59
#Mann= 5 ,-1 , 0
  3457.3     .05       0  5026.6     .03       0  5034.5     .05       0
    5139     .12       0  5162.6     .05       0
Bank Sta=5026.6,5034.5
XS Rating Curve= 0 ,0
Exp/Cntr=0.3,0.1

Type RM Length L Ch R = 1 ,53727   ,306,306,306
BEGIN DESCRIPTION:
Mapping XS 235084ea
END DESCRIPTION:
XS GIS Cut Line= 4
      2678919.91       6899886.8      2677170.76      6900064.76
      2677031.87      6900051.73      2676190.42      6900190.53
#Sta/Elev= 30
  3196.9  447.64    3581  444.35  3612.9  445.01  3653.2   443.4  3685.7  444.18
  3743.6  443.18  3780.3  441.51  3785.3  442.98  3879.9  441.16    3885  442.68
  4074.2  439.76  4173.9  439.03  4178.9  440.14  4356.8  436.98  4667.2  437.84
  4728.7  439.36  4748.8   437.9  4909.6  439.13  4969.9  438.38  5036.3  433.96
  5037.5  433.46  5044.2  433.96  5118.3  437.48  5141.1  436.54  5184.5  437.24
  5240.5  441.22    5429   446.2  5698.5  457.12    5810  459.66  5947.4  460.83
#Mann= 3 ,-1 , 0
  3196.9     .05       0  5036.3     .03       0  5044.2     .05       0
Bank Sta=5036.3,5044.2
XS Rating Curve= 0 ,0
Exp/Cntr=0.3,0.1

Type RM Length L Ch R = 1 ,53421   ,1384,1384,1384
BEGIN DESCRIPTION:
Mapping XS 8793e079
END DESCRIPTION:
XS GIS Cut Line= 3
      2678497.28      6899897.84      2677276.04      6899814.29
      2677000.01       6899710.5
#Sta/Elev= 30
  3775.9   444.4  3837.3  443.51  3847.3  442.71  3897.5  441.54  3977.7  438.73
  3997.7   438.9  4007.7  437.65  4094.4  438.88  4099.4  438.46  4158.1  438.41
  4258.3  436.56  4458.8  435.53  4589.1  436.76  4831.5  437.74  4859.7  436.98
  4949.9  436.16  4959.9  435.54    4966  433.21  4967.2  432.71  4972.7  432.71
  4973.9  433.21    4990  433.99  4997.5  435.75  5010.7  436.14  5055.4  435.54
  5080.3  436.99  5085.6   436.4  5117.6  438.14  5190.5  439.78  5294.9  444.12
#Mann= 3 ,-1 , 0
  3775.9     .05       0    4966     .03       0  4973.9     .05       0
Bank Sta=4966,4973.9
XS Rating Curve= 0 ,0
Exp/Cntr=0.3,0.1

Type RM Length L Ch R = 1 ,52037   ,637,637,637
BEGIN DESCRIPTION:
Mapping XS d5be616e
END DESCRIPTION:
XS GIS Cut Line= 3
      2678518.93      6899863.09      2678162.26       6899524.2
      2677204.91      6899385.84
#Sta/Elev= 30
    4508  443.74  4596.3  442.19  4702.6  438.06    4752  437.04  4780.3  435.41
  4808.6  435.45  4815.5  434.58  4843.8  433.84  4879.4  435.53  5022.4  432.84
  5023.6  432.34  5030.6  432.84  5059.6  434.33  5097.3  434.34  5117.5  435.75
  5200.2  436.41  5299.3  434.29  5319.5  435.27  5406.1  435.48  5420.6  434.97
  5430.7  433.53  5501.4  433.84  5546.8  436.15  5602.5  436.58  5622.7  437.99
  5757.7  440.95  5794.4  443.09  5844.9  443.98  5893.3  445.98  5967.3  446.39
#Mann= 3 ,-1 , 0
    4508     .05       0  5022.4     .03       0  5030.6     .05       0
Bank Sta=5022.4,5030.6
XS Rating Curve= 0 ,0
Exp/Cntr=0.3,0.1

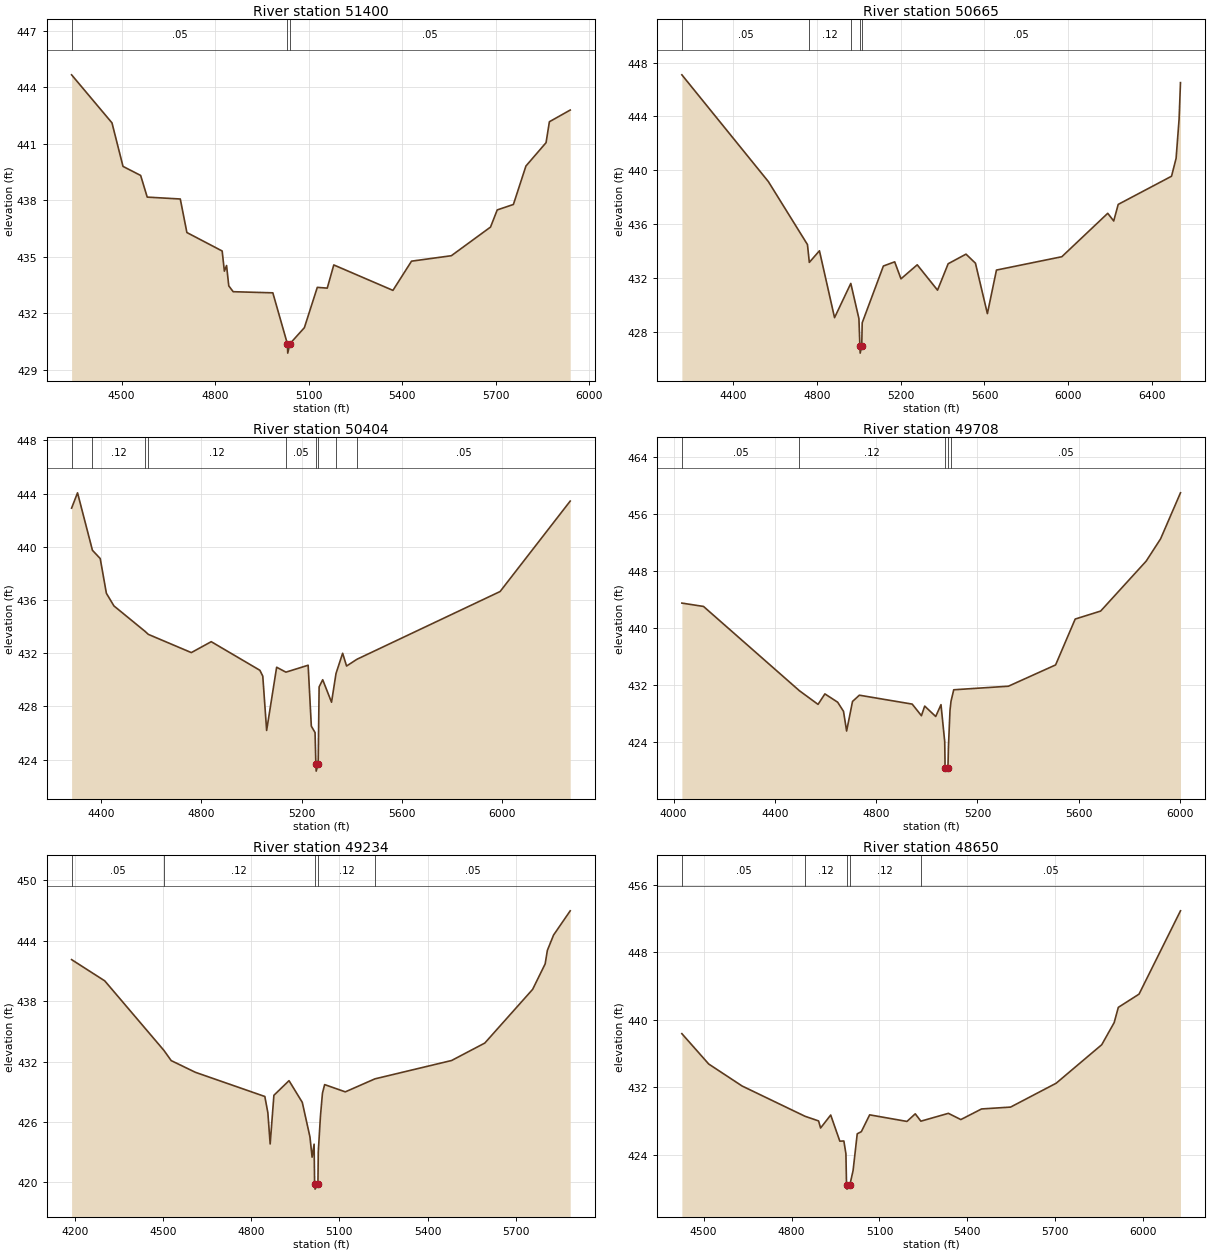
Type RM Length L Ch R = 1 ,51400   ,735,735,735
BEGIN DESCRIPTION:
Mapping XS b7e9284c
END DESCRIPTION:
XS GIS Cut Line= 3
      2679014.91      6899605.38      2678537.47      6899132.28
      2677652.06      6898854.51
#Sta/Elev= 30
  4339.6  444.66  4469.2  442.11  4504.6   439.8  4561.2  439.32  4582.3  438.17
  4688.4  438.07  4709.6  436.29  4822.8  435.31  4829.9  434.24  4836.9  434.54
    4844  433.46  4858.1  433.15  4985.4  433.09    5032  430.39  5033.2  429.89
  5040.3  430.39  5086.6  431.24  5128.1  433.38    5160  433.34    5181  434.57
  5370.8  433.22  5430.4  434.77  5558.3  435.06    5684  436.58  5705.5  437.49
  5757.4  437.78  5797.6  439.82  5862.2  441.06  5872.9  442.17  5939.7  442.79
#Mann= 3 ,-1 , 0
  4339.6     .05       0    5032     .03       0  5040.3     .05       0
Bank Sta=5032,5040.3
XS Rating Curve= 0 ,0
Exp/Cntr=0.3,0.1

Type RM Length L Ch R = 1 ,50665   ,261,261,261
BEGIN DESCRIPTION:
Mapping XS 87fedec4
END DESCRIPTION:
XS GIS Cut Line= 5
      2679571.32      6899536.79      2679107.79      6898833.67
      2678706.74      6898672.21      2678644.24      6898370.13
      2678041.62      6897845.43
#Sta/Elev= 30
  4154.5  447.09  4567.8  439.17  4754.5   434.5  4763.4  433.18  4811.7  434.04
  4883.9  429.08  4961.5  431.62  5000.3  429.01  5005.1  426.95  5006.3  426.45
  5013.7  426.95    5016   428.7  5117.2  432.91  5171.1  433.22  5201.3  431.96
  5278.9     433  5375.9  431.12  5426.7  433.08  5511.9  433.79    5557  433.12
    5614  429.38  5657.4  432.61  5969.7   433.6    6189  436.82  6217.5  436.25
    6239  437.48  6493.8  439.57  6515.6   440.9  6529.9  443.81  6536.5  446.51
#Mann= 5 ,-1 , 0
  4154.5     .05       0  4763.4     .12       0  4961.5     .05       0
  5005.1     .03       0  5013.7     .05       0
Bank Sta=5005.1,5013.7
XS Rating Curve= 0 ,0
Exp/Cntr=0.3,0.1

Type RM Length L Ch R = 1 ,50404   ,696,696,696
BEGIN DESCRIPTION:
Jones Creek 76.0
END DESCRIPTION:
XS GIS Cut Line= 3
      2679898.17      6898876.65      2679171.59      6898597.99
      2678597.35      6897531.56
#Sta/Elev= 30
    4282  442.91  4305.7  444.06  4365.2  439.74  4396.2  439.12  4420.8  436.51
  4450.9  435.56  4574.2  433.66  4588.2  433.42  4759.7  432.05  4839.1  432.87
  5033.3  430.72  5044.8  430.28  5060.2   426.2  5100.1  430.95  5137.1  430.58
  5225.8   431.1  5238.5  426.52  5253.4  426.04  5256.6  423.64  5257.9  423.14
  5265.8  423.64  5269.6  429.47  5283.9  430.01  5319.1  428.32    5337  430.48
  5363.4     432  5379.1  431.04  5420.7  431.55  5991.6  436.64  6271.4  443.44
#Mann= 9 ,-1 , 0
    4282     .05       0  4365.2     .12       0  4574.2     .05       0
  4588.2     .12       0  5137.1     .05       0  5256.6     .07       0
  5265.8     .05       0    5337     .12       0  5420.7     .05       0
Bank Sta=5256.6,5265.8
XS Rating Curve= 0 ,0
Exp/Cntr=0.3,0.1

Type RM Length L Ch R = 1 ,49708   ,474,474,474
BEGIN DESCRIPTION:
Jones Creek 74.0
END DESCRIPTION:
XS GIS Cut Line= 3
      2679928.75       6898808.5      2679361.86      6898024.36
        2678776.      6897210.99
#Sta/Elev= 30
  4032.4  443.54  4117.9  443.07  4496.7  431.24  4570.4  429.32  4597.5  430.79
  4647.8  429.63    4671  428.35  4683.3  425.58  4706.6  429.73  4733.6  430.61
  4942.4  429.36  4978.9  427.73  4991.8  429.08  5035.3  427.62  5056.2  429.28
  5070.9   424.1  5072.4  420.45    5074  419.95  5083.7  420.45  5085.6  423.36
  5091.8   428.5  5095.8  429.76  5106.5  431.37  5322.5  431.87    5509  434.86
  5586.4   441.3    5687  442.42  5866.8  449.43  5923.8  452.56  6002.4  459.02
#Mann= 5 ,-1 , 0
  4032.4     .05       0  4496.7     .12       0  5072.4     .07       0
  5083.7     .12       0  5095.8     .05       0
Bank Sta=5072.4,5083.7
XS Rating Curve= 0 ,0
Exp/Cntr=0.3,0.1

Type RM Length L Ch R = 1 ,49234   ,584,584,584
BEGIN DESCRIPTION:
Mapping XS 7db10001
END DESCRIPTION:
XS GIS Cut Line= 3
      2679954.79      6898660.91      2679776.84      6897897.04
      2679161.53       6897225.4
#Sta/Elev= 30
  4189.4  442.11  4302.2     440  4503.1  433.11  4528.1  432.09  4610.3  430.93
  4846.4  428.53  4856.7  426.91  4864.5  423.82  4877.2  428.65  4928.6   430.1
  4973.7  427.95  4999.7  424.53  5007.1  422.51  5013.9   423.8  5015.6  419.84
  5017.2  419.34  5026.9  419.84  5028.1  423.03  5035.5   426.6  5042.3  428.86
  5049.7  429.71    5120  428.99  5220.7  430.28  5481.3   432.1  5594.2  433.83
  5756.9  439.16  5799.5  441.69  5806.9  443.02  5827.9  444.54  5884.6  446.95
#Mann= 5 ,-1 , 0
  4189.4     .05       0  4503.1     .12       0  5015.6     .07       0
  5026.9     .12       0  5220.7     .05       0
Bank Sta=5015.6,5026.9
XS Rating Curve= 0 ,0
Exp/Cntr=0.3,0.1

Type RM Length L Ch R = 1 ,48650   ,450,450,450
BEGIN DESCRIPTION:
Jones Creek 72.0
END DESCRIPTION:
XS GIS Cut Line= 3
      2680426.01      6898311.03        2680276.        6897761.
      2679475.99      6896960.99
#Sta/Elev= 30
  4425.7  438.37  4517.3  434.77  4631.3  432.16    4846  428.57  4892.2  428.02
  4899.1  427.18  4933.6  428.72  4964.7  425.62  4978.5  425.64  4985.5  424.13
  4987.6  420.43  4989.1  419.93  4998.9  420.43    5010  422.14  5024.1  426.49
  5038.2  426.75  5066.5  428.74  5193.8  427.96  5222.1  428.86  5241.3  427.99
  5335.2  428.92  5377.7  428.18  5448.4  429.44  5547.4  429.66  5702.9  432.49
  5858.5  437.06  5900.9  439.68  5915.1  441.49  5985.8  443.06  6127.2  452.94
#Mann= 5 ,-1 , 0
  4425.7     .05       0    4846     .12       0  4987.6     .07       0
  4998.9     .12       0  5241.3     .05       0
Bank Sta=4987.6,4998.9
XS Rating Curve= 0 ,0
Exp/Cntr=0.3,0.1

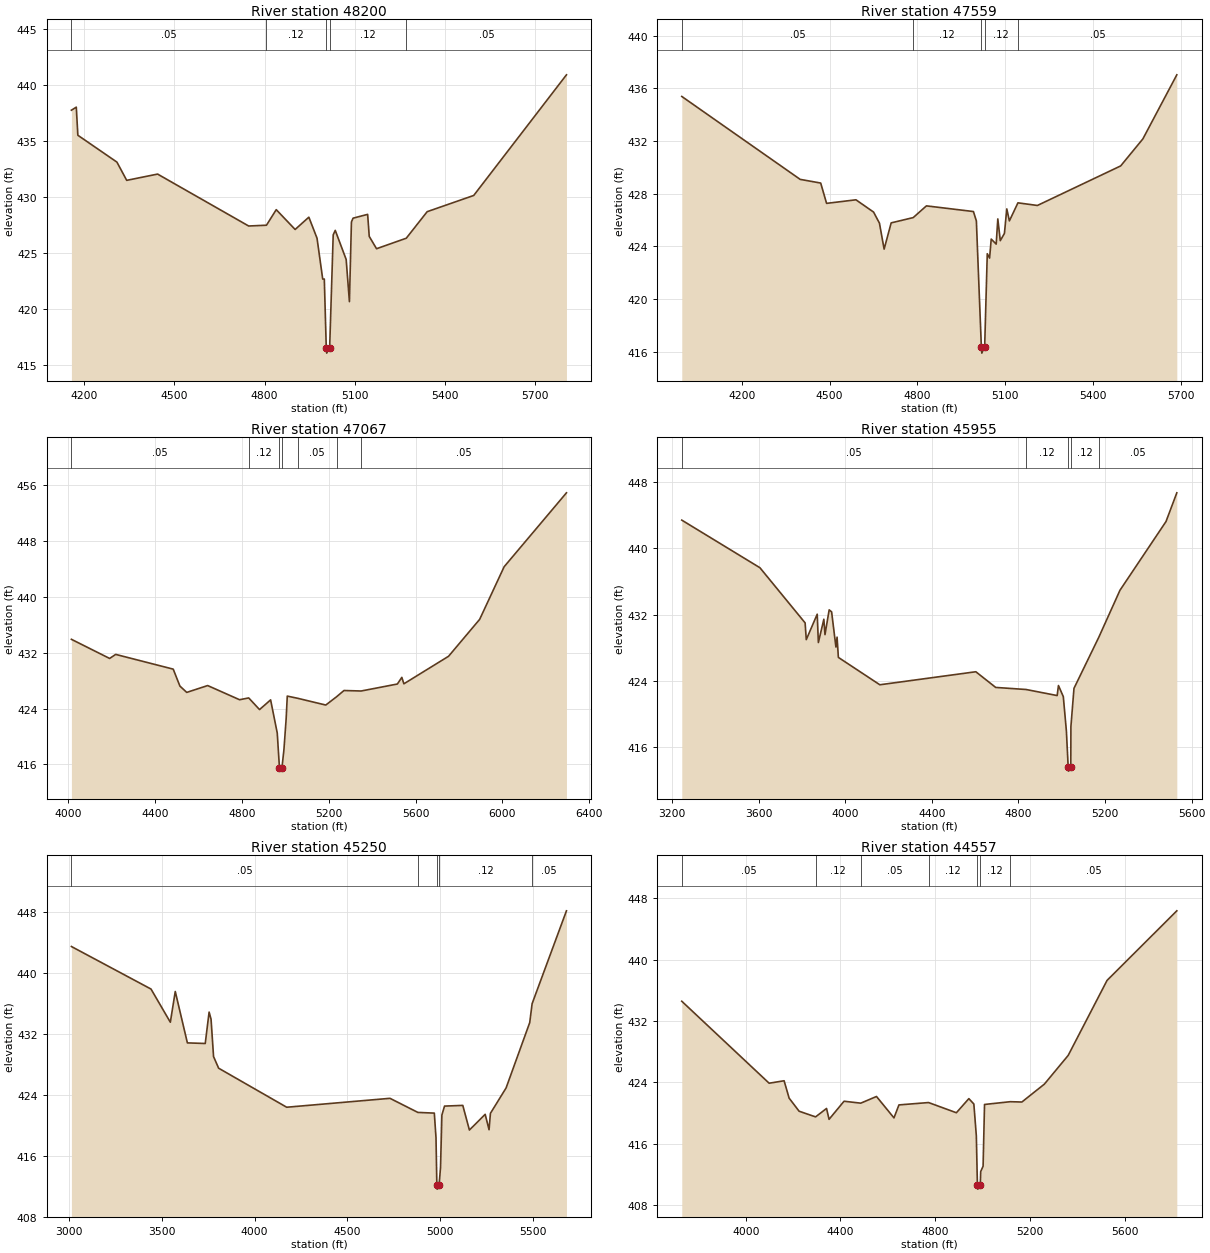
Type RM Length L Ch R = 1 ,48200   ,641,641,641
BEGIN DESCRIPTION:
Jones Creek 71.0
END DESCRIPTION:
XS GIS Cut Line= 3
      2680775.99      6898260.96        2680526.        6897461.
      2680225.99      6896710.99
#Sta/Elev= 30
  4157.6  437.75  4173.8  438.02    4179  435.51  4308.9  433.11  4341.4  431.48
  4444.1  432.04  4746.9   427.4  4806.1  427.47  4838.6  428.86  4901.4  427.09
    4947  428.19  4974.2  426.31  4993.1  422.66  4998.4  422.66  5004.9  416.54
  5006.4  416.04  5016.2  416.54    5028  426.61  5034.8  427.01  5071.1  424.41
  5081.9  420.64  5088.6  427.76    5094   428.1  5142.5  428.44  5147.8  426.47
  5172.1  425.37    5271  426.31  5340.4  428.68  5495.2  430.13  5803.5  440.91
#Mann= 5 ,-1 , 0
  4157.6     .05       0  4806.1     .12       0  5004.9     .07       0
  5016.2     .12       0    5271     .05       0
Bank Sta=5004.9,5016.2
XS Rating Curve= 0 ,0
Exp/Cntr=0.3,0.1

Type RM Length L Ch R = 1 ,47559   ,492,492,492
BEGIN DESCRIPTION:
Mapping XS f79c6d9b
END DESCRIPTION:
XS GIS Cut Line= 3
      2681031.47      6898094.11      2680942.93      6897083.67
      2680333.51      6896786.78
#Sta/Elev= 30
  3994.8  435.38  4399.5  429.09  4469.7  428.81  4489.8  427.27  4590.2  427.54
  4650.4  426.61  4670.5  425.77  4686.5   423.8  4710.6  425.79  4785.9  426.19
  4831.1  427.08  4991.7  426.65  5001.8  425.94  5018.8  416.41  5020.4  415.91
  5030.2  416.41  5039.1  423.45    5047  423.12  5052.6  424.56  5069.6  424.18
  5075.1  426.09  5083.6  424.44  5097.7  424.99  5105.8  426.85  5114.7  425.94
  5143.9  427.31  5210.4  427.11  5495.1  430.11    5571  432.16    5687  437.02
#Mann= 5 ,-1 , 0
  3994.8     .05       0  4785.9     .12       0  5018.8     .07       0
  5030.2     .12       0  5143.9     .05       0
Bank Sta=5018.8,5030.2
XS Rating Curve= 0 ,0
Exp/Cntr=0.3,0.1

Type RM Length L Ch R = 1 ,47067   ,1112,1112,1112
BEGIN DESCRIPTION:
Jones Creek 68.0
END DESCRIPTION:
XS GIS Cut Line= 3
      2681176.65      6898091.07      2681367.62      6897144.87
      2681075.99      6895860.96
#Sta/Elev= 30
  4013.8  433.92  4189.9  431.18  4217.9  431.76  4483.1  429.65  4513.8  427.23
  4545.4  426.32  4641.8   427.3    4789  425.27    4831  425.53    4881  423.86
    4932  425.25  4962.6   420.5  4972.7  415.55  4974.3  415.05  4984.3  415.55
  4993.3  418.09  5003.6  422.53  5008.8  425.79  5056.3  425.48  5186.3  424.51
  5236.6  425.71  5270.2  426.59  5349.4  426.52  5516.3  427.52  5536.8  428.47
  5546.3  427.55  5752.2  431.49  5895.7  436.78  6008.5  444.31  6295.7  454.89
#Mann= 7 ,-1 , 0
  4013.8     .05       0    4831     .12       0  4972.7     .07       0
  4984.3     .12       0  5056.3     .05       0  5236.6     .12       0
  5349.4     .05       0
Bank Sta=4972.7,4984.3
XS Rating Curve= 0 ,0
Exp/Cntr=0.3,0.1

Type RM Length L Ch R = 1 ,45955   ,705,705,705
BEGIN DESCRIPTION:
Jones Creek 67.0
END DESCRIPTION:
XS GIS Cut Line= 3
      2682425.99      6897960.96        2681826.        6896311.
      2681425.98      6895960.98
#Sta/Elev= 30
  3244.3   443.4  3605.4  437.66  3814.2  431.01  3819.5  428.99  3870.1  432.06
  3875.4  428.64  3900.7  431.45    3906  429.59  3925.3  432.58  3936.6  432.34
  3956.5   428.1  3961.8  429.29  3967.8  426.85  4159.4  423.55  4602.9  425.12
  4694.7  423.23    4835  422.98  4978.7  422.25  4984.7  423.46  5007.1  422.12
  5021.3  417.98  5029.6  413.64  5031.2  413.14  5041.6  413.64  5042.2  418.51
  5056.4  423.12  5170.9  429.27    5269  434.95  5481.6  443.23  5531.5  446.69
#Mann= 5 ,-1 , 0
  3244.3     .05       0    4835     .12       0  5029.6     .07       0
  5041.6     .12       0  5170.9     .05       0
Bank Sta=5029.6,5041.6
XS Rating Curve= 0 ,0
Exp/Cntr=0.3,0.1

Type RM Length L Ch R = 1 ,45250   ,693,693,693
BEGIN DESCRIPTION:
Jones Creek 66.0
END DESCRIPTION:
XS GIS Cut Line= 3
      2682876.01      6897811.03      2682291.07      6895911.14
      2681825.97      6895410.97
#Sta/Elev= 30
  3012.1  443.45  3441.6  437.87  3545.8  433.52  3572.4  437.55  3637.8  430.81
  3734.1  430.73    3755  434.85  3765.5  433.91    3779  429.01  3806.4  427.49
  4173.6  422.37  4730.8  423.54  4881.4  421.69  4970.1   421.6  4979.2  418.35
  4983.7  412.13  4985.3  411.63  4995.7  412.13  5003.6  414.49  5010.9  421.34
  5025.1  422.52  5123.7  422.61  5159.4  419.38  5244.5  421.44  5265.4  419.42
  5272.8  421.57  5357.3   424.9  5484.8  433.47  5497.7  435.95    5683  448.13
#Mann= 5 ,-1 , 0
  3012.1     .05       0  4881.4     .12       0  4983.7     .07       0
  4995.7     .12       0  5497.7     .05       0
Bank Sta=4983.7,4995.7
XS Rating Curve= 0 ,0
Exp/Cntr=0.3,0.1

Type RM Length L Ch R = 1 ,44557   ,680,680,680
BEGIN DESCRIPTION:
Jones Creek 65.0
END DESCRIPTION:
XS GIS Cut Line= 3
      2683125.99      6896810.97        2682726.        6895611.
      2682050.97      6895135.98
#Sta/Elev= 30
    3730  434.59  4098.9   423.9  4162.1  424.22  4183.2  421.96  4225.4  420.25
    4295  419.51  4341.3  420.61  4351.9  419.19  4415.1  421.55  4485.8   421.3
  4552.2  422.17    4626  419.38    4647  421.07    4772  421.38  4889.5  420.05
  4942.2  421.89  4963.3  421.19  4973.8  417.02  4978.3  410.59    4980  410.09
  4990.4  410.59  4992.2  412.38  5002.3  413.08  5008.4  421.13    5117  421.49
  5166.1  421.45    5261  423.78  5361.7  427.53  5525.8  437.31  5820.3  446.38
#Mann= 7 ,-1 , 0
    3730     .05       0    4295     .12       0  4485.8     .05       0
    4772     .12       0  4978.3     .07       0  4990.4     .12       0
    5117     .05       0
Bank Sta=4978.3,4990.4
XS Rating Curve= 0 ,0
Exp/Cntr=0.3,0.1