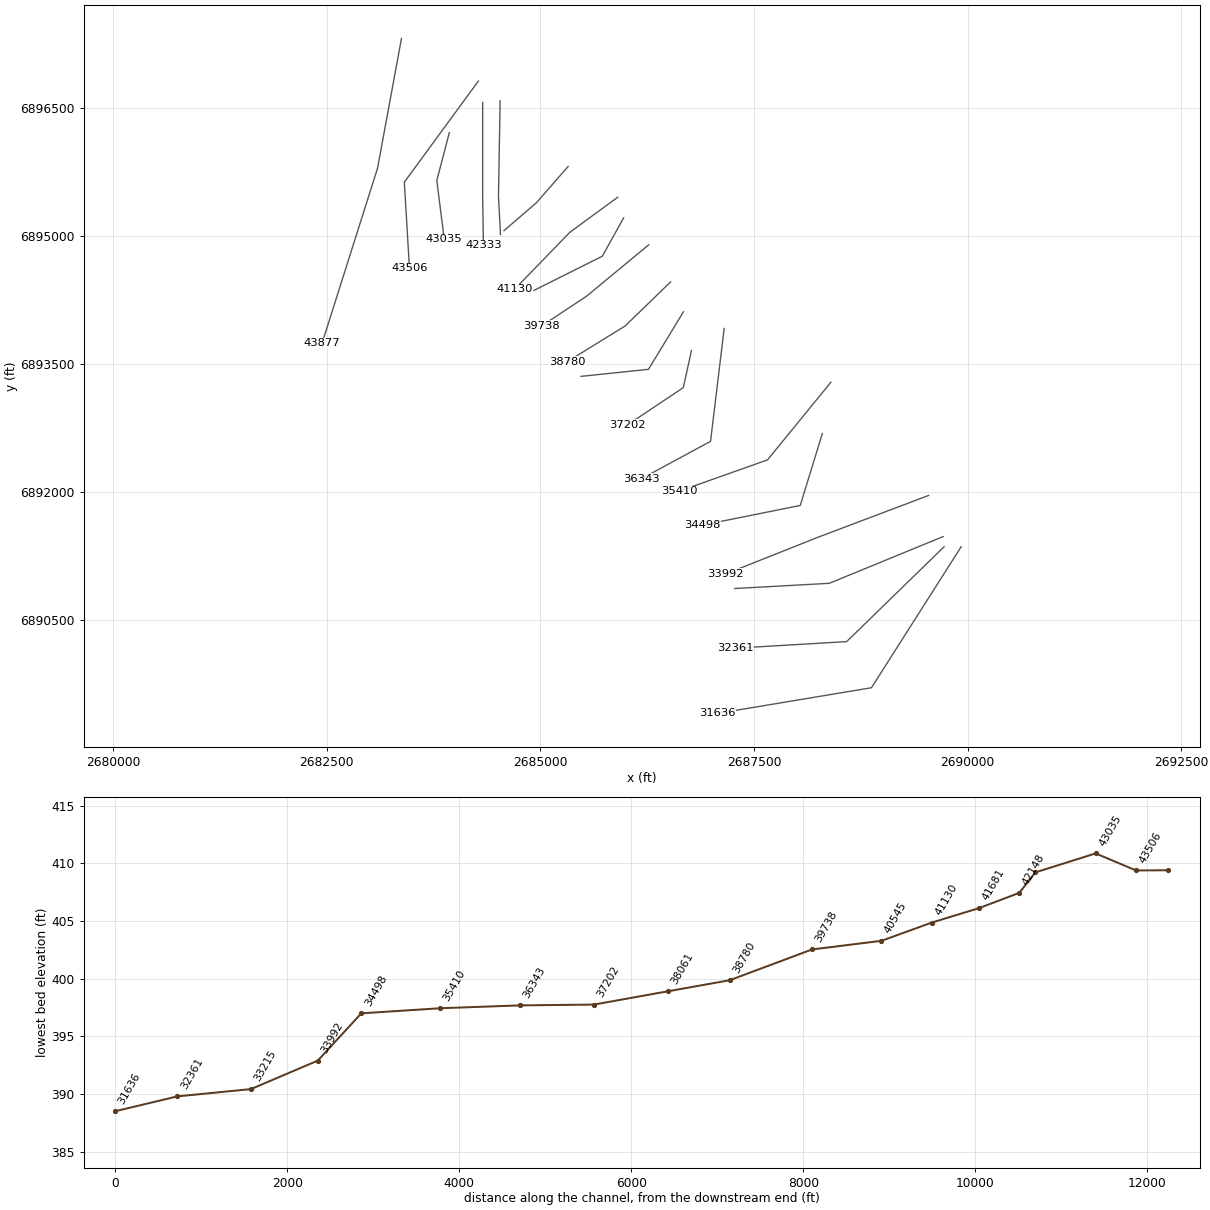
HEC-RAS study Jones Creek.prj: Jones Creek Base Level Engineering

--- Jones Creek.g01 (geometry) --- (continued)

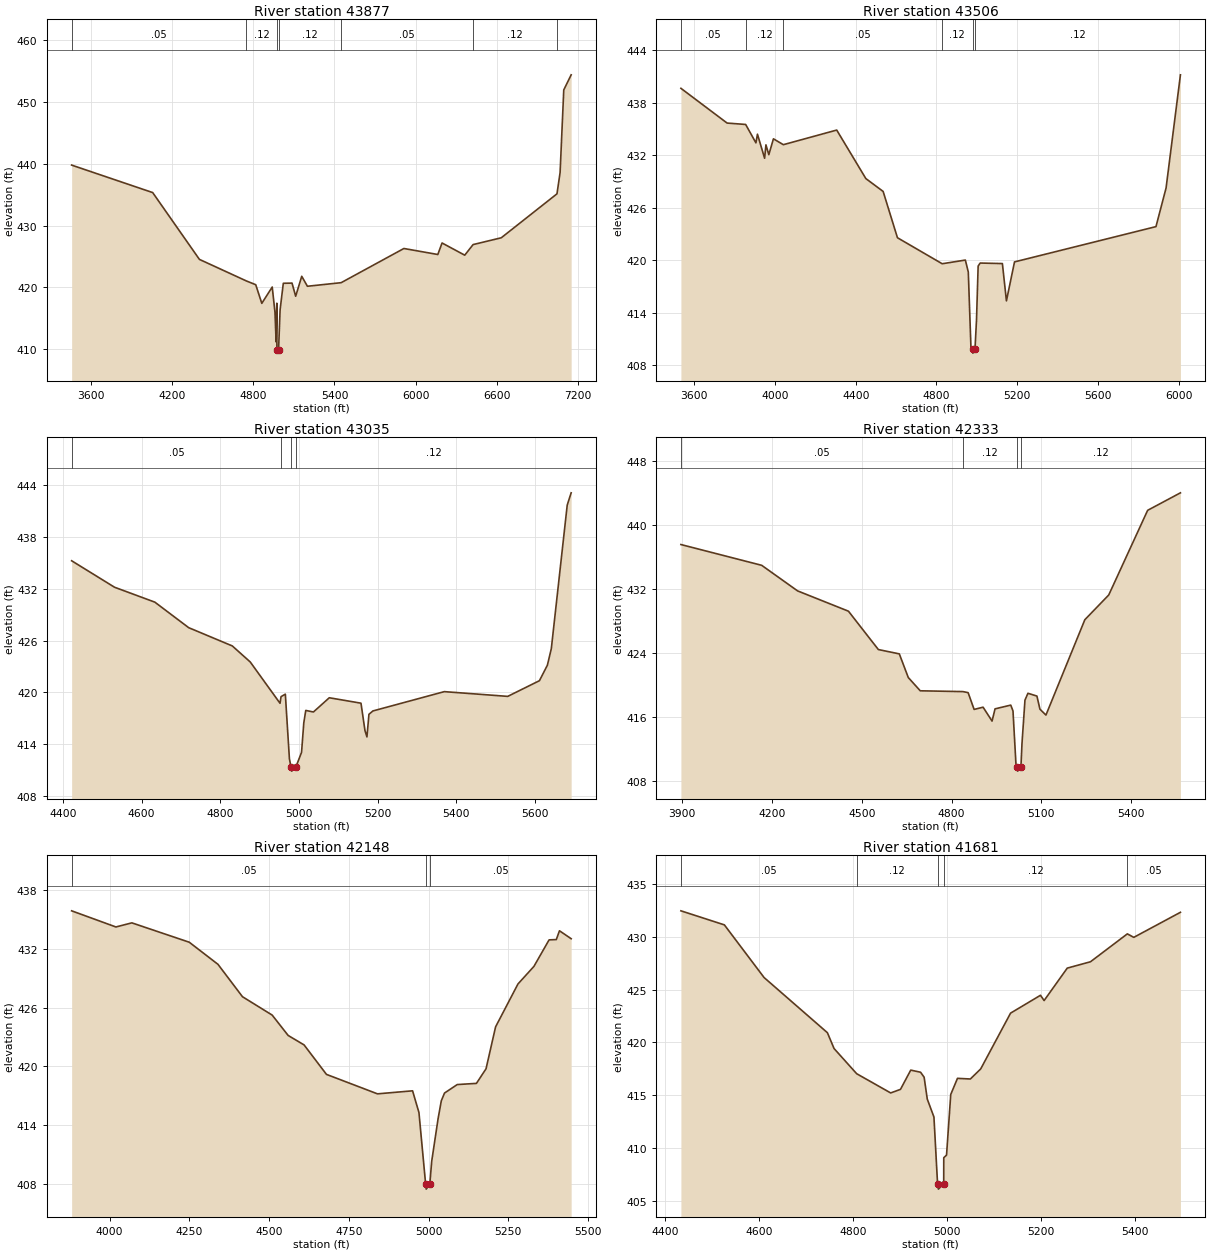
Type RM Length L Ch R = 1 ,43877   ,371,371,371
BEGIN DESCRIPTION:
Jones Creek 64.0
END DESCRIPTION:
XS GIS Cut Line= 3
        2683376.      6897310.99      2683095.84       6895791.4
      2682445.61       6893740.2
#Sta/Elev= 30
  3454.8  439.77  4054.7  435.33  4400.5  424.54  4748.9  421.05  4817.4  420.45
  4862.2  417.44  4939.4  420.08  4959.7  415.99  4968.2  411.22  4973.3  417.46
    4974   409.9  4975.7   409.4  4986.2   409.9  4997.7  416.41  5021.4  420.68
  5085.9  420.71  5112.9  418.59  5157.8  421.81  5199.7   420.2  5449.7  420.78
  5913.9   426.3  6164.9  425.33  6196.3  427.19  6364.2  425.22    6426  426.93
  6634.6  428.03  7046.9  435.13    7070  438.58  7097.1  451.91  7151.8  454.35
#Mann= 7 ,-1 , 0
  3454.8     .05       0  4748.9     .12       0    4974     .07       0
  4986.2     .12       0  5449.7     .05       0    6426     .12       0
  7046.9     .05       0
Bank Sta=4974,4986.2
XS Rating Curve= 0 ,0
Exp/Cntr=0.3,0.1

Type RM Length L Ch R = 1 ,43506   ,471,471,471
BEGIN DESCRIPTION:
Jones Creek 63.0
END DESCRIPTION:
XS GIS Cut Line= 3
      2684275.98      6896810.97      2683409.34      6895627.69
       2683468.9      6894619.94
#Sta/Elev= 30
  3533.3  439.63  3762.2  435.66  3854.2   435.5  3905.1   433.4  3912.7  434.39
  3948.2  431.64  3954.7  433.17  3969.1  432.05  3991.9  433.86  4041.1  433.19
  4305.6  434.86    4450  429.32  4535.7  427.85  4606.7  422.56  4828.5  419.59
  4943.3  420.01  4957.9  418.64  4971.1  409.96  4978.8  409.88  4980.5  409.38
  4991.2  409.88  4998.6  413.18  5006.7  419.32  5016.7  419.67  5126.9  419.61
  5146.9  415.35    5187   419.8  5888.2  423.83  5938.3  428.24  6009.5  441.17
#Mann= 6 ,-1 , 0
  3533.3     .05       0  3854.2     .12       0  4041.1     .05       0
  4828.5     .12       0  4978.8     .07       0  4991.2     .12       0
Bank Sta=4978.8,4991.2
XS Rating Curve= 0 ,0
Exp/Cntr=0.3,0.1

Type RM Length L Ch R = 1 ,43035   ,702,702,702
BEGIN DESCRIPTION:
Jones Creek 62.0
END DESCRIPTION:
XS GIS Cut Line= 3
      2683935.62      6896206.48      2683789.36       6895647.6
      2683875.99      6894961.04
#Sta/Elev= 30
  4422.3  435.26  4531.3  432.19  4633.8  430.46  4719.8   427.5  4830.7  425.38
  4876.3  423.52    4952  418.73  4954.6   419.5  4965.5  419.79  4975.8  412.32
  4979.7  411.36  4981.5  410.86  4992.5  411.36  5006.7  413.04  5012.4  416.46
  5017.4   417.9  5036.9  417.72  5077.2  419.37  5157.8  418.74  5167.9  415.57
  5172.9  414.83    5178  417.45  5188.1  417.84  5369.5  420.08  5530.8  419.53
  5611.4  421.35  5631.6  423.15  5641.6  425.07    5682  441.72    5692  443.14
#Mann= 4 ,-1 , 0
  4422.3     .05       0  4954.6     .12       0  4979.7     .07       0
  4992.5     .12       0
Bank Sta=4979.7,4992.5
XS Rating Curve= 0 ,0
Exp/Cntr=0.3,0.1

Type RM Length L Ch R = 1 ,42333   ,185,185,185
BEGIN DESCRIPTION:
Jones Creek 60.0
END DESCRIPTION:
XS GIS Cut Line= 3
        2684326.      6896561.04        2684326.        6895461.
      2684334.93      6894891.41
#Sta/Elev= 30
  3895.4  437.56  4165.4  434.96  4285.4  431.76  4455.4  429.22  4555.4  424.42
  4625.4  423.88  4655.4  420.92  4695.4  419.26  4838.2  419.16  4855.4  419.03
  4875.4  416.93  4905.4  417.21  4935.4  415.47  4945.4     417  4997.9  417.47
  5005.4  416.74  5015.4  410.01  5018.9  409.71  5020.8  409.21  5031.9  409.71
  5035.4  412.63  5045.4  418.09  5055.4  418.95  5085.4   418.6  5095.5  416.96
  5115.5  416.22  5245.5  428.15  5325.5  431.25  5455.5  441.84  5565.1  444.03
#Mann= 4 ,-1 , 0
  3895.4     .05       0  4838.2     .12       0  5018.9     .07       0
  5031.9     .12       0
Bank Sta=5018.9,5031.9
XS Rating Curve= 0 ,0
Exp/Cntr=0.3,0.1

Type RM Length L Ch R = 1 ,42148   ,467,467,467
BEGIN DESCRIPTION:
Jones Creek 59.0
END DESCRIPTION:
XS GIS Cut Line= 3
      2684530.24      6896579.74        2684511.        6895461.
       2684534.5      6895014.42
#Sta/Elev= 30
  3881.1  435.89  4019.9  434.24  4069.9  434.66  4249.9  432.68  4339.9  430.42
  4416.7  427.11  4509.9  425.23  4559.9  423.15  4609.9  422.18    4680  419.17
    4840  417.18    4950  417.49    4970  415.27    4991  407.94  4992.8  407.44
    5004  407.94    5010  410.29    5030  414.64  5040.1  416.47  5050.1  417.26
  5090.1  418.13  5150.2  418.25  5180.3  419.74  5210.3  424.03  5280.4  428.41
  5330.5  430.21    5378  432.92  5400.6  432.95  5410.6  433.85  5447.2  433.04
#Mann= 3 ,-1 , 0
  3881.1     .05       0    4991     .03       0    5004     .05       0
Bank Sta=4991,5004
XS Rating Curve= 0 ,0
Exp/Cntr=0.3,0.1

Type RM Length L Ch R = 1 ,41681   ,551,551,551
BEGIN DESCRIPTION:
Jones Creek 58.0
END DESCRIPTION:
XS GIS Cut Line= 3
      2685325.99      6895810.98      2684953.19      6895384.96
      2684576.01      6895061.01
#Sta/Elev= 30
  4433.9  432.45  4526.4  431.12  4610.9  426.14  4745.7  420.92  4759.9  419.42
    4808  417.04  4880.4  415.22  4901.3  415.56  4923.1  417.38    4944  417.18
  4951.6  416.71  4958.3  414.64  4972.5  412.94  4980.2  406.62    4982  406.12
  4993.3  406.62  4993.4  409.09  4999.3  409.34  5008.3  415.08  5022.6   416.6
    5050  416.54    5072  417.49  5135.6  422.77  5199.3  424.46    5207  423.96
  5256.3  427.03  5305.7  427.63  5384.2  430.27  5397.9  429.94  5497.2  432.31
#Mann= 5 ,-1 , 0
  4433.9     .05       0    4808     .12       0  4980.2     .07       0
  4993.3     .12       0  5384.2     .05       0
Bank Sta=4980.2,4993.3
XS Rating Curve= 0 ,0
Exp/Cntr=0.3,0.1

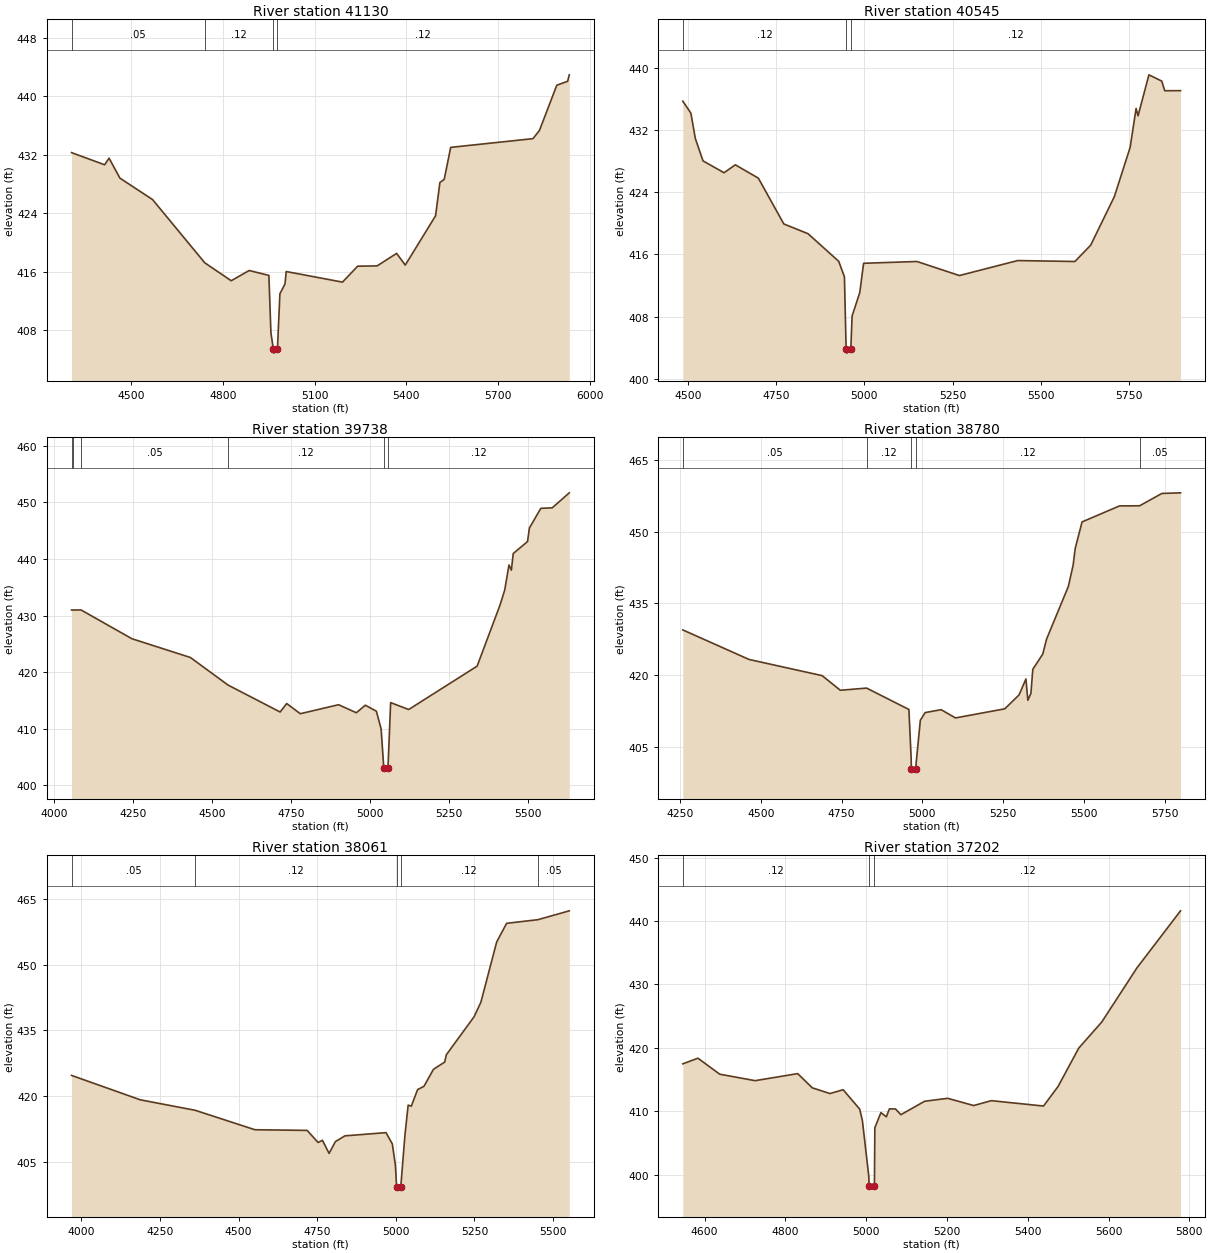
Type RM Length L Ch R = 1 ,41130   ,585,585,585
BEGIN DESCRIPTION:
Jones Creek 57.0
END DESCRIPTION:
XS GIS Cut Line= 3
      2685906.08      6895451.27      2685346.41      6895041.23
       2684697.5      6894371.83
#Sta/Elev= 30
  4306.2  432.28  4414.2  430.62  4428.8  431.52  4464.3  428.79  4570.9  425.86
  4741.5  417.21  4827.9  414.76  4886.6  416.16  4950.9  415.49  4957.6  407.64
  4965.7  405.36  4967.6  404.86  4978.8  405.36  4986.9  412.97  5003.6  414.33
  5007.5  416.02  5191.4  414.57  5240.9  416.75  5304.6  416.79  5368.2   418.5
  5396.5   416.9  5495.5  423.64  5509.6  428.19  5523.8  428.63  5544.9     433
  5813.7  434.19    5835  435.32  5891.6   441.5  5926.9  442.03  5932.3  442.92
#Mann= 4 ,-1 , 0
  4306.2     .05       0  4741.5     .12       0  4965.7     .07       0
  4978.8     .12       0
Bank Sta=4965.7,4978.8
XS Rating Curve= 0 ,0
Exp/Cntr=0.3,0.1

Type RM Length L Ch R = 1 ,40545   ,807,807,807
BEGIN DESCRIPTION:
Jones Creek 56.0
END DESCRIPTION:
XS GIS Cut Line= 3
      2685975.99      6895210.98        2685726.        6894761.
      2684925.99      6894360.99
#Sta/Elev= 30
  4485.8  435.76  4508.7  434.21  4521.2  430.95    4543  428.06  4602.5  426.53
  4634.5  427.55  4699.7  425.83  4771.8  419.93  4840.4  418.67  4927.3  415.11
  4943.4  413.11  4948.2  403.78  4950.1  403.28  4961.4  403.78  4965.1  408.06
  4986.8  411.08  4997.7  414.86  5148.7  415.09  5268.9  413.28  5433.8  415.21
  5595.9  415.09  5640.6  417.19  5707.7  423.46  5752.4  429.81  5769.2  434.82
  5774.8  433.87  5805.5  439.15  5841.9  438.34  5850.3   437.1    5895  437.11
#Mann= 3 ,-1 , 0
  4485.8     .12       0  4948.2     .07       0  4961.4     .12       0
Bank Sta=4948.2,4961.4
XS Rating Curve= 0 ,0
Exp/Cntr=0.3,0.1

Type RM Length L Ch R = 1 ,39738   ,958,958,958
BEGIN DESCRIPTION:
Jones Creek 55.0
END DESCRIPTION:
XS GIS Cut Line= 3
      2686270.71      6894895.75       2685542.5      6894293.79
      2685016.96      6893945.62
#Sta/Elev= 30
  4055.2  430.98  4059.5  430.98  4085.1     431  4246.3  425.91  4431.3   422.6
  4550.5  417.73  4715.3  412.97  4736.1  414.47  4779.1  412.67  4900.3  414.26
  4956.5  412.84  4984.9  414.17  5019.9  413.12    5035  409.98  5043.4  403.03
  5045.3  402.53  5056.6  403.03  5065.1  414.63  5122.2  413.41  5338.8  421.07
    5411  431.82  5426.1  434.51  5439.6  438.94  5447.1  438.02  5453.1  440.96
  5498.3  443.07  5504.3  445.47  5540.4  448.94  5576.5  449.03  5630.4  451.68
#Mann= 6 ,-1 , 0
  4055.2     .05       0  4059.5     .12       0  4085.1     .05       0
  4550.5     .12       0  5043.4     .07       0  5056.6     .12       0
Bank Sta=5043.4,5056.6
XS Rating Curve= 0 ,0
Exp/Cntr=0.3,0.1

Type RM Length L Ch R = 1 ,38780   ,719,719,719
BEGIN DESCRIPTION:
Jones Creek 53.0
END DESCRIPTION:
XS GIS Cut Line= 3
      2686525.99      6894460.99      2685993.31      6893944.73
      2685312.91      6893525.09
#Sta/Elev= 30
  4258.2  429.41  4463.3  423.23  4689.7  419.84    4746  416.78  4827.2  417.24
  4958.3  412.76  4965.4  402.35  4965.8  400.36  4967.7  399.86    4979  400.36
  4993.7   410.5  5008.6  412.11  5058.1  412.72  5102.6  410.99  5255.3   412.9
  5299.4  415.81  5320.7  419.15  5326.6  414.68  5336.1  416.14    5342  421.17
  5372.8  424.35  5384.6  427.49    5452   438.5  5466.8  442.95  5473.2  446.43
  5494.5  452.01  5610.4  455.36  5672.8  455.39  5741.7  457.97  5799.4   458.1
#Mann= 5 ,-1 , 0
  4258.2     .05       0  4827.2     .12       0  4965.8     .07       0
    4979     .12       0  5672.8     .05       0
Bank Sta=4965.8,4979
XS Rating Curve= 0 ,0
Exp/Cntr=0.3,0.1

Type RM Length L Ch R = 1 ,38061   ,859,859,859
BEGIN DESCRIPTION:
Jones Creek 51.0
END DESCRIPTION:
XS GIS Cut Line= 3
        2686676.      6894111.01      2686266.35       6893437.4
      2685476.43      6893354.94
#Sta/Elev= 30
  3968.9  424.77  4187.8  419.21  4361.8  416.84  4552.1  412.41    4718  412.26
  4752.8  409.51  4766.7  410.01  4787.8  407.03  4807.9  409.71  4838.1  411.02
  4968.8  411.75  4988.9  409.18  4998.9   404.2  5002.4   399.4  5004.3   398.9
  5015.7   399.4  5029.1  411.26  5039.2  418.01  5049.2  417.77  5069.3  421.55
  5089.4  422.28  5119.6  426.15  5155.4  427.81  5160.5  429.45  5248.8  438.11
  5270.4   441.4  5320.7  455.12  5352.3  459.37  5451.7  460.19  5551.5  462.21
#Mann= 5 ,-1 , 0
  3968.9     .05       0  4361.8     .12       0  5002.4     .07       0
  5015.7     .12       0  5451.7     .05       0
Bank Sta=5002.4,5015.7
XS Rating Curve= 0 ,0
Exp/Cntr=0.3,0.1

Type RM Length L Ch R = 1 ,37202   ,859,859,859
BEGIN DESCRIPTION:
Jones Creek 50.0
END DESCRIPTION:
XS GIS Cut Line= 3
      2686769.83       6893658.8      2686674.12      6893223.18
      2686019.99      6892787.05
#Sta/Elev= 30
    4546  417.49  4583.4  418.38  4637.4  415.86  4724.9  414.84  4830.4  415.95
  4866.5  413.71  4910.3  412.81    4943  413.41    4984  410.35  4990.6  408.54
  5006.4   399.8  5007.1  398.25    5009  397.75  5020.4  398.25  5021.4  407.42
  5036.4   409.8  5049.9  409.15  5057.4  410.39  5072.5  410.38  5085.9  409.48
  5144.6  411.59  5201.7  412.06  5266.2  410.92  5309.8  411.69    5439  410.84
  5475.1  413.93  5526.2  419.97  5583.2  424.08  5670.4  432.62  5778.2   441.6
#Mann= 3 ,-1 , 0
    4546     .12       0  5007.1     .07       0  5020.4     .12       0
Bank Sta=5007.1,5020.4
XS Rating Curve= 0 ,0
Exp/Cntr=0.3,0.1

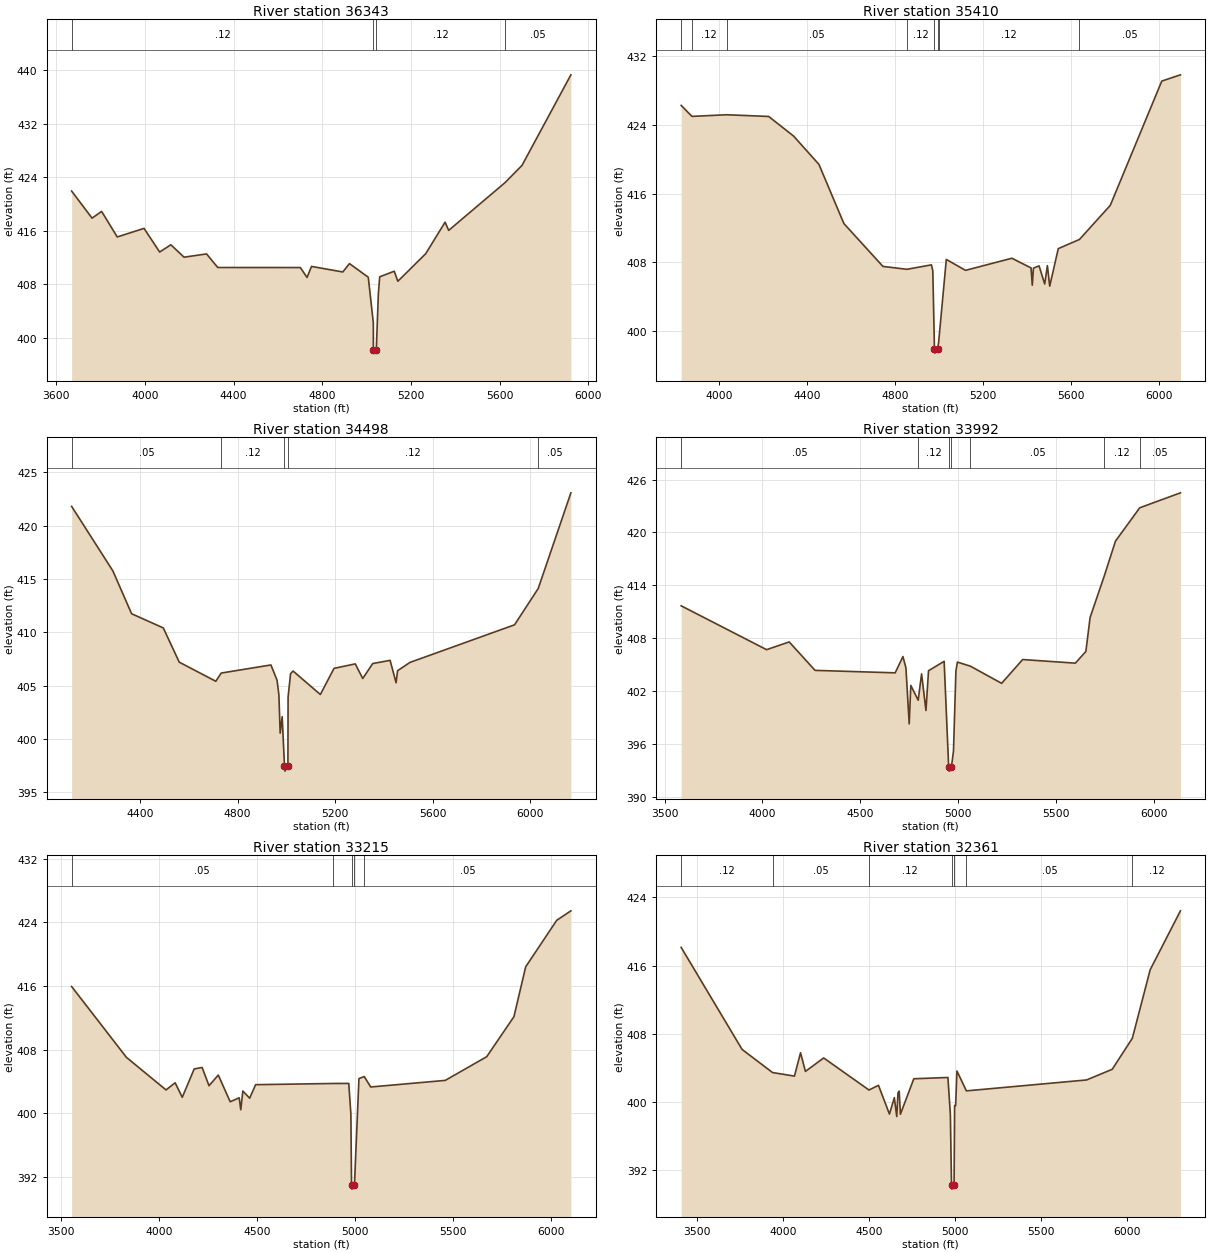
Type RM Length L Ch R = 1 ,36343   ,933,933,933
BEGIN DESCRIPTION:
Jones Creek 49.0
END DESCRIPTION:
XS GIS Cut Line= 3
      2687152.34      6893915.35      2686992.66      6892594.26
      2686181.89       6892156.1
#Sta/Elev= 30
  3669.3  421.92  3761.5  417.87  3804.6  418.88  3875.1  415.06    3996  416.34
  4066.5   412.8  4116.9  413.89  4176.4  412.03    4278  412.52  4328.4  410.49
  4701.1  410.48  4731.3     409  4751.5  410.65  4892.5  409.82  4922.7  411.07
  5007.6  409.03  5030.3   402.2  5030.5  398.18  5032.4  397.68  5043.8  398.18
    5053  406.52  5059.1   409.1  5124.7  409.93  5140.9  408.43  5266.6  412.55
  5354.1  417.27  5370.3  416.04    5624  423.17    5701  425.76  5921.6  439.31
#Mann= 4 ,-1 , 0
  3669.3     .12       0  5030.5     .07       0  5043.8     .12       0
    5624     .05       0
Bank Sta=5030.5,5043.8
XS Rating Curve= 0 ,0
Exp/Cntr=0.3,0.1

Type RM Length L Ch R = 1 ,35410   ,912,912,912
BEGIN DESCRIPTION:
Jones Creek 47.0
END DESCRIPTION:
XS GIS Cut Line= 3
        2688401.      6893286.01      2687659.27      6892377.42
      2686626.02      6892011.01
#Sta/Elev= 30
  3827.1  426.28    3876     425  4033.4  425.19  4224.9  424.99  4338.3   422.7
  4453.2  419.41  4566.6  412.52    4744  407.53  4853.2  407.19  4964.4  407.71
  4970.8  407.01  4978.2  397.93  4980.2  397.43  4992.2  397.93  4997.2  398.68
  5032.1  408.34  5119.4  407.07  5330.2  408.48  5417.3  407.35  5422.9  405.34
  5428.2  407.33  5453.7  407.59  5479.3  405.48  5491.5  407.62  5502.1  405.23
    5541   409.6  5637.4  410.67  5777.4  414.64  6011.4  429.11  6096.3  429.84
#Mann= 8 ,-1 , 0
  3827.1     .05       0    3876     .12       0  4033.4     .05       0
  4853.2     .12       0  4978.2     .07       0  4992.2     .12       0
  4997.2     .12       0  5637.4     .05       0
Bank Sta=4978.2,4992.2
XS Rating Curve= 0 ,0
Exp/Cntr=0.3,0.1

Type RM Length L Ch R = 1 ,34498   ,506,506,506
BEGIN DESCRIPTION:
Jones Creek 46.0
END DESCRIPTION:
XS GIS Cut Line= 3
      2688300.99      6892685.97      2688042.65      6891844.33
      2686899.49      6891614.71
#Sta/Elev= 30
  4119.6   421.8  4288.5  415.76  4365.4  411.74  4495.3  410.41  4560.8   407.2
  4710.6  405.41  4732.7  406.18  4936.5  406.94  4961.6  405.51  4969.2  404.12
  4974.4  400.55  4982.6  402.09  4992.1  397.49  4994.1  396.99  5006.1  397.49
  5006.8  403.93    5017  406.12  5027.2  406.37  5139.1  404.17  5195.1  406.62
  5282.2  407.04  5312.8  405.67  5353.6  407.07    5425  407.37  5449.5  405.27
  5455.6   406.4  5506.6  407.18    5935   410.7    6032   414.1    6166  423.07
#Mann= 5 ,-1 , 0
  4119.6     .05       0  4732.7     .12       0  4992.1     .07       0
  5006.1     .12       0    6032     .05       0
Bank Sta=4992.1,5006.1
XS Rating Curve= 0 ,0
Exp/Cntr=0.3,0.1

Type RM Length L Ch R = 1 ,33992   ,777,777,777
BEGIN DESCRIPTION:
Jones Creek 44.0
END DESCRIPTION:
XS GIS Cut Line= 3
      2689545.62      6891961.65      2688247.83      6891471.19
      2687167.09      6891041.49
#Sta/Elev= 30
  3584.7  411.66  4021.1  406.68  4136.5  407.56  4268.5  404.33  4677.8  404.05
  4717.5   405.9  4732.8  404.61  4749.5  398.26  4757.7  402.62  4795.4  400.94
  4812.7  403.93  4835.1  399.77  4848.2  404.29    4928  405.36  4951.1  393.39
  4953.1  392.89  4965.3  393.39  4975.7  395.17  4988.1  404.25  4995.6  405.27
  5061.8  404.81  5221.6  402.86  5329.2  405.56  5598.2  405.15    5652  406.48
  5673.5  410.33  5746.1  415.06  5803.1     419    5927  422.79  6135.1  424.49
#Mann= 7 ,-1 , 0
  3584.7     .05       0  4795.4     .12       0  4951.1     .07       0
  4965.3     .12       0  5061.8     .05       0  5746.1     .12       0
    5927     .05       0
Bank Sta=4951.1,4965.3
XS Rating Curve= 0 ,0
Exp/Cntr=0.3,0.1

Type RM Length L Ch R = 1 ,33215   ,854,854,854
BEGIN DESCRIPTION:
Jones Creek 43.0
END DESCRIPTION:
XS GIS Cut Line= 3
      2689714.87      6891479.87      2688382.38      6890932.99
      2687275.59      6890872.23
#Sta/Elev= 30
  3553.6  415.93  3833.4  407.01  4035.6  402.91    4082  403.81  4118.4  401.98
  4179.3  405.55  4219.7  405.74    4255  403.44  4302.4  404.78  4363.1  401.42
  4409.2  401.92  4417.1  400.41  4427.7  402.77  4462.5  401.87  4492.8  403.57
    4887  403.72  4968.4  403.73  4979.2  399.88  4982.5  390.92  4984.5  390.42
  4997.4  390.92  5020.4  404.34  5047.4  404.59  5080.5  403.28    5461  404.11
  5672.5  407.09  5811.6  412.13  5871.6  418.41  6030.2  424.27  6102.4  425.46
#Mann= 5 ,-1 , 0
  3553.6     .05       0    4887     .12       0  4982.5     .07       0
  4997.4     .12       0  5047.4     .05       0
Bank Sta=4982.5,4997.4
XS Rating Curve= 0 ,0
Exp/Cntr=0.3,0.1

Type RM Length L Ch R = 1 ,32361   ,725,725,725
BEGIN DESCRIPTION:
Jones Creek 42.0
END DESCRIPTION:
XS GIS Cut Line= 3
      2689726.03      6891361.03      2688585.87      6890250.95
      2687280.47      6890173.47
#Sta/Elev= 30
  3408.7  418.13  3762.3  406.17  3939.2  403.46  4066.3  403.04  4101.8  405.78
  4130.1  403.59  4236.1  405.17  4499.3  401.41  4554.3  401.96    4618  398.59
  4646.3  400.51  4660.5   398.3  4667.4  401.05  4674.6  401.28  4681.6  398.57
  4759.5  402.73  4957.5  402.88  4971.7  398.55  4978.4  390.29  4980.4  389.79
  4993.3  390.29  4996.4  399.59  5002.4  399.59  5009.9  403.64  5064.8  401.31
  5762.5  402.59  5911.5  403.84  6028.4  407.48  6131.9  415.51  6307.7  422.42
#Mann= 7 ,-1 , 0
  3408.7     .12       0  3939.2     .05       0  4499.3     .12       0
  4978.4     .07       0  4993.3     .12       0  5064.8     .05       0
  6028.4     .12       0
Bank Sta=4978.4,4993.3
XS Rating Curve= 0 ,0
Exp/Cntr=0.3,0.1

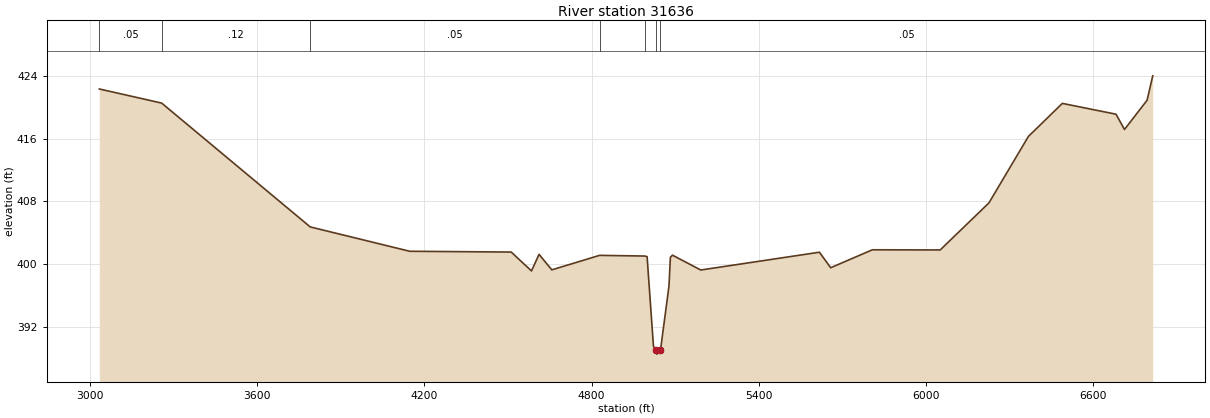
Type RM Length L Ch R = 1 ,31636   ,480,480,480
BEGIN DESCRIPTION:
Jones Creek 40.0
END DESCRIPTION:
XS GIS Cut Line= 3
      2689925.99      6891360.98        2688876.        6889711.
      2687075.97      6889410.99
#Sta/Elev= 30
  3033.5  422.35  3257.2  420.55  3790.3  404.74  4147.7  401.63  4511.7  401.53
  4584.5  399.12  4611.6  401.24  4657.4  399.26    4829  401.11  4992.1  401.02
  4999.4  400.94  5022.2  389.51  5032.5     389  5034.5   388.5  5047.4     389
  5077.9  397.19    5083  400.87  5090.6  401.13    5192  399.24  5617.8  401.51
  5658.3  399.53  5807.9  401.82  6051.2   401.8  6226.1   407.8    6368   416.3
  6489.7  420.51  6682.3  419.13  6712.7  417.18  6793.8  420.91  6814.1  424.03
#Mann= 7 ,-1 , 0
  3033.5     .05       0  3257.2     .12       0  3790.3     .05       0
    4829     .12       0  4992.1     .05       0  5032.5     .04       0
  5047.4     .05       0
Bank Sta=5032.5,5047.4
XS Rating Curve= 0 ,0
Exp/Cntr=0.3,0.1