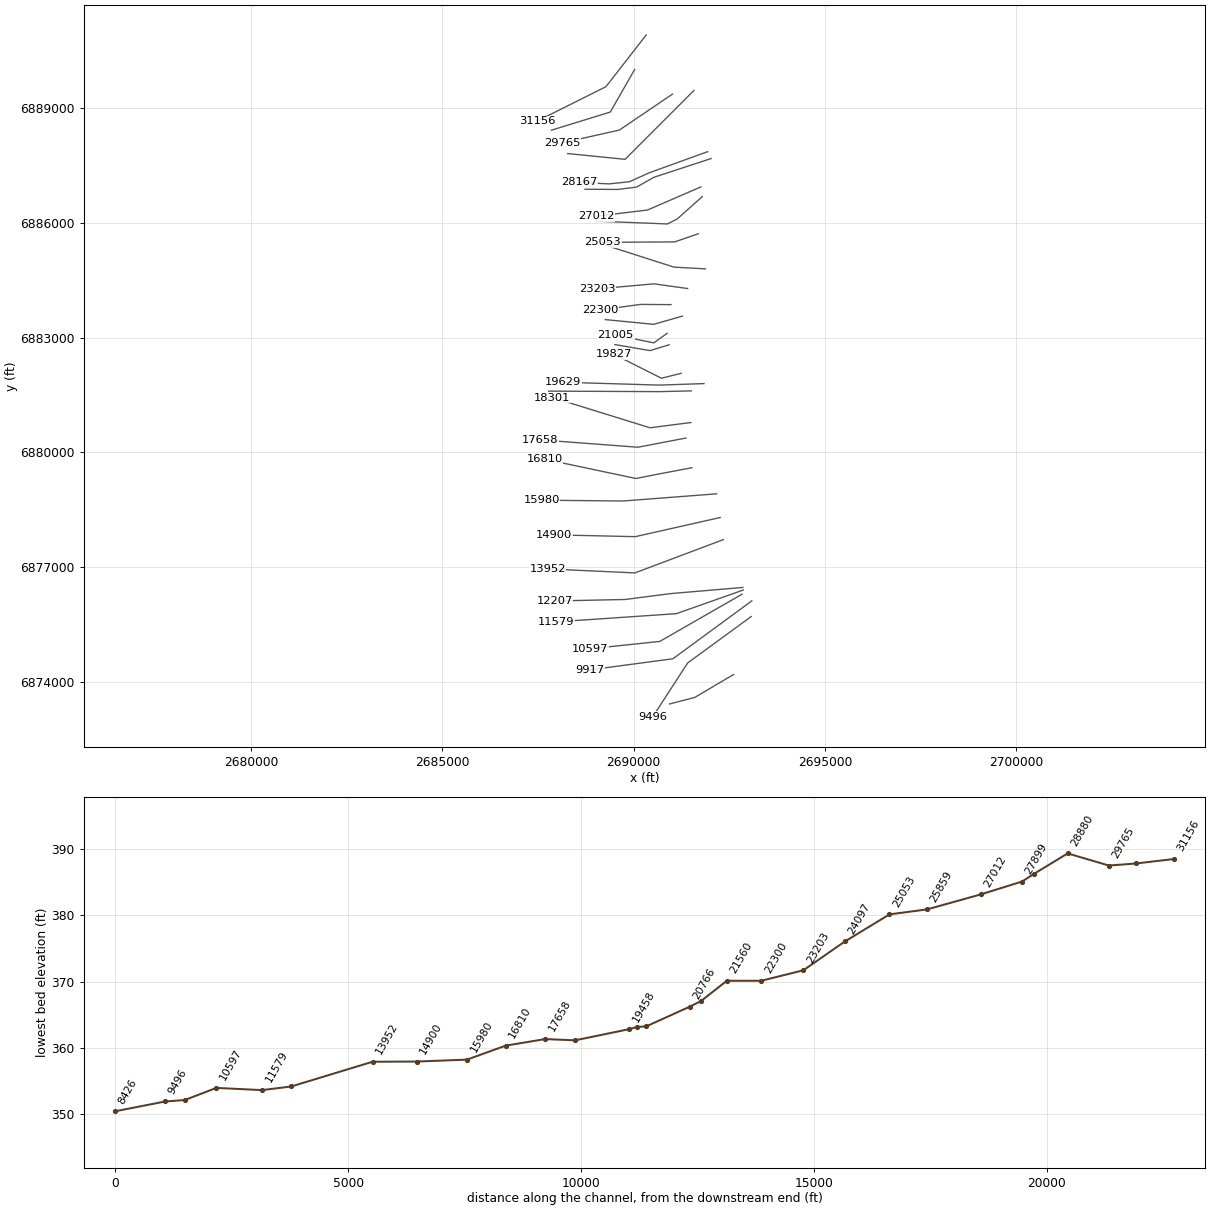
HEC-RAS study Jones Creek.prj: Jones Creek Base Level Engineering

--- Jones Creek.g01 (geometry) --- (continued)

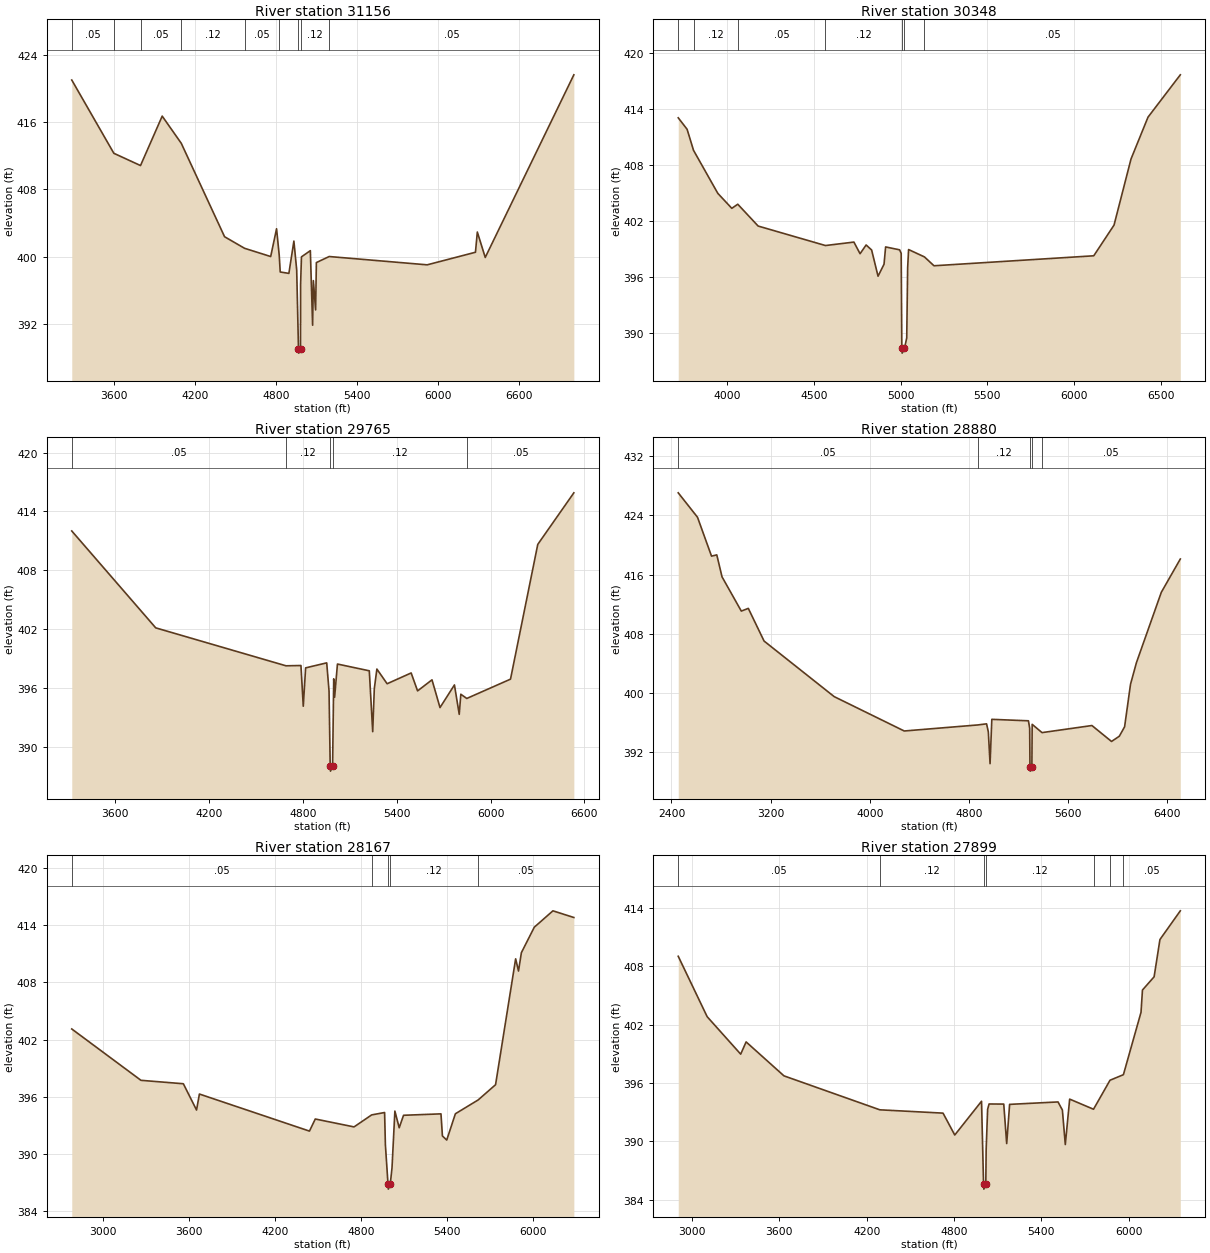
Type RM Length L Ch R = 1 ,31156   ,808,808,808
BEGIN DESCRIPTION:
Jones Creek 39.0
END DESCRIPTION:
XS GIS Cut Line= 3
      2690326.03      6890911.04        2689276.        6889561.
      2687475.97      6888660.99
#Sta/Elev= 30
  3284.5  421.04  3596.6  412.31  3794.2  410.85  3955.1  416.74  4096.5   413.5
  4417.5  402.37  4565.8  400.99  4759.5  400.01    4803  403.32  4822.8  400.16
  4830.1  398.17  4894.4     398  4931.5  401.85  4952.3  398.41  4965.6     389
  4967.6   388.5  4980.5     389  4981.2  396.68  4987.6  399.97  5053.5  400.71
  5070.3  391.83  5075.9  397.14  5092.6  393.65  5098.2  399.29  5193.3  400.01
    5920  399.02  6277.8  400.52  6291.7  402.93  6350.4   399.9  7007.3  421.66
#Mann= 9 ,-1 , 0
  3284.5     .05       0  3596.6     .12       0  3794.2     .05       0
  4096.5     .12       0  4565.8     .05       0  4822.8     .12       0
  4965.6     .07       0  4980.5     .12       0  5193.3     .05       0
Bank Sta=4965.6,4980.5
XS Rating Curve= 0 ,0
Exp/Cntr=0.3,0.1

Type RM Length L Ch R = 1 ,30348   ,583,583,583
BEGIN DESCRIPTION:
Jones Creek 38.0
END DESCRIPTION:
XS GIS Cut Line= 3
      2690025.99      6890010.98      2689389.68      6888897.81
      2687849.33      6888422.22
#Sta/Elev= 30
  3717.8  413.07  3768.9  411.84    3806  409.58  3945.9  404.97  4026.6  403.36
    4061   403.8  4178.5  401.46  4566.5  399.37  4730.5  399.74    4766  398.49
    4801  399.43  4832.7  398.89  4869.6  396.08  4904.2  397.37  4913.3  399.22
  4993.9  398.91  5003.1  398.53  5006.7  388.33  5008.7  387.83    5022  388.33
    5035  389.46  5040.3  396.97  5045.7  398.94  5137.1  398.15  5192.2   397.2
  6113.2  398.27    6230  401.56  6327.9  408.65  6425.9  413.14  6612.1  417.68
#Mann= 7 ,-1 , 0
  3717.8     .05       0    3806     .12       0    4061     .05       0
  4566.5     .12       0  5006.7     .07       0    5022     .12       0
  5137.1     .05       0
Bank Sta=5006.7,5022
XS Rating Curve= 0 ,0
Exp/Cntr=0.3,0.1

Type RM Length L Ch R = 1 ,29765   ,885,885,885
BEGIN DESCRIPTION:
Jones Creek 37.0
END DESCRIPTION:
XS GIS Cut Line= 3
      2691016.09      6889366.61      2689626.71      6888426.06
      2688130.86      6888090.59
#Sta/Elev= 30
  3322.2  412.01  3859.1  402.13  4692.3  398.26  4787.8  398.29  4802.7  394.14
  4817.7  398.05  4952.6  398.56  4967.5  395.68  4974.9  388.02  4976.9  387.52
  4990.2  388.02  4997.4  396.93  5003.1  395.05  5021.2  398.44  5224.9  397.75
  5246.7  391.54  5256.9  395.91  5273.4  397.93  5338.9  396.43  5492.6  397.53
  5533.6   395.7  5625.9  396.83  5677.1     394  5769.4  396.31  5800.1  393.31
  5810.3  395.36  5848.3  394.93    6128   396.9  6302.3  410.64    6533   415.9
#Mann= 5 ,-1 , 0
  3322.2     .05       0  4692.3     .12       0  4974.9     .07       0
  4990.2     .12       0  5848.3     .05       0
Bank Sta=4974.9,4990.2
XS Rating Curve= 0 ,0
Exp/Cntr=0.3,0.1

Type RM Length L Ch R = 1 ,28880   ,713,713,713
BEGIN DESCRIPTION:
Jones Creek 35.0
END DESCRIPTION:
XS GIS Cut Line= 3
      2691576.03      6889461.03        2689776.        6887661.
      2688276.01        6887811.
#Sta/Elev= 30
  2454.4  427.07    2610  423.76  2723.1  418.49  2765.6  418.66    2808  415.68
  2963.6  411.04  3020.1  411.41  3147.4  406.98  3713.1  399.45  4278.8  394.79
  4873.4  395.61  4943.5  395.76  4957.6  394.68  4971.7  390.36  4985.9  396.37
  5281.4  396.17  5291.5  395.18  5293.9  389.85  5295.9  389.35  5309.2  389.85
  5311.6  395.69  5391.1  394.57    5794  395.53  5952.3  393.37  6015.1  394.08
  6057.8  395.36  6105.5  401.12  6153.3  404.05  6354.2  413.59  6507.5   418.1
#Mann= 5 ,-1 , 0
  2454.4     .05       0  4873.4     .12       0  5293.9     .07       0
  5309.2     .12       0  5391.1     .05       0
Bank Sta=5293.9,5309.2
XS Rating Curve= 0 ,0
Exp/Cntr=0.3,0.1

Type RM Length L Ch R = 1 ,28167   ,268,268,268
BEGIN DESCRIPTION:
Jones Creek 33.0
END DESCRIPTION:
XS GIS Cut Line= 5
      2691934.44       6887860.5      2690404.08      6887307.56
      2689890.19      6887074.92      2689356.34       6887018.5
      2688580.23      6887057.52
#Sta/Elev= 30
  2782.3  403.12  3265.4  397.73  3561.4  397.37  3653.4  394.61  3673.4  396.29
  4441.7   392.4  4482.4  393.67  4752.9  392.84    4876   394.1  4966.3  394.35
  4971.8  390.99  4990.2  386.81  4992.2  386.31  5005.6  386.81    5018  388.54
  5038.1   394.5  5068.3  392.75  5098.5  394.06  5359.9  394.21    5370  391.89
  5400.1  391.46  5460.5  394.22  5619.4  395.67    5741  397.27  5881.2  410.48
  5901.2   409.2  5921.3  411.13  6011.4   413.8  6141.5  415.52  6287.5  414.82
#Mann= 5 ,-1 , 0
  2782.3     .05       0    4876     .12       0  4990.2     .07       0
  5005.6     .12       0  5619.4     .05       0
Bank Sta=4990.2,5005.6
XS Rating Curve= 0 ,0
Exp/Cntr=0.3,0.1

Type RM Length L Ch R = 1 ,27899   ,887,887,887
BEGIN DESCRIPTION:
Mapping XS 13e8273c
END DESCRIPTION:
XS GIS Cut Line= 5
      2692024.79      6887680.84      2690527.35      6887190.37
      2690075.96      6886934.29      2689589.85      6886873.53
      2688726.14      6886877.87
#Sta/Elev= 30
  2905.8  409.03  3104.5  402.82  3334.8  398.97    3372  400.23    3632  396.74
  4290.5  393.25  4724.5  392.91    4805  390.66  4988.9  394.13  5002.8   385.6
  5004.8   385.1  5018.2   385.6  5020.6  389.14  5030.7   393.3  5040.8  393.85
  5141.5  393.84  5161.7  389.78  5181.8  393.81  5514.2  394.06  5544.2  393.23
  5564.2  389.68  5594.2  394.35    5758  393.31  5871.3  396.29  5963.3  396.86
  6084.2  403.27  6094.2  405.56  6174.2  406.92  6214.2  410.75  6354.1   413.7
#Mann= 7 ,-1 , 0
  2905.8     .05       0  4290.5     .12       0  5002.8     .07       0
  5018.2     .12       0    5758     .05       0  5871.3     .12       0
  5963.3     .05       0
Bank Sta=5002.8,5018.2
XS Rating Curve= 0 ,0
Exp/Cntr=0.3,0.1

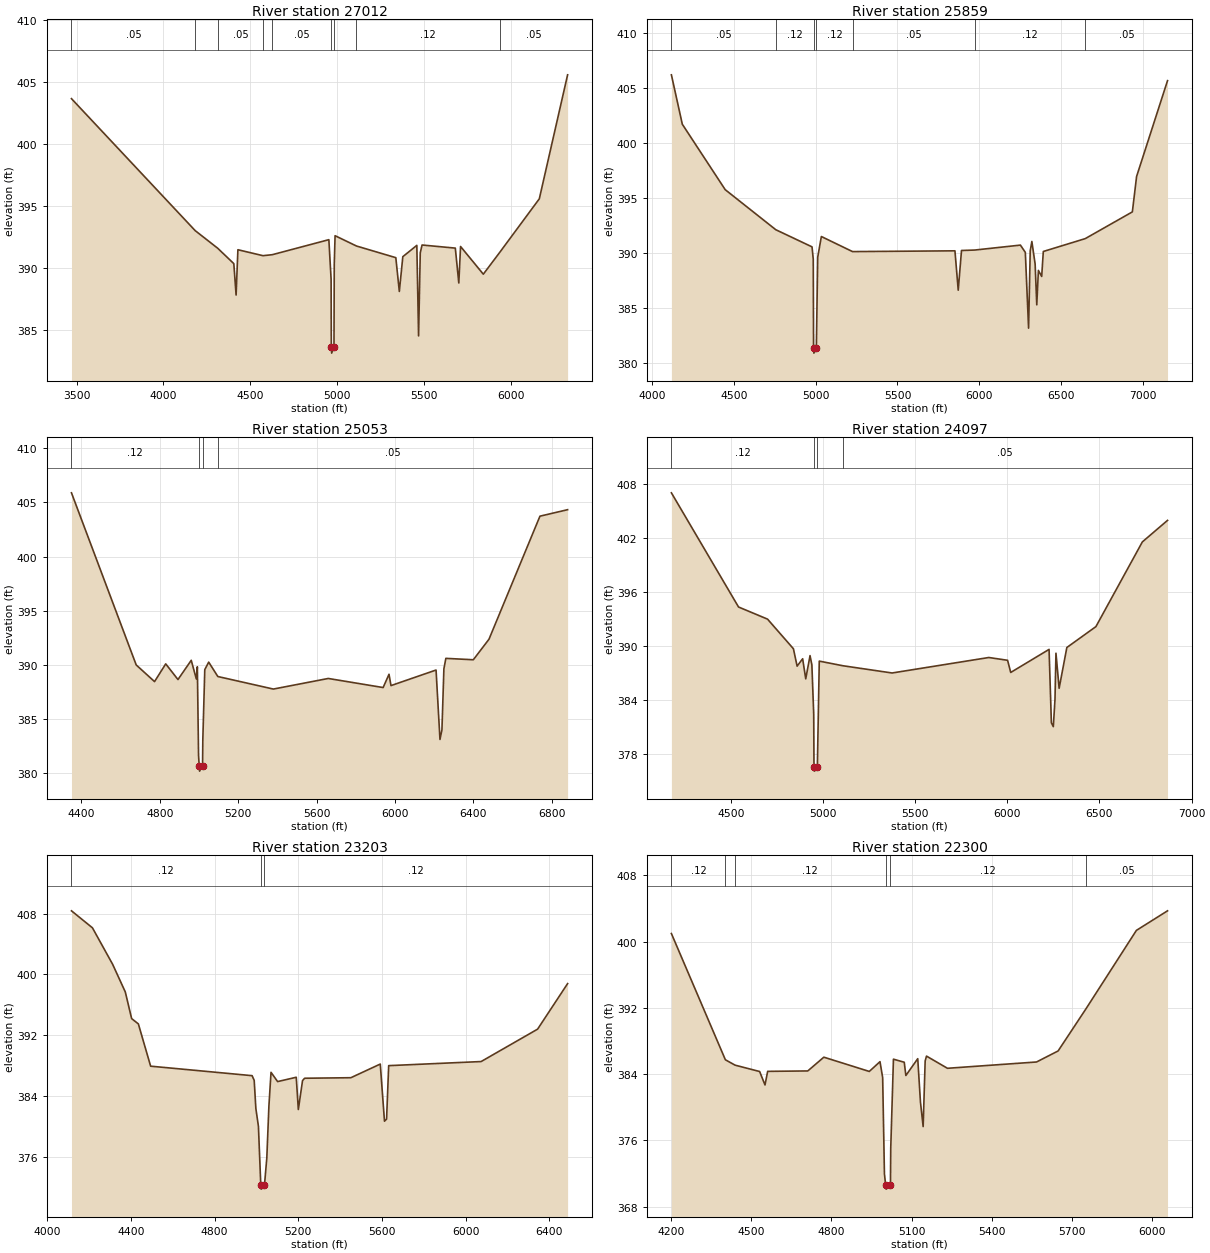
Type RM Length L Ch R = 1 ,27012   ,1153,1153,1153
BEGIN DESCRIPTION:
Mapping XS 7f03374c
END DESCRIPTION:
XS GIS Cut Line= 3
      2691755.69      6886938.65      2690362.42      6886335.34
      2689034.28      6886174.74
#Sta/Elev= 30
  3470.8  403.66  4182.9  393.03  4312.6  391.61  4405.4  390.37  4418.5  387.84
  4428.9  391.49  4573.3  391.01    4627  391.09  4952.5   392.3  4965.5   389.1
  4966.6  383.66  4968.6  383.16    4982  383.66  4983.6   390.3  4988.3  392.62
  5111.3  391.79    5338  390.85  5358.2  388.13  5378.3  390.93  5458.9  391.84
    5469  384.55  5478.7  391.24  5489.1  391.87  5680.5  391.62  5700.6  388.81
  5710.7  391.75  5841.7  389.52  5936.4  391.28    6164  395.59  6326.9  405.58
#Mann= 9 ,-1 , 0
  3470.8     .05       0  4182.9     .12       0  4312.6     .05       0
  4573.3     .12       0    4627     .05       0  4966.6     .03       0
    4982     .05       0  5111.3     .12       0  5936.4     .05       0
Bank Sta=4966.6,4982
XS Rating Curve= 0 ,0
Exp/Cntr=0.3,0.1

Type RM Length L Ch R = 1 ,25859   ,806,806,806
BEGIN DESCRIPTION:
Mapping XS 3a54b10a
END DESCRIPTION:
XS GIS Cut Line= 4
      2691794.68      6886686.87      2691139.33      6886100.96
      2690883.25      6885970.75      2689016.96      6886044.54
#Sta/Elev= 30
  4117.5   406.2  4184.2  401.71  4446.6  395.76  4755.8  392.12  4977.5  390.56
    4985  389.45  4986.9   381.4  4988.9   380.9    5004   381.4  5012.3  389.62
  5034.6   391.5  5225.2  390.13  5851.5   390.2  5871.6  386.62  5891.6  390.23
  5972.2  390.27  6251.9  390.72  6281.9  390.06  6301.9  383.17  6311.9   390.2
  6321.9  391.05  6341.9     389  6351.9  385.29  6361.9  388.42    6382  387.87
    6392  390.14  6648.5  391.31  6936.5  393.74  6962.4  396.96  7151.6  405.67
#Mann= 7 ,-1 , 0
  4117.5     .05       0  4755.8     .12       0  4986.9     .07       0
    5004     .12       0  5225.2     .05       0  5972.2     .12       0
  6648.5     .05       0
Bank Sta=4986.9,5004
XS Rating Curve= 0 ,0
Exp/Cntr=0.3,0.1

Type RM Length L Ch R = 1 ,25053   ,956,956,956
BEGIN DESCRIPTION:
Mapping XS 1ac9e6f7
END DESCRIPTION:
XS GIS Cut Line= 3
      2691690.56      6885714.68      2691074.22        6885502.
      2689194.87      6885488.98
#Sta/Elev= 30
  4349.4  405.89  4679.7  389.97  4773.3  388.43  4830.3  390.07  4892.8  388.62
  4960.5   390.4  4986.4  388.68  4991.7   389.8  4997.8   381.6  5001.1  380.65
  5003.1  380.15  5018.2  380.65  5019.6  383.08  5029.6  389.54  5049.6  390.23
  5096.2   388.9  5379.6  387.74  5659.6  388.72  5939.6  387.88  5969.6  389.11
  5979.6  388.06  6209.6   389.5  6229.6  383.08  6239.6  383.96  6249.6  389.61
  6259.6  390.58  6399.7  390.45  6479.7  392.35  6739.7  403.73  6880.8  404.33
#Mann= 4 ,-1 , 0
  4349.4     .12       0  5001.1     .07       0  5018.2     .12       0
  5096.2     .05       0
Bank Sta=5001.1,5018.2
XS Rating Curve= 0 ,0
Exp/Cntr=0.3,0.1

Type RM Length L Ch R = 1 ,24097   ,894,894,894
BEGIN DESCRIPTION:
Jones Creek 29.0
END DESCRIPTION:
XS GIS Cut Line= 3
      2691876.88      6884796.38      2691056.09      6884840.97
      2689276.03      6885410.99
#Sta/Elev= 30
    4178  406.98  4542.1   394.3  4699.6  392.95  4839.9  389.66  4859.9  387.73
  4889.9  388.55  4906.7  386.32    4930   388.9    4940  387.87    4950  382.38
  4951.4  376.57  4953.4  376.07  4968.6  376.57    4970  376.85  4980.1  388.29
  5106.4  387.78    5375  386.97  5899.8  388.69  6001.5  388.38  6018.6  387.03
  6226.5  389.59  6239.1  381.44  6249.6  381.01  6258.7  384.06  6263.9  389.17
  6281.1  385.27    6323   389.8  6480.6  392.12  6732.6  401.53  6869.1  403.92
#Mann= 4 ,-1 , 0
    4178     .12       0  4951.4     .07       0  4968.6     .12       0
  5106.4     .05       0
Bank Sta=4951.4,4968.6
XS Rating Curve= 0 ,0
Exp/Cntr=0.3,0.1

Type RM Length L Ch R = 1 ,23203   ,903,903,903
BEGIN DESCRIPTION:
Jones Creek 28.0
END DESCRIPTION:
XS GIS Cut Line= 3
       2691410.7      6884282.21      2690535.22      6884404.58
      2689054.38      6884273.73
#Sta/Elev= 30
    4116  408.38  4216.2  406.14  4312.6  401.34  4373.2  397.69  4403.5  394.18
  4435.6  393.48  4494.3  387.91    4979  386.66  4989.1  386.04  4997.1  382.32
  5009.3  379.99  5020.6  372.21  5022.6  371.71  5038.1  372.21  5049.4  375.83
  5059.4  382.67  5069.5   387.1    5101  385.88    5190  386.45    5200   382.2
  5220.1  386.01  5230.1  386.32    5451  386.39  5591.5  388.19  5611.6  380.66
  5621.6  380.93  5631.7  387.98  6073.4  388.52  6343.3  392.79  6486.6  398.79
#Mann= 3 ,-1 , 0
    4116     .12       0  5020.6     .07       0  5038.1     .12       0
Bank Sta=5020.6,5038.1
XS Rating Curve= 0 ,0
Exp/Cntr=0.3,0.1

Type RM Length L Ch R = 1 ,22300   ,740,740,740
BEGIN DESCRIPTION:
Jones Creek 27.0
END DESCRIPTION:
XS GIS Cut Line= 3
      2690976.02        6883861.      2690177.84       6883866.8
      2689130.63      6883723.22
#Sta/Elev= 30
  4201.8  400.97  4403.6  385.74  4439.8  385.09  4531.8  384.32  4551.8   382.7
  4561.8  384.34  4711.8  384.39  4771.8  386.05  4941.8  384.33  4981.8  385.51
  4991.8  383.59  4998.4  371.98  5002.9  370.63  5004.9  370.13  5020.9  370.63
    5022  375.08  5032.1  385.81  5072.5  385.44  5078.5  383.84    5123  385.87
  5133.1  380.63  5143.2  377.68  5150.7  385.59  5155.7  386.18    5234  384.71
  5567.1  385.47  5647.8   386.8  5751.3  391.85  5940.6  401.35    6057  403.71
#Mann= 6 ,-1 , 0
  4201.8     .12       0  4403.6     .05       0  4439.8     .12       0
  5002.9     .07       0  5020.9     .12       0  5751.3     .05       0
Bank Sta=5002.9,5020.9
XS Rating Curve= 0 ,0
Exp/Cntr=0.3,0.1

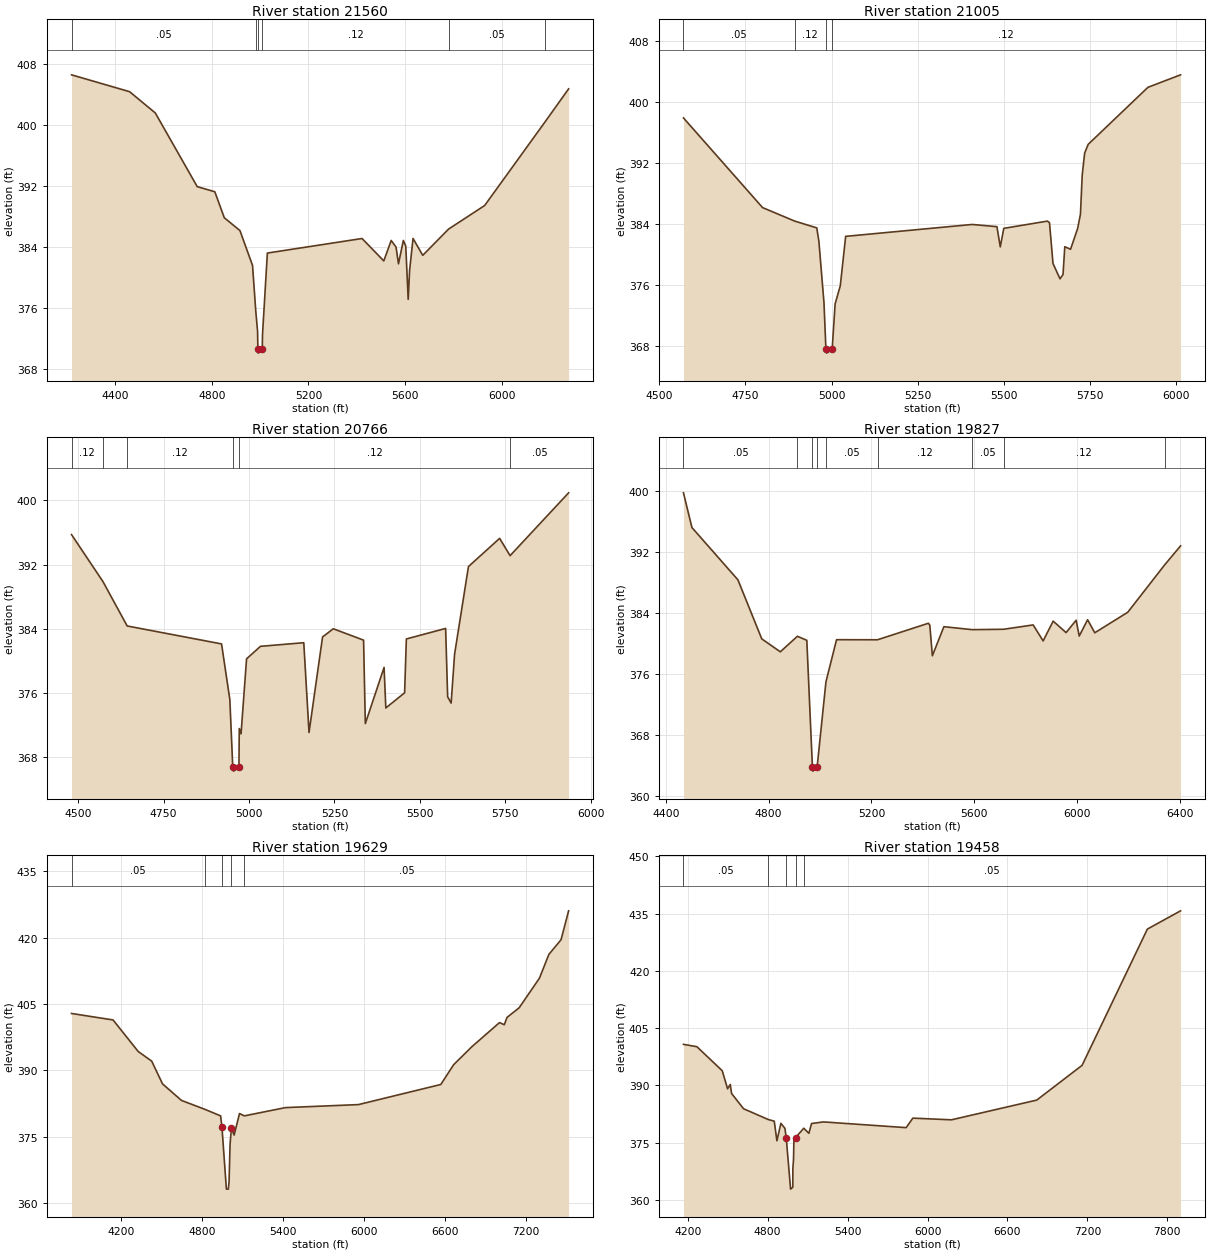
Type RM Length L Ch R = 1 ,21560   ,555,555,555
BEGIN DESCRIPTION:
Jones Creek 26.0
END DESCRIPTION:
XS GIS Cut Line= 3
      2691276.05      6883561.01      2690525.87      6883345.94
      2689255.28       6883469.7
#Sta/Elev= 30
  4219.6  406.62  4459.8  404.41  4566.3  401.62  4739.8  391.96  4812.6  391.29
  4851.8  387.88  4916.6   386.2  4968.7  381.62  4982.1  375.63  4989.5     373
  4990.8  370.63  4992.8  370.13  5008.9  370.63  5009.9  372.54    5030  383.25
  5421.9  385.16  5511.8  382.22  5542.4   384.9  5562.5  384.04  5572.6  381.84
  5592.7   384.9  5602.7  384.16  5612.8  377.18  5618.6  380.98  5632.8  385.17
    5673  382.95  5780.1   386.4  5929.1  389.48  6177.8  400.39  6276.6  404.78
#Mann= 6 ,-1 , 0
  4219.6     .05       0  4982.1     .12       0  4990.8     .07       0
  5008.9     .12       0  5780.1     .05       0  6177.8     .12       0
Bank Sta=4990.8,5008.9
XS Rating Curve= 0 ,0
Exp/Cntr=0.3,0.1

Type RM Length L Ch R = 1 ,21005   ,239,239,239
BEGIN DESCRIPTION:
Jones Creek 25.0
END DESCRIPTION:
XS GIS Cut Line= 3
      2690876.01      6883111.01      2690526.15        6882861.
      2689533.08      6883063.45
#Sta/Elev= 30
    4570  397.91  4799.8  386.15  4892.6  384.39  4957.1  383.49  4963.3  381.72
    4978  373.69  4983.7  367.57  4985.7  367.07  5001.8  367.57  5010.4  373.53
  5025.4   375.9    5041  382.38  5408.4  383.94  5480.3  383.65    5490     381
  5500.2  383.43  5626.8  384.38  5632.9  384.18  5643.1  378.82  5663.5  376.81
  5672.2  377.38  5677.3  381.02  5694.1  380.69  5714.6  383.41  5722.8  385.28
  5727.9   390.4    5735   393.3  5745.2  394.44  5918.7  401.92  6013.5  403.56
#Mann= 4 ,-1 , 0
    4570     .05       0  4892.6     .12       0  4983.7     .07       0
  5001.8     .12       0
Bank Sta=4983.7,5001.8
XS Rating Curve= 0 ,0
Exp/Cntr=0.3,0.1

Type RM Length L Ch R = 1 ,20766   ,939,939,939
BEGIN DESCRIPTION:
Jones Creek 24.0
END DESCRIPTION:
XS GIS Cut Line= 3
      2690926.03      6882811.01      2690428.96      6882658.99
      2689506.99      6882816.93
#Sta/Elev= 30
  4480.2  395.74  4572.2  389.88  4643.1  384.34  4919.4   382.1  4943.7  375.15
  4952.2  366.73  4954.2  366.23  4970.3  366.73  4971.3  371.54  4976.5  370.88
  4992.6  380.24  5033.4   381.8  5160.1  382.25  5175.5  371.05  5215.1  382.97
  5246.5  383.99  5335.2  382.57  5340.3  372.16  5395.2  379.17  5400.3  374.11
  5455.3     376  5460.4  382.72  5575.4  384.03  5581.3  375.51  5591.5  374.72
  5601.6  380.82  5642.2  391.75  5733.5  395.27  5764.1  393.11  5935.4  400.95
#Mann= 6 ,-1 , 0
  4480.2     .12       0  4572.2     .05       0  4643.1     .12       0
  4952.2     .07       0  4970.3     .12       0  5764.1     .05       0
Bank Sta=4952.2,4970.3
XS Rating Curve= 0 ,0
Exp/Cntr=0.3,0.1

Type RM Length L Ch R = 1 ,19827   ,198,198,198
BEGIN DESCRIPTION:
Jones Creek 23.0
END DESCRIPTION:
XS GIS Cut Line= 3
      2691241.42      6882064.32      2690726.04      6881936.07
      2689474.09      6882566.46
#Sta/Elev= 30
  4468.9  399.81  4501.8  395.25  4680.6  388.38  4773.3  380.62  4845.5  378.92
  4911.9  380.96  4948.5  380.43  4970.3  363.74  4972.3  363.24  4988.5  363.74
  5022.9  374.97  5064.1  380.51  5223.4   380.5  5421.1  382.67  5426.7  382.42
  5436.7   378.4  5481.5  382.22  5591.6  381.83  5713.4  381.88  5828.6  382.45
  5867.4  380.35  5906.4  382.95  5956.6  381.44  5995.7  383.07  6007.7  380.99
  6040.3  383.13  6068.2  381.42  6196.5  384.12  6339.6  390.33  6401.7  392.84
#Mann= 9 ,-1 , 0
  4468.9     .05       0  4911.9     .12       0  4970.3     .07       0
  4988.5     .12       0  5022.9     .05       0  5223.4     .12       0
  5591.6     .05       0  5713.4     .12       0  6339.6     .05       0
Bank Sta=4970.3,4988.5
XS Rating Curve= 0 ,0
Exp/Cntr=0.3,0.1

Type RM Length L Ch R = 1 ,19629   ,171,171,171
BEGIN DESCRIPTION:
Jones Creek 22.0
END DESCRIPTION:
XS GIS Cut Line= 3
       2691839.5      6881796.44      2690675.98       6881756.8
      2688159.98      6881831.13
#Sta/Elev= 30
  3835.8  402.87  4143.4  401.41  4329.6  394.28  4429.6   392.1  4509.7  386.96
  4649.8  383.22  4824.3  381.19  4939.9  379.72  4949.9  377.21  4982.7  363.16
  4997.2  363.16  5002.5  364.84    5010  373.38    5020  376.94    5040  375.38
    5080  380.25  5115.1  379.72  5420.2  381.59  5960.4  382.27  6570.7  386.82
  6665.9   391.3  6800.8  395.36  7005.3  400.81  7040.9  400.33  7060.9  401.98
  7150.9  404.16    7301  410.85    7371  416.23  7461.1  419.55  7517.1  426.08
#Mann= 5 ,-1 , 0
  3835.8     .05       0  4824.3     .12       0  4949.9     .07       0
    5020     .12       0  5115.1     .05       0
Bank Sta=4949.9,5020
XS Rating Curve= 0 ,0
Exp/Cntr=0.3,0.1

Type RM Length L Ch R = 1 ,19458   ,1157,1157,1157
BEGIN DESCRIPTION:
Jones Creek 21.0
END DESCRIPTION:
XS GIS Cut Line= 3
      2691506.98      6881605.32       2690675.9      6881585.87
      2687776.93      6881599.03
#Sta/Elev= 30
  4168.7  400.76  4269.7  400.13  4459.8  393.84  4499.8   389.1  4519.8  390.25
  4529.8  387.88  4619.8  383.88  4805.6  381.05  4849.9  380.63  4869.9  375.49
  4899.9  380.06  4929.9  378.76  4939.9  376.26  4972.6  362.82  4989.2  363.32
  4989.6  368.18  4994.6  370.64  4997.5  375.68  5009.9  376.32  5071.5  378.77
  5109.9  377.45  5129.9  380.01  5219.9  380.43  5839.9  378.93  5889.9  381.42
  6179.9  380.98  6819.9  386.15  7159.9  395.25  7649.9  430.95    7899  435.74
#Mann= 5 ,-1 , 0
  4168.7     .05       0  4805.6     .12       0  4939.9     .07       0
  5009.9     .12       0  5071.5     .05       0
Bank Sta=4939.9,5009.9
XS Rating Curve= 0 ,0
Exp/Cntr=0.3,0.1

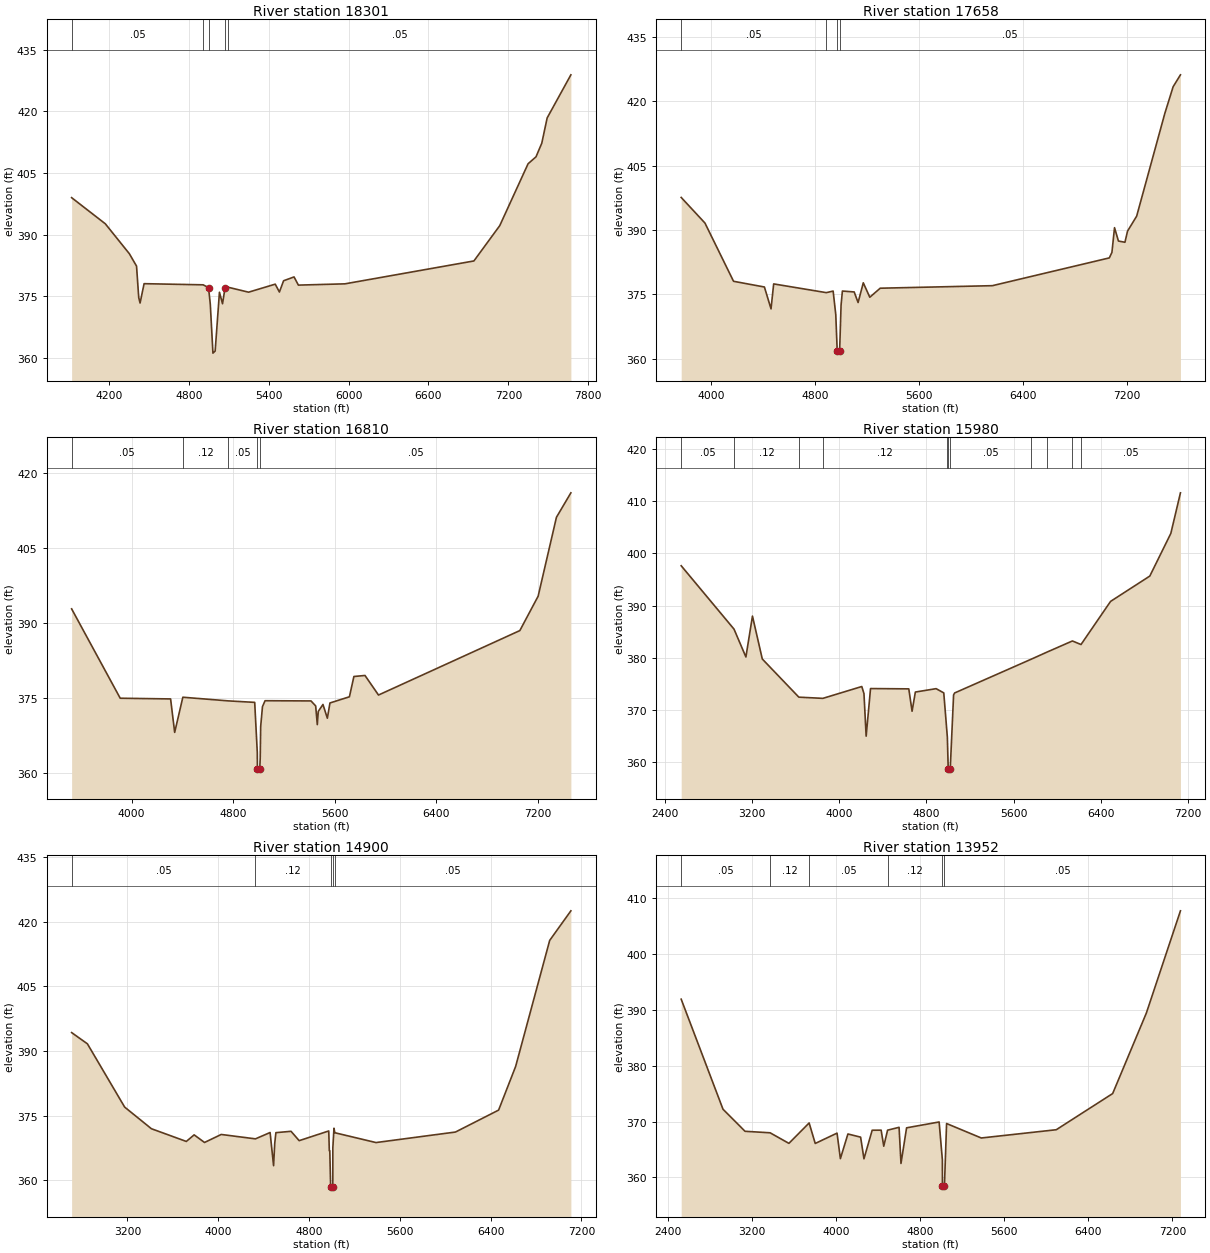
Type RM Length L Ch R = 1 ,18301   ,643,643,643
BEGIN DESCRIPTION:
Jones Creek 18.0
END DESCRIPTION:
XS GIS Cut Line= 3
      2691495.72      6880777.55       2690425.4      6880640.95
      2687875.94      6881431.78
#Sta/Elev= 30
    3921  398.97    4174  392.61  4354.2  385.34  4408.4  382.31  4424.8  374.67
  4434.9  373.33  4465.1  378.04  4908.2  377.76    4949  377.09  4962.1  373.04
    4982  361.14  4998.6  361.64  5030.8  375.95  5053.9  373.15  5072.7  377.01
  5096.1  377.17  5249.4  375.97  5449.6  377.92    5481  376.01  5512.4  378.75
  5590.9  379.68  5623.5  377.69  5973.1     378  6941.3  383.57  7135.3  392.16
    7348  407.22  7407.5  408.91  7450.9  412.23  7491.2  418.37  7669.3  428.86
#Mann= 5 ,-1 , 0
    3921     .05       0  4908.2     .12       0    4949     .07       0
  5072.7     .12       0  5096.1     .05       0
Bank Sta=4949,5072.7
XS Rating Curve= 0 ,0
Exp/Cntr=0.3,0.1

Type RM Length L Ch R = 1 ,17658   ,848,848,848
BEGIN DESCRIPTION:
Mapping XS 388a5a0a
END DESCRIPTION:
XS GIS Cut Line= 3
      2691365.76      6880371.88       2690110.6       6880132.3
      2687549.56       6880324.9
#Sta/Elev= 30
  3767.5  397.59  3950.5  391.63  4170.8  378.06  4408.6  376.73  4459.5  371.64
  4479.9  377.45  4885.2  375.42    4938  375.78  4958.4  370.29  4969.4  361.83
  4971.4  361.33    4988  361.83  4999.1   372.5  5009.3  375.79  5100.1  375.58
  5130.2  373.12  5170.3  377.71  5220.4  374.35  5300.6  376.45  6164.8  377.04
  7065.6  383.51  7085.7  384.79  7105.7  390.55  7135.8  387.44    7186  387.15
    7206  389.75  7276.2  393.23  7493.4  417.18    7557  423.36  7613.6  426.15
#Mann= 4 ,-1 , 0
  3767.5     .05       0  4885.2     .12       0  4969.4     .03       0
    4988     .05       0
Bank Sta=4969.4,4988
XS Rating Curve= 0 ,0
Exp/Cntr=0.3,0.1

Type RM Length L Ch R = 1 ,16810   ,830,830,830
BEGIN DESCRIPTION:
Mapping XS 650b78eb
END DESCRIPTION:
XS GIS Cut Line= 4
      2691522.02      6879595.84      2690693.94      6879439.59
      2690058.52      6879314.59      2687669.48      6879819.47
#Sta/Elev= 30
  3527.6  392.84  3910.3  374.94  4307.1   374.8  4339.2   368.1  4403.6  375.14
  4760.5  374.41  4969.5  374.11  4989.9  364.04  4990.7  360.84  4992.7  360.34
  5009.4  360.84    5013     363  5016.6  369.28  5030.7  373.26  5051.1  374.44
  5412.8   374.4  5449.7   373.4  5462.5  369.65  5470.2   372.3  5507.1  373.69
  5541.7  370.94  5562.2  373.99  5715.5  375.23  5750.7  379.29  5838.1   379.5
  5944.5  375.58  7057.8  388.49  7201.9  395.38    7346  411.18  7459.7  416.08
#Mann= 5 ,-1 , 0
  3527.6     .05       0  4403.6     .12       0  4760.5     .05       0
  4990.7     .03       0  5009.4     .05       0
Bank Sta=4990.7,5009.4
XS Rating Curve= 0 ,0
Exp/Cntr=0.3,0.1

Type RM Length L Ch R = 1 ,15980   ,1080,1080,1080
BEGIN DESCRIPTION:
Mapping XS 5c6b6b8b
END DESCRIPTION:
XS GIS Cut Line= 3
      2692167.86      6878913.55      2689725.19      6878726.05
      2687594.95      6878746.89
#Sta/Elev= 30
  2550.7  397.63  3035.3  385.47  3144.3  380.13  3204.5  387.97  3294.7  379.74
  3629.9  372.42  3850.6  372.19  4207.4  374.46  4227.5   373.1  4247.5  364.94
  4287.7  374.07  4638.7  374.01  4668.8  369.72  4698.9   373.4  4889.4  374.05
  4959.6  373.24  4992.4  364.76  5000.3  358.73  5002.3  358.23  5019.1  358.73
  5049.7  372.86  5059.7  373.23  5762.6  379.71  5907.2  381.07  6139.6   383.2
  6218.7  382.52  6489.8  390.79  6849.8  395.65  7042.6  403.83  7130.9  411.62
#Mann= 11 ,-1 , 0
  2550.7     .05       0  3035.3     .12       0  3629.9     .05       0
  3850.6     .12       0  4992.4     .05       0  5000.3     .03       0
  5019.1     .05       0  5762.6     .12       0  5907.2     .05       0
  6139.6     .12       0  6218.7     .05       0
Bank Sta=5000.3,5019.1
XS Rating Curve= 0 ,0
Exp/Cntr=0.3,0.1

Type RM Length L Ch R = 1 ,14900   ,948,948,948
BEGIN DESCRIPTION:
Mapping XS 17407723
END DESCRIPTION:
XS GIS Cut Line= 3
      2692261.69      6878293.77       2690042.9      6877793.76
      2687919.45       6877840.6
#Sta/Elev= 30
  2708.6  394.25  2847.7  391.64  3175.7  376.97  3411.5  371.95    3719     369
  3787.9  370.53  3879.5  368.76  4026.5  370.62    4328   369.6  4457.1  371.07
  4487.8  363.38  4498.1  368.59  4508.3  371.04  4641.6  371.35  4713.3  369.18
  4973.8  371.43  4978.9  366.83    4983  366.83  4990.5  358.44  4992.5  357.94
  5009.4  358.44  5009.9  367.55  5019.9  372.07  5027.3  371.02    5390  368.74
  6090.2  371.18  6470.3  376.27  6620.3  386.39  6920.4  415.63    7107  422.49
#Mann= 5 ,-1 , 0
  2708.6     .05       0    4328     .12       0  4990.5     .07       0
  5009.4     .12       0  5027.3     .05       0
Bank Sta=4990.5,5009.4
XS Rating Curve= 0 ,0
Exp/Cntr=0.3,0.1

Type RM Length L Ch R = 1 ,13952   ,1745,1745,1745
BEGIN DESCRIPTION:
Mapping XS 772dd1e0
END DESCRIPTION:
XS GIS Cut Line= 3
      2692344.99      6877715.64      2690032.48      6876845.84
      2687751.23      6876950.01
#Sta/Elev= 30
  2522.4  391.93  2920.5  372.22  3130.3  368.27    3369     368  3548.1  366.11
  3740.7  369.76  3798.8  366.09  4006.4  367.94  4038.4  363.37    4110  367.79
  4230.9  367.22  4262.8  363.34  4341.1  368.46  4426.5  368.47  4451.4   365.6
  4487.7  368.47  4597.2  368.98  4615.4  362.51  4668.8  368.89  4978.6  369.94
  5009.6  363.13  5010.1  358.41  5012.1  357.91    5029  358.41  5049.6  369.66
    5380  367.07  6094.2  368.55  6631.3  375.03  6951.6  389.43  7276.7  407.76
#Mann= 6 ,-1 , 0
  2522.4     .05       0    3369     .12       0  3740.7     .05       0
  4487.7     .12       0  5010.1     .07       0    5029     .05       0
Bank Sta=5010.1,5029
XS Rating Curve= 0 ,0
Exp/Cntr=0.3,0.1

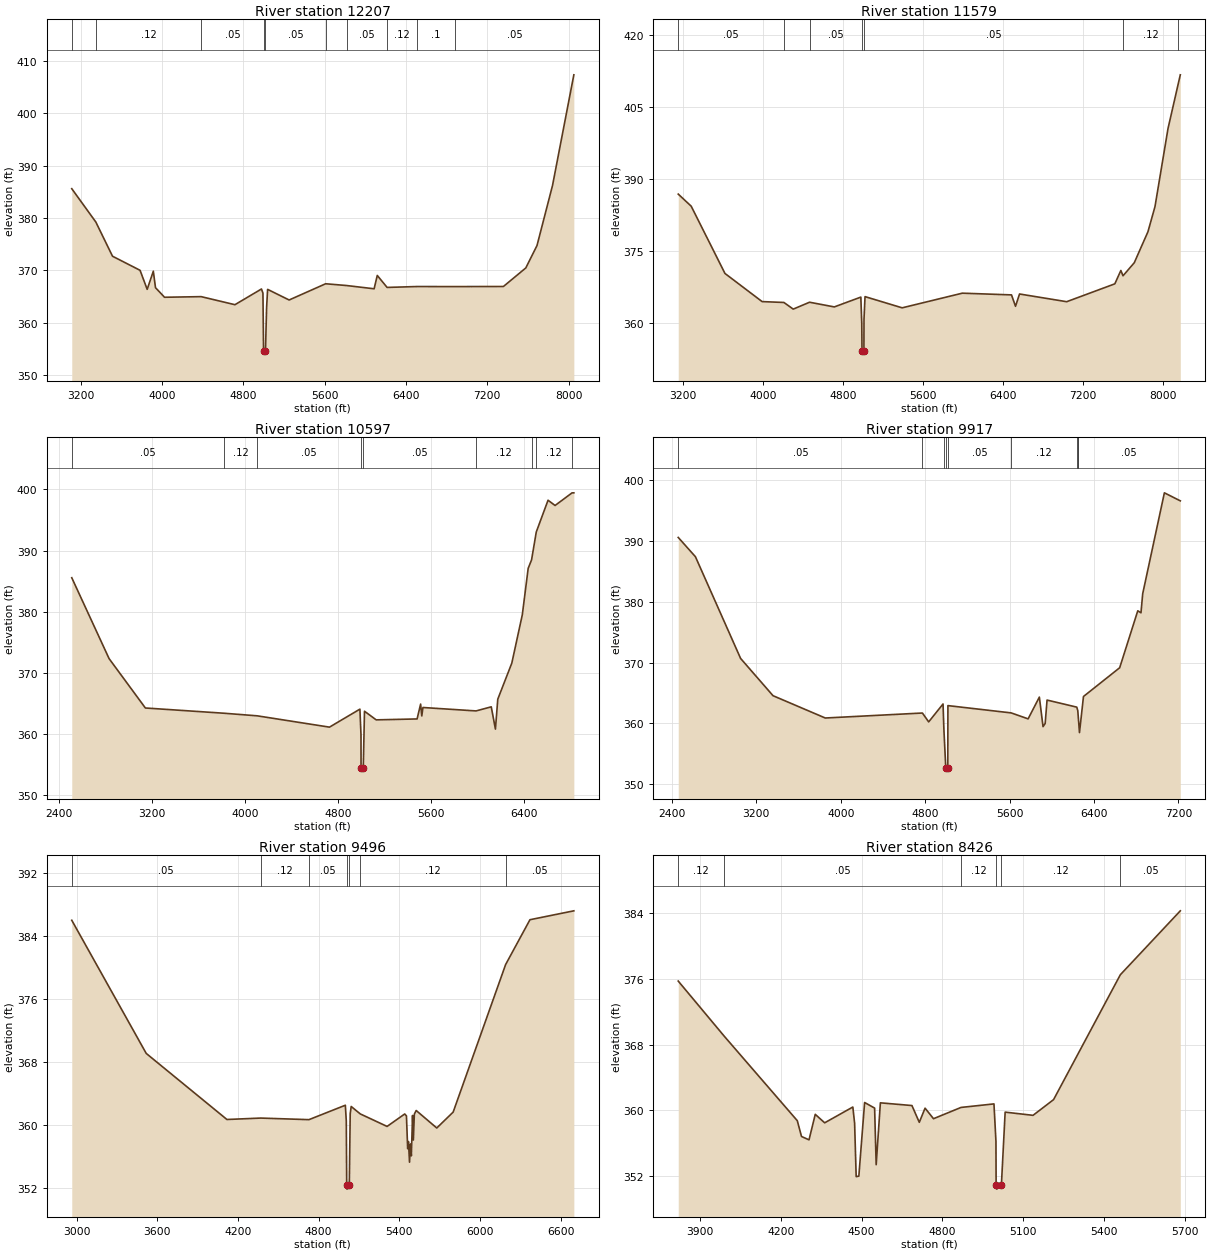
Type RM Length L Ch R = 1 ,12207   ,628,628,628
BEGIN DESCRIPTION:
Mapping XS 1e207c74
END DESCRIPTION:
XS GIS Cut Line= 4
      2692855.35      6876465.63      2690975.37      6876305.42
      2689774.35      6876150.78       2687933.5      6876111.47
#Sta/Elev= 30
  3113.2  385.59    3350  379.22    3514  372.69    3785     370  3855.2  366.36
  3915.5  369.83  3936.9  366.68  4025.8  364.85    4386  364.97  4718.3  363.43
  4979.3  366.43  4993.8  365.64  4999.9  354.68  5001.9  354.18  5018.9  354.68
  5029.6  362.77  5039.7  366.36  5251.4  364.33  5610.8  367.43  5817.2  367.09
  6087.5  366.47  6118.5  369.02  6215.2  366.73  6512.1   366.9  6881.7  366.89
  7359.5  366.91  7579.6  370.45  7689.6  374.72  7842.3  386.19  8052.2  407.34
#Mann= 10 ,-1 , 0
  3113.2     .05       0    3350     .12       0    4386     .05       0
  4999.9     .03       0  5018.9     .05       0  5610.8     .12       0
  5817.2     .05       0  6215.2     .12       0  6512.1      .1       0
  6881.7     .05       0
Bank Sta=4999.9,5018.9
XS Rating Curve= 0 ,0
Exp/Cntr=0.3,0.1

Type RM Length L Ch R = 1 ,11579   ,982,982,982
BEGIN DESCRIPTION:
Mapping XS 3228a4d8
END DESCRIPTION:
XS GIS Cut Line= 3
      2692866.25      6876397.93      2691116.25      6875779.87
      2687963.42      6875564.59
#Sta/Elev= 30
  3154.1  386.84  3283.5  384.32    3621  370.27  3992.2  364.39  4209.8  364.21
    4303  362.82  4466.3  364.26  4713.3  363.28  4978.5  365.33  4987.7  359.87
  4990.2  354.13  4992.2  353.63  5009.2  354.13    5010  360.73  5020.3  365.43
  5391.2  363.09  5992.6  366.15  6483.7  365.79  6523.8  363.41  6563.9  365.98
    7035  364.37  7516.1   368.1  7576.2  370.89    7598  369.78  7710.3  372.51
  7846.9  378.98    7917  384.21  8047.3  400.53  8147.9  409.73  8170.2  411.75
#Mann= 7 ,-1 , 0
  3154.1     .05       0  4209.8     .12       0  4466.3     .05       0
  4990.2     .03       0  5009.2     .05       0    7598     .12       0
  8147.9     .05       0
Bank Sta=4990.2,5009.2
XS Rating Curve= 0 ,0
Exp/Cntr=0.3,0.1

Type RM Length L Ch R = 1 ,10597   ,680,680,680
BEGIN DESCRIPTION:
Mapping XS 6c188ed3
END DESCRIPTION:
XS GIS Cut Line= 3
      2692834.52      6876288.53      2690683.52      6875054.18
      2688855.36      6874861.46
#Sta/Elev= 30
  2512.3  385.57  2833.3  372.35  3145.4  364.28  3823.5  363.42  4106.7     363
  4728.7  361.15  4990.5  364.09  4999.9  359.88  5000.4  354.46  5002.4  353.96
  5019.4  354.46    5030  363.75  5130.6  362.34  5482.5  362.49  5512.7  364.92
  5522.8  362.98  5532.8  364.36  5989.6   363.8  6120.3  364.47  6156.2  360.83
  6176.4  365.72    6297  371.61  6387.5  379.53  6437.8   387.1    6467  388.49
  6507.5  393.05  6608.7  398.24  6669.1  397.38  6814.9  399.44  6830.6  399.45
#Mann= 9 ,-1 , 0
  2512.3     .05       0  3823.5     .12       0  4106.7     .05       0
  5000.4     .03       0  5019.4     .05       0  5989.6     .12       0
    6467     .05       0  6507.5     .12       0  6814.9     .05       0
Bank Sta=5000.4,5019.4
XS Rating Curve= 0 ,0
Exp/Cntr=0.3,0.1

Type RM Length L Ch R = 1 ,9917    ,421,421,421
BEGIN DESCRIPTION:
Mapping XS 3eb4e368
END DESCRIPTION:
XS GIS Cut Line= 3
      2693089.46      6876114.49      2691026.98      6874600.62
      2688846.44      6874308.95
#Sta/Elev= 30
  2460.2  390.58  2623.1  387.41  3051.4  370.67  3358.6  364.54  3853.8  360.87
  4774.3  361.69  4833.8  360.23  4969.9  363.18    4978     359  4995.9  352.63
  4997.9  352.13  5014.9  352.63  5016.1  362.91  5615.7  361.71  5776.3  360.73
  5882.7  364.31  5917.6  359.45  5937.7  359.96  5955.7  363.82  6237.3  362.66
  6245.4  362.18  6246.9  362.09    6263  358.47  6300.9  364.41    6644  369.14
  6815.5  378.51  6845.7  378.18  6862.3  381.33  7067.7  397.92  7218.6   396.6
#Mann= 9 ,-1 , 0
  2460.2     .05       0  4774.3     .12       0    4978     .05       0
  4995.9     .03       0  5014.9     .05       0  5615.7     .12       0
  6237.3     .05       0  6245.4     .12       0  6246.9     .05       0
Bank Sta=4995.9,5014.9
XS Rating Curve= 0 ,0
Exp/Cntr=0.3,0.1

Type RM Length L Ch R = 1 ,9496    ,1070,1070,1070
BEGIN DESCRIPTION:
Mapping XS 64f290b6
END DESCRIPTION:
XS GIS Cut Line= 3
      2693074.17      6875705.23      2691412.69      6874491.68
      2690501.01      6873086.02
#Sta/Elev= 30
  2964.4  386.04  3517.9  369.14    4118  360.75  4368.7  360.93  4727.9  360.73
  4998.4  362.56  5005.4  360.57  5008.6  352.41  5010.6  351.91  5027.8  352.41
  5034.6  361.48    5042   362.4  5109.3  361.46  5308.7  359.87  5439.9  361.45
  5452.7  361.21  5461.9  357.04  5467.8  357.95  5475.6  355.33    5483  357.64
    5489  356.13  5498.1  361.26  5504.1  358.14  5511.4  361.43  5525.2  361.89
  5678.2  359.67  5800.1  361.69  6190.1  380.42    6371  386.11  6697.3  387.24
#Mann= 7 ,-1 , 0
  2964.4     .05       0  4368.7     .12       0  4727.9     .05       0
  5008.6     .03       0  5027.8     .05       0  5109.3     .12       0
  6190.1     .05       0
Bank Sta=5008.6,5027.8
XS Rating Curve= 0 ,0
Exp/Cntr=0.3,0.1

Type RM Length L Ch R = 1 ,8426    ,487,487,487
BEGIN DESCRIPTION:
Mapping XS 923183fd
END DESCRIPTION:
XS GIS Cut Line= 3
      2692613.79      6874189.16      2691596.43      6873588.47
      2690936.68      6873418.32
#Sta/Elev= 30
  3819.7  375.73  3990.9  369.01  4261.4  358.76  4277.1  356.84  4304.9  356.43
  4328.1  359.53    4363   358.5  4467.5  360.42  4474.1  358.45  4479.9  351.96
  4489.8  352.02  4511.2  360.97  4548.3  360.29  4554.1  353.41  4569.7  360.93
  4686.8   360.6  4714.1  358.56  4735.5  360.28  4766.8     359  4868.8  360.37
  4991.1   360.8  4998.5  356.24  4999.1  350.94  5001.1  350.44  5018.7  350.94
  5032.6   359.8  5136.1  359.41  5212.3  361.32    5460   376.5  5682.5  384.27
#Mann= 6 ,-1 , 0
  3819.7     .12       0  3990.9     .05       0  4868.8     .12       0
  4999.1     .07       0  5018.7     .12       0    5460     .05       0
Bank Sta=4999.1,5018.7
XS Rating Curve= 0 ,0
Exp/Cntr=0.3,0.1