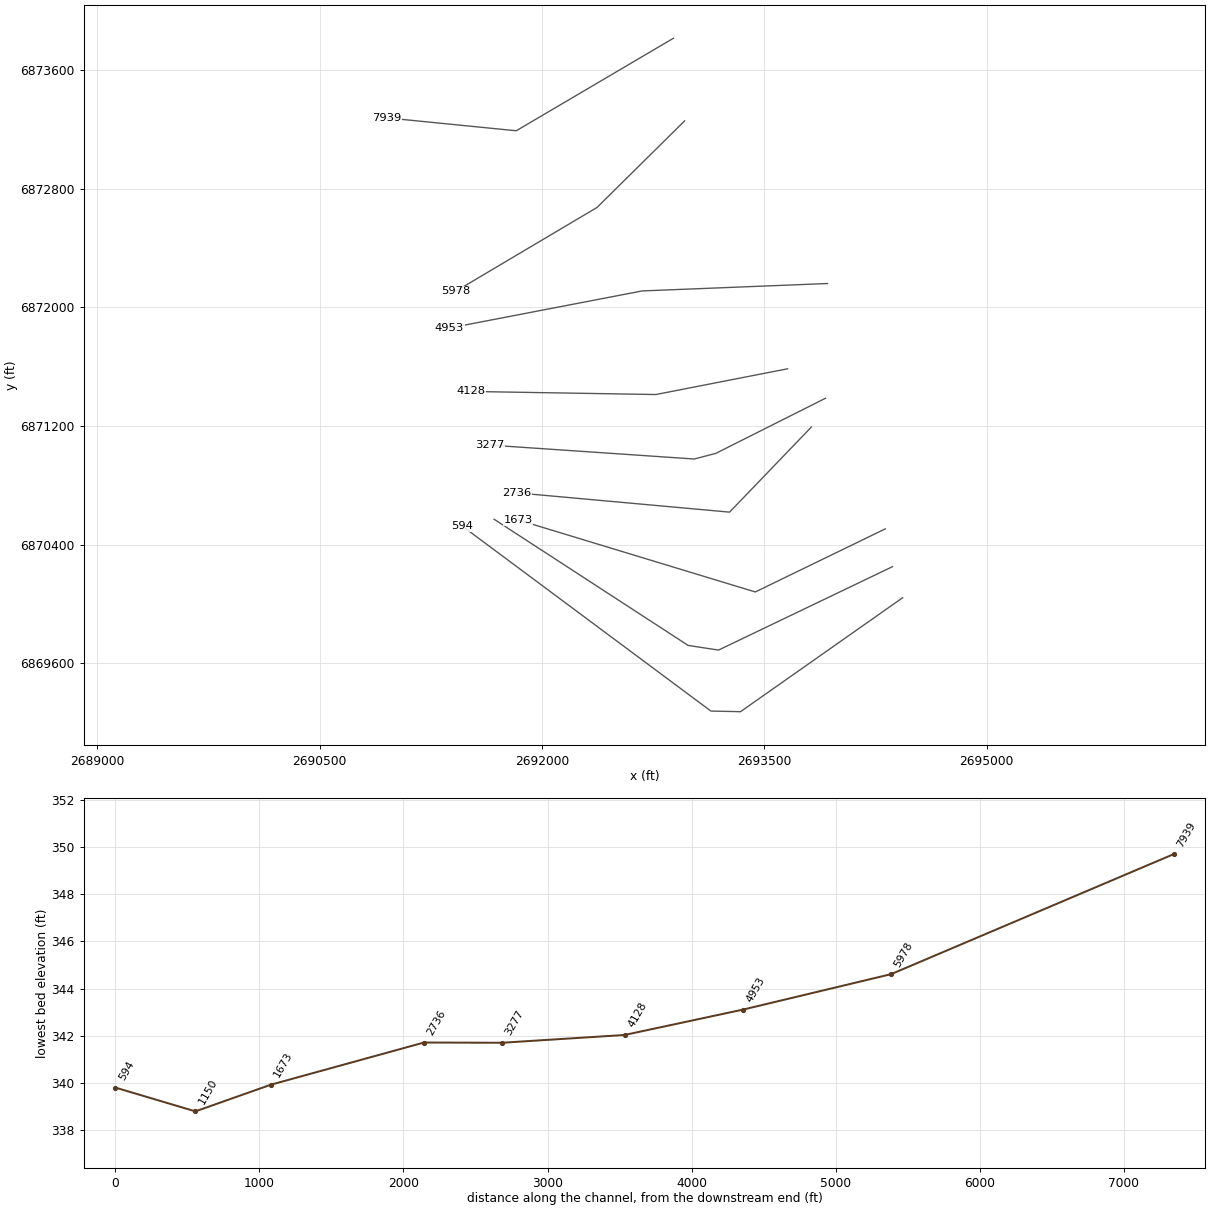
HEC-RAS study Jones Creek.prj: Jones Creek Base Level Engineering

--- Jones Creek.g01 (geometry) --- (continued)

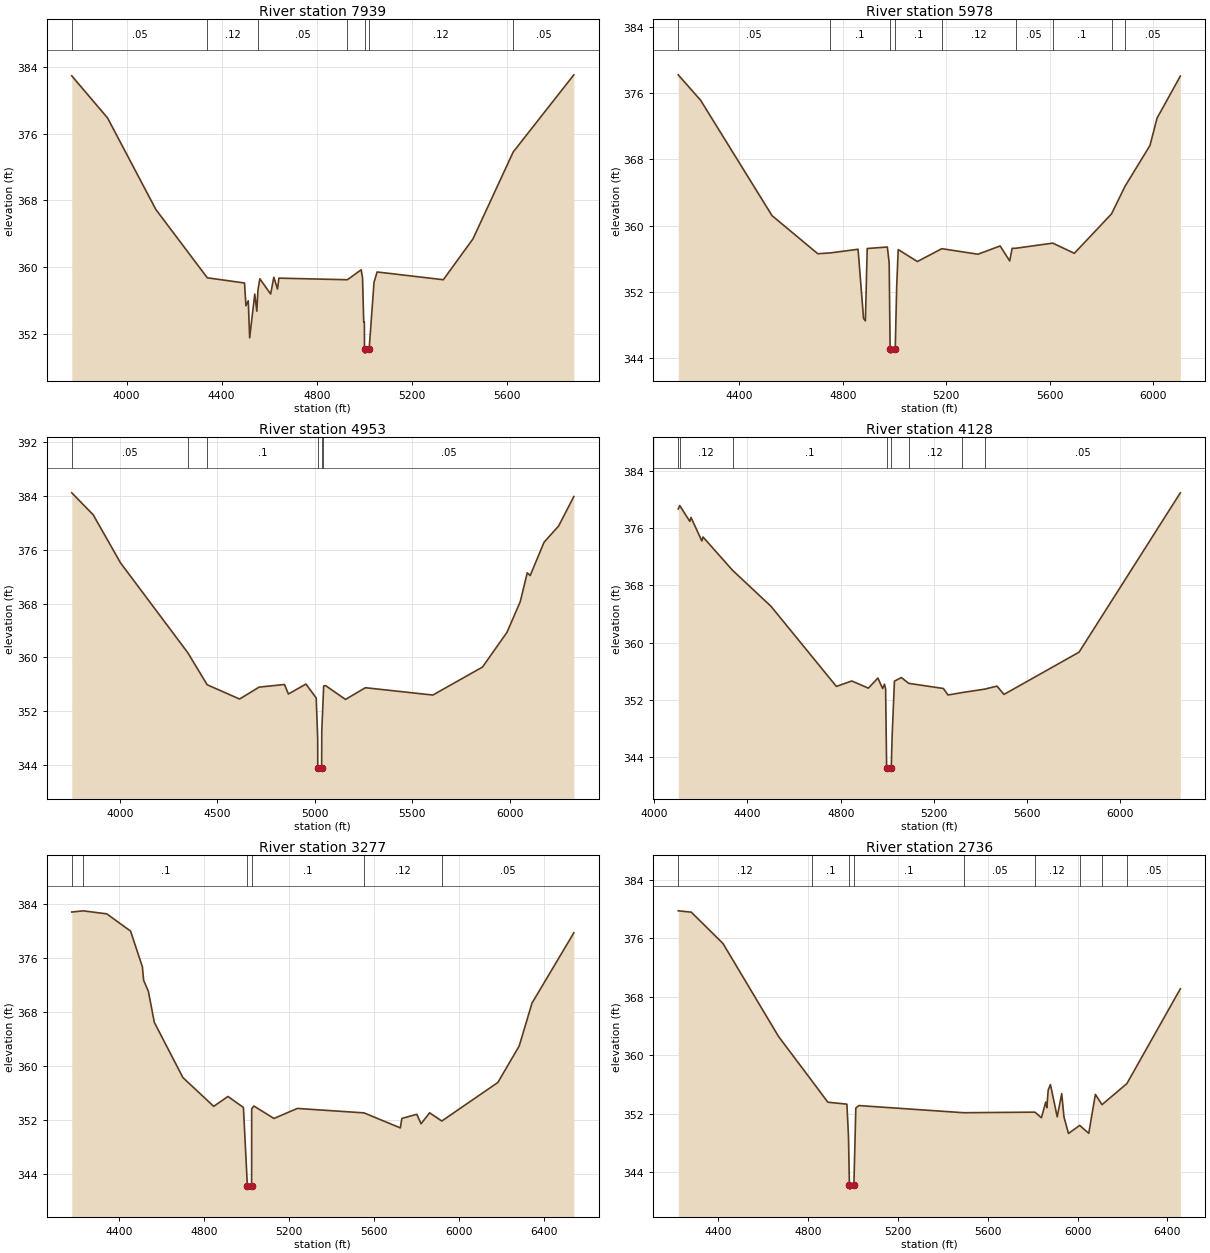
Type RM Length L Ch R = 1 ,7939    ,1961,1961,1961
BEGIN DESCRIPTION:
Jones Creek 6.0
END DESCRIPTION:
XS GIS Cut Line= 3
      2692886.64      6873814.59       2691826.4      6873190.87
      2690950.02      6873278.05
#Sta/Elev= 30
  3769.9  382.91  3920.3  377.87  4123.3  366.91  4339.8  358.72  4496.3   358.1
  4502.1  355.37    4512  355.97  4517.8  351.53  4539.2  356.77    4548  354.72
  4552.6  357.25  4560.7   358.6    4606  356.78  4619.3  358.79  4634.9  357.38
  4640.8  358.68  4928.7  358.49  4986.5  359.68  4992.3  358.76  4997.3  353.43
    5000  353.43  5000.6   350.2  5002.6   349.7  5020.2   350.2  5040.6  358.18
  5053.7  359.42    5332  358.49  5456.8  363.39  5625.8  373.79  5880.7  383.03
#Mann= 7 ,-1 , 0
  3769.9     .05       0  4339.8     .12       0  4552.6     .05       0
  4928.7     .12       0  5000.6     .07       0  5020.2     .12       0
  5625.8     .05       0
Bank Sta=5000.6,5020.2
XS Rating Curve= 0 ,0
Exp/Cntr=0.3,0.1

Type RM Length L Ch R = 1 ,5978    ,1025,1025,1025
BEGIN DESCRIPTION:
Mapping XS 191db6c0
END DESCRIPTION:
XS GIS Cut Line= 3
      2692962.13      6873257.41      2692371.89      6872674.11
      2691417.05      6872108.16
#Sta/Elev= 30
  4164.5  378.21  4251.2  375.13  4526.9  361.21  4703.7  356.61  4752.2  356.71
  4859.3  357.15  4880.5  348.79  4887.6  348.51  4894.6  357.24  4972.4  357.42
  4979.5  355.51  4983.1  345.11  4985.1  344.61  5002.9  345.11  5008.6  352.71
  5014.4  357.11  5088.5  355.67  5182.9  357.22  5322.5  356.55  5408.2  357.55
  5445.2  355.74  5454.5  357.26  5467.9  357.27  5611.6  357.89  5694.8  356.66
  5838.5  361.42  5890.7  364.75  5987.2  369.69  6014.4  372.98  6104.3  378.05
#Mann= 9 ,-1 , 0
  4164.5     .05       0  4752.2      .1       0  4983.1     .07       0
  5002.9      .1       0  5182.9     .12       0  5467.9     .05       0
  5611.6      .1       0  5838.5     .12       0  5890.7     .05       0
Bank Sta=4983.1,5002.9
XS Rating Curve= 0 ,0
Exp/Cntr=0.3,0.1

Type RM Length L Ch R = 1 ,4953    ,825,825,825
BEGIN DESCRIPTION:
Jones Creek 3.0
END DESCRIPTION:
XS GIS Cut Line= 3
      2693926.02        6872161.        2692676.        6872111.
      2691376.04      6871861.01
#Sta/Elev= 30
  3753.8  384.45  3863.9  381.18    4004  374.04  4349.1  360.69  4448.1  355.94
  4614.5  353.82  4714.6  355.59  4844.7  355.98  4864.7  354.57  4954.8  356.04
  5007.4  353.97    5015  347.94  5015.3  343.61  5017.3  343.11  5035.1  343.61
  5035.9     349  5042.5  353.61  5045.6  355.77  5055.7  355.81  5157.6  353.76
  5259.4   355.5  5605.6  354.41  5860.2  358.57    5986  363.74  6053.7  368.28
  6089.8  372.57  6104.6  372.16  6175.9  377.11  6250.7  379.53  6328.6   383.9
#Mann= 6 ,-1 , 0
  3753.8     .05       0  4349.1     .12       0  4448.1      .1       0
  5015.3     .07       0  5035.1      .1       0  5042.5     .05       0
Bank Sta=5015.3,5035.1
XS Rating Curve= 0 ,0
Exp/Cntr=0.3,0.1

Type RM Length L Ch R = 1 ,4128    ,851,851,851
BEGIN DESCRIPTION:
Mapping XS 7ab2bf4c
END DESCRIPTION:
XS GIS Cut Line= 3
      2693656.91      6871586.09      2692768.01      6871412.48
      2691519.48      6871433.29
#Sta/Elev= 30
  4102.9   378.7  4109.4  379.18  4152.6  376.96  4157.7  377.52  4204.2  374.23
  4209.3  374.78  4336.4  370.11  4501.2  365.08  4781.5  353.88  4847.6  354.64
  4918.9  353.64  4959.7  355.05  4980.1  353.57  4987.7  354.19  4992.8  353.53
  4997.1  342.53  4999.1  342.03    5017  342.53  5020.6  346.83  5030.6  354.62
  5060.6  355.12  5091.8  354.31  5240.6  353.59  5260.6  352.68  5319.2  353.01
  5418.2   353.5  5470.7  353.92  5500.7  352.76  5822.8  358.67  6257.3  380.96
#Mann= 8 ,-1 , 0
  4102.9      .1       0  4109.4     .12       0  4336.4      .1       0
  4997.1     .07       0    5017      .1       0  5091.8     .12       0
  5319.2      .1       0  5418.2     .05       0
Bank Sta=4997.1,5017
XS Rating Curve= 0 ,0
Exp/Cntr=0.3,0.1

Type RM Length L Ch R = 1 ,3277    ,541,541,541
BEGIN DESCRIPTION:
Mapping XS 799d4720
END DESCRIPTION:
XS GIS Cut Line= 4
      2693912.62      6871387.53      2693173.05      6871016.01
      2693027.21      6870977.82      2691649.89      6871071.49
#Sta/Elev= 30
  4179.5  382.87    4233  383.05    4344   382.6  4455.7  380.04  4511.4  374.72
  4517.1  372.73  4539.4  371.09  4567.4  366.48  4701.7  358.27  4846.4     354
  4913.4  355.47    4986  353.83  5004.5   342.2  5006.5   341.7  5024.4   342.2
  5024.8  353.64  5035.1  354.05  5129.4   352.2  5239.3  353.69  5552.6  353.03
    5723   350.8  5730.4   352.2  5800.6  352.82  5820.6  351.41  5860.7  353.04
  5918.1  351.82  6181.5  357.55  6281.7  362.97  6341.8  369.34  6538.4  379.78
#Mann= 6 ,-1 , 0
  4179.5     .12       0    4233      .1       0  5004.5     .07       0
  5024.4      .1       0  5552.6     .12       0  5918.1     .05       0
Bank Sta=5004.5,5024.4
XS Rating Curve= 0 ,0
Exp/Cntr=0.3,0.1

Type RM Length L Ch R = 1 ,2736    ,1063,1063,1063
BEGIN DESCRIPTION:
Mapping XS 084b9f61
END DESCRIPTION:
XS GIS Cut Line= 3
      2693816.61      6871192.56      2693265.41      6870619.66
      2691829.91      6870749.76
#Sta/Elev= 30
  4220.9  379.74  4278.9  379.56  4420.4  375.27  4667.9  362.56  4814.7  356.57
  4887.3  353.59  4972.2  353.32  4979.2  348.97  4983.4  342.21  4985.4  341.71
  5003.3  342.21  5011.9  352.79  5025.4  353.13  5492.9  352.15  5809.7  352.23
  5838.7  351.46  5857.7   353.6  5862.7  352.84  5868.8  355.25  5878.8     356
    5909  351.58  5929.1  354.76  5939.1  351.57  5959.2  349.31  6008.9  350.42
  6049.5  349.34    6079  354.66  6108.5  353.25  6219.3  356.13  6457.3  369.08
#Mann= 9 ,-1 , 0
  4220.9     .12       0  4814.7      .1       0  4983.4     .07       0
  5003.3      .1       0  5492.9     .05       0  5809.7     .12       0
  6008.9     .05       0  6108.5      .1       0  6219.3     .05       0
Bank Sta=4983.4,5003.3
XS Rating Curve= 0 ,0
Exp/Cntr=0.3,0.1

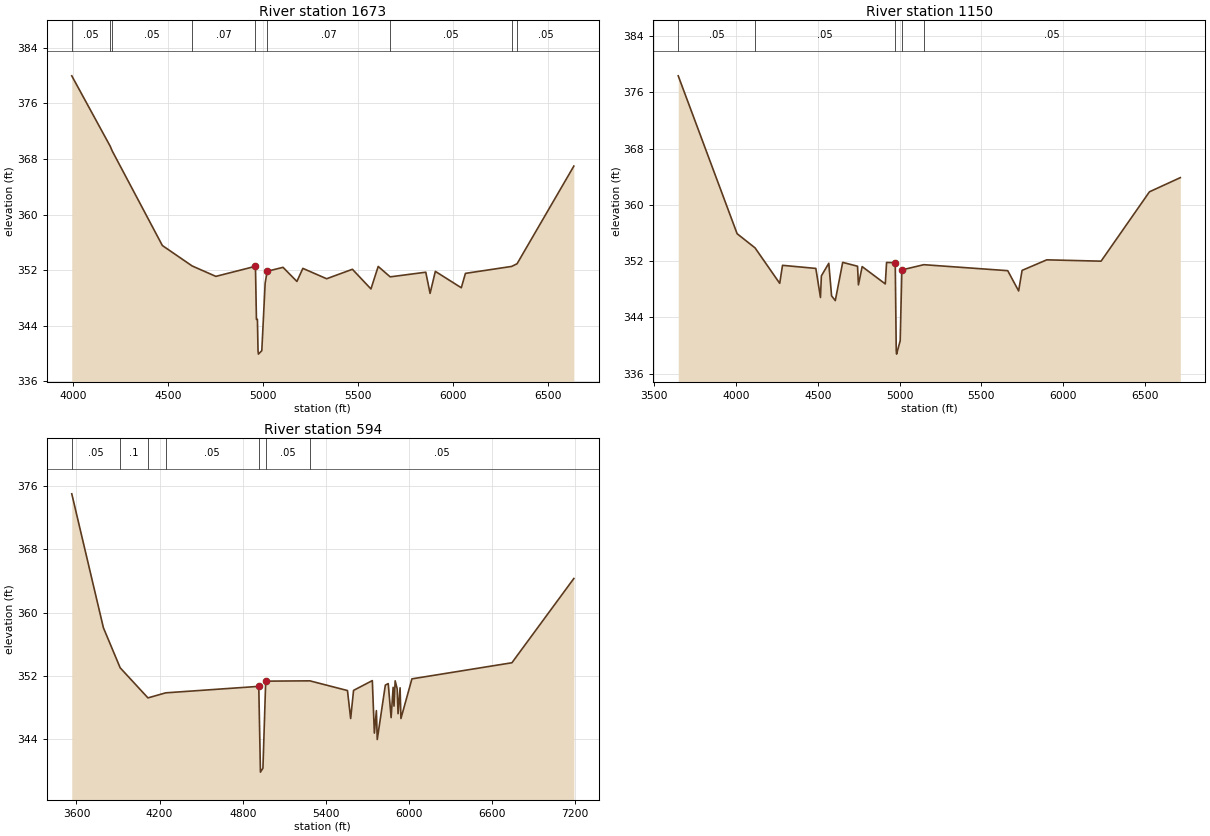
Type RM Length L Ch R = 1 ,1673    ,523,523,523
BEGIN DESCRIPTION:
Mapping XS c6bd8d5a
END DESCRIPTION:
XS GIS Cut Line= 3
      2694315.74       6870506.8      2693439.02      6870081.46
      2691839.24      6870567.03
#Sta/Elev= 30
  3991.4  379.97  4193.8  369.85  4204.8  369.15  4468.9  355.55  4625.8  352.61
  4750.9  351.11  4959.6  352.56  4964.7  344.92    4970  344.92  4973.1  340.42
  4975.1  339.92    4993  340.42  5010.7  350.14  5021.3  351.84  5104.9  352.41
    5178  350.38  5209.4  352.26  5334.8  350.77  5470.6  352.13  5568.3   349.3
  5606.5  352.54  5669.6  351.04  5857.3  351.71    5880  348.66  5907.7  351.83
  6044.5  349.47  6066.3  351.54  6309.5  352.54  6338.3  352.92  6637.7  366.98
#Mann= 9 ,-1 , 0
  3991.4     .05       0  4193.8      .1       0  4204.8     .05       0
  4625.8     .07       0  4959.6     .05       0  5021.3     .07       0
  5669.6     .05       0  6309.5     .12       0  6338.3     .05       0
Bank Sta=4959.6,5021.3
XS Rating Curve= 0 ,0
Exp/Cntr=0.3,0.1

Type RM Length L Ch R = 1 ,1150    ,556,556,556
BEGIN DESCRIPTION:
Mapping XS 8f4149ec
END DESCRIPTION:
XS GIS Cut Line= 4
      2694364.74      6870252.14       2693191.1      6869689.62
      2692986.24      6869720.87      2691677.19      6870571.58
#Sta/Elev= 30
  3646.5  378.34  4006.6   355.9  4116.2  353.89    4267  348.85  4284.1  351.41
  4487.9  350.97  4516.2  346.84  4521.7  349.91    4567   351.7  4584.2  347.07
  4606.8   346.4  4652.1  351.83  4742.8  351.28  4748.3  348.63    4771  351.23
  4912.5  348.77  4920.4  351.82  4973.4  351.78  4979.5  339.29  4981.5  338.79
  5003.7   340.7  5013.8  350.76  5148.2   351.5  5661.2  350.65  5727.8  347.77
  5748.9  350.69  5899.8  352.19  6231.9     352  6527.8  361.86  6716.4  363.87
#Mann= 5 ,-1 , 0
  3646.5     .05       0  4116.2     .05       0  4973.4     .05       0
  5013.8     .05       0  5148.2     .05       0
Bank Sta=4973.4,5013.8
XS Rating Curve= 0 ,0
Exp/Cntr=0.3,0.1

Type RM Length L Ch R = 1 ,594     ,0,0,0
BEGIN DESCRIPTION:
Mapping XS 3c84b58c
END DESCRIPTION:
XS GIS Cut Line= 4
      2694432.92      6870042.38      2693339.19      6869274.17
      2693139.54      6869278.51      2691464.23      6870524.14
#Sta/Elev= 30
  3566.2  375.04  3794.6  358.08  3915.6  353.01  4116.1   349.2  4244.4  349.84
    4916  350.66    4928   339.8    4946   340.3    4966  351.32  5284.5  351.36
  5556.2  350.13  5579.2  346.59  5600.1  350.15  5735.6  351.39  5750.3  344.74
  5764.9  347.59  5771.1  343.93  5829.5  350.82  5850.4  351.01  5871.2   346.7
  5885.8  350.54  5892.1  348.16  5900.4  351.36    5915  350.34  5921.3   347.2
  5935.9  350.48  5942.1  346.59  6021.4  351.61  6743.1  353.65  7190.1  364.32
#Mann= 7 ,-1 , 0
  3566.2     .05       0  3915.6      .1       0  4116.1      .1       0
  4244.4     .05       0    4916     .05       0    4966     .05       0
  5284.5     .05       0
Bank Sta=4916,4966
XS Rating Curve= 0 ,0
Exp/Cntr=0.3,0.1

Chan Stop Cuts=-1
Use User Specified Reach Order=0
Composite Channel Slope=5