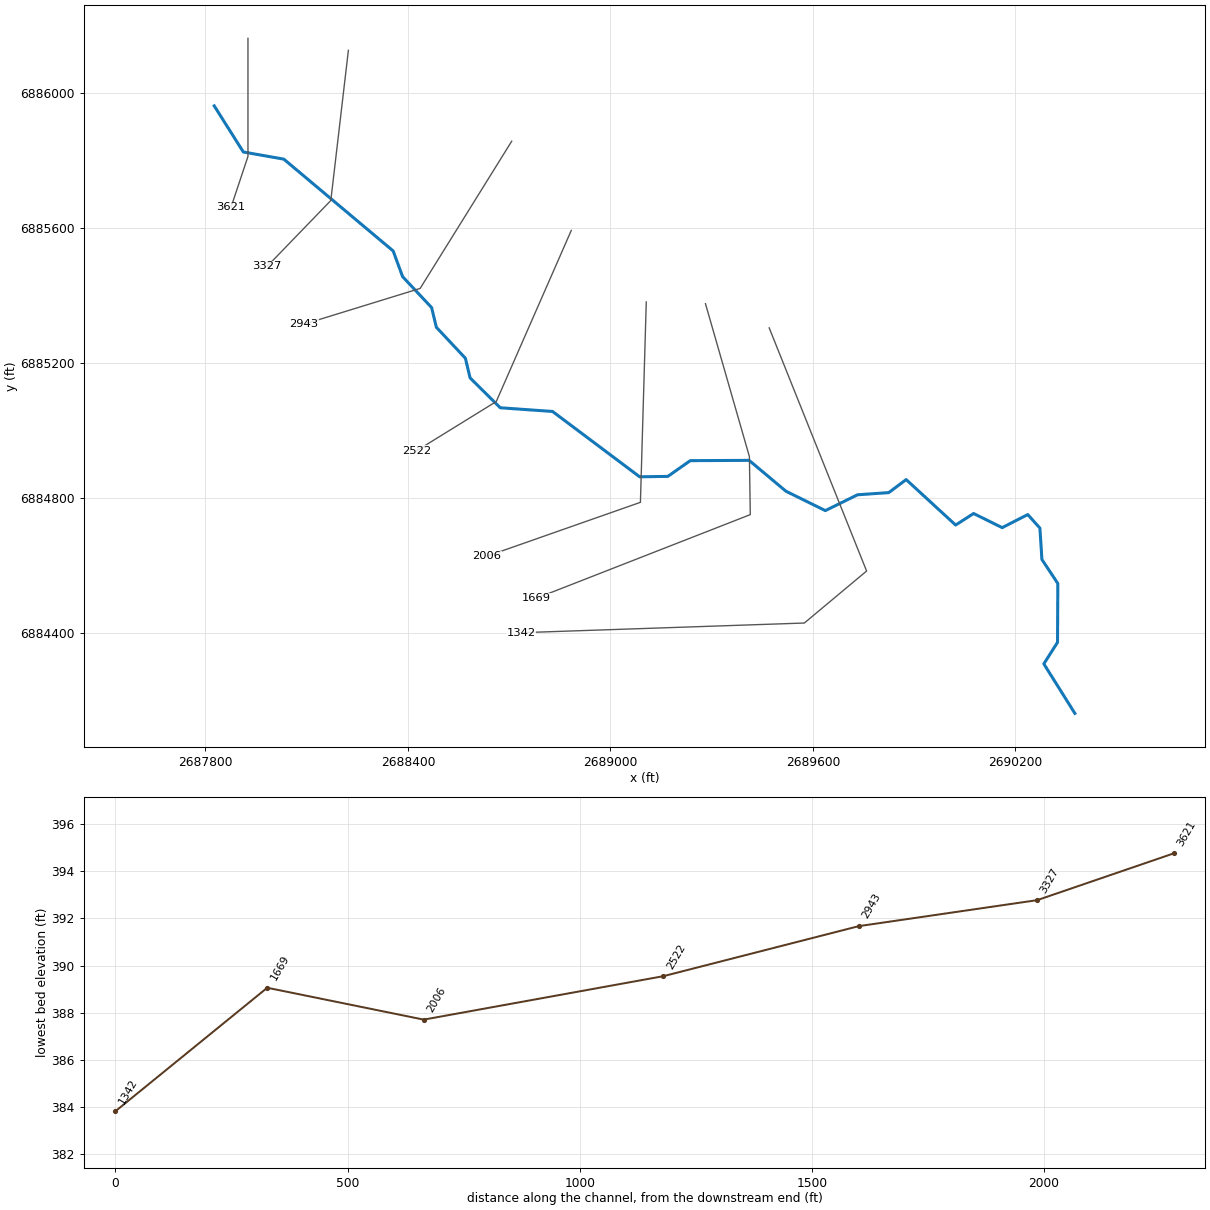
--- Jones T1.prj (project) ---

Proj Title=Jones T1 Base Level Engineering
Current Plan=p01
Default Exp/Contr=0.3,0.1
English Units
Geom File=g01
Flow File=f01
Plan File=p01
BEGIN DESCRIPTION:
Jones T1
END DESCRIPTION:

--- Jones T1.p01 (plan) ---

Plan Title=Multiple Run
Short Identifier=Multiple
Geom File=g01
Flow File=f01
Subcritical Flow
K Sum by GR= 0
Std Step Tol= 0.01
Critical Tol= 0.01
Num of Std Step Trials= 20
Max Error Tol= 0.3
Flow Tol Ratio= 0.001
Split Flow NTrial= 30
Split Flow Tol= 0.02
Split Flow Ratio= 0.02
Log Output Level= 0
Friction Slope Method= 1
Unsteady Friction Slope Method= 2
Unsteady Bridges Friction Slope Method= 1
Parabolic Critical Depth
Global Vel Dist=  1 , 1 , 1
Global Log Level= 0
CheckData=True
Encroach Param= -1, 0, 0, 0
BEGIN DESCRIPTION:
Multiple Run
END DESCRIPTION:

--- Jones T1.f01 (steady flow) ---

Flow Title=Multiple
Number of Profiles=7
Profile Names=10-year,25-year,50-year,1pct_min,100-year,1pct_plu,500-year
River Rch & RM= Jones T1,Reach-1,3621
     658     892    1083     653    1303    2599    1883
Boundary for River Rch & Prof#=Jones T1,Reach-1,1
Up Type=0
Dn Type=3
Dn Slope=0.005
Boundary for River Rch & Prof#=Jones T1,Reach-1,2
Up Type=0
Dn Type=3
Dn Slope=0.005
Boundary for River Rch & Prof#=Jones T1,Reach-1,3
Up Type=0
Dn Type=3
Dn Slope=0.005
Boundary for River Rch & Prof#=Jones T1,Reach-1,4
Up Type=0
Dn Type=3
Dn Slope=0.005
Boundary for River Rch & Prof#=Jones T1,Reach-1,5
Up Type=0
Dn Type=3
Dn Slope=0.005
Boundary for River Rch & Prof#=Jones T1,Reach-1,6
Up Type=0
Dn Type=3
Dn Slope=0.005
Boundary for River Rch & Prof#=Jones T1,Reach-1,7
Up Type=0
Dn Type=3
Dn Slope=0.005

--- Jones T1.g01 (geometry) ---

Geom Title=Existing Conditions

River Reach=Jones T1,Reach-1
Reach XY= 30
      2687826.00      6885961.00      2687912.34      6885824.24
      2688032.17      6885803.14      2688356.21      6885531.09
      2688384.18      6885454.96      2688470.13      6885363.28
      2688484.18      6885304.96      2688570.13      6885213.28
      2688584.15      6885154.93      2688673.54      6885066.46
      2688828.44      6885055.52      2689086.48      6884861.94
      2689170.02      6884863.16      2689236.50      6884909.78
      2689410.84      6884910.62      2689519.95      6884819.16
      2689636.68      6884761.75      2689731.97      6884808.62
      2689824.50      6884815.10      2689876.10      6884853.69
      2690022.66      6884718.99      2690075.91      6884753.16
      2690160.64      6884711.29      2690236.43      6884750.04
      2690272.39      6884709.98      2690278.36      6884616.98
      2690325.48      6884545.78      2690324.62      6884371.44
      2690284.02      6884307.68      2690376.00      6884161.00

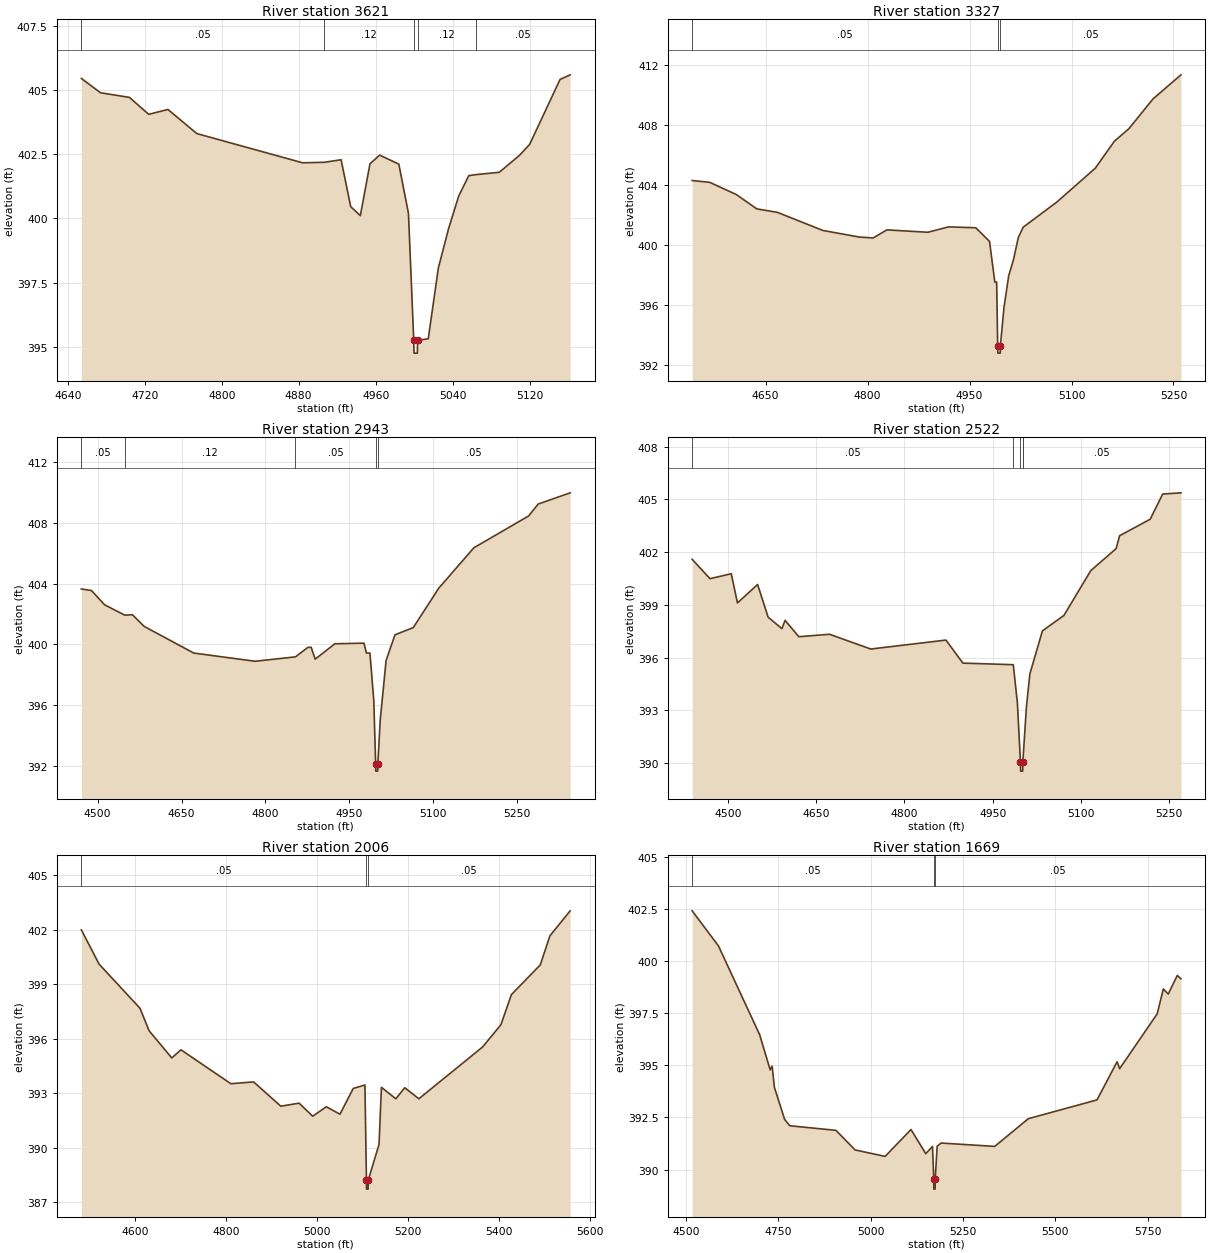
Type RM Length L Ch R = 1,3621,294,294,294
BEGIN DESCRIPTION:
Jones T1 5.0
END DESCRIPTION:
XS GIS Cut Line= 3
      2687926.00      6886161.03      2687926.00      6885811.00
      2687876.01      6885661.04
#Sta/Elev= 30
  4654.1  405.46  4674.1  404.90  4704.1  404.72  4724.1  404.06  4744.1  404.25
  4774.1  403.31  4884.1  402.17  4906.8  402.19  4924.1  402.29  4934.1  400.46
  4944.1  400.11  4954.1  402.13  4964.1  402.47  4984.1  402.12  4994.1  400.20
  4999.6  395.25  4999.9  394.75  5003.4  394.75  5003.6  395.25  5014.7  395.31
  5025.2  398.07  5035.8  399.60  5046.3  400.87  5056.8  401.67  5064.6  401.71
  5088.5  401.80  5109.5  402.46  5120.1  402.89  5151.7  405.42  5162.2  405.60
#Mann=5,-1,0
  4654.1    0.05       0  4906.8    0.12       0  4999.6    0.07       0
  5003.6    0.12       0  5064.6    0.05       0
Bank Sta=4999.6,5003.6
Exp/Cntr=0.3,0.1

Type RM Length L Ch R = 1,3327,384,384,384
BEGIN DESCRIPTION:
Mapping XS aca291e3
END DESCRIPTION:
XS GIS Cut Line= 3
      2688223.55      6886125.41      2688171.46      6885680.51
      2687983.07      6885485.62
#Sta/Elev= 30
  4542.0  404.28  4567.8  404.16  4606.8  403.35  4637.1  402.39  4667.3  402.16
  4734.3  400.95  4788.1  400.51  4808.2  400.45  4828.4  400.99  4888.8  400.83
  4919.0  401.19  4959.2  401.13  4979.4  400.22  4987.2  397.51  4989.9  397.51
  4991.4  393.27  4991.7  392.77  4995.2  392.77  4995.4  393.27  5000.6  395.79
  5007.6  397.93  5014.8  399.03  5021.7  400.47  5028.9  401.17  5078.3  402.84
  5134.9  405.10  5163.2  406.91  5184.3  407.73  5219.8  409.72  5261.0  411.33
#Mann=3,-1,0
  4542.0    0.05       0  4991.4    0.03       0  4995.4    0.05       0
Bank Sta=4991.4,4995.4
Exp/Cntr=0.3,0.1

Type RM Length L Ch R = 1,2943,421,421,421
BEGIN DESCRIPTION:
Mapping XS b7584a6b
END DESCRIPTION:
XS GIS Cut Line= 3
      2688707.49      6885856.29      2688436.22      6885420.09
      2688091.20      6885313.76
#Sta/Elev= 30
  4470.8  403.64  4488.9  403.54  4512.4  402.60  4548.6  401.92  4562.1  401.95
  4583.3  401.18  4671.9  399.43  4781.7  398.89  4853.9  399.18  4876.1  399.80
  4882.0  399.81  4889.2  399.03  4924.5  400.04  4976.5  400.08  4981.0  399.43
  4987.2  399.43  4994.1  396.31  4997.4  392.17  4997.6  391.67  5001.1  391.67
  5001.4  392.17  5005.6  395.03  5016.1  398.94  5032.0  400.63  5064.7  401.10
  5110.3  403.69  5173.2  406.35  5271.2  408.44  5288.2  409.22  5345.5  409.96
#Mann=5,-1,0
  4470.8    0.05       0  4548.6    0.12       0  4853.9    0.05       0
  4997.4    0.03       0  5001.4    0.05       0
Bank Sta=4997.4,5001.4
Exp/Cntr=0.3,0.1

Type RM Length L Ch R = 1,2522,516,516,516
BEGIN DESCRIPTION:
Mapping XS d4052648
END DESCRIPTION:
XS GIS Cut Line= 3
      2688883.93      6885591.91      2688661.70      6885084.94
      2688425.56      6884939.08
#Sta/Elev= 30
  4439.0  401.59  4469.3  400.49  4505.5  400.77  4516.0  399.11  4550.3  400.16
  4568.2  398.30  4591.6  397.65  4597.0  398.12  4620.4  397.19  4672.6  397.33
  4742.7  396.49  4870.5  397.00  4899.3  395.69  4985.0  395.60  4992.0  393.42
  4997.2  390.05  4997.5  389.55  5001.0  389.55  5001.2  390.05  5002.0  390.46
  5007.3  393.19  5013.2  395.08  5034.5  397.52  5071.1  398.40  5116.8  400.95
  5159.9  402.20  5165.7  402.93  5217.8  403.87  5239.0  405.30  5270.1  405.37
#Mann=5,-1,0
  4439.0    0.05       0  4985.0    0.12       0  4997.2    0.07       0
  5001.2    0.12       0  5002.0    0.05       0
Bank Sta=4997.2,5001.2
Exp/Cntr=0.3,0.1

Type RM Length L Ch R = 1,2006,337,337,337
BEGIN DESCRIPTION:
Mapping XS 08b07e63
END DESCRIPTION:
XS GIS Cut Line= 3
      2689106.14      6885380.06      2689088.78      6884786.32
      2688633.90      6884626.60
#Sta/Elev= 30
  4481.0  402.00  4520.1  400.11  4610.1  397.68  4630.1  396.44  4680.1  394.94
  4700.2  395.39  4810.2  393.52  4860.2  393.62  4920.2  392.28  4960.3  392.45
  4990.3  391.73  5020.3  392.25  5050.3  391.84  5079.6  393.26  5105.3  393.45
  5108.6  388.21  5108.8  387.71  5112.3  387.71  5112.6  388.21  5136.3  390.17
  5141.6  393.32  5173.3  392.69  5193.0  393.30  5224.0  392.69  5364.1  395.54
  5404.6  396.77  5427.7  398.43  5491.3  400.07  5512.5  401.67  5557.1  403.05
#Mann=3,-1,0
  4481.0    0.05       0  5108.6    0.04       0  5112.6    0.05       0
Bank Sta=5108.6,5112.6
Exp/Cntr=0.3,0.1

Type RM Length L Ch R = 1,1669,327,327,327
BEGIN DESCRIPTION:
Mapping XS bee82895
END DESCRIPTION:
XS GIS Cut Line= 4
      2689281.50      6885374.83      2689411.70      6884921.74
      2689414.30      6884749.87      2688781.47      6884502.46
#Sta/Elev= 30
  4517.3  402.41  4588.4  400.73  4699.9  396.47  4728.5  394.78  4733.7  394.96
  4739.8  393.95  4767.4  392.41  4781.4  392.10  4906.3  391.88  4958.3  390.94
  5039.5  390.63  5109.5  391.92  5149.5  390.76  5167.7  391.11  5171.1  389.56
  5171.3  389.06  5174.8  389.06  5175.1  389.56  5180.3  391.12  5191.0  391.27
  5336.0  391.11  5427.2  392.44  5612.9  393.34  5667.2  395.17  5674.2  394.84
  5775.8  397.47  5792.3  398.66  5805.7  398.42  5830.1  399.31  5840.1  399.15
#Mann=3,-1,0
  4517.3    0.05       0  5171.1    0.04       0  5175.1    0.05       0
Bank Sta=5171.1,5175.1
Exp/Cntr=0.3,0.1

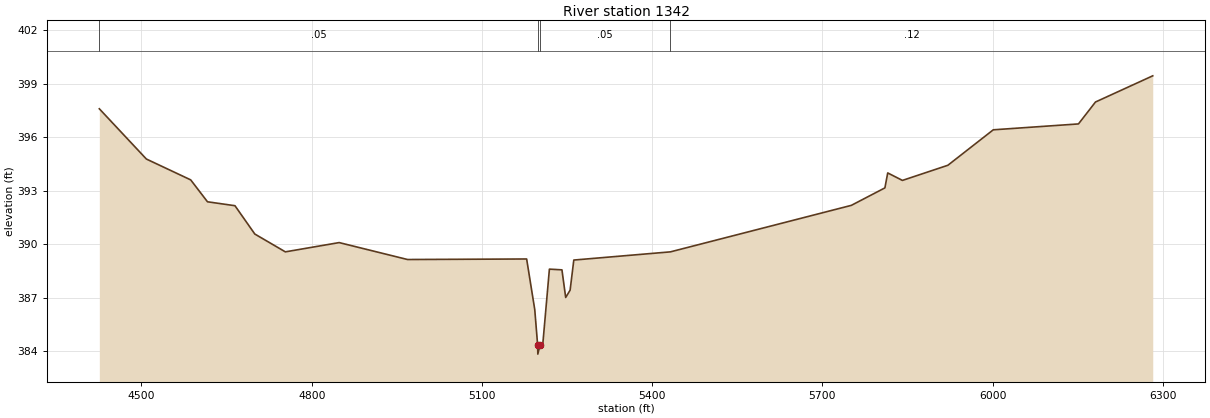
Type RM Length L Ch R = 1,1342,0,0,0
BEGIN DESCRIPTION:
Jones T1 1.0
END DESCRIPTION:
XS GIS Cut Line= 4
      2689470.28      6885303.27      2689758.92      6884582.77
      2689574.46      6884428.69      2688735.17      6884400.04
#Sta/Elev= 30
  4425.8  397.60  4508.7  394.78  4586.8  393.61  4616.4  392.38  4664.8  392.16
  4699.8  390.57  4753.6  389.57  4848.4  390.09  4968.9  389.14  5178.8  389.17
  5193.1  386.33  5198.2  384.33  5198.5  383.83  5202.2  384.33  5207.1  384.33
  5218.9  388.60  5241.0  388.56  5247.6  387.01  5255.4  387.42  5261.9  389.11
  5432.2  389.57  5751.0  392.18  5810.1  393.16  5815.1  394.00  5841.0  393.58
  5921.1  394.43  6001.1  396.42  6151.2  396.75  6181.2  397.98  6282.1  399.45
#Mann=4,-1,0
  4425.8    0.05       0  5198.2    0.03       0  5202.2    0.05       0
  5432.2    0.12       0
Bank Sta=5198.2,5202.2
Exp/Cntr=0.3,0.1

Chan Stop Cuts=-1