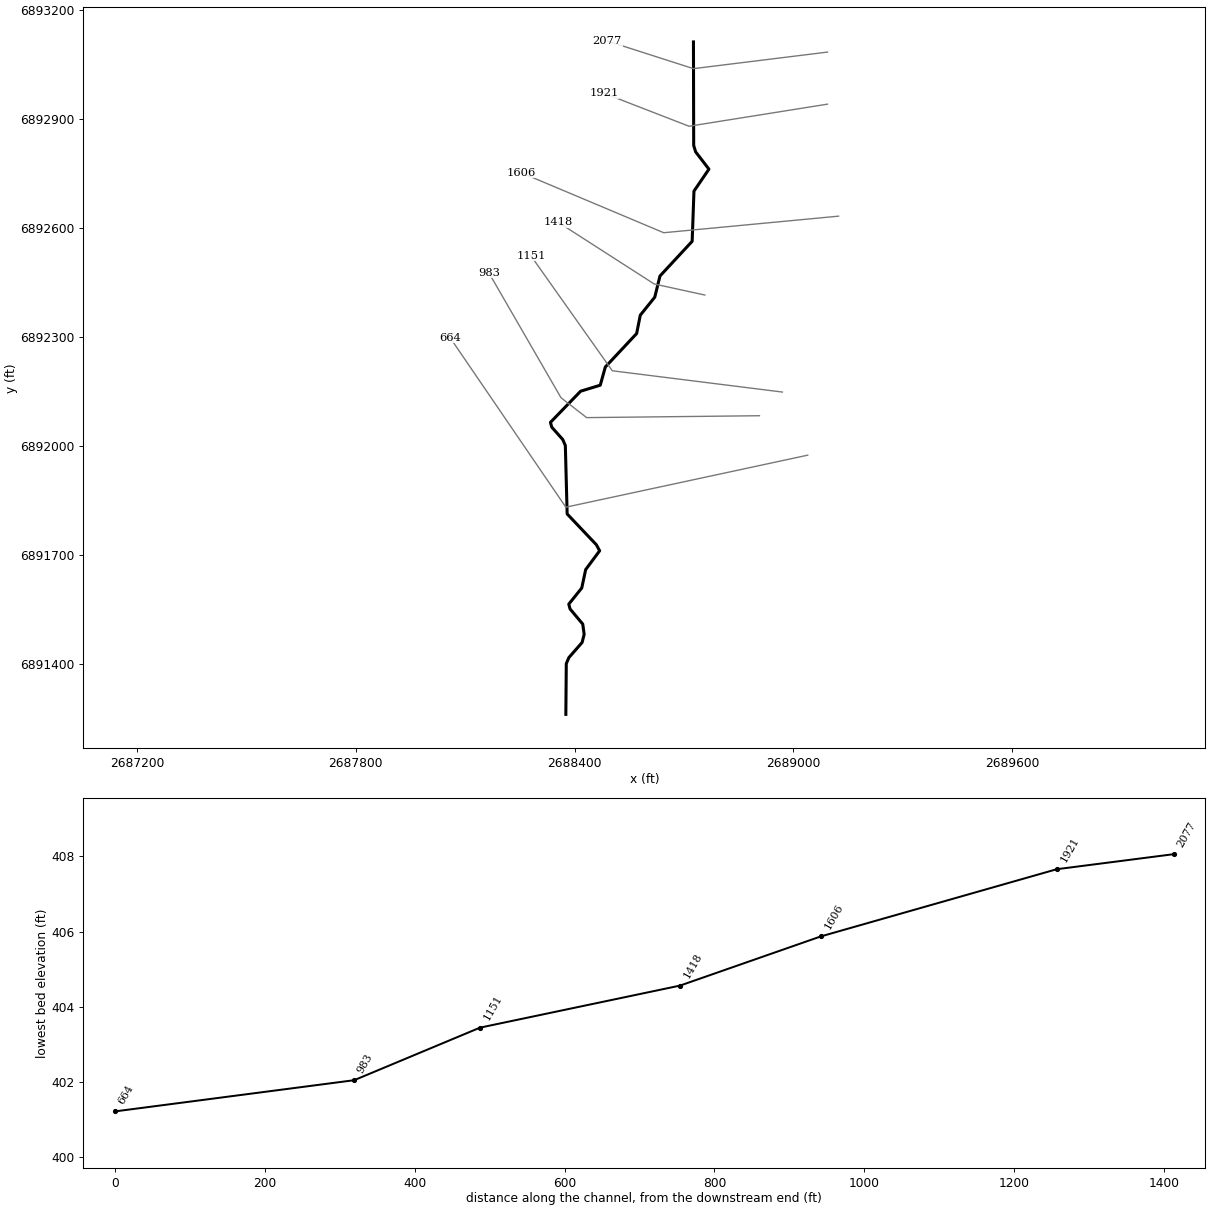
--- Jones T2.prj (project) ---

Proj Title=Jones T2 Base Level Engineering
Current Plan=p01
Default Exp/Contr=0.3,0.1
English Units
Geom File=g01
Flow File=f01
Plan File=p01
BEGIN DESCRIPTION:
Jones T2
END DESCRIPTION:

--- Jones T2.p01 (plan) ---

Plan Title=Multiple Run
Short Identifier=Multiple
Geom File=g01
Flow File=f01
Subcritical Flow
K Sum by GR= 0
Std Step Tol= 0.01
Critical Tol= 0.01
Num of Std Step Trials= 20
Max Error Tol= 0.3
Flow Tol Ratio= 0.001
Split Flow NTrial= 30
Split Flow Tol= 0.02
Split Flow Ratio= 0.02
Log Output Level= 0
Friction Slope Method= 1
Unsteady Friction Slope Method= 2
Unsteady Bridges Friction Slope Method= 1
Parabolic Critical Depth
Global Vel Dist=  1 , 1 , 1
Global Log Level= 0
CheckData=True
Encroach Param= -1, 0, 0, 0
BEGIN DESCRIPTION:
Multiple Run
END DESCRIPTION:

--- Jones T2.f01 (steady flow) ---

Flow Title=Multiple
Number of Profiles=7
Profile Names=10-year,25-year,50-year,1pct_min,100-year,1pct_plu,500-year
River Rch & RM= Jones T2,Reach-1,2077
     373     486     575     338     674    1346     927
Boundary for River Rch & Prof#=Jones T2,Reach-1,1
Up Type=0
Dn Type=3
Dn Slope=0.005
Boundary for River Rch & Prof#=Jones T2,Reach-1,2
Up Type=0
Dn Type=3
Dn Slope=0.005
Boundary for River Rch & Prof#=Jones T2,Reach-1,3
Up Type=0
Dn Type=3
Dn Slope=0.005
Boundary for River Rch & Prof#=Jones T2,Reach-1,4
Up Type=0
Dn Type=3
Dn Slope=0.005
Boundary for River Rch & Prof#=Jones T2,Reach-1,5
Up Type=0
Dn Type=3
Dn Slope=0.005
Boundary for River Rch & Prof#=Jones T2,Reach-1,6
Up Type=0
Dn Type=3
Dn Slope=0.005
Boundary for River Rch & Prof#=Jones T2,Reach-1,7
Up Type=0
Dn Type=3
Dn Slope=0.005

--- Jones T2.g01 (geometry) ---

Geom Title=Existing Conditions

River Reach=Jones T2,Reach-1
Reach XY= 30
      2688726.00      6893111.00      2688726.66      6892826.16
      2688732.02      6892808.55      2688768.44      6892761.00
      2688727.40      6892700.56      2688722.45      6892562.47
      2688634.16      6892467.05      2688619.90      6892408.81
      2688580.19      6892359.27      2688570.15      6892308.71
      2688484.30      6892216.74      2688470.38      6892166.62
      2688416.54      6892150.11      2688333.79      6892064.43
      2688337.33      6892051.16      2688367.53      6892017.19
      2688374.61      6892000.57      2688379.56      6891812.46
      2688459.68      6891727.69      2688468.70      6891711.08
      2688430.40      6891659.35      2688419.64      6891608.72
      2688384.07      6891564.31      2688387.52      6891551.08
      2688422.39      6891509.36      2688426.21      6891481.21
      2688420.61      6891458.83      2688384.18      6891417.08
      2688377.19      6891400.52      2688376.00      6891261.00

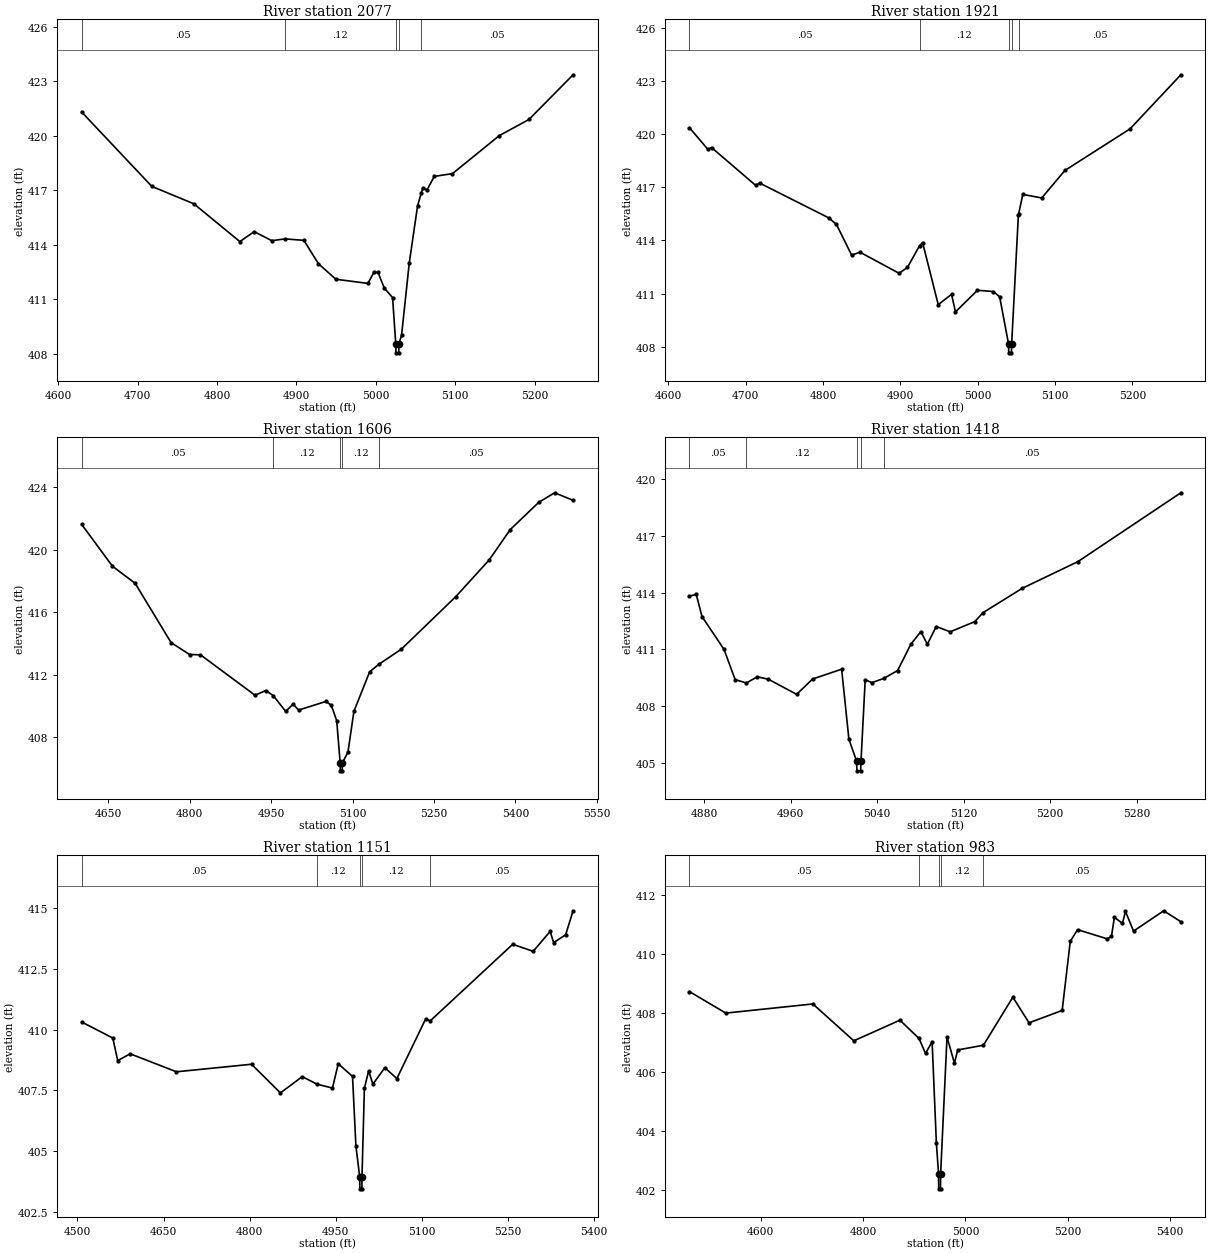
Type RM Length L Ch R = 1,2077,156,156,156
BEGIN DESCRIPTION:
Jones T2 2.0
END DESCRIPTION:
XS GIS Cut Line= 3
      2689093.67      6893083.08      2688725.98      6893037.50
      2688489.61      6893113.54
#Sta/Elev= 30
  4629.5  421.31  4717.8  417.22  4770.8  416.26  4828.7  414.18  4846.7  414.73
  4869.0  414.23  4885.5  414.33  4909.3  414.25  4927.7  412.96  4949.6  412.11
  4989.9  411.88  4997.5  412.49  5002.6  412.49  5010.5  411.63  5021.0  411.10
  5025.0  408.56  5025.3  408.06  5028.8  408.06  5029.0  408.56  5032.3  409.02
  5042.0  413.00  5052.5  416.16  5057.0  416.83  5059.1  417.14  5064.3  417.02
  5073.5  417.77  5096.4  417.92  5155.3  420.01  5192.7  420.90  5248.3  423.36
#Mann=5,-1,0
  4629.5    0.05       0  4885.5    0.12       0  5025.0    0.07       0
  5029.0    0.12       0  5057.0    0.05       0
Bank Sta=5025,5029
Exp/Cntr=0.3,0.1

Type RM Length L Ch R = 1,1921,315,315,315
BEGIN DESCRIPTION:
Mapping XS c68c5101
END DESCRIPTION:
XS GIS Cut Line= 3
      2689093.60      6892939.84      2688713.86      6892879.08
      2688480.27      6892969.92
#Sta/Elev= 30
  4627.5  420.37  4651.1  419.15  4656.2  419.24  4713.1  417.11  4718.2  417.24
  4807.4  415.28  4817.5  414.91  4837.2  413.17  4847.9  413.34  4898.5  412.15
  4909.3  412.48  4925.0  413.71  4928.9  413.88  4949.1  410.38  4966.3  410.96
  4971.4  409.97  4999.8  411.19  5020.5  411.12  5028.5  410.82  5040.0  408.16
  5040.2  407.66  5043.7  407.66  5044.0  408.16  5052.7  415.43  5053.1  415.51
  5058.4  416.60  5082.9  416.40  5112.8  417.95  5197.1  420.30  5262.7  423.35
#Mann=5,-1,0
  4627.5    0.05       0  4925.0    0.12       0  5040.0    0.07       0
  5044.0    0.12       0  5053.1    0.05       0
Bank Sta=5040,5044
Exp/Cntr=0.3,0.1

Type RM Length L Ch R = 1,1606,188,188,188
BEGIN DESCRIPTION:
Mapping XS 678a6d42
END DESCRIPTION:
XS GIS Cut Line= 3
      2689124.02      6892631.69      2688644.42      6892586.11
      2688253.78      6892751.05
#Sta/Elev= 30
  4600.6  421.61  4657.3  418.94  4699.1  417.85  4765.4  414.06  4799.5  413.30
  4819.6  413.28  4920.1  410.70  4940.1  411.00  4953.8  410.67  4976.6  409.67
  4990.4  410.13  5000.4  409.75  5050.6  410.30  5060.7  410.06  5070.7  409.07
  5077.1  406.37  5077.3  405.87  5080.8  405.87  5081.1  406.37  5091.5  407.08
  5102.4  409.67  5131.5  412.20  5148.6  412.68  5189.8  413.64  5290.0  416.99
  5352.0  419.35  5390.3  421.27  5443.1  423.02  5472.3  423.63  5506.4  423.15
#Mann=5,-1,0
  4600.6    0.05       0  4953.8    0.12       0  5077.1    0.07       0
  5081.1    0.12       0  5148.6    0.05       0
Bank Sta=5077.1,5081.1
Exp/Cntr=0.3,0.1

Type RM Length L Ch R = 1,1418,267,267,267
BEGIN DESCRIPTION:
Mapping XS 7b970920
END DESCRIPTION:
XS GIS Cut Line= 3
      2688757.28      6892414.67      2688618.37      6892445.06
      2688355.80      6892614.32
#Sta/Elev= 30
  4866.2  413.81  4872.5  413.90  4877.8  412.73  4898.2  410.99  4908.5  409.39
  4918.9  409.21  4928.9  409.54  4939.2  409.41  4965.4  408.61  4980.1  409.42
  5007.0  409.94  5013.7  406.24  5020.9  405.06  5021.1  404.56  5024.6  404.56
  5024.9  405.06  5028.8  409.38  5035.0  409.23  5045.9  409.45  5058.8  409.87
  5071.1  411.27  5080.3  411.93  5086.3  411.26  5094.5  412.20  5107.4  411.92
  5130.2  412.46  5137.7  412.93  5174.0  414.22  5225.4  415.63  5320.8  419.28
#Mann=5,-1,0
  4866.2    0.05       0  4918.9    0.12       0  5020.9    0.07       0
  5024.9    0.12       0  5045.9    0.05       0
Bank Sta=5020.9,5024.9
Exp/Cntr=0.3,0.1

Type RM Length L Ch R = 1,1151,168,168,168
BEGIN DESCRIPTION:
Mapping XS a7e014ec
END DESCRIPTION:
XS GIS Cut Line= 3
      2688969.90      6892147.75      2688503.36      6892206.34
      2688280.45      6892522.31
#Sta/Elev= 30
  4507.3  410.31  4561.6  409.65  4570.1  408.72  4591.9  409.00  4672.5  408.26
  4803.5  408.57  4853.9  407.39  4891.9  408.06  4917.7  407.75  4944.6  407.59
  4954.7  408.59  4979.6  408.07  4985.5  405.20  4992.1  403.94  4992.4  403.44
  4995.9  403.44  4996.1  403.94  5000.3  407.58  5007.7  408.30  5015.1  407.75
  5036.0  408.43  5056.9  407.98  5107.4  410.45  5114.8  410.35  5258.9  413.51
  5294.6  413.22  5324.2  414.04  5330.3  413.58  5351.2  413.90  5364.2  414.89
#Mann=5,-1,0
  4507.3    0.05       0  4917.7    0.12       0  4992.1    0.07       0
  4996.1    0.12       0  5114.8    0.05       0
Bank Sta=4992.1,4996.1
Exp/Cntr=0.3,0.1

Type RM Length L Ch R = 1,983,319,319,319
BEGIN DESCRIPTION:
Mapping XS 908c9bde
END DESCRIPTION:
XS GIS Cut Line= 4
      2688907.04      6892082.64      2688433.05      6892077.43
      2688362.73      6892132.12      2688164.79      6892475.91
#Sta/Elev= 30
  4460.9  408.73  4531.9  408.00  4702.0  408.31  4782.0  407.06  4872.0  407.76
  4909.3  407.14  4922.0  406.63  4934.9  407.03  4943.2  403.60  4947.5  402.54
  4947.8  402.04  4951.3  402.04  4951.5  402.54  4964.0  407.19  4978.5  406.30
  4984.8  406.75  5035.1  406.91  5092.6  408.54  5124.2  407.67  5188.9  408.09
  5204.7  410.43  5218.9  410.83  5276.6  410.52  5285.2  410.60  5290.9  411.25
  5306.7  411.04  5312.5  411.45  5328.3  410.78  5387.2  411.47  5420.7  411.10
#Mann=5,-1,0
  4460.9    0.05       0  4909.3    0.12       0  4947.5    0.07       0
  4951.5    0.12       0  5035.1    0.05       0
Bank Sta=4947.5,4951.5
Exp/Cntr=0.3,0.1

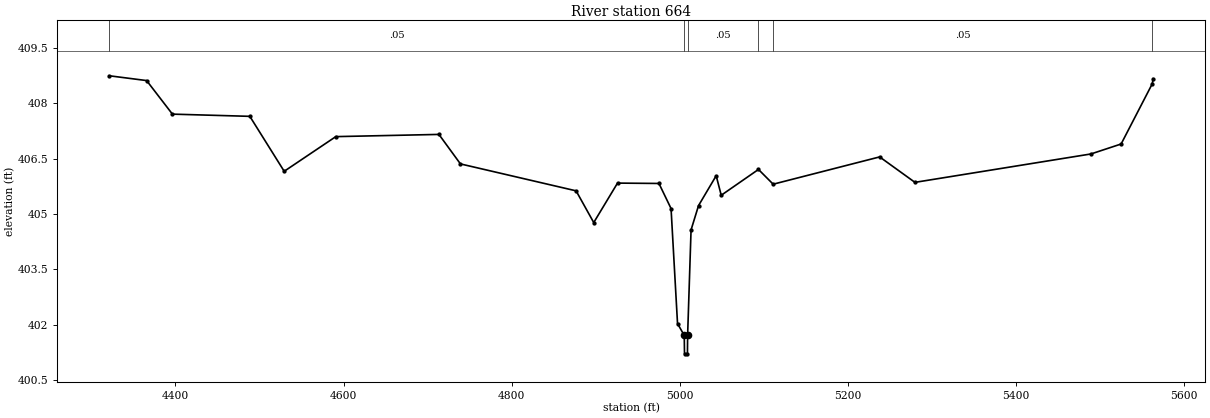
Type RM Length L Ch R = 1,664,0,0,0
BEGIN DESCRIPTION:
Jones T2 1.0
END DESCRIPTION:
XS GIS Cut Line= 3
      2689039.40      6891974.14      2688375.97      6891830.98
      2688058.98      6892296.75
#Sta/Elev= 30
  4321.3  408.75  4365.7  408.62  4396.4  407.71  4488.5  407.65  4529.4  406.16
  4590.8  407.10  4713.5  407.16  4739.1  406.36  4876.7  405.63  4897.7  404.77
  4926.0  405.84  4975.3  405.83  4989.7  405.15  4997.4  402.03  5005.4  401.71
  5005.7  401.21  5009.2  401.21  5009.4  401.71  5013.5  404.57  5022.4  405.23
  5043.4  406.04  5049.4  405.51  5093.7  406.21  5111.2  405.81  5237.9  406.55
  5279.9  405.86  5489.3  406.63  5525.2  406.90  5562.2  408.53  5563.4  408.67
#Mann=6,-1,0
  4321.3    0.05       0  5005.4    0.03       0  5009.4    0.05       0
  5093.7    0.12       0  5111.2    0.05       0  5562.2    0.12       0
Bank Sta=5005.4,5009.4
Exp/Cntr=0.3,0.1

Chan Stop Cuts=-1