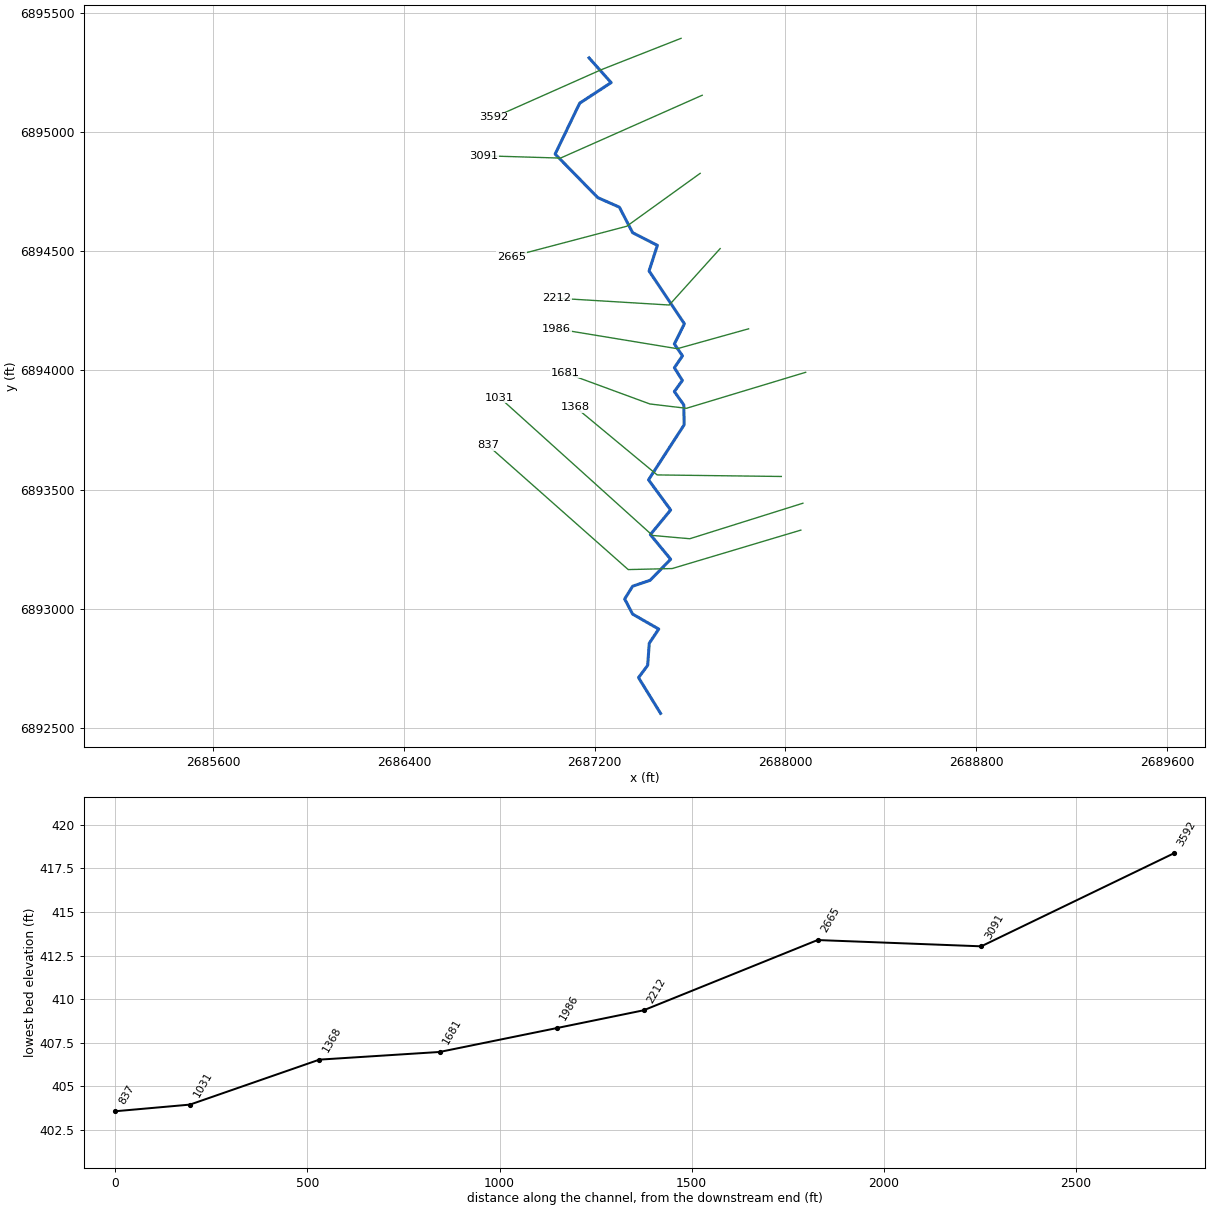
--- Jones T3.prj (project) ---

Proj Title=Jones T3 Base Level Engineering
Current Plan=p01
Default Exp/Contr=0.3,0.1
English Units
Geom File=g01
Flow File=f01
Plan File=p01
BEGIN DESCRIPTION:
Jones T3
END DESCRIPTION:

--- Jones T3.p01 (plan) ---

Plan Title=Multiple Run
Short Identifier=Multiple
Geom File=g01
Flow File=f01
Subcritical Flow
K Sum by GR= 0
Std Step Tol= 0.01
Critical Tol= 0.01
Num of Std Step Trials= 20
Max Error Tol= 0.3
Flow Tol Ratio= 0.001
Split Flow NTrial= 30
Split Flow Tol= 0.02
Split Flow Ratio= 0.02
Log Output Level= 0
Friction Slope Method= 1
Unsteady Friction Slope Method= 2
Unsteady Bridges Friction Slope Method= 1
Parabolic Critical Depth
Global Vel Dist=  1 , 1 , 1
Global Log Level= 0
CheckData=True
Encroach Param= -1, 0, 0, 0
BEGIN DESCRIPTION:
Multiple Run
END DESCRIPTION:

--- Jones T3.f01 (steady flow) ---

Flow Title=Multiple
Number of Profiles=7
Profile Names=10-year,25-year,50-year,1pct_min,100-year,1pct_plu,500-year
River Rch & RM= Jones T3,Reach-1,3592
     599     804     971     581    1160    2314    1655
Boundary for River Rch & Prof#=Jones T3,Reach-1,1
Up Type=0
Dn Type=3
Dn Slope=0.005
Boundary for River Rch & Prof#=Jones T3,Reach-1,2
Up Type=0
Dn Type=3
Dn Slope=0.005
Boundary for River Rch & Prof#=Jones T3,Reach-1,3
Up Type=0
Dn Type=3
Dn Slope=0.005
Boundary for River Rch & Prof#=Jones T3,Reach-1,4
Up Type=0
Dn Type=3
Dn Slope=0.005
Boundary for River Rch & Prof#=Jones T3,Reach-1,5
Up Type=0
Dn Type=3
Dn Slope=0.005
Boundary for River Rch & Prof#=Jones T3,Reach-1,6
Up Type=0
Dn Type=3
Dn Slope=0.005
Boundary for River Rch & Prof#=Jones T3,Reach-1,7
Up Type=0
Dn Type=3
Dn Slope=0.005

--- Jones T3.g01 (geometry) ---

Geom Title=Existing Conditions

River Reach=Jones T3,Reach-1
Reach XY= 30
      2687176.00      6895311.00      2687268.60      6895207.41
      2687136.64      6895121.00      2687033.77      6894907.59
      2687212.80      6894724.64      2687303.14      6894684.83
      2687358.97      6894577.50      2687462.60      6894524.73
      2687427.84      6894417.13      2687575.99      6894195.64
      2687533.82      6894110.91      2687567.98      6894061.00
      2687534.00      6894011.00      2687567.46      6893957.67
      2687533.79      6893911.10      2687573.64      6893855.11
      2687574.91      6893771.55      2687425.53      6893540.84
      2687518.38      6893414.33      2687433.12      6893311.00
      2687518.40      6893207.65      2687432.06      6893119.17
      2687358.77      6893094.50      2687325.45      6893040.87
      2687358.79      6892977.50      2687468.31      6892914.67
      2687428.56      6892855.12      2687421.91      6892762.50
      2687383.51      6892710.99      2687476.00      6892561.00

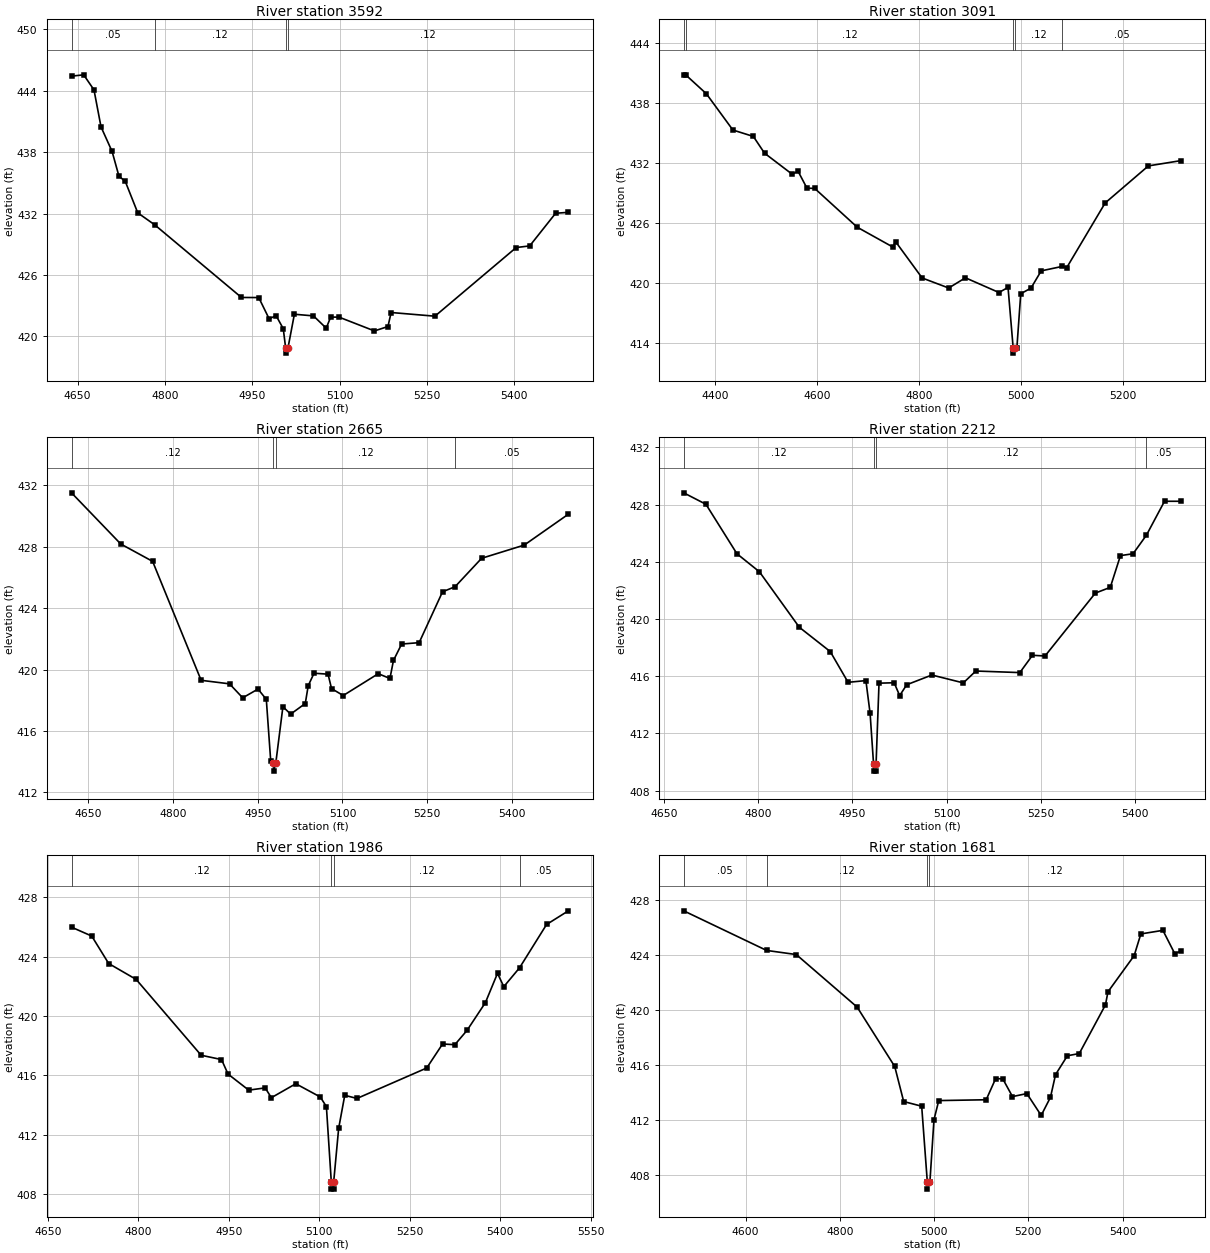
Type RM Length L Ch R = 1,3592,501,501,501
BEGIN DESCRIPTION:
Jones T3 6.0
END DESCRIPTION:
XS GIS Cut Line= 3
      2687561.88      6895393.10      2687226.00      6895261.00
      2686775.97      6895060.99
#Sta/Elev= 30
  4639.6  445.43  4660.5  445.56  4678.2  444.09  4690.3  440.47  4709.3  438.07
  4721.1  435.65  4731.9  435.15  4753.4  432.07  4782.5  430.90  4931.5  423.80
  4961.2  423.79  4979.0  421.72  4991.0  422.02  5003.3  420.75  5007.4  418.86
  5007.7  418.36  5011.4  418.86  5022.4  422.16  5055.2  422.00  5077.1  420.80
  5084.7  421.88  5099.0  421.88  5159.9  420.53  5183.1  420.96  5188.6  422.33
  5263.8  421.97  5403.4  428.68  5426.6  428.84  5471.1  432.03  5493.0  432.12
#Mann=4,-1,0
  4639.6    0.05       0  4782.5    0.12       0  5007.4    0.07       0
  5011.4    0.12       0
Bank Sta=5007.4,5011.4
Exp/Cntr=0.3,0.1

Type RM Length L Ch R = 1,3091,426,426,426
BEGIN DESCRIPTION:
Jones T3 5.0
END DESCRIPTION:
XS GIS Cut Line= 3
      2687650.79      6895154.36      2687056.27      6894890.67
      2686732.89      6894900.46
#Sta/Elev= 30
  4338.6  440.81  4342.4  440.81  4383.0  438.92  4435.0  435.30  4475.1  434.66
  4497.0  432.99  4551.4  430.88  4562.6  431.20  4580.1  429.50  4595.4  429.47
  4678.7  425.60  4748.5  423.62  4754.0  424.15  4806.0  420.53  4858.0  419.53
  4890.8  420.55  4956.5  419.08  4974.3  419.59  4984.4  413.53  4984.6  413.03
  4988.4  413.53  4991.6  413.53  4999.2  418.96  5019.3  419.52  5039.3  421.24
  5080.9  421.69  5089.3  421.56  5164.7  428.02  5249.4  431.72  5312.5  432.24
#Mann=5,-1,0
  4338.6    0.05       0  4342.4    0.12       0  4984.4    0.07       0
  4988.4    0.12       0  5080.9    0.05       0
Bank Sta=4984.4,4988.4
Exp/Cntr=0.3,0.1

Type RM Length L Ch R = 1,2665,453,453,453
BEGIN DESCRIPTION:
Jones T3 4.0
END DESCRIPTION:
XS GIS Cut Line= 3
      2687642.11      6894826.66      2687334.05      6894604.69
      2686850.52      6894477.41
#Sta/Elev= 30
  4620.3  431.50  4707.5  428.17  4763.9  427.04  4849.8  419.30  4900.1  419.07
  4923.4  418.16  4950.5  418.73  4965.2  418.06  4973.0  414.05  4977.9  413.89
  4978.1  413.39  4981.9  413.89  4994.6  417.58  5008.3  417.10  5034.2  417.79
  5039.4  418.95  5049.7  419.76  5074.5  419.70  5080.7  418.76  5101.4  418.31
  5163.4  419.73  5184.1  419.42  5190.3  420.59  5204.8  421.66  5235.8  421.75
  5277.2  425.06  5299.4  425.39  5346.4  427.24  5421.9  428.10  5500.0  430.11
#Mann=4,-1,0
  4620.3    0.12       0  4977.9    0.07       0  4981.9    0.12       0
  5299.4    0.05       0
Bank Sta=4977.9,4981.9
Exp/Cntr=0.3,0.1

Type RM Length L Ch R = 1,2212,226,226,226
BEGIN DESCRIPTION:
Jones T3 3.0
END DESCRIPTION:
XS GIS Cut Line= 3
      2687725.97      6894510.96      2687512.45      6894274.23
      2687040.41      6894302.85
#Sta/Elev= 30
  4681.2  428.82  4716.6  428.02  4766.0  424.56  4801.8  423.30  4865.4  419.42
  4914.7  417.72  4943.1  415.57  4971.5  415.69  4978.2  413.39  4983.7  409.86
  4983.9  409.36  4987.4  409.36  4987.7  409.86  4992.4  415.51  5016.5  415.54
  5025.3  414.64  5036.5  415.40  5076.6  416.08  5126.7  415.53  5146.7  416.36
  5216.8  416.25  5236.9  417.46  5256.9  417.41  5337.1  421.81  5360.9  422.21
  5377.1  424.43  5397.2  424.56  5418.5  425.86  5447.3  428.23  5472.9  428.23
#Mann=4,-1,0
  4681.2    0.12       0  4983.7    0.07       0  4987.7    0.12       0
  5418.5    0.05       0
Bank Sta=4983.7,4987.7
Exp/Cntr=0.3,0.1

Type RM Length L Ch R = 1,1986,305,305,305
BEGIN DESCRIPTION:
Jones T3 2.0
END DESCRIPTION:
XS GIS Cut Line= 3
      2687845.38      6894174.43      2687546.20      6894090.97
      2687040.42      6894174.32
#Sta/Elev= 30
  4689.4  425.99  4722.9  425.39  4751.0  423.54  4796.5  422.47  4904.2  417.36
  4937.9  417.07  4948.8  416.09  4983.0  415.01  5010.3  415.16  5020.5  414.50
  5061.0  415.44  5101.5  414.55  5111.7  413.90  5119.8  408.84  5120.1  408.34
  5123.6  408.34  5123.8  408.84  5132.0  412.43  5142.1  414.66  5162.4  414.45
  5277.9  416.50  5304.2  418.12  5324.5  418.07  5344.8  419.04  5375.2  420.91
  5395.2  422.88  5405.6  421.98  5431.7  423.25  5476.5  426.17  5512.6  427.09
#Mann=4,-1,0
  4689.4    0.12       0  5119.8    0.07       0  5123.8    0.12       0
  5431.7    0.05       0
Bank Sta=5119.8,5123.8
Exp/Cntr=0.3,0.1

Type RM Length L Ch R = 1,1681,313,313,313
BEGIN DESCRIPTION:
Mapping XS cd8e0490
END DESCRIPTION:
XS GIS Cut Line= 4
      2688084.71      6893991.96      2687584.67      6893840.91
      2687431.03      6893859.14      2687076.88      6893989.34
#Sta/Elev= 30
  4468.8  427.21  4644.7  424.33  4707.7  424.03  4836.8  420.21  4916.6  415.89
  4935.6  413.34  4973.8  413.00  4985.8  407.47  4986.1  406.97  4989.8  407.47
  4991.2  407.47  4999.9  412.02  5010.0  413.41  5110.7  413.47  5130.8  415.01
  5145.9  414.99  5166.5  413.70  5197.0  413.92  5227.4  412.33  5247.1  413.65
  5257.9  415.30  5283.0  416.67  5308.2  416.83  5363.8  420.37  5369.1  421.32
  5424.7  423.95  5438.9  425.53  5485.7  425.79  5510.8  424.10  5523.2  424.27
#Mann=4,-1,0
  4468.8    0.05       0  4644.7    0.12       0  4985.8    0.07       0
  4989.8    0.12       0
Bank Sta=4985.8,4989.8
Exp/Cntr=0.3,0.1

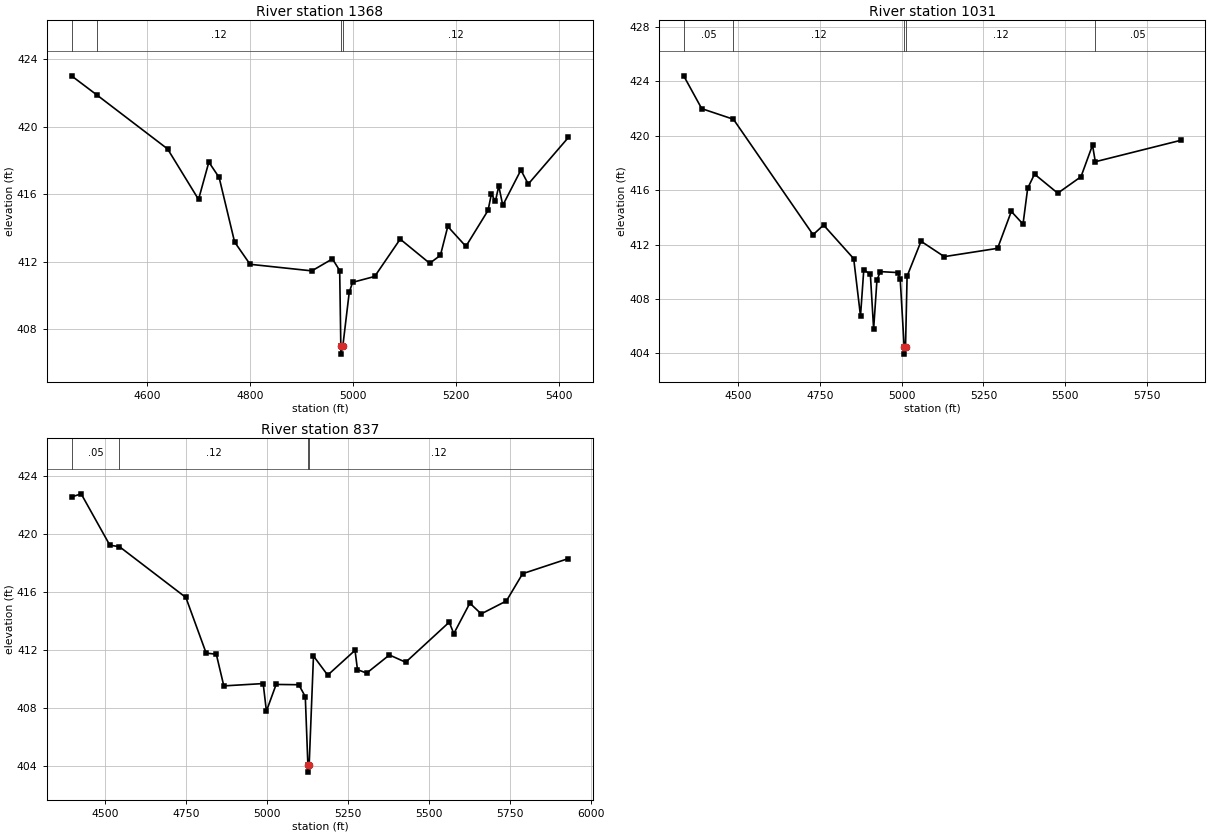
Type RM Length L Ch R = 1,1368,337,337,337
BEGIN DESCRIPTION:
Mapping XS 3b2680c5
END DESCRIPTION:
XS GIS Cut Line= 3
      2687982.63      6893554.89      2687461.84      6893561.40
      2687119.99      6893844.83
#Sta/Elev= 30
  4453.7  423.01  4502.4  421.89  4640.3  418.68  4700.4  415.69  4720.4  417.90
  4740.4  416.99  4770.4  413.17  4800.4  411.85  4920.4  411.46  4960.4  412.17
  4974.5  411.48  4976.7  407.03  4976.9  406.53  4980.7  407.03  4993.0  410.18
  4999.5  410.78  5042.5  411.13  5092.0  413.34  5149.3  411.91  5170.1  412.38
  5184.4  414.09  5219.6  412.91  5262.6  415.04  5269.1  416.01  5276.9  415.58
  5283.4  416.49  5291.2  415.34  5326.4  417.43  5340.7  416.60  5418.6  419.36
#Mann=4,-1,0
  4453.7    0.05       0  4502.4    0.12       0  4976.7    0.07       0
  4980.7    0.12       0
Bank Sta=4976.7,4980.7
Exp/Cntr=0.3,0.1

Type RM Length L Ch R = 1,1031,194,194,194
BEGIN DESCRIPTION:
Mapping XS c37393d3
END DESCRIPTION:
XS GIS Cut Line= 4
      2688073.09      6893442.62      2687598.68      6893293.68
      2687442.31      6893307.49      2686801.00      6893886.00
#Sta/Elev= 30
  4334.5  424.39  4389.5  421.98  4486.4  421.20  4729.7  412.72  4761.8  413.43
  4853.8  410.96  4874.6  406.75  4884.6  410.14  4904.7  409.82  4914.7  405.79
  4924.8  409.37  4934.8  410.01  4988.7  409.94  4995.9  409.45  5008.1  404.45
  5008.4  403.95  5012.1  404.45  5016.9  409.67  5059.5  412.24  5130.5  411.11
  5293.4  411.72  5335.3  414.43  5371.1  413.50  5385.3  416.13  5406.2  417.17
  5477.2  415.77  5548.2  416.98  5583.4  419.30  5591.9  418.08  5852.4  419.65
#Mann=5,-1,0
  4334.5    0.05       0  4486.4    0.12       0  5008.1    0.07       0
  5012.1    0.12       0  5591.9    0.05       0
Bank Sta=5008.1,5012.1
Exp/Cntr=0.3,0.1

Type RM Length L Ch R = 1,837,0,0,0
BEGIN DESCRIPTION:
Mapping XS ce7e6fa6
END DESCRIPTION:
XS GIS Cut Line= 4
      2688064.54      6893329.85      2687524.78      6893168.60
      2687340.31      6893164.26      2686751.02      6893685.98
#Sta/Elev= 30
  4395.4  422.52  4425.2  422.74  4513.8  419.20  4543.5  419.10  4748.7  415.60
  4811.3  411.77  4842.7  411.69  4865.9  409.51  4987.5  409.67  4997.5  407.77
  5027.5  409.61  5097.5  409.59  5117.6  408.77  5125.6  404.07  5125.8  403.57
  5129.6  404.07  5142.9  411.57  5186.8  410.25  5271.2  411.96  5278.8  410.63
  5307.2  410.39  5377.4  411.64  5427.7  411.14  5562.3  413.90  5576.4  413.11
  5625.9  415.21  5661.0  414.47  5738.8  415.36  5789.0  417.24  5930.3  418.28
#Mann=4,-1,0
  4395.4    0.05       0  4543.5    0.12       0  5125.6    0.07       0
  5129.6    0.12       0
Bank Sta=5125.6,5129.6
Exp/Cntr=0.3,0.1

Chan Stop Cuts=-1