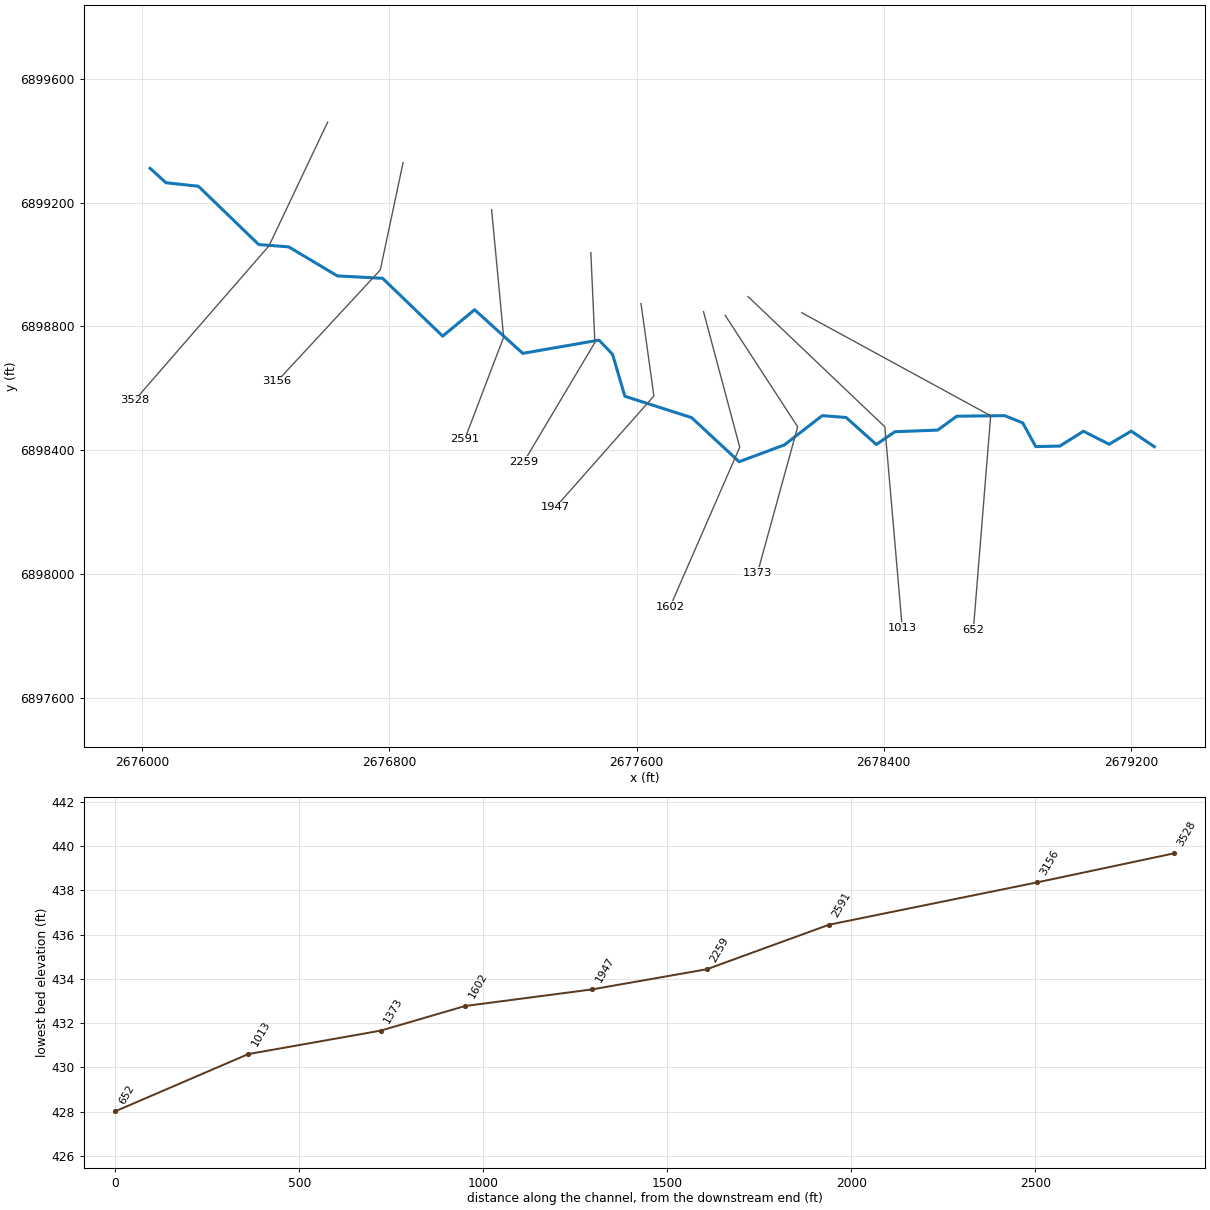
--- Jones T4.prj (project) ---

Proj Title=Jones T4 Base Level Engineering
Current Plan=p01
Default Exp/Contr=0.3,0.1
English Units
Geom File=g01
Flow File=f01
Plan File=p01
BEGIN DESCRIPTION:
Jones T4
END DESCRIPTION:

--- Jones T4.p01 (plan) ---

Plan Title=Multiple Run
Short Identifier=Multiple
Geom File=g01
Flow File=f01
Subcritical Flow
K Sum by GR= 0
Std Step Tol= 0.01
Critical Tol= 0.01
Num of Std Step Trials= 20
Max Error Tol= 0.3
Flow Tol Ratio= 0.001
Split Flow NTrial= 30
Split Flow Tol= 0.02
Split Flow Ratio= 0.02
Log Output Level= 0
Friction Slope Method= 1
Unsteady Friction Slope Method= 2
Unsteady Bridges Friction Slope Method= 1
Parabolic Critical Depth
Global Vel Dist=  1 , 1 , 1
Global Log Level= 0
CheckData=True
Encroach Param= -1, 0, 0, 0
BEGIN DESCRIPTION:
Multiple Run
END DESCRIPTION:

--- Jones T4.f01 (steady flow) ---

Flow Title=Multiple
Number of Profiles=7
Profile Names=10-year,25-year,50-year,1pct_min,100-year,1pct_plu,500-year
River Rch & RM= Jones T4,Reach-1,3528
     375     487     574     336     671    1339     915
River Rch & RM= Jones T4,Reach-1,2591
     659     888    1074     644    1284    2562    1837
Boundary for River Rch & Prof#=Jones T4,Reach-1,1
Up Type=0
Dn Type=3
Dn Slope=0.005
Boundary for River Rch & Prof#=Jones T4,Reach-1,2
Up Type=0
Dn Type=3
Dn Slope=0.005
Boundary for River Rch & Prof#=Jones T4,Reach-1,3
Up Type=0
Dn Type=3
Dn Slope=0.005
Boundary for River Rch & Prof#=Jones T4,Reach-1,4
Up Type=0
Dn Type=3
Dn Slope=0.005
Boundary for River Rch & Prof#=Jones T4,Reach-1,5
Up Type=0
Dn Type=3
Dn Slope=0.005
Boundary for River Rch & Prof#=Jones T4,Reach-1,6
Up Type=0
Dn Type=3
Dn Slope=0.005
Boundary for River Rch & Prof#=Jones T4,Reach-1,7
Up Type=0
Dn Type=3
Dn Slope=0.005

--- Jones T4.g01 (geometry) ---

Geom Title=Existing Conditions

River Reach=Jones T4,Reach-1
Reach XY= 30
      2676026.00      6899311.00      2676077.41      6899264.39
      2676182.18      6899253.16      2676377.50      6899064.61
      2676474.41      6899057.17      2676631.93      6898963.25
      2676778.45      6898955.53      2676972.67      6898768.61
      2677076.00      6898853.90      2677231.89      6898712.96
      2677478.71      6898755.72      2677522.48      6898709.75
      2677562.28      6898574.23      2677778.30      6898505.17
      2677932.04      6898362.61      2678078.29      6898416.84
      2678200.97      6898511.50      2678278.43      6898505.57
      2678375.90      6898418.33      2678436.44      6898459.60
      2678574.43      6898464.79      2678636.51      6898509.78
      2678791.26      6898511.51      2678849.85      6898488.16
      2678891.90      6898411.54      2678969.95      6898413.15
      2679046.21      6898461.21      2679129.31      6898419.11
      2679200.90      6898461.50      2679276.00      6898411.00

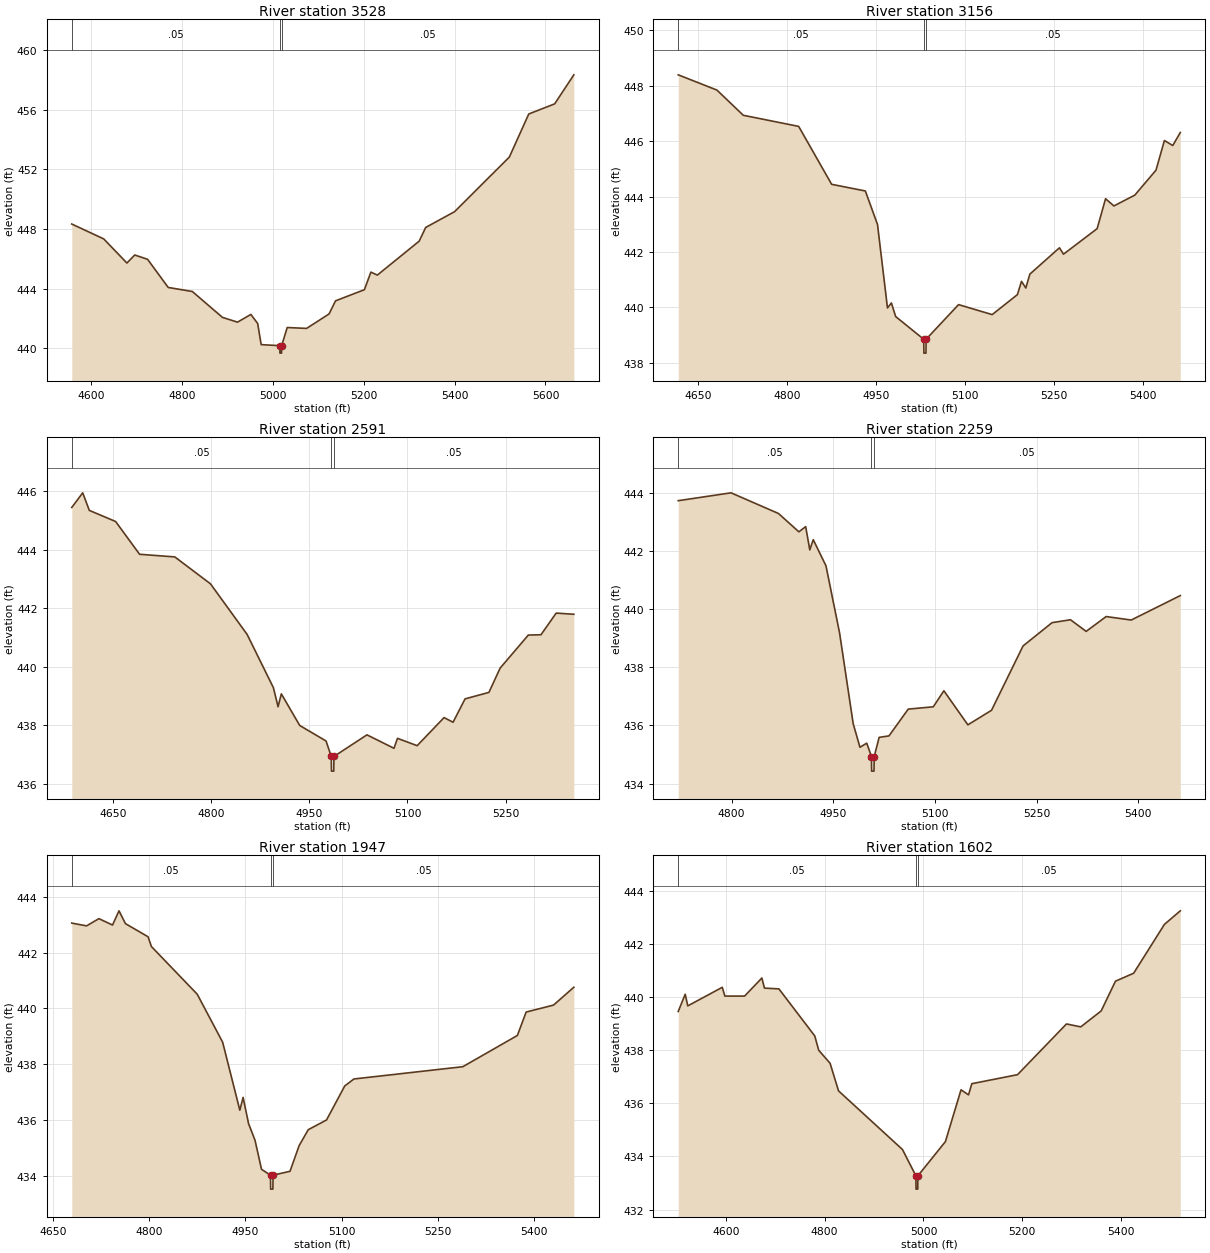
Type RM Length L Ch R = 1,3528,372,372,372
BEGIN DESCRIPTION:
Jones T4 2.0
END DESCRIPTION:
XS GIS Cut Line= 3
      2676600.70      6899460.64      2676410.91      6899060.79
      2675976.02      6898561.02
#Sta/Elev= 30
  4557.4  448.33  4627.8  447.33  4678.8  445.71  4696.0  446.25  4724.3  445.96
  4769.7  444.07  4822.7  443.80  4889.1  442.06  4922.3  441.74  4951.6  442.26
  4966.6  441.65  4974.3  440.23  5015.4  440.16  5015.6  439.66  5019.1  439.66
  5019.4  440.16  5031.6  441.38  5074.3  441.32  5123.7  442.29  5137.9  443.17
  5201.5  443.92  5215.8  445.10  5230.0  444.90  5322.1  447.18  5336.4  448.10
  5400.0  449.16  5520.6  452.83  5563.3  455.72  5620.3  456.40  5662.5  458.35
#Mann=3,-1,0
  4557.4    0.05       0  5015.4    0.04       0  5019.4    0.05       0
Bank Sta=5015.4,5019.4
Exp/Cntr=0.3,0.1

Type RM Length L Ch R = 1,3156,565,565,565
BEGIN DESCRIPTION:
Mapping XS 435dd860
END DESCRIPTION:
XS GIS Cut Line= 3
      2676844.62      6899329.53      2676770.84      6898982.35
      2676436.66      6898622.13
#Sta/Elev= 30
  4616.3  448.39  4681.5  447.84  4726.0  446.93  4819.3  446.53  4874.9  444.44
  4931.7  444.20  4952.2  442.99  4969.0  439.98  4975.6  440.16  4982.8  439.67
  5030.1  438.85  5030.4  438.35  5033.9  438.35  5034.1  438.85  5088.8  440.10
  5145.5  439.74  5188.0  440.46  5194.9  440.94  5202.2  440.70  5209.0  441.20
  5258.9  442.15  5265.7  441.92  5322.4  442.84  5336.6  443.92  5350.7  443.66
  5385.9  444.05  5421.6  444.95  5435.8  446.02  5449.9  445.84  5462.6  446.31
#Mann=3,-1,0
  4616.3    0.05       0  5030.1    0.04       0  5034.1    0.05       0
Bank Sta=5030.1,5034.1
Exp/Cntr=0.3,0.1

Type RM Length L Ch R = 1,2591,332,332,332
BEGIN DESCRIPTION:
Mapping XS 8c31ebf3
END DESCRIPTION:
XS GIS Cut Line= 3
      2677131.08      6899177.66      2677170.15      6898765.33
      2677044.40      6898435.78
#Sta/Elev= 30
  4587.2  445.45  4603.9  445.95  4614.0  445.35  4654.2  444.97  4690.8  443.85
  4744.6  443.76  4799.1  442.84  4855.1  441.11  4895.2  439.29  4902.3  438.64
  4907.3  439.08  4935.4  438.00  4975.6  437.47  4983.6  436.94  4983.9  436.44
  4987.4  436.44  4987.6  436.94  5038.1  437.68  5079.4  437.22  5084.7  437.56
  5114.8  437.31  5155.9  438.27  5169.6  438.11  5188.0  438.91  5224.4  439.13
  5241.5  439.96  5284.6  441.09  5303.9  441.10  5327.1  441.84  5354.1  441.80
#Mann=3,-1,0
  4587.2    0.05       0  4983.6    0.04       0  4987.6    0.05       0
Bank Sta=4983.6,4987.6
Exp/Cntr=0.3,0.1

Type RM Length L Ch R = 1,2259,312,312,312
BEGIN DESCRIPTION:
Mapping XS 22b03083
END DESCRIPTION:
XS GIS Cut Line= 3
      2677452.26      6899038.79      2677465.29      6898747.97
      2677235.25      6898361.69
#Sta/Elev= 30
  4721.2  443.72  4799.1  443.99  4869.1  443.28  4899.2  442.65  4909.2  442.83
  4915.3  442.03  4920.4  442.38  4939.2  441.48  4959.2  439.18  4979.3  436.06
  4989.3  435.25  4999.3  435.39  5006.3  434.93  5006.5  434.43  5010.0  434.43
  5010.3  434.93  5017.6  435.59  5032.1  435.64  5060.5  436.56  5097.5  436.64
  5113.1  437.19  5148.5  436.02  5183.4  436.52  5229.9  438.73  5272.7  439.53
  5299.9  439.63  5323.0  439.23  5352.5  439.74  5389.5  439.62  5461.9  440.46
#Mann=3,-1,0
  4721.2    0.05       0  5006.3    0.03       0  5010.3    0.05       0
Bank Sta=5006.3,5010.3
Exp/Cntr=0.3,0.1

Type RM Length L Ch R = 1,1947,345,345,345
BEGIN DESCRIPTION:
Mapping XS 146051af
END DESCRIPTION:
XS GIS Cut Line= 3
      2677614.59      6898873.87      2677656.26      6898575.23
      2677337.65      6898215.06
#Sta/Elev= 30
  4679.6  443.06  4702.7  442.96  4721.9  443.22  4743.1  442.99  4753.2  443.50
  4763.3  443.04  4798.5  442.57  4803.7  442.22  4875.1  440.51  4914.7  438.79
  4941.5  436.35  4946.6  436.81  4955.1  435.87  4965.2  435.27  4975.3  434.23
  4989.3  434.02  4989.5  433.52  4993.0  433.52  4993.3  434.02  5019.7  434.16
  5033.9  435.08  5048.1  435.65  5076.6  436.00  5105.0  437.22  5119.3  437.47
  5289.0  437.91  5374.0  439.03  5387.7  439.87  5430.4  440.12  5462.0  440.76
#Mann=3,-1,0
  4679.6    0.05       0  4989.3    0.03       0  4993.3    0.05       0
Bank Sta=4989.3,4993.3
Exp/Cntr=0.3,0.1

Type RM Length L Ch R = 1,1602,229,229,229
BEGIN DESCRIPTION:
Mapping XS 24bf466b
END DESCRIPTION:
XS GIS Cut Line= 3
      2677816.85      6898847.78      2677934.04      6898409.43
      2677709.02      6897894.49
#Sta/Elev= 30
  4503.9  439.46  4518.0  440.11  4523.2  439.67  4593.0  440.37  4598.2  440.04
  4638.2  440.04  4673.1  440.72  4678.3  440.34  4707.6  440.31  4780.1  438.54
  4788.1  438.00  4811.1  437.51  4828.2  436.47  4957.6  434.26  4984.7  433.27
  4985.0  432.77  4988.5  432.77  4988.7  433.27  5044.4  434.56  5076.0  436.51
  5091.2  436.32  5097.8  436.74  5190.3  437.08  5289.3  438.99  5318.2  438.88
  5359.5  439.48  5388.4  440.60  5425.2  440.90  5487.5  442.74  5519.6  443.25
#Mann=3,-1,0
  4503.9    0.05       0  4984.7    0.04       0  4988.7    0.05       0
Bank Sta=4984.7,4988.7
Exp/Cntr=0.3,0.1

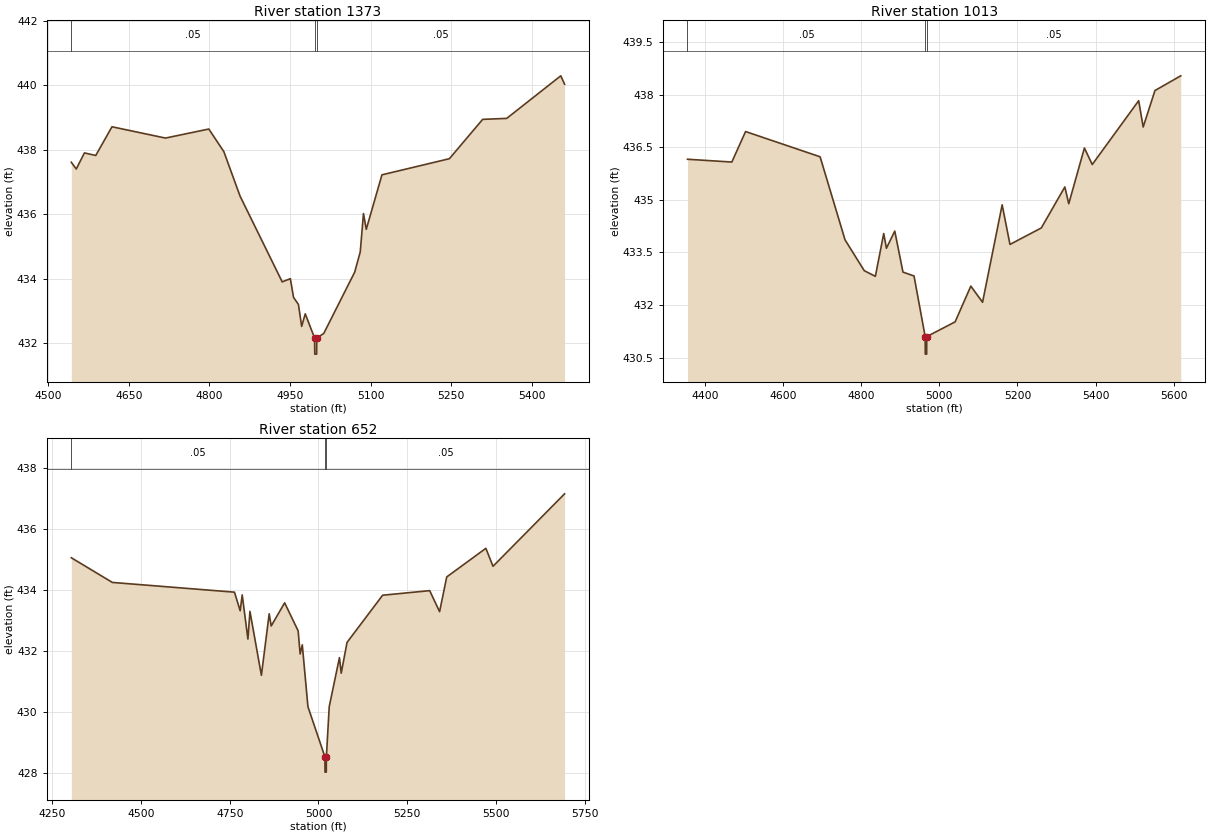
Type RM Length L Ch R = 1,1373,360,360,360
BEGIN DESCRIPTION:
Mapping XS 6e2a2f4e
END DESCRIPTION:
XS GIS Cut Line= 3
      2677887.18      6898835.61      2678121.54      6898475.40
      2677991.83      6898004.16
#Sta/Elev= 30
  4542.9  437.61  4552.1  437.40  4567.3  437.90  4588.4  437.82  4618.6  438.71
  4718.2  438.36  4798.9  438.64  4826.9  437.94  4857.1  436.56  4935.6  433.90
  4950.7  434.00  4956.7  433.42  4965.8  433.20  4971.8  432.52  4978.5  432.91
  4995.9  432.16  4996.2  431.66  4999.7  431.66  4999.9  432.16  5012.9  432.30
  5070.5  434.20  5080.9  434.83  5086.9  436.02  5092.1  435.53  5121.3  437.22
  5246.9  437.72  5308.9  438.94  5353.6  438.97  5454.3  440.29  5461.4  440.03
#Mann=3,-1,0
  4542.9    0.05       0  4995.9    0.04       0  4999.9    0.05       0
Bank Sta=4995.9,4999.9
Exp/Cntr=0.3,0.1

Type RM Length L Ch R = 1,1013,361,361,361
BEGIN DESCRIPTION:
Mapping XS dbefd000
END DESCRIPTION:
XS GIS Cut Line= 3
      2677960.95      6898896.40      2678403.65      6898475.40
      2678460.01      6897825.16
#Sta/Elev= 30
  4354.7  436.16  4468.3  436.08  4503.5  436.95  4694.4  436.23  4758.3  433.86
  4807.6  432.98  4836.0  432.82  4857.4  434.04  4864.3  433.62  4885.7  434.11
  4906.7  432.94  4935.0  432.83  4963.6  431.10  4963.9  430.60  4967.4  430.60
  4967.6  431.10  5040.3  431.52  5080.5  432.54  5110.6  432.08  5160.8  434.86
  5180.8  433.73  5261.1  434.20  5321.4  435.37  5331.4  434.89  5371.5  436.48
  5391.6  436.01  5510.5  437.83  5522.1  437.08  5552.2  438.12  5618.3  438.54
#Mann=3,-1,0
  4354.7    0.05       0  4963.6    0.03       0  4967.6    0.05       0
Bank Sta=4963.6,4967.6
Exp/Cntr=0.3,0.1

Type RM Length L Ch R = 1,652,0,0,0
BEGIN DESCRIPTION:
Jones T4 1.0
END DESCRIPTION:
XS GIS Cut Line= 3
      2678134.52      6898844.35      2678746.07      6898511.21
      2678690.11      6897819.97
#Sta/Elev= 30
  4303.6  435.06  4419.2  434.25  4763.3  433.93  4779.4  433.32  4785.1  433.84
  4801.2  432.39  4806.9  433.30  4839.2  431.20  4861.1  433.22  4866.8  432.82
  4904.7  433.58  4942.7  432.66  4948.4  431.90  4954.4  432.20  4970.3  430.17
  5018.2  428.52  5018.5  428.02  5022.0  428.02  5022.3  428.52  5030.3  430.17
  5059.1  431.78  5064.1  431.27  5080.5  432.28  5180.8  433.83  5313.4  433.98
  5341.3  433.29  5361.4  434.43  5471.7  435.37  5491.8  434.78  5693.5  437.16
#Mann=3,-1,0
  4303.6    0.05       0  5018.2    0.03       0  5022.3    0.05       0
Bank Sta=5018.2,5022.3
Exp/Cntr=0.3,0.1

Chan Stop Cuts=-1