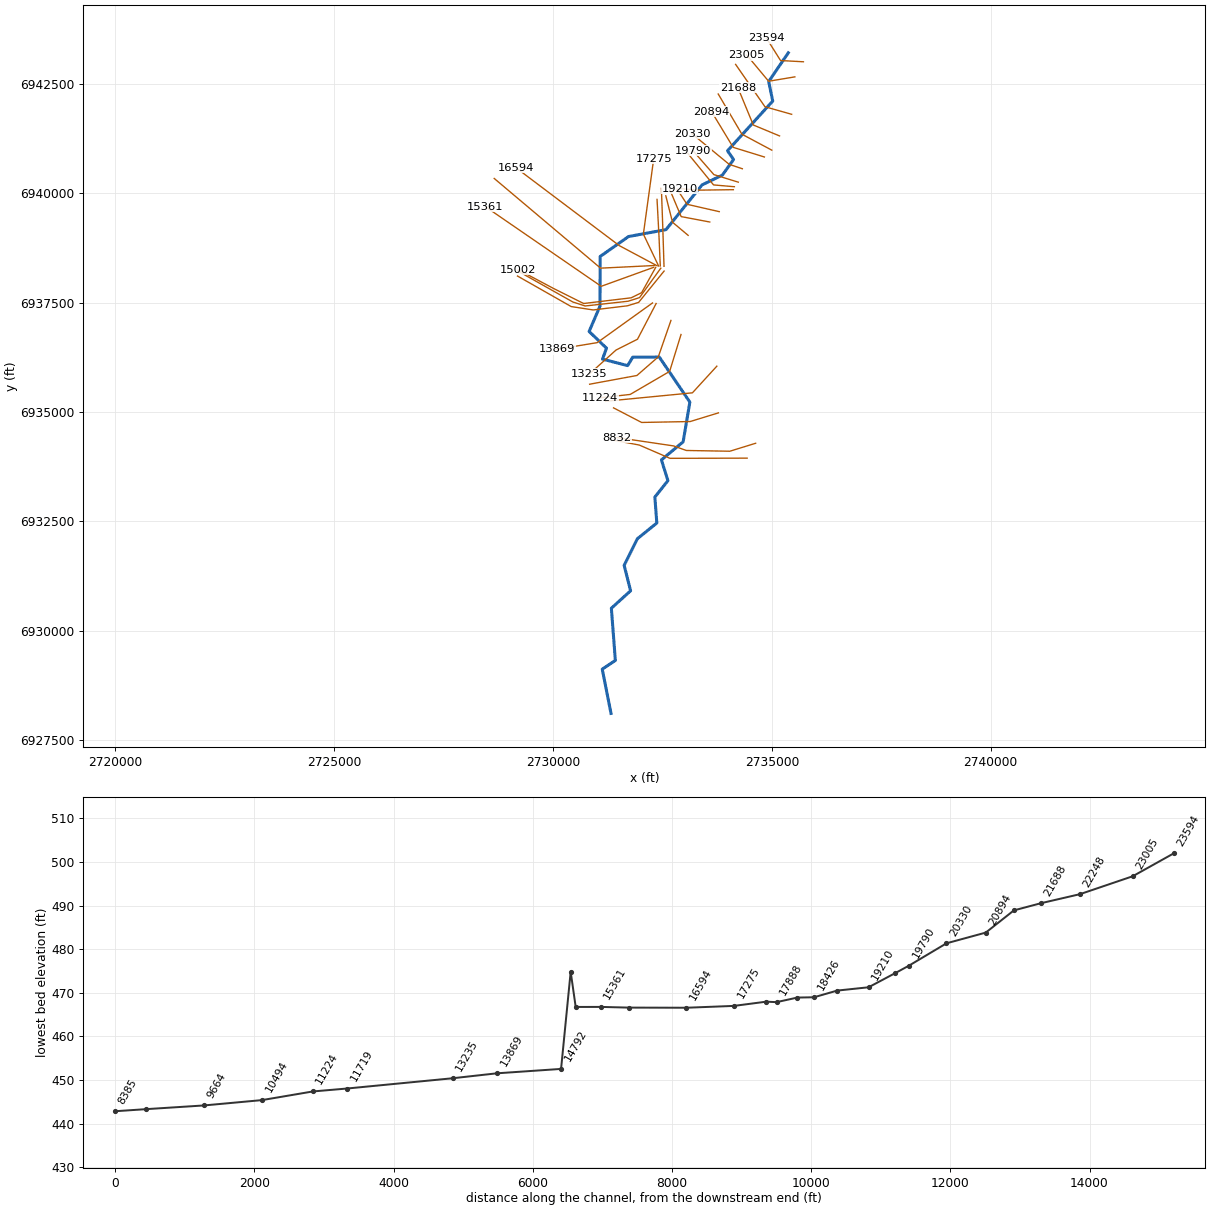
--- Little Allen Creek.prj (project) ---

Proj Title=Little Allen Creek Base Level Engineering
Current Plan=p01
Default Exp/Contr=0.3,0.1
English Units
Geom File=g01
Flow File=f01
Plan File=p01
Y Axis Title=Elevation
X Axis Title(PF)=Main Channel Distance
X Axis Title(XS)=Station
BEGIN DESCRIPTION:
Little Allen Creek
END DESCRIPTION:
DSS Export Rating Curves= 0
DSS Export Rating Curve Sorted= 0
DSS Export Volume Flow Curves= 0
DXF OffsetX= 0
DXF OffsetY= 0
DXF ScaleX= 1
DXF ScaleY= 10

--- Little Allen Creek.p01 (plan) ---

Plan Title=Multiple Run
Short Identifier=Multiple
Geom File=g01
Flow File=f01
Subcritical Flow
K Sum by GR= 0
Std Step Tol= 0.01
Critical Tol= 0.01
Num of Std Step Trials= 20
Max Error Tol= 0.3
Flow Tol Ratio= 0.001
Split Flow NTrial= 30
Split Flow Tol= 0.02
Split Flow Ratio= 0.02
Log Output Level= 0
Friction Slope Method= 1
Unsteady Friction Slope Method= 2
Unsteady Bridges Friction Slope Method= 1
Parabolic Critical Depth
Global Vel Dist=  1 , 1 , 1
Global Log Level= 0
CheckData=True
Encroach Param= -1, 0, 0, 0
BEGIN DESCRIPTION:
Multiple Run
END DESCRIPTION:

--- Little Allen Creek.f01 (steady flow) ---

Flow Title=Multiple
Program Version=4.10
Number of Profiles= 7
Profile Names=10-year,25-year,50-year,1pct_min,100-year,1pct_plu,500-year
River Rch & RM=Little Allen Cre,Reach-1         ,23594
     436     568     672     395     788    1572    1081
River Rch & RM=Little Allen Cre,Reach-1         ,16594
    1434    1970    2412    1459    2911    5808    4240
River Rch & RM=Little Allen Cre,Reach-1         ,14792
    1644    2276    2802    1704    3399    6783    5003
River Rch & RM=Little Allen Cre,Reach-1         ,8832
    1717    2379    2930    1782    3555    7094    5235
River Rch & RM=Little Allen Cre,Reach-1         ,6506
    1857    2578    3179    1935    3860    7702    5692
Boundary for River Rch & Prof#=Little Allen Cre,Reach-1         , 1
Up Type= 0
Dn Type= 3
Dn Slope=0.00232
Boundary for River Rch & Prof#=Little Allen Cre,Reach-1         , 2
Up Type= 0
Dn Type= 3
Dn Slope=0.00232
Boundary for River Rch & Prof#=Little Allen Cre,Reach-1         , 3
Up Type= 0
Dn Type= 3
Dn Slope=0.00232
Boundary for River Rch & Prof#=Little Allen Cre,Reach-1         , 4
Up Type= 0
Dn Type= 3
Dn Slope=0.00232
Boundary for River Rch & Prof#=Little Allen Cre,Reach-1         , 5
Up Type= 0
Dn Type= 3
Dn Slope=0.00232
Boundary for River Rch & Prof#=Little Allen Cre,Reach-1         , 6
Up Type= 0
Dn Type= 3
Dn Slope=0.00232
Boundary for River Rch & Prof#=Little Allen Cre,Reach-1         , 7
Up Type= 0
Dn Type= 3
Dn Slope=0.00232
DSS Import GetInterval= 0
DSS Import GetPeak= 0
DSS Import FillOption= 0

--- Little Allen Creek.g01 (geometry) ---

Geom Title=Existing Conditions
Program Version=4.10

River Reach=Little Allen Cre,Reach-1
Reach XY= 30
        2735376.        6943211.      2734927.97       6942555.1
      2735020.48      6942108.56      2733986.82      6940971.32
      2734125.45      6940771.64      2733870.39      6940415.77
       2733405.8      6940191.41      2732582.12      6939168.88
        2731726.        6939011.      2731078.05      6938555.16
       2731074.8       6937421.5      2730825.51      6936840.77
      2731223.08      6936459.26      2731131.28      6936208.29
      2731705.95      6936060.48       2731822.3      6936253.32
      2732428.99      6936255.53      2733126.97      6935226.56
      2732973.63      6934318.83      2732477.59      6933904.95
      2732626.11       6933431.1      2732327.57      6933055.35
      2732372.33      6932462.58      2731928.47      6932102.91
      2731626.02      6931495.59      2731773.18      6930912.84
      2731333.77      6930514.38      2731424.95      6929321.11
      2731125.28      6929121.52        2731326.        6928111.

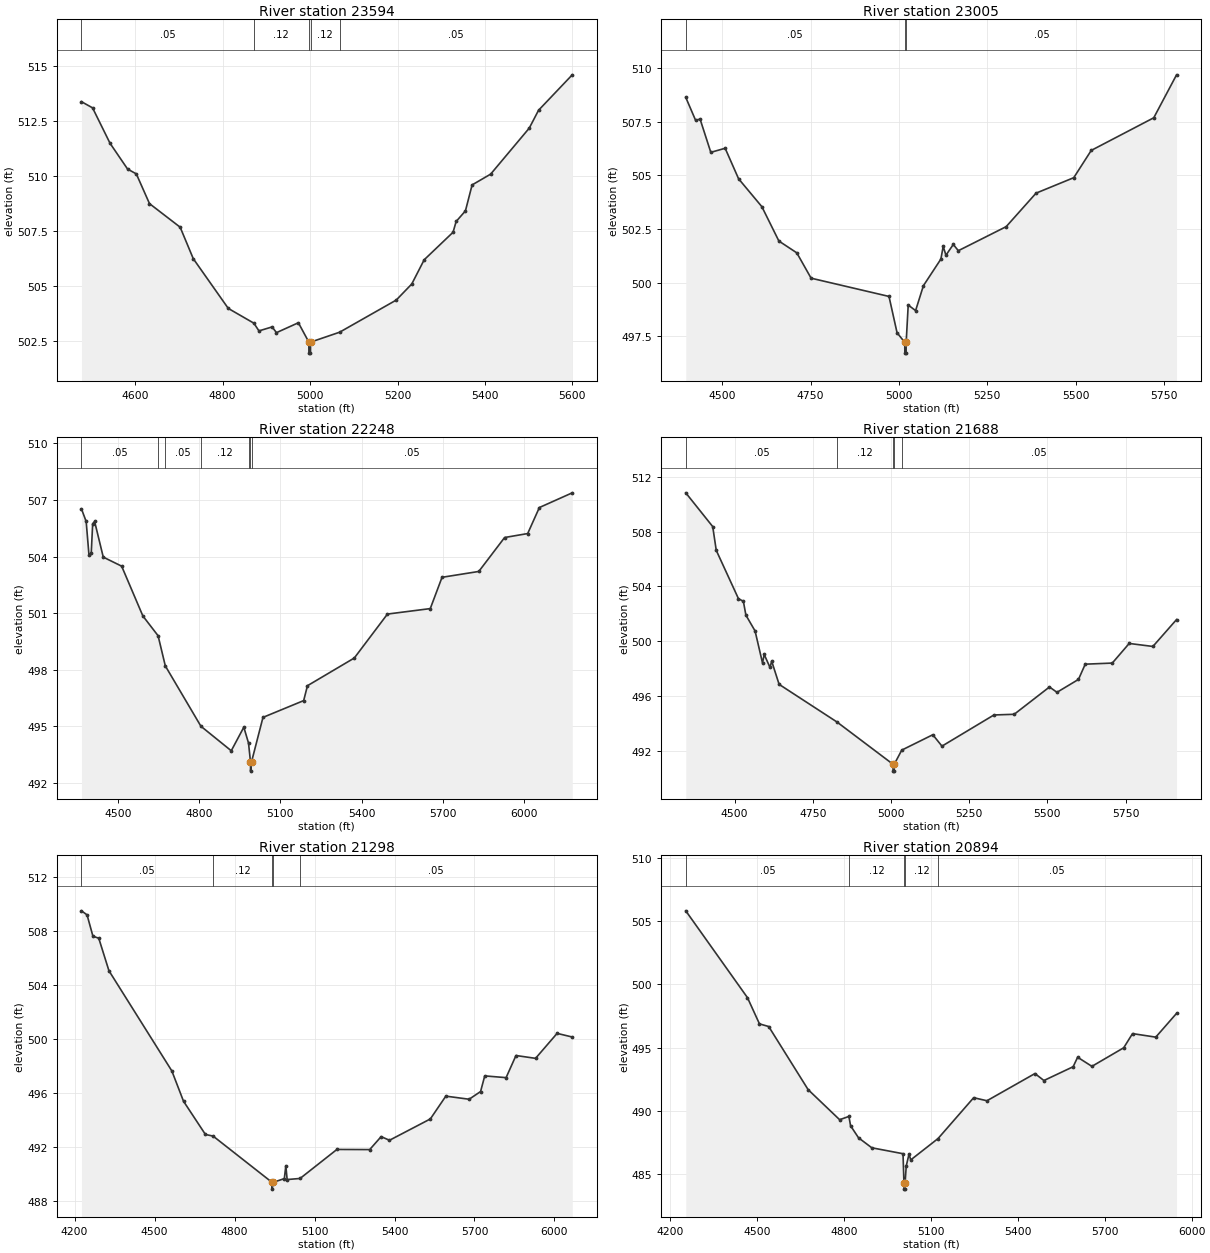
Type RM Length L Ch R = 1 ,23594   ,589,589,589
BEGIN DESCRIPTION:
Little Allen Creek 29.0
END DESCRIPTION:
XS GIS Cut Line= 3
      2735721.35      6943005.89      2735199.31      6943034.08
      2734880.31      6943541.78
#Sta/Elev= 30
  4477.2  513.38  4502.6   513.1  4542.6  511.49  4582.7  510.32  4602.7   510.1
  4632.8  508.75  4702.9  507.68  4732.9  506.25    4813  503.99  4871.5  503.32
  4883.1  502.97  4913.2  503.15  4923.2  502.89  4973.3  503.34  4997.2  502.46
  4997.4  501.96  5000.9  501.96  5001.2  502.46  5067.6  502.91  5197.1  504.37
  5232.6   505.1    5261   506.2    5327  507.45  5334.1  507.94  5355.3  508.42
  5370.6   509.6    5413  510.09  5501.3  512.18  5522.5  512.99  5599.6   514.6
#Mann= 5 ,-1 , 0
  4477.2     .05       0  4871.5     .12       0  4997.2     .07       0
  5001.2     .12       0  5067.6     .05       0
Bank Sta=4997.2,5001.2
XS Rating Curve= 0 ,0
Exp/Cntr=0.3,0.1

Type RM Length L Ch R = 1 ,23005   ,757,757,757
BEGIN DESCRIPTION:
Little Allen Creek 28.0
END DESCRIPTION:
XS GIS Cut Line= 3
      2735525.98        6942661.        2734926.        6942561.
      2734425.99      6943161.02
#Sta/Elev= 30
  4396.4  508.63  4424.3  507.56  4436.9  507.62  4467.3  506.07  4507.9  506.26
  4545.9  504.84  4611.8  503.54    4660  501.94  4710.7  501.39  4751.2  500.21
  4971.7  499.36  4994.5  497.67  5016.3  497.22  5016.6  496.72  5020.1  496.72
  5020.3  497.22  5026.1  498.96    5047   498.7  5069.1  499.86  5118.6   501.1
  5125.1  501.69  5132.9  501.28  5153.7  501.78    5168  501.49  5303.4  502.61
    5388  504.17  5494.7  504.89  5544.2  506.16  5721.2  507.68  5785.7  509.68
#Mann= 3 ,-1 , 0
  4396.4     .05       0  5016.3     .04       0  5020.3     .05       0
Bank Sta=5016.3,5020.3
XS Rating Curve= 0 ,0
Exp/Cntr=0.3,0.1

Type RM Length L Ch R = 1 ,22248   ,560,560,560
BEGIN DESCRIPTION:
Little Allen Creek 27.0
END DESCRIPTION:
XS GIS Cut Line= 3
      2735452.73      6941805.26      2734842.43      6941978.07
      2734172.27      6942946.26
#Sta/Elev= 30
  4365.7  506.53  4383.1  505.86  4393.5  504.07  4401.9   504.2  4407.1  505.74
  4414.3  505.86  4446.2  503.97  4514.1  503.49  4592.4  500.85  4648.6   499.8
  4675.3   498.2  4806.7     495  4918.7   493.7  4965.1  494.95  4982.4  494.11
  4989.7  493.12    4990  492.62  4993.7  493.12  5035.8  495.47    5186  496.36
    5200  497.15    5373  498.62  5495.3  500.95  5653.4  501.24  5696.8   502.9
  5832.5  503.21  5927.8  505.01    6013  505.22  6056.1   506.6  6177.5  507.38
#Mann= 7 ,-1 , 0
  4365.7     .05       0  4648.6     .12       0  4675.3     .05       0
  4806.7     .12       0  4982.4     .05       0  4989.7     .04       0
  4993.7     .05       0
Bank Sta=4989.7,4993.7
XS Rating Curve= 0 ,0
Exp/Cntr=0.3,0.1

Type RM Length L Ch R = 1 ,21688   ,390,390,390
BEGIN DESCRIPTION:
Little Allen Creek 26.0
END DESCRIPTION:
XS GIS Cut Line= 3
      2735176.04      6941310.98        2734576.        6941561.
      2734225.99      6942411.02
#Sta/Elev= 30
  4343.8  510.82    4430  508.36  4441.3  506.63  4512.3  503.11    4528  502.92
  4536.1  501.91  4565.4  500.76  4589.2  498.43  4594.6  499.05  4613.1   498.1
  4618.5  498.56  4642.3  496.87  4827.2  494.13  5006.5  491.05  5006.8  490.55
  5010.3  490.55  5010.5  491.05  5034.4  492.08  5133.7   493.2    5163  492.37
  5329.1  494.64    5394  494.69  5506.8  496.68  5530.7  496.29  5599.5  497.23
  5621.1  498.34  5707.6  498.42  5761.7  499.85  5837.4  499.63  5913.1  501.59
#Mann= 5 ,-1 , 0
  4343.8     .05       0  4827.2     .12       0  5006.5     .07       0
  5010.5     .12       0  5034.4     .05       0
Bank Sta=5006.5,5010.5
XS Rating Curve= 0 ,0
Exp/Cntr=0.3,0.1

Type RM Length L Ch R = 1 ,21298   ,404,404,404
BEGIN DESCRIPTION:
Little Allen Creek 25.0
END DESCRIPTION:
XS GIS Cut Line= 3
      2734998.85      6940985.72      2734316.19      6941350.49
      2733774.91      6942269.54
#Sta/Elev= 30
    4226  509.52    4247  509.22    4269  507.64  4290.9  507.49  4329.1  505.08
  4564.9  497.66  4608.8  495.41  4690.9  492.95  4719.7  492.83  4940.9   489.4
  4941.2   488.9  4944.9   489.4  4986.8  489.68  4992.5  490.64  4997.3  489.61
  5045.9  489.69    5184  491.84    5307  491.83  5349.9  492.79  5381.2  492.52
  5534.4   494.1  5592.5  495.79  5679.9  495.56  5722.8  496.13  5738.4  497.29
  5818.5  497.16  5855.6   498.8    5929  498.59  6009.8  500.44  6066.6  500.17
#Mann= 5 ,-1 , 0
    4226     .05       0  4719.7     .12       0  4940.9     .07       0
  4944.9     .12       0  5045.9     .05       0
Bank Sta=4940.9,4944.9
XS Rating Curve= 0 ,0
Exp/Cntr=0.3,0.1

Type RM Length L Ch R = 1 ,20894   ,564,564,564
BEGIN DESCRIPTION:
Little Allen Creek 24.0
END DESCRIPTION:
XS GIS Cut Line= 3
      2734829.58      6940829.47      2734116.47       6941049.9
      2733625.98      6941861.03
#Sta/Elev= 30
  4253.6  505.82  4466.7  498.95    4508  496.88  4539.9  496.67    4676  491.68
  4784.8   489.3  4816.8  489.56  4822.6  488.82    4850  487.87  4895.8  487.08
  5003.6  486.61  5006.8  484.31  5007.1  483.81  5010.6  483.81  5010.8  484.31
  5014.7  485.64  5024.4  486.59  5030.2  486.12  5124.5  487.81  5247.5  491.04
  5293.4   490.8    5459  492.95    5490   492.4  5590.9  493.49  5606.4  494.24
  5655.7  493.52  5765.5  494.99  5795.9  496.11  5876.1  495.83  5947.9  497.71
#Mann= 5 ,-1 , 0
  4253.6     .05       0  4816.8     .12       0  5006.8     .07       0
  5010.8     .12       0  5124.5     .05       0
Bank Sta=5006.8,5010.8
XS Rating Curve= 0 ,0
Exp/Cntr=0.3,0.1

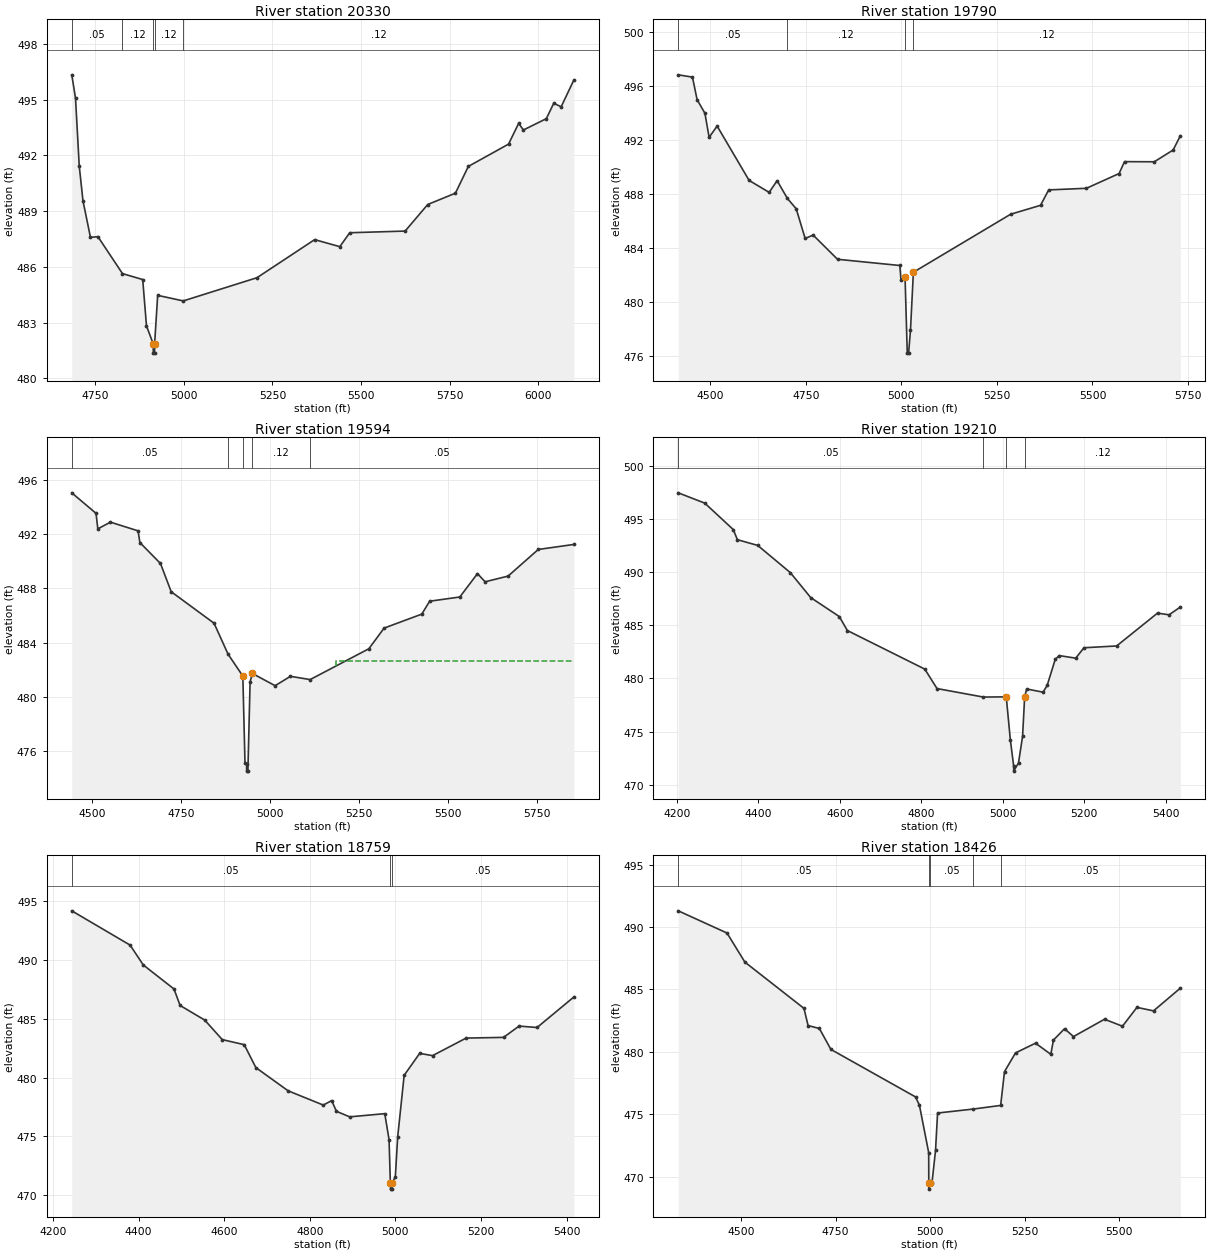
Type RM Length L Ch R = 1 ,20330   ,540,540,540
BEGIN DESCRIPTION:
Little Allen Creek 23.0
END DESCRIPTION:
XS GIS Cut Line= 3
      2734326.04      6940560.99        2734026.        6940661.
      2733176.01      6941360.99
#Sta/Elev= 30
  4683.5  496.34  4694.1  495.08  4704.6  491.43  4715.2  489.55  4736.3  487.59
  4757.3  487.63  4826.7  485.64  4883.8  485.32  4894.4  482.83  4913.4  481.86
  4913.7  481.36  4917.2  481.36  4917.4  481.86    4926  484.47  4998.2  484.17
  5206.4  485.42  5369.2  487.47  5440.2  487.09  5468.2  487.84  5624.6  487.93
  5688.4  489.36  5766.6  489.97    5803  491.41  5916.5  492.61  5945.2  493.73
  5958.4  493.37  6023.2  493.98  6044.2  494.81  6065.1  494.62  6100.9  496.06
#Mann= 5 ,-1 , 0
  4683.5     .05       0  4826.7     .12       0  4913.4     .07       0
  4917.4     .12       0  4998.2     .12       0
Bank Sta=4913.4,4917.4
XS Rating Curve= 0 ,0
Exp/Cntr=0.3,0.1

Type RM Length L Ch R = 1 ,19790   ,196,196,196
BEGIN DESCRIPTION:
Little Allen Creek 22.0
END DESCRIPTION:
XS GIS Cut Line= 3
      2734233.22      6940253.95      2733675.35      6940426.69
      2733195.67       6940976.7
#Sta/Elev= 30
    4416  496.81  4453.2  496.64  4465.4  494.97  4485.8  493.97  4496.8  492.19
  4517.8  493.02  4601.5     489  4653.9  488.12  4674.8  488.98  4701.6  487.67
  4724.6  486.91  4748.1  484.71    4769  484.96  4832.8  483.17  4995.9  482.71
  4998.8  481.65  5009.5  481.87  5015.3  476.23  5018.8  476.23  5023.7  477.91
  5031.3  482.21  5285.7   486.5    5364  487.16  5385.4   488.3  5484.1  488.42
  5569.6  489.51  5583.8  490.39  5661.7  490.38    5711  491.25  5729.8   492.3
#Mann= 4 ,-1 , 0
    4416     .05       0  4701.6     .12       0  5009.5     .07       0
  5031.3     .12       0
Bank Sta=5009.5,5031.3
XS Rating Curve= 0 ,0
Exp/Cntr=0.3,0.1

Type RM Length L Ch R = 1 ,19594   ,384,384,384
BEGIN DESCRIPTION:
Mapping XS f59cf619
END DESCRIPTION:
XS GIS Cut Line= 3
      2734144.36      6940149.72      2733668.59      6940190.94
      2733078.24      6940914.12
#Sta/Elev= 30
  4442.9  495.02  4511.1  493.51  4516.1  492.37  4551.7  492.86  4629.3  492.22
  4634.3  491.36  4692.2  489.82  4722.3  487.74  4842.8  485.42  4882.2  483.14
  4923.7  481.53  4929.7  475.16  4934.2  475.03  4934.4  474.53  4937.9  474.53
  4944.1  481.11  4950.5  481.72  5014.4  480.82  5057.5  481.51  5112.8  481.27
  5277.9  483.54  5320.7  485.06  5426.6  486.09  5448.8  487.04  5533.5  487.35
  5583.1  489.07  5604.7  488.47  5669.2  488.89    5754  490.85    5854  491.22
#Mann= 5 ,-1 , 0
  4442.9     .05       0  4882.2     .12       0  4923.7     .07       0
  4950.5     .12       0  5112.8     .05       0
#XS Ineff= 2 , 0
       0                  5185.3       0  482.64
Permanent Ineff=
       F       F
Bank Sta=4923.7,4950.5
XS Rating Curve= 0 ,0
Exp/Cntr=0.3,0.1

Type RM Length L Ch R = 1 ,19210   ,451,451,451
BEGIN DESCRIPTION:
Little Allen Creek 21.0
END DESCRIPTION:
XS GIS Cut Line= 3
      2734121.23      6940082.08       2733324.5       6940071.5
      2732890.23      6940108.05
#Sta/Elev= 30
  4203.2  497.47  4268.4   496.5  4338.4  494.01  4348.4  493.06  4398.4  492.52
  4478.4  489.96  4528.5  487.61  4598.5  485.83  4618.5  484.51  4808.5  480.88
  4838.5  479.05  4952.3  478.25  5008.5  478.27  5018.6   474.2  5026.6  471.78
  5026.8  471.28  5038.6  472.06  5048.6  474.57  5053.7   478.3  5058.7  479.01
  5098.8  478.71  5108.9  479.34  5128.9  481.82    5139  482.15  5179.1  481.91
  5199.2  482.89  5279.5  483.06  5379.8  486.15  5408.1  485.99  5435.8  486.72
#Mann= 4 ,-1 , 0
  4203.2     .05       0  4952.3     .12       0  5008.5     .07       0
  5053.7     .12       0
Bank Sta=5008.5,5053.7
XS Rating Curve= 0 ,0
Exp/Cntr=0.3,0.1

Type RM Length L Ch R = 1 ,18759   ,333,333,333
BEGIN DESCRIPTION:
Little Allen Creek 19.0
END DESCRIPTION:
XS GIS Cut Line= 3
      2733798.82      6939579.91      2733061.88      6939748.18
      2732833.43      6940097.03
#Sta/Elev= 30
  4244.1  494.16  4380.3  491.25  4411.2  489.56  4482.9  487.52  4497.2  486.12
  4554.7  484.88  4595.7  483.22    4647  482.79  4674.2  480.84  4749.6  478.87
  4831.7  477.66  4851.2  478.04  4862.4  477.13  4893.2  476.66  4975.3  476.93
  4985.3  474.73  4988.4  471.02  4988.7  470.52  4992.2  470.52  4992.4  471.02
    5000  471.58  5005.5  474.97  5020.6  480.19  5056.8  482.05    5087  481.86
  5165.3  483.35  5252.8  483.41    5289  484.37  5331.1  484.25    5417  486.84
#Mann= 3 ,-1 , 0
  4244.1     .05       0  4988.4     .04       0  4992.4     .05       0
Bank Sta=4988.4,4992.4
XS Rating Curve= 0 ,0
Exp/Cntr=0.3,0.1

Type RM Length L Ch R = 1 ,18426   ,239,239,239
BEGIN DESCRIPTION:
Little Allen Creek 18.0
END DESCRIPTION:
XS GIS Cut Line= 3
      2733582.67      6939342.93       2732928.3      6939466.85
       2732671.5      6940076.69
#Sta/Elev= 30
    4334   491.3    4463  489.52  4510.2  487.19  4666.5  483.48  4677.4   482.1
  4707.2  481.87  4737.7  480.19  4961.6  476.38  4971.8  475.72  4996.3  471.92
  4996.6  469.49  4996.9  468.99  5000.6  469.49    5005  469.49  5014.4  472.09
  5019.8  475.09  5114.3  475.41  5186.6   475.7  5196.8  478.41  5225.9  479.91
  5278.8  480.69  5319.2   479.8  5326.3  480.94  5355.5  481.85  5379.2  481.22
  5461.3  482.61  5508.7  482.05    5547  483.56  5590.8  483.28  5661.7   485.1
#Mann= 5 ,-1 , 0
    4334     .05       0  4996.6     .04       0  5000.6     .05       0
  5114.3     .12       0  5186.6     .05       0
Bank Sta=4996.6,5000.6
XS Rating Curve= 0 ,0
Exp/Cntr=0.3,0.1

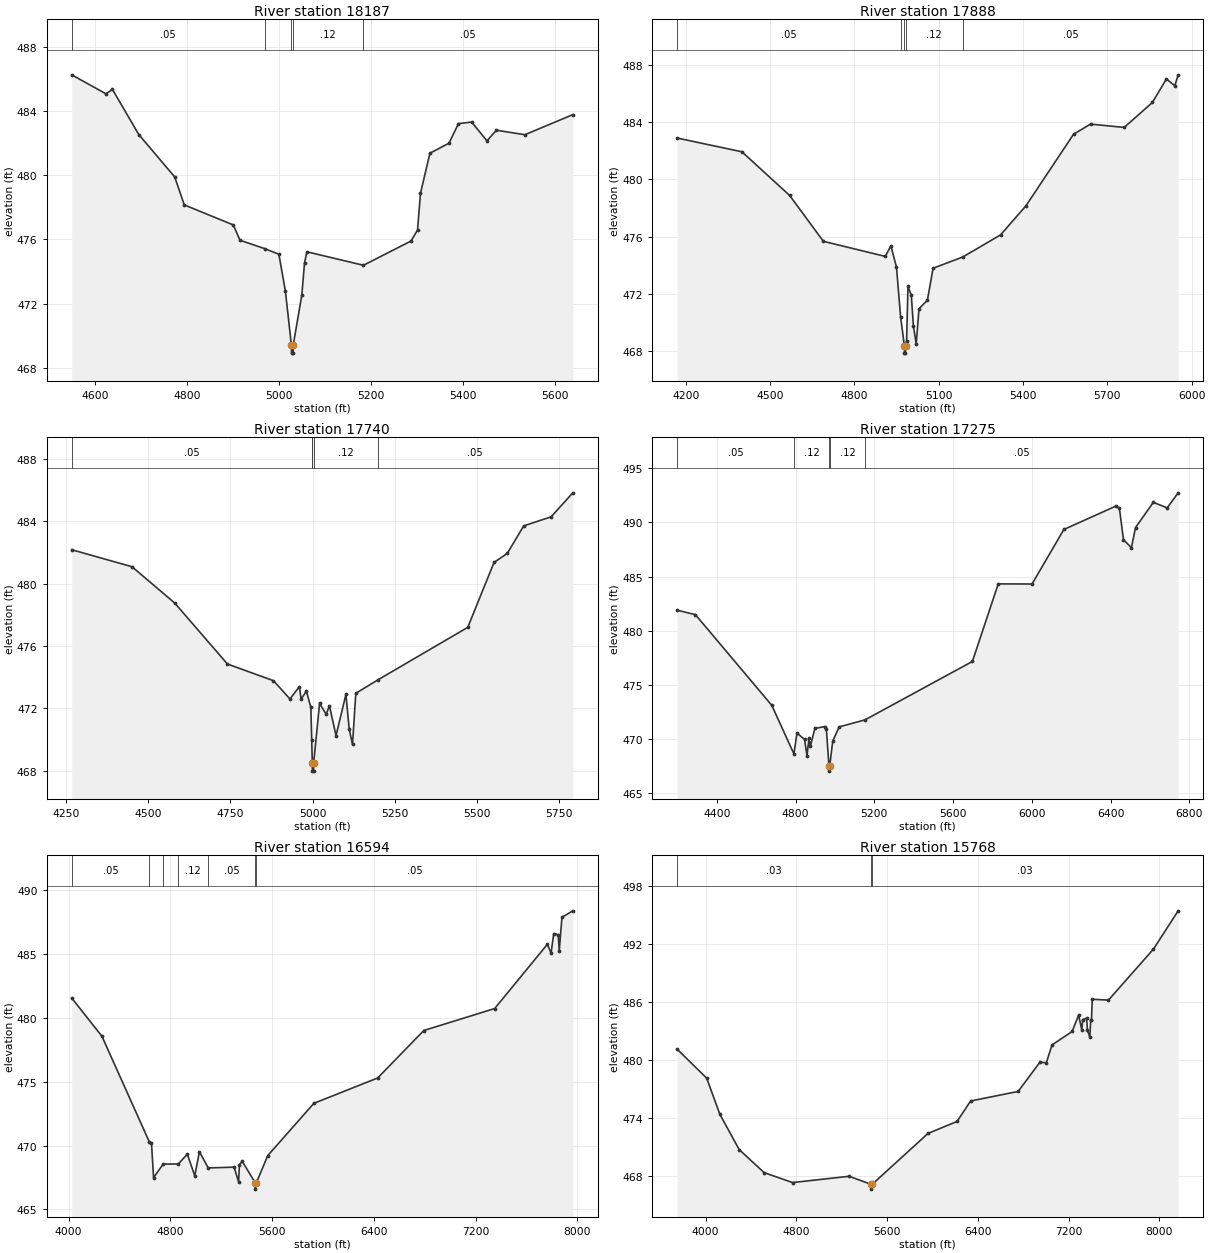
Type RM Length L Ch R = 1 ,18187   ,299,299,299
BEGIN DESCRIPTION:
Mapping XS d97340f9
END DESCRIPTION:
XS GIS Cut Line= 3
      2733087.92      6939038.23      2732731.14      6939337.72
       2732577.5      6939941.87
#Sta/Elev= 30
  4549.5  486.25  4623.8  485.07  4638.1  485.34  4695.3  482.53  4773.4  479.89
  4794.2  478.15  4900.9   476.9  4915.2  475.95  4968.6  475.43  4999.8  475.08
    5014  472.78    5027  469.42  5027.3  468.92  5030.8  468.92    5031  469.42
  5049.7  472.54  5055.6  474.55  5060.8  475.23  5183.6  474.39    5287   475.9
  5301.2  476.58  5307.6  478.87  5328.2  481.37  5369.5  481.99  5390.2  483.21
  5418.8  483.31  5452.1  482.14  5472.7   482.8  5534.6  482.52  5638.7  483.77
#Mann= 5 ,-1 , 0
  4549.5     .05       0  4968.6     .12       0    5027     .07       0
    5031     .12       0  5183.6     .05       0
Bank Sta=5027,5031
XS Rating Curve= 0 ,0
Exp/Cntr=0.3,0.1

Type RM Length L Ch R = 1 ,17888   ,148,148,148
BEGIN DESCRIPTION:
Mapping XS 68985f10
END DESCRIPTION:
XS GIS Cut Line= 3
      2732536.59      6938330.43      2732510.57      6939161.33
      2732476.88      6940112.73
#Sta/Elev= 30
  4168.7  482.88  4399.4  481.92  4569.5  478.87  4689.5  475.67  4909.6  474.62
  4929.6  475.36  4949.6  473.86  4964.1  470.42  4977.7  468.37  4977.9  467.87
  4981.4  467.87  4981.7  468.37  4985.5  468.73  4990.5  472.52  5002.3  471.91
  5009.7  469.77  5019.7  468.51  5029.7  470.97  5059.7  471.57  5079.7  473.79
  5185.5  474.58  5319.9  476.12  5409.9  478.14    5580  483.15  5640.1  483.85
  5760.1  483.62  5860.2  485.36  5910.2     487  5940.3  486.53    5952  487.29
#Mann= 5 ,-1 , 0
  4168.7     .05       0  4964.1     .12       0  4977.7     .07       0
  4981.7     .12       0  5185.5     .05       0
Bank Sta=4977.7,4981.7
XS Rating Curve= 0 ,0
Exp/Cntr=0.3,0.1

Type RM Length L Ch R = 1 ,17740   ,465,465,465
BEGIN DESCRIPTION:
Mapping XS 14fbc483
END DESCRIPTION:
XS GIS Cut Line= 3
      2732451.47      6938337.89      2732419.64      6939064.49
       2732377.4      6939860.07
#Sta/Elev= 30
  4267.4  482.18  4450.7  481.09  4580.8  478.76    4741  474.85  4881.1  473.78
  4931.1  472.61  4959.9   473.4  4964.9   472.6  4981.2  473.11  4994.7  472.07
  4997.3     470  4999.2  468.48  4999.5  467.98    5003  467.98  5003.2  468.48
  5021.2  472.32  5041.3  471.63  5051.3  472.17  5071.3  470.26  5101.4   472.9
  5111.4  470.67  5121.4  469.69  5131.4  472.97  5198.3  473.83  5471.9   477.2
    5552  481.37    5592  481.94  5642.1  483.71  5725.4  484.29  5791.4  485.83
#Mann= 5 ,-1 , 0
  4267.4     .05       0  4997.3     .12       0  4999.2     .07       0
  5003.2     .12       0  5198.3     .05       0
Bank Sta=4999.2,5003.2
XS Rating Curve= 0 ,0
Exp/Cntr=0.3,0.1

Type RM Length L Ch R = 1 ,17275   ,681,681,681
BEGIN DESCRIPTION:
Mapping XS f0bf0f09
END DESCRIPTION:
XS GIS Cut Line= 3
       2732413.4      6938337.01      2732065.16       6939066.5
      2732300.99      6940785.96
#Sta/Elev= 30
  4198.6  481.89  4291.6  481.48  4679.5  473.09  4791.8   468.6  4807.3  470.53
  4845.7  469.94  4858.2  468.42  4867.9  470.04  4875.4  469.32  4898.1  470.96
    4949  471.13  4956.5  470.87  4969.7  467.51  4969.9  467.01  4973.7  467.51
  4988.8  469.79  5021.6   471.1  5152.8  471.75  5697.9  477.15  5829.1  484.32
  6000.7  484.31  6162.2  489.35  6424.6   491.5    6444  491.35    6465   488.4
  6505.3  487.67  6526.2  489.53  6616.4  491.86    6687  491.35  6742.5  492.74
#Mann= 5 ,-1 , 0
  4198.6     .05       0  4791.8     .12       0  4969.7     .07       0
  4973.7     .12       0  5152.8     .05       0
Bank Sta=4969.7,4973.7
XS Rating Curve= 0 ,0
Exp/Cntr=0.3,0.1

Type RM Length L Ch R = 1 ,16594   ,826,826,826
BEGIN DESCRIPTION:
Mapping XS 27de76a5
END DESCRIPTION:
XS GIS Cut Line= 3
      2732378.13      6938343.08      2731516.94      6938801.92
      2729151.01      6940585.99
#Sta/Elev= 30
  4024.2  481.55  4261.6  478.56  4634.7  470.28  4651.3   470.2  4667.6  467.49
  4743.1  468.55    4862  468.56  4933.1  469.33  4991.4  467.63  5027.9  469.52
  5097.4  468.25  5300.6  468.31    5336  467.16  5342.3   468.5  5364.4  468.77
  5466.6  467.09    5468  466.59    5476  467.09  5564.8  469.21    5928  473.31
  6428.9  475.29  6792.2  479.01  7349.1  480.73  7763.4  485.76  7792.5  485.07
  7813.3   486.6  7848.7  486.51  7856.8  485.25  7877.9  487.87  7963.2  488.38
#Mann= 7 ,-1 , 0
  4024.2     .05       0  4634.7     .12       0  4743.1      .1       0
    4862     .12       0  5097.4     .05       0  5466.6     .05       0
    5476     .05       0
Bank Sta=5466.6,5476
XS Rating Curve= 0 ,0
Exp/Cntr=0.3,0.1

Type RM Length L Ch R = 1 ,15768   ,407,407,407
BEGIN DESCRIPTION:
Mapping XS 56d453b4
END DESCRIPTION:
XS GIS Cut Line= 3
      2732322.33       6938348.7      2731087.58      6938288.36
       2728657.4      6940339.01
#Sta/Elev= 30
  3748.6  481.12  4009.5  478.12  4125.4  474.38  4295.6  470.72  4515.8  468.33
  4766.1   467.3  5264.2  467.95  5458.2  467.12  5459.6  466.62  5468.2  467.12
  5959.9  472.39    6216  473.63  6335.7  475.75  6754.4  476.74  6946.7  479.77
  7002.7  479.71  7053.3  481.56  7230.2  482.95  7287.4  484.64  7315.9  483.09
  7322.5  484.18  7357.7  484.33  7365.4  483.09  7386.3  482.35    7394  484.16
  7400.6   484.1  7407.5  486.29  7550.1   486.2  7946.7  491.48  8164.6  495.45
#Mann= 3 ,-1 , 0
  3748.6     .03       0  5458.2     .03       0  5468.2     .03       0
Bank Sta=5458.2,5468.2
XS Rating Curve= 0 ,0
Exp/Cntr=0.3,0.1

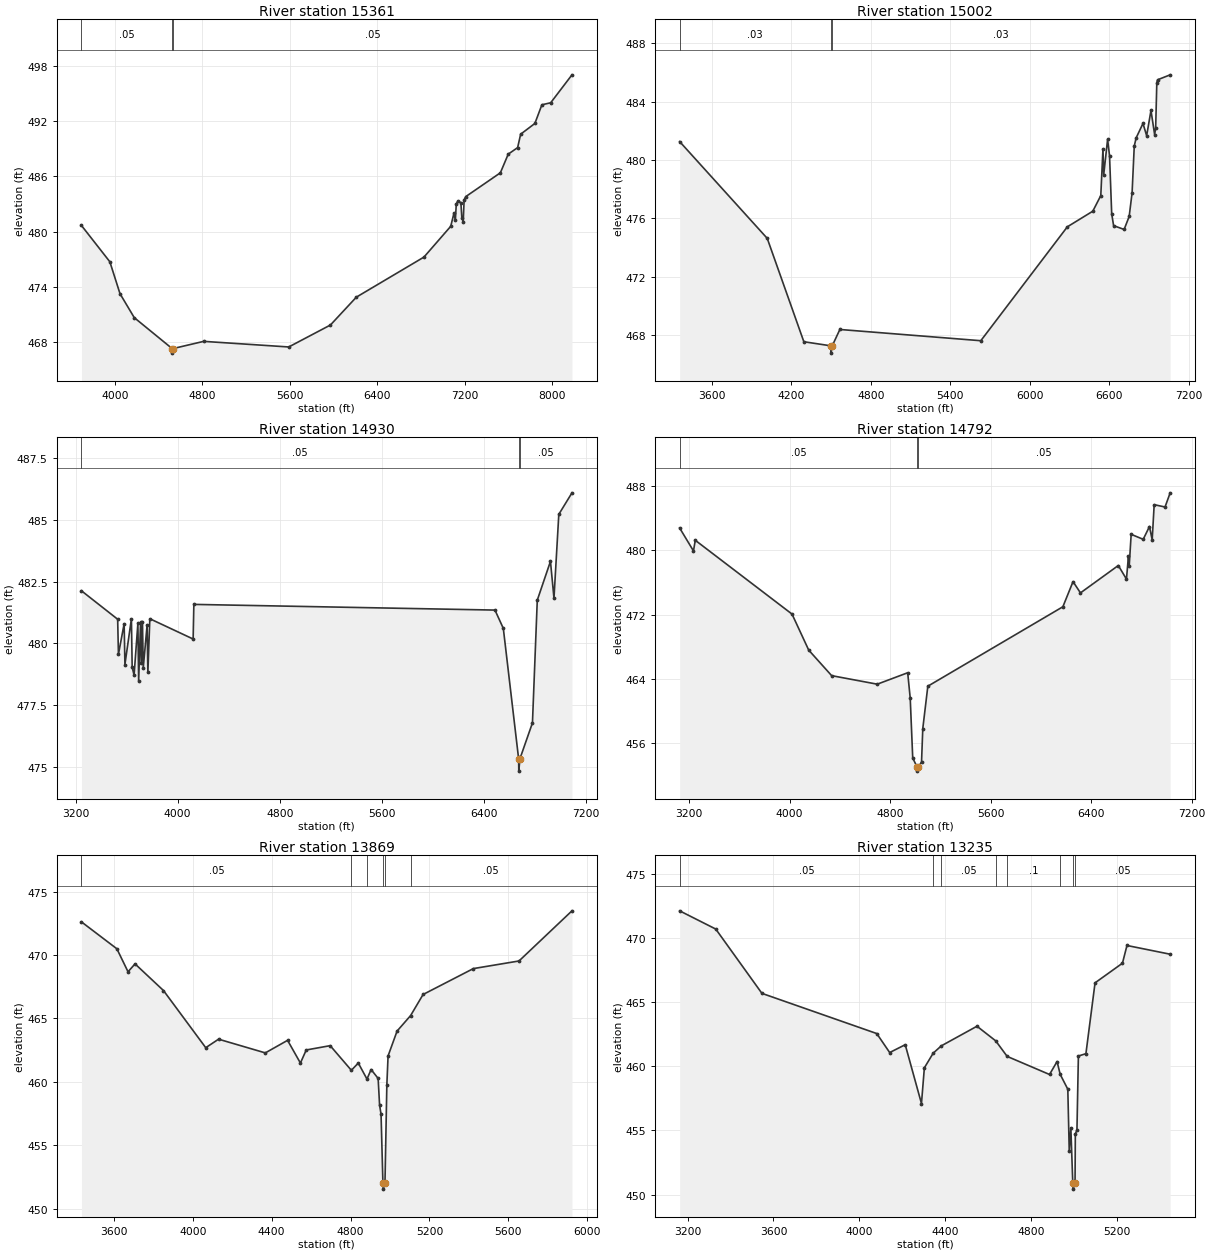
Type RM Length L Ch R = 1 ,15361   ,359,359,359
BEGIN DESCRIPTION:
Mapping XS 9f3546a5
END DESCRIPTION:
XS GIS Cut Line= 3
       2732300.2      6938306.97      2731102.06      6937873.42
      2728456.57      6939693.52
#Sta/Elev= 30
  3694.2  480.67  3953.9  476.72    4047  473.24  4177.2  470.64  4523.1  467.28
  4524.5  466.78  4533.3  467.28  4811.9  468.06  5589.6  467.45    5971  469.84
  6207.8  472.87  6826.1  477.23    7071  480.58  7099.9  481.99  7112.9  481.22
  7121.7  483.02  7136.3  483.33  7163.6  483.15  7172.4  481.53  7184.9  481.09
  7193.4  483.46  7208.3  483.81  7524.7   486.4  7596.6  488.43  7682.5  489.14
  7710.2   490.6  7840.3  491.77  7904.3   493.8  7984.9  494.02  8179.5  497.06
#Mann= 3 ,-1 , 0
  3694.2     .05       0  4523.1     .03       0  4533.3     .05       0
Bank Sta=4523.1,4533.3
XS Rating Curve= 0 ,0
Exp/Cntr=0.3,0.1

Type RM Length L Ch R = 1 ,15002   ,72,72,72
BEGIN DESCRIPTION:
Mapping XS 9d2ba176
END DESCRIPTION:
XS GIS Cut Line= 6
      2732346.01       6938304.8      2732024.83      6937727.55
      2731786.12      6937610.36      2730701.05      6937480.15
      2730015.28      6937823.03      2729209.48      6938251.93
#Sta/Elev= 30
  3359.1  481.26  4019.7  474.63  4295.8  467.55  4499.7  467.27  4501.1  466.77
  4509.9  467.27  4567.4  468.39  5630.2  467.62  6282.7  475.42  6474.7  476.49
    6535  477.56  6551.3  480.76    6557  478.99  6586.3  481.41  6600.9  480.29
  6617.2  476.31  6631.6   475.5  6710.9  475.24    6749  476.13    6771  477.75
  6787.3  480.95  6801.5  481.51  6853.2   482.5  6880.8  481.66  6913.4  483.39
  6941.1  481.73  6948.8  482.21  6957.4  485.29  6963.1  485.49  7058.1  485.83
#Mann= 3 ,-1 , 0
  3359.1     .03       0  4499.7     .03       0  4509.9     .03       0
Bank Sta=4499.7,4509.9
XS Rating Curve= 0 ,0
Exp/Cntr=0.3,0.1

Type RM Length L Ch R = 1 ,14930   ,138,138,138
BEGIN DESCRIPTION:
Mapping XS 1bd56d3f
END DESCRIPTION:
XS GIS Cut Line= 6
      2732463.18      6938287.42      2731977.09       6937614.7
      2731716.67      6937532.24      2730735.77      6937423.73
      2730453.65      6937514.87      2729191.44      6938226.24
#Sta/Elev= 30
  3246.1  482.13  3529.9  480.98    3536  479.56  3580.7   480.8  3586.8  479.15
  3637.6     481  3643.6  479.04  3658.5  478.72  3688.4  480.81  3694.4  478.49
  3709.3  480.85  3715.4  479.21  3724.2  480.88  3730.3  479.01  3760.7  480.75
  3766.6  478.83    3782     481  4121.3  480.18  4126.9  481.58  6486.3  481.35
  6551.7  480.61  6671.6  475.34    6673  474.84  6681.8  475.34    6780  476.79
  6817.8  481.75  6921.1  483.32  6948.6  481.83  6986.5  485.22  7089.7  486.09
#Mann= 3 ,-1 , 0
  3246.1     .05       0  6671.6    .035       0  6681.8     .05       0
Bank Sta=6671.6,6681.8
XS Rating Curve= 0 ,0
Exp/Cntr=0.3,0.1

Type RM Length L Ch R = 1 ,14792   ,923,923,923
BEGIN DESCRIPTION:
Mapping XS bdb5f7c4
END DESCRIPTION:
XS GIS Cut Line= 6
      2732538.71      6938222.11      2731957.12      6937505.98
      2731701.05      6937427.85      2730919.16      6937332.97
      2730416.32      6937410.49      2729189.55      6938108.41
#Sta/Elev= 30
  3125.4  482.75  3235.5   479.9    3250  481.22  4019.7  472.06  4152.5  467.59
    4335  464.42  4697.9  463.36  4940.1  464.78  4960.1  461.64  4980.1   454.2
  5015.1  453.07  5016.5  452.57  5025.3  453.07  5050.2  453.71  5060.2  457.86
  5100.3  463.11  6174.9  472.97  6255.6  476.09  6314.7  474.69  6615.9  478.09
  6680.8   476.4  6696.6  479.26  6702.4  477.97  6718.2  481.96    6814  481.34
  6863.8  482.93  6885.4  481.28  6901.3  485.64  6987.7  485.35  7028.5  487.11
#Mann= 3 ,-1 , 0
  3125.4     .05       0  5015.1    .035       0  5025.3     .05       0
Bank Sta=5015.1,5025.3
XS Rating Curve= 0 ,0
Exp/Cntr=0.3,0.1

Type RM Length L Ch R = 1 ,13869   ,634,634,634
BEGIN DESCRIPTION:
Mapping XS 8fd68120
END DESCRIPTION:
XS GIS Cut Line= 3
      2732273.99      6937492.97      2731010.94      6936585.84
      2730090.95      6936433.95
#Sta/Elev= 30
  3435.6  472.61  3615.3  470.49  3671.8  468.68  3707.4   469.3  3851.7   467.2
  4065.9   462.7    4131  463.37    4368  462.29  4480.9  463.28    4546  461.49
  4575.5  462.52    4697  462.86  4804.3  460.92  4839.5  461.49  4883.5  460.23
  4904.5  460.98  4940.1  460.28  4947.5  458.17  4954.9  457.46  4964.3  452.06
  4965.8  451.56  4974.8  452.06  4984.3  459.77  4990.5  462.05  5036.2  464.01
  5104.8  465.23    5168  466.89  5422.9  468.93  5654.5  469.53  5923.1  473.48
#Mann= 6 ,-1 , 0
  3435.6     .05       0  4804.3     .12       0  4883.5      .1       0
  4964.3     .07       0  4974.8      .1       0  5104.8     .05       0
Bank Sta=4964.3,4974.8
XS Rating Curve= 0 ,0
Exp/Cntr=0.3,0.1

Type RM Length L Ch R = 1 ,13235   ,1516,1516,1516
BEGIN DESCRIPTION:
Mapping XS d0de50fb
END DESCRIPTION:
XS GIS Cut Line= 4
      2732356.43      6937479.94      2731931.08      6936663.96
      2731440.63      6936416.57      2730832.99      6935869.69
#Sta/Elev= 30
  3162.5  472.11  3330.9  470.69  3546.2  465.68  4081.5  462.55  4141.8  461.07
  4214.3  461.68    4290   457.1  4303.5  459.88  4344.6  461.02  4382.4  461.59
  4548.8  463.12  4636.2  461.98  4689.5  460.77  4887.1  459.36  4922.2  460.37
  4936.8  459.37  4972.3  458.21    4979  453.38  4986.5  455.19  4995.4  450.93
  4996.8  450.43    5006  450.93  5007.4  454.73  5014.9  455.03  5021.6   460.8
  5056.7  460.98  5099.3   466.5  5227.1  468.03  5248.1  469.41  5449.5  468.73
#Mann= 8 ,-1 , 0
  3162.5     .05       0  4344.6     .12       0  4382.4     .05       0
  4636.2     .12       0  4689.5      .1       0  4936.8     .05       0
  4995.4     .04       0    5006     .05       0
Bank Sta=4995.4,5006
XS Rating Curve= 0 ,0
Exp/Cntr=0.3,0.1

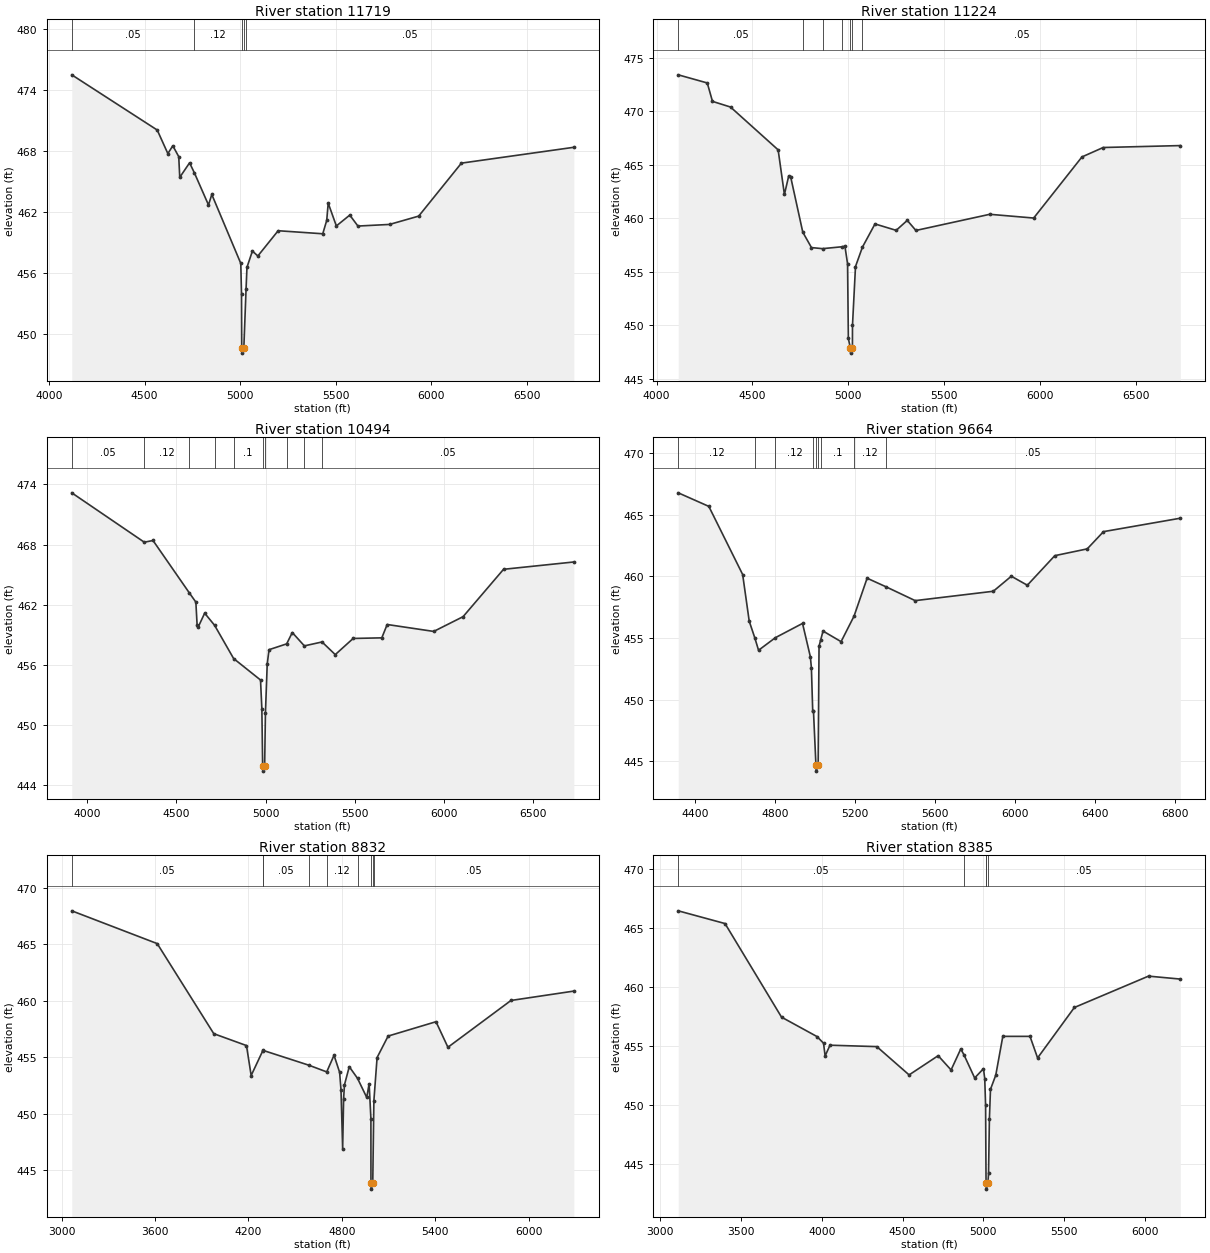
Type RM Length L Ch R = 1 ,11719   ,495,495,495
BEGIN DESCRIPTION:
Mapping XS c549c5c1
END DESCRIPTION:
XS GIS Cut Line= 4
      2732694.98      6937093.68      2732406.23      6936261.02
      2731918.06      6935834.97      2730837.29      6935635.31
#Sta/Elev= 30
  4118.7   475.5  4566.1  470.06  4621.7  467.74  4647.6  468.51  4678.7  467.44
    4684   465.4  4735.4  466.83  4761.1  465.82  4834.4  462.68  4851.8  463.71
  5003.5  456.92  5007.3  453.86  5008.4  448.58  5009.9  448.08  5019.4  448.58
  5031.2  454.44  5035.8  456.53  5064.3  458.14  5092.7  457.65  5199.1  460.14
  5432.6  459.84  5453.4  461.16  5461.1  462.86  5503.8  460.61    5574  461.68
  5616.7   460.6  5782.2  460.76  5934.8  461.58  6158.5   466.8    6747  468.36
#Mann= 5 ,-1 , 0
  4118.7     .05       0  4761.1     .12       0  5008.4     .07       0
  5019.4     .12       0  5031.2     .05       0
Bank Sta=5008.4,5019.4
XS Rating Curve= 0 ,0
Exp/Cntr=0.3,0.1

Type RM Length L Ch R = 1 ,11224   ,730,730,730
BEGIN DESCRIPTION:
Mapping XS 56b28d74
END DESCRIPTION:
XS GIS Cut Line= 4
      2732925.35      6936771.61      2732664.95      6935927.91
      2731763.91      6935401.87      2731076.37      6935323.74
#Sta/Elev= 30
  4113.1   473.4  4264.5  472.64  4291.7  470.92  4385.8  470.39  4634.1  466.39
  4666.8  462.22  4689.3  463.96  4699.4  463.87  4762.6   458.7  4807.9  457.26
  4865.8  457.16    4969  457.34  4982.4  457.39  4996.1  455.75  5000.3  448.77
  5010.4   447.9    5012   447.4  5021.5   447.9  5021.8  449.99  5037.5  455.49
  5073.9  457.31  5139.2  459.47  5249.6  458.87  5307.5   459.8  5352.5  458.86
  5737.7  460.37  5966.7  460.02  6218.5  465.73  6329.2  466.61  6731.4  466.79
#Mann= 7 ,-1 , 0
  4113.1     .05       0  4762.6     .12       0  4865.8      .1       0
    4969     .12       0  5010.4     .07       0  5021.5     .12       0
  5073.9     .05       0
Bank Sta=5010.4,5021.5
XS Rating Curve= 0 ,0
Exp/Cntr=0.3,0.1

Type RM Length L Ch R = 1 ,10494   ,830,830,830
BEGIN DESCRIPTION:
Mapping XS 1c198970
END DESCRIPTION:
XS GIS Cut Line= 3
      2733743.06      6936047.69      2733185.78      6935438.33
      2731203.37      6935245.81
#Sta/Elev= 30
  3912.4  473.15  4319.3  468.23  4368.3   468.4  4570.9  463.21  4608.8  462.26
  4615.6  460.03    4623  459.82  4658.2  461.16  4713.9  459.95  4820.6  456.64
  4971.6   454.5  4979.1  451.65  4983.6  445.92  4985.1  445.42  4994.7  445.92
  4999.2  451.23  5009.2  456.08  5019.3  457.52  5118.3   458.1  5149.9  459.23
  5217.6   457.9  5316.8  458.29    5391  457.03  5491.5  458.64  5652.2   458.7
  5682.4  460.03  5943.6  459.34  6108.3  460.81  6335.4  465.53  6729.9  466.26
#Mann= 10 ,-1 , 0
  3912.4     .05       0  4319.3     .12       0  4570.9     .05       0
  4713.9     .12       0  4820.6      .1       0  4983.6     .07       0
  4994.7      .1       0  5118.3     .12       0  5217.6      .1       0
  5316.8     .05       0
Bank Sta=4983.6,4994.7
XS Rating Curve= 0 ,0
Exp/Cntr=0.3,0.1

Type RM Length L Ch R = 1 ,9664    ,832,832,832
BEGIN DESCRIPTION:
Mapping XS 231ad6a7
END DESCRIPTION:
XS GIS Cut Line= 4
       2733779.5      6934979.98       2733133.7      6934782.08
      2732024.33      6934761.24      2731383.67      6935094.59
#Sta/Elev= 30
  4317.3  466.79    4470  465.69    4639  460.16  4671.8  456.37  4699.4  455.03
  4718.4  454.01  4802.2  455.03    4938  456.19    4977  453.49  4982.2   452.6
  4988.9  449.06  4992.7  449.06  5004.9   444.7  5006.4   444.2    5016   444.7
  5020.4  454.33    5028  454.81  5040.4  455.57  5130.5  454.71  5195.2  456.78
  5260.5  459.86  5355.2  459.16  5500.5  458.04  5890.6   458.8  5980.6  460.02
  6060.6  459.29  6197.8  461.69  6359.7  462.24  6440.9  463.64  6824.5  464.73
#Mann= 9 ,-1 , 0
  4317.3     .12       0  4699.4     .05       0  4802.2     .12       0
  4992.7      .1       0  5004.9     .07       0    5016      .1       0
    5028      .1       0  5195.2     .12       0  5355.2     .05       0
Bank Sta=5004.9,5016
XS Rating Curve= 0 ,0
Exp/Cntr=0.3,0.1

Type RM Length L Ch R = 1 ,8832    ,447,447,447
BEGIN DESCRIPTION:
Mapping XS 7ecc407b
END DESCRIPTION:
XS GIS Cut Line= 5
      2734630.31      6934285.62      2734040.02      6934103.33
       2733046.1      6934120.69       2732755.3      6934224.86
      2731466.23      6934415.83
#Sta/Elev= 30
  3065.4  467.97  3614.1  465.07  3977.3   457.1  4187.3  456.05  4217.3   453.4
  4291.2  455.57  4294.8  455.62  4588.4  454.31  4702.5  453.72  4749.4  455.19
  4785.4  453.68  4794.2  452.12  4804.8  446.93  4810.9  451.31  4816.2  452.57
  4847.3  454.18  4900.3  453.15  4959.4  451.46  4974.8  452.67  4986.2  449.59
  4986.5  443.85  4988.1  443.35    4998  443.85  5005.3  451.17  5025.9  454.99
  5096.7  456.89  5404.2  458.16  5480.8   455.9  5885.6  460.04  6289.3  460.87
#Mann= 9 ,-1 , 0
  3065.4     .05       0  4291.2     .12       0  4294.8     .05       0
  4588.4      .1       0  4702.5     .12       0  4900.3      .1       0
  4986.5     .07       0    4998      .1       0  5005.3     .05       0
Bank Sta=4986.5,4998
XS Rating Curve= 0 ,0
Exp/Cntr=0.3,0.1

Type RM Length L Ch R = 1 ,8385    ,654,654,654
BEGIN DESCRIPTION:
Mapping XS 9a8113ff
END DESCRIPTION:
XS GIS Cut Line= 4
      2734435.83      6933945.34       2732673.7        6933941.
      2731970.58      6934244.82      2731399.32      6934353.01
#Sta/Elev= 30
  3110.6  466.48  3400.4   465.4  3750.4  457.46  3970.4  455.81  4010.4  455.25
  4020.4  454.17  4050.4  455.08  4340.4  454.96  4540.4  452.56  4720.4  454.19
  4800.4  452.98  4860.4  454.76  4879.7  454.28  4946.5   452.3    5001  453.09
  5008.9  452.23  5014.2  449.97    5017  443.37  5018.6  442.87  5028.5  443.37
  5032.4  444.21  5037.8  448.86  5044.5  451.34  5077.2  452.54  5120.8  455.83
  5289.2  455.83  5336.2     454    5564  458.28  6023.1  460.94  6220.1  460.69
#Mann= 5 ,-1 , 0
  3110.6     .05       0  4879.7      .1       0  5014.2     .05       0
    5017     .07       0  5028.5     .05       0
Bank Sta=5017,5028.5
XS Rating Curve= 0 ,0
Exp/Cntr=0.3,0.1