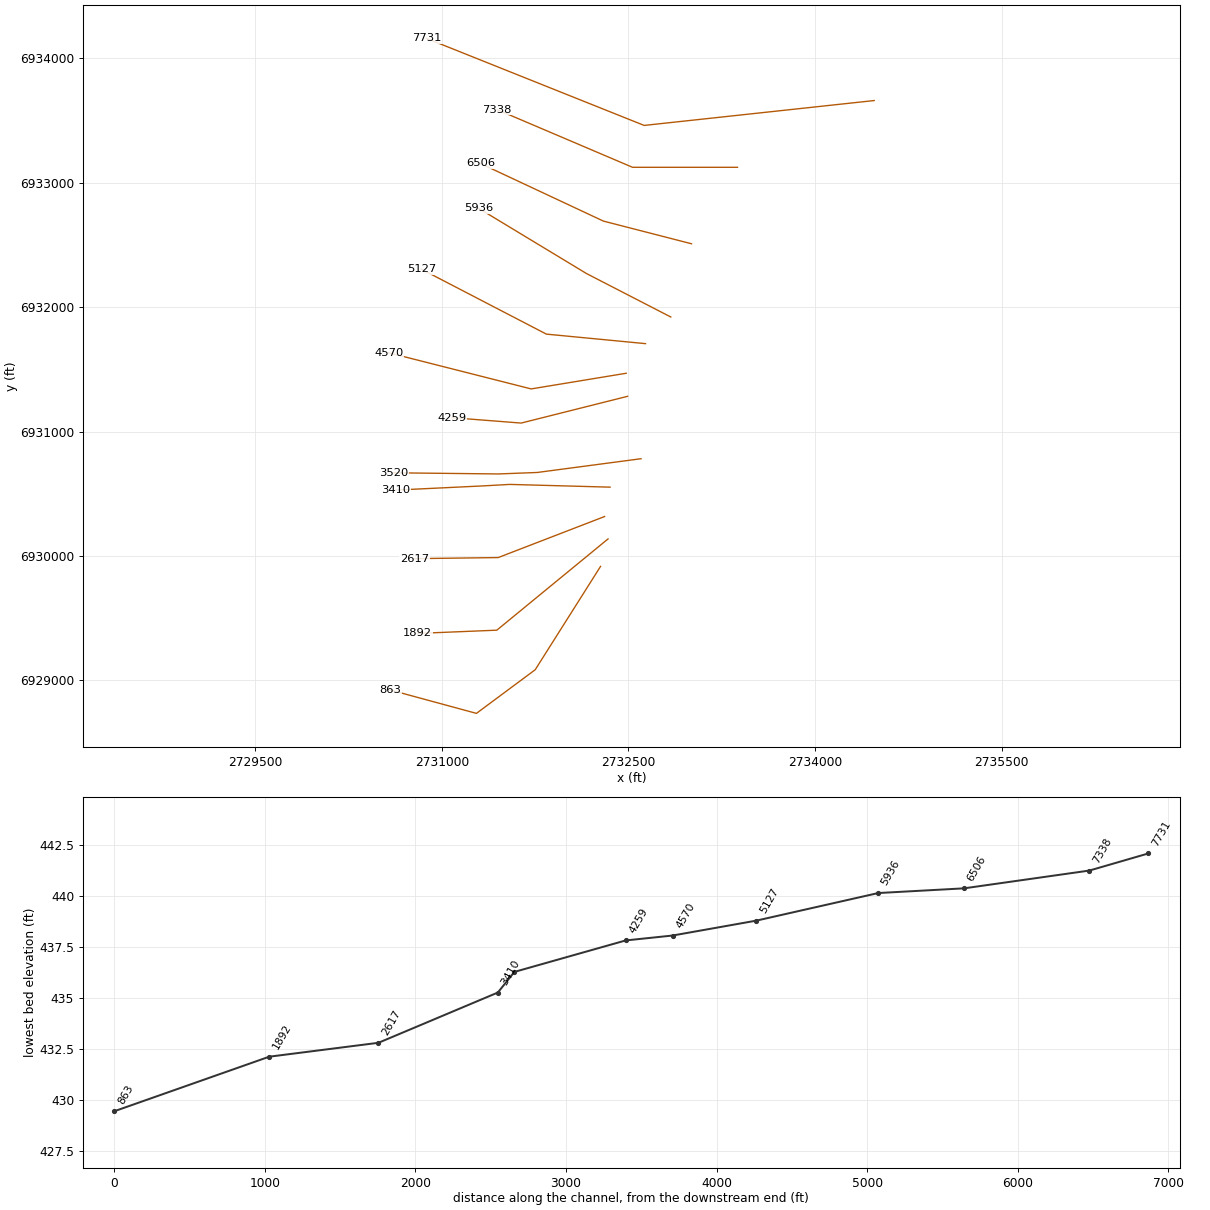
HEC-RAS study Little Allen Creek.prj: Little Allen Creek Base Level Engineering

--- Little Allen Creek.g01 (geometry) --- (continued)

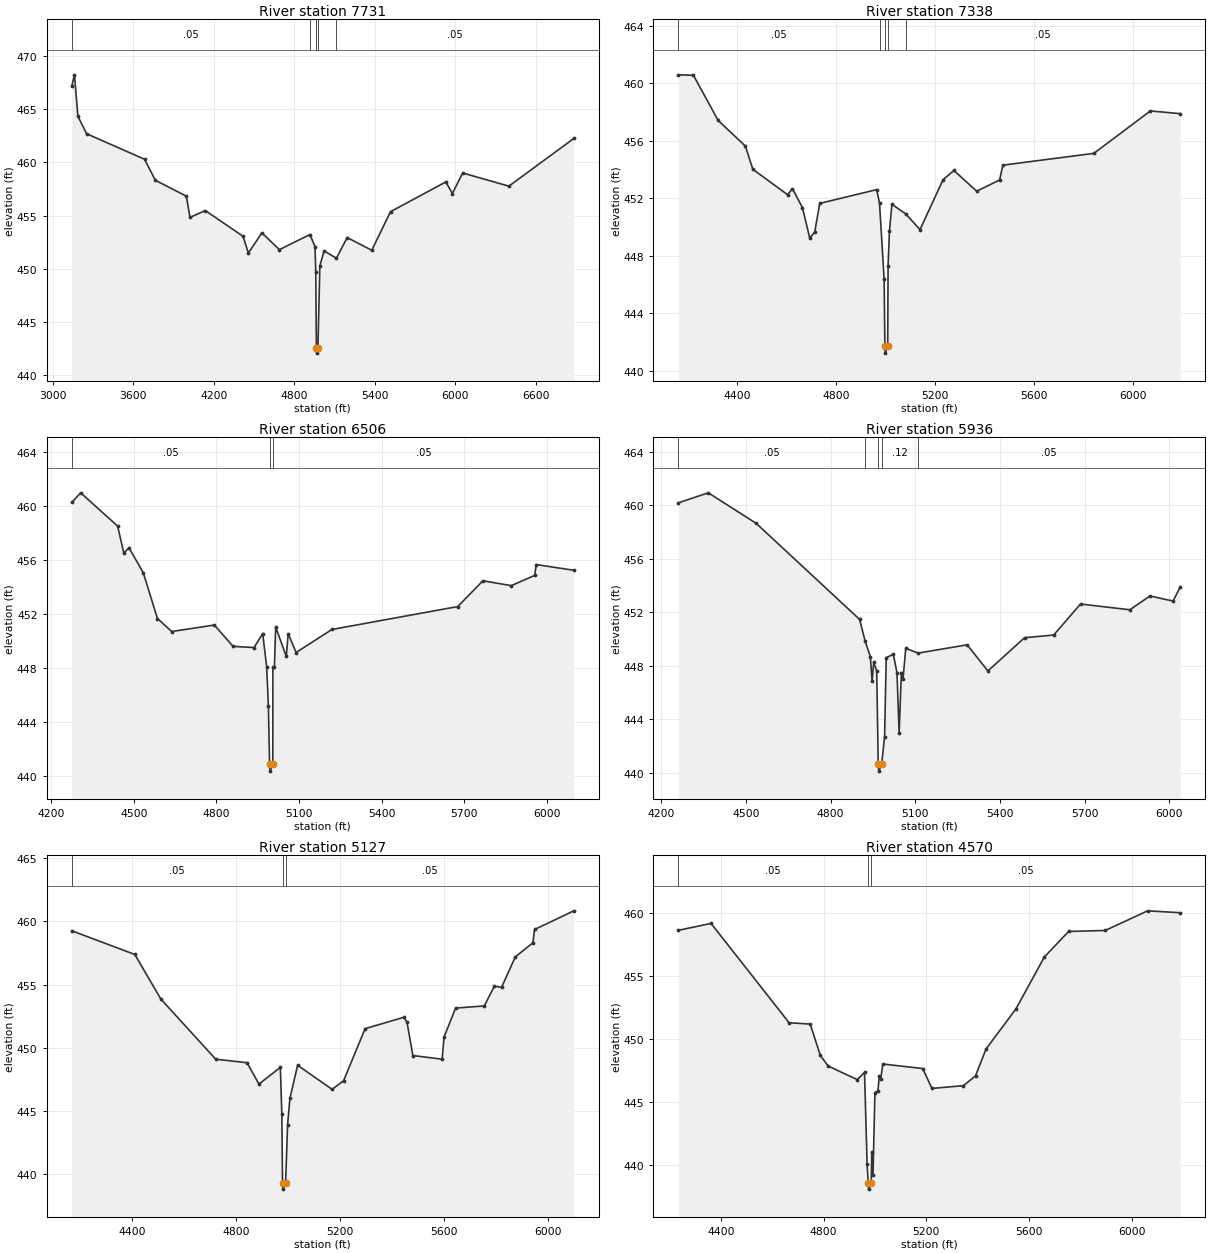
Type RM Length L Ch R = 1 ,7731    ,393,393,393
BEGIN DESCRIPTION:
Little Allen Creek 3.0
END DESCRIPTION:
XS GIS Cut Line= 3
      2734475.97        6933661.      2732626.85      6933461.01
      2730875.99        6934161.
#Sta/Elev= 30
  3140.1  467.16  3160.2  468.24  3185.9  464.34  3250.7   462.7  3683.2   460.3
  3763.7  458.32    3995  456.83  4021.9  454.83  4135.8  455.48  4417.5  453.06
  4457.7  451.48  4558.3  453.38    4689   451.8  4916.7  453.22  4954.6  452.09
  4960.6  449.67  4964.9  442.57  4966.5  442.07  4976.4  442.57  4990.8  450.27
  5022.5  451.69  5114.1  450.99  5194.8  452.94  5377.9  451.74  5517.9  455.37
  5930.9  458.17  5979.4  457.08  6056.3  459.01    6401  457.77  6885.6  462.26
#Mann= 5 ,-1 , 0
  3140.1     .05       0  4916.7     .12       0  4964.9     .07       0
  4976.4     .12       0  5114.1     .05       0
Bank Sta=4964.9,4976.4
XS Rating Curve= 0 ,0
Exp/Cntr=0.3,0.1

Type RM Length L Ch R = 1 ,7338    ,832,832,832
BEGIN DESCRIPTION:
Mapping XS 22f9c247
END DESCRIPTION:
XS GIS Cut Line= 3
      2733377.18       6933124.4      2732533.42       6933124.4
      2731444.87      6933587.95
#Sta/Elev= 30
    4163  460.58  4224.2  460.55  4324.2  457.41  4434.2  455.62  4464.2  454.01
  4604.2  452.25  4624.2  452.66  4664.2  451.35  4694.2  449.22  4714.2  449.67
  4734.2  451.64  4964.2   452.6  4975.6  451.65  4994.2  446.37  4997.2  441.73
  4998.8  441.23  5008.7  441.73  5010.1  447.26  5015.6  449.71  5025.7  451.58
  5081.3  450.91  5139.1  449.82  5232.2  453.29  5275.7  453.93  5368.1  452.49
  5460.4  453.27  5473.5   454.3  5840.9  455.12  6069.1  458.07  6189.9  457.88
#Mann= 5 ,-1 , 0
    4163     .05       0  4975.6     .12       0  4997.2     .07       0
  5008.7     .12       0  5081.3     .05       0
Bank Sta=4997.2,5008.7
XS Rating Curve= 0 ,0
Exp/Cntr=0.3,0.1

Type RM Length L Ch R = 1 ,6506    ,570,570,570
BEGIN DESCRIPTION:
Mapping XS 75c066ae
END DESCRIPTION:
XS GIS Cut Line= 3
      2733007.42       6932509.8      2732299.05      6932692.11
      2731310.21       6933155.3
#Sta/Elev= 30
  4274.4  460.28  4306.8  460.99  4441.1  458.52  4463.3  456.53  4482.4  456.91
    4534  455.07  4585.6  451.67  4637.3  450.71  4792.2  451.19  4860.1  449.61
  4936.4  449.52  4967.7  450.56  4982.3  448.09  4988.4  445.21  4992.9  440.86
  4994.5  440.36  5004.5  440.86  5004.8  448.06  5010.3  448.06  5014.9  451.05
  5053.4  448.86  5060.5  450.56  5088.9  449.15    5219  450.86  5676.2  452.56
  5767.5  454.47  5870.6  454.11  5955.7  454.87  5961.2  455.67  6097.8  455.25
#Mann= 3 ,-1 , 0
  4274.4     .05       0  4992.9     .04       0  5004.5     .05       0
Bank Sta=4992.9,5004.5
XS Rating Curve= 0 ,0
Exp/Cntr=0.3,0.1

Type RM Length L Ch R = 1 ,5936    ,809,809,809
BEGIN DESCRIPTION:
Mapping XS 80d07487
END DESCRIPTION:
XS GIS Cut Line= 3
      2732840.74      6931921.26      2732163.63      6932270.23
      2731294.04      6932796.15
#Sta/Elev= 30
  4260.6  460.18  4367.2  460.93  4537.2  458.64  4902.8  451.47  4922.7  449.83
  4940.9  448.69  4947.1  446.85  4952.7  448.25  4963.4  447.64  4968.9  440.63
  4970.6  440.13  4980.8  440.63  4991.4  442.68  4997.2  448.61  5022.3  448.86
  5035.3  447.48  5042.9  442.98  5050.8   447.5  5056.6  447.02  5066.3  449.31
  5109.8  448.95  5283.6  449.57  5357.3  447.62    5487   450.1  5590.1   450.3
  5685.2  452.62  5859.8  452.19  5931.1  453.22  6012.9  452.84  6038.6  453.91
#Mann= 5 ,-1 , 0
  4260.6     .05       0  4922.7     .12       0  4968.9     .07       0
  4980.8     .12       0  5109.8     .05       0
Bank Sta=4968.9,4980.8
XS Rating Curve= 0 ,0
Exp/Cntr=0.3,0.1

Type RM Length L Ch R = 1 ,5127    ,557,557,557
BEGIN DESCRIPTION:
Mapping XS ec6879e2
END DESCRIPTION:
XS GIS Cut Line= 3
      2732637.51      6931707.11      2731841.01      6931783.54
      2730836.18      6932305.34
#Sta/Elev= 30
  4168.3  459.26  4410.9  457.38  4511.4  453.84  4722.3  449.08  4842.9   448.8
  4888.8  447.11  4971.1  448.43  4976.8  444.73  4979.4  439.28  4981.1  438.78
  4991.3  439.28  4998.9  443.86  5007.9  445.97  5037.5   448.6  5170.2  446.69
  5214.4  447.37  5297.3   451.5  5446.4   452.4  5458.6  452.01  5481.2  449.37
  5593.8  449.08  5601.3  450.84  5645.5  453.13  5756.1   453.3  5794.7  454.87
  5822.4  454.77  5875.5  457.19  5943.2  458.31  5949.5  459.36  6100.7  460.84
#Mann= 3 ,-1 , 0
  4168.3     .05       0  4979.4     .04       0  4991.3     .05       0
Bank Sta=4979.4,4991.3
XS Rating Curve= 0 ,0
Exp/Cntr=0.3,0.1

Type RM Length L Ch R = 1 ,4570    ,311,311,311
BEGIN DESCRIPTION:
Mapping XS d5dfb016
END DESCRIPTION:
XS GIS Cut Line= 3
      2732482.16      6931469.01      2731718.32      6931343.15
      2730572.48      6931633.95
#Sta/Elev= 30
  4233.4  458.61  4361.3  459.16  4665.3  451.27  4747.7  451.16  4786.9  448.68
  4817.3  447.83  4931.2  446.75  4959.2  447.33  4969.4  440.03  4973.5  438.55
  4975.2  438.05  4985.4  438.55  4987.3     441  4992.3  439.21  4999.8  445.72
  5011.3  445.84  5017.1  447.05  5022.3  446.79  5030.6  447.99  5186.1  447.63
  5221.9  446.05  5344.8  446.27  5391.7  447.05  5432.9  449.19  5549.6  452.38
  5659.9  456.49  5754.4  458.52  5897.2   458.6  6062.3  460.16  6189.7  460.01
#Mann= 3 ,-1 , 0
  4233.4     .05       0  4973.5     .04       0  4985.4     .05       0
Bank Sta=4973.5,4985.4
XS Rating Curve= 0 ,0
Exp/Cntr=0.3,0.1

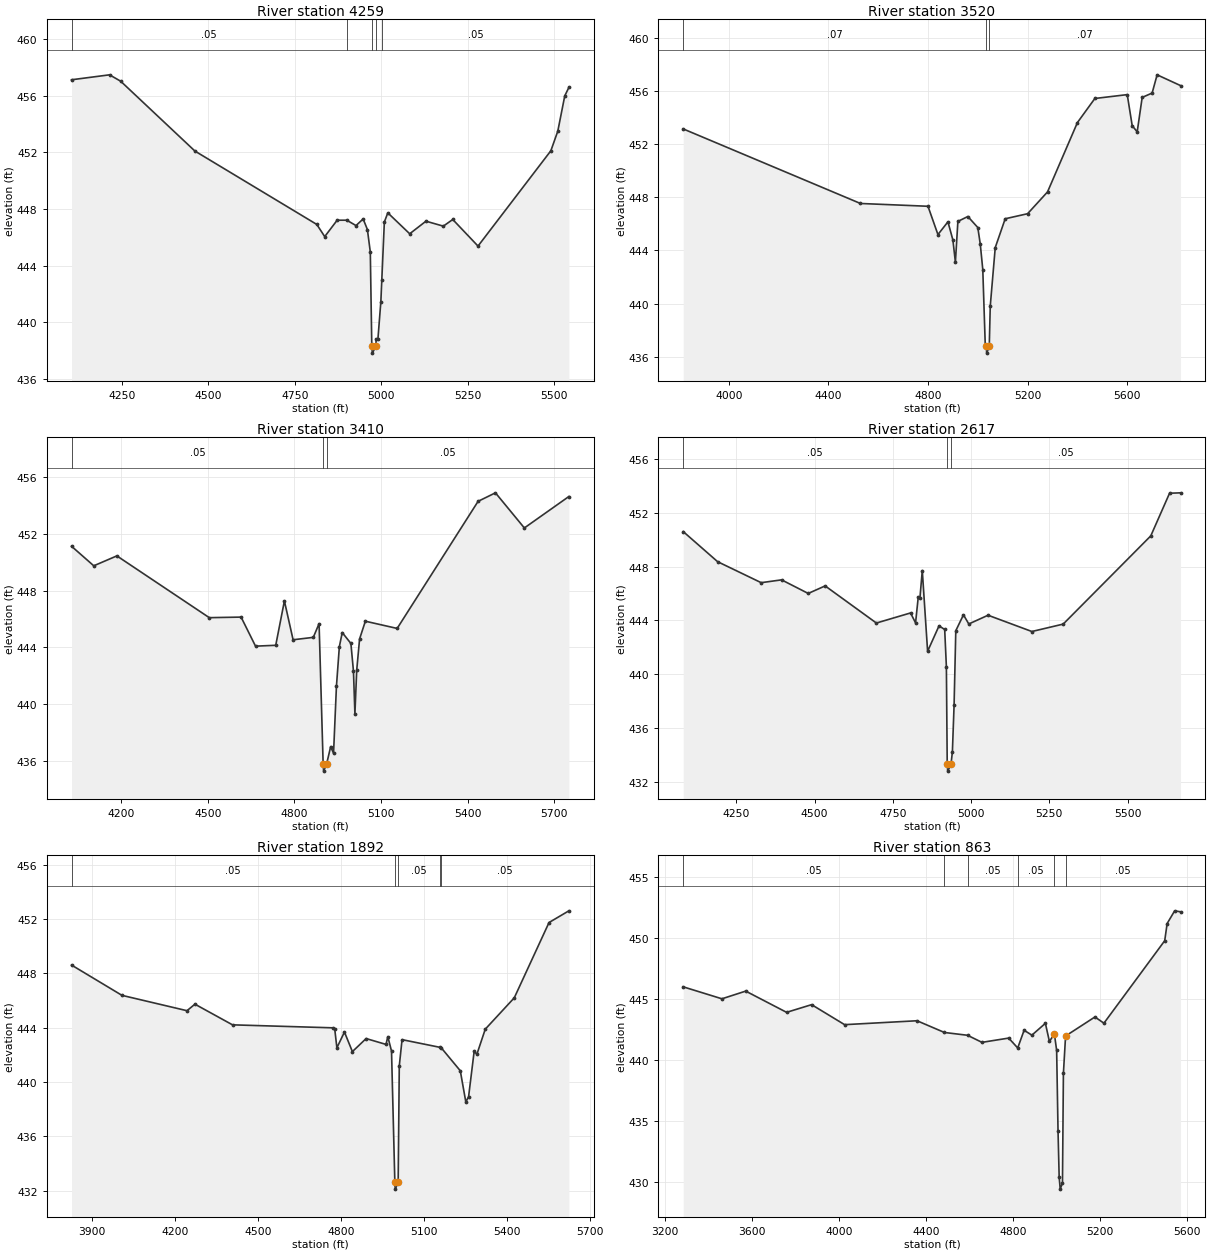
Type RM Length L Ch R = 1 ,4259    ,739,739,739
BEGIN DESCRIPTION:
Mapping XS 5f65ea72
END DESCRIPTION:
XS GIS Cut Line= 3
       2732493.7      6931283.74      2731638.14      6931068.71
      2731084.09      6931111.92
#Sta/Elev= 30
  4104.8  457.14  4214.7  457.49  4246.8  457.04  4461.5   452.1  4813.9  446.91
  4836.8  446.05  4872.8  447.21  4900.6  447.21  4927.3  446.83  4947.9   447.3
  4960.2  446.55  4968.6  444.96  4972.9  438.31  4974.6  437.81  4984.8  438.31
  4985.5   438.8  4990.6   438.8  4999.1  441.45  5001.8  442.96  5009.2  447.08
  5019.2  447.73  5082.5  446.25  5129.5  447.14  5179.7  446.79    5207  447.26
    5280  445.38  5490.6  452.12  5510.7  453.51  5530.8     456  5542.7   456.6
#Mann= 5 ,-1 , 0
  4104.8     .05       0  4900.6     .12       0  4972.9     .07       0
  4984.8     .12       0  5001.8     .05       0
Bank Sta=4972.9,4984.8
XS Rating Curve= 0 ,0
Exp/Cntr=0.3,0.1

Type RM Length L Ch R = 1 ,3520    ,110,110,110
BEGIN DESCRIPTION:
Mapping XS 27b5f3ac
END DESCRIPTION:
XS GIS Cut Line= 4
       2732601.6      6930782.16       2731766.5      6930671.52
        2731454.      6930659.71      2730611.88      6930668.96
#Sta/Elev= 30
  3816.9  453.14  4528.7  447.53  4799.9  447.32  4839.9  445.19    4880  446.15
    4900  444.78    4910  443.11    4920  446.18    4960  446.55    5000  445.72
    5010  444.46    5020  442.56    5030  436.84    5034  436.77  5035.7  436.27
    5046  436.77    5050  439.81    5070  444.21    5110  446.38    5200  446.76
    5280   448.4  5400.1  453.62  5470.1  455.43  5600.1  455.72  5620.1  453.38
  5640.1  452.92  5660.1  455.51  5700.1  455.84  5720.1  457.21  5814.2   456.4
#Mann= 3 ,-1 , 0
  3816.9     .07       0    5034     .05       0    5046     .07       0
Bank Sta=5034,5046
XS Rating Curve= 0 ,0
Exp/Cntr=0.3,0.1

Type RM Length L Ch R = 1 ,3410    ,793,793,793
BEGIN DESCRIPTION:
Mapping XS a650e4bf
END DESCRIPTION:
XS GIS Cut Line= 4
      2732352.97      6930553.59      2731546.23      6930575.64
      2731328.35      6930563.49      2730632.01      6930530.07
#Sta/Elev= 30
    4028  451.13    4105  449.75    4185  450.45  4505.1  446.09  4615.2  446.13
  4665.2  444.08  4735.2  444.14  4765.2  447.27  4795.3  444.53  4865.3   444.7
  4885.3  445.67  4899.4  435.76  4901.1  435.26  4911.4  435.76  4925.4  436.99
  4935.4  436.52  4945.4  441.24  4955.5  444.04  4965.5  445.04  4995.5  444.27
  5004.4  442.31  5009.4   439.3  5015.6  442.37  5025.6  444.59  5045.6  445.84
  5155.7  445.33    5436   454.3  5496.1   454.9  5596.2  452.42  5750.4  454.64
#Mann= 3 ,-1 , 0
    4028     .05       0  4899.4    .035       0  4911.4     .05       0
Bank Sta=4899.4,4911.4
XS Rating Curve= 0 ,0
Exp/Cntr=0.3,0.1

Type RM Length L Ch R = 1 ,2617    ,725,725,725
BEGIN DESCRIPTION:
Mapping XS c2c4b40d
END DESCRIPTION:
XS GIS Cut Line= 3
      2732308.75      6930317.49      2731453.69      6929987.62
      2730780.93      6929978.94
#Sta/Elev= 30
  4080.1  450.61  4190.1  448.37  4329.3  446.81  4394.5  447.02  4479.6  446.01
  4533.7  446.57  4697.4  443.81  4806.6  444.56  4822.6  443.82  4831.2  445.74
  4836.5  445.65  4844.1  447.71  4861.1  441.71  4897.6   443.6  4915.7  443.33
  4921.1  440.57  4923.8   433.3  4925.4   432.8  4935.8   433.3  4940.3  434.23
  4945.7   437.7  4951.2  443.24  4975.7  444.42  4992.7  443.74  5054.3  444.39
  5194.3  443.18  5294.3  443.73  5574.3  450.29  5634.3  453.46  5669.4  453.49
#Mann= 3 ,-1 , 0
  4080.1     .05       0  4923.8    .035       0  4935.8     .05       0
Bank Sta=4923.8,4935.8
XS Rating Curve= 0 ,0
Exp/Cntr=0.3,0.1

Type RM Length L Ch R = 1 ,1892    ,1029,1029,1029
BEGIN DESCRIPTION:
Mapping XS 52198e8c
END DESCRIPTION:
XS GIS Cut Line= 3
      2732336.51       6930137.5      2731442.41        6929404.
      2730804.42      6929377.96
#Sta/Elev= 30
  3827.3  448.61  4009.3  446.38    4244  445.25  4272.7  445.73  4408.3  444.21
  4770.7  443.99  4777.2  443.91    4785  442.52  4812.3  443.68    4841  442.24
  4890.5   443.2  4962.3  442.77  4968.8  443.34  4982.2  442.28  4994.2  432.62
  4995.8  432.12  5006.2  432.62  5010.2  441.18  5020.2  443.12  5155.8  442.56
  5162.5   442.5  5230.4  440.83  5250.4  438.53  5260.4  438.93  5280.4  442.25
  5290.4  442.05  5320.5  443.89  5425.3   446.2  5550.7  451.74  5622.3   452.6
#Mann= 5 ,-1 , 0
  3827.3     .05       0  4994.2    .035       0  5006.2     .05       0
  5155.8     .12       0  5162.5     .05       0
Bank Sta=4994.2,5006.2
XS Rating Curve= 0 ,0
Exp/Cntr=0.3,0.1

Type RM Length L Ch R = 1 ,863     ,0,0,0
BEGIN DESCRIPTION:
Mapping XS 8df3290b
END DESCRIPTION:
XS GIS Cut Line= 4
      2732276.31      6929916.65        2731751.        6929086.
      2731278.62      6928735.31      2730585.61      6928923.31
#Sta/Elev= 30
  3283.3  446.03  3461.6  445.05    3571  445.68  3759.2  443.94  3874.4  444.57
  4026.2  442.93  4359.5  443.25  4485.6  442.29  4591.9  442.06  4658.4  441.48
  4781.5  441.83    4823  441.02  4852.4  442.47  4888.2  442.07  4950.4  443.04
  4968.8  441.56  4991.9  442.16  5002.2  440.82  5008.6  434.19  5013.8  430.44
  5018.6  429.45    5029  429.95  5033.3  438.93  5043.3     442  5178.4  443.56
  5219.8  443.05  5499.6  449.81  5510.8  451.22  5545.4  452.26  5572.5  452.18
#Mann= 6 ,-1 , 0
  3283.3     .05       0  4485.6      .1       0  4591.9     .05       0
    4823     .05       0  4991.9    .035       0  5043.3     .05       0
Bank Sta=4991.9,5043.3
XS Rating Curve= 0 ,0
Exp/Cntr=0.3,0.1

Chan Stop Cuts=-1
Use User Specified Reach Order=0
Composite Channel Slope=5