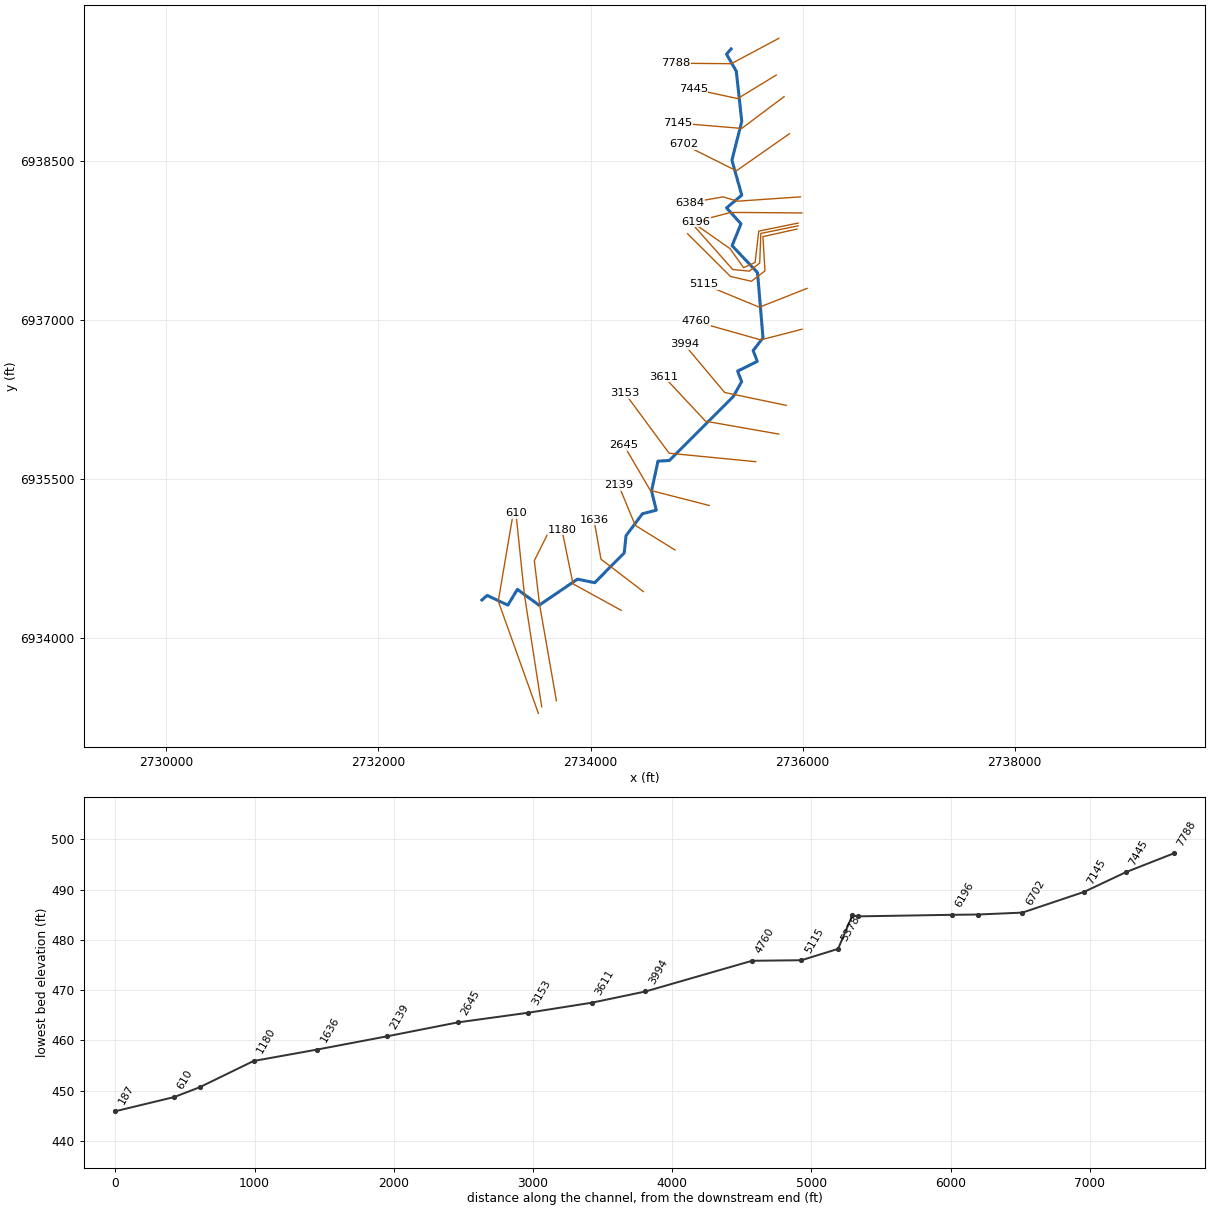
--- Little Allen T1.prj (project) ---

Proj Title=Little Allen T1 Base Level Engineering
Current Plan=p01
Default Exp/Contr=0.3,0.1
English Units
Geom File=g01
Flow File=f01
Plan File=p01
Y Axis Title=Elevation
X Axis Title(PF)=Main Channel Distance
X Axis Title(XS)=Station
BEGIN DESCRIPTION:
Little Allen T1
END DESCRIPTION:
DSS Export Rating Curves= 0
DSS Export Rating Curve Sorted= 0
DSS Export Volume Flow Curves= 0
DXF OffsetX= 0
DXF OffsetY= 0
DXF ScaleX= 1
DXF ScaleY= 10

--- Little Allen T1.p01 (plan) ---

Plan Title=Multiple Run
Short Identifier=Multiple
Geom File=g01
Flow File=f01
Subcritical Flow
K Sum by GR= 0
Std Step Tol= 0.01
Critical Tol= 0.01
Num of Std Step Trials= 20
Max Error Tol= 0.3
Flow Tol Ratio= 0.001
Split Flow NTrial= 30
Split Flow Tol= 0.02
Split Flow Ratio= 0.02
Log Output Level= 0
Friction Slope Method= 1
Unsteady Friction Slope Method= 2
Unsteady Bridges Friction Slope Method= 1
Parabolic Critical Depth
Global Vel Dist=  1 , 1 , 1
Global Log Level= 0
CheckData=True
Encroach Param= -1, 0, 0, 0
BEGIN DESCRIPTION:
Multiple Run
END DESCRIPTION:

--- Little Allen T1.f01 (steady flow) ---

Flow Title=Multiple
Number of Profiles=7
Profile Names=10-year,25-year,50-year,1pct_min,100-year,1pct_plu,500-year
River Rch & RM= Little Allen T1,Reach-1,7788
     285     361     418     242     482     962     638
Boundary for River Rch & Prof#=Little Allen T1,Reach-1,1
Up Type=0
Dn Type=3
Dn Slope=0.005
Boundary for River Rch & Prof#=Little Allen T1,Reach-1,2
Up Type=0
Dn Type=3
Dn Slope=0.005
Boundary for River Rch & Prof#=Little Allen T1,Reach-1,3
Up Type=0
Dn Type=3
Dn Slope=0.005
Boundary for River Rch & Prof#=Little Allen T1,Reach-1,4
Up Type=0
Dn Type=3
Dn Slope=0.005
Boundary for River Rch & Prof#=Little Allen T1,Reach-1,5
Up Type=0
Dn Type=3
Dn Slope=0.005
Boundary for River Rch & Prof#=Little Allen T1,Reach-1,6
Up Type=0
Dn Type=3
Dn Slope=0.005
Boundary for River Rch & Prof#=Little Allen T1,Reach-1,7
Up Type=0
Dn Type=3
Dn Slope=0.005

--- Little Allen T1.g01 (geometry) ---

Geom Title=Existing Conditions
Program Version=4.10

River Reach=Little Allen T1 ,Reach-1
Reach XY= 30
        2735326.        6939561.      2735282.87      6939511.12
       2735374.8       6939350.5      2735426.43      6938876.18
      2735333.53      6938511.01      2735426.44      6938181.03
      2735282.98      6938061.21       2735418.9        6937911.
      2735335.29      6937704.33      2735574.95      6937450.57
      2735626.48      6936835.97      2735533.84       6936714.4
      2735572.84      6936612.18      2735387.11       6936521.1
       2735425.2       6936421.7      2735346.39      6936280.84
      2734743.04      6935677.24      2734636.48      6935671.51
      2734575.72      6935390.82       2734620.6      6935208.03
      2734489.63        6935175.       2734335.3      6934967.67
      2734317.88      6934804.95      2734039.21      6934524.12
      2733877.64      6934557.86       2733515.3       6934311.7
      2733310.52      6934461.11      2733220.36      6934312.61
      2733025.88      6934404.13        2732976.        6934361.

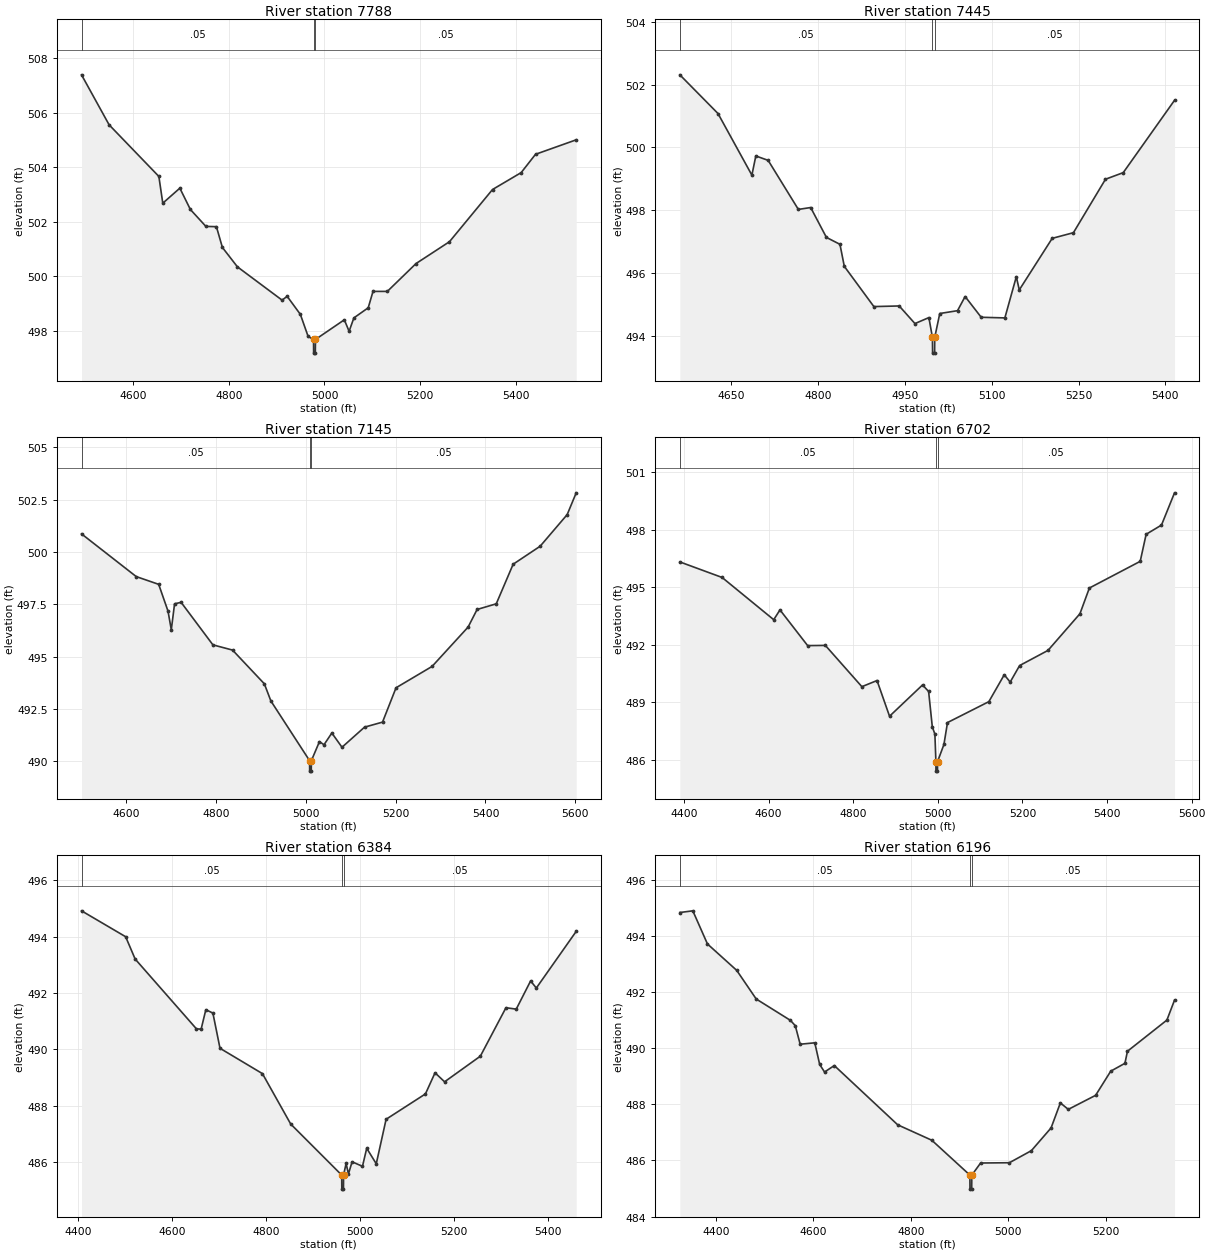
Type RM Length L Ch R = 1 ,7788    ,343,343,343
BEGIN DESCRIPTION:
Little Allen T1 11.0
END DESCRIPTION:
XS GIS Cut Line= 3
      2735775.97      6939660.98      2735327.62      6939421.71
      2734800.94      6939425.92
#Sta/Elev= 30
  4491.8  507.38  4549.5  505.55  4653.6  503.66  4661.8  502.68  4697.5  503.23
  4719.5  502.45    4752  501.83    4774  501.82  4786.5  501.06  4817.9  500.35
  4911.4  499.13    4922  499.27  4949.6  498.61  4965.9   497.8  4977.2  497.69
  4977.4  497.19  4980.9  497.19  4981.2  497.69  5041.6  498.41  5051.6  497.99
  5061.6  498.48  5091.6  498.85  5101.6  499.45  5131.6  499.45  5191.6  500.47
  5261.6  501.27  5351.6  503.18  5411.6   503.8  5441.6  504.47  5526.7     505
#Mann= 3 ,-1 , 0
  4491.8     .05       0  4977.2     .04       0  4981.2     .05       0
Bank Sta=4977.2,4981.2
XS Rating Curve= 0 ,0
Exp/Cntr=0.3,0.1

Type RM Length L Ch R = 1 ,7445    ,300,300,300
BEGIN DESCRIPTION:
Mapping XS dbefe0bd
END DESCRIPTION:
XS GIS Cut Line= 3
       2735752.3      6939314.79      2735387.76      6939092.59
      2734969.34       6939182.5
#Sta/Elev= 30
    4561  502.31  4626.9  501.08  4685.5  499.12  4692.3  499.73  4713.6  499.59
  4765.8  498.03  4787.1  498.09  4814.3  497.14  4837.7  496.92  4845.2  496.22
  4896.3  494.94  4940.1  494.96  4967.3   494.4  4991.4  494.59  4997.5  493.96
  4997.8  493.46  5001.3  493.46  5001.5  493.96  5010.2  494.72  5040.9  494.81
    5054  495.26  5081.8   494.6  5122.7  494.58  5142.5  495.89  5147.6  495.47
  5204.5  497.11  5241.2  497.29  5296.6  498.99  5327.3   499.2  5415.9   501.5
#Mann= 3 ,-1 , 0
    4561     .05       0  4997.5     .04       0  5001.5     .05       0
Bank Sta=4997.5,5001.5
XS Rating Curve= 0 ,0
Exp/Cntr=0.3,0.1

Type RM Length L Ch R = 1 ,7145    ,443,443,443
BEGIN DESCRIPTION:
Little Allen T1 10.0
END DESCRIPTION:
XS GIS Cut Line= 3
      2735826.02      6939111.01        2735426.        6938811.
        2734826.        6938861.
#Sta/Elev= 30
  4500.1  500.87    4622  498.83    4672  498.46  4692.8  497.18  4700.1  496.29
  4707.4  497.53    4722   497.6  4792.8  495.57  4836.6  495.32  4907.4  493.71
    4922  492.89  5008.2  490.04  5008.4  489.54  5011.9  489.54  5012.2  490.04
  5030.2  490.95  5040.3   490.8  5057.8  491.36  5080.4  490.68  5130.6  491.64
  5170.7  491.88  5200.8  493.52  5281.1  494.54  5361.4  496.42  5381.4  497.26
  5424.1  497.53  5461.7  499.42  5521.9  500.28  5582.1  501.79  5602.2  502.83
#Mann= 3 ,-1 , 0
  4500.1     .05       0  5008.2     .04       0  5012.2     .05       0
Bank Sta=5008.2,5012.2
XS Rating Curve= 0 ,0
Exp/Cntr=0.3,0.1

Type RM Length L Ch R = 1 ,6702    ,318,318,318
BEGIN DESCRIPTION:
Little Allen T1 9.0
END DESCRIPTION:
XS GIS Cut Line= 3
      2735876.02      6938761.01        2735376.        6938411.
      2734875.97      6938661.01
#Sta/Elev= 30
  4390.1  496.32    4490  495.51    4612  493.31  4626.8  493.82  4692.2  491.96
  4734.1  491.97  4820.4  489.82  4856.2  490.14  4885.8  488.28  4963.8  489.91
  4978.2  489.57  4986.9  487.73    4993  487.35  4995.4  485.92  4995.6  485.42
  4999.1  485.42  4999.4  485.92  5014.4  486.81  5022.8  487.95  5120.6  489.04
    5157  490.44    5171  490.06  5193.3  490.92  5260.4  491.71  5335.9  493.62
  5358.2  494.96  5478.4  496.35  5492.4  497.76  5528.7  498.24  5559.5  499.92
#Mann= 3 ,-1 , 0
  4390.1     .05       0  4995.4     .05       0  4999.4     .05       0
Bank Sta=4995.4,4999.4
XS Rating Curve= 0 ,0
Exp/Cntr=0.3,0.1

Type RM Length L Ch R = 1 ,6384    ,188,188,188
BEGIN DESCRIPTION:
Mapping XS a9f0696c
END DESCRIPTION:
XS GIS Cut Line= 5
       2735979.6      6938165.07      2735504.36      6938132.52
      2735387.18      6938123.84      2735250.46      6938165.07
      2734940.52      6938110.88
#Sta/Elev= 30
    4408  494.92  4501.8     494  4521.9  493.21  4652.2  490.73  4662.2  490.72
  4672.2  491.41  4687.2  491.29  4702.3  490.04  4792.5  489.14  4852.6  487.35
  4960.9  485.54  4961.2  485.04  4964.7  485.04  4964.9  485.54  4970.3  485.95
  4975.3  485.58    4983  486.01  5005.1  485.85  5014.1  486.49  5034.4  485.94
  5055.3  487.52  5138.9  488.42  5159.3  489.17  5179.6  488.85  5255.6  489.76
    5310  491.48  5331.9  491.43  5362.4  492.43  5374.6  492.18  5459.3  494.19
#Mann= 3 ,-1 , 0
    4408     .05       0  4960.9     .05       0  4964.9     .05       0
Bank Sta=4960.9,4964.9
XS Rating Curve= 0 ,0
Exp/Cntr=0.3,0.1

Type RM Length L Ch R = 1 ,6196    ,676,676,676
BEGIN DESCRIPTION:
Mapping XS 103739d5
END DESCRIPTION:
XS GIS Cut Line= 4
      2735992.64      6938013.16      2735469.64       6938017.5
       2735319.9       6938017.5      2734989.47      6937931.11
#Sta/Elev= 30
  4326.4  494.83    4353  494.89    4383  493.71    4443  492.77    4483  491.75
  4553.1  490.99  4563.1   490.8  4573.1  490.14  4603.1  490.19  4613.1  489.42
  4623.1  489.15  4643.1  489.38  4773.1  487.27  4843.1  486.72  4921.1  485.48
  4921.3  484.98  4924.8  484.98  4925.1  485.48  4943.1  485.91  5002.1  485.92
  5047.2  486.35  5087.6  487.16  5106.6  488.05  5122.9  487.82  5178.9  488.32
  5209.9  489.18    5239  489.46  5244.2  489.89  5325.1     491  5340.7  491.71
#Mann= 3 ,-1 , 0
  4326.4     .05       0  4921.1     .05       0  4925.1     .05       0
Bank Sta=4921.1,4925.1
XS Rating Curve= 0 ,0
Exp/Cntr=0.3,0.1

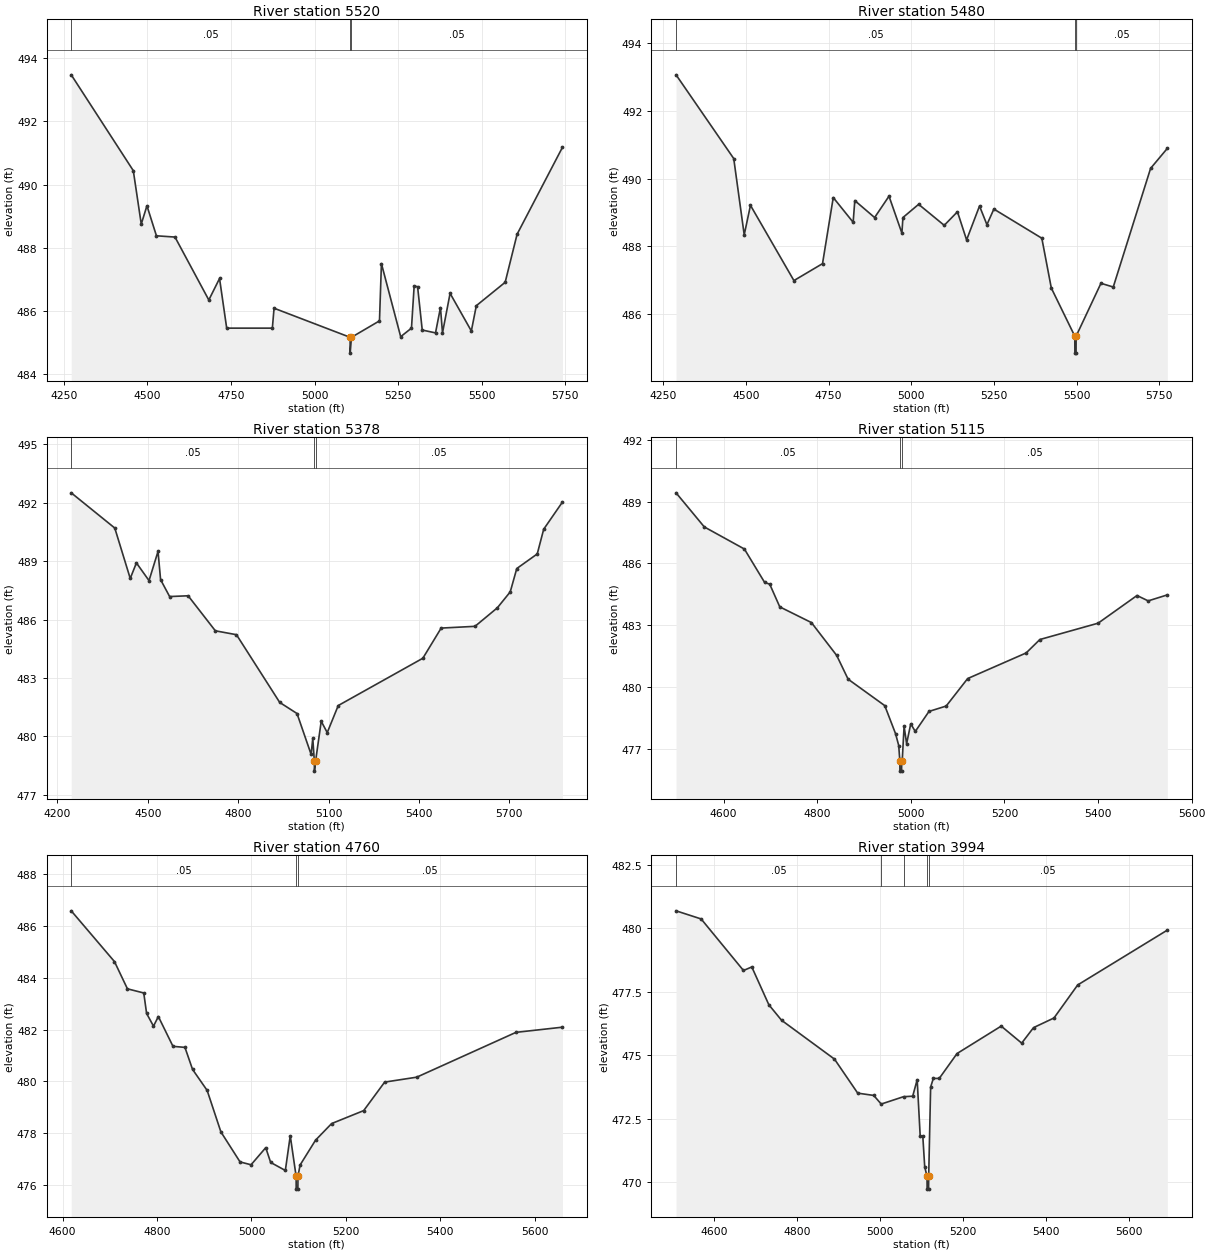
Type RM Length L Ch R = 1 ,5520    ,40,40,40
BEGIN DESCRIPTION:
Mapping XS 69c40702
END DESCRIPTION:
XS GIS Cut Line= 6
      2735957.94      6937917.68      2735586.83      6937841.72
      2735552.11      6937546.58       2735443.6      6937496.67
      2735315.56      6937676.79      2734990.48      6937904.35
#Sta/Elev= 30
  4272.1  493.47  4457.8  490.44  4481.6  488.75  4498.6  489.33    4527  488.38
  4582.5  488.34  4683.7  486.35  4715.8  487.03  4737.2  485.46  4873.8  485.46
  4878.9  486.09  5106.4  485.17  5106.6  484.67  5110.4  485.17  5194.3  485.69
  5200.1   487.5  5257.7  485.19    5290  485.46    5298  486.79  5308.3  486.77
  5322.2   485.4  5361.9  485.31  5376.7  486.11  5382.8  485.31  5405.5  486.56
  5469.1  485.37    5484  486.17  5570.3  486.91    5606  488.43  5741.8  491.18
#Mann= 3 ,-1 , 0
  4272.1     .05       0  5106.4     .04       0  5110.4     .05       0
Bank Sta=5106.4,5110.4
XS Rating Curve= 0 ,0
Exp/Cntr=0.3,0.1

Type RM Length L Ch R = 1 ,5480    ,102,102,102
BEGIN DESCRIPTION:
Mapping XS 888a042c
END DESCRIPTION:
XS GIS Cut Line= 6
      2735957.91      6937891.63      2735606.36      6937820.02
      2735595.51      6937540.07      2735497.85      6937464.12
       2735341.6      6937479.31      2734985.69      6937880.79
#Sta/Elev= 30
    4289  493.06  4463.4  490.59  4495.1  488.34    4514  489.21  4645.4  486.99
  4731.9  487.49  4764.3  489.44  4824.5  488.71  4829.5  489.35  4889.4  488.85
  4932.9  489.48  4971.9  488.39    4975  488.85  5022.5  489.24  5099.9  488.62
  5139.9  489.02  5167.5  488.19  5206.6  489.19    5229  488.64    5250   489.1
    5395  488.24  5423.7  486.77  5494.7  485.35    5495  484.85  5498.5  484.85
  5498.7  485.35  5573.8  486.91    5611   486.8  5723.9   490.3  5774.5  490.89
#Mann= 3 ,-1 , 0
    4289     .05       0  5494.7     .04       0  5498.7     .05       0
Bank Sta=5494.7,5498.7
XS Rating Curve= 0 ,0
Exp/Cntr=0.3,0.1

Type RM Length L Ch R = 1 ,5378    ,263,263,263
BEGIN DESCRIPTION:
Mapping XS e050a412
END DESCRIPTION:
XS GIS Cut Line= 6
      2735947.08      6937861.25      2735625.89      6937789.64
      2735645.42      6937466.29      2735517.38      6937368.63
       2735319.9       6937414.2      2734915.66      6937816.91
#Sta/Elev= 30
  4246.2  492.51  4390.7   490.7    4442  488.11  4462.5  488.91  4504.3     488
  4534.2   489.5  4542.7  488.05  4572.7  487.18  4634.1  487.22  4724.4  485.42
  4794.5  485.22    4938  481.74  4995.4  481.17  5042.2  479.07  5047.7   479.9
  5052.9  478.71  5053.2  478.21  5056.9  478.71  5075.7  480.77  5095.7  480.19
  5132.2  481.58  5412.9  484.01  5473.7  485.56    5586  485.65    5660   486.6
  5702.9  487.42  5724.6  488.62  5792.5  489.37  5813.9  490.64  5876.3  492.04
#Mann= 3 ,-1 , 0
  4246.2     .05       0  5052.9     .04       0  5056.9     .05       0
Bank Sta=5052.9,5056.9
XS Rating Curve= 0 ,0
Exp/Cntr=0.3,0.1

Type RM Length L Ch R = 1 ,5115    ,355,355,355
BEGIN DESCRIPTION:
Mapping XS dd31f229
END DESCRIPTION:
XS GIS Cut Line= 3
      2736042.02      6937301.66      2735592.76      6937123.69
      2735069.31      6937339.99
#Sta/Elev= 30
  4498.4  489.42  4558.7  487.77  4644.4   486.7  4687.7  485.08  4698.5     485
    4720   483.9  4787.6  483.14  4841.6  481.55    4866   480.4  4944.3  479.12
  4967.4  477.76  4974.1  477.19  4976.5  476.45  4976.7  475.95  4980.2  475.95
  4980.5  476.45  4981.6  476.45  4985.6  478.12    4991  477.28  4999.8  478.24
  5009.5  477.87  5038.8  478.84  5075.5   479.1  5121.4  480.43  5246.4  481.67
  5275.7  482.32  5400.1  483.11  5483.2  484.45  5507.1  484.19    5548  484.48
#Mann= 3 ,-1 , 0
  4498.4     .05       0  4976.5     .04       0  4980.5     .05       0
Bank Sta=4976.5,4980.5
XS Rating Curve= 0 ,0
Exp/Cntr=0.3,0.1

Type RM Length L Ch R = 1 ,4760    ,766,766,766
BEGIN DESCRIPTION:
Mapping XS bd4e1b83
END DESCRIPTION:
XS GIS Cut Line= 3
      2735994.66      6936916.22      2735605.78      6936815.53
      2734991.23      6936989.13
#Sta/Elev= 30
  4618.3  486.58  4709.9  484.62  4737.3  483.57  4771.9  483.41  4777.9  482.62
  4792.5  482.13  4802.8   482.5  4833.8  481.35  4859.1  481.31  4875.2  480.46
  4906.1  479.65  4935.2  478.05  4975.8  476.89  4999.1  476.78  5030.2  477.44
  5040.6  476.87  5071.7  476.56  5082.1   477.9  5094.5  476.34  5094.7  475.84
  5098.2  475.84  5098.5  476.34  5102.9  476.77  5135.7  477.73  5169.7  478.37
  5237.6  478.87    5282  479.97  5349.9  480.16  5560.1  481.89  5658.6  482.09
#Mann= 3 ,-1 , 0
  4618.3     .05       0  5094.5     .04       0  5098.5     .05       0
Bank Sta=5094.5,5098.5
XS Rating Curve= 0 ,0
Exp/Cntr=0.3,0.1

Type RM Length L Ch R = 1 ,3994    ,383,383,383
BEGIN DESCRIPTION:
Mapping XS 4ccaa15d
END DESCRIPTION:
XS GIS Cut Line= 3
      2735845.34      6936197.48       2735265.5      6936319.01
      2734883.55      6936773.88
#Sta/Elev= 30
  4507.2  480.69  4567.8  480.37    4670  478.34  4690.1  478.48  4731.3  476.99
    4762  476.38  4889.8  474.85  4945.9  473.51  4984.6  473.42  5002.6  473.08
  5056.5  473.37  5078.7  473.39  5089.5  474.04  5096.8  471.81  5103.1  471.81
  5107.7  470.61  5113.3  470.23  5113.5  469.73    5117  469.73  5117.3  470.23
    5122  473.75  5128.5  474.09  5142.8  474.09  5185.8  475.07  5292.4  476.15
  5341.9  475.48  5370.5  476.09  5419.9  476.47  5477.1  477.77  5693.6  479.93
#Mann= 5 ,-1 , 0
  4507.2     .05       0  5002.6     .12       0  5056.5     .05       0
  5113.3     .04       0  5117.3     .05       0
Bank Sta=5113.3,5117.3
XS Rating Curve= 0 ,0
Exp/Cntr=0.3,0.1

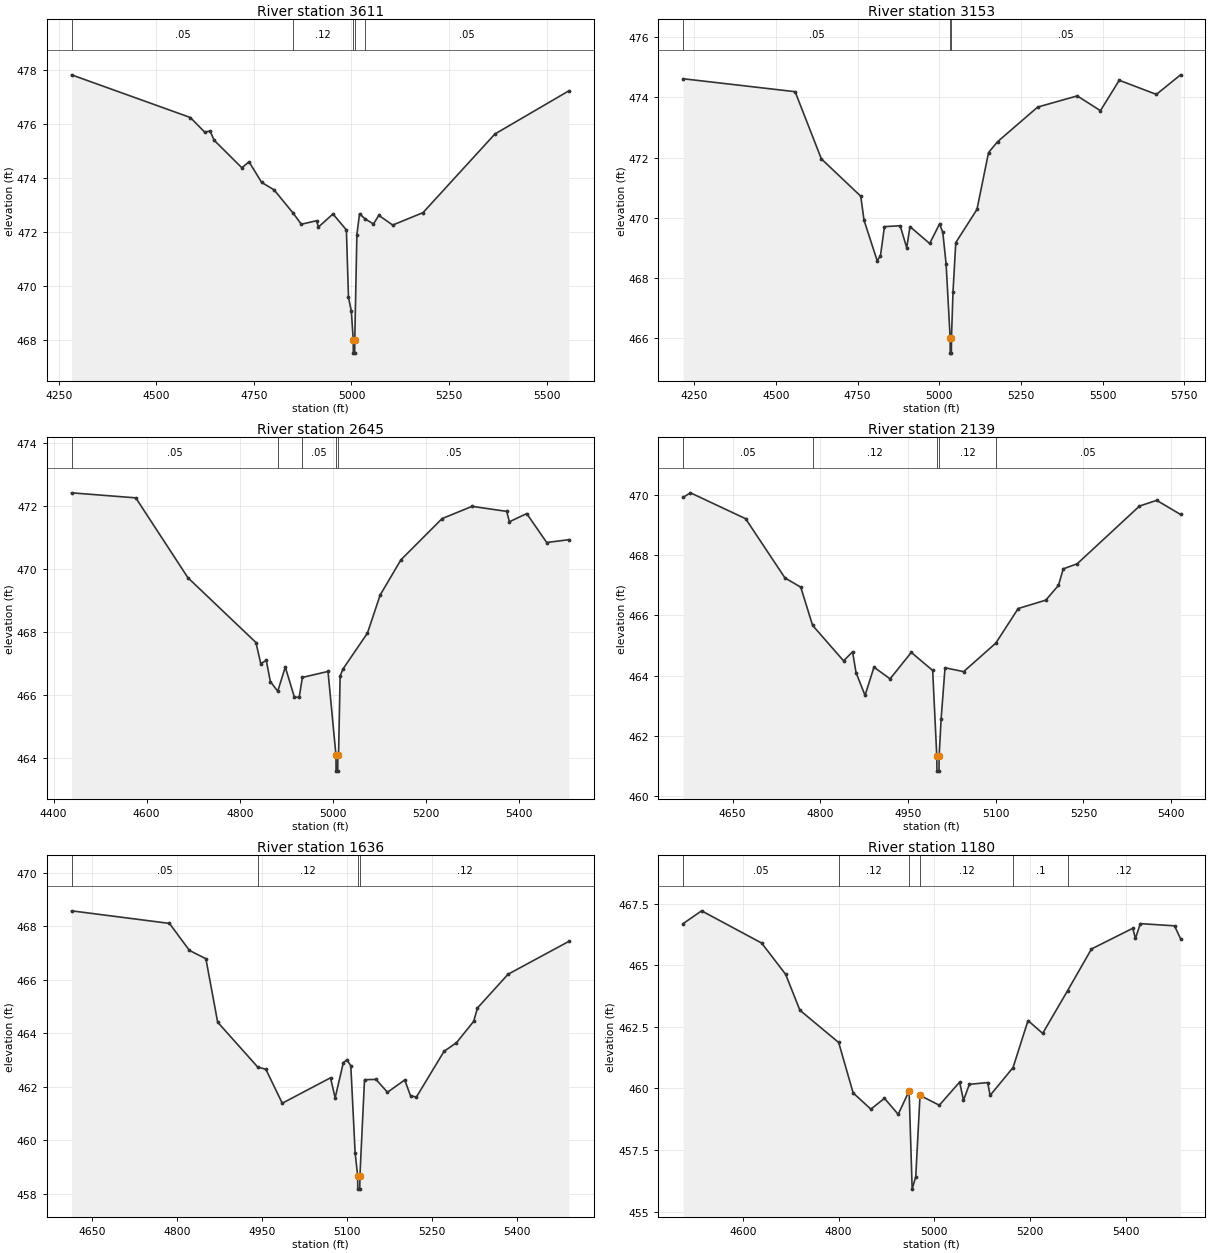
Type RM Length L Ch R = 1 ,3611    ,458,458,458
BEGIN DESCRIPTION:
Mapping XS 4232ac35
END DESCRIPTION:
XS GIS Cut Line= 3
      2735775.87      6935926.65      2735084.95      6936048.17
      2734693.67      6936467.15
#Sta/Elev= 30
  4282.6  477.81  4587.1  476.23  4623.9  475.69  4637.8  475.73    4648  475.39
  4719.1  474.37  4737.5  474.59  4769.8  473.83  4801.9  473.55  4851.2  472.68
  4871.4  472.28  4910.4  472.41  4915.5  472.18  4952.6  472.66    4987  472.07
  4992.4  469.57  4999.7  469.06  5004.5  468.01  5004.8  467.51  5008.3  467.51
  5008.5  468.01  5013.9  471.89  5020.7  472.67  5034.7  472.48  5056.4  472.29
  5070.1  472.61  5105.7  472.25  5183.4  472.71  5367.6  475.62  5557.4  477.22
#Mann= 5 ,-1 , 0
  4282.6     .05       0  4851.2     .12       0  5004.5     .07       0
  5008.5     .12       0  5034.7     .05       0
Bank Sta=5004.5,5008.5
XS Rating Curve= 0 ,0
Exp/Cntr=0.3,0.1

Type RM Length L Ch R = 1 ,3153    ,508,508,508
BEGIN DESCRIPTION:
Mapping XS 5ffdd597
END DESCRIPTION:
XS GIS Cut Line= 3
      2735557.13      6935666.23       2734741.2      6935746.09
      2734324.55      6936312.04
#Sta/Elev= 30
  4215.7  474.62  4558.5  474.19  4638.8  471.96  4759.4  470.72  4769.5  469.92
  4809.7  468.58  4819.7  468.74    4832  469.71    4880  469.74  4900.1  469.01
  4910.1  469.71  4970.4  469.15  5000.6   469.8  5010.6  469.52  5020.7  468.47
  5033.1  466.01  5033.3  465.51  5036.8  465.51  5037.1  466.01  5041.8  467.55
  5050.3  469.18  5115.1  470.28  5150.6  472.17  5178.2  472.53    5301  473.68
  5422.1  474.05  5493.1  473.56  5550.7  474.57  5664.3   474.1  5738.3  474.75
#Mann= 3 ,-1 , 0
  4215.7     .05       0  5033.1     .04       0  5037.1     .05       0
Bank Sta=5033.1,5037.1
XS Rating Curve= 0 ,0
Exp/Cntr=0.3,0.1

Type RM Length L Ch R = 1 ,2645    ,506,506,506
BEGIN DESCRIPTION:
Mapping XS 27fe3828
END DESCRIPTION:
XS GIS Cut Line= 3
      2735119.67      6935253.03      2734564.12      6935395.39
       2734314.1       6935822.5
#Sta/Elev= 30
  4438.6  472.43  4576.6  472.27  4688.6  469.73  4834.7  467.67    4845     467
  4856.9   467.1  4865.6  466.43  4881.5  466.12  4897.7  466.89  4917.3  465.93
  4927.6  465.93  4934.4  466.56  4989.5  466.75  5006.6  464.08  5006.8  463.58
  5010.3  463.58  5010.6  464.08  5012.1  464.08  5015.5   466.6  5021.3  466.82
  5074.2  467.97  5101.5  469.18  5146.1   470.3  5234.5  471.61  5298.9     472
  5373.3  471.84  5379.1  471.51  5416.3  471.77  5459.2  470.85    5507  470.94
#Mann= 5 ,-1 , 0
  4438.6     .05       0  4881.5     .12       0  4934.4     .05       0
  5006.6     .04       0  5010.6     .05       0
Bank Sta=5006.6,5010.6
XS Rating Curve= 0 ,0
Exp/Cntr=0.3,0.1

Type RM Length L Ch R = 1 ,2139    ,503,503,503
BEGIN DESCRIPTION:
Mapping XS d6404cb2
END DESCRIPTION:
XS GIS Cut Line= 3
      2734796.74       6934832.9      2734421.75      6935065.53
      2734265.52      6935443.97
#Sta/Elev= 30
  4565.3  469.93  4577.9  470.08  4672.1  469.22  4739.4  467.25  4766.5  466.94
  4786.7  465.67  4839.7  464.49  4855.1  464.79    4861   464.1  4876.4  463.34
  4891.7  464.28  4919.2  463.89  4955.5  464.77  4992.1  464.17  4999.1  461.32
  4999.4  460.82  5002.9  460.82  5003.1  461.32  5006.6  462.57  5013.2  464.26
    5045  464.13  5100.1  465.08  5138.3  466.23  5185.6  466.51  5207.2     467
  5215.4  467.55  5239.3  467.72  5345.8  469.64  5375.2  469.83    5416  469.36
#Mann= 5 ,-1 , 0
  4565.3     .05       0  4786.7     .12       0  4999.1     .07       0
  5003.1     .12       0  5100.1     .05       0
Bank Sta=4999.1,5003.1
XS Rating Curve= 0 ,0
Exp/Cntr=0.3,0.1

Type RM Length L Ch R = 1 ,1636    ,456,456,456
BEGIN DESCRIPTION:
Mapping XS 89aacc74
END DESCRIPTION:
XS GIS Cut Line= 3
      2734498.11      6934440.56      2734098.84      6934746.09
      2734033.01      6935116.83
#Sta/Elev= 30
    4613  468.58  4786.1  468.11  4821.4   467.1  4850.5  466.79  4871.3  464.42
  4942.2  462.74  4956.5  462.66  4985.5  461.39  5070.8  462.34    5079  461.59
  5093.5  462.91  5099.8  463.01  5106.7  462.79  5114.3  459.54  5118.8  458.68
    5119  458.18  5122.5  458.18  5122.8  458.68  5130.9  462.27  5151.2  462.28
  5171.5   461.8    5202  462.26  5212.2  461.67  5222.6  461.62  5271.5  463.33
  5293.4  463.65  5323.9  464.45  5330.6  464.95  5384.6  466.21  5492.3  467.44
#Mann= 4 ,-1 , 0
    4613     .05       0  4942.2     .12       0  5118.8     .07       0
  5122.8     .12       0
Bank Sta=5118.8,5122.8
XS Rating Curve= 0 ,0
Exp/Cntr=0.3,0.1

Type RM Length L Ch R = 1 ,1180    ,387,387,387
BEGIN DESCRIPTION:
Mapping XS 3ab272ee
END DESCRIPTION:
XS GIS Cut Line= 3
      2734289.81      6934263.45      2733834.95      6934513.45
       2733730.9       6935023.3
#Sta/Elev= 30
  4475.2   466.7  4513.8  467.22  4639.3  465.91  4689.4  464.64  4719.2  463.18
  4800.2  461.87  4830.5  459.82  4867.5  459.16  4895.9   459.6  4924.6  458.95
  4947.4   459.9  4953.8  455.91  4961.3  456.42  4970.2  459.72  5010.5  459.32
    5053  460.26    5061  459.52  5073.4  460.17  5111.6  460.24  5116.7  459.72
  5164.6  460.85  5195.9  462.76  5226.5  462.24  5278.7  463.98  5328.5  465.67
  5414.7  466.51  5420.4   466.1  5430.6   466.7    5502  466.61  5514.6  466.09
#Mann= 6 ,-1 , 0
  4475.2     .05       0  4800.2     .12       0  4947.4     .07       0
  4970.2     .12       0  5164.6      .1       0  5278.7     .12       0
Bank Sta=4947.4,4970.2
XS Rating Curve= 0 ,0
Exp/Cntr=0.3,0.1

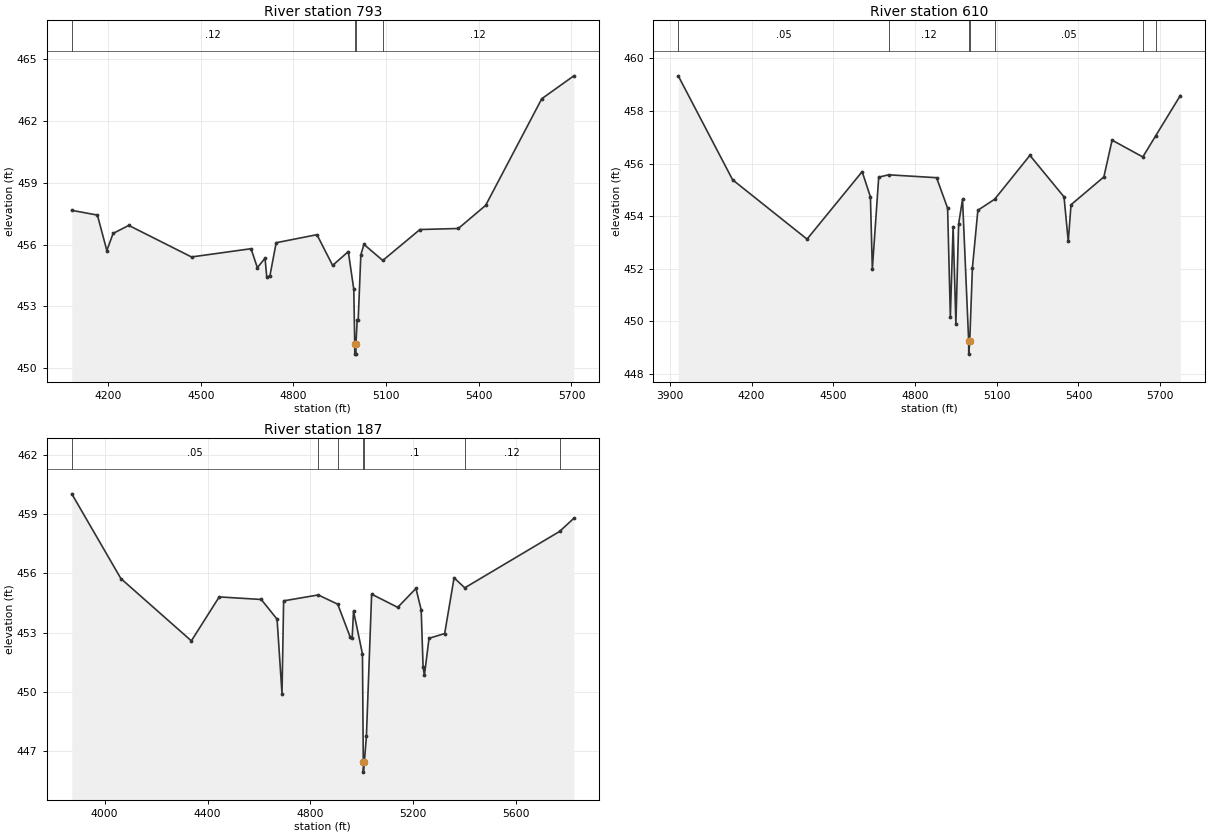
Type RM Length L Ch R = 1 ,793     ,183,183,183
BEGIN DESCRIPTION:
Mapping XS 59d7b896
END DESCRIPTION:
XS GIS Cut Line= 4
      2733678.71      6933409.24      2733518.98      6934322.48
      2733470.37       6934732.2      2733598.05      6934987.57
#Sta/Elev= 30
  4082.5  457.66  4165.5  457.43    4196  455.71  4216.3  456.54    4267  456.93
  4470.1   455.4  4662.9   455.8  4683.2  454.88  4708.1  455.34  4713.7  454.43
  4723.8  454.48  4744.1  456.09  4876.1  456.48  4926.9  454.99  4977.6  455.66
  4995.4  453.83  4998.4  451.19  4998.7  450.69  5002.2  450.69  5002.4  451.19
  5006.3  452.33  5009.6  452.33  5018.2   455.5  5028.2  456.01  5089.2  455.23
  5209.5  456.73  5333.7  456.78  5422.2   457.9  5603.9  463.07  5707.7  464.18
#Mann= 4 ,-1 , 0
  4082.5     .12       0  4998.4     .07       0  5002.4     .12       0
  5089.2     .12       0
Bank Sta=4998.4,5002.4
XS Rating Curve= 0 ,0
Exp/Cntr=0.3,0.1

Type RM Length L Ch R = 1 ,610     ,423,423,423
BEGIN DESCRIPTION:
Mapping XS dc6c852c
END DESCRIPTION:
XS GIS Cut Line= 3
      2733539.81      6933353.73      2733376.62      6934412.76
      2733296.76      6935180.08
#Sta/Elev= 30
  3930.9  459.34  4130.5  455.38  4403.7  453.12    4606  455.69  4636.4  454.73
  4643.4  451.97  4666.8  455.48  4703.1  455.57  4879.2  455.46  4919.7   454.3
  4929.8  450.16  4939.9   453.6  4950.1   449.9  4960.2   453.7  4974.5  454.64
    4997  449.24  4997.3  448.74    5001  449.24  5010.7  452.02  5030.8  454.22
  5092.4  454.64  5221.8  456.31    5347  454.73  5362.6  453.03  5372.7  454.43
  5493.3  455.49  5523.5  456.89  5636.2  456.25  5683.2  457.05  5773.9  458.59
#Mann= 7 ,-1 , 0
  3930.9     .05       0  4703.1     .12       0    4997     .07       0
    5001     .12       0  5092.4     .05       0  5636.2     .12       0
  5683.2      .1       0
Bank Sta=4997,5001
XS Rating Curve= 0 ,0
Exp/Cntr=0.3,0.1

Type RM Length L Ch R = 1 ,187     ,0,0,0
BEGIN DESCRIPTION:
Little Allen T1 1.0
END DESCRIPTION:
XS GIS Cut Line= 3
      2733508.58      6933291.18      2733130.09      6934350.26
      2733268.96      6935166.15
#Sta/Elev= 30
  3872.2  460.04  4063.2  455.74  4337.2  452.58  4445.5  454.81    4609  454.68
  4670.5  453.68  4689.7   449.9    4696  454.61  4830.7  454.91  4906.4  454.44
  4955.2  452.76  4962.5  452.72  4967.8  454.09  5002.5  451.92  5005.8  446.42
    5006  445.92  5009.8  446.42  5017.9  447.74  5038.2  454.95  5139.6  454.28
  5210.6  455.24  5230.9  454.15  5238.3  451.26  5243.4  450.83  5261.4  452.71
  5322.2  452.95  5358.8  455.78  5400.3  455.27  5768.9  458.13  5824.5   458.8
#Mann= 7 ,-1 , 0
  3872.2     .05       0  4830.7     .12       0  4906.4      .1       0
  5005.8     .07       0  5009.8      .1       0  5400.3     .12       0
  5768.9      .1       0
Bank Sta=5005.8,5009.8
XS Rating Curve= 0 ,0
Exp/Cntr=0.3,0.1

Chan Stop Cuts=-1
Use User Specified Reach Order=0
Composite Channel Slope=5