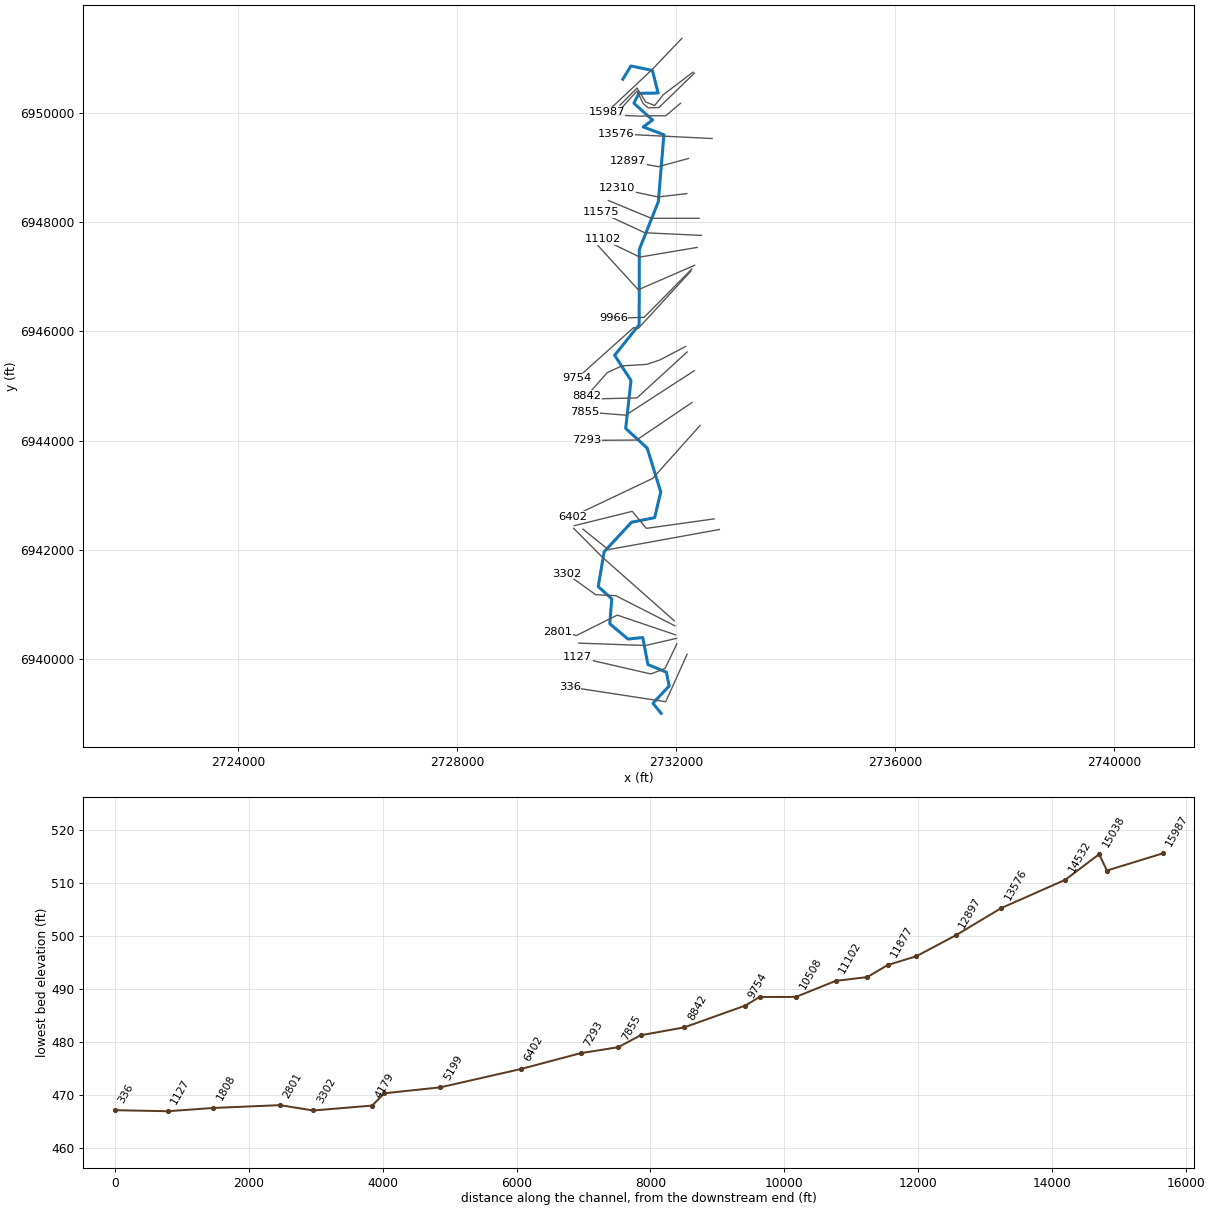
--- Little Allen T2.prj (project) ---

Proj Title=Little Allen T2 Base Level Engineering
Current Plan=p01
Default Exp/Contr=0.3,0.1
English Units
Geom File=g01
Flow File=f01
Plan File=p01
Y Axis Title=Elevation
X Axis Title(PF)=Main Channel Distance
X Axis Title(XS)=Station
BEGIN DESCRIPTION:
Little Allen T2
END DESCRIPTION:
DSS Export Rating Curves= 0
DSS Export Rating Curve Sorted= 0
DSS Export Volume Flow Curves= 0
DXF OffsetX= 0
DXF OffsetY= 0
DXF ScaleX= 1
DXF ScaleY= 10

--- Little Allen T2.p01 (plan) ---

Plan Title=Multiple Run
Short Identifier=Multiple
Geom File=g01
Flow File=f01
Subcritical Flow
K Sum by GR= 0
Std Step Tol= 0.01
Critical Tol= 0.01
Num of Std Step Trials= 20
Max Error Tol= 0.3
Flow Tol Ratio= 0.001
Split Flow NTrial= 30
Split Flow Tol= 0.02
Split Flow Ratio= 0.02
Log Output Level= 0
Friction Slope Method= 1
Unsteady Friction Slope Method= 2
Unsteady Bridges Friction Slope Method= 1
Parabolic Critical Depth
Global Vel Dist=  1 , 1 , 1
Global Log Level= 0
CheckData=True
Encroach Param= -1, 0, 0, 0
BEGIN DESCRIPTION:
Multiple Run
END DESCRIPTION:

--- Little Allen T2.f01 (steady flow) ---

Flow Title=Multiple
Program Version=4.10
Number of Profiles= 7
Profile Names=10-year,25-year,50-year,1pct_min,100-year,1pct_plu,500-year
River Rch & RM=Little Allen T2,Reach-1         ,15987
     396     509     597     348     694    1384     934
River Rch & RM=Little Allen T2,Reach-1         ,9754
     655     869    1040     617    1231    2457    1724
River Rch & RM=Little Allen T2,Reach-1         ,6402
    1129    1542    1882    1136    2266    4521    3284
River Rch & RM=Little Allen T2,Reach-1         ,2801
    1207    1648    2009    1211    2415    4819    3492
Boundary for River Rch & Prof#=Little Allen T2,Reach-1         , 1
Up Type= 0
Dn Type= 3
Dn Slope=0.005
Boundary for River Rch & Prof#=Little Allen T2,Reach-1         , 2
Up Type= 0
Dn Type= 3
Dn Slope=0.005
Boundary for River Rch & Prof#=Little Allen T2,Reach-1         , 3
Up Type= 0
Dn Type= 3
Dn Slope=0.005
Boundary for River Rch & Prof#=Little Allen T2,Reach-1         , 4
Up Type= 0
Dn Type= 3
Dn Slope=0.005
Boundary for River Rch & Prof#=Little Allen T2,Reach-1         , 5
Up Type= 0
Dn Type= 3
Dn Slope=0.005
Boundary for River Rch & Prof#=Little Allen T2,Reach-1         , 6
Up Type= 0
Dn Type= 3
Dn Slope=0.005
Boundary for River Rch & Prof#=Little Allen T2,Reach-1         , 7
Up Type= 0
Dn Type= 3
Dn Slope=0.005
DSS Import GetInterval= 0
DSS Import GetPeak= 0
DSS Import FillOption= 0

--- Little Allen T2.g01 (geometry) ---

Geom Title=Existing Conditions
Program Version=4.10

River Reach=Little Allen T2 ,Reach-1
Reach XY= 30
        2731026.        6950611.      2731172.58      6950853.24
      2731565.66      6950771.24      2731671.05      6950358.49
      2731319.31      6950352.05      2731227.08      6950171.55
      2731568.62      6949864.41      2731398.15      6949737.23
      2731775.64      6949595.84       2731674.8       6948371.5
      2731326.52      6947495.78      2731324.81      6946121.48
        2730876.        6945561.       2731174.8       6945100.5
      2731077.92      6944222.95      2731470.55      6943863.45
      2731718.46        6943061.      2731606.51      6942590.22
      2731184.49      6942507.47      2730684.14      6941967.06
      2730575.91      6941330.87      2730823.87      6941105.05
      2730786.74       6940651.3      2731119.26      6940370.13
      2731389.74      6940397.81      2731483.68      6939904.48
      2731820.54      6939763.47      2731872.97      6939512.39
      2731576.03      6939195.58        2731726.        6939011.

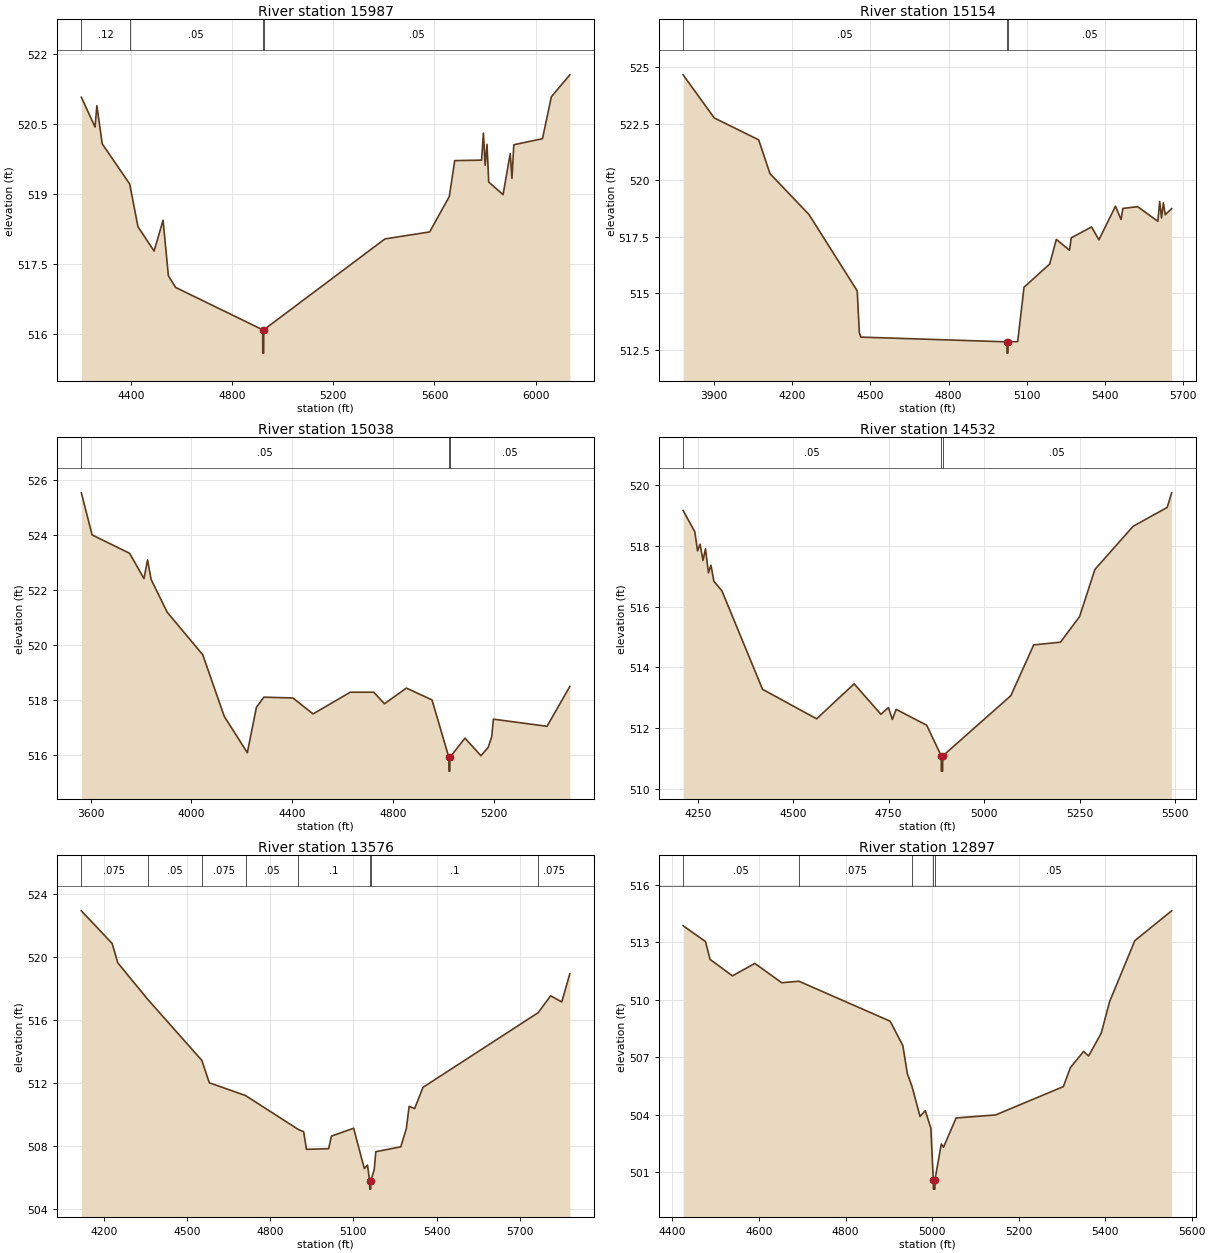
Type RM Length L Ch R = 1 ,15987   ,833,833,833
BEGIN DESCRIPTION:
Little Allen T2 24.0
END DESCRIPTION:
XS GIS Cut Line= 3
      2732105.34      6951358.39      2731550.65      6950777.67
      2730728.68      6950005.12
#Sta/Elev= 30
    4204  521.07  4258.2  520.43  4265.4  520.89  4286.5  520.07    4395  519.21
    4428  518.29  4491.5  517.77  4527.1  518.43  4548.1  517.24  4576.5  516.99
    4921  516.08  4921.3  515.58  4924.8  515.58    4925  516.08  5404.2  518.03
    5581  518.18  5658.6  518.94  5680.1  519.71  5786.1  519.72  5793.4   520.3
  5800.3  519.61  5807.6  520.06  5814.4  519.25  5871.1  518.98  5899.4  519.86
  5906.3  519.33  5913.6  520.05  6026.9  520.18  6062.1  521.08  6135.1  521.55
#Mann= 4 ,-1 , 0
    4204     .12       0    4395     .05       0    4921     .04       0
    4925     .05       0
Bank Sta=4921,4925
XS Rating Curve= 0 ,0
Exp/Cntr=0.3,0.1

Type RM Length L Ch R = 1 ,15154   ,116,116,116
BEGIN DESCRIPTION:
Mapping XS 471f2816
END DESCRIPTION:
XS GIS Cut Line= 6
      2732305.84      6950738.59      2731761.59      6950324.54
      2731607.95      6950129.23      2731443.88      6950194.33
      2731285.03      6950449.54      2730975.13      6950137.04
#Sta/Elev= 30
  3780.7  524.67  3900.2  522.76  4070.8  521.79  4114.4  520.29  4264.1  518.48
  4449.2   515.1  4457.4  513.25  4463.3  513.05  5024.4  512.84  5024.7  512.34
  5028.2  512.34  5028.4  512.84  5065.5  512.85  5089.8  515.26  5188.5  516.29
    5214  517.38  5264.4   516.9  5271.4  517.45  5349.2  517.93  5377.5  517.36
  5441.1  518.85  5462.4  518.26  5469.4  518.75    5526  518.83  5603.8  518.18
  5610.8  519.06  5617.9  518.33    5625     519  5632.1  518.47  5656.7  518.74
#Mann= 3 ,-1 , 0
  3780.7     .05       0  5024.4     .05       0  5028.4     .05       0
Bank Sta=5024.4,5028.4
XS Rating Curve= 0 ,0
Exp/Cntr=0.3,0.1

Type RM Length L Ch R = 1 ,15038   ,506,506,506
BEGIN DESCRIPTION:
Mapping XS 4d908e27
END DESCRIPTION:
XS GIS Cut Line= 6
      2732334.54      6950723.01      2731686.07      6950092.77
      2731488.15      6950087.56      2731399.61      6950163.08
      2731285.03      6950394.85      2730983.79      6950065.05
#Sta/Elev= 30
  3563.5  525.55  3606.3  524.02  3755.1  523.35    3812  522.43  3826.2  523.11
  3840.4   522.4  3903.9  521.21  4045.3  519.66  4130.6  517.42    4222   516.1
  4258.1  517.75  4287.8  518.12  4402.8  518.09  4482.8  517.51  4630.5   518.3
  4723.3   518.3  4766.2  517.88  4853.2  518.45  4954.7  518.02  5021.7  515.93
  5021.9  515.43  5025.4  515.43  5025.7  515.93  5085.5  516.63    5149  515.99
  5177.4  516.29  5191.6  516.68  5198.4  517.32  5411.1  517.06  5501.6  518.51
#Mann= 3 ,-1 , 0
  3563.5     .05       0  5021.7     .05       0  5025.7     .05       0
Bank Sta=5021.7,5025.7
XS Rating Curve= 0 ,0
Exp/Cntr=0.3,0.1

Type RM Length L Ch R = 1 ,14532   ,956,956,956
BEGIN DESCRIPTION:
Mapping XS 886f9e20
END DESCRIPTION:
XS GIS Cut Line= 5
       2732079.3       6950170.9      2731809.68      6949941.17
      2731560.12      6949943.34      2731338.76      6949934.66
       2730885.2      6949956.36
#Sta/Elev= 30
  4211.8  519.16  4242.4  518.46  4249.6  517.83  4256.2  518.05  4263.9  517.52
  4270.4   517.9  4278.1  517.11  4284.7  517.36  4292.4  516.83  4313.3  516.52
  4419.8  513.28  4561.4  512.31  4659.7  513.46  4729.7  512.46  4749.7  512.68
  4759.7  512.29  4769.7  512.62  4849.7   512.1  4887.8  511.09    4888  510.59
  4891.5  510.59  4891.8  511.09  5070.1  513.07    5130  514.74  5200.1  514.83
  5250.1  515.67  5290.2  517.22  5390.3  518.64  5479.6  519.26  5491.2  519.74
#Mann= 3 ,-1 , 0
  4211.8     .05       0  4887.8     .05       0  4891.8     .05       0
Bank Sta=4887.8,4891.8
XS Rating Curve= 0 ,0
Exp/Cntr=0.3,0.1

Type RM Length L Ch R = 1 ,13576   ,679,679,679
BEGIN DESCRIPTION:
Mapping XS 804d3cef
END DESCRIPTION:
XS GIS Cut Line= 3
      2732657.17      6949525.51      2731601.64       6949577.6
      2730896.81      6949612.32
#Sta/Elev= 30
  4118.3  522.94  4229.6  520.86  4249.6  519.64  4357.1  517.33  4553.1  513.43
    4580  512.01  4710.6   511.2  4900.5  509.05  4920.4   508.9  4930.5  507.78
  5010.6  507.82  5020.6  508.62  5100.7  509.12  5139.2  506.56  5150.7  506.78
  5158.7  505.75    5159  505.25  5162.5  505.25  5162.7  505.75  5175.1  506.51
  5180.8  507.63  5270.9  507.94  5290.9   509.1  5300.9  510.51  5320.9  510.37
    5351  511.72  5766.8  516.47  5811.5  517.54  5851.6  517.15  5880.8  518.94
#Mann= 8 ,-1 , 0
  4118.3    .075       0  4357.1     .05       0  4553.1    .075       0
  4710.6     .05       0  4900.5      .1       0  5158.7     .07       0
  5162.7      .1       0  5766.8    .075       0
Bank Sta=5158.7,5162.7
XS Rating Curve= 0 ,0
Exp/Cntr=0.3,0.1

Type RM Length L Ch R = 1 ,12897   ,587,587,587
BEGIN DESCRIPTION:
Little Allen T2 21.0
END DESCRIPTION:
XS GIS Cut Line= 3
      2732225.97      6949160.99        2731676.        6949011.
      2731125.98        6949111.
#Sta/Elev= 30
  4424.6  513.87  4476.4  513.04  4486.8  512.11  4538.6  511.25  4590.4   511.9
  4652.6  510.89  4692.2  510.97  4903.1  508.88  4932.5   507.6  4942.8  506.14
  4953.6  505.47  4972.2   503.9  4984.3   504.2  4997.2  503.29  5002.8   500.6
  5003.1   500.1  5006.6   500.1  5006.8   500.6  5021.3  502.46  5026.4  502.29
  5055.6  503.82  5147.1  503.98  5303.4  505.46  5319.9  506.46  5350.4   507.3
  5361.8  507.06  5391.1  508.26  5410.1  509.89  5468.6  513.09  5553.7  514.65
#Mann= 5 ,-1 , 0
  4424.6     .05       0  4692.2    .075       0  4953.6     .05       0
  5002.8     .05       0  5006.8     .05       0
Bank Sta=5002.8,5006.8
XS Rating Curve= 0 ,0
Exp/Cntr=0.3,0.1

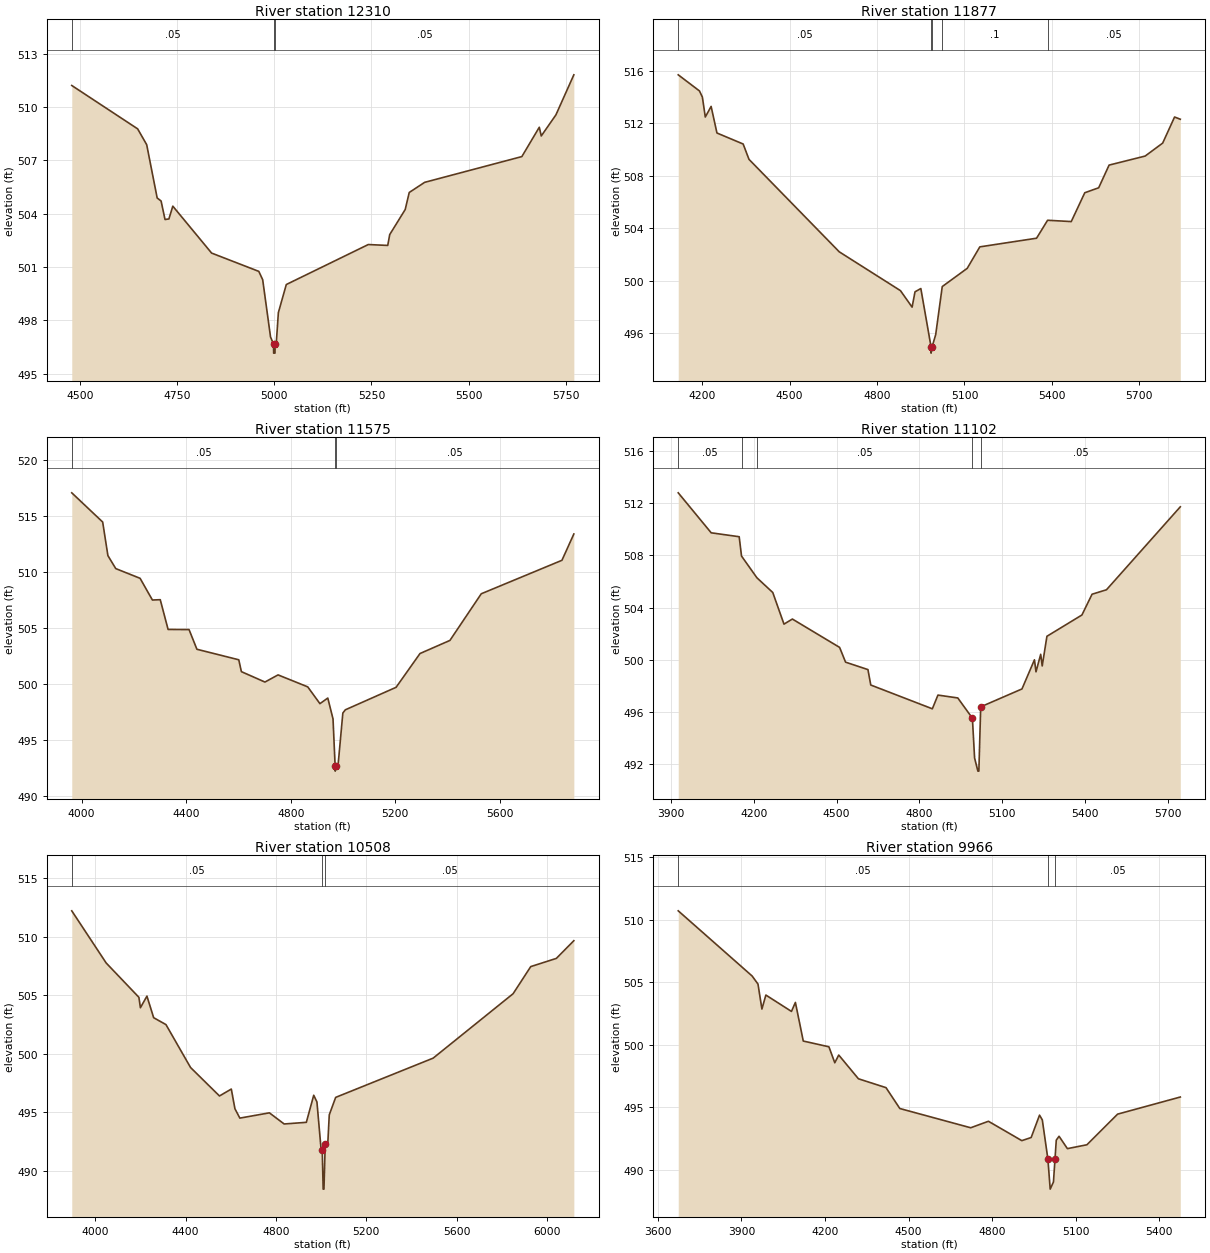
Type RM Length L Ch R = 1 ,12310   ,433,433,433
BEGIN DESCRIPTION:
Mapping XS b34e9799
END DESCRIPTION:
XS GIS Cut Line= 3
      2732194.55      6948518.05      2731671.52      6948457.28
      2730920.85      6948613.49
#Sta/Elev= 30
    4478  511.22  4647.7  508.78    4671  507.89    4698  504.89  4708.1  504.72
  4718.2  503.68  4728.2  503.71  4738.3  504.43  4838.2  501.79  4959.8  500.76
  4969.8  500.29    4990  497.07  4997.8  496.66    4998  496.16  5001.5  496.16
  5001.8  496.66  5004.6  496.66  5010.2  498.44  5030.6  500.02  5241.8  502.27
  5291.9  502.22    5297  502.83  5336.9  504.24  5347.3   505.2    5387  505.77
  5637.4  507.22  5682.3  508.87  5687.4  508.38  5725.2  509.57  5771.3  511.82
#Mann= 3 ,-1 , 0
    4478     .05       0  4997.8     .05       0  5001.8     .05       0
Bank Sta=4997.8,5001.8
XS Rating Curve= 0 ,0
Exp/Cntr=0.3,0.1

Type RM Length L Ch R = 1 ,11877   ,302,302,302
BEGIN DESCRIPTION:
Mapping XS b9613a2c
END DESCRIPTION:
XS GIS Cut Line= 3
      2732418.95      6948066.37      2731547.38      6948066.37
      2730760.08      6948392.39
#Sta/Elev= 30
  4117.4  515.71  4190.3  514.48  4200.3  514.01  4210.3  512.49  4230.3   513.3
  4250.3  511.27  4340.3  510.43  4360.3  509.26  4670.3   502.2  4880.3  499.24
  4920.3  497.98  4930.3  499.15  4950.3   499.4  4985.2  494.97  4985.4  494.47
  4989.2  494.97  5001.3  495.88  5023.8  499.55  5109.5  500.94  5152.8  502.58
  5347.6  503.24  5385.5  504.61  5466.7  504.51  5513.1  506.71  5560.9  507.09
  5596.6  508.82  5720.4  509.51  5780.6   510.5  5821.4  512.49  5841.1  512.32
#Mann= 5 ,-1 , 0
  4117.4     .05       0  4985.2     .05       0  4989.2     .05       0
  5023.8      .1       0  5385.5     .05       0
Bank Sta=4985.2,4989.2
XS Rating Curve= 0 ,0
Exp/Cntr=0.3,0.1

Type RM Length L Ch R = 1 ,11575   ,473,473,473
BEGIN DESCRIPTION:
Mapping XS b2990907
END DESCRIPTION:
XS GIS Cut Line= 3
      2732464.03      6947753.87      2731425.86      6947802.48
      2730627.26        6948174.
#Sta/Elev= 30
  3962.6  517.08  4080.8  514.47  4100.8  511.47  4130.8  510.31  4223.9  509.44
    4271   507.5    4301  507.53    4331  504.87  4411.1  504.86  4441.2   503.1
  4601.3  502.16  4611.3   501.1  4701.4  500.17  4751.5  500.81    4865  499.74
  4911.7  498.24  4941.7  498.74  4961.7  496.88  4969.7  492.71    4970  492.21
  4973.7  492.71  4981.7  492.92  4999.3   497.4  5008.8  497.69  5202.9   499.7
  5294.4  502.72  5408.8  503.89  5528.7  508.06  5837.2  511.05  5882.7   513.4
#Mann= 3 ,-1 , 0
  3962.6     .05       0  4969.7     .05       0  4973.7     .05       0
Bank Sta=4969.7,4973.7
XS Rating Curve= 0 ,0
Exp/Cntr=0.3,0.1

Type RM Length L Ch R = 1 ,11102   ,594,594,594
BEGIN DESCRIPTION:
Mapping XS 290a7bb0
END DESCRIPTION:
XS GIS Cut Line= 3
      2732383.72      6947533.96      2731335.12      6947356.88
      2730655.31      6947686.37
#Sta/Elev= 30
  3926.4  512.79  4045.8  509.73  4147.2  509.43  4155.7  507.95  4211.4  506.29
  4268.9  505.16  4309.5  502.74  4339.9  503.13    4511  500.96  4532.6  499.83
  4613.7  499.26  4623.9  498.08    4847  496.26  4867.3  497.31  4939.2  497.09
  4992.1  495.54    5000   492.5    5012  491.49  5015.5  491.49  5022.2  496.41
  5171.7  497.78  5216.9  500.01  5222.5  499.09  5239.5  500.43    5245  499.54
  5262.1  501.81  5388.9  503.44  5425.6  505.03  5477.8  505.37  5745.3  511.72
#Mann= 5 ,-1 , 0
  3926.4     .05       0  4155.7    .075       0  4211.4     .05       0
  4992.1     .03       0  5022.2     .05       0
Bank Sta=4992.1,5022.2
XS Rating Curve= 0 ,0
Exp/Cntr=0.3,0.1

Type RM Length L Ch R = 1 ,10508   ,542,542,542
BEGIN DESCRIPTION:
Mapping XS 664d1aeb
END DESCRIPTION:
XS GIS Cut Line= 3
      2732338.59      6947207.57      2731307.34      6946759.66
      2730567.77      6947572.14
#Sta/Elev= 30
  3896.1  512.21  4048.4  507.76  4193.3  504.83    4200  503.94  4228.9  504.93
  4258.7  503.09  4313.2   502.5    4422  498.84  4550.1  496.41  4602.5     497
  4618.5  495.32  4640.3  494.52  4771.1  494.97  4836.5  494.02  4934.7  494.16
  4967.4  496.47  4981.6   495.9  4999.6  491.95    5005  491.84  5009.2  488.46
  5012.7  488.46  5018.4  492.34  5029.4  492.25  5036.2   494.8  5064.6  496.29
  5496.3  499.64  5850.4  505.14  5928.2  507.45  6041.6  508.15  6119.1  509.66
#Mann= 3 ,-1 , 0
  3896.1     .05       0    5005     .04       0  5018.4     .05       0
#XS Ineff= 2 , 0
       0  4967.4  496.47               0
Permanent Ineff=
       F       F
Bank Sta=5005,5018.4
XS Rating Curve= 0 ,0
Exp/Cntr=0.3,0.1

Type RM Length L Ch R = 1 ,9966    ,212,212,212
BEGIN DESCRIPTION:
Mapping XS 59651a7b
END DESCRIPTION:
XS GIS Cut Line= 3
      2732284.18      6947137.65      2731416.13      6946256.59
      2730850.95        6946236.
#Sta/Elev= 30
    3673  510.72    3938  505.51  3959.3  504.86  3973.4  502.86  3987.6  503.98
  4079.5  502.67  4093.6  503.39  4121.9   500.3  4213.9  499.84    4235  498.56
  4249.2  499.18  4319.9  497.28  4418.9  496.57  4468.5   494.9  4722.9  493.36
  4786.6  493.88  4906.4  492.33    4940  492.58    4970  494.37    4980  493.99
    5000  490.86  5008.3  488.45    5020  489.02  5025.5 490.844  5030.1  492.37
  5040.1  492.68  5070.1  491.69  5140.1     492  5250.2  494.45  5475.4  495.82
#Mann= 3 ,-1 , 0
    3673     .05       0    5000     .04       0  5025.5     .05       0
Bank Sta=5000,5025.5
XS Rating Curve= 0 ,0
Exp/Cntr=0.3,0.1

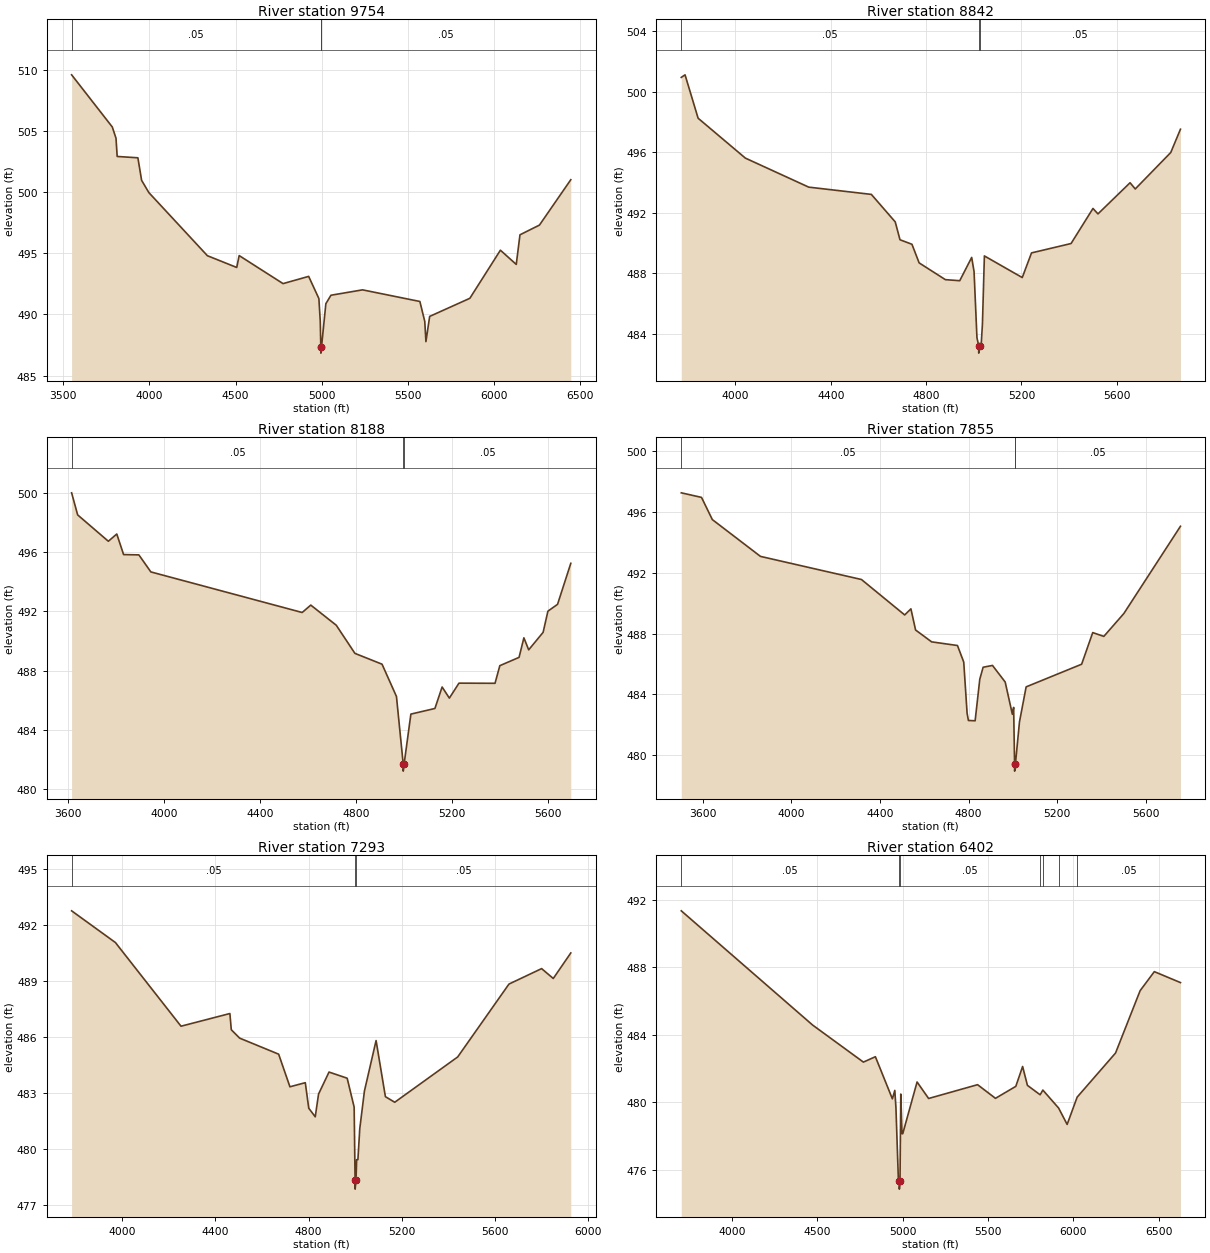
Type RM Length L Ch R = 1 ,9754    ,912,912,912
BEGIN DESCRIPTION:
Mapping XS 7b11b9b1
END DESCRIPTION:
XS GIS Cut Line= 4
      2732269.46      6947100.97      2731307.67      6946052.38
      2731220.87      6946066.27      2730189.68      6945140.75
#Sta/Elev= 30
  3548.7  509.57  3784.6  505.31  3806.2  504.39    3813   502.9  3933.2  502.79
  3954.8  500.95  3996.7  499.95  4336.5  494.79  4506.7  493.83  4520.9   494.8
  4775.5  492.51  4924.1   493.1  4983.4  491.29  4991.5  489.41  4994.5  487.33
  4994.8  486.83  4998.5  487.33  5023.9  490.87  5053.5  491.56  5236.8     492
  5569.4  491.05  5597.8  489.42  5604.5  487.77  5626.2  489.83  5859.4  491.31
  6036.6  495.24  6128.6  494.08  6150.2   496.5  6263.1  497.29  6445.1     501
#Mann= 3 ,-1 , 0
  3548.7     .05       0  4994.5     .05       0  4998.5     .05       0
Bank Sta=4994.5,4998.5
XS Rating Curve= 0 ,0
Exp/Cntr=0.3,0.1

Type RM Length L Ch R = 1 ,8842    ,654,654,654
BEGIN DESCRIPTION:
Little Allen T2 10.0
END DESCRIPTION:
XS GIS Cut Line= 6
      2732169.42      6945720.99      2731700.68      6945474.47
       2731461.1      6945394.61      2731009.71      6945366.83
      2730742.35       6945245.3      2730367.37      6944821.71
#Sta/Elev= 30
  3773.2  500.95    3789  501.12  3843.8  498.25  4042.1  495.61  4307.9  493.69
  4570.5  493.21  4670.7  491.39  4690.6  490.21  4740.8  489.91  4770.9  488.68
  4881.1  487.57  4941.2   487.5  4991.3  489.04  5001.3   488.1  5013.4  483.73
  5020.7  483.21  5020.9  482.71  5024.7  483.21    5031  483.23  5036.4  484.63
  5044.6  489.14  5203.4  487.71  5242.3  489.34  5408.1  489.96  5500.1  492.28
    5521  491.92  5655.6  493.98  5677.4  493.57  5826.3  495.98    5867  497.52
#Mann= 3 ,-1 , 0
  3773.2     .05       0  5020.7     .05       0  5024.7     .05       0
Bank Sta=5020.7,5024.7
XS Rating Curve= 0 ,0
Exp/Cntr=0.3,0.1

Type RM Length L Ch R = 1 ,8188    ,333,333,333
BEGIN DESCRIPTION:
Mapping XS 4aea40bd
END DESCRIPTION:
XS GIS Cut Line= 3
      2732200.71      6945621.89      2731284.06      6944781.63
      2730450.82       6944760.8
#Sta/Elev= 30
  3616.1     500  3641.2  498.51  3768.9  496.73    3804  497.22  3832.4  495.83
  3895.9  495.81  3945.8  494.66  4575.4  491.92  4611.2  492.42  4717.2  491.06
  4794.9  489.16  4907.7  488.43  4967.7  486.25  4995.7  481.71  4995.9  481.21
  4999.7  481.71  5027.7  485.06  5127.7  485.44  5157.7  486.89  5187.8  486.14
  5227.8  487.15  5377.8  487.14  5397.8  488.33  5477.8  488.89  5497.9  490.21
  5517.9   489.4  5577.9  490.58  5597.9  492.01  5637.9  492.47  5693.1  495.24
#Mann= 3 ,-1 , 0
  3616.1     .05       0  4995.7    .035       0  4999.7     .05       0
Bank Sta=4995.7,4999.7
XS Rating Curve= 0 ,0
Exp/Cntr=0.3,0.1

Type RM Length L Ch R = 1 ,7855    ,562,562,562
BEGIN DESCRIPTION:
Mapping XS b705ddf5
END DESCRIPTION:
XS GIS Cut Line= 3
      2732332.69      6945279.78      2731077.94      6944465.64
      2730320.95      6944525.71
#Sta/Elev= 30
  3502.3  497.26  3593.7  496.96  3642.6   495.5  3860.1  493.08  4316.3  491.56
  4511.6  489.23  4539.7  489.63  4560.8  488.24  4633.3  487.46    4750  487.22
  4778.4  486.13  4793.5  482.77  4799.5  482.29  4829.8  482.27  4850.9  485.01
    4866  485.79  4908.2  485.91  4965.6  484.82    4998   482.7  5003.8  483.15
    5008  479.46  5008.3  478.96    5012  479.46  5030.1  482.19  5060.2   484.5
    5311  485.99  5361.1  488.07  5411.3  487.82  5501.5  489.32  5757.4  495.06
#Mann= 3 ,-1 , 0
  3502.3     .05       0    5008    .035       0    5012     .05       0
Bank Sta=5008,5012
XS Rating Curve= 0 ,0
Exp/Cntr=0.3,0.1

Type RM Length L Ch R = 1 ,7293    ,891,891,891
BEGIN DESCRIPTION:
Mapping XS 6b192297
END DESCRIPTION:
XS GIS Cut Line= 3
      2732291.02      6944698.31      2731277.12       6944010.8
      2730360.76      6944003.86
#Sta/Elev= 30
  3783.2  492.76    3971  491.06  4252.5  486.57  4462.1  487.25  4468.2  486.38
  4504.1  485.93  4671.3  485.07  4719.7  483.32  4785.6  483.54  4800.5  482.17
  4828.3  481.71  4842.5  482.93  4887.4  484.11  4965.3  483.78  4995.2  482.23
  4999.2  478.33  4999.5  477.83  5003.2  478.33  5005.9  479.41  5011.3  479.41
  5019.3  481.07  5039.3  483.09  5089.3   485.8  5129.3  482.79  5169.3  482.49
  5439.3  484.92  5659.3  488.83  5799.4  489.66  5849.4  489.13  5924.6   490.5
#Mann= 3 ,-1 , 0
  3783.2     .05       0  4999.2     .04       0  5003.2     .05       0
Bank Sta=4999.2,5003.2
XS Rating Curve= 0 ,0
Exp/Cntr=0.3,0.1

Type RM Length L Ch R = 1 ,6402    ,1203,1203,1203
BEGIN DESCRIPTION:
Little Allen T2 6.0
END DESCRIPTION:
XS GIS Cut Line= 3
      2732435.99      6944277.02      2731571.77      6943309.22
      2730102.63      6942610.33
#Sta/Elev= 30
  3702.5  491.36  4471.9  484.58  4769.5  482.38  4839.7   482.7  4939.2   480.2
  4953.4   480.7  4960.1  479.67  4974.3  475.42  4979.8  475.34  4980.1  474.84
  4983.9  475.34  4988.5  480.48  4995.5  478.13    5000  478.13  5083.9   481.2
  5151.5  480.22  5438.3  481.04  5543.2  480.23  5662.3  480.94  5702.2  482.12
  5730.4     481  5804.9  480.44  5820.8  480.72  5913.3  479.65  5963.1  478.68
  6021.7   480.3  6246.7  482.92  6390.6  486.62  6473.9  487.75  6626.9   487.1
#Mann= 7 ,-1 , 0
  3702.5     .05       0  4979.8     .04       0  4983.9     .05       0
  5804.9     .12       0  5820.8     .05       0  5913.3     .12       0
  6021.7     .05       0
Bank Sta=4979.8,4983.9
XS Rating Curve= 0 ,0
Exp/Cntr=0.3,0.1

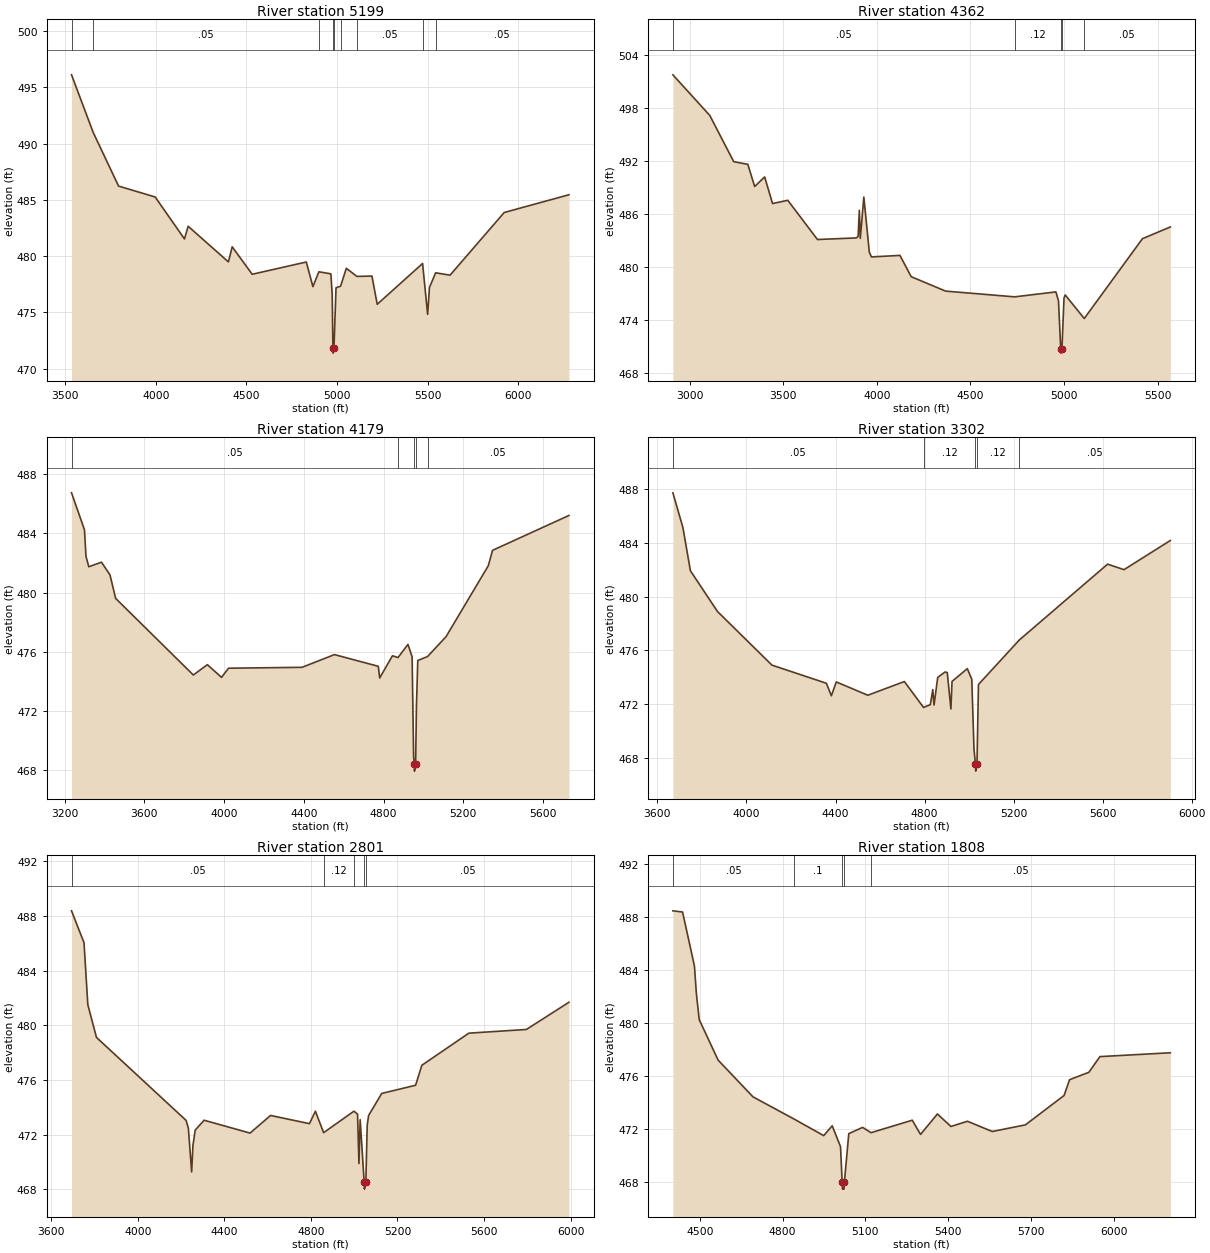
Type RM Length L Ch R = 1 ,5199    ,837,837,837
BEGIN DESCRIPTION:
Mapping XS 23490fd2
END DESCRIPTION:
XS GIS Cut Line= 4
      2732692.93      6942568.67       2731456.8      6942395.06
      2731198.38      6942706.33      2730139.18      6942444.12
#Sta/Elev= 30
  3535.5  496.12  3654.7  491.01  3794.9  486.23  3996.9  485.26  4158.5  481.53
  4178.7  482.66  4400.8  479.49  4421.8  480.83  4532.1  478.39  4830.6  479.48
    4867  477.29  4899.8  478.61    4966  478.43  4973.4  476.61  4977.3  471.88
  4978.3  471.38  4983.3  471.88  4994.6  477.19  5019.6  477.33  5051.4  478.92
  5109.7   478.2  5192.8  478.23  5221.7  475.72  5472.1  479.35  5499.8  474.83
  5510.1  477.22    5544  478.52  5623.5  478.31  5922.2  483.88  6279.5  485.46
#Mann= 9 ,-1 , 0
  3535.5     .12       0  3654.7     .05       0  4899.8     .12       0
  4977.3     .07       0  4983.3     .12       0  5019.6      .1       0
  5109.7     .05       0  5472.1     .12       0    5544     .05       0
Bank Sta=4977.3,4983.3
XS Rating Curve= 0 ,0
Exp/Cntr=0.3,0.1

Type RM Length L Ch R = 1 ,4362    ,183,183,183
BEGIN DESCRIPTION:
Mapping XS 03d5df21
END DESCRIPTION:
XS GIS Cut Line= 3
       2732790.1      6942374.22      2730762.36      6942006.17
      2730297.05      6942381.19
#Sta/Elev= 30
  2909.7  501.75    3107  497.15  3234.9  491.92  3310.2  491.62  3346.7  489.11
  3400.2  490.19  3442.4  487.18  3523.7  487.55  3682.4  483.11  3889.6  483.29
  3899.7  483.45  3906.2  486.42  3911.3  483.24  3930.2  487.92  3959.6  481.67
  3970.9  481.14  4123.3  481.31  4183.4   478.9  4367.2  477.27    4736  476.62
  4956.7  477.18  4970.6  476.16  4982.4  470.75  4983.4  470.25  4989.1  470.75
  5000.1   476.5  5006.5  476.83  5108.3  474.17  5419.2   483.2  5568.2  484.53
#Mann= 5 ,-1 , 0
  2909.7     .05       0    4736     .12       0  4982.4     .07       0
  4989.1     .12       0  5108.3     .05       0
Bank Sta=4982.4,4989.1
XS Rating Curve= 0 ,0
Exp/Cntr=0.3,0.1

Type RM Length L Ch R = 1 ,4179    ,877,877,877
BEGIN DESCRIPTION:
Mapping XS 09a51e2e
END DESCRIPTION:
XS GIS Cut Line= 3
      2731963.73       6940706.7       2730644.3      6941874.22
      2730127.83      6942395.04
#Sta/Elev= 30
  3234.8  486.75  3299.7  484.25  3307.2  482.46  3321.4  481.75    3385  482.06
  3427.7   481.2  3456.1  479.61  3845.9  474.43  3916.1  475.13  3987.2  474.27
  4022.4  474.89  4391.2  474.95  4553.7  475.81  4773.5  475.02  4780.7  474.23
  4844.6  475.73  4872.6  475.61  4922.4   476.5  4943.3  475.66  4950.8  468.93
  4954.1  468.43  4955.2  467.93  4960.9  468.43    4965  472.34  4971.7  475.41
  5020.9  475.68  5113.4  477.02  5325.5  481.82  5346.7  482.86  5730.1  485.22
#Mann= 5 ,-1 , 0
  3234.8     .05       0  4872.6     .12       0  4954.1     .07       0
  4960.9     .12       0  5020.9     .05       0
Bank Sta=4954.1,4960.9
XS Rating Curve= 0 ,0
Exp/Cntr=0.3,0.1

Type RM Length L Ch R = 1 ,3302    ,501,501,501
BEGIN DESCRIPTION:
Mapping XS a88de0d5
END DESCRIPTION:
XS GIS Cut Line= 4
      2731976.08      6940612.99      2730895.32      6941164.23
      2730530.73      6941181.59      2729996.91      6941563.51
#Sta/Elev= 30
  3669.5  487.72  3714.5  485.14  3748.2  481.92  3870.1  478.88  4114.7  474.89
  4359.2  473.54  4381.4  472.61  4403.6  473.64  4545.2  472.65  4709.3  473.67
  4795.6  471.74    4826  471.95    4837  473.07  4842.6  471.92  4859.3  473.98
  4892.1  474.38  4902.1  474.34  4918.5  471.63  4923.5  473.68  4992.2  474.63
  5012.2  473.84  5022.2  468.64  5028.8   467.5  5029.9     467  5035.6   467.5
  5042.2  473.45  5226.2  476.77  5622.4  482.41  5696.1     482  5904.1  484.17
#Mann= 5 ,-1 , 0
  3669.5     .05       0  4795.6     .12       0  5028.8     .07       0
  5035.6     .12       0  5226.2     .05       0
Bank Sta=5028.8,5035.6
XS Rating Curve= 0 ,0
Exp/Cntr=0.3,0.1

Type RM Length L Ch R = 1 ,2801    ,993,993,993
BEGIN DESCRIPTION:
Mapping XS 1a3401b2
END DESCRIPTION:
XS GIS Cut Line= 4
       2731987.3      6940448.09      2730923.96      6940808.32
      2730177.43      6940435.06      2729843.22      6940504.51
#Sta/Elev= 30
  3693.7  488.37  3751.3  486.04    3769   481.5  3808.9  479.11    4223  473.04
  4233.5  472.48  4248.8  469.27  4254.7   471.2  4265.2  472.33  4306.3  473.05
  4518.6  472.11  4613.6   473.4  4793.1   472.8  4820.7  473.71  4858.6  472.14
  4998.6  473.71  5015.4   473.5  5021.9  469.88  5027.5  473.09  5046.1  468.51
  5047.2  468.01  5053.7  468.51  5060.1  472.69  5066.6   473.4  5127.2  475.01
  5283.7  475.61  5312.6  477.07  5529.7  479.42  5795.5  479.69  5992.4  481.68
#Mann= 5 ,-1 , 0
  3693.7     .05       0  4858.6     .12       0  4998.6     .05       0
  5046.1     .04       0  5053.7     .05       0
Bank Sta=5046.1,5053.7
XS Rating Curve= 0 ,0
Exp/Cntr=0.3,0.1

Type RM Length L Ch R = 1 ,1808    ,681,681,681
BEGIN DESCRIPTION:
Mapping XS fe4ad092
END DESCRIPTION:
XS GIS Cut Line= 3
      2732009.03      6940382.98      2731440.45      6940252.77
      2730220.92      6940296.17
#Sta/Elev= 30
  4402.3  488.44  4437.4  488.35  4480.4  484.29  4487.5   482.2  4497.7  480.25
  4566.2   477.2  4692.7  474.43  4841.5  472.76  4949.1  471.51  4979.9  472.25
  5010.1  470.68  5016.1  467.98  5017.3  467.48  5022.8  467.48    5024  467.98
  5040.1  471.66  5090.1  472.13  5120.7  471.73  5270.2  472.67  5300.2   471.6
  5361.5  473.14  5410.3   472.2  5470.4  472.59  5560.4  471.82  5680.5  472.32
  5820.6  474.53  5840.6  475.72  5910.6  476.28  5950.7  477.46  6205.9  477.75
#Mann= 5 ,-1 , 0
  4402.3     .05       0  4841.5      .1       0  5016.1     .07       0
    5024      .1       0  5120.7     .05       0
Bank Sta=5016.1,5024
XS Rating Curve= 0 ,0
Exp/Cntr=0.3,0.1

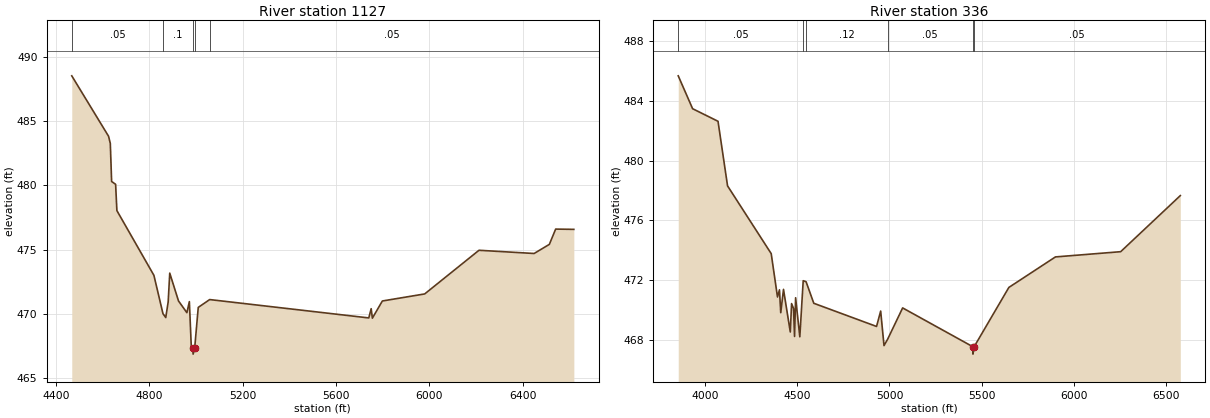
Type RM Length L Ch R = 1 ,1127    ,791,791,791
BEGIN DESCRIPTION:
Mapping XS 3759abbc
END DESCRIPTION:
XS GIS Cut Line= 4
      2732013.37      6940283.14      2731796.36      6939831.76
      2731535.94      6939731.94       2730200.1      6940039.87
#Sta/Elev= 30
  4467.9  488.54  4625.6  483.83    4633  483.27  4638.6  480.31  4655.7  480.09
  4661.2  478.04  4819.7     473  4858.6  470.01  4870.5  469.71  4880.8  470.92
  4887.6  473.17  4925.2     471    4961  470.09  4971.6  470.95  4979.7   467.5
  4986.5  467.36  4987.7  466.86  4994.5  467.36  5009.7   470.5  5058.6  471.11
  5740.2  469.68  5750.4   470.4  5755.5  469.66  5798.3     471  5979.7  471.55
  6212.2  474.95  6448.3   474.7  6513.6  475.41  6540.6   476.6  6618.5  476.58
#Mann= 5 ,-1 , 0
  4467.9     .05       0  4858.6      .1       0  4986.5     .07       0
  4994.5      .1       0  5058.6     .05       0
Bank Sta=4986.5,4994.5
XS Rating Curve= 0 ,0
Exp/Cntr=0.3,0.1

Type RM Length L Ch R = 1 ,336     ,0,0,0
BEGIN DESCRIPTION:
Little Allen T2 1.0
END DESCRIPTION:
XS GIS Cut Line= 3
      2732200.01       6940092.2      2731809.38      6939224.12
      2730055.93      6939493.22
#Sta/Elev= 30
  3853.3  485.67  3931.4  483.47  4069.3  482.63  4121.1  478.31  4358.1  473.78
  4392.2  470.88  4402.9  471.36  4409.9  469.83  4424.8  471.39  4461.7  468.54
  4468.7  470.44  4479.3  470.11  4484.8  468.24  4490.6  470.83  4513.4  468.22
  4531.8  471.97  4547.5   471.9  4589.3  470.46    4930  468.91  4952.4  469.94
  4970.5  467.63  4990.3  468.06  5071.7  470.15  5452.1  467.56  5453.3  467.06
  5460.1  467.56  5648.4  471.52  5901.3  473.56  6255.4  473.91  6579.2  477.66
#Mann= 6 ,-1 , 0
  3853.3     .05       0  4531.8      .1       0  4547.5     .12       0
  4990.3     .05       0  5452.1     .04       0  5460.1     .05       0
Bank Sta=5452.1,5460.1
XS Rating Curve= 0 ,0
Exp/Cntr=0.3,0.1

Chan Stop Cuts=-1
Use User Specified Reach Order=0
Composite Channel Slope=5