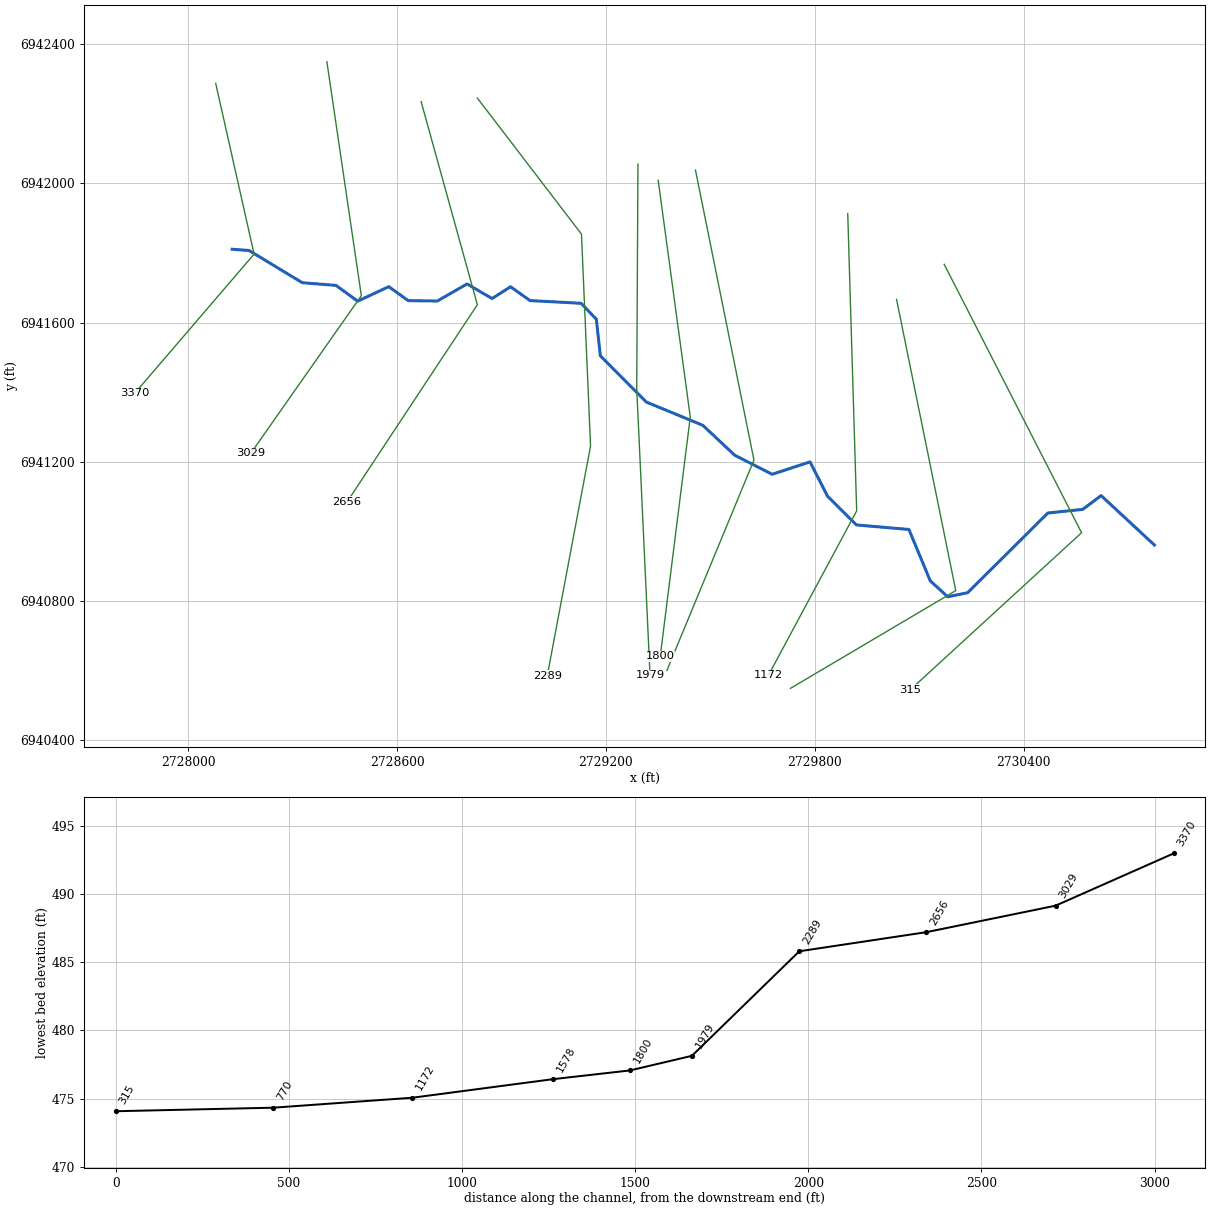
--- Little Allen T2_1.prj (project) ---

Proj Title=Little Allen T2_1 Base Level Engineering
Current Plan=p01
Default Exp/Contr=0.3,0.1
English Units
Geom File=g01
Flow File=f01
Plan File=p01
BEGIN DESCRIPTION:
Little Allen T2_1
END DESCRIPTION:

--- Little Allen T2_1.p01 (plan) ---

Plan Title=Multiple Run
Short Identifier=Multiple
Geom File=g01
Flow File=f01
Subcritical Flow
K Sum by GR= 0
Std Step Tol= 0.01
Critical Tol= 0.01
Num of Std Step Trials= 20
Max Error Tol= 0.3
Flow Tol Ratio= 0.001
Split Flow NTrial= 30
Split Flow Tol= 0.02
Split Flow Ratio= 0.02
Log Output Level= 0
Friction Slope Method= 1
Unsteady Friction Slope Method= 2
Unsteady Bridges Friction Slope Method= 1
Parabolic Critical Depth
Global Vel Dist=  1 , 1 , 1
Global Log Level= 0
CheckData=True
Encroach Param= -1, 0, 0, 0
BEGIN DESCRIPTION:
Multiple Run
END DESCRIPTION:

--- Little Allen T2_1.f01 (steady flow) ---

Flow Title=Multiple
Number of Profiles=7
Profile Names=10-year,25-year,50-year,1pct_min,100-year,1pct_plu,500-year
River Rch & RM= Little Allen T2_,Reach-1,3370
     278     350     406     234     467     932     615
Boundary for River Rch & Prof#=Little Allen T2_,Reach-1,1
Up Type=0
Dn Type=3
Dn Slope=0.005
Boundary for River Rch & Prof#=Little Allen T2_,Reach-1,2
Up Type=0
Dn Type=3
Dn Slope=0.005
Boundary for River Rch & Prof#=Little Allen T2_,Reach-1,3
Up Type=0
Dn Type=3
Dn Slope=0.005
Boundary for River Rch & Prof#=Little Allen T2_,Reach-1,4
Up Type=0
Dn Type=3
Dn Slope=0.005
Boundary for River Rch & Prof#=Little Allen T2_,Reach-1,5
Up Type=0
Dn Type=3
Dn Slope=0.005
Boundary for River Rch & Prof#=Little Allen T2_,Reach-1,6
Up Type=0
Dn Type=3
Dn Slope=0.005
Boundary for River Rch & Prof#=Little Allen T2_,Reach-1,7
Up Type=0
Dn Type=3
Dn Slope=0.005

--- Little Allen T2_1.g01 (geometry) ---

Geom Title=Existing Conditions

River Reach=Little Allen T2_,Reach-1
Reach XY= 30
      2728126.00      6941811.00      2728174.51      6941807.40
      2728327.58      6941714.82      2728424.42      6941707.11
      2728486.71      6941661.81      2728575.99      6941703.40
      2728631.89      6941663.36      2728715.45      6941662.13
      2728801.04      6941711.31      2728872.77      6941669.32
      2728925.90      6941703.21      2728981.86      6941663.46
      2729128.73      6941655.65      2729172.49      6941609.75
      2729183.86      6941504.83      2729316.32      6941371.76
      2729478.29      6941305.15      2729569.95      6941219.15
      2729677.74      6941164.37      2729786.37      6941200.02
      2729836.77      6941101.33      2729919.80      6941018.81
      2730070.59      6941005.82      2730131.73      6940858.38
      2730181.87      6940812.50      2730239.20      6940824.10
      2730469.83      6941053.14      2730570.11      6941063.56
      2730622.78      6941103.14      2730776.00      6940961.00

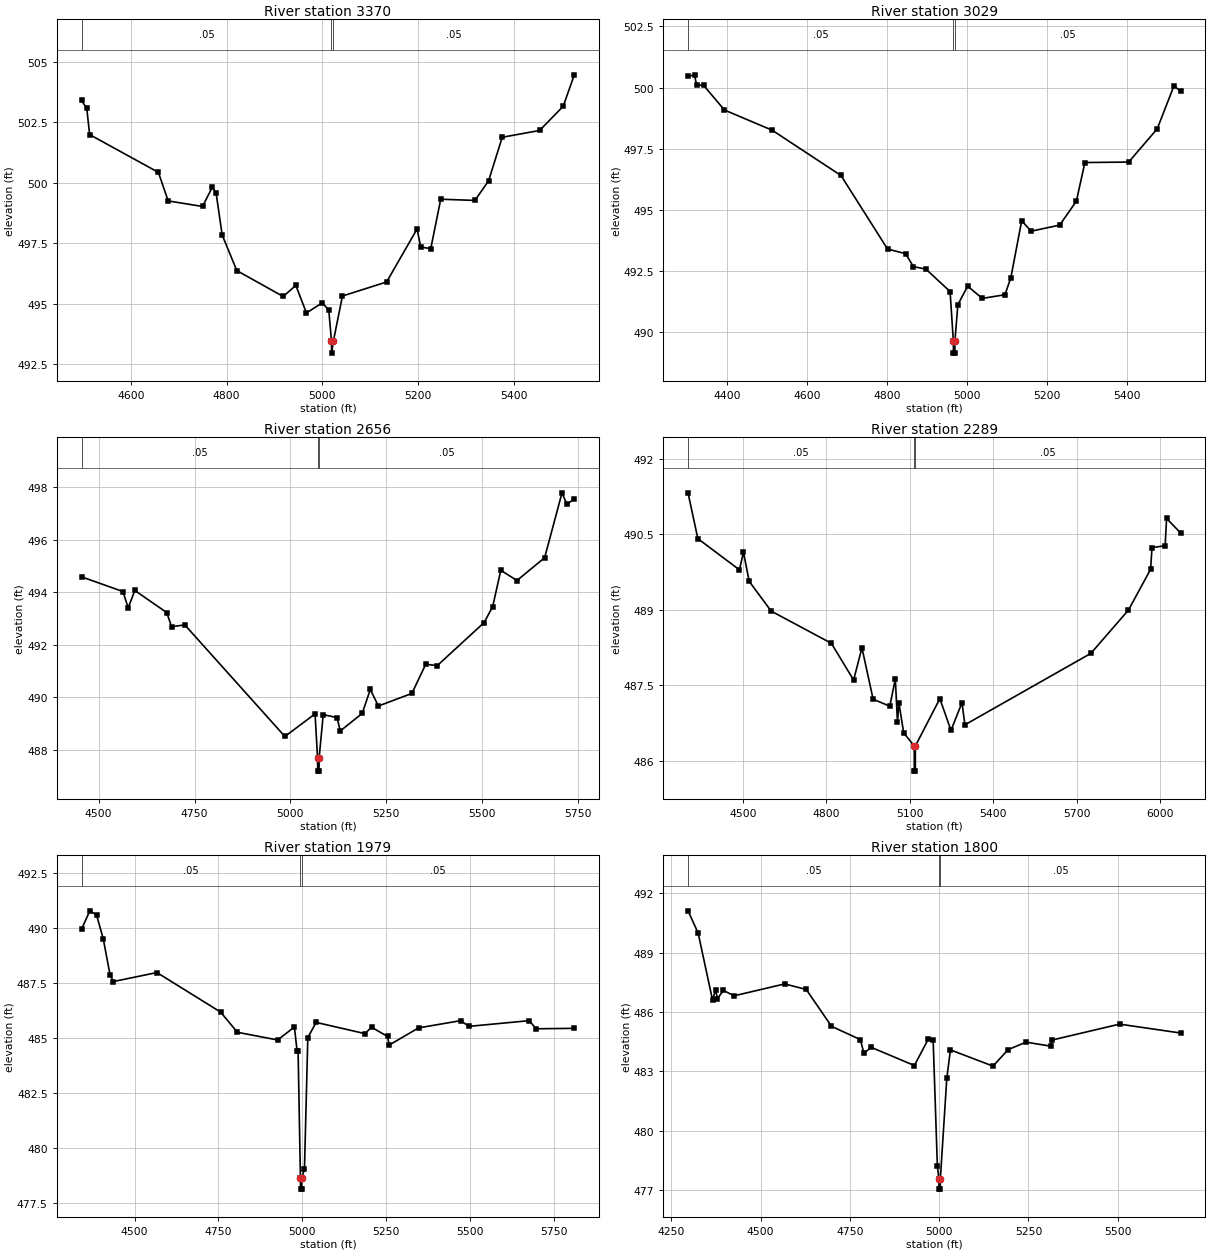
Type RM Length L Ch R = 1,3370,341,341,341
BEGIN DESCRIPTION:
Little Allen T2_1 3.0
END DESCRIPTION:
XS GIS Cut Line= 3
      2728078.78      6942287.47      2728189.07      6941797.02
      2727846.56      6941397.68
#Sta/Elev= 30
  4497.3  503.40  4508.2  503.07  4514.2  501.99  4657.7  500.43  4678.2  499.25
  4749.9  499.02  4770.4  499.82  4778.2  499.58  4790.9  497.84  4821.5  496.37
  4918.3  495.30  4944.7  495.76  4966.8  494.62  5000.0  495.04  5013.5  494.73
  5019.1  493.46  5019.4  492.96  5023.1  493.46  5042.0  495.32  5134.2  495.90
  5197.8  498.09  5205.5  497.34  5226.4  497.28  5247.2  499.32  5318.6  499.27
  5347.1  500.08  5375.6  501.88  5453.6  502.16  5502.9  503.16  5526.1  504.46
#Mann=3,-1,0
  4497.3    0.05       0  5019.1    0.04       0  5023.1    0.05       0
Bank Sta=5019.1,5023.1
Exp/Cntr=0.3,0.1

Type RM Length L Ch R = 1,3029,373,373,373
BEGIN DESCRIPTION:
Mapping XS 66bd3a9c
END DESCRIPTION:
XS GIS Cut Line= 3
      2728398.23      6942349.51      2728497.19      6941677.65
      2728179.49      6941224.54
#Sta/Elev= 30
  4301.7  500.46  4318.0  500.52  4323.1  500.10  4340.6  500.09  4392.8  499.08
  4512.5  498.25  4684.3  496.40  4800.8  493.39  4846.0  493.20  4865.4  492.67
  4896.6  492.57  4957.2  491.65  4965.3  489.63  4965.6  489.13  4969.1  489.13
  4969.3  489.63  4976.6  491.11  5001.1  491.87  5037.8  491.37  5094.4  491.52
  5109.2  492.22  5136.3  494.55  5159.8  494.12  5231.3  494.37  5273.1  495.35
  5294.3  496.93  5403.9  496.95  5475.3  498.31  5517.2  500.07  5534.2  499.84
#Mann=3,-1,0
  4301.7    0.05       0  4965.3    0.04       0  4969.3    0.05       0
Bank Sta=4965.3,4969.3
Exp/Cntr=0.3,0.1

Type RM Length L Ch R = 1,2656,367,367,367
BEGIN DESCRIPTION:
Mapping XS 2598a0ef
END DESCRIPTION:
XS GIS Cut Line= 3
      2728669.07      6942234.91      2728830.52      6941651.61
      2728456.19      6941084.91
#Sta/Elev= 30
  4455.6  494.59  4563.4  494.03  4577.1  493.41  4594.5  494.07  4677.6  493.23
  4690.4  492.69  4724.7  492.76  4985.6  488.51  5064.2  489.37  5070.8  487.69
  5071.1  487.19  5074.6  487.19  5074.8  487.69  5085.5  489.34  5121.5  489.23
  5130.0  488.72  5187.2  489.39  5208.2  490.30  5229.3  489.67  5316.6  490.15
  5352.7  491.26  5382.9  491.21  5505.0  492.85  5527.3  493.46  5548.4  494.84
  5590.5  494.45  5662.7  495.32  5707.9  497.79  5720.7  497.35  5740.0  497.56
#Mann=3,-1,0
  4455.6    0.05       0  5070.8    0.04       0  5074.8    0.05       0
Bank Sta=5070.8,5074.8
Exp/Cntr=0.3,0.1

Type RM Length L Ch R = 1,2289,310,310,310
BEGIN DESCRIPTION:
Mapping XS 9fab2ace
END DESCRIPTION:
XS GIS Cut Line= 4
      2728830.54      6942245.34      2729129.72      6941854.47
      2729155.77      6941245.49      2729031.51      6940585.95
#Sta/Elev= 30
  4301.9  491.32  4337.2  490.41  4486.8  489.79  4501.3  490.14  4522.1  489.56
  4601.1  488.97  4817.6  488.33  4897.7  487.60  4927.7  488.24  4967.8  487.22
  5027.8  487.08  5047.8  487.62  5055.5  486.76  5060.5  487.15  5077.9  486.55
  5115.9  486.29  5116.1  485.79  5119.6  485.79  5119.9  486.29  5208.0  487.23
  5248.0  486.60  5287.6  487.15  5298.1  486.71  5751.3  488.13  5886.5  488.99
  5966.2  489.80  5971.3  490.23  6018.6  490.27  6023.7  490.81  6074.8  490.52
#Mann=3,-1,0
  4301.9    0.05       0  5115.9    0.05       0  5119.9    0.05       0
Bank Sta=5115.9,5119.9
Exp/Cntr=0.3,0.1

Type RM Length L Ch R = 1,1979,179,179,179
BEGIN DESCRIPTION:
Mapping XS 24717d84
END DESCRIPTION:
XS GIS Cut Line= 3
      2729291.98      6942055.75      2729288.51      6941409.95
      2729326.70      6940587.05
#Sta/Elev= 30
  4341.7  489.97  4366.5  490.80  4386.5  490.61  4406.5  489.52  4426.5  487.90
  4436.5  487.58  4566.5  487.99  4756.5  486.19  4806.5  485.27  4926.5  484.92
  4976.5  485.51  4984.5  484.42  4987.5  484.42  4994.5  478.63  4994.7  478.13
  4998.2  478.13  4998.5  478.63  5006.5  479.05  5016.5  485.03  5041.4  485.72
  5186.7  485.21  5206.7  485.50  5254.3  485.08  5259.3  484.69  5346.8  485.47
  5472.3  485.80  5497.0  485.54  5677.2  485.80  5697.2  485.43  5811.3  485.45
#Mann=3,-1,0
  4341.7    0.05       0  4994.5    0.04       0  4998.5    0.05       0
Bank Sta=4994.5,4998.5
Exp/Cntr=0.3,0.1

Type RM Length L Ch R = 1,1800,222,222,222
BEGIN DESCRIPTION:
Mapping XS 8eb4a366
END DESCRIPTION:
XS GIS Cut Line= 3
      2729350.15      6942009.03      2729442.31      6941328.90
      2729355.99      6940641.04
#Sta/Elev= 30
  4296.8  491.11  4325.1  489.99  4365.4  486.61  4374.1  487.13  4379.1  486.67
  4395.7  487.09  4426.0  486.82  4567.3  487.42  4627.8  487.14  4698.5  485.28
  4779.2  484.61  4789.3  483.92  4809.5  484.22  4930.6  483.30  4969.6  484.64
  4983.1  484.58  4994.9  478.23  4999.2  477.56  4999.4  477.06  5002.9  477.06
  5003.2  477.56  5021.3  482.65  5031.4  484.09  5150.8  483.27  5192.7  484.10
  5243.1  484.48  5311.7  484.28  5316.8  484.59  5505.1  485.39  5676.4  484.94
#Mann=3,-1,0
  4296.8    0.05       0  4999.2    0.04       0  5003.2    0.05       0
Bank Sta=4999.2,5003.2
Exp/Cntr=0.3,0.1

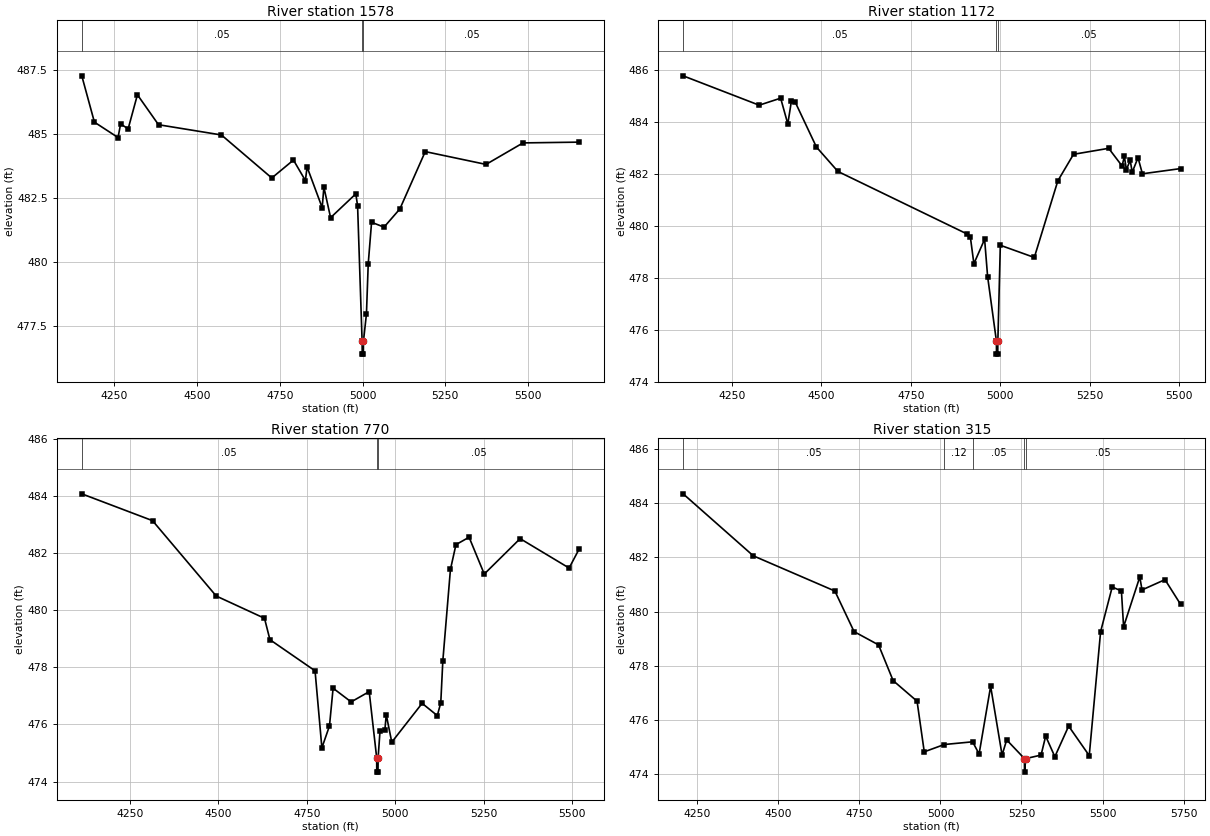
Type RM Length L Ch R = 1,1578,406,406,406
BEGIN DESCRIPTION:
Mapping XS 7e63ff40
END DESCRIPTION:
XS GIS Cut Line= 3
      2729457.26      6942038.41      2729625.31      6941205.08
      2729375.30      6940600.87
#Sta/Elev= 30
  4151.2  487.29  4189.4  485.48  4260.8  484.88  4268.6  485.41  4291.4  485.22
  4319.4  486.55  4383.2  485.38  4573.4  484.98  4725.7  483.30  4791.2  484.00
  4827.3  483.20  4832.4  483.73  4878.1  482.14  4883.2  482.94  4903.5  481.75
  4979.7  482.68  4985.1  482.22  4998.8  476.92  4999.1  476.42  5002.6  476.42
  5002.8  476.92  5011.9  477.99  5017.3  479.95  5027.4  481.57  5065.1  481.38
  5112.9  482.09  5189.7  484.33  5373.5  483.83  5485.3  484.67  5655.2  484.70
#Mann=3,-1,0
  4151.2    0.05       0  4998.8    0.04       0  5002.8    0.05       0
Bank Sta=4998.8,5002.8
Exp/Cntr=0.3,0.1

Type RM Length L Ch R = 1,1172,402,402,402
BEGIN DESCRIPTION:
Mapping XS 3408518b
END DESCRIPTION:
XS GIS Cut Line= 3
      2729894.76      6941913.46      2729920.45      6941059.25
      2729667.00      6940587.07
#Sta/Elev= 30
  4113.4  485.77  4326.0  484.64  4386.0  484.91  4406.0  483.92  4416.0  484.79
  4426.0  484.78  4486.0  483.03  4546.1  482.09  4906.2  479.69  4916.2  479.58
  4926.2  478.54  4956.2  479.48  4964.6  478.04  4989.2  475.56  4989.4  475.06
  4992.9  475.06  4993.2  475.56  5000.1  479.25  5095.1  478.78  5160.9  481.73
  5204.7  482.75  5303.0  482.98  5340.5  482.30  5346.8  482.67  5352.5  482.16
  5363.1  482.52  5368.8  482.06  5385.0  482.62  5397.3  482.00  5503.9  482.20
#Mann=3,-1,0
  4113.4    0.05       0  4989.2    0.04       0  4993.2    0.05       0
Bank Sta=4989.2,4993.2
Exp/Cntr=0.3,0.1

Type RM Length L Ch R = 1,770,455,455,455
BEGIN DESCRIPTION:
Mapping XS e04557d9
END DESCRIPTION:
XS GIS Cut Line= 3
      2730035.03      6941666.94      2730205.18      6940830.08
      2729730.25      6940549.29
#Sta/Elev= 30
  4114.2  484.08  4314.1  483.14  4494.1  480.50  4630.5  479.72  4645.9  478.97
  4773.4  477.88  4792.7  475.18  4814.2  475.95  4824.4  477.27  4875.4  476.79
  4926.4  477.15  4947.6  474.83  4947.8  474.33  4951.3  474.33  4951.6  474.83
  4957.0  475.77  4970.6  475.79  4974.6  476.34  4990.2  475.38  5076.0  476.74
  5118.9  476.31  5128.7  476.76  5134.5  478.23  5156.0  481.43  5171.6  482.30
  5208.7  482.56  5251.6  481.27  5353.0  482.51  5491.4  481.48  5519.9  482.15
#Mann=3,-1,0
  4114.2    0.05       0  4947.6    0.04       0  4951.6    0.05       0
Bank Sta=4947.6,4951.6
Exp/Cntr=0.3,0.1

Type RM Length L Ch R = 1,315,0,0,0
BEGIN DESCRIPTION:
Little Allen T2_1 1.0
END DESCRIPTION:
XS GIS Cut Line= 3
      2730171.88      6941767.73      2730566.63      6940996.42
      2730074.15      6940544.88
#Sta/Elev= 30
  4206.1  484.35  4422.6  482.06  4674.2  480.76  4733.5  479.26  4809.0  478.77
  4854.0  477.45  4927.8  476.69  4950.0  474.82  5011.8  475.09  5099.2  475.19
  5119.2  474.74  5154.8  477.24  5190.1  474.70  5204.3  475.26  5259.1  474.57
  5259.3  474.07  5263.1  474.57  5310.4  474.70  5324.6  475.40  5352.9  474.64
  5395.5  475.77  5459.0  474.68  5494.1  479.26  5529.9  480.91  5558.3  480.76
  5565.0  479.44  5615.0  481.28  5621.8  480.80  5692.7  481.18  5740.7  480.27
#Mann=5,-1,0
  4206.1    0.05       0  5011.8    0.12       0  5099.2    0.05       0
  5259.1    0.04       0  5263.1    0.05       0
Bank Sta=5259.1,5263.1
Exp/Cntr=0.3,0.1

Chan Stop Cuts=-1