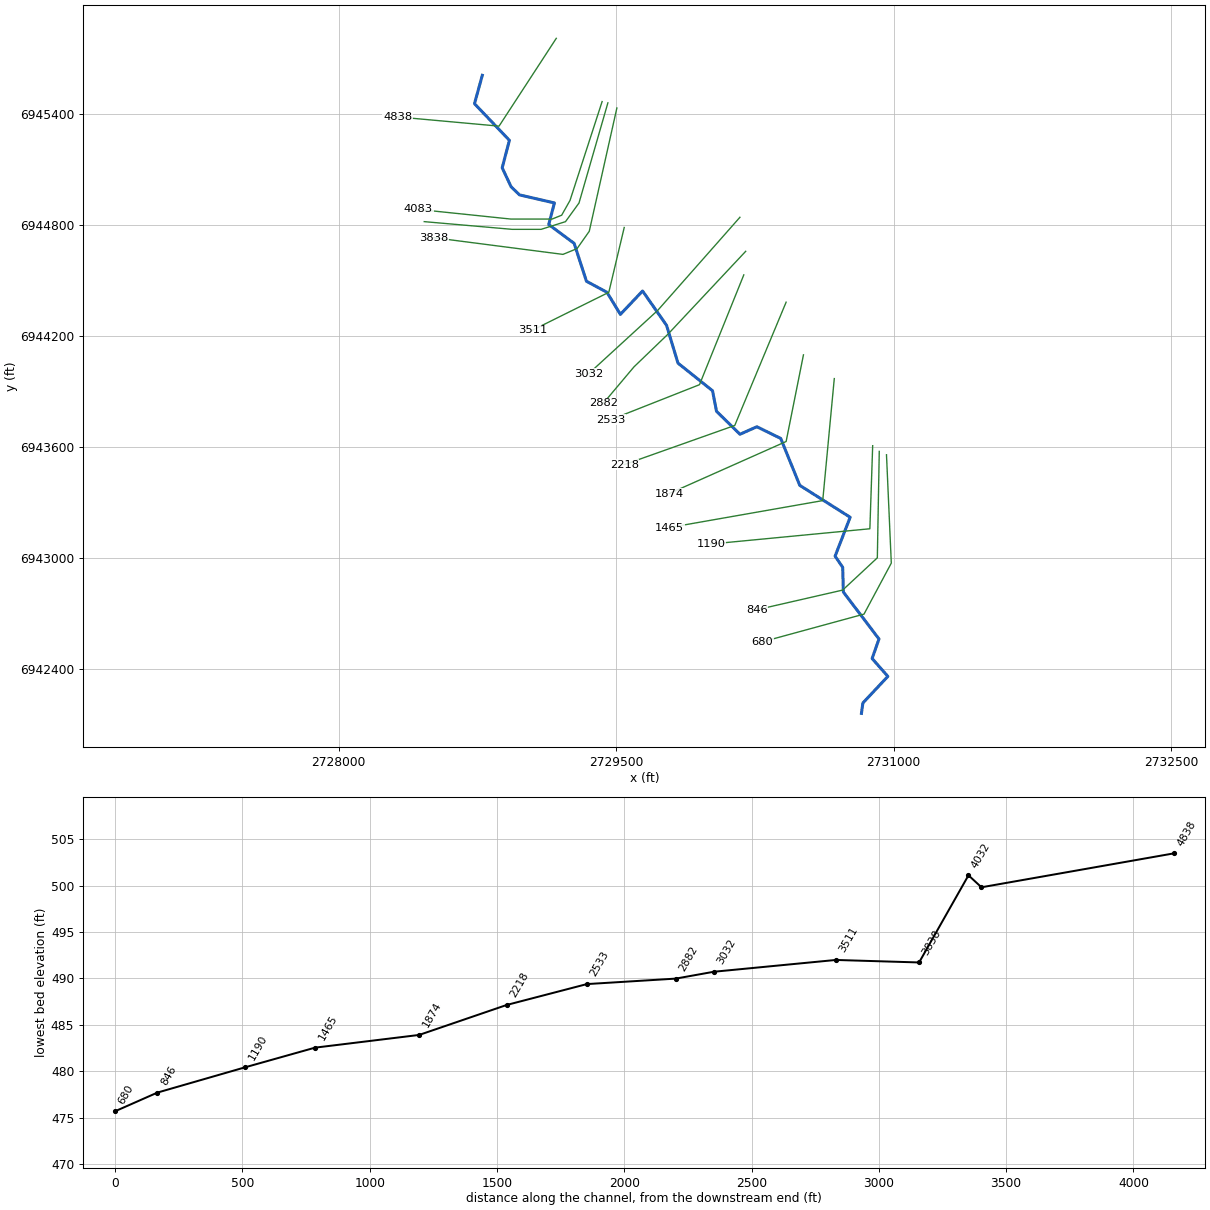
--- Little Allen T2_2.prj (project) ---

Proj Title=Little Allen T2_2 Base Level Engineering
Current Plan=p01
Default Exp/Contr=0.3,0.1
English Units
Geom File=g01
Flow File=f01
Plan File=p01
Y Axis Title=Elevation
X Axis Title(PF)=Main Channel Distance
X Axis Title(XS)=Station
BEGIN DESCRIPTION:
Little Allen T2_2
END DESCRIPTION:
DSS Export Rating Curves= 0
DSS Export Rating Curve Sorted= 0
DSS Export Volume Flow Curves= 0
DXF OffsetX= 0
DXF OffsetY= 0
DXF ScaleX= 1
DXF ScaleY= 10

--- Little Allen T2_2.p01 (plan) ---

Plan Title=Multiple Run
Short Identifier=Multiple
Geom File=g01
Flow File=f01
Subcritical Flow
K Sum by GR= 0
Std Step Tol= 0.01
Critical Tol= 0.01
Num of Std Step Trials= 20
Max Error Tol= 0.3
Flow Tol Ratio= 0.001
Split Flow NTrial= 30
Split Flow Tol= 0.02
Split Flow Ratio= 0.02
Log Output Level= 0
Friction Slope Method= 1
Unsteady Friction Slope Method= 2
Unsteady Bridges Friction Slope Method= 1
Parabolic Critical Depth
Global Vel Dist=  1 , 1 , 1
Global Log Level= 0
CheckData=True
Encroach Param= -1, 0, 0, 0
BEGIN DESCRIPTION:
Multiple Run
END DESCRIPTION:

--- Little Allen T2_2.f01 (steady flow) ---

Flow Title=Multiple
Program Version=4.10
Number of Profiles= 7
Profile Names=10-year,25-year,50-year,1pct_min,100-year,1pct_plu,500-year
River Rch & RM=Little Allen T2_,Reach-1         ,4838
     259     327     378     218     434     867     572
Boundary for River Rch & Prof#=Little Allen T2_,Reach-1         , 1
Up Type= 0
Dn Type= 3
Dn Slope=0.0094
Boundary for River Rch & Prof#=Little Allen T2_,Reach-1         , 2
Up Type= 0
Dn Type= 3
Dn Slope=0.0094
Boundary for River Rch & Prof#=Little Allen T2_,Reach-1         , 3
Up Type= 0
Dn Type= 3
Dn Slope=0.0094
Boundary for River Rch & Prof#=Little Allen T2_,Reach-1         , 4
Up Type= 0
Dn Type= 3
Dn Slope=0.0094
Boundary for River Rch & Prof#=Little Allen T2_,Reach-1         , 5
Up Type= 0
Dn Type= 3
Dn Slope=0.0094
Boundary for River Rch & Prof#=Little Allen T2_,Reach-1         , 6
Up Type= 0
Dn Type= 3
Dn Slope=0.0094
Boundary for River Rch & Prof#=Little Allen T2_,Reach-1         , 7
Up Type= 0
Dn Type= 3
Dn Slope=0.0094
DSS Import GetInterval= 0
DSS Import GetPeak= 0
DSS Import FillOption= 0

--- Little Allen T2_2.g01 (geometry) ---

Geom Title=Existing Conditions

River Reach=Little Allen T2_,Reach-1
Reach XY= 30
      2728776.00      6945611.00      2728733.75      6945457.58
      2728922.54      6945259.50      2728883.53      6945110.99
      2728931.69      6945008.42      2728977.25      6944964.46
      2729165.95      6944921.05      2729135.14      6944804.25
      2729272.49      6944702.52      2729339.26      6944497.35
      2729449.83      6944438.12      2729522.60      6944318.41
      2729642.61      6944444.86      2729772.17      6944259.42
      2729834.07      6944054.68      2730020.71      6943905.52
      2730042.47      6943794.27      2730169.27      6943670.15
      2730260.59      6943710.86      2730389.63      6943647.56
      2730492.49      6943393.95      2730765.04      6943221.38
      2730683.56      6943011.00      2730724.60      6942950.56
      2730728.25      6942816.93      2730920.88      6942563.29
      2730883.85      6942457.59      2730968.91      6942361.00
      2730833.76      6942217.21      2730826.00      6942161.00

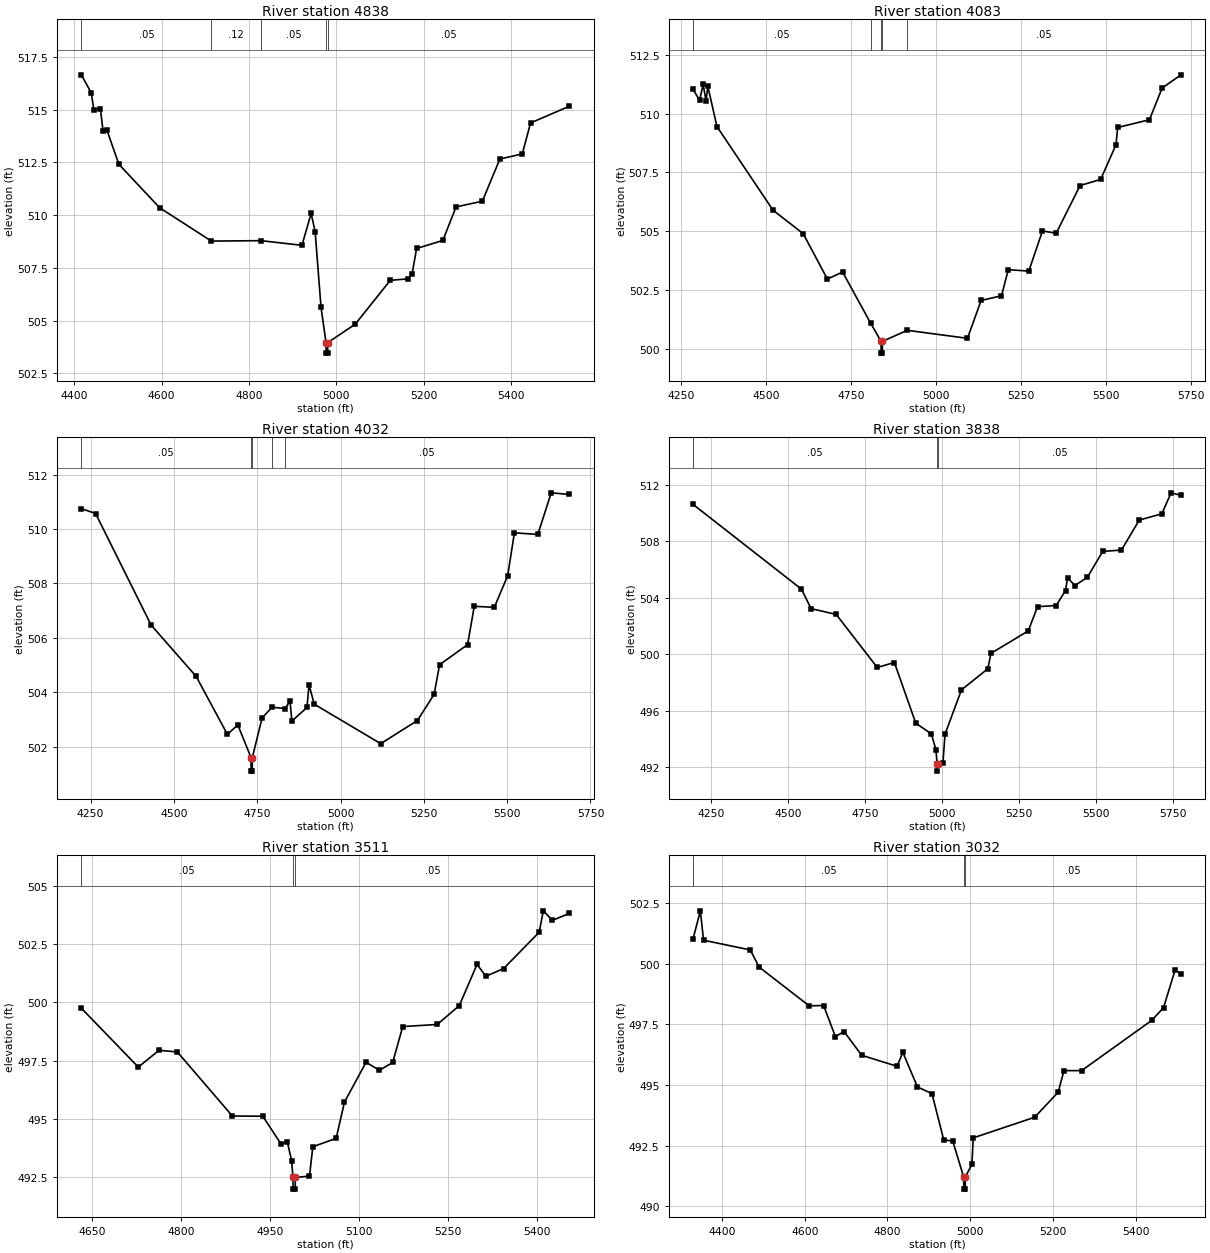
Type RM Length L Ch R = 1,4838,755,755,755
BEGIN DESCRIPTION:
Little Allen T2_2 5.0
END DESCRIPTION:
XS GIS Cut Line= 3
      2729176.00      6945811.00      2728866.48      6945336.20
      2728317.62      6945386.10
#Sta/Elev= 30
  4416.0  516.65  4438.7  515.80  4444.7  514.99  4459.8  515.03  4465.8  513.99
  4474.9  514.02  4502.0  512.41  4595.5  510.35  4713.9  508.77  4827.7  508.79
  4921.5  508.57  4942.5  510.08  4951.7  509.22  4965.1  505.64  4976.6  503.96
  4976.9  503.46  4980.4  503.46  4980.6  503.96  5043.5  504.83  5123.8  506.91
  5164.0  506.98  5174.0  507.23  5184.1  508.42  5244.3  508.80  5274.5  510.39
  5334.7  510.66  5374.9  512.66  5426.2  512.90  5445.2  514.37  5533.9  515.16
#Mann=5,-1,0
  4416.0    0.05       0  4713.9    0.12       0  4827.7    0.05       0
  4976.6    0.04       0  4980.6    0.05       0
Bank Sta=4976.6,4980.6
Exp/Cntr=0.3,0.1

Type RM Length L Ch R = 1,4083,51,51,51
BEGIN DESCRIPTION:
Mapping XS 09e54b1c
END DESCRIPTION:
XS GIS Cut Line= 6
      2729423.82      6945469.19      2729250.20      6944934.45
      2729205.06      6944854.59      2729152.98      6944833.75
      2728930.76      6944833.75      2728430.83      6944885.83
#Sta/Elev= 30
  4285.6  511.04  4304.7  510.56  4315.2  511.24  4323.8  510.54  4329.1  511.16
  4355.8  509.45  4520.8  505.89  4609.6  504.89  4680.6  502.96  4725.3  503.26
  4807.6  501.09  4838.5  500.31  4838.7  499.81  4842.2  499.81  4842.5  500.31
  4915.4  500.78  5092.6  500.44  5132.6  502.05  5192.6  502.25  5212.6  503.36
  5272.9  503.30  5313.1  505.01  5353.4  504.91  5423.7  506.94  5484.1  507.20
  5529.2  508.67  5534.3  509.41  5627.7  509.74  5665.0  511.09  5720.5  511.65
#Mann=5,-1,0
  4285.6    0.05       0  4807.6    0.12       0  4838.5    0.05       0
  4842.5    0.12       0  4915.4    0.05       0
Bank Sta=4838.5,4842.5
Exp/Cntr=0.3,0.1

Type RM Length L Ch R = 1,4032,194,194,194
BEGIN DESCRIPTION:
Mapping XS 2d8c5f76
END DESCRIPTION:
XS GIS Cut Line= 6
      2729455.05      6945462.18      2729298.81      6944920.56
      2729225.90      6944819.86      2729093.95      6944778.20
      2728937.70      6944778.20      2728461.97      6944819.87
#Sta/Elev= 30
  4222.1  510.75  4265.0  510.57  4431.5  506.47  4566.8  504.58  4660.5  502.45
  4691.7  502.80  4731.3  501.60  4731.6  501.10  4735.1  501.10  4735.3  501.60
  4764.5  503.05  4794.4  503.45  4834.0  503.40  4848.4  503.68  4853.9  502.94
  4899.2  503.44  4905.4  504.27  4921.2  503.56  5120.6  502.11  5230.6  502.96
  5280.8  503.92  5297.1  505.01  5381.2  505.75  5401.3  507.16  5461.5  507.12
  5501.7  508.29  5521.7  509.86  5592.0  509.80  5632.2  511.33  5686.4  511.27
#Mann=5,-1,0
  4222.1    0.05       0  4731.3    0.05       0  4735.3    0.05       0
  4794.4    0.12       0  4834.0    0.05       0
Bank Sta=4731.3,4735.3
Exp/Cntr=0.3,0.1

Type RM Length L Ch R = 1,3838,327,327,327
BEGIN DESCRIPTION:
Mapping XS 131a7986
END DESCRIPTION:
XS GIS Cut Line= 5
      2729503.68      6945434.49      2729354.37      6944767.78
      2729288.40      6944674.03      2729212.01      6944642.78
      2728514.11      6944733.06
#Sta/Elev= 30
  4191.3  510.62  4543.3  504.61  4574.4  503.23  4656.0  502.82  4789.2  499.06
  4844.9  499.41  4914.3  495.11  4964.8  494.35  4979.6  493.24  4983.7  492.21
  4983.9  491.71  4987.7  492.21  5002.5  492.30  5009.2  494.32  5062.6  497.47
  5148.3  498.97  5158.4  500.06  5279.4  501.65  5309.7  503.37  5370.2  503.45
  5400.4  504.51  5407.0  505.42  5430.7  504.87  5471.0  505.44  5521.4  507.29
  5581.9  507.38  5639.9  509.51  5713.0  509.95  5743.2  511.44  5775.4  511.26
#Mann=3,-1,0
  4191.3    0.05       0  4983.7   0.035       0  4987.7    0.05       0
Bank Sta=4983.7,4987.7
Exp/Cntr=0.3,0.1

Type RM Length L Ch R = 1,3511,479,479,479
BEGIN DESCRIPTION:
Mapping XS a43ad6cf
END DESCRIPTION:
XS GIS Cut Line= 3
      2729543.38      6944788.37      2729460.05      6944437.70
      2729046.88      6944232.85
#Sta/Elev= 30
  4632.2  499.75  4728.1  497.22  4763.1  497.94  4793.9  497.87  4886.5  495.12
  4937.8  495.11  4968.7  493.91  4979.0  494.02  4986.3  493.20  4988.6  492.48
  4988.8  491.98  4992.3  491.98  4992.6  492.48  5016.4  492.54  5022.0  493.80
  5061.3  494.16  5075.3  495.72  5111.7  497.43  5134.1  497.08  5156.5  497.42
  5173.4  498.96  5231.5  499.05  5268.6  499.86  5298.5  501.63  5313.4  501.12
  5343.2  501.45  5403.1  503.01  5410.1  503.93  5425.5  503.52  5453.8  503.82
#Mann=3,-1,0
  4632.2    0.05       0  4988.6    0.05       0  4992.6    0.05       0
Bank Sta=4988.6,4992.6
Exp/Cntr=0.3,0.1

Type RM Length L Ch R = 1,3032,150,150,150
BEGIN DESCRIPTION:
Mapping XS a0a02572
END DESCRIPTION:
XS GIS Cut Line= 3
      2730168.98      6944843.50      2729724.52      6944340.02
      2729350.26      6943996.95
#Sta/Elev= 30
  4330.1  501.02  4347.8  502.17  4355.4  500.96  4468.3  500.56  4490.0  499.85
  4610.5  498.26  4645.6  498.27  4674.1  496.99  4695.0  497.20  4737.7  496.22
  4823.0  495.77  4837.2  496.34  4872.3  494.92  4907.5  494.64  4935.9  492.74
  4957.7  492.69  4984.1  491.21  4984.4  490.71  4987.9  490.71  4988.1  491.21
  5004.1  491.73  5007.1  492.82  5155.7  493.67  5212.4  494.70  5226.6  495.59
  5269.1  495.59  5438.7  497.66  5467.1  498.18  5495.4  499.75  5509.4  499.56
#Mann=3,-1,0
  4330.1    0.05       0  4984.1    0.05       0  4988.1    0.05       0
Bank Sta=4984.1,4988.1
Exp/Cntr=0.3,0.1

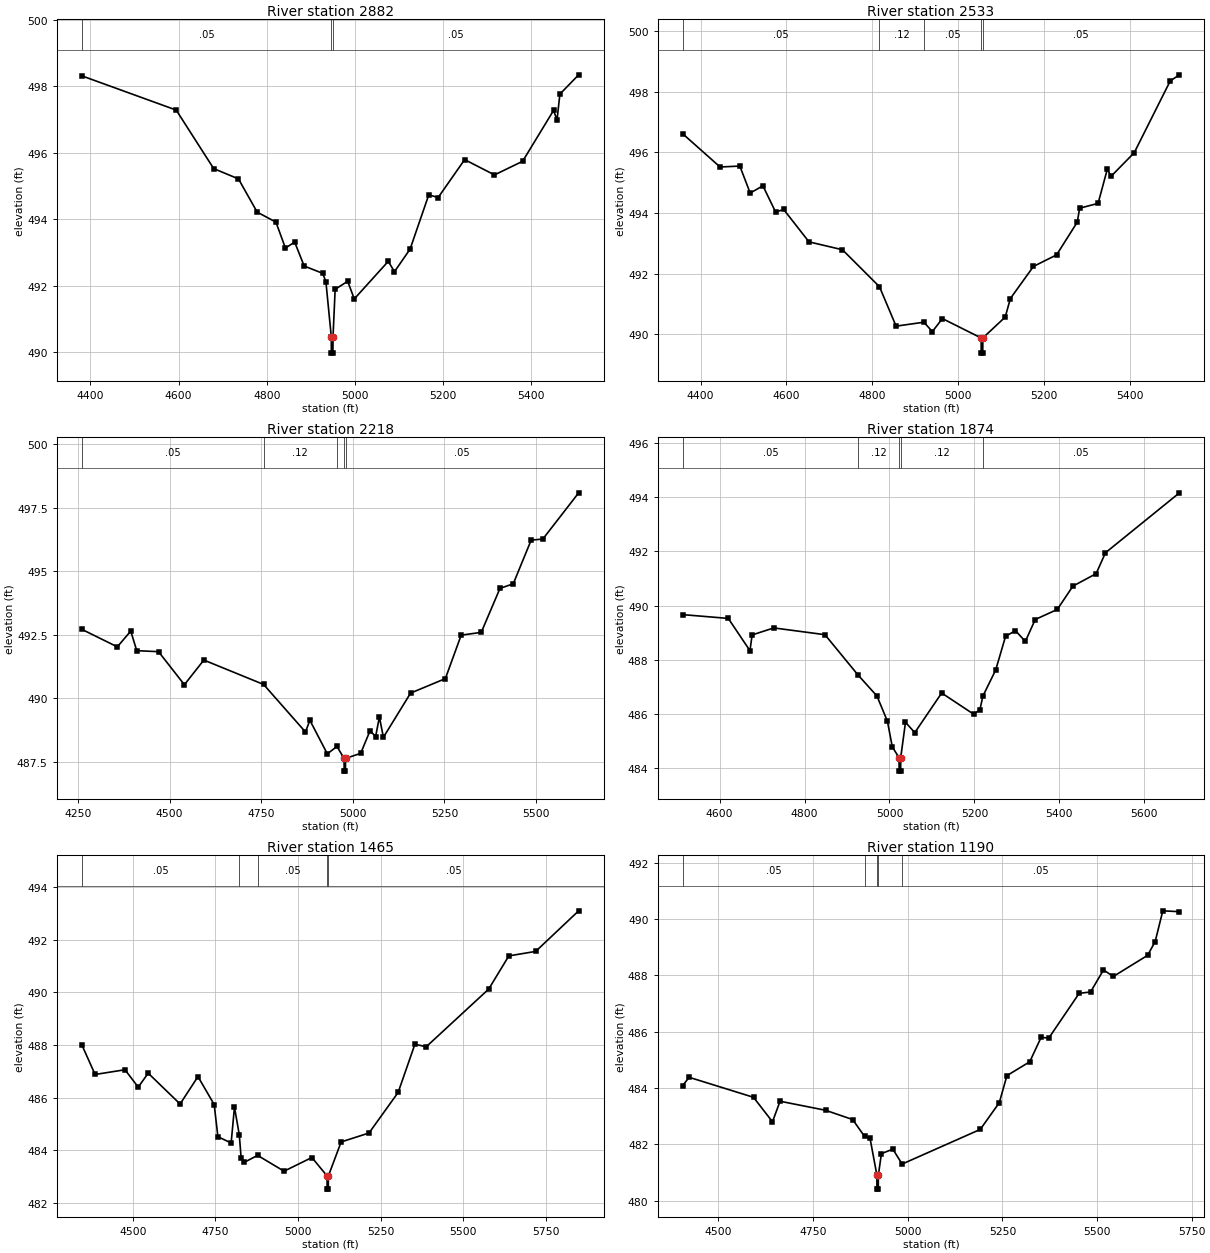
Type RM Length L Ch R = 1,2882,349,349,349
BEGIN DESCRIPTION:
Mapping XS f9b24f58
END DESCRIPTION:
XS GIS Cut Line= 4
      2730200.20      6944659.44      2729780.08      6944211.55
      2729596.05      6944034.46      2729430.17      6943837.49
#Sta/Elev= 30
  4380.2  498.31  4594.4  497.28  4679.4  495.52  4735.6  495.21  4778.1  494.21
  4820.6  493.91  4842.1  493.13  4863.1  493.31  4884.6  492.59  4926.6  492.37
  4933.9  492.12  4946.1  490.47  4946.3  489.97  4949.8  489.97  4950.1  490.47
  4954.9  491.89  4983.3  492.13  4998.3  491.60  5075.3  492.73  5089.5  492.42
  5124.9  493.10  5167.2  494.73  5188.5  494.65  5248.6  495.79  5316.3  495.33
  5380.1  495.74  5450.3  497.27  5458.1  496.98  5464.6  497.76  5507.2  498.34
#Mann=3,-1,0
  4380.2    0.05       0  4946.1    0.05       0  4950.1    0.05       0
Bank Sta=4946.1,4950.1
Exp/Cntr=0.3,0.1

Type RM Length L Ch R = 1,2533,315,315,315
BEGIN DESCRIPTION:
Mapping XS b8ef0f89
END DESCRIPTION:
XS GIS Cut Line= 3
      2730189.96      6944532.04      2729950.36      6943938.25
      2729469.82      6943748.64
#Sta/Elev= 30
  4358.0  496.62  4445.4  495.52  4491.4  495.55  4515.5  494.66  4545.1  494.90
  4574.8  494.03  4593.4  494.12  4652.4  493.05  4730.3  492.79  4816.5  491.57
  4855.2  490.27  4919.9  490.40  4939.6  490.09  4963.0  490.52  5053.2  489.88
  5053.4  489.38  5056.9  489.38  5057.2  489.88  5109.3  490.57  5121.2  491.18
  5175.0  492.24  5228.8  492.62  5277.0  493.70  5282.5  494.16  5325.5  494.32
  5347.0  495.45  5355.5  495.21  5409.6  495.99  5493.5  498.36  5514.9  498.56
#Mann=5,-1,0
  4358.0    0.05       0  4816.5    0.12       0  4919.9    0.05       0
  5053.2    0.04       0  5057.2    0.05       0
Bank Sta=5053.2,5057.2
Exp/Cntr=0.3,0.1

Type RM Length L Ch R = 1,2218,344,344,344
BEGIN DESCRIPTION:
Mapping XS 8189bfbc
END DESCRIPTION:
XS GIS Cut Line= 3
      2730418.75      6944384.41      2730140.98      6943717.77
      2729543.82      6943505.98
#Sta/Elev= 30
  4260.4  492.71  4357.4  492.02  4394.1  492.64  4410.4  491.87  4469.9  491.83
  4540.4  490.53  4593.5  491.50  4756.6  490.54  4870.8  488.67  4882.8  489.13
  4930.4  487.81  4956.7  488.10  4976.1  487.63  4976.4  487.13  4979.9  487.13
  4980.1  487.63  5021.4  487.83  5047.0  488.72  5062.2  488.49  5072.5  489.26
  5083.4  488.46  5157.6  490.20  5252.5  490.77  5295.6  492.48  5350.4  492.59
  5401.5  494.32  5437.7  494.50  5486.6  496.22  5518.4  496.26  5616.2  498.08
#Mann=5,-1,0
  4260.4    0.05       0  4756.6    0.12       0  4956.7    0.05       0
  4976.1    0.04       0  4980.1    0.05       0
Bank Sta=4976.1,4980.1
Exp/Cntr=0.3,0.1

Type RM Length L Ch R = 1,1874,409,409,409
BEGIN DESCRIPTION:
Mapping XS 6b35a76a
END DESCRIPTION:
XS GIS Cut Line= 3
      2730512.51      6944099.69      2730418.76      6943630.96
      2729786.83      6943349.72
#Sta/Elev= 30
  4512.9  489.67  4620.6  489.53  4671.6  488.34  4676.7  488.92  4727.7  489.18
  4848.1  488.93  4926.2  487.44  4970.5  486.67  4995.2  485.74  5006.7  484.79
  5022.5  484.40  5022.8  483.90  5026.3  483.90  5026.5  484.40  5037.7  485.70
  5059.6  485.32  5122.9  486.78  5198.1  486.00  5212.8  486.16  5220.0  486.67
  5250.1  487.63  5273.3  488.87  5296.6  489.08  5319.8  488.68  5343.1  489.49
  5395.0  489.86  5431.8  490.72  5486.5  491.18  5508.4  491.95  5682.6  494.16
#Mann=5,-1,0
  4512.9    0.05       0  4926.2    0.12       0  5022.5    0.07       0
  5026.5    0.12       0  5220.0    0.05       0
Bank Sta=5022.5,5026.5
Exp/Cntr=0.3,0.1

Type RM Length L Ch R = 1,1465,275,275,275
BEGIN DESCRIPTION:
Mapping XS ddfdaaf8
END DESCRIPTION:
XS GIS Cut Line= 3
      2730679.18      6943971.23      2730616.68      6943311.52
      2729787.75      6943165.85
#Sta/Elev= 30
  4345.6  488.01  4386.0  486.88  4476.4  487.06  4516.6  486.40  4546.7  486.93
  4643.3  485.76  4697.4  486.80  4746.5  485.74  4757.7  484.52  4797.8  484.28
  4807.9  485.64  4822.5  484.59  4828.0  483.72  4838.0  483.55  4878.0  483.81
  4958.0  483.21  5042.3  483.73  5088.2  483.03  5088.4  482.53  5091.9  482.53
  5092.2  483.03  5130.8  484.32  5215.3  484.66  5303.4  486.20  5354.2  488.03
  5388.3  487.93  5577.5  490.12  5638.5  491.38  5719.7  491.55  5849.9  493.09
#Mann=5,-1,0
  4345.6    0.05       0  4822.5    0.12       0  4878.0    0.05       0
  5088.2    0.04       0  5092.2    0.05       0
Bank Sta=5088.2,5092.2
Exp/Cntr=0.3,0.1

Type RM Length L Ch R = 1,1190,344,344,344
BEGIN DESCRIPTION:
Mapping XS eccc73e2
END DESCRIPTION:
XS GIS Cut Line= 3
      2730886.79      6943608.44      2730871.60      6943159.20
      2730012.24      6943076.74
#Sta/Elev= 30
  4405.0  484.08  4422.4  484.38  4592.5  483.67  4642.6  482.80  4662.6  483.53
  4782.7  483.21  4854.5  482.88  4885.9  482.28  4900.3  482.22  4918.4  480.91
  4918.6  480.41  4922.1  480.41  4922.4  480.91  4930.4  481.67  4960.6  481.83
  4985.1  481.30  5191.6  482.53  5241.9  483.48  5262.0  484.44  5322.2  484.93
  5352.4  485.80  5372.5  485.77  5452.8  487.36  5483.0  487.41  5517.1  488.19
  5543.2  487.96  5633.7  488.71  5653.7  489.20  5673.8  490.29  5717.8  490.26
#Mann=5,-1,0
  4405.0    0.05       0  4885.9    0.12       0  4918.4    0.04       0
  4922.4    0.12       0  4985.1    0.05       0
Bank Sta=4918.4,4922.4
Exp/Cntr=0.3,0.1

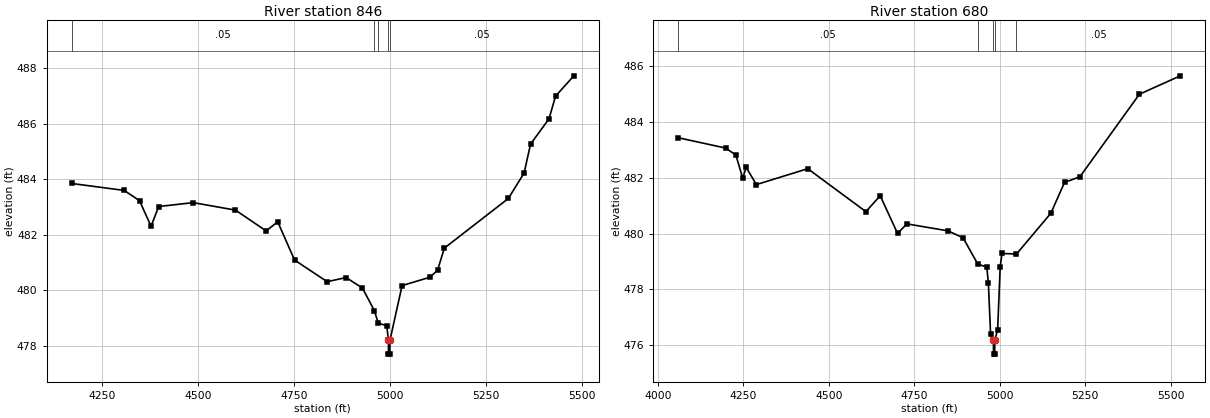
Type RM Length L Ch R = 1,846,166,166,166
BEGIN DESCRIPTION:
Mapping XS 1fdbf6c6
END DESCRIPTION:
XS GIS Cut Line= 4
      2730922.38      6943577.60      2730911.96      6943002.08
      2730724.46      6942827.60      2730259.63      6942721.13
#Sta/Elev= 30
  4170.7  483.84  4307.3  483.59  4347.3  483.22  4377.3  482.30  4397.3  483.01
  4487.3  483.15  4597.4  482.88  4677.4  482.13  4707.4  482.46  4751.4  481.08
  4836.4  480.30  4885.8  480.45  4928.3  480.07  4959.3  479.26  4969.4  478.81
  4991.8  478.71  4996.0  478.19  4996.2  477.69  4999.7  477.69  5000.0  478.19
  5031.6  480.16  5103.9  480.46  5124.0  480.71  5141.7  481.51  5308.6  483.30
  5349.7  484.22  5366.5  485.26  5414.5  486.17  5431.7  486.99  5479.3  487.72
#Mann=5,-1,0
  4170.7    0.05       0  4959.3    0.12       0  4969.4    0.05       0
  4996.0    0.04       0  5000.0    0.05       0
Bank Sta=4996,5000
Exp/Cntr=0.3,0.1

Type RM Length L Ch R = 1,680,0,0,0
BEGIN DESCRIPTION:
Little Allen T2_2 1.0
END DESCRIPTION:
XS GIS Cut Line= 4
      2730961.44      6943559.41      2730987.48      6942973.44
      2730839.95      6942697.79      2730290.51      6942547.95
#Sta/Elev= 30
  4059.1  483.44  4197.6  483.07  4227.7  482.82  4247.7  481.99  4257.7  482.38
  4287.7  481.76  4437.9  482.33  4608.1  480.79  4649.9  481.36  4700.6  480.01
  4728.2  480.35  4848.5  480.10  4892.4  479.85  4935.3  478.91  4961.7  478.80
  4966.3  478.24  4972.8  476.39  4981.1  476.18  4981.4  475.68  4984.9  475.68
  4985.1  476.18  4993.5  476.56  5000.9  478.81  5006.1  479.29  5048.6  479.27
  5149.0  480.73  5189.2  481.84  5234.1  482.04  5408.1  485.00  5527.8  485.66
#Mann=5,-1,0
  4059.1    0.05       0  4935.3    0.12       0  4981.1    0.07       0
  4985.1    0.12       0  5048.6    0.05       0
Bank Sta=4981.1,4985.1
Exp/Cntr=0.3,0.1

Chan Stop Cuts=-1