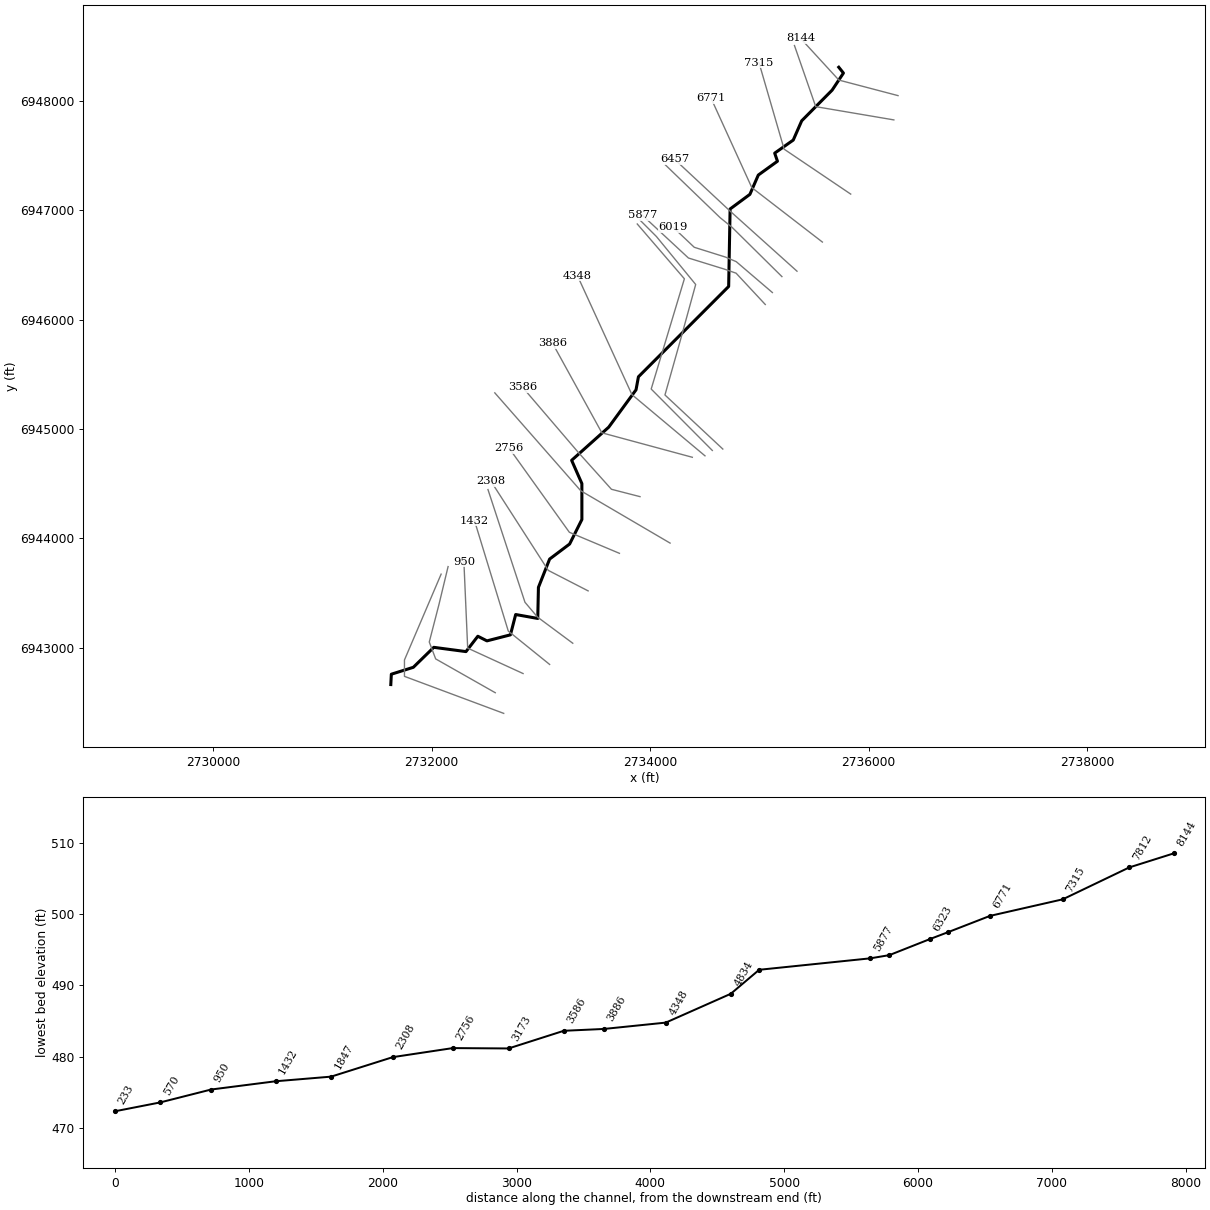
--- Little Allen T2_3.prj (project) ---

Proj Title=Little Allen T2_3 Base Level Engineering
Current Plan=p01
Default Exp/Contr=0.3,0.1
English Units
Geom File=g01
Flow File=f01
Plan File=p01
Y Axis Title=Elevation
X Axis Title(PF)=Main Channel Distance
X Axis Title(XS)=Station
BEGIN DESCRIPTION:
Little Allen T2_3
END DESCRIPTION:
DSS Export Rating Curves= 0
DSS Export Rating Curve Sorted= 0
DSS Export Volume Flow Curves= 0
DXF OffsetX= 0
DXF OffsetY= 0
DXF ScaleX= 1
DXF ScaleY= 10

--- Little Allen T2_3.p01 (plan) ---

Plan Title=Multiple Run
Short Identifier=Multiple
Geom File=g01
Flow File=f01
Subcritical Flow
K Sum by GR= 0
Std Step Tol= 0.01
Critical Tol= 0.01
Num of Std Step Trials= 20
Max Error Tol= 0.3
Flow Tol Ratio= 0.001
Split Flow NTrial= 30
Split Flow Tol= 0.02
Split Flow Ratio= 0.02
Log Output Level= 0
Friction Slope Method= 1
Unsteady Friction Slope Method= 2
Unsteady Bridges Friction Slope Method= 1
Parabolic Critical Depth
Global Vel Dist=  1 , 1 , 1
Global Log Level= 0
CheckData=True
Encroach Param= -1, 0, 0, 0
BEGIN DESCRIPTION:
Multiple Run
END DESCRIPTION:

--- Little Allen T2_3.f01 (steady flow) ---

Flow Title=Multiple
Number of Profiles=7
Profile Names=10-year,25-year,50-year,1pct_min,100-year,1pct_plu,500-year
River Rch & RM= Little Allen T2_,Reach-1,8144
     415     540     638     375     749    1494    1028
River Rch & RM= Little Allen T2_,Reach-1,5046
     654     874    1050     626    1250    2494    1768
Boundary for River Rch & Prof#=Little Allen T2_,Reach-1,1
Up Type=0
Dn Type=3
Dn Slope=0.005
Boundary for River Rch & Prof#=Little Allen T2_,Reach-1,2
Up Type=0
Dn Type=3
Dn Slope=0.005
Boundary for River Rch & Prof#=Little Allen T2_,Reach-1,3
Up Type=0
Dn Type=3
Dn Slope=0.005
Boundary for River Rch & Prof#=Little Allen T2_,Reach-1,4
Up Type=0
Dn Type=3
Dn Slope=0.005
Boundary for River Rch & Prof#=Little Allen T2_,Reach-1,5
Up Type=0
Dn Type=3
Dn Slope=0.005
Boundary for River Rch & Prof#=Little Allen T2_,Reach-1,6
Up Type=0
Dn Type=3
Dn Slope=0.005
Boundary for River Rch & Prof#=Little Allen T2_,Reach-1,7
Up Type=0
Dn Type=3
Dn Slope=0.005

--- Little Allen T2_3.g01 (geometry) ---

Geom Title=Existing Conditions
Program Version=4.10

River Reach=Little Allen T2_,Reach-1
Reach XY= 30
        2735726.        6948311.      2735768.73      6948257.67
      2735665.22      6948101.32      2735386.76      6947820.68
      2735309.37      6947644.29      2735139.51      6947524.68
      2735164.89      6947450.69      2734989.61      6947324.24
      2734912.53      6947147.43      2734731.45      6947013.47
      2734718.26      6946304.54      2733892.46      6945477.75
      2733870.48      6945358.57      2733620.38      6945016.62
      2733281.09       6944713.3       2733374.8       6944500.5
      2733374.94      6944171.44      2733262.74      6943947.35
      2733079.61      6943809.52       2732977.2       6943550.5
        2732971.      6943265.99      2732768.93      6943302.01
      2732720.99      6943116.01      2732505.79      6943060.79
      2732422.58      6943103.19      2732314.17      6942962.63
      2732019.33      6943001.61      2731832.19      6942818.86
      2731630.98      6942755.73        2731626.        6942661.

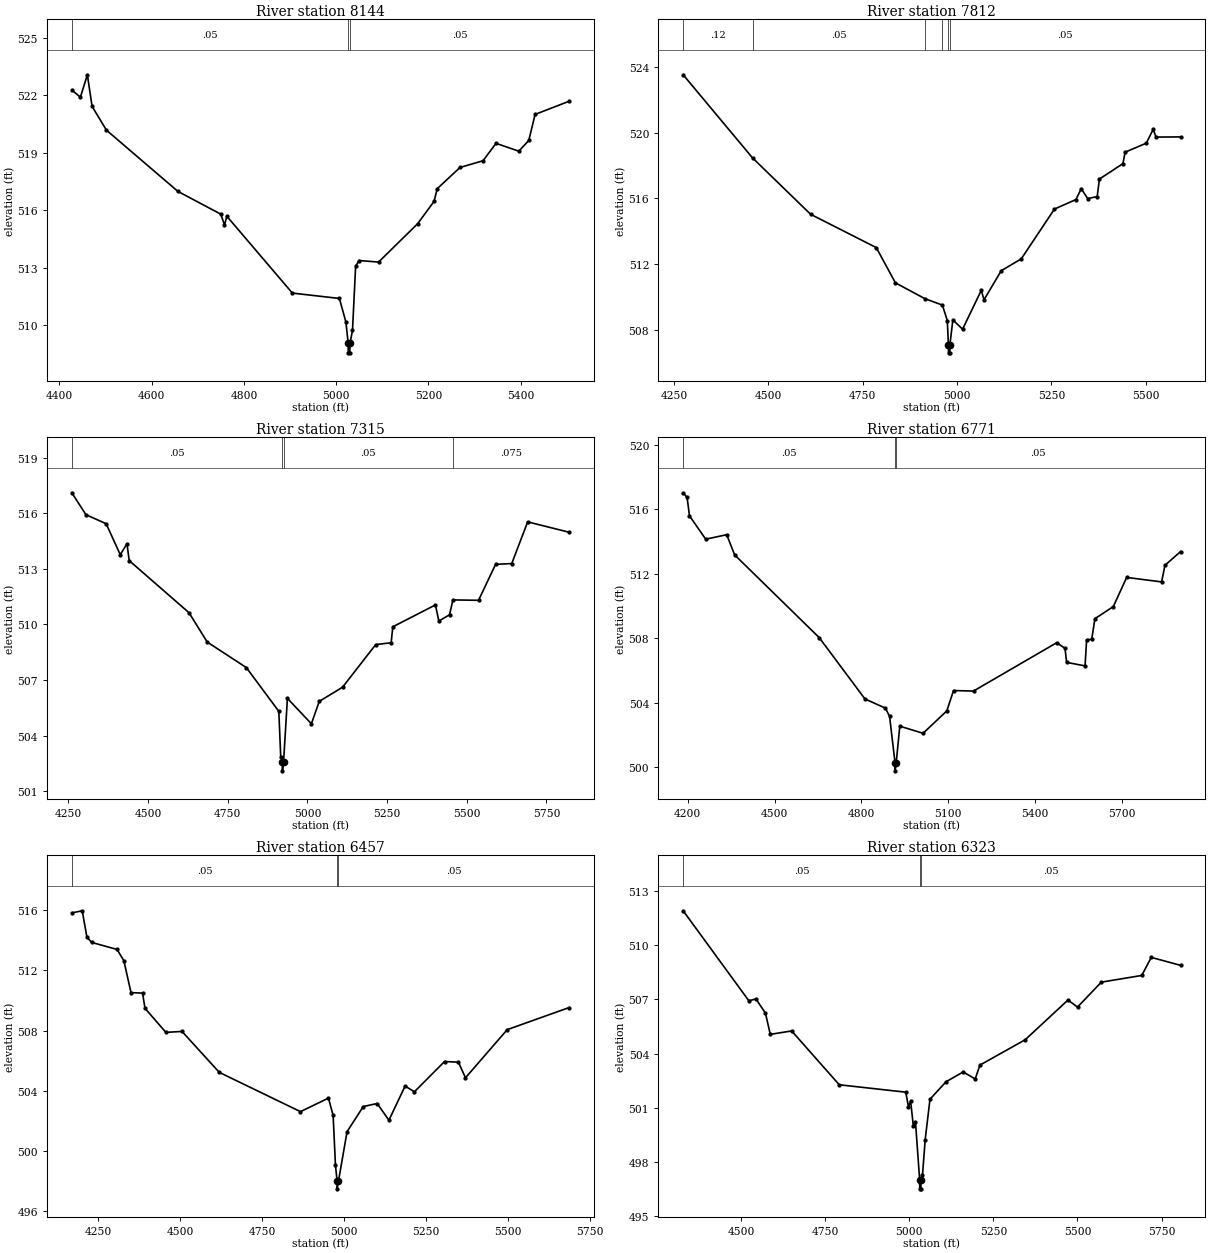
Type RM Length L Ch R = 1 ,8144    ,332,332,332
BEGIN DESCRIPTION:
Little Allen T2_3 15.0
END DESCRIPTION:
XS GIS Cut Line= 3
      2736268.46      6948051.16       2735726.8      6948193.52
      2735376.09      6948575.47
#Sta/Elev= 30
  4426.9  522.27  4445.5   521.9  4460.5  523.07  4470.8  521.42  4501.8  520.18
  4656.9  516.98    4750  515.79  4757.9  515.23  4763.1  515.68  4905.1  511.67
  5007.1  511.39  5021.3  510.15  5026.1  509.05  5026.3  508.55  5029.8  508.55
  5030.1  509.05  5035.5  509.72  5042.3  513.07  5049.7  513.37  5092.1  513.29
  5176.7  515.29  5212.4  516.46  5219.2  517.12  5268.6  518.23  5318.5  518.58
  5346.8  519.49  5396.2  519.08  5417.8  519.64  5431.5     521  5505.5  521.69
#Mann= 3 ,-1 , 0
  4426.9     .05       0  5026.1     .04       0  5030.1     .05       0
Bank Sta=5026.1,5030.1
XS Rating Curve= 0 ,0
Exp/Cntr=0.3,0.1

Type RM Length L Ch R = 1 ,7812    ,497,497,497
BEGIN DESCRIPTION:
Little Allen T2_3 14.0
END DESCRIPTION:
XS GIS Cut Line= 3
       2736230.3      6947828.93      2735515.22      6947950.24
      2735320.53      6948509.52
#Sta/Elev= 30
  4274.7  523.54  4458.4  518.47  4612.3  515.03  4786.2     513  4836.9  510.85
  4914.5  509.89  4961.4  509.49  4974.3  508.55  4977.3  507.08  4977.6  506.58
  4981.1  506.58  4981.3  507.08  4989.1  508.59  5014.8  508.02  5064.3  510.39
  5071.7  509.82  5117.3  511.59  5170.2  512.31  5258.2  515.35  5315.1  515.93
  5329.1  516.59  5346.2  515.99  5371.4  516.11  5377.3  517.18  5439.5  518.12
  5445.5  518.82  5501.6  519.37  5519.6  520.21  5527.4  519.74  5592.2  519.75
#Mann= 6 ,-1 , 0
  4274.7     .12       0  4458.4     .05       0  4914.5     .12       0
  4961.4     .05       0  4977.3     .04       0  4981.3     .05       0
Bank Sta=4977.3,4981.3
XS Rating Curve= 0 ,0
Exp/Cntr=0.3,0.1

Type RM Length L Ch R = 1 ,7315    ,544,544,544
BEGIN DESCRIPTION:
Little Allen T2_3 13.0
END DESCRIPTION:
XS GIS Cut Line= 3
      2735835.28      6947149.85        2735226.        6947561.
      2734995.46      6948354.25
#Sta/Elev= 30
  4260.6   517.1  4304.7  515.92  4368.3  515.43  4412.6  513.76  4433.6  514.35
  4440.7  513.44  4628.4  510.63  4685.4  509.05  4808.3  507.67  4910.2  505.31
  4916.2  502.86  4921.2   502.6  4921.5   502.1  4925.2   502.6  4937.2  506.01
  5012.4  504.64  5037.3  505.85  5110.2  506.61  5214.3  508.91  5262.8  509.01
    5268  509.87  5401.8  511.05  5412.5  510.18  5446.1  510.52  5456.6  511.32
  5537.1   511.3  5590.6  513.24  5641.3  513.28  5691.2  515.53  5821.7  514.97
#Mann= 4 ,-1 , 0
  4260.6     .05       0  4921.2     .04       0  4925.2     .05       0
  5456.6    .075       0
Bank Sta=4921.2,4925.2
XS Rating Curve= 0 ,0
Exp/Cntr=0.3,0.1

Type RM Length L Ch R = 1 ,6771    ,314,314,314
BEGIN DESCRIPTION:
Little Allen T2_3 12.0
END DESCRIPTION:
XS GIS Cut Line= 3
      2735576.03      6946710.97       2734930.2      6947209.24
      2734555.93      6948030.03
#Sta/Elev= 30
  4184.3  517.02  4197.9  516.73  4206.1  515.59  4262.2  514.14  4334.7  514.42
  4361.9  513.17  4654.4  508.03  4812.1  504.23  4882.7  503.66  4897.2  503.15
    4916  500.27  4916.3  499.77    4920  500.27  4932.5  502.54  5012.9   502.1
  5094.9  503.49    5118  504.75  5187.1  504.72  5474.5  507.72  5503.1  507.37
  5508.6   506.5  5572.3  506.28  5577.7   507.9  5595.3  507.93  5606.4  509.21
  5669.9  509.96    5716  511.77  5836.7  511.49  5848.2  512.52  5902.1  513.37
#Mann= 3 ,-1 , 0
  4184.3     .05       0    4916     .05       0    4920     .05       0
Bank Sta=4916,4920
XS Rating Curve= 0 ,0
Exp/Cntr=0.3,0.1

Type RM Length L Ch R = 1 ,6457    ,134,134,134
BEGIN DESCRIPTION:
Mapping XS 6f8ae1e2
END DESCRIPTION:
XS GIS Cut Line= 3
      2735343.72      6946444.22      2734729.11      6946996.33
       2734224.8      6947466.84
#Sta/Elev= 30
  4170.6  515.82  4202.2  515.96  4216.4  514.22  4230.6  513.86  4308.3  513.39
  4329.2  512.64  4350.9  510.52  4386.1  510.49  4393.5  509.48  4457.1  507.88
  4506.4  507.94    4620  505.22  4867.4  502.61  4952.7  503.51  4966.9  502.36
  4974.1  499.04  4979.1  497.98  4979.3  497.48  4983.1  497.98  5009.4  501.28
  5058.8  502.95  5101.3  503.15  5136.9  502.04  5186.3  504.31  5214.6  503.93
  5306.4  505.94  5348.9   505.9  5370.3  504.86  5497.5  508.06  5686.5  509.53
#Mann= 3 ,-1 , 0
  4170.6     .05       0  4979.1     .05       0  4983.1     .05       0
Bank Sta=4979.1,4983.1
XS Rating Curve= 0 ,0
Exp/Cntr=0.3,0.1

Type RM Length L Ch R = 1 ,6323    ,304,304,304
BEGIN DESCRIPTION:
Mapping XS bf56dd15
END DESCRIPTION:
XS GIS Cut Line= 4
      2735205.68      6946394.75      2734749.94      6946845.29
      2734640.57      6946933.83       2734139.1       6947417.1
#Sta/Elev= 30
  4328.3  511.91  4523.4  506.93  4544.6  507.03  4572.9  506.24  4587.1  505.07
  4650.7  505.26  4792.1  502.28  4989.8  501.87  4997.8  501.06  5004.2  501.37
  5012.2  500.01  5018.6  500.24    5031  497.02  5031.2  496.52  5034.7  496.52
    5035  497.02  5039.4  497.26  5047.4  499.23  5061.7  501.48  5109.6  502.45
  5160.5  502.99    5196   502.6  5210.2  503.37  5344.5  504.77  5471.8  506.97
  5500.1  506.58  5570.9  507.96    5691  508.33  5719.3  509.33  5806.3  508.89
#Mann= 3 ,-1 , 0
  4328.3     .05       0    5031     .05       0    5035     .05       0
Bank Sta=5031,5035
XS Rating Curve= 0 ,0
Exp/Cntr=0.3,0.1

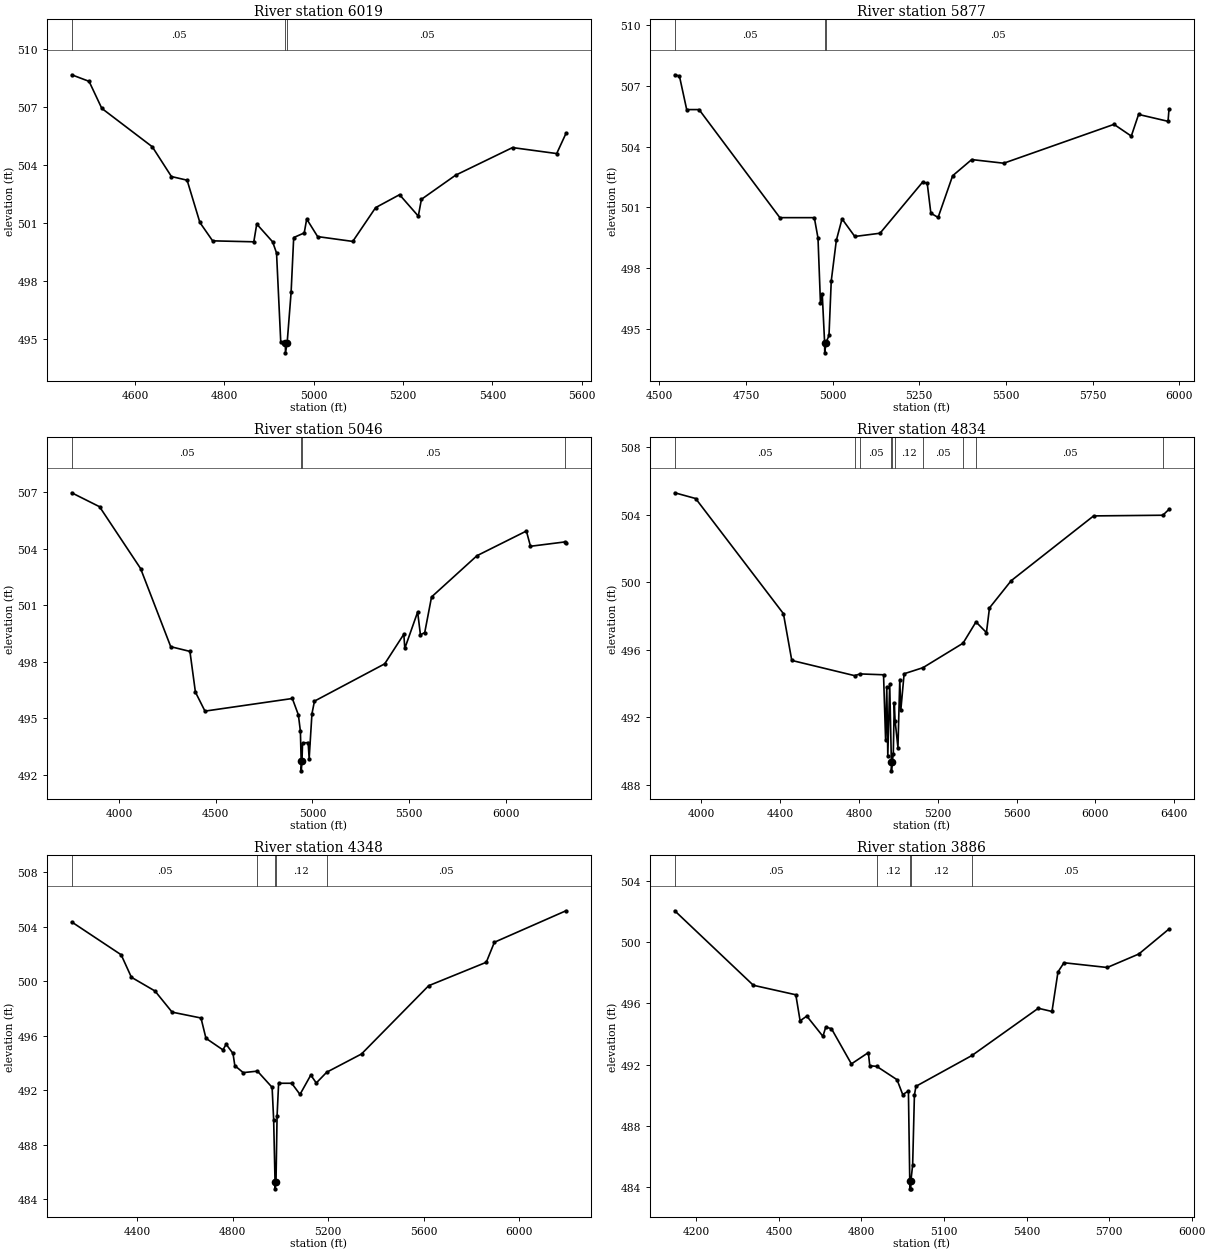
Type RM Length L Ch R = 1 ,6019    ,142,142,142
BEGIN DESCRIPTION:
Mapping XS 71659ed3
END DESCRIPTION:
XS GIS Cut Line= 5
      2735118.42      6946248.94       2734787.7      6946531.48
      2734690.05      6946573.15      2734403.59      6946662.99
      2734210.98       6946845.2
#Sta/Elev= 30
  4458.1  508.66    4497  508.32  4525.5  506.92  4638.6  504.93  4681.4  503.39
  4716.5   503.2  4745.1  501.01  4773.6  500.06  4865.8  500.01  4872.4  500.93
  4907.9  500.01  4916.7  499.43  4926.1  494.84  4936.4  494.76  4936.7  494.26
  4940.4  494.76  4949.3  497.39  4955.1  500.23  4978.7  500.47  4984.2  501.19
  5008.7  500.28  5087.3  500.03  5138.5  501.78  5192.1  502.45  5234.1  501.34
    5241  502.21  5317.6  503.46    5445  504.89  5543.9  504.58  5564.6  505.62
#Mann= 3 ,-1 , 0
  4458.1     .05       0  4936.4     .05       0  4940.4     .05       0
Bank Sta=4936.4,4940.4
XS Rating Curve= 0 ,0
Exp/Cntr=0.3,0.1

Type RM Length L Ch R = 1 ,5877    ,831,831,831
BEGIN DESCRIPTION:
Mapping XS 0014c645
END DESCRIPTION:
XS GIS Cut Line= 5
      2735053.35      6946139.53       2734786.4      6946426.02
      2734680.06      6946462.91       2734350.2       6946564.9
      2733927.97      6946956.83
#Sta/Elev= 30
  4544.8  507.55  4558.3  507.49  4579.3  505.83    4615  505.83    4848  500.49
  4947.4  500.49    4958  499.48  4965.1  496.27  4970.3   496.7  4977.1  494.31
  4977.4  493.81  4981.1  494.31  4989.7  494.67  4996.2  497.36  5010.9  499.37
  5027.3  500.43  5064.1  499.56  5136.9  499.72  5259.9  502.25    5273  502.19
  5283.5  500.71  5304.4   500.5  5346.3  502.56  5401.3  503.36  5493.7  503.18
  5811.7   505.1  5861.6  504.52  5882.6  505.59  5967.6  505.25  5970.3  505.84
#Mann= 3 ,-1 , 0
  4544.8     .05       0  4977.1     .05       0  4981.1     .05       0
Bank Sta=4977.1,4981.1
XS Rating Curve= 0 ,0
Exp/Cntr=0.3,0.1

Type RM Length L Ch R = 1 ,5046    ,212,212,212
BEGIN DESCRIPTION:
Mapping XS f32995dd
END DESCRIPTION:
XS GIS Cut Line= 6
      2734664.76      6944816.47      2734135.22      6945311.29
      2734276.02      6945810.98      2734416.47      6946322.57
      2734057.09      6946761.66      2733907.34      6946911.41
#Sta/Elev= 30
  3756.1  506.96    3900  506.22    4112  502.94  4267.8  498.79    4367  498.54
  4395.3  496.38  4444.7  495.37  4896.1  496.04  4927.3  495.17  4937.7   494.3
  4941.8   492.7    4942   492.2  4945.8   492.7  4948.9  493.68  4977.8   493.7
    4983  492.85  4997.4  495.23  5010.4   495.9  5373.3  497.88    5472  499.45
  5477.2   498.7  5543.5  500.63  5557.9  499.42  5580.1  499.54  5615.3  501.43
    5850  503.62  6105.3  504.93  6126.5  504.12  6303.3  504.35  6309.7  504.27
#Mann= 4 ,-1 , 0
  3756.1     .05       0  4941.8     .05       0  4945.8     .05       0
  6303.3     .12       0
Bank Sta=4941.8,4945.8
XS Rating Curve= 0 ,0
Exp/Cntr=0.3,0.1

Type RM Length L Ch R = 1 ,4834    ,486,486,486
BEGIN DESCRIPTION:
Mapping XS ed34678d
END DESCRIPTION:
XS GIS Cut Line= 4
      2734568.68      6944803.61       2734009.2      6945365.69
      2734313.02       6946374.8      2733881.74      6946876.22
#Sta/Elev= 30
  3865.3   505.3  3971.4  504.96  4416.9  498.14  4459.3  495.37  4777.6  494.47
  4806.7  494.57    4925  494.52  4935.4  490.66  4941.4   493.8  4946.6   489.7
  4956.3  493.95  4964.8  489.33    4965  488.83  4968.8  489.33  4974.4  489.83
  4979.6  492.85  4983.5  491.81  4998.1   490.2  5007.4  494.24  5012.6  492.42
  5029.4  494.58    5125  494.94  5328.4  496.39  5394.1  497.65  5447.2  497.02
  5462.6  498.48  5572.5  500.09  5991.1  503.93  6342.4  503.97  6373.6  504.32
#Mann= 10 ,-1 , 0
  3865.3     .05       0  4777.6     .12       0  4806.7     .05       0
  4964.8     .07       0  4968.8     .05       0  4983.5     .12       0
    5125     .05       0  5328.4     .12       0  5394.1     .05       0
  6342.4     .12       0
Bank Sta=4964.8,4968.8
XS Rating Curve= 0 ,0
Exp/Cntr=0.3,0.1

Type RM Length L Ch R = 1 ,4348    ,462,462,462
BEGIN DESCRIPTION:
Mapping XS 2bd42e46
END DESCRIPTION:
XS GIS Cut Line= 3
      2734501.58      6944754.41      2733833.16      6945314.33
      2733334.01      6946403.78
#Sta/Elev= 30
  4125.5  504.37  4332.7  501.96  4375.6  500.31  4474.5   499.3  4546.1  497.75
  4667.1  497.32  4687.9  495.83  4758.9  494.98  4772.5  495.39  4801.1  494.72
  4808.9  493.82    4844  493.31  4903.5  493.42    4965  492.23  4971.5  489.84
  4977.3  485.28  4977.6  484.78  4981.3  485.28  4985.8  490.13  4992.3  492.53
    5047  492.53  5081.8  491.71    5127  493.13    5150  492.55  5193.7  493.34
  5339.5  494.68  5620.8  499.69  5862.1  501.41  5896.1  502.88  6195.8  505.19
#Mann= 5 ,-1 , 0
  4125.5     .05       0  4903.5     .12       0  4977.3     .07       0
  4981.3     .12       0  5193.7     .05       0
Bank Sta=4977.3,4981.3
XS Rating Curve= 0 ,0
Exp/Cntr=0.3,0.1

Type RM Length L Ch R = 1 ,3886    ,300,300,300
BEGIN DESCRIPTION:
Mapping XS 19003e78
END DESCRIPTION:
XS GIS Cut Line= 3
      2734385.78      6944741.13       2733557.7      6944965.08
      2733105.13      6945786.98
#Sta/Elev= 30
  4121.5  502.03  4407.2  497.17  4561.5  496.55  4577.1  494.85  4601.4  495.16
    4660  493.84  4670.3  494.44    4691  494.34  4763.5  492.04  4825.1  492.78
  4830.3  491.92  4855.5  491.88  4929.3  491.01    4950  490.04  4970.7  490.27
  4975.6  484.39  4975.9  483.89  4979.4  483.89  4979.6  484.39  4986.1  485.45
  4992.5  490.01  4998.2  490.58  5201.6  492.59  5442.7  495.67  5492.4  495.46
  5514.2  498.04    5536  498.64  5693.1  498.33    5808  499.21  5917.6  500.84
#Mann= 5 ,-1 , 0
  4121.5     .05       0  4855.5     .12       0  4975.6     .07       0
  4979.6     .12       0  5201.6     .05       0
Bank Sta=4975.6,4979.6
XS Rating Curve= 0 ,0
Exp/Cntr=0.3,0.1

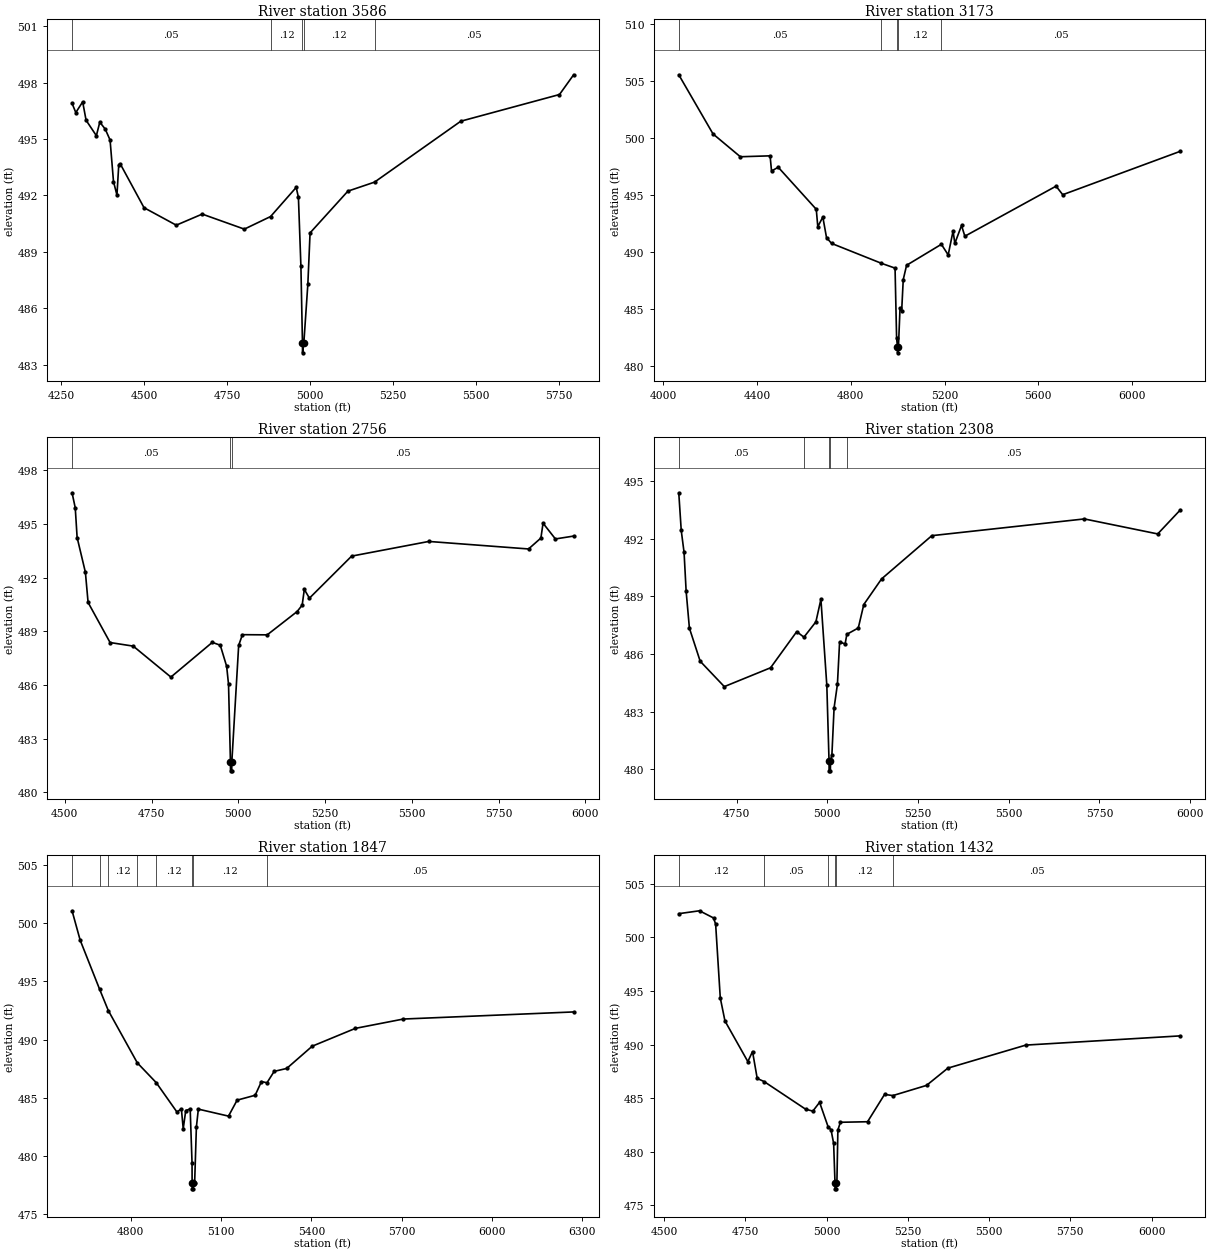
Type RM Length L Ch R = 1 ,3586    ,413,413,413
BEGIN DESCRIPTION:
Mapping XS 197e87a4
END DESCRIPTION:
XS GIS Cut Line= 4
      2733906.98      6944380.81      2733645.43      6944448.22
       2733337.1      6944791.61       2732829.9      6945384.46
#Sta/Elev= 30
  4282.1   496.9  4293.4  496.41  4314.1  496.98  4324.4     496  4355.4  495.18
  4365.7   495.9  4382.1  495.53  4396.7  494.95    4407  492.74  4417.4  492.02
  4422.8  493.61    4428  493.66    4499  491.35  4596.2  490.42  4674.4  491.01
  4801.4  490.21  4880.5  490.88  4957.7  492.43  4964.4   491.9  4971.9  488.24
  4976.6  484.13  4976.8  483.63  4980.6  484.13  4992.8  487.28  4999.5  490.01
  5113.5  492.23  5193.8  492.71  5453.8  495.95  5751.3  497.37  5793.9  498.42
#Mann= 5 ,-1 , 0
  4282.1     .05       0  4880.5     .12       0  4976.6     .07       0
  4980.6     .12       0  5193.8     .05       0
Bank Sta=4976.6,4980.6
XS Rating Curve= 0 ,0
Exp/Cntr=0.3,0.1

Type RM Length L Ch R = 1 ,3173    ,417,417,417
BEGIN DESCRIPTION:
Mapping XS 163d2a7a
END DESCRIPTION:
XS GIS Cut Line= 3
      2734182.11      6943955.78      2733364.38      6944434.96
      2732577.96      6945330.75
#Sta/Elev= 30
  4065.9  505.54  4212.1  500.35  4328.6  498.35  4455.5  498.43  4461.6   497.1
  4490.2  497.43  4652.5  493.74    4659  492.22  4680.5  493.06  4696.2  491.26
  4717.6  490.75  4929.6  489.01  4988.6  488.58  4995.2  482.47    4999  481.65
  4999.2  481.15    5003  481.65  5009.8  485.04  5016.9  484.86  5023.6  487.58
  5037.8  488.83  5186.2  490.67  5215.3  489.74  5236.1  491.83  5243.7  490.75
  5272.2  492.32  5286.4  491.38  5675.5  495.77    5704  495.02  6205.7  498.83
#Mann= 5 ,-1 , 0
  4065.9     .05       0  4929.6     .12       0    4999     .07       0
    5003     .12       0  5186.2     .05       0
Bank Sta=4999,5003
XS Rating Curve= 0 ,0
Exp/Cntr=0.3,0.1

Type RM Length L Ch R = 1 ,2756    ,448,448,448
BEGIN DESCRIPTION:
Mapping XS ca42f307
END DESCRIPTION:
XS GIS Cut Line= 3
      2733718.55      6943862.04      2733260.22      6944054.75
      2732708.16      6944825.55
#Sta/Elev= 30
  4520.8  496.74    4530   495.9  4535.4  494.24  4559.2   492.3    4567  490.61
  4630.4  488.37  4697.1  488.17  4805.6  486.44  4924.9  488.38  4947.9  488.22
  4966.3  487.04  4971.7  486.03  4977.2   481.7  4977.4   481.2  4980.9   481.2
  4981.2   481.7  5000.9  488.21  5011.7  488.81  5083.2   488.8  5169.2   490.1
  5183.9  490.46  5190.1  491.34  5204.8  490.85  5326.4   493.2  5548.7  494.02
  5836.2   493.6  5871.8  494.21    5878  495.04  5913.6  494.16  5966.1  494.32
#Mann= 3 ,-1 , 0
  4520.8     .05       0  4977.2     .04       0  4981.2     .05       0
Bank Sta=4977.2,4981.2
XS Rating Curve= 0 ,0
Exp/Cntr=0.3,0.1

Type RM Length L Ch R = 1 ,2308    ,461,461,461
BEGIN DESCRIPTION:
Mapping XS 1dbb7393
END DESCRIPTION:
XS GIS Cut Line= 3
      2733432.07       6943518.3      2733067.51      6943705.79
      2732541.49      6944523.46
#Sta/Elev= 30
  4590.8  494.39  4597.6  492.43  4605.4  491.29  4611.1  489.27  4620.1  487.35
  4649.8  485.63  4716.3  484.31  4843.8  485.29  4915.9  487.17  4935.7  486.88
  4968.7  487.68  4982.5  488.85  4998.8  484.37  5004.9  480.43  5005.1  479.93
  5008.6  479.93  5008.9  480.43  5012.8  480.77  5018.8   483.2    5028  484.43
    5034  486.63  5049.2  486.53    5054  487.03  5085.5  487.36  5100.7  488.58
  5149.6  489.91  5288.2  492.16  5708.5  493.03  5910.6  492.25    5973   493.5
#Mann= 5 ,-1 , 0
  4590.8     .05       0  4935.7     .12       0  5004.9     .07       0
  5008.9     .12       0    5054     .05       0
Bank Sta=5004.9,5008.9
XS Rating Curve= 0 ,0
Exp/Cntr=0.3,0.1

Type RM Length L Ch R = 1 ,1847    ,415,415,415
BEGIN DESCRIPTION:
Mapping XS 49d6a202
END DESCRIPTION:
XS GIS Cut Line= 4
      2733291.45      6943039.13      2732968.55      6943278.71
      2732853.97      6943414.12      2732515.41      6944445.41
#Sta/Elev= 30
  4605.8  501.05  4632.7  498.53  4696.9  494.34  4726.1  492.49  4822.4     488
  4885.3   486.3    4954  483.78  4968.6  484.06  4974.8  482.35  4983.2  483.91
  4997.9  484.04  5004.1  479.38  5004.3  477.69  5004.6  477.19  5008.1  477.19
  5008.3  477.69  5012.7  477.69  5018.5  482.49    5025  484.03  5125.1  483.43
  5153.7   484.8  5213.6  485.22  5234.6   486.4  5252.8  486.29  5276.7  487.27
  5318.3  487.52    5403  489.43  5546.3  490.96  5705.4  491.76  6270.7  492.37
#Mann= 8 ,-1 , 0
  4605.8     .12       0  4696.9      .1       0  4726.1     .12       0
  4822.4      .1       0  4885.3     .12       0  5004.3     .07       0
  5008.3     .12       0  5252.8     .05       0
Bank Sta=5004.3,5008.3
XS Rating Curve= 0 ,0
Exp/Cntr=0.3,0.1

Type RM Length L Ch R = 1 ,1432    ,482,482,482
BEGIN DESCRIPTION:
Mapping XS fd145933
END DESCRIPTION:
XS GIS Cut Line= 3
      2733079.63      6942845.14      2732701.19      6943150.67
      2732392.16      6944161.08
#Sta/Elev= 30
  4545.5  502.21  4609.3  502.48  4652.4  501.81  4658.9  501.24  4673.2  494.35
  4687.6   492.2    4758  488.41  4772.4  489.35  4786.8  486.84  4807.9  486.55
  4935.7  483.97  4957.9  483.79  4978.7  484.61  5004.8  482.34  5013.9  482.05
  5021.9  480.78  5026.2  477.04  5026.4  476.54  5029.9  476.54  5030.2  477.04
  5031.9  477.04    5035  482.03  5042.7  482.75  5126.3   482.8  5178.6  485.35
  5204.1  485.24  5307.7  486.19  5373.3   487.8  5613.2  489.95  6088.5  490.81
#Mann= 6 ,-1 , 0
  4545.5     .12       0  4807.9     .05       0  5004.8     .12       0
  5026.2     .03       0  5030.2     .12       0  5204.1     .05       0
Bank Sta=5026.2,5030.2
XS Rating Curve= 0 ,0
Exp/Cntr=0.3,0.1

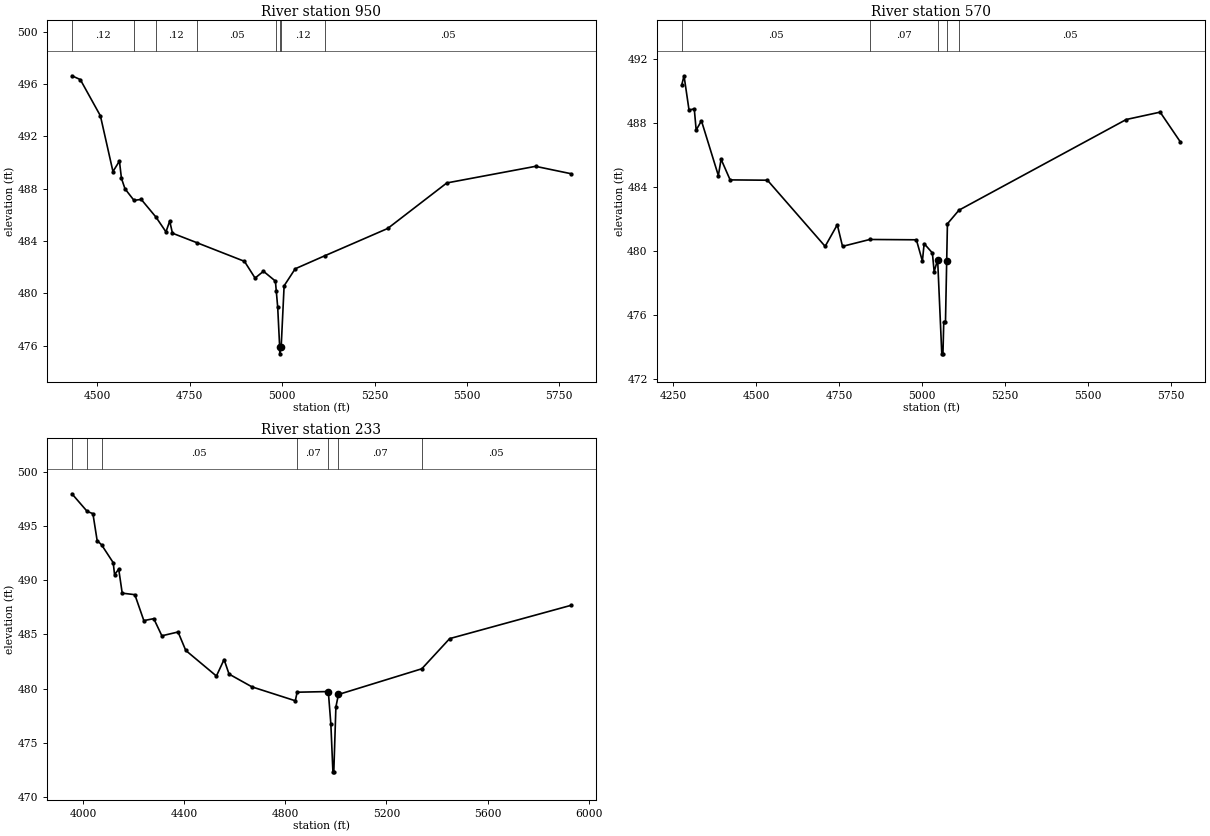
Type RM Length L Ch R = 1 ,950     ,380,380,380
BEGIN DESCRIPTION:
Mapping XS e176f38a
END DESCRIPTION:
XS GIS Cut Line= 3
      2732836.61      6942761.77      2732329.66      6942994.42
      2732294.94      6943786.07
#Sta/Elev= 30
  4430.8  496.63  4453.5  496.34  4507.9  493.57  4541.9  489.31  4559.4  490.11
  4564.9  488.79  4574.5  487.99  4598.8  487.11  4618.5  487.18  4658.3  485.83
  4685.4   484.7  4695.5  485.53  4702.9   484.6  4768.5  483.88  4897.8  482.45
  4926.6  481.17  4949.3  481.69  4981.6  480.94  4983.9  480.21  4987.8  478.96
  4993.2  475.88  4993.4  475.38  4997.2  475.88  5005.2  480.58  5035.2  481.88
  5114.9  482.87  5285.5  484.96  5445.6  488.44  5685.8  489.71    5781  489.15
#Mann= 8 ,-1 , 0
  4430.8     .12       0  4598.8     .05       0  4658.3     .12       0
  4768.5     .05       0  4983.9     .12       0  4993.2     .07       0
  4997.2     .12       0  5114.9     .05       0
Bank Sta=4993.2,4997.2
XS Rating Curve= 0 ,0
Exp/Cntr=0.3,0.1

Type RM Length L Ch R = 1 ,570     ,337,337,337
BEGIN DESCRIPTION:
Mapping XS c6335e2d
END DESCRIPTION:
XS GIS Cut Line= 5
      2732582.19      6942586.19      2732036.64      6942895.86
      2731978.08      6943050.34      2732066.96      6943394.47
      2732150.31      6943740.64
#Sta/Elev= 30
  4274.7  490.34  4281.8  490.93  4296.8   488.8  4312.7  488.86  4318.4  487.54
  4334.3  488.12  4385.3   484.7  4393.5  485.72  4420.8  484.43  4533.3  484.41
  4707.3  480.28  4743.9  481.63  4759.7  480.28  4841.9  480.71  4982.4  480.69
  5000.5  479.36  5005.8  480.45  5030.6  479.87    5036   478.7  5046.5  479.45
    5059  473.57  5062.5  473.57  5064.9  475.53  5070.1  475.53 5073.77 479.362
    5076  481.69  5110.8  482.54  5615.2   488.2  5717.4  488.66  5778.7  486.79
#Mann= 5 ,-1 , 0
  4274.7     .05       0  4841.9     .07       0  5046.5     .05       0
 5073.77     .07       0  5110.8     .05       0
Bank Sta=5046.5,5073.77
XS Rating Curve= 0 ,0
Exp/Cntr=0.3,0.1

Type RM Length L Ch R = 1 ,233     ,0,0,0
BEGIN DESCRIPTION:
Little Allen T2_3 1.0
END DESCRIPTION:
XS GIS Cut Line= 4
      2732659.48      6942397.21        2731751.        6942736.
        2731751.        6942886.      2732086.61      6943671.51
#Sta/Elev= 30
  3955.4  497.96    4016  496.33  4038.5  496.13  4055.2  493.65  4072.9  493.25
  4118.8  491.61  4124.1  490.51  4140.6  491.01  4154.4   488.8  4204.4  488.66
    4240  486.27  4279.3  486.45  4311.3  484.87  4375.4  485.22  4405.9  483.52
  4527.2  481.16  4557.5  482.68  4577.2  481.34  4668.1  480.16  4839.4  478.88
  4846.6  479.67    4970  479.73    4980  476.75  4988.2  472.33  4991.7  472.33
    5000  478.31    5010  479.46    5340  481.83  5450.2  484.61  5929.2  487.67
#Mann= 7 ,-1 , 0
  3955.4     .05       0    4016     .12       0  4072.9     .05       0
  4846.6     .07       0    4970     .05       0    5010     .07       0
    5340     .05       0
Bank Sta=4970,5010
XS Rating Curve= 0 ,0
Exp/Cntr=0.3,0.1

Chan Stop Cuts=-1
Use User Specified Reach Order=0
Composite Channel Slope=5