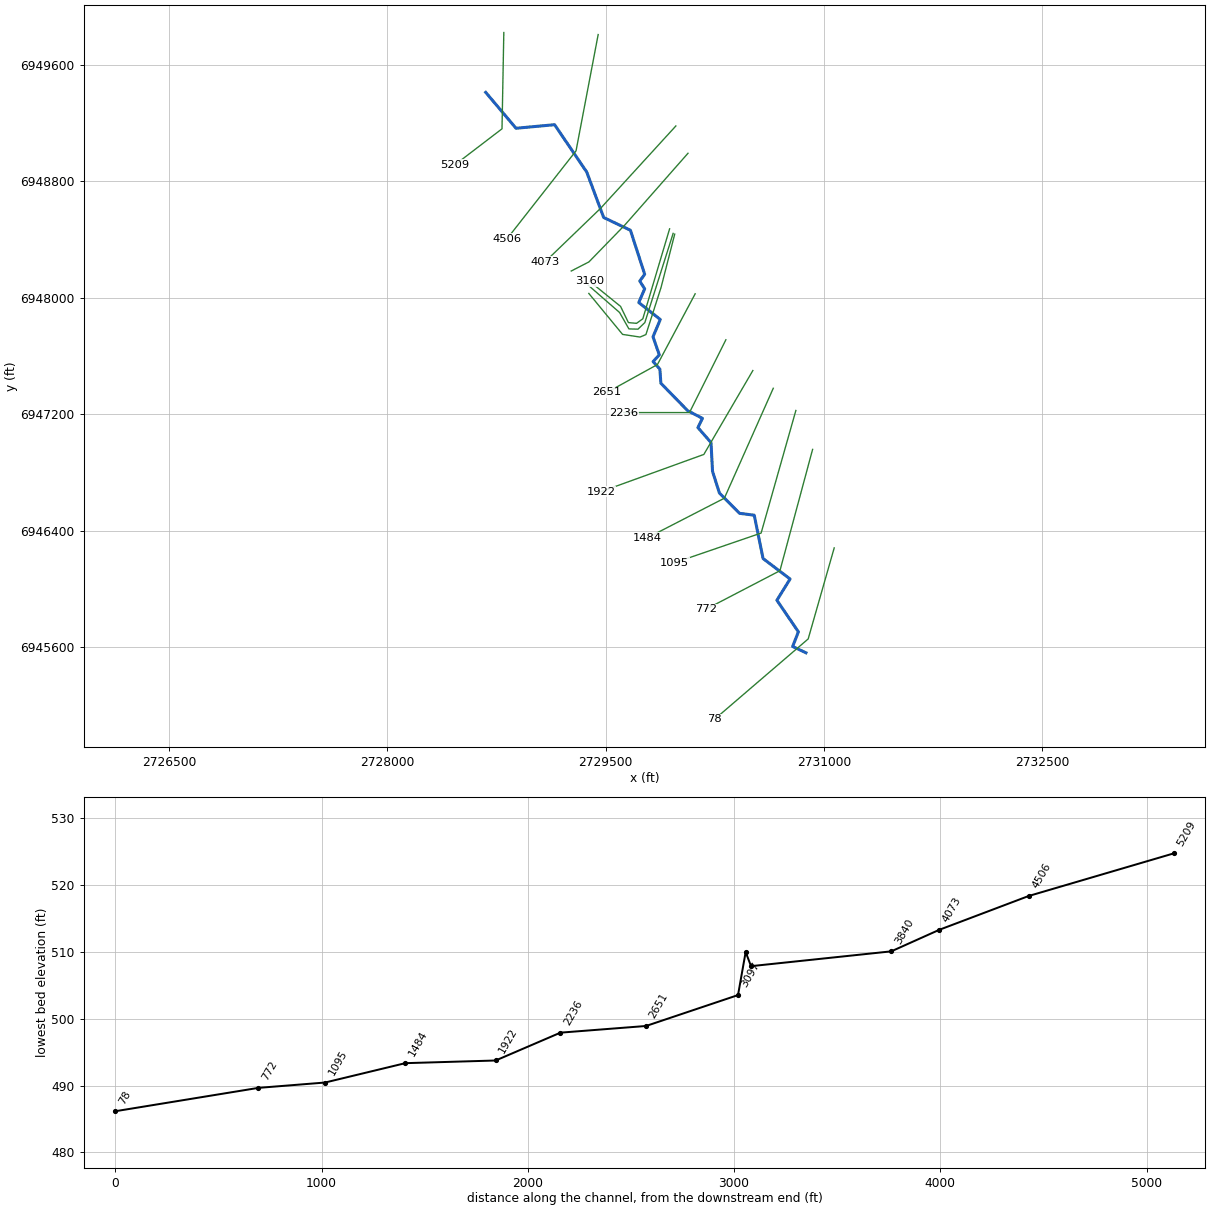
--- Little Allen T2_4.prj (project) ---

Proj Title=Little Allen T2_4 Base Level Engineering
Current Plan=p01
Default Exp/Contr=0.3,0.1
English Units
Geom File=g01
Flow File=f01
Plan File=p01
Y Axis Title=Elevation
X Axis Title(PF)=Main Channel Distance
X Axis Title(XS)=Station
BEGIN DESCRIPTION:
Little Allen T2_4
END DESCRIPTION:
DSS Export Rating Curves= 0
DSS Export Rating Curve Sorted= 0
DSS Export Volume Flow Curves= 0
DXF OffsetX= 0
DXF OffsetY= 0
DXF ScaleX= 1
DXF ScaleY= 10

--- Little Allen T2_4.p01 (plan) ---

Plan Title=Multiple Run
Short Identifier=Multiple
Geom File=g01
Flow File=f01
Subcritical Flow
K Sum by GR= 0
Std Step Tol= 0.01
Critical Tol= 0.01
Num of Std Step Trials= 20
Max Error Tol= 0.3
Flow Tol Ratio= 0.001
Split Flow NTrial= 30
Split Flow Tol= 0.02
Split Flow Ratio= 0.02
Log Output Level= 0
Friction Slope Method= 1
Unsteady Friction Slope Method= 2
Unsteady Bridges Friction Slope Method= 1
Parabolic Critical Depth
Global Vel Dist=  1 , 1 , 1
Global Log Level= 0
CheckData=True
Encroach Param= -1, 0, 0, 0
BEGIN DESCRIPTION:
Multiple Run
END DESCRIPTION:

--- Little Allen T2_4.f01 (steady flow) ---

Flow Title=Multiple
Number of Profiles=7
Profile Names=10-year,25-year,50-year,1pct_min,100-year,1pct_plu,500-year
River Rch & RM= Little Allen T2_,Reach-1,5209
     116     137     152      85     169     337     205
River Rch & RM= Little Allen T2_,Reach-1,2651
     249     312     360     207     412     823     539
Boundary for River Rch & Prof#=Little Allen T2_,Reach-1,1
Up Type=0
Dn Type=3
Dn Slope=0.005
Boundary for River Rch & Prof#=Little Allen T2_,Reach-1,2
Up Type=0
Dn Type=3
Dn Slope=0.005
Boundary for River Rch & Prof#=Little Allen T2_,Reach-1,3
Up Type=0
Dn Type=3
Dn Slope=0.005
Boundary for River Rch & Prof#=Little Allen T2_,Reach-1,4
Up Type=0
Dn Type=3
Dn Slope=0.005
Boundary for River Rch & Prof#=Little Allen T2_,Reach-1,5
Up Type=0
Dn Type=3
Dn Slope=0.005
Boundary for River Rch & Prof#=Little Allen T2_,Reach-1,6
Up Type=0
Dn Type=3
Dn Slope=0.005
Boundary for River Rch & Prof#=Little Allen T2_,Reach-1,7
Up Type=0
Dn Type=3
Dn Slope=0.005

--- Little Allen T2_4.g01 (geometry) ---

Geom Title=Existing Conditions
Program Version=4.10

River Reach=Little Allen T2_,Reach-1
Reach XY= 30
        2728676.        6949411.       2728884.3      6949164.07
      2729149.41      6949188.57      2729370.16      6948863.29
      2729486.61      6948550.94      2729670.29      6948463.58
      2729768.22       6948160.9      2729734.55      6948114.33
      2729768.18      6948061.09      2729727.58      6947966.87
      2729875.46      6947850.53      2729825.42      6947731.05
      2729868.76      6947607.55        2729826.        6947561.
      2729872.61      6947509.59      2729879.58      6947412.48
      2730062.82      6947224.63      2730164.89      6947171.32
      2730134.02      6947107.68      2730223.84      6947005.11
      2730234.28      6946807.78      2730281.52      6946658.57
      2730419.88      6946518.88      2730520.96      6946505.92
      2730581.42      6946208.33      2730767.04      6946067.69
      2730676.56      6945921.64      2730824.16      6945704.87
      2730784.81      6945604.04        2730876.        6945561.

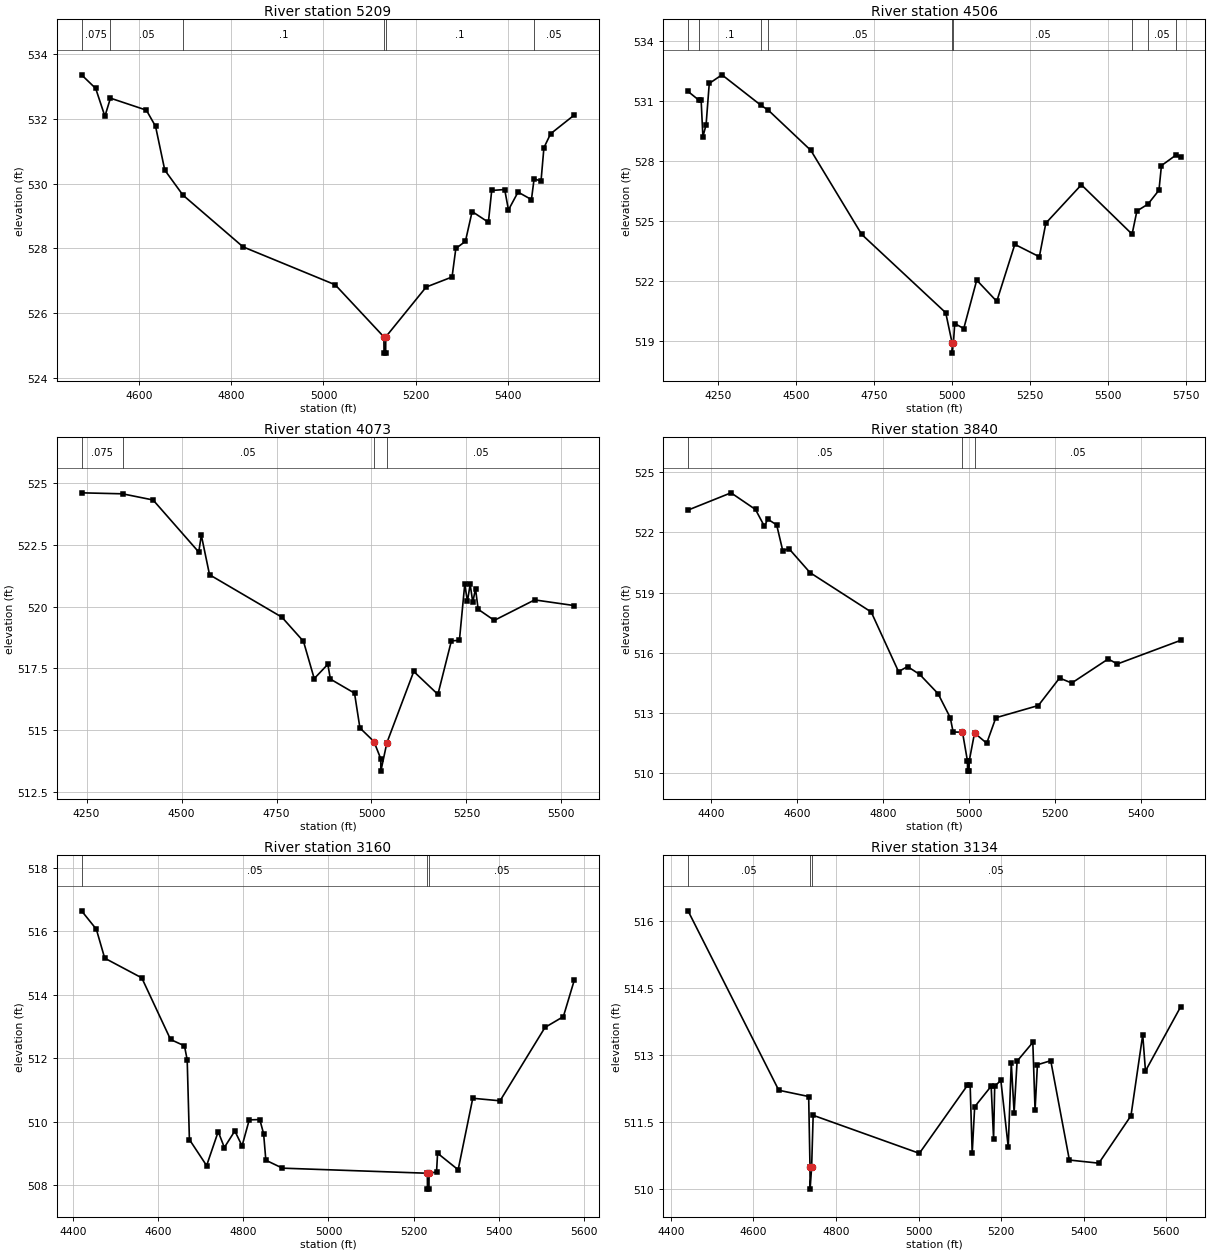
Type RM Length L Ch R = 1 ,5209    ,703,703,703
BEGIN DESCRIPTION:
Little Allen T2_4 8.0
END DESCRIPTION:
XS GIS Cut Line= 3
      2728800.53      6949821.66      2728788.15      6949160.34
      2728463.52       6948912.1
#Sta/Elev= 30
  4474.6  533.36  4505.3  532.94  4525.3  532.08  4537.3  532.64  4615.3  532.27
  4635.3  531.77  4655.3  530.42  4694.6  529.65  4825.3  528.05  5025.4  526.88
  5131.2  525.27  5131.5  524.77    5135  524.77  5135.2  525.27    5223  526.81
  5279.2  527.12  5287.4     528  5308.2  528.22  5322.8  529.14  5358.1  528.81
  5365.3  529.79  5393.5  529.82  5401.7  529.19  5422.5  529.74  5451.6  529.51
  5457.4  530.15  5472.4  530.08  5478.7  531.11  5493.2  531.54  5544.7  532.12
#Mann= 6 ,-1 , 0
  4474.6    .075       0  4537.3     .05       0  4694.6      .1       0
  5131.2     .05       0  5135.2      .1       0  5457.4     .05       0
Bank Sta=5131.2,5135.2
XS Rating Curve= 0 ,0
Exp/Cntr=0.3,0.1

Type RM Length L Ch R = 1 ,4506    ,433,433,433
BEGIN DESCRIPTION:
Mapping XS 64a05110
END DESCRIPTION:
XS GIS Cut Line= 3
      2729448.73      6949807.91      2729296.83       6949009.3
      2728823.73        6948406.
#Sta/Elev= 30
  4153.6  531.48  4187.8  531.05  4195.6  531.06  4201.3  529.21  4211.5  529.81
  4221.7  531.88  4262.4  532.31  4387.9  530.78  4411.1  530.54  4547.4  528.53
  4710.3  524.33  4979.7  520.41  5000.3  518.89  5000.5  518.39  5004.3  518.89
  5008.6  519.87  5037.5  519.62  5079.1  522.04  5143.3  520.98  5201.2  523.83
  5279.8  523.21  5300.6  524.89  5414.5  526.81  5577.1  524.34  5592.6   525.5
  5627.9  525.84  5663.3  526.54  5671.2  527.77  5717.3  528.29  5733.2  528.18
#Mann= 9 ,-1 , 0
  4153.6    .075       0  4187.8      .1       0  4387.9    .075       0
  4411.1     .05       0  5000.3     .03       0  5004.3     .05       0
  5577.1    .075       0  5627.9     .05       0  5717.3    .075       0
Bank Sta=5000.3,5004.3
XS Rating Curve= 0 ,0
Exp/Cntr=0.3,0.1

Type RM Length L Ch R = 1 ,4073    ,233,233,233
BEGIN DESCRIPTION:
Mapping XS 22509a61
END DESCRIPTION:
XS GIS Cut Line= 3
      2729982.57      6949179.99      2729465.23      6948614.04
      2729083.28      6948245.98
#Sta/Elev= 30
  4236.8  524.61  4344.6  524.57  4425.1  524.32  4545.3  522.21  4552.1  522.89
  4573.7  521.29  4764.2  519.57    4821  518.59  4849.3  517.08  4885.1  517.66
  4891.9  517.06  4955.4  516.49  4969.6  515.08  5006.5  514.53  5024.5  513.83
  5024.7  513.33  5040.6  514.48  5111.3  517.37  5174.9  516.44  5210.4  518.61
  5231.5  518.63  5245.6  520.91  5252.6  520.21  5259.8   520.9  5266.7  520.18
  5273.9  520.72  5280.9  519.89  5323.3  519.44  5429.6  520.27    5534  520.04
#Mann= 4 ,-1 , 0
  4236.8    .075       0  4344.6     .05       0  5006.5     .03       0
  5040.6     .05       0
Bank Sta=5006.5,5040.6
XS Rating Curve= 0 ,0
Exp/Cntr=0.3,0.1

Type RM Length L Ch R = 1 ,3840    ,680,680,680
BEGIN DESCRIPTION:
Mapping XS 66072683
END DESCRIPTION:
XS GIS Cut Line= 4
      2730065.95      6948992.55       2729631.9      6948499.46
      2729385.37      6948245.99      2729263.81      6948183.47
#Sta/Elev= 30
  4346.5  523.11  4446.6  523.97  4503.6  523.14  4524.4   522.3    4532  522.66
  4552.9  522.37  4567.1  521.08  4581.4  521.19  4630.7  519.99    4773  518.03
  4836.6  515.06  4857.5  515.31  4885.9  514.92  4928.6  513.96  4957.1  512.76
  4963.7  512.05  4985.5  512.04  4997.1   510.6  4997.3   510.1  5000.8   510.1
  5001.1   510.6  5013.6     512  5041.9  511.49  5063.1  512.76  5162.1  513.37
  5211.5  514.74  5239.8  514.49  5324.7  515.69    5346  515.44  5493.7  516.62
#Mann= 3 ,-1 , 0
  4346.5     .05       0  4985.5     .04       0  5013.6     .05       0
Bank Sta=4985.5,5013.6
XS Rating Curve= 0 ,0
Exp/Cntr=0.3,0.1

Type RM Length L Ch R = 1 ,3160    ,26,26,26
BEGIN DESCRIPTION:
Mapping XS a781753c
END DESCRIPTION:
XS GIS Cut Line= 6
      2729939.44      6948473.21      2729755.42      6947855.19
      2729712.02      6947823.94      2729656.46      6947829.15
      2729602.64      6947940.26      2729390.93      6948112.05
#Sta/Elev= 30
  4420.5  516.64  4455.2  516.06  4474.8  515.15  4561.8  514.53  4629.4  512.59
    4662  512.39  4668.4  511.95  4673.6  509.44    4714  508.62  4741.2  509.69
  4755.6  509.19  4780.2  509.71  4797.2  509.24    4814  510.06  4838.8  510.07
  4847.8  509.62    4853  508.79    4892  508.54    5232  508.38  5232.3  507.88
  5235.8  507.88    5236  508.38  5253.6  508.42    5256  509.01  5304.3  508.49
  5338.6  510.74  5402.6  510.66  5508.1  512.97  5551.2  513.31  5576.9  514.46
#Mann= 3 ,-1 , 0
  4420.5     .05       0    5232     .03       0    5236     .05       0
Bank Sta=5232,5236
XS Rating Curve= 0 ,0
Exp/Cntr=0.3,0.1

Type RM Length L Ch R = 1 ,3134    ,37,37,37
BEGIN DESCRIPTION:
Mapping XS a20f7eef
END DESCRIPTION:
XS GIS Cut Line= 6
      2729963.76      6948442.02      2729769.31      6947829.15
      2729722.43      6947784.01      2729659.93      6947785.74
       2729595.7      6947898.59      2729380.76       6948085.8
#Sta/Elev= 30
  4441.8  516.22  4661.5  512.21  4733.9  512.07  4737.1   510.5  4737.4     510
  4741.1   510.5  4744.8  511.65  5001.9   510.8  5118.3  512.32  5124.9  512.32
  5129.8   510.8  5135.8  511.84  5175.7   512.3  5181.6  511.12  5184.3   512.3
  5199.2  512.43  5217.1  510.94  5224.4  512.82  5231.3  511.71  5238.5  512.86
  5276.6  513.28    5282  511.76  5287.7  512.78    5320  512.87  5365.1  510.65
  5436.4  510.58  5514.2  511.64  5542.7  513.45  5549.3  512.64  5634.8  514.08
#Mann= 3 ,-1 , 0
  4441.8     .05       0  4737.1     .03       0  4741.1     .05       0
Bank Sta=4737.1,4741.1
XS Rating Curve= 0 ,0
Exp/Cntr=0.3,0.1

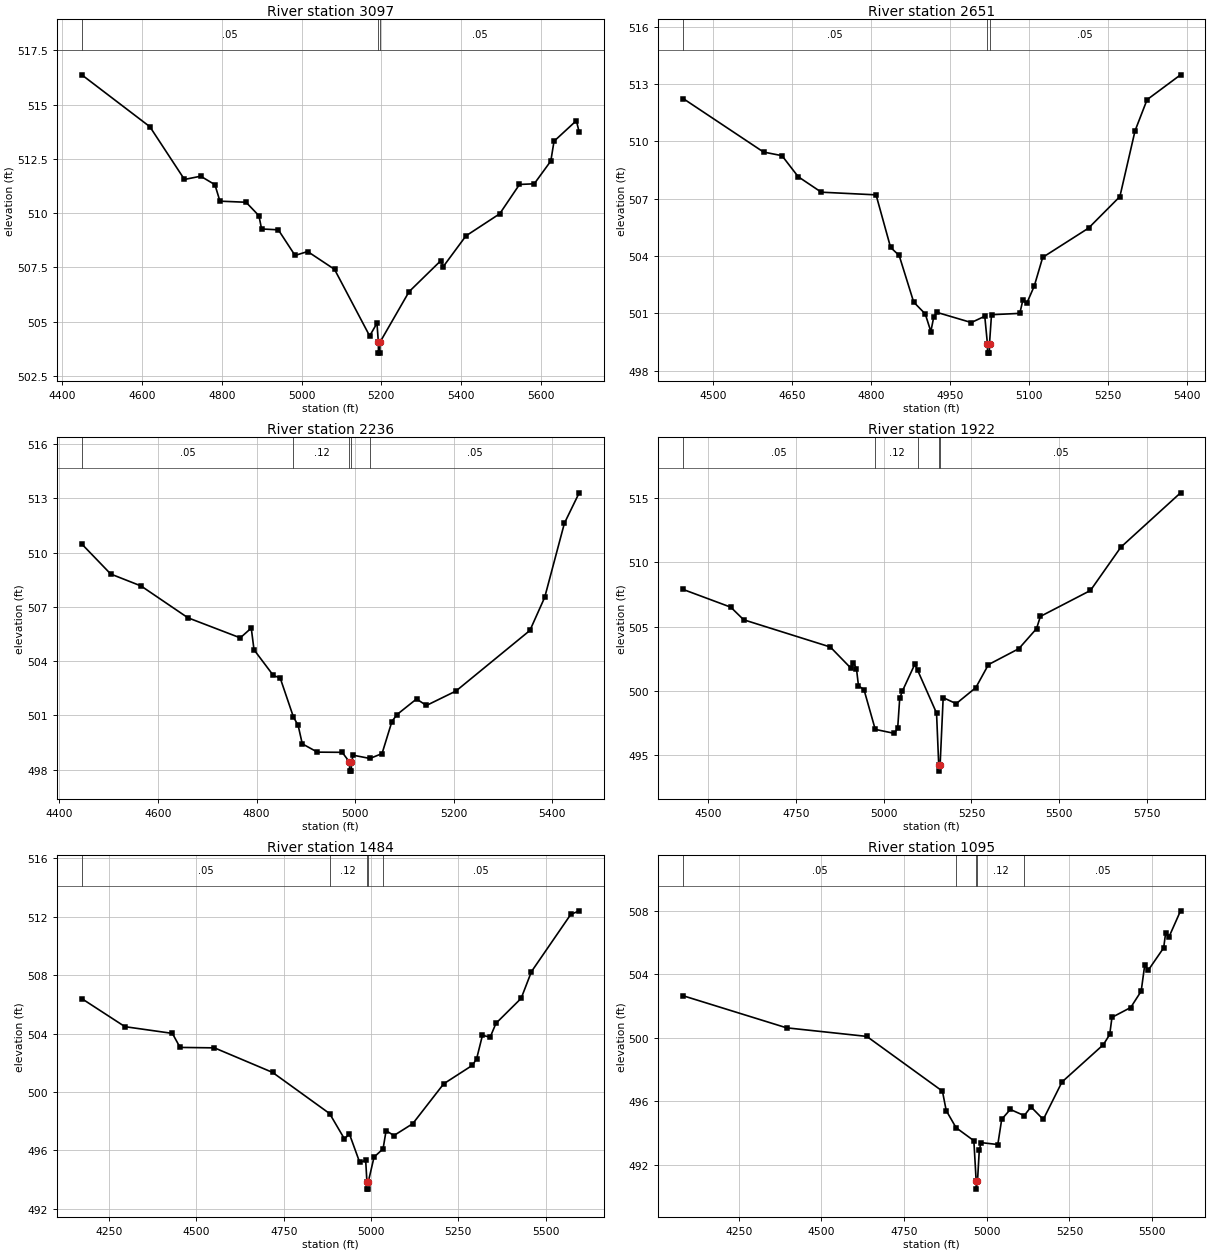
Type RM Length L Ch R = 1 ,3097    ,446,446,446
BEGIN DESCRIPTION:
Mapping XS bec08688
END DESCRIPTION:
XS GIS Cut Line= 6
       2729974.6      6948436.77      2729880.85       6948070.9
      2729776.69      6947746.68      2729736.32      6947729.75
      2729616.53      6947747.98      2729384.75      6948029.24
#Sta/Elev= 30
  4448.7  516.37  4619.5  513.98  4706.3  511.55    4747   511.7  4782.7  511.31
  4795.3  510.55  4860.9   510.5  4893.1  509.88  4899.8  509.27  4941.8  509.23
  4983.8  508.05  5015.4  508.23  5082.8  507.41    5171  504.34  5189.3  504.93
  5192.8  504.05    5193  503.55  5196.5  503.55  5196.8  504.05  5269.8  506.38
    5349   507.8  5355.8  507.54  5412.5  508.95  5497.3  509.97  5546.9  511.32
  5583.9  511.35  5625.5   512.4  5633.5  513.31  5689.6  514.26  5696.7  513.72
#Mann= 3 ,-1 , 0
  4448.7     .05       0  5192.8     .03       0  5196.8     .05       0
Bank Sta=5192.8,5196.8
XS Rating Curve= 0 ,0
Exp/Cntr=0.3,0.1

Type RM Length L Ch R = 1 ,2651    ,415,415,415
BEGIN DESCRIPTION:
Mapping XS fdd89089
END DESCRIPTION:
XS GIS Cut Line= 3
      2730115.07      6948026.79      2729855.94      6947541.08
      2729510.31      6947350.08
#Sta/Elev= 30
  4442.9  512.24  4595.7  509.44  4630.8  509.25  4661.6  508.15  4705.5  507.34
  4809.6   507.2  4837.2  504.45  4853.5  504.03  4881.1  501.59  4903.1  500.97
  4913.7  500.05  4919.4  500.83  4925.5  501.05  4990.6  500.52  5016.2  500.85
  5021.2  499.42  5021.5  498.92    5025  498.92  5025.2  499.42    5029  500.93
  5082.8     501  5088.5  501.68  5096.2  501.54  5110.3  502.43  5126.3  503.93
  5213.4  505.46    5273  507.11  5301.8  510.55  5324.7  512.18  5388.3  513.48
#Mann= 3 ,-1 , 0
  4442.9     .05       0  5021.2     .04       0  5025.2     .05       0
Bank Sta=5021.2,5025.2
XS Rating Curve= 0 ,0
Exp/Cntr=0.3,0.1

Type RM Length L Ch R = 1 ,2236    ,314,314,314
BEGIN DESCRIPTION:
Little Allen T2_4 3.0
END DESCRIPTION:
XS GIS Cut Line= 3
      2730326.02      6947711.04        2730076.        6947211.
      2729625.96        6947211.
#Sta/Elev= 30
  4445.3  510.48    4504  508.82  4565.5  508.16  4660.6   506.4  4766.8  505.29
  4789.1  505.83  4794.7  504.63  4833.9  503.21  4847.8  503.07  4874.7  500.91
  4884.2  500.45  4892.6  499.43  4923.3  498.97  4973.6  498.96  4988.4  498.42
  4988.6  497.92  4992.1  497.92  4992.4  498.42    4996   498.8  5029.8  498.62
  5054.4  498.89  5074.4  500.66  5084.4  501.04  5124.4  501.91  5144.4  501.55
  5204.4  502.35  5354.4   505.7  5384.4  507.53  5424.4  511.63  5454.4  513.31
#Mann= 5 ,-1 , 0
  4445.3     .05       0  4874.7     .12       0  4988.4     .07       0
  4992.4     .12       0  5029.8     .05       0
Bank Sta=4988.4,4992.4
XS Rating Curve= 0 ,0
Exp/Cntr=0.3,0.1

Type RM Length L Ch R = 1 ,1922    ,438,438,438
BEGIN DESCRIPTION:
Little Allen T2_4 2.0
END DESCRIPTION:
XS GIS Cut Line= 3
      2730511.43      6947499.81       2730174.6      6946923.39
      2729470.36       6946668.4
#Sta/Elev= 30
  4428.9  507.89  4564.6  506.51  4601.3  505.53  4848.1  503.41  4906.8  501.76
    4914  502.17  4922.5  501.73  4928.3  500.39    4944  500.09    4976     497
    5030  496.69  5039.9  497.08  5045.7  499.41    5053  499.96  5088.7  502.07
  5096.9  501.59  5150.6  498.27  5156.8  494.25  5157.1  493.75  5160.8  494.25
  5169.5  499.47  5206.5     499  5262.5  500.25  5298.4  502.04    5385  503.28
  5435.4  504.84  5446.3  505.79  5588.9  507.81  5675.5  511.18  5845.5  515.41
#Mann= 5 ,-1 , 0
  4428.9     .05       0    4976     .12       0  5096.9     .05       0
  5156.8     .07       0  5160.8     .05       0
Bank Sta=5156.8,5160.8
XS Rating Curve= 0 ,0
Exp/Cntr=0.3,0.1

Type RM Length L Ch R = 1 ,1484    ,389,389,389
BEGIN DESCRIPTION:
Mapping XS 1c7002a2
END DESCRIPTION:
XS GIS Cut Line= 3
      2730651.64      6947378.04      2730315.69      6946622.81
      2729784.41      6946349.36
#Sta/Elev= 30
  4171.9  506.39  4295.5  504.47  4431.3  504.01  4453.2  503.05  4551.7  503.02
  4718.1  501.34  4881.5  498.52  4923.8  496.79  4938.2  497.12  4967.6  495.18
  4984.7  495.32  4988.2  493.85  4988.5  493.35    4992  493.35  4992.2  493.85
  5008.6  495.54  5034.5  496.11  5043.1  497.35  5065.6  497.02  5119.4  497.83
  5208.1  500.56  5290.5  501.83  5302.4  502.28    5319  503.88  5341.1  503.75
  5357.7   504.7  5429.8  506.41  5459.3  508.24  5571.7  512.15    5596   512.4
#Mann= 5 ,-1 , 0
  4171.9     .05       0  4881.5     .12       0  4988.2     .07       0
  4992.2     .12       0  5034.5     .05       0
Bank Sta=4988.2,4992.2
XS Rating Curve= 0 ,0
Exp/Cntr=0.3,0.1

Type RM Length L Ch R = 1 ,1095    ,323,323,323
BEGIN DESCRIPTION:
Mapping XS 0a1c999b
END DESCRIPTION:
XS GIS Cut Line= 3
       2730806.8      6947225.27      2730568.08      6946383.23
      2729973.43      6946179.22
#Sta/Elev= 30
  4082.1  502.63  4394.9  500.61  4637.4  500.07  4866.1  496.62  4877.5   495.4
  4907.3  494.32  4961.1   493.5  4968.1  490.95  4968.4  490.45  4972.1  490.95
  4977.5   492.9  4982.8  493.38  5033.5  493.26  5045.3  494.85  5071.3  495.47
  5113.4  495.08  5133.8  495.63    5171  494.84  5227.6   497.2  5352.7  499.55
  5371.8  500.19  5378.7  501.27  5435.3  501.89    5467  502.92  5477.8  504.58
  5488.1  504.23    5535  505.65    5541   506.6  5551.6  506.36    5586  507.98
#Mann= 5 ,-1 , 0
  4082.1     .05       0  4907.3     .12       0  4968.1     .07       0
  4972.1     .12       0  5113.4     .05       0
Bank Sta=4968.1,4972.1
XS Rating Curve= 0 ,0
Exp/Cntr=0.3,0.1

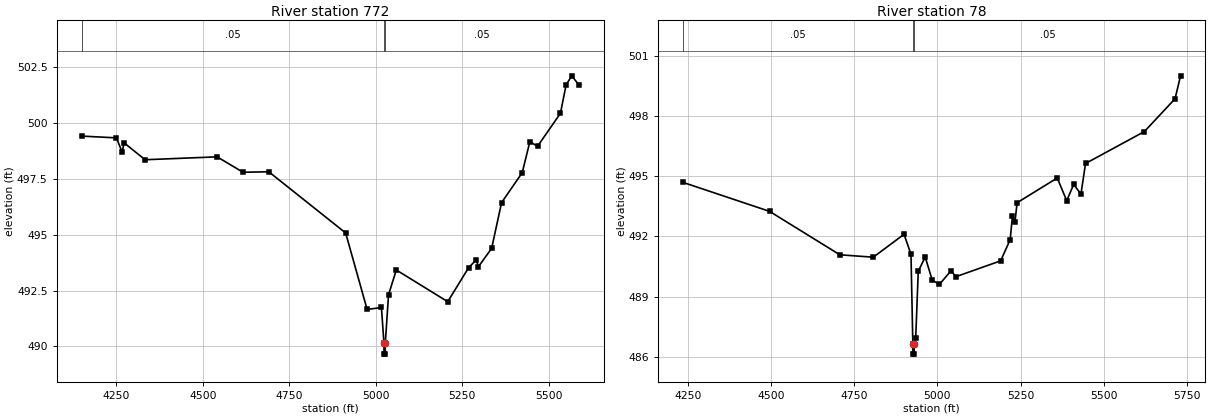
Type RM Length L Ch R = 1 ,772     ,694,694,694
BEGIN DESCRIPTION:
Mapping XS 81d51552
END DESCRIPTION:
XS GIS Cut Line= 3
      2730921.81      6946958.11      2730697.42      6946124.55
      2730187.03      6945858.94
#Sta/Elev= 30
  4149.5  499.42  4250.1  499.34  4266.8  498.69    4272  499.12  4332.9  498.36
  4541.3  498.49    4616   497.8  4690.7  497.82  4912.9  495.08    4975  491.65
  5016.4  491.74  5023.6  490.15  5023.9  489.65  5027.4  489.65  5027.6  490.15
  5036.9  492.31  5059.4  493.42  5208.1     492  5268.8  493.53  5290.9  493.88
  5296.5  493.56  5335.1  494.39  5363.8  496.44  5423.5  497.78  5445.6  499.17
  5467.7  498.96    5534  500.44  5550.5  501.72  5566.7  502.12  5588.1   501.7
#Mann= 3 ,-1 , 0
  4149.5     .05       0  5023.6     .04       0  5027.6     .05       0
Bank Sta=5023.6,5027.6
XS Rating Curve= 0 ,0
Exp/Cntr=0.3,0.1

Type RM Length L Ch R = 1 ,78      ,0,0,0
BEGIN DESCRIPTION:
Little Allen T2_4 1.0
END DESCRIPTION:
XS GIS Cut Line= 3
      2731070.21      6946281.21      2730891.43      6945656.01
      2730249.07      6945104.79
#Sta/Elev= 30
  4234.8  494.69    4495  493.25  4706.5  491.09  4807.1  490.97  4899.6  492.11
  4920.5  491.11  4926.1  486.65  4926.4  486.15  4929.9  486.15  4930.1  486.65
  4934.7  486.95  4942.4  490.27  4963.3  490.98  4984.4  489.83  5006.1  489.62
  5041.2   490.3  5055.5     490  5190.4  490.79    5219  491.85  5225.6     493
  5233.2  492.71  5239.8  493.68  5360.6  494.91  5389.1  493.78  5409.9  494.59
  5431.9  494.11  5445.6  495.63  5622.8  497.22    5715  498.85  5731.5  499.99
#Mann= 3 ,-1 , 0
  4234.8     .05       0  4926.1     .04       0  4930.1     .05       0
Bank Sta=4926.1,4930.1
XS Rating Curve= 0 ,0
Exp/Cntr=0.3,0.1

Chan Stop Cuts=-1
Use User Specified Reach Order=0
Composite Channel Slope=5