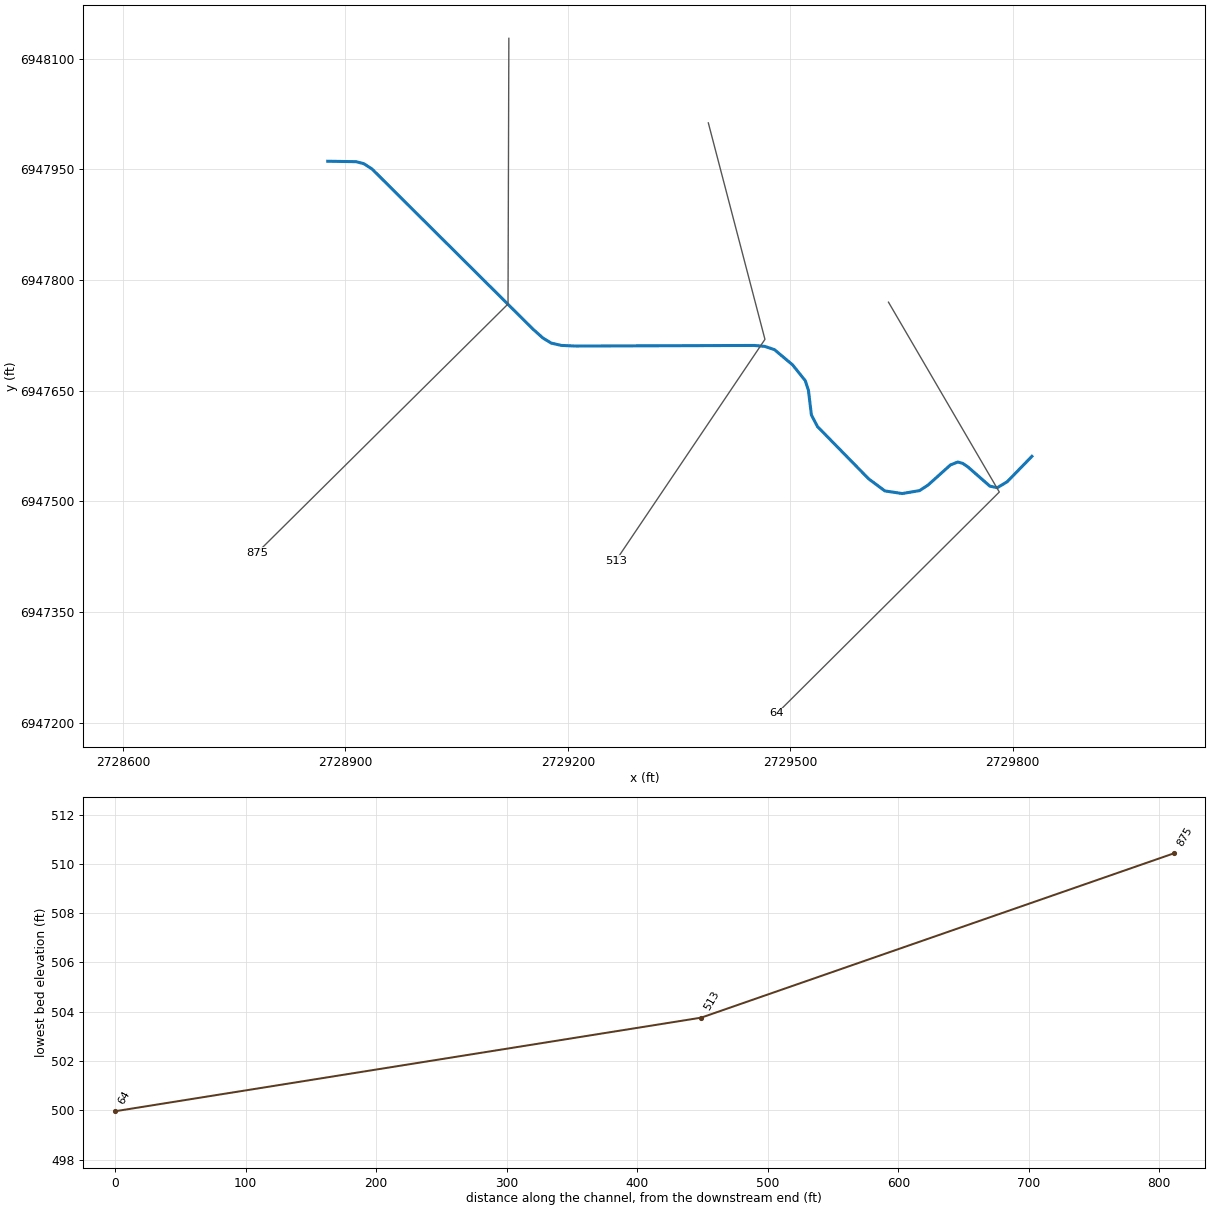
--- Little Allen T2_4_1.prj (project) ---

Proj Title=Little Allen T2_4_1 Base Level Engineering
Current Plan=p01
Default Exp/Contr=0.3,0.1
English Units
Geom File=g01
Flow File=f01
Plan File=p01
BEGIN DESCRIPTION:
Little Allen T2_4_1
END DESCRIPTION:

--- Little Allen T2_4_1.p01 (plan) ---

Plan Title=Multiple Run
Short Identifier=Multiple
Geom File=g01
Flow File=f01
Subcritical Flow
K Sum by GR= 0
Std Step Tol= 0.01
Critical Tol= 0.01
Num of Std Step Trials= 20
Max Error Tol= 0.3
Flow Tol Ratio= 0.001
Split Flow NTrial= 30
Split Flow Tol= 0.02
Split Flow Ratio= 0.02
Log Output Level= 0
Friction Slope Method= 1
Unsteady Friction Slope Method= 2
Unsteady Bridges Friction Slope Method= 1
Parabolic Critical Depth
Global Vel Dist=  1 , 1 , 1
Global Log Level= 0
CheckData=True
Encroach Param= -1, 0, 0, 0
BEGIN DESCRIPTION:
Multiple Run
END DESCRIPTION:

--- Little Allen T2_4_1.f01 (steady flow) ---

Flow Title=Multiple
Number of Profiles=7
Profile Names=10-year,25-year,50-year,1pct_min,100-year,1pct_plu,500-year
River Rch & RM= Little Allen T2_,Reach-1,875
     100     117     129      71     142     284     171
Boundary for River Rch & Prof#=Little Allen T2_,Reach-1,1
Up Type=0
Dn Type=3
Dn Slope=0.005
Boundary for River Rch & Prof#=Little Allen T2_,Reach-1,2
Up Type=0
Dn Type=3
Dn Slope=0.005
Boundary for River Rch & Prof#=Little Allen T2_,Reach-1,3
Up Type=0
Dn Type=3
Dn Slope=0.005
Boundary for River Rch & Prof#=Little Allen T2_,Reach-1,4
Up Type=0
Dn Type=3
Dn Slope=0.005
Boundary for River Rch & Prof#=Little Allen T2_,Reach-1,5
Up Type=0
Dn Type=3
Dn Slope=0.005
Boundary for River Rch & Prof#=Little Allen T2_,Reach-1,6
Up Type=0
Dn Type=3
Dn Slope=0.005
Boundary for River Rch & Prof#=Little Allen T2_,Reach-1,7
Up Type=0
Dn Type=3
Dn Slope=0.005

--- Little Allen T2_4_1.g01 (geometry) ---

Geom Title=Existing Conditions

River Reach=Little Allen T2_,Reach-1
Reach XY= 30
      2728876.00      6947961.00      2728914.16      6947960.41
      2728924.64      6947957.73      2728935.79      6947950.49
      2729152.47      6947733.86      2729166.20      6947721.48
      2729177.46      6947714.54      2729191.16      6947711.38
      2729210.80      6947710.51      2729451.21      6947711.33
      2729465.72      6947710.01      2729478.70      6947705.64
      2729503.19      6947684.97      2729520.26      6947663.57
      2729524.52      6947650.53      2729528.55      6947617.08
      2729536.78      6947601.31      2729605.87      6947530.42
      2729627.64      6947514.15      2729651.00      6947510.59
      2729674.35      6947514.55      2729685.68      6947521.87
      2729716.14      6947549.39      2729726.09      6947553.33
      2729732.73      6947551.44      2729739.38      6947546.93
      2729769.34      6947520.60      2729779.34      6947518.51
      2729792.78      6947526.69      2729826.00      6947561.00

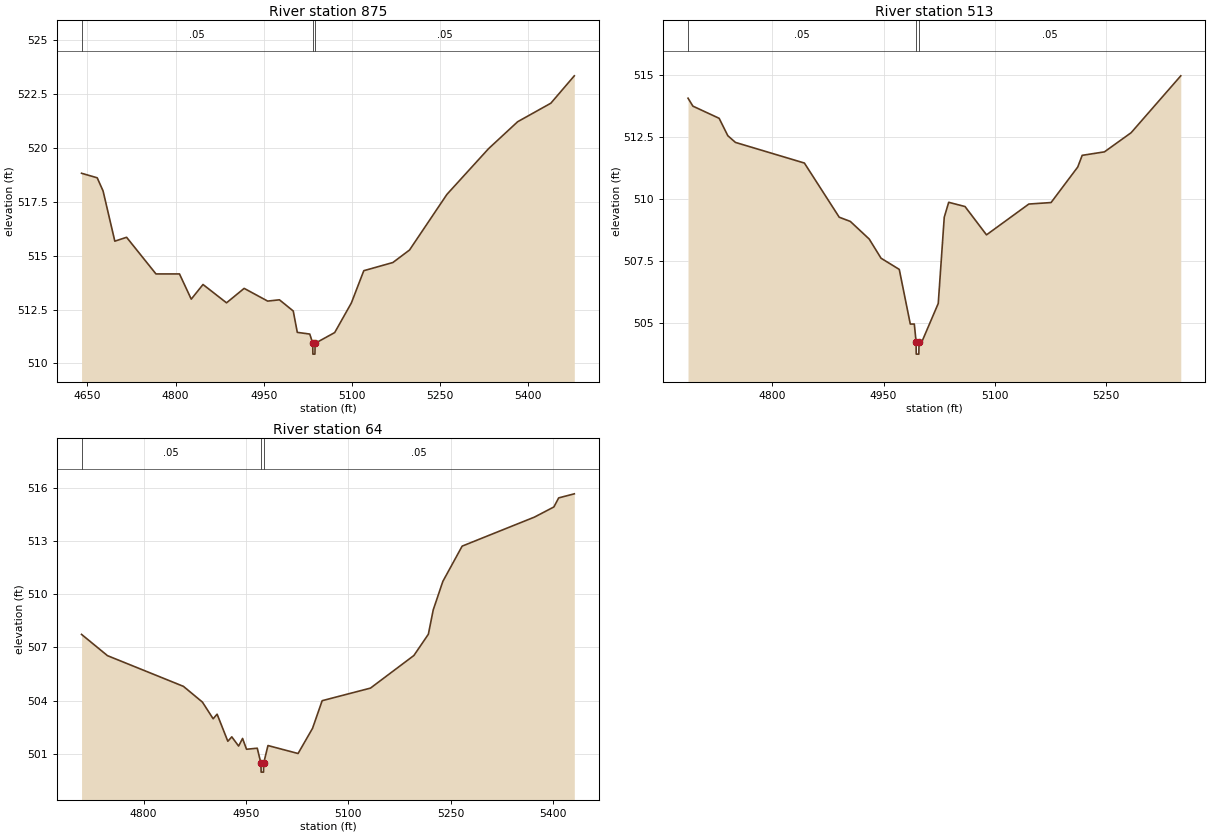
Type RM Length L Ch R = 1,875,362,362,362
BEGIN DESCRIPTION:
Little Allen T2_4_1 2.0
END DESCRIPTION:
XS GIS Cut Line= 3
      2729120.38      6948127.59      2729119.26      6947767.49
      2728780.53      6947430.09
#Sta/Elev= 30
  4639.9  518.82  4666.5  518.61  4676.5  518.00  4696.5  515.67  4716.5  515.85
  4766.5  514.15  4806.5  514.15  4826.5  512.98  4846.5  513.66  4886.5  512.81
  4916.5  513.48  4956.5  512.89  4976.5  512.95  5000.0  512.43  5006.9  511.44
  5028.1  511.36  5033.2  510.93  5033.4  510.43  5036.9  510.43  5037.2  510.93
  5070.5  511.43  5098.8  512.80  5120.0  514.30  5169.5  514.68  5197.8  515.26
  5261.4  517.84  5332.2  519.96  5381.7  521.21  5438.2  522.07  5478.1  523.34
#Mann=3,-1,0
  4639.9    0.05       0  5033.2    0.04       0  5037.2    0.05       0
Bank Sta=5033.2,5037.2
Exp/Cntr=0.3,0.1

Type RM Length L Ch R = 1,513,449,449,449
BEGIN DESCRIPTION:
Mapping XS 9488e2e4
END DESCRIPTION:
XS GIS Cut Line= 3
      2729389.48      6948012.98      2729465.87      6947719.59
      2729264.47      6947419.23
#Sta/Elev= 30
  4686.2  514.06  4692.8  513.74  4728.2  513.25  4739.9  512.55  4750.2  512.28
  4843.2  511.45  4890.2  509.27  4905.2  509.10  4930.7  508.39  4946.6  507.62
  4971.2  507.17  4986.1  504.97  4991.5  504.97  4993.9  504.26  4994.1  503.76
  4997.6  503.76  4997.9  504.26  5001.9  504.27  5023.8  505.80  5031.9  509.27
  5037.9  509.87  5059.9  509.70  5088.9  508.56  5146.0  509.80  5176.0  509.86
  5212.0  511.29  5218.0  511.76  5248.0  511.90  5284.0  512.67  5351.0  514.96
#Mann=3,-1,0
  4686.2    0.05       0  4993.9    0.04       0  4997.9    0.05       0
Bank Sta=4993.9,4997.9
Exp/Cntr=0.3,0.1

Type RM Length L Ch R = 1,64,0,0,0
BEGIN DESCRIPTION:
Little Allen T2_4_1 1.0
END DESCRIPTION:
XS GIS Cut Line= 3
      2729632.52      6947769.97      2729782.04      6947512.65
      2729482.02      6947212.63
#Sta/Elev= 30
  4709.1  507.73  4747.1  506.53  4858.3  504.80  4886.2  503.91  4901.9  502.97
  4907.7  503.23  4923.4  501.70  4929.2  501.95  4939.2  501.43  4945.0  501.86
  4950.8  501.25  4966.5  501.31  4971.9  500.46  4972.2  499.96  4975.7  499.96
  4975.9  500.46  4982.2  501.46  5026.3  501.01  5047.5  502.43  5061.6  503.99
  5132.4  504.70  5196.0  506.54  5217.2  507.74  5224.3  509.11  5238.4  510.72
  5266.7  512.71  5372.8  514.35  5401.1  514.92  5408.1  515.43  5431.0  515.66
#Mann=3,-1,0
  4709.1    0.05       0  4971.9    0.04       0  4975.9    0.05       0
Bank Sta=4971.9,4975.9
Exp/Cntr=0.3,0.1

Chan Stop Cuts=-1