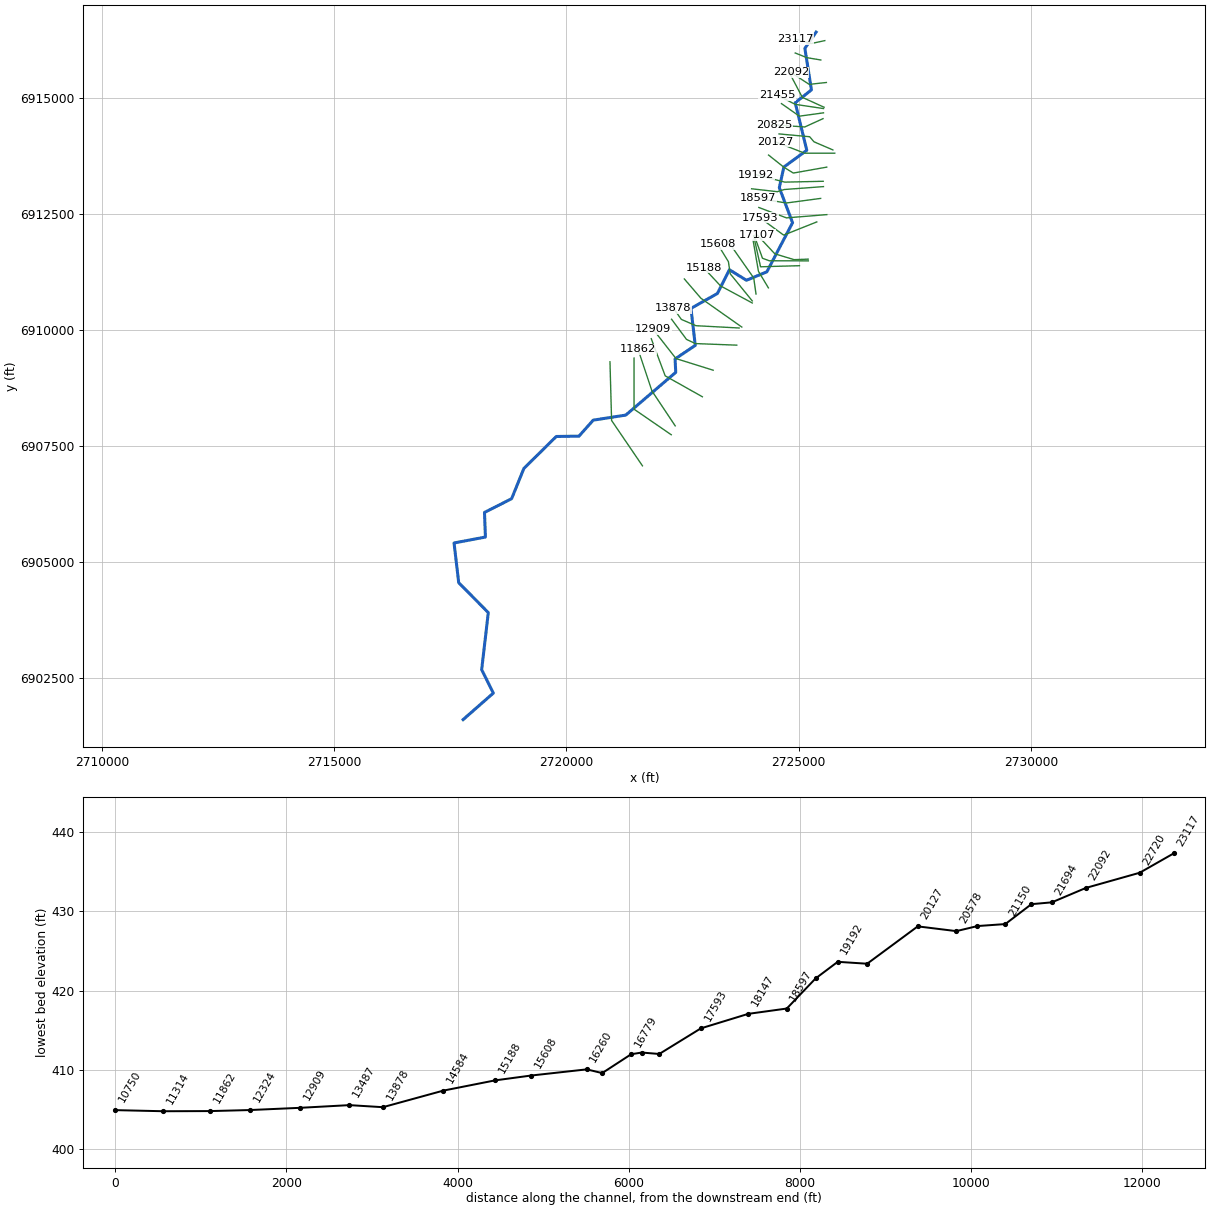
--- Massey Branch.prj (project) ---

Proj Title=Massey Branch Base Level Engineering
Current Plan=p01
Default Exp/Contr=0.3,0.1
English Units
Geom File=g01
Flow File=f01
Plan File=p01
Y Axis Title=Elevation
X Axis Title(PF)=Main Channel Distance
X Axis Title(XS)=Station
BEGIN DESCRIPTION:
Massey Branch
END DESCRIPTION:
DSS Export Rating Curves= 0
DSS Export Rating Curve Sorted= 0
DSS Export Volume Flow Curves= 0
DXF OffsetX= 0
DXF OffsetY= 0
DXF ScaleX= 1
DXF ScaleY= 10

--- Massey Branch.p01 (plan) ---

Plan Title=Multiple Run
Short Identifier=Multiple
Geom File=g01
Flow File=f01
Subcritical Flow
K Sum by GR= 0
Std Step Tol= 0.01
Critical Tol= 0.01
Num of Std Step Trials= 20
Max Error Tol= 0.3
Flow Tol Ratio= 0.001
Split Flow NTrial= 30
Split Flow Tol= 0.02
Split Flow Ratio= 0.02
Log Output Level= 0
Friction Slope Method= 1
Unsteady Friction Slope Method= 2
Unsteady Bridges Friction Slope Method= 1
Parabolic Critical Depth
Global Vel Dist=  1 , 1 , 1
Global Log Level= 0
CheckData=True
Encroach Param= -1, 0, 0, 0
BEGIN DESCRIPTION:
Multiple Run
END DESCRIPTION:

--- Massey Branch.f01 (steady flow) ---

Flow Title=Multiple
Program Version=4.10
Number of Profiles= 7
Profile Names=10-year,25-year,50-year,1pct_min,100-year,1pct_plu,500-year
River Rch & RM=Massey Branch,Reach-1         ,23117
     590     786     944     563    1123    2240    1585
River Rch & RM=Massey Branch,Reach-1         ,17107
     887    1209    1474     891    1777    3545    2581
River Rch & RM=Massey Branch,Reach-1         ,16260
    1090    1498    1836    1114    2223    4435    3255
River Rch & RM=Massey Branch,Reach-1         ,9835
    1253    1736    2139    1304    2601    5190    3847
River Rch & RM=Massey Branch,Reach-1         ,9665
    1281    1777    2190    1336    2666    5319    3950
Boundary for River Rch & Prof#=Massey Branch,Reach-1         , 1
Up Type= 0
Dn Type= 3
Dn Slope=0.005
Boundary for River Rch & Prof#=Massey Branch,Reach-1         , 2
Up Type= 0
Dn Type= 3
Dn Slope=0.005
Boundary for River Rch & Prof#=Massey Branch,Reach-1         , 3
Up Type= 0
Dn Type= 3
Dn Slope=0.005
Boundary for River Rch & Prof#=Massey Branch,Reach-1         , 4
Up Type= 0
Dn Type= 3
Dn Slope=0.005
Boundary for River Rch & Prof#=Massey Branch,Reach-1         , 5
Up Type= 0
Dn Type= 3
Dn Slope=0.005
Boundary for River Rch & Prof#=Massey Branch,Reach-1         , 6
Up Type= 0
Dn Type= 3
Dn Slope=0.005
Boundary for River Rch & Prof#=Massey Branch,Reach-1         , 7
Up Type= 0
Dn Type= 3
Dn Slope=0.005
DSS Import GetInterval= 0
DSS Import GetPeak= 0
DSS Import FillOption= 0

--- Massey Branch.g01 (geometry) ---

Geom Title=Existing Conditions
Program Version=4.10

River Reach=Massey Branch   ,Reach-1
Reach XY= 30
        2725376.        6916411.      2725133.23      6916061.32
      2725274.38      6915167.03       2724925.7       6914890.9
      2725174.42      6913867.04      2724681.03      6913505.92
      2724583.01       6913061.2      2724868.59       6912307.6
      2724315.25      6911250.58        2723876.      6911068.56
      2723509.27      6911294.77      2723249.95       6910783.8
      2722681.09       6910463.3      2722773.95      6909666.84
      2722339.49      6909374.68      2722353.36      6909086.99
      2721278.42      6908166.54      2720577.45       6908057.5
      2720270.14      6907713.07      2719781.46       6907705.8
      2719084.16      6907017.05      2718820.42      6906366.58
      2718236.45      6906070.79      2718256.44       6905540.8
      2717580.94      6905413.56      2717681.45      6904557.99
      2718318.19      6903914.42      2718175.58      6902686.01
      2718426.61      6902181.26        2717776.        6901611.

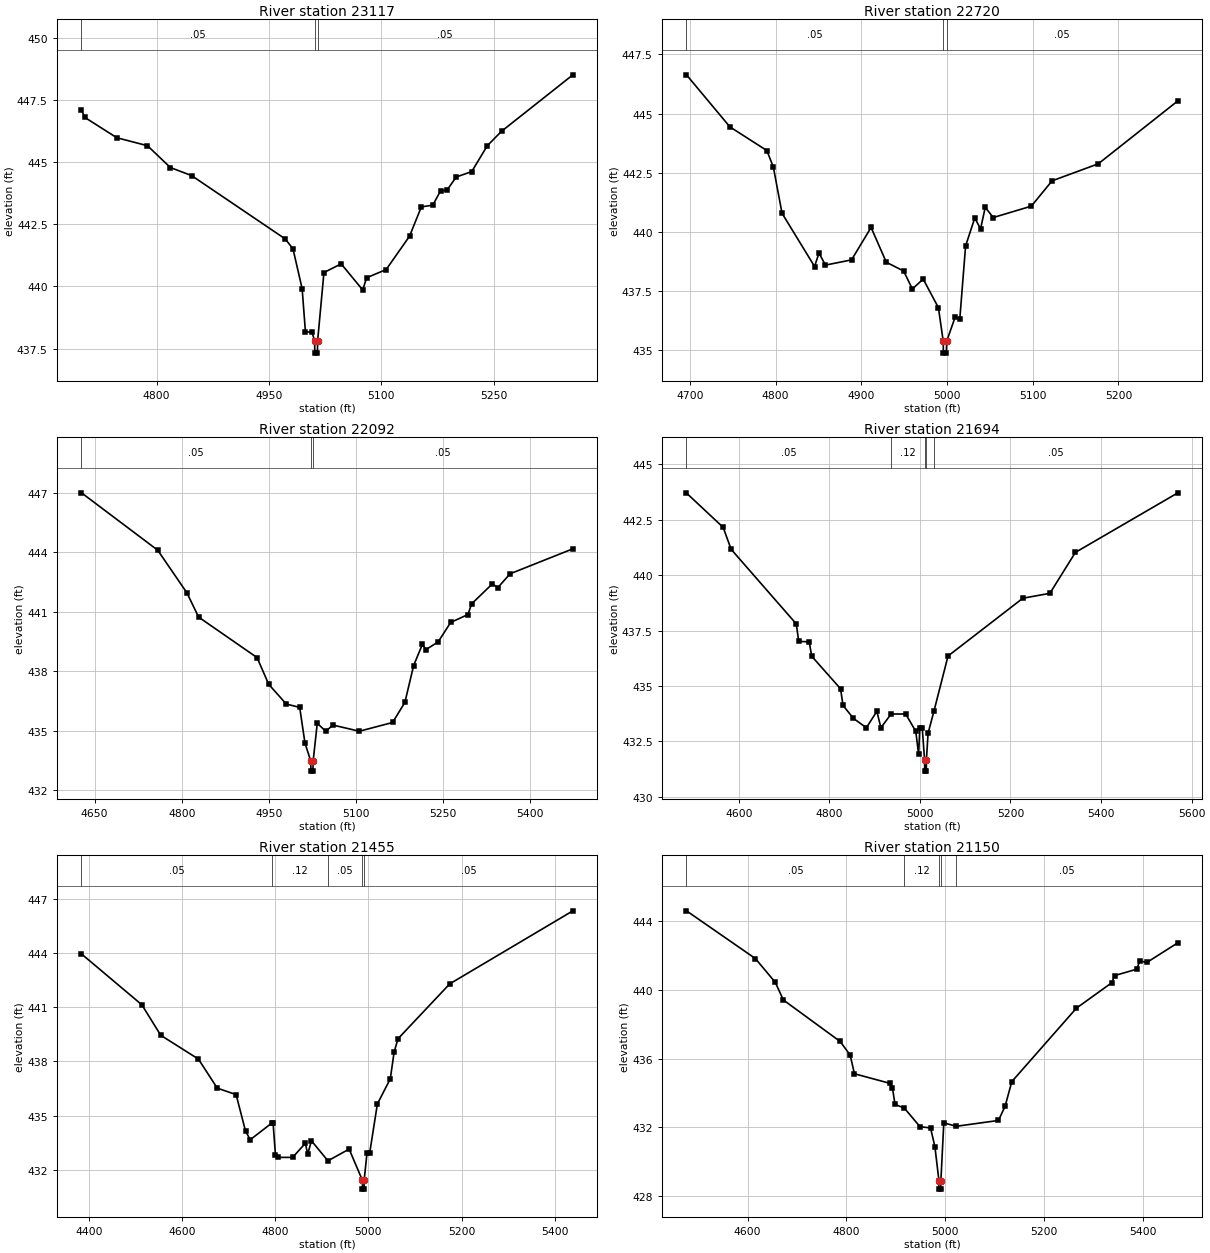
Type RM Length L Ch R = 1 ,23117   ,397,397,397
BEGIN DESCRIPTION:
Massey Branch 33.0
END DESCRIPTION:
XS GIS Cut Line= 3
       2725562.1      6916227.58      2725268.47      6916164.15
        2724926.        6916261.
#Sta/Elev= 30
  4699.6   447.1  4703.9   446.8  4746.8  445.98  4787.7  445.66  4818.4  444.78
  4846.6  444.46  4971.8  441.91  4982.1  441.51  4994.3  439.91  4998.7  438.17
  5007.3  438.17    5011  437.82  5011.2  437.32  5014.7  437.32    5015  437.82
  5023.4  440.56  5046.4  440.91  5075.2  439.86  5080.4  440.35  5106.5  440.68
  5137.7  442.02  5153.5   443.2  5168.8  443.27  5179.2  443.85  5187.5  443.86
    5200   444.4  5220.8  444.62  5241.6  445.66  5260.6  446.24  5355.9  448.51
#Mann= 3 ,-1 , 0
  4699.6     .05       0    5011     .04       0    5015     .05       0
Bank Sta=5011,5015
XS Rating Curve= 0 ,0
Exp/Cntr=0.3,0.1

Type RM Length L Ch R = 1 ,22720   ,628,628,628
BEGIN DESCRIPTION:
Massey Branch 32.0
END DESCRIPTION:
XS GIS Cut Line= 3
      2725475.98        6915811.        2725176.        6915861.
      2724925.98      6915961.01
#Sta/Elev= 30
  4695.9  446.64  4746.6  444.44  4789.7  443.44  4797.3  442.74  4807.4  440.79
  4845.4  438.54  4850.5  439.11  4858.1   438.6  4888.5  438.82  4911.3  440.19
  4929.1  438.72  4949.3  438.35  4959.5  437.59  4972.1  438.01  4989.9   436.8
  4995.5  435.38  4995.7  434.88  4999.2  434.88  4999.5  435.38  5009.4   436.4
  5014.8  436.31  5021.6  439.41  5032.3  440.59  5039.1  440.13  5044.5  441.04
  5053.9  440.61  5098.3  441.09  5122.5  442.16  5176.4  442.88  5269.3  445.54
#Mann= 3 ,-1 , 0
  4695.9     .05       0  4995.5     .04       0  4999.5     .05       0
Bank Sta=4995.5,4999.5
XS Rating Curve= 0 ,0
Exp/Cntr=0.3,0.1

Type RM Length L Ch R = 1 ,22092   ,398,398,398
BEGIN DESCRIPTION:
Massey Branch 31.0
END DESCRIPTION:
XS GIS Cut Line= 3
      2725596.44      6915326.25      2725226.02        6915286.
      2724829.88      6915544.83
#Sta/Elev= 30
  4627.4  446.99  4758.6   444.1  4808.9  441.95    4829  440.73  4929.6  438.69
  4949.7  437.34  4979.9  436.35    5003  436.18    5012  434.39  5022.1  433.47
  5022.3  432.97  5025.8  432.97  5026.1  433.47  5033.2  435.38  5047.8  434.98
  5060.3  435.29  5105.6  434.98  5162.9  435.42    5184  436.43  5199.1  438.29
  5214.2  439.36  5220.2  439.09  5241.3  439.48  5262.8  440.46  5292.6  440.86
  5298.7  441.39  5334.8  442.41  5343.9  442.21    5365  442.91  5473.2  444.17
#Mann= 3 ,-1 , 0
  4627.4     .05       0  5022.1     .04       0  5026.1     .05       0
Bank Sta=5022.1,5026.1
XS Rating Curve= 0 ,0
Exp/Cntr=0.3,0.1

Type RM Length L Ch R = 1 ,21694   ,239,239,239
BEGIN DESCRIPTION:
Massey Branch 30.0
END DESCRIPTION:
XS GIS Cut Line= 3
      2725546.73      6914793.31      2725077.73      6915006.81
       2724813.3      6915511.31
#Sta/Elev= 30
  4484.7  443.71  4565.7  442.16  4583.3  441.17  4727.1   437.8  4732.6  437.01
  4755.7  436.99  4761.2  436.34  4824.9  434.87  4830.3  434.12  4853.4  433.53
  4881.9  433.11    4905  433.85    4914  433.11  4936.5  433.73  4968.7  433.73
  4990.9  432.95  4997.2  431.92    5000  433.12  5005.2  433.12  5010.4  431.65
  5010.7  431.15  5014.2  431.15  5014.4  431.65  5018.1  432.86  5031.2  433.87
  5062.2  436.35  5227.4  438.96    5287  439.18  5343.4  441.03  5569.6  443.72
#Mann= 5 ,-1 , 0
  4484.7     .05       0  4936.5     .12       0  5010.4     .07       0
  5014.4     .12       0  5031.2     .05       0
Bank Sta=5010.4,5014.4
XS Rating Curve= 0 ,0
Exp/Cntr=0.3,0.1

Type RM Length L Ch R = 1 ,21455   ,305,305,305
BEGIN DESCRIPTION:
Massey Branch 29.0
END DESCRIPTION:
XS GIS Cut Line= 3
      2725534.23      6914764.87      2724925.06      6914855.65
       2724534.7      6915056.29
#Sta/Elev= 30
  4384.1  443.96  4513.7  441.14  4554.2  439.45  4635.1  438.13  4675.5  436.52
    4716  436.16  4736.2  434.14  4746.3  433.66    4794  434.61  4795.3  434.61
  4800.4  432.83  4806.9  432.68  4837.3  432.68  4864.6  433.46  4869.7  432.86
  4877.7   433.6  4913.1  432.49  4958.6  433.14  4986.9  431.42  4987.2  430.92
  4990.7  430.92  4990.9  431.42    4997  432.94  5002.7  432.92  5019.2  435.64
    5047  437.04  5055.2  438.53  5063.6  439.26  5174.5   442.3  5438.9  446.35
#Mann= 5 ,-1 , 0
  4384.1     .05       0    4794     .12       0  4913.1     .05       0
  4986.9     .04       0  4990.9     .05       0
Bank Sta=4986.9,4990.9
XS Rating Curve= 0 ,0
Exp/Cntr=0.3,0.1

Type RM Length L Ch R = 1 ,21150   ,325,325,325
BEGIN DESCRIPTION:
Massey Branch 28.0
END DESCRIPTION:
XS GIS Cut Line= 3
      2725534.18      6914672.86      2725015.37      6914601.45
      2724629.46      6914871.46
#Sta/Elev= 30
  4476.3  444.62  4615.8  441.84  4656.2  440.45  4672.3  439.43  4787.4  437.01
  4807.6  436.22  4816.3  435.13  4888.3  434.57  4893.3   434.3  4898.4  433.35
  4917.6  433.12  4948.9  432.05  4970.4  431.97  4979.2  430.88  4987.3  428.91
  4987.5  428.41    4991  428.41  4991.3  428.91  4997.2  432.27  5022.4  432.07
  5107.8  432.41  5121.3  433.24  5134.8  434.67  5265.6  438.95  5337.1  440.43
  5343.2  440.85  5387.7  441.22  5393.8  441.69  5408.6  441.62    5471  442.76
#Mann= 5 ,-1 , 0
  4476.3     .05       0  4917.6     .12       0  4987.3     .07       0
  4991.3     .12       0  5022.4     .05       0
Bank Sta=4987.3,4991.3
XS Rating Curve= 0 ,0
Exp/Cntr=0.3,0.1

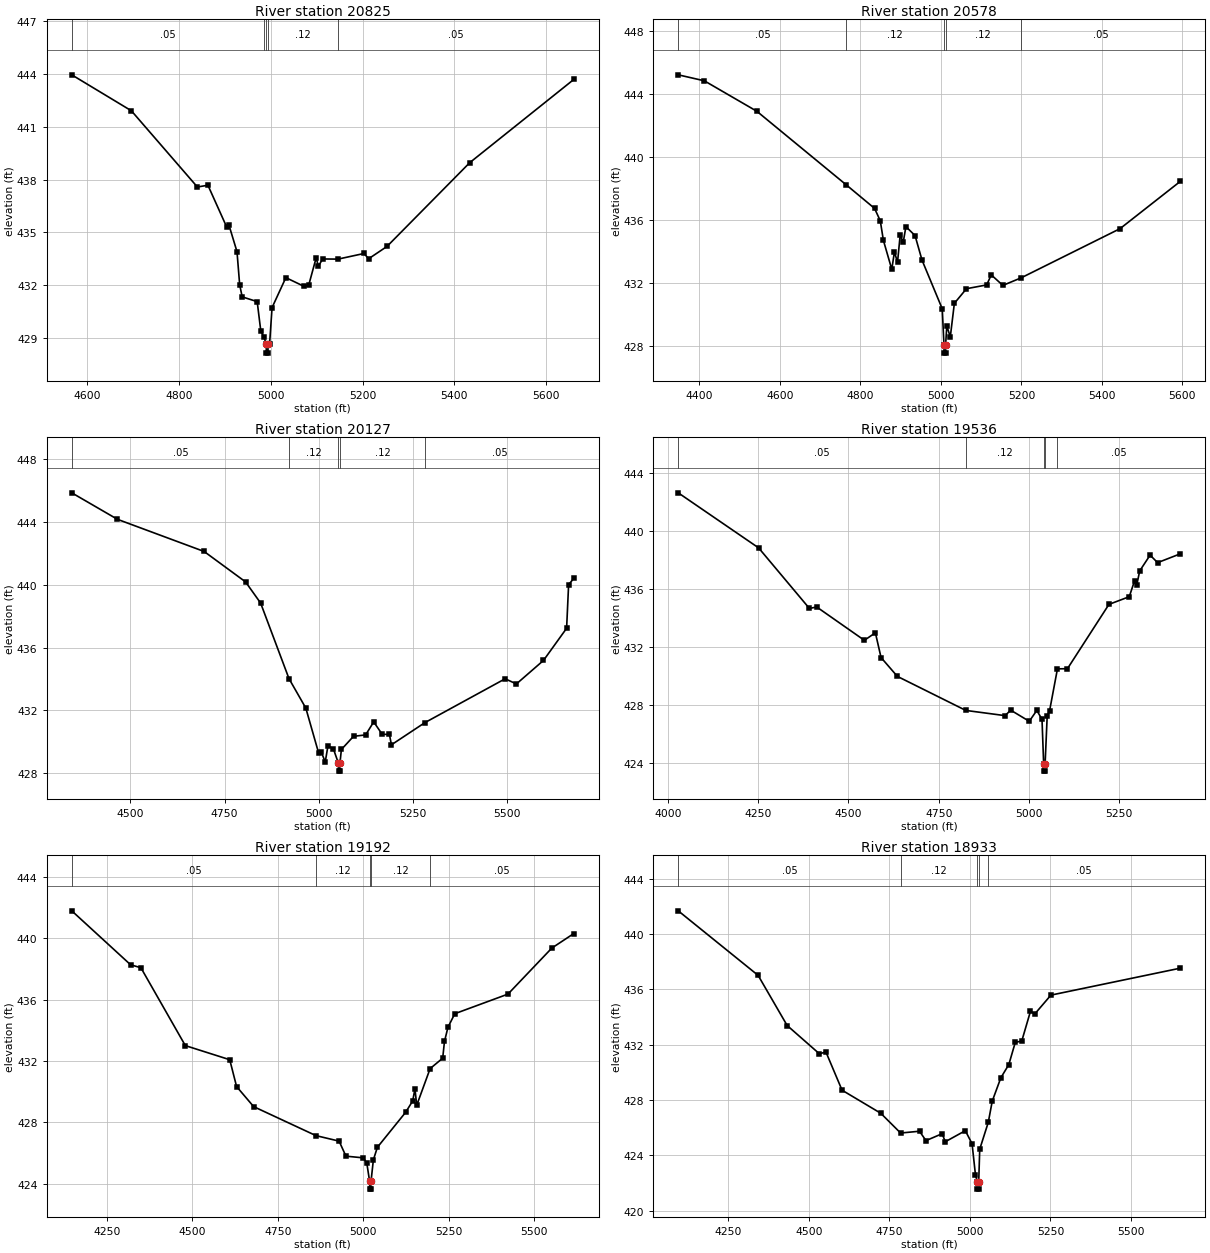
Type RM Length L Ch R = 1 ,20825   ,247,247,247
BEGIN DESCRIPTION:
Mapping XS dddc06c5
END DESCRIPTION:
XS GIS Cut Line= 3
       2725523.8      6914547.87      2725131.42      6914369.05
      2724469.66      6914414.09
#Sta/Elev= 30
  4565.9  443.94  4695.9   441.9  4839.7  437.58  4862.7  437.68  4903.3  435.33
  4908.8   435.4  4926.1  433.91  4931.9  432.04  4937.4  431.35  4970.1  431.08
    4978  429.41  4985.1  429.06  4989.8  428.66  4990.1  428.16  4993.6  428.16
  4993.8  428.66  4997.1  428.66  5002.5  430.74  5032.6  432.44  5072.7  431.94
  5082.7  432.04  5098.6  433.56  5103.6  433.09  5112.8   433.5  5146.2  433.49
    5203  433.81    5213  433.51  5253.1  434.21  5433.5  438.96  5660.4  443.68
#Mann= 5 ,-1 , 0
  4565.9     .05       0  4985.1     .12       0  4989.8     .07       0
  4993.8     .12       0  5146.2     .05       0
Bank Sta=4989.8,4993.8
XS Rating Curve= 0 ,0
Exp/Cntr=0.3,0.1

Type RM Length L Ch R = 1 ,20578   ,451,451,451
BEGIN DESCRIPTION:
Mapping XS 6b888474
END DESCRIPTION:
XS GIS Cut Line= 4
      2725735.58      6913875.13      2725329.34       6914049.6
      2725235.59      6914158.98      2724576.78      6914218.87
#Sta/Elev= 30
  4347.2  445.23    4412  444.85  4542.6  442.91  4765.1  438.22  4835.1  436.73
  4849.3  435.94    4857   434.7  4877.9  432.85  4884.5  433.97  4892.1  433.29
  4898.7  435.02  4906.4  434.59    4913  435.57  4935.7     435    4953  433.44
  5003.3  430.34  5007.6  428.02  5007.9  427.52  5011.4  427.52  5011.6  428.02
  5014.6  429.25  5023.3  428.55  5033.4  430.69  5063.5  431.62  5113.7  431.86
  5125.1   432.5  5153.9  431.83  5199.3  432.31  5445.1  435.44  5594.9  438.45
#Mann= 5 ,-1 , 0
  4347.2     .05       0  4765.1     .12       0  5007.6     .07       0
  5011.6     .12       0  5199.3     .05       0
Bank Sta=5007.6,5011.6
XS Rating Curve= 0 ,0
Exp/Cntr=0.3,0.1

Type RM Length L Ch R = 1 ,20127   ,591,591,591
BEGIN DESCRIPTION:
Mapping XS feed1708
END DESCRIPTION:
XS GIS Cut Line= 3
      2725777.28      6913804.81      2725126.21      6913804.81
      2724490.94      6914052.15
#Sta/Elev= 30
  4344.5  445.87  4465.8  444.18  4695.8  442.13  4805.8  440.19  4845.8  438.84
  4921.1  434.02  4965.8  432.14    5000  429.26  5006.5  429.37  5017.3   428.7
  5024.5  429.72  5038.7  429.56  5052.4  428.62  5052.6  428.12  5056.1  428.12
  5056.4  428.62  5060.2   429.5  5092.4  430.34  5124.6  430.43    5146  431.26
  5168.5  430.47  5187.7  430.46  5193.1   429.8  5281.7  431.21  5494.9  434.01
  5524.8  433.68  5596.7  435.18  5658.1  437.23  5663.4  440.01  5677.3  440.42
#Mann= 5 ,-1 , 0
  4344.5     .05       0  4921.1     .12       0  5052.4     .07       0
  5056.4     .12       0  5281.7     .05       0
Bank Sta=5052.4,5056.4
XS Rating Curve= 0 ,0
Exp/Cntr=0.3,0.1

Type RM Length L Ch R = 1 ,19536   ,344,344,344
BEGIN DESCRIPTION:
Mapping XS 2edcf3a6
END DESCRIPTION:
XS GIS Cut Line= 4
       2725603.8      6913504.29      2724885.07      6913376.69
      2724681.94      6913501.69      2724351.24      6913764.68
#Sta/Elev= 30
  4028.3  442.62    4251  438.82  4391.7  434.64    4412  434.74    4544  432.44
  4574.5  432.96  4590.2  431.25  4635.4  429.95  4825.1   427.6  4933.9  427.24
  4949.3  427.62  5000.8  426.85  5021.7   427.6  5036.1  426.99  5040.7  423.91
  5040.9  423.41  5044.4  423.41  5044.7  423.91  5050.5  427.22  5056.9  427.55
  5078.9  430.47  5106.6  430.48  5221.6  434.92  5277.9  435.45  5292.4  436.54
  5298.8  436.28  5306.8  437.23  5335.6  438.32  5356.4   437.8  5419.3  438.41
#Mann= 5 ,-1 , 0
  4028.3     .05       0  4825.1     .12       0  5040.7     .07       0
  5044.7     .12       0  5078.9     .05       0
Bank Sta=5040.7,5044.7
XS Rating Curve= 0 ,0
Exp/Cntr=0.3,0.1

Type RM Length L Ch R = 1 ,19192   ,259,259,259
BEGIN DESCRIPTION:
Mapping XS 767338e7
END DESCRIPTION:
XS GIS Cut Line= 3
      2725528.27       6913199.6      2724700.17      6913181.37
      2724079.42       6913342.4
#Sta/Elev= 30
    4147   441.8  4319.3  438.28  4349.3  438.09  4479.4  433.01  4609.4  432.09
  4629.4  430.34  4679.4  429.03  4861.7  427.14  4929.5  426.78  4949.5   425.8
  5000.3  425.69  5010.6  425.34  5018.9  424.15  5019.2  423.65  5022.7  423.65
  5022.9  424.15  5029.8  425.56  5041.6  426.38  5124.2  428.66  5144.9   429.4
  5151.5  430.19  5156.7  429.12  5195.9  431.51  5232.7  432.19  5237.9  433.28
  5248.2  434.21  5268.1  435.09  5423.8  436.37  5552.1  439.37  5616.6  440.32
#Mann= 5 ,-1 , 0
    4147     .05       0  4861.7     .12       0  5018.9     .07       0
  5022.9     .12       0  5195.9     .05       0
Bank Sta=5018.9,5022.9
XS Rating Curve= 0 ,0
Exp/Cntr=0.3,0.1

Type RM Length L Ch R = 1 ,18933   ,336,336,336
BEGIN DESCRIPTION:
Mapping XS d9241c34
END DESCRIPTION:
XS GIS Cut Line= 4
      2725533.46      6913085.02      2724692.36      6913022.52
      2724538.71      6912975.64      2723986.59      6913038.15
#Sta/Elev= 30
  4093.9  441.69    4342  437.02  4432.3  433.39  4532.6  431.34  4552.6  431.48
  4602.8  428.71  4723.1  427.04  4784.7  425.61  4843.4  425.74  4863.5  425.06
  4913.6  425.56  4923.6  424.98  4985.8  425.78  5006.7  424.83  5017.2  422.59
  5023.3  422.05  5023.5  421.55    5027  421.55  5027.3  422.05  5030.5  424.44
    5057  426.38  5069.4  427.92  5096.1  429.61  5120.8  430.56  5140.9  432.17
  5161.1  432.27  5188.1  434.42  5201.3  434.22  5251.6  435.59  5653.6  437.54
#Mann= 5 ,-1 , 0
  4093.9     .05       0  4784.7     .12       0  5023.3     .07       0
  5027.3     .12       0    5057     .05       0
Bank Sta=5023.3,5027.3
XS Rating Curve= 0 ,0
Exp/Cntr=0.3,0.1

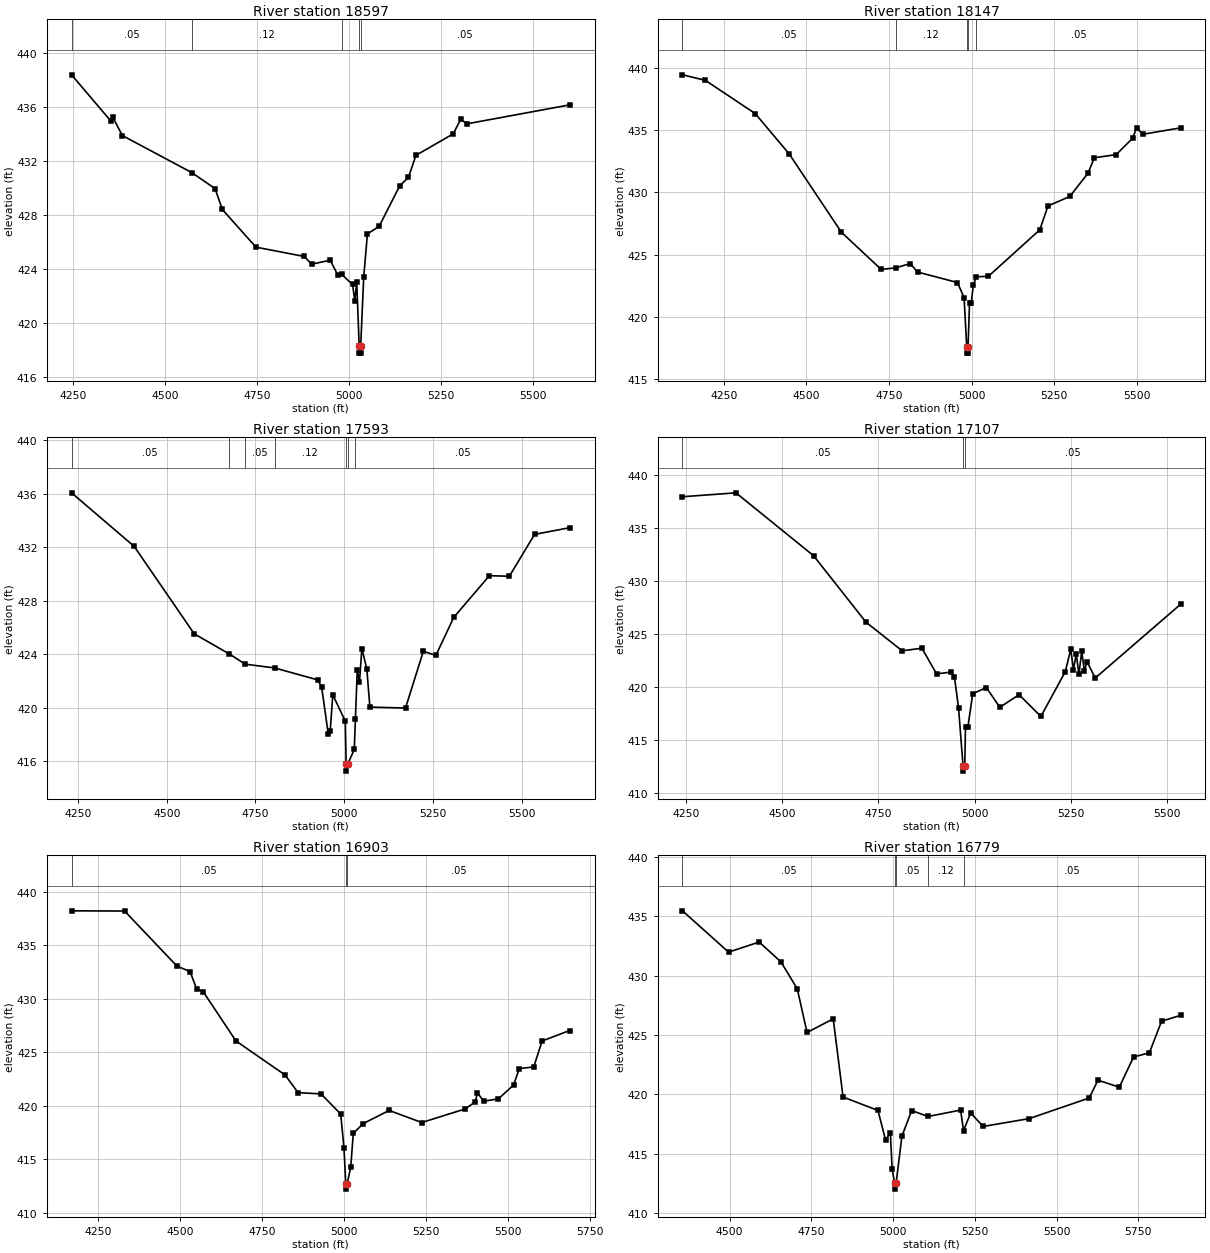
Type RM Length L Ch R = 1 ,18597   ,450,450,450
BEGIN DESCRIPTION:
Mapping XS b77c2fb0
END DESCRIPTION:
XS GIS Cut Line= 3
      2725472.56       6912830.9      2724732.94      6912731.94
      2724133.97       6912830.9
#Sta/Elev= 30
  4246.4   438.4  4353.8  434.95  4358.8  435.25  4384.2   433.9    4573  431.15
  4636.4  429.96  4655.9  428.42  4747.4  425.62  4878.5  424.93  4898.7  424.36
  4949.2  424.65  4969.3  423.58    4980  423.61  5009.8  422.85  5016.2  421.65
  5021.3  423.02    5028  418.26  5028.3  417.76  5031.8  417.76    5032  418.26
  5040.2  423.39  5050.3   426.6  5082.3  427.17  5138.3  430.18  5161.8  430.79
  5182.1  432.43  5283.4  434.02  5303.7  435.09  5321.6  434.77  5599.7  436.17
#Mann= 5 ,-1 , 0
  4246.4     .05       0    4573     .12       0    4980     .05       0
    5028     .04       0    5032     .05       0
Bank Sta=5028,5032
XS Rating Curve= 0 ,0
Exp/Cntr=0.3,0.1

Type RM Length L Ch R = 1 ,18147   ,554,554,554
BEGIN DESCRIPTION:
Mapping XS 04850723
END DESCRIPTION:
XS GIS Cut Line= 3
      2725605.29      6912481.93      2724738.15      6912411.62
       2724141.8      6912635.58
#Sta/Elev= 30
  4124.8  439.44  4193.8     439  4344.8  436.33  4447.9  433.08  4605.7   426.8
  4726.1  423.81  4769.8  423.94  4814.1  424.28  4836.4   423.6  4956.8  422.76
  4976.9  421.55  4984.9  417.59  4985.2  417.09  4988.7  417.09  4988.9  417.59
  4993.4  421.14  4998.6  421.14  5004.8  422.54  5013.8  423.22  5050.5  423.26
  5205.9  426.99  5230.8  428.91  5296.6  429.67  5351.7  431.53    5371  432.78
  5437.1  433.03  5486.9  434.35  5499.1  435.19  5517.2  434.66  5631.8  435.18
#Mann= 5 ,-1 , 0
  4124.8     .05       0  4769.8     .12       0  4984.9     .07       0
  4988.9     .12       0  5013.8     .05       0
Bank Sta=4984.9,4988.9
XS Rating Curve= 0 ,0
Exp/Cntr=0.3,0.1

Type RM Length L Ch R = 1 ,17593   ,486,486,486
BEGIN DESCRIPTION:
Mapping XS 0e1c42ec
END DESCRIPTION:
XS GIS Cut Line= 3
      2725390.01      6912324.66      2724676.43      6912040.79
      2724163.43      6912415.77
#Sta/Elev= 30
  4231.9  436.08  4408.4  432.07  4577.6  425.53  4675.4  424.04  4721.4  423.26
  4803.9  422.98    4925  422.09  4936.4  421.58  4955.3  418.02  4960.7  418.27
    4968  420.97  5003.2     419  5005.6  415.76  5005.9  415.26  5009.6  415.76
  5028.5  416.88  5031.7  419.13    5037  422.85  5043.2  421.91  5049.9  424.43
    5064  422.88  5072.5  420.05  5172.9  419.98  5223.1  424.22  5258.6  423.92
  5308.8  426.76  5409.2  429.88  5465.6  429.84  5536.6  432.97  5635.3  433.47
#Mann= 7 ,-1 , 0
  4231.9     .05       0  4675.4     .12       0  4721.4     .05       0
  4803.9     .12       0  5005.6     .07       0  5009.6     .12       0
  5031.7     .05       0
Bank Sta=5005.6,5009.6
XS Rating Curve= 0 ,0
Exp/Cntr=0.3,0.1

Type RM Length L Ch R = 1 ,17107   ,204,204,204
BEGIN DESCRIPTION:
Mapping XS fc11a0ce
END DESCRIPTION:
XS GIS Cut Line= 4
      2725204.68      6911523.43      2724900.82      6911512.58
      2724486.32      6911638.45      2724106.58      6912044.23
#Sta/Elev= 30
  4241.5  437.94  4380.3  438.31  4581.9  432.37  4717.8   426.1  4811.9  423.39
    4863  423.64  4901.1  421.22  4939.2  421.38  4947.7  420.88  4958.2  418.01
  4969.9  412.53  4970.3  412.03  4974.3  412.53  4976.3  416.24  4982.6  416.24
  4995.1  419.34  5030.3  419.92  5065.5  418.06  5115.3  419.25    5172  417.19
  5235.5  421.43  5249.6  423.55  5256.5   421.6  5263.8  423.09  5270.7  421.17
    5278  423.34  5284.8  421.51  5292.1  422.34  5313.1  420.82  5534.5  427.78
#Mann= 3 ,-1 , 0
  4241.5     .05       0  4969.9     .04       0  4974.3     .05       0
Bank Sta=4969.9,4974.3
XS Rating Curve= 0 ,0
Exp/Cntr=0.3,0.1

Type RM Length L Ch R = 1 ,16903   ,124,124,124
BEGIN DESCRIPTION:
Mapping XS 2f456e82
END DESCRIPTION:
XS GIS Cut Line= 4
      2725207.95      6911486.54      2724365.95      6911488.71
      2724220.56      6911542.96      2724042.59      6912035.61
#Sta/Elev= 30
  4167.8   438.2  4329.8  438.18  4489.8  433.03  4529.8  432.53  4549.8  430.89
  4569.8  430.65  4669.8  426.05  4819.8  422.87  4859.8  421.22  4929.8   421.1
  4989.8  419.22  4999.8  416.04  5005.1  412.71  5005.5  412.21  5009.5  412.71
  5020.4  414.28  5028.2  417.42  5058.5  418.33  5137.8  419.56  5237.3  418.43
    5370   419.7  5400.6  420.36  5407.5  421.21    5426  420.42  5471.2  420.64
    5518  421.94    5535  423.47  5579.3  423.62  5604.7  426.04  5688.8  427.02
#Mann= 3 ,-1 , 0
  4167.8     .05       0  5005.1     .04       0  5009.5     .05       0
Bank Sta=5005.1,5009.5
XS Rating Curve= 0 ,0
Exp/Cntr=0.3,0.1

Type RM Length L Ch R = 1 ,16779   ,339,339,339
BEGIN DESCRIPTION:
Mapping XS cc7c3efe
END DESCRIPTION:
XS GIS Cut Line= 4
      2725016.97      6911382.37      2724381.15      6911365.01
      2724179.32       6911358.5      2724029.93      6912027.53
#Sta/Elev= 30
  4355.8  435.45  4496.8  431.97  4590.5  432.82  4656.9  431.15  4706.9  428.88
  4736.9   425.2  4816.9  426.35    4847  419.76  4953.8  418.63    4977  416.15
  4991.9  416.74    4997  413.71  5004.8   412.5  5005.2     412  5009.3   412.5
    5027  416.46    5057  418.62    5107  418.12  5206.6  418.66  5215.6  416.93
  5237.3  418.42  5275.5  417.28  5416.1  417.94  5600.1  419.68  5626.7  421.18
  5692.1  420.59  5735.5  423.13  5784.1  423.49  5821.4  426.15  5879.3  426.64
#Mann= 5 ,-1 , 0
  4355.8     .05       0  5004.8     .04       0  5009.3     .05       0
    5107     .12       0  5215.6     .05       0
Bank Sta=5004.8,5009.3
XS Rating Curve= 0 ,0
Exp/Cntr=0.3,0.1

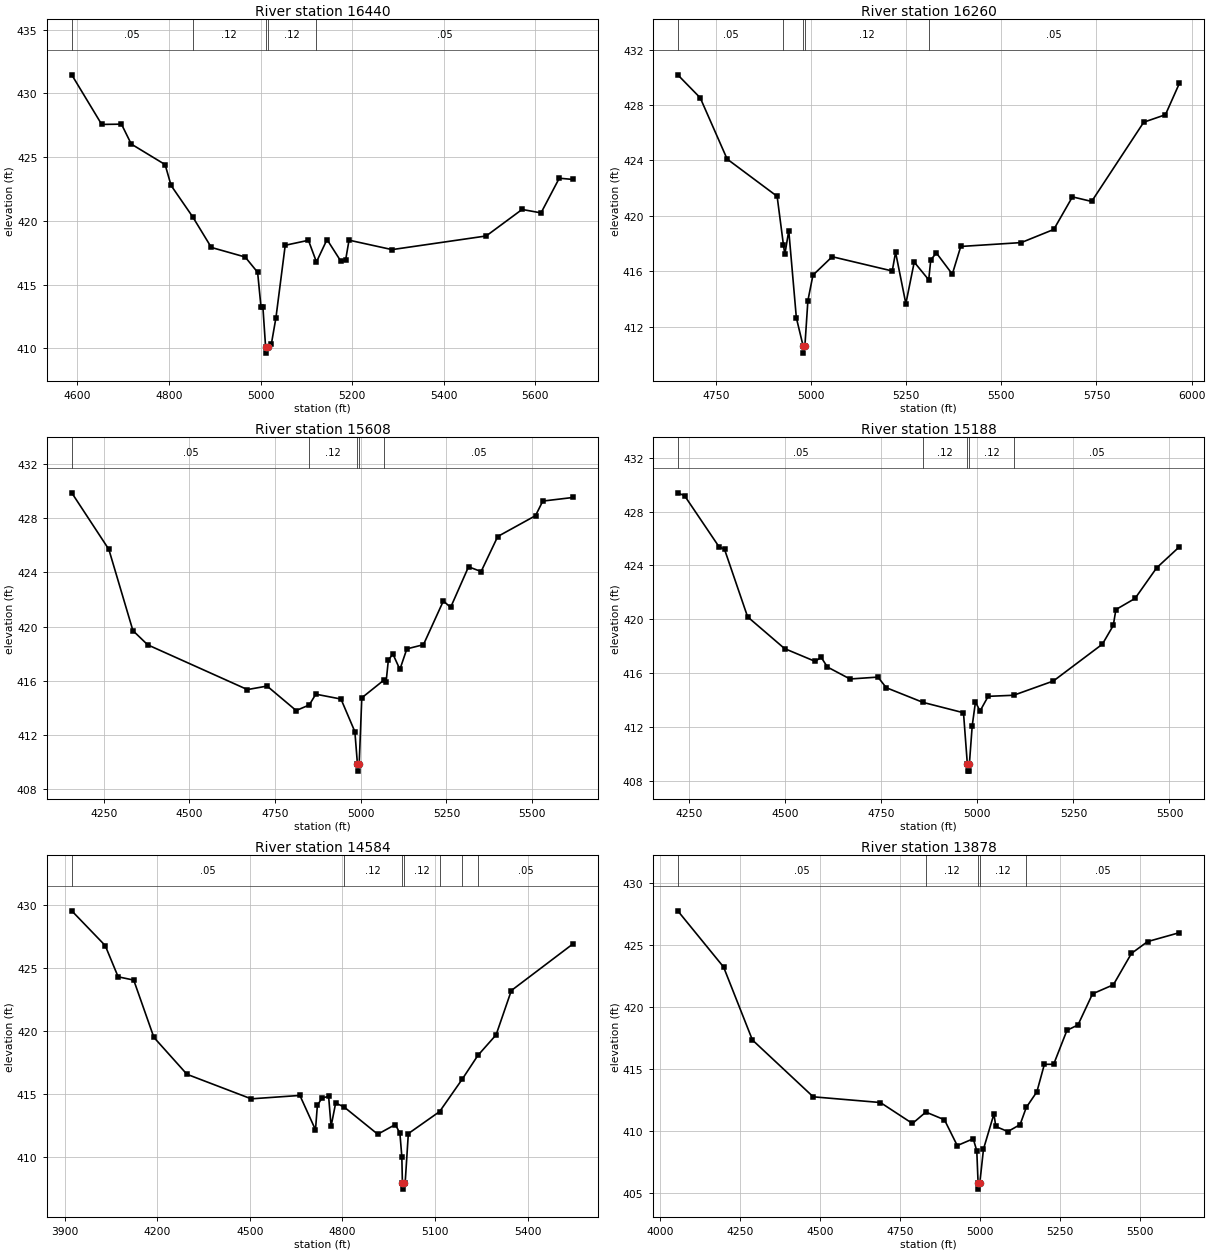
Type RM Length L Ch R = 1 ,16440   ,180,180,180
BEGIN DESCRIPTION:
Mapping XS bdf9c900
END DESCRIPTION:
XS GIS Cut Line= 3
      2724348.15      6910904.96      2724133.32      6911263.01
       2724018.3      6911931.43
#Sta/Elev= 30
  4587.5  431.45  4652.9  427.56  4696.1  427.58  4717.5  426.02  4791.4  424.41
  4804.5  422.77  4851.7  420.31  4892.4  417.91  4966.3  417.16  4993.5  415.96
    5001   413.2  5005.1   413.2  5010.9  410.12  5011.4  409.62  5015.4  410.12
  5023.5  410.33  5033.5  412.39  5053.8  418.08  5104.5  418.47    5122  416.77
  5145.1  418.53  5175.5  416.82  5185.7  416.92  5193.2  418.48  5287.1  417.74
  5492.8  418.81  5571.2  420.89  5612.6  420.62  5652.4  423.34  5683.3  423.24
#Mann= 5 ,-1 , 0
  4587.5     .05       0  4851.7     .12       0  5010.9     .07       0
  5015.4     .12       0    5122     .05       0
Bank Sta=5010.9,5015.4
XS Rating Curve= 0 ,0
Exp/Cntr=0.3,0.1

Type RM Length L Ch R = 1 ,16260   ,652,652,652
BEGIN DESCRIPTION:
Massey Branch 17.0
END DESCRIPTION:
XS GIS Cut Line= 3
      2724081.23      6910772.61      2724032.19      6911118.85
        2723476.        6911911.
#Sta/Elev= 30
  4650.3  430.18  4709.3  428.52    4780   424.1  4911.3  421.41  4927.8  417.92
  4931.5  417.21  4941.9  418.93  4961.8  412.64  4979.7  410.59  4980.2  410.09
  4984.2  410.59  4992.1  413.88  5005.4  415.72  5055.9  417.05  5213.7  416.02
  5222.4  417.37  5249.4  413.66  5271.4  416.66  5309.5  415.38  5314.8  416.82
  5329.6  417.32  5371.4  415.79  5393.6  417.79  5552.5  418.07    5638  419.02
  5686.9  421.37  5737.4  421.04  5874.2  426.76  5931.2   427.3  5967.9  429.57
#Mann= 5 ,-1 , 0
  4650.3     .05       0  4927.8     .12       0  4979.7     .07       0
  4984.2     .12       0  5309.5     .05       0
Bank Sta=4979.7,4984.2
XS Rating Curve= 0 ,0
Exp/Cntr=0.3,0.1

Type RM Length L Ch R = 1 ,15608   ,420,420,420
BEGIN DESCRIPTION:
Mapping XS 3745fab7
END DESCRIPTION:
XS GIS Cut Line= 4
      2724000.78        6910624.      2723526.83      6911207.31
      2723487.77      6911467.73      2723253.38      6911850.57
#Sta/Elev= 30
  4156.7  429.89  4264.9  425.71  4335.2   419.7  4378.3  418.65  4669.2  415.34
  4726.7   415.6  4811.5  413.79  4849.6   414.2  4868.9     415  4942.3  414.64
  4982.8  412.23  4990.4  409.81    4991  409.31  4995.4  409.81    5003  414.73
  5066.5  416.02  5073.8  415.87  5080.6  417.54    5094  417.96  5114.2  416.83
  5134.5  418.35  5182.9  418.66    5241  421.89  5262.3  421.42  5314.5  424.42
  5351.2  424.07  5399.7  426.66  5509.9   428.2  5531.2  429.28  5620.5  429.55
#Mann= 5 ,-1 , 0
  4156.7     .05       0  4849.6     .12       0  4990.4     .07       0
  4995.4     .12       0  5066.5     .05       0
Bank Sta=4990.4,4995.4
XS Rating Curve= 0 ,0
Exp/Cntr=0.3,0.1

Type RM Length L Ch R = 1 ,15188   ,604,604,604
BEGIN DESCRIPTION:
Mapping XS 236eb309
END DESCRIPTION:
XS GIS Cut Line= 3
      2724000.77      6910579.72       2723318.5       6910946.9
      2722956.49      6911334.95
#Sta/Elev= 30
  4220.3  429.39  4238.2  429.17  4327.9  425.37    4342  425.19  4402.1  420.17
  4498.3  417.81  4577.8  416.86  4593.5  417.16  4609.8  416.44  4668.6  415.55
  4741.2  415.69  4763.1   414.9  4858.6  413.81  4963.9  413.04    4974   409.2
  4974.6   408.7  4978.4   408.7  4979.1   409.2  4986.6  412.07  4995.1  413.85
  5006.8  413.16  5028.1  414.26  5094.4  414.34  5197.8   415.4  5325.4  418.14
  5353.7  419.53  5360.5  420.71  5410.4  421.54  5466.5  423.81  5525.8  425.38
#Mann= 5 ,-1 , 0
  4220.3     .05       0  4858.6     .12       0    4974     .07       0
  4979.1     .12       0  5094.4     .05       0
Bank Sta=4974,4979.1
XS Rating Curve= 0 ,0
Exp/Cntr=0.3,0.1

Type RM Length L Ch R = 1 ,14584   ,706,706,706
BEGIN DESCRIPTION:
Massey Branch 15.0
END DESCRIPTION:
XS GIS Cut Line= 3
      2723775.97      6910061.02      2722895.84      6910681.39
      2722538.54      6911096.76
#Sta/Elev= 30
  3923.2  429.51  4031.6  426.75  4073.4  424.27  4123.9  424.01  4189.2  419.46
  4296.3  416.53  4504.5  414.58  4662.1  414.85  4712.6  412.12  4718.7  414.06
  4733.5  414.64  4755.1  414.78  4763.1   412.4  4777.9  414.24  4804.3  413.95
  4914.2  411.77  4971.3  412.54    4986  411.84  4992.2     410  4994.1  407.91
  4994.9  407.41  4999.5  407.91    5003  407.91  5013.3  411.82  5114.7  413.57
  5187.3  416.12  5238.6  418.03  5297.5  419.66  5346.9  423.18  5547.9  426.91
#Mann= 7 ,-1 , 0
  3923.2     .05       0  4804.3     .12       0  4994.1     .07       0
  4999.5     .12       0  5114.7     .05       0  5187.3     .12       0
  5238.6     .05       0
Bank Sta=4994.1,4999.5
XS Rating Curve= 0 ,0
Exp/Cntr=0.3,0.1

Type RM Length L Ch R = 1 ,13878   ,391,391,391
BEGIN DESCRIPTION:
Mapping XS 569814db
END DESCRIPTION:
XS GIS Cut Line= 4
      2723719.24      6910041.17      2722789.57      6910090.65
      2722474.46      6910226.06      2722303.36      6910467.16
#Sta/Elev= 30
  4054.3  427.75  4197.7  423.22  4287.9  417.34  4478.1  412.76  4688.4   412.3
  4788.6  410.61  4830.6  411.53  4888.7  410.91  4928.8  408.83  4978.8  409.38
  4989.9  408.41    4994  405.82  4994.8  405.32  4999.4  405.82  5010.9  408.55
  5043.6  411.38  5049.3  410.37  5087.1  409.96  5125.4  410.52  5144.7   411.9
  5177.9  413.16  5201.4  415.38  5230.4  415.38  5272.1  418.12  5306.5  418.55
  5352.1  421.06  5417.3  421.79  5473.9  424.32  5524.3  425.27  5623.9  425.99
#Mann= 5 ,-1 , 0
  4054.3     .05       0  4830.6     .12       0    4994     .07       0
  4999.4     .12       0  5144.7     .05       0
Bank Sta=4994,4999.4
XS Rating Curve= 0 ,0
Exp/Cntr=0.3,0.1

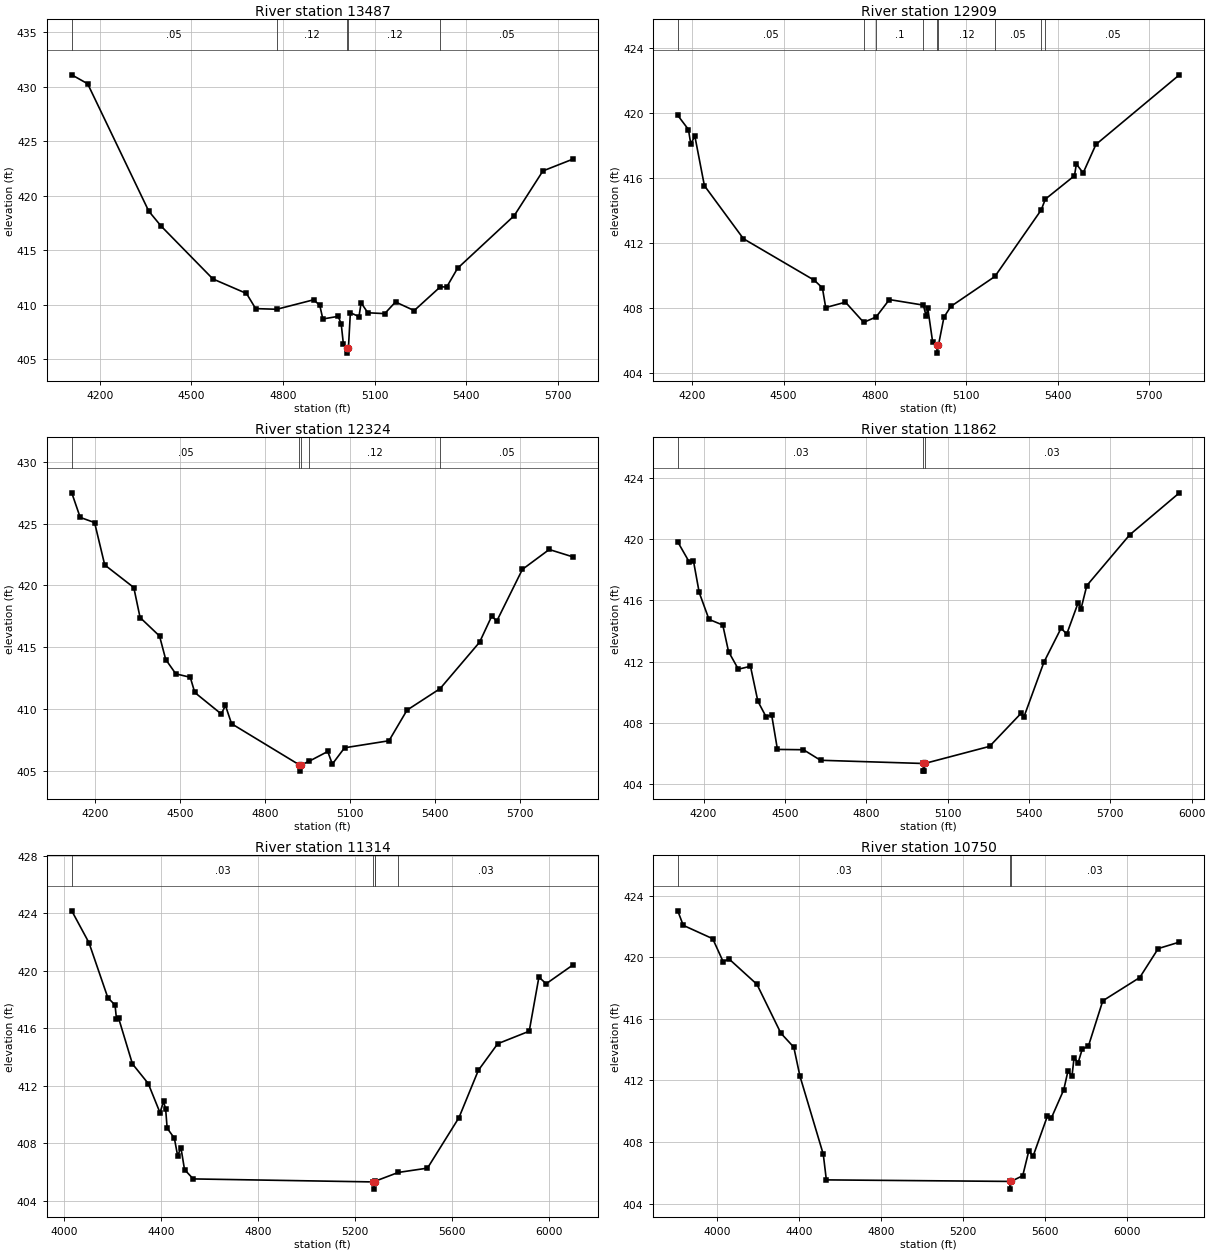
Type RM Length L Ch R = 1 ,13487   ,578,578,578
BEGIN DESCRIPTION:
Massey Branch 11.0
END DESCRIPTION:
XS GIS Cut Line= 4
      2723668.03      6909671.81      2722776.48       6909705.8
      2722585.14      6909795.51      2722263.94      6910229.56
#Sta/Elev= 30
  4107.8  431.09  4159.9  430.27    4360   418.6    4400  417.24  4570.2  412.38
  4680.2  411.05  4710.3  409.66  4779.4   409.6  4900.4  410.47  4920.4  409.96
  4930.4  408.71  4980.5  408.95  4990.5  408.28  4997.7  406.42  5008.8  406.08
  5009.6  405.58  5014.3  406.08  5020.6  409.28  5048.9  408.93  5055.8  410.19
  5077.8  409.28  5133.1   409.2  5168.5  410.27  5229.7  409.48  5315.4  411.66
  5336.2  411.64  5371.6  413.35  5557.4  418.18  5651.4  422.28  5751.3  423.38
#Mann= 5 ,-1 , 0
  4107.8     .05       0  4779.4     .12       0  5008.8     .07       0
  5014.3     .12       0  5315.4     .05       0
Bank Sta=5008.8,5014.3
XS Rating Curve= 0 ,0
Exp/Cntr=0.3,0.1

Type RM Length L Ch R = 1 ,12909   ,585,585,585
BEGIN DESCRIPTION:
Massey Branch 10.0
END DESCRIPTION:
XS GIS Cut Line= 3
       2723159.5       6909132.5      2722359.48       6909382.5
      2721860.53      6910019.98
#Sta/Elev= 30
  4152.4  419.85  4187.5  418.98  4195.2  418.09  4208.5  418.58  4239.9  415.53
  4368.1  412.27  4600.7  409.72  4627.5  409.25  4638.4  408.04  4703.3  408.37
  4763.1  407.13  4803.8  407.46  4847.5  408.53  4959.1  408.19  4968.4  407.51
  4973.6  408.01  4989.8   405.9  5003.2  405.74  5004.1  405.24  5008.8  405.74
  5026.8  407.45  5049.4  408.11  5194.1  409.95  5346.3  414.04  5359.7   414.7
  5455.4  416.14  5461.7  416.86  5483.9  416.31  5525.9  418.06  5800.1  422.34
#Mann= 9 ,-1 , 0
  4152.4     .05       0  4763.1     .12       0  4803.8      .1       0
  4959.1     .12       0  5003.2     .07       0  5008.8     .12       0
  5194.1     .05       0  5346.3     .12       0  5359.7     .05       0
Bank Sta=5003.2,5008.8
XS Rating Curve= 0 ,0
Exp/Cntr=0.3,0.1

Type RM Length L Ch R = 1 ,12324   ,462,462,462
BEGIN DESCRIPTION:
Massey Branch 9.0
END DESCRIPTION:
XS GIS Cut Line= 3
      2722926.37        6908561.      2722126.33      6909011.03
      2721826.34        6909811.
#Sta/Elev= 30
  4118.1   427.5  4147.9  425.51  4198.8  425.09  4234.6  421.66  4337.3  419.83
  4359.5   417.4  4428.3   415.9  4450.1     414  4485.7  412.84  4536.8  412.56
  4552.7  411.33  4646.3  409.59  4661.1  410.28  4682.7   408.8  4922.7  405.46
  4923.6  404.96  4928.4  405.46  4957.5  405.77  5022.5  406.55  5038.7  405.53
  5081.9  406.85  5238.9  407.42  5302.6   409.9  5419.4  411.64  5558.9   415.4
    5602  417.52  5619.4   417.1  5710.2   421.3    5805  422.91  5890.4   422.3
#Mann= 5 ,-1 , 0
  4118.1     .05       0  4922.7     .07       0  4928.4     .05       0
  4957.5     .12       0  5419.4     .05       0
Bank Sta=4922.7,4928.4
XS Rating Curve= 0 ,0
Exp/Cntr=0.3,0.1

Type RM Length L Ch R = 1 ,11862   ,548,548,548
BEGIN DESCRIPTION:
Massey Branch 8.0
END DESCRIPTION:
XS GIS Cut Line= 3
      2722341.35      6907935.15      2721841.36      6908685.13
      2721541.38      6909585.08
#Sta/Elev= 30
  4104.9  419.83    4148  418.49  4162.8  418.59    4184  416.52  4220.1  414.76
    4271  414.39  4292.2  412.65  4328.3   411.5  4373.1  411.69  4400.4   409.4
  4430.2   408.4  4451.3   408.5  4472.5  406.25  4568.4  406.23  4631.5  405.54
  5009.7  405.33  5010.6  404.83  5014.5  404.83  5015.4  405.33  5254.9  406.45
  5370.8  408.61  5381.4  408.37  5455.3  411.96  5518.5  414.18  5539.5   413.8
  5581.8  415.86  5592.2  415.46  5613.4  416.97  5771.5  420.29  5954.9  423.04
#Mann= 3 ,-1 , 0
  4104.9     .03       0  5009.7     .03       0  5015.4     .03       0
Bank Sta=5009.7,5015.4
XS Rating Curve= 0 ,0
Exp/Cntr=0.3,0.1

Type RM Length L Ch R = 1 ,11314   ,564,564,564
BEGIN DESCRIPTION:
Massey Branch 7.0
END DESCRIPTION:
XS GIS Cut Line= 3
      2722256.25      6907743.41      2721456.28      6908293.39
      2721456.28      6909393.39
#Sta/Elev= 30
  4031.1  424.16  4102.2  421.94    4180  418.12  4209.8  417.61  4215.8  416.63
  4224.7  416.69  4281.5  413.52  4346.9  412.15  4395.5  410.12    4410  410.91
  4418.8  410.36  4424.9  409.05  4454.7  408.35  4468.3  407.12  4481.7   407.7
  4496.6  406.17  4532.5  405.52  5276.6  405.31  5277.6  404.81  5282.4  405.31
  5284.9  405.37  5378.9  405.97  5499.5  406.27  5629.5  409.78  5709.5  413.07
  5789.5  414.92  5919.5  415.79  5959.5  419.55  5989.5  419.09  6101.9  420.42
#Mann= 5 ,-1 , 0
  4031.1     .03       0  5276.6     .03       0  5282.4     .03       0
  5284.9     .03       0  5378.9     .03       0
Bank Sta=5276.6,5282.4
XS Rating Curve= 0 ,0
Exp/Cntr=0.3,0.1

Type RM Length L Ch R = 1 ,10750   ,915,915,915
BEGIN DESCRIPTION:
Massey Branch 6.0
END DESCRIPTION:
XS GIS Cut Line= 3
       2721636.5      6907074.66      2720972.42       6908050.5
      2720937.71      6909314.25
#Sta/Elev= 30
  3809.5  423.01  3836.2  422.07  3979.9   421.2  4030.7  419.71  4059.1  419.89
  4195.4  418.24    4312  415.07    4375  414.16  4404.8  412.29  4518.7  407.21
  4533.6  405.55  5427.5  405.45  5428.5  404.95  5433.5  405.45  5490.6  405.82
  5520.6  407.45  5540.6  407.07  5610.6  409.68  5630.6  409.58  5690.6   411.4
  5710.6  412.59  5730.7   412.3  5740.7  413.46  5760.7  413.16  5780.7  414.04
  5810.7  414.23  5880.7  417.17  6060.8  418.68  6150.8  420.56  6254.1  420.98
#Mann= 3 ,-1 , 0
  3809.5     .03       0  5427.5     .03       0  5433.5     .03       0
Bank Sta=5427.5,5433.5
XS Rating Curve= 0 ,0
Exp/Cntr=0.3,0.1