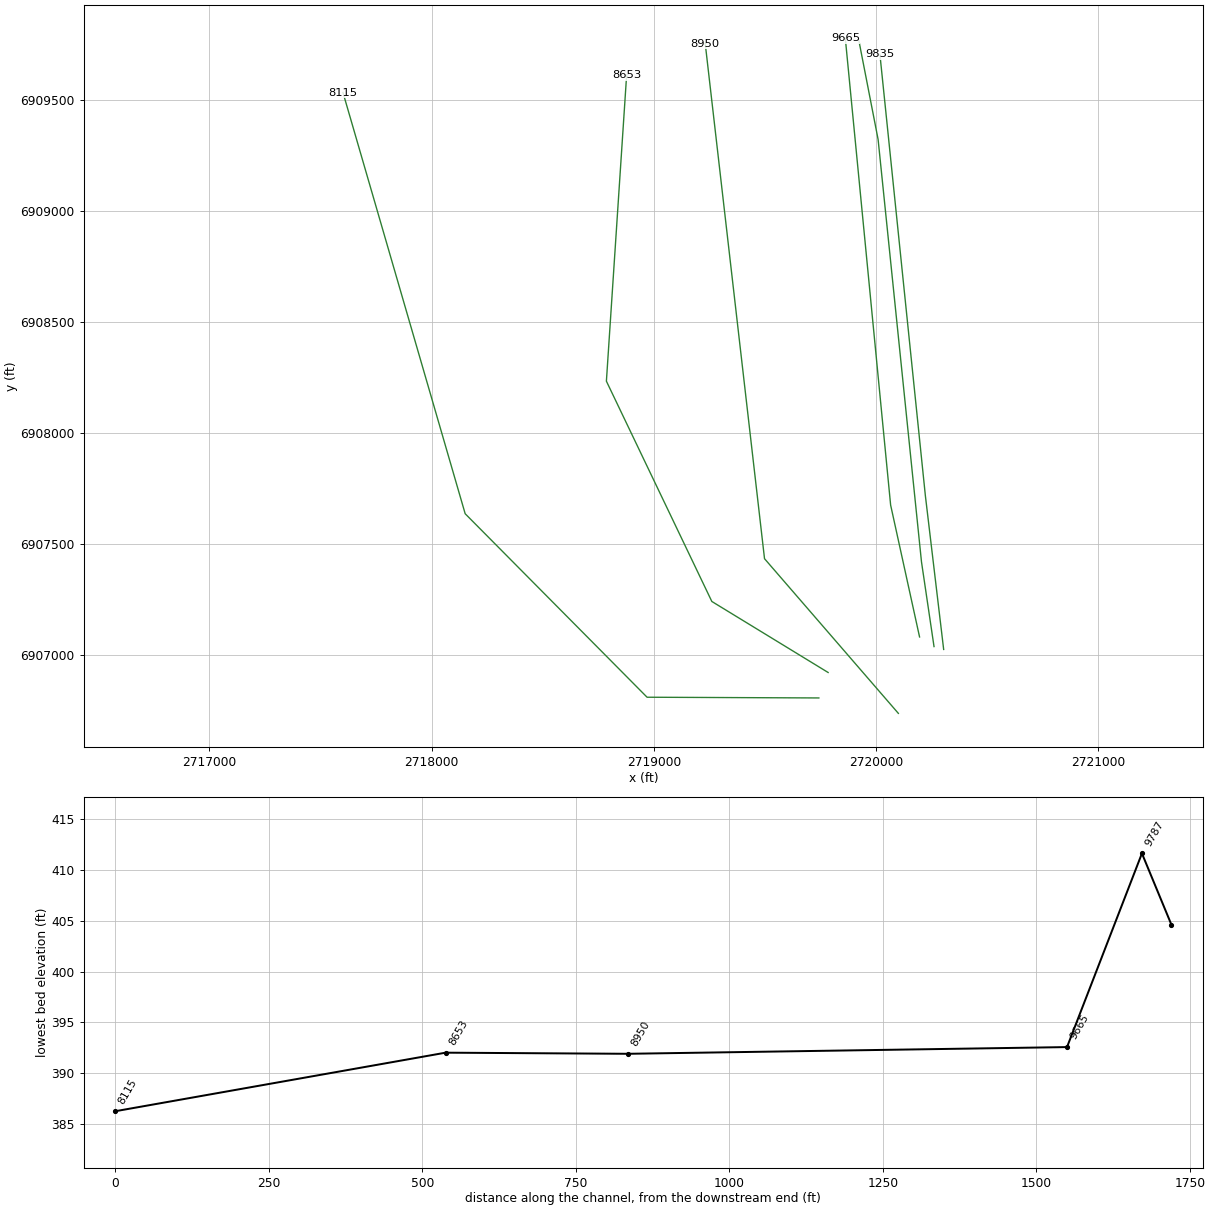
HEC-RAS study Massey Branch.prj: Massey Branch Base Level Engineering

--- Massey Branch.g01 (geometry) --- (continued)

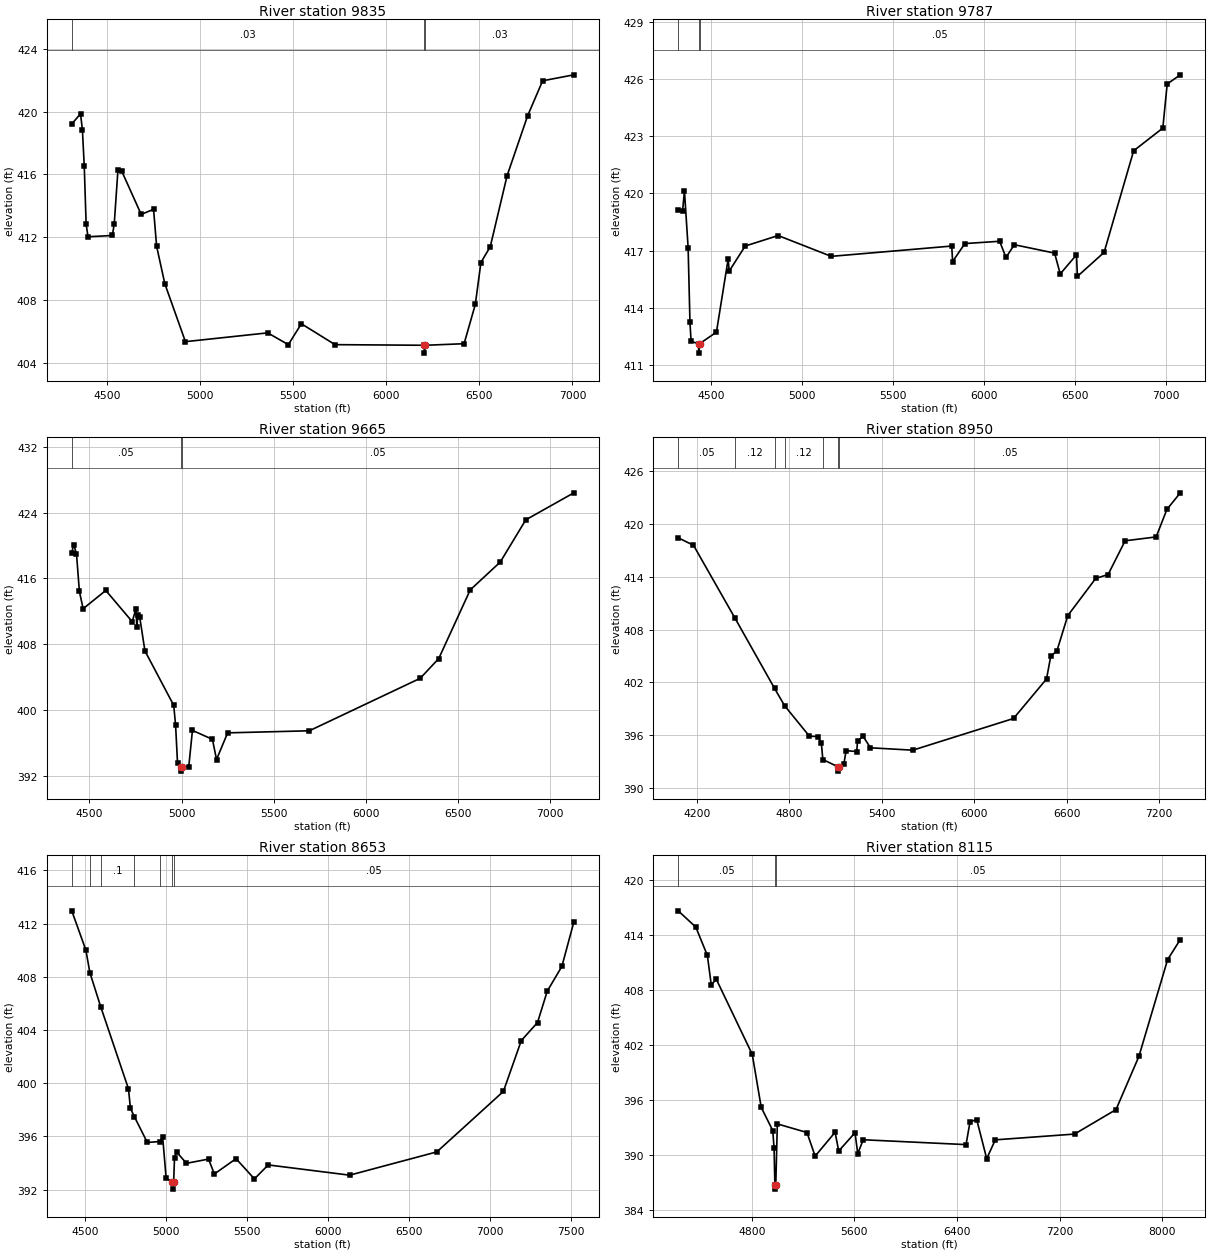
Type RM Length L Ch R = 1 ,9835    ,48,48,48
BEGIN DESCRIPTION:
Mapping XS 958e6425
END DESCRIPTION:
XS GIS Cut Line= 3
       2720304.9      6907024.34      2720222.44      6907718.76
      2720017.95      6909707.87
#Sta/Elev= 30
  4308.8  419.21  4355.8  419.86  4365.9  418.85  4375.9  416.53    4386  412.84
  4396.1  412.03    4527  412.11  4537.1  412.85  4557.2  416.31  4577.3  416.21
  4682.1  413.45  4748.5  413.78  4764.8  411.43    4809  409.04  4919.7  405.35
  5362.2  405.91  5472.8  405.16  5543.1  406.49  5724.1  405.16  6203.1  405.12
  6204.2  404.62  6210.1  405.12  6417.7  405.22    6478  407.72  6508.2  410.39
  6558.5   411.4  6648.9  415.92  6759.5  419.74  6839.9  421.96  7007.7  422.34
#Mann= 3 ,-1 , 0
  4308.8     .03       0  6203.1     .03       0  6210.1     .03       0
Bank Sta=6203.1,6210.1
XS Rating Curve= 0 ,0
Exp/Cntr=0.3,0.1

Type RM Length L Ch R = 1 ,9787    ,122,122,122
BEGIN DESCRIPTION:
Mapping XS 93961c07
END DESCRIPTION:
XS GIS Cut Line= 4
       2720261.5      6907037.31      2720205.07      6907419.28
      2720009.76      6909324.66      2719922.95      6909771.73
#Sta/Elev= 30
  4320.3  419.13  4344.2  419.07  4354.4  420.14  4374.6  417.15  4384.7  413.25
  4390.9  412.24  4431.7  412.13  4432.8  411.63  4438.7  412.13  4530.1  412.73
  4594.7  416.58  4599.7  415.92  4687.9  417.24    4869  417.79  5160.5   416.7
    5822  417.24    5827  416.43  5894.3  417.37  6085.3  417.49  6119.9  416.64
  6165.7  417.31  6386.9  416.87  6417.8  415.78    6507  416.78  6512.1  415.65
  6658.8  416.91  6820.9  422.23  6981.1  423.42  7005.1  425.73  7077.2  426.21
#Mann= 3 ,-1 , 0
  4320.3     .05       0  4431.7     .04       0  4438.7     .05       0
Bank Sta=4431.7,4438.7
XS Rating Curve= 0 ,0
Exp/Cntr=0.3,0.1

Type RM Length L Ch R = 1 ,9665    ,715,715,715
BEGIN DESCRIPTION:
Mapping XS 02139a1c
END DESCRIPTION:
XS GIS Cut Line= 3
       2720196.4       6907080.7      2720066.19      6907675.35
       2719862.2      6909780.35
#Sta/Elev= 30
    4404  419.14  4414.5  420.09  4429.6  418.99  4445.3  414.41  4465.7  412.31
  4588.6  414.53  4731.9  410.74  4751.9  412.28    4757  410.13  4762.6  411.56
  4772.8  411.26  4800.8  407.19  4957.1  400.57  4967.3  398.13  4977.6  393.59
  4994.5  393.08  4995.6  392.58  5001.5  393.08  5038.5  393.09  5058.6  397.53
  5167.1  396.44  5189.2  393.99  5249.5  397.23  5692.6  397.48  6294.4  403.86
  6394.8  406.26  6565.6   414.6  6728.4  417.98    6867  423.11  7127.6  426.39
#Mann= 3 ,-1 , 0
    4404     .05       0  4994.5     .04       0  5001.5     .05       0
Bank Sta=4994.5,5001.5
XS Rating Curve= 0 ,0
Exp/Cntr=0.3,0.1

Type RM Length L Ch R = 1 ,8950    ,297,297,297
BEGIN DESCRIPTION:
Massey Branch 2.0
END DESCRIPTION:
XS GIS Cut Line= 3
        2720101.      6906736.01      2719498.54      6907433.56
      2719231.58      6909756.97
#Sta/Elev= 30
  4078.3  418.43  4177.4  417.58  4447.8  409.27  4704.1  401.31  4768.8  399.36
  4929.5   395.9  4985.5  395.84  5007.5  395.14  5017.3  393.24  5114.7  392.42
  5115.8  391.92  5121.7  392.42  5153.6  392.71  5168.5  394.25  5237.6  394.14
  5242.7  395.38  5279.3  395.86  5326.7  394.57  5601.4   394.3  6255.6   397.9
  6469.9  402.39  6497.2  404.97  6537.5  405.59  6607.9  409.59  6789.1  413.81
  6869.7  414.26  6980.4  418.09  7181.7  418.53  7251.7  421.66  7338.7  423.54
#Mann= 7 ,-1 , 0
  4078.3     .05       0  4447.8     .12       0  4704.1      .1       0
  4768.8     .12       0  5017.3     .05       0  5114.7     .07       0
  5121.7     .05       0
Bank Sta=5114.7,5121.7
XS Rating Curve= 0 ,0
Exp/Cntr=0.3,0.1

Type RM Length L Ch R = 1 ,8653    ,538,538,538
BEGIN DESCRIPTION:
Mapping XS 1184c383
END DESCRIPTION:
XS GIS Cut Line= 4
      2719784.79      6906920.41      2719261.34      6907240.74
      2718786.76      6908234.15      2718877.87      6909614.71
#Sta/Elev= 30
  4418.6  412.96  4505.5  410.01  4530.2  408.32  4596.8  405.76  4768.6  399.57
  4780.6   398.1  4805.3  397.47  4884.7  395.54    4962  395.61  4979.5  395.94
  5000.8  392.87  5040.1  392.53  5041.2  392.03  5047.2  392.53  5052.7   394.4
  5065.8  394.82  5126.3  393.97  5262.4  394.29  5298.6  393.17  5432.3  394.32
  5545.7   392.8  5630.9  393.85  6133.2  393.08  6671.3  394.83  7082.1  399.38
  7192.4   403.2  7292.6  404.56  7352.7  406.92  7442.9  408.78  7516.8  412.12
#Mann= 7 ,-1 , 0
  4418.6     .05       0  4530.2     .12       0  4596.8      .1       0
  4805.3     .05       0    4962     .12       0  5040.1     .07       0
  5047.2     .05       0
Bank Sta=5040.1,5047.2
XS Rating Curve= 0 ,0
Exp/Cntr=0.3,0.1

Type RM Length L Ch R = 1 ,8115    ,0,0,0
BEGIN DESCRIPTION:
Massey Branch 1.0
END DESCRIPTION:
XS GIS Cut Line= 4
      2719743.15      6906805.59      2718969.86      6906808.83
      2718151.11      6907636.32        2717601.      6909535.99
#Sta/Elev= 30
  4226.7  416.65  4363.9  414.87  4453.9  411.78  4483.9  408.59  4523.9  409.17
  4803.9  400.98  4873.9  395.19  4963.9  392.66  4973.9  390.75  4980.3  386.77
  4981.4  386.27  4987.4  386.77  4999.4  393.39  5230.5  392.45  5294.2  389.87
  5449.8  392.48  5478.1  390.43  5605.3  392.43  5626.5  390.14  5668.9  391.66
  6470.9  391.13  6502.1  393.62  6554.2  393.86    6632   389.6  6699.2  391.65
  7317.1  392.28  7640.3  394.95  7818.7  400.75  8042.9  411.33  8141.8  413.52
#Mann= 3 ,-1 , 0
  4226.7     .05       0  4980.3     .04       0  4987.4     .05       0
Bank Sta=4980.3,4987.4
XS Rating Curve= 0 ,0
Exp/Cntr=0.3,0.1

Chan Stop Cuts=-1
Use User Specified Reach Order=0
Composite Channel Slope=5