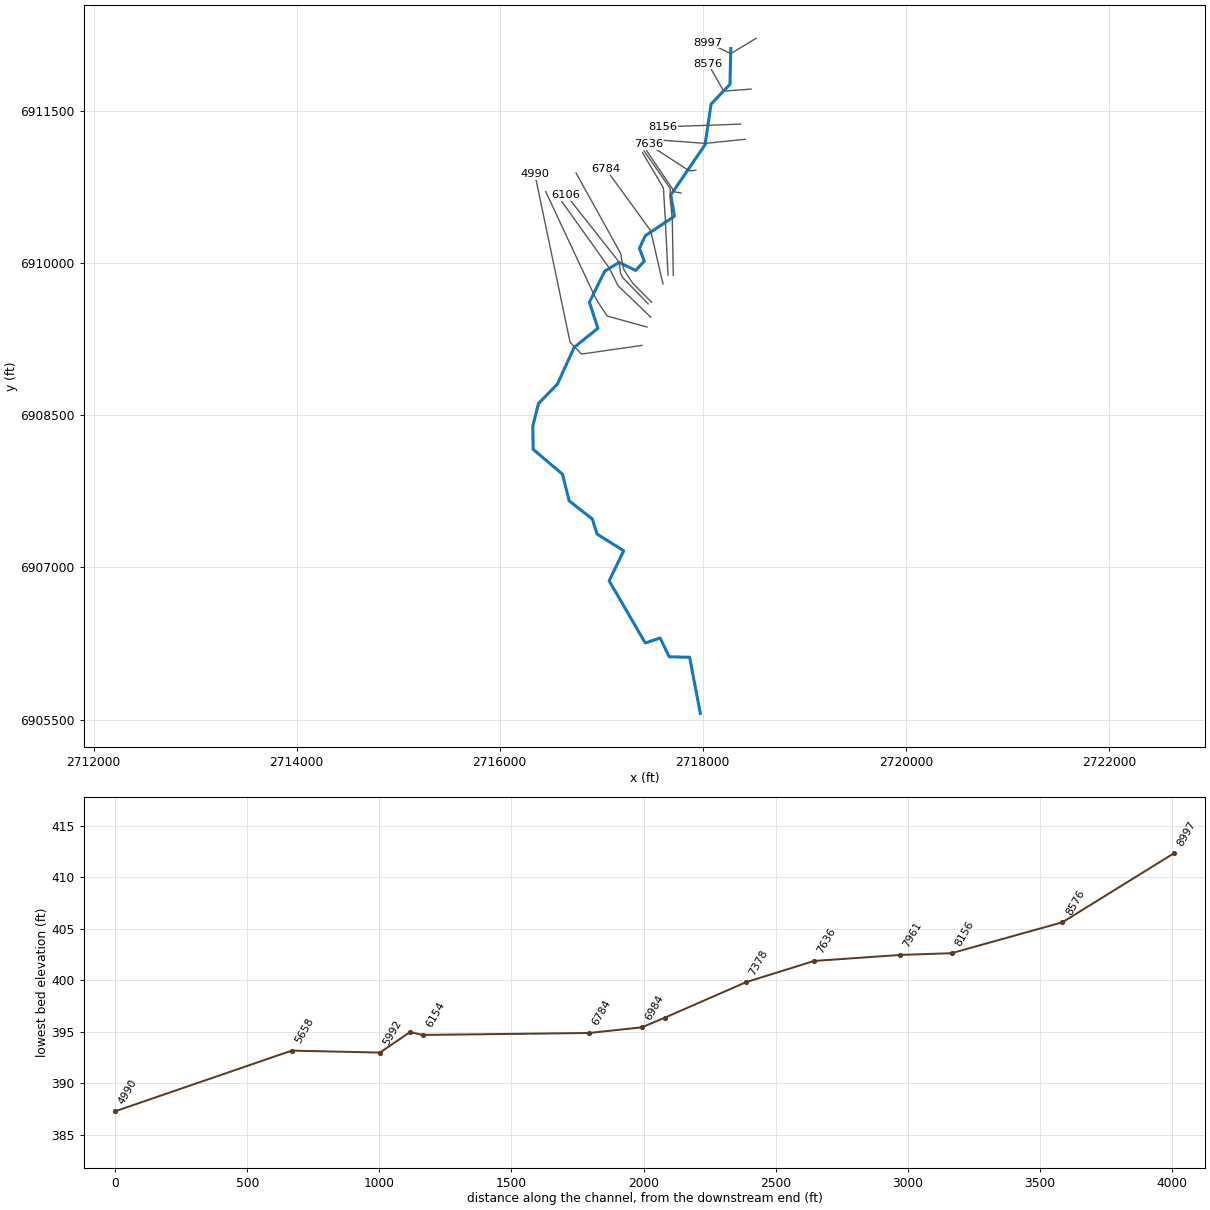
--- Massey T1.prj (project) ---

Proj Title=Massey T1 Base Level Engineering
Current Plan=p01
Default Exp/Contr=0.3,0.1
English Units
Geom File=g01
Flow File=f01
Plan File=p01
BEGIN DESCRIPTION:
Massey T1
END DESCRIPTION:

--- Massey T1.p01 (plan) ---

Plan Title=Multiple Run
Short Identifier=Multiple
Geom File=g01
Flow File=f01
Subcritical Flow
K Sum by GR= 0
Std Step Tol= 0.01
Critical Tol= 0.01
Num of Std Step Trials= 20
Max Error Tol= 0.3
Flow Tol Ratio= 0.001
Split Flow NTrial= 30
Split Flow Tol= 0.02
Split Flow Ratio= 0.02
Log Output Level= 0
Friction Slope Method= 1
Unsteady Friction Slope Method= 2
Unsteady Bridges Friction Slope Method= 1
Parabolic Critical Depth
Global Vel Dist=  1 , 1 , 1
Global Log Level= 0
CheckData=True
Encroach Param= -1, 0, 0, 0
BEGIN DESCRIPTION:
Multiple Run
END DESCRIPTION:

--- Massey T1.f01 (steady flow) ---

Flow Title=Multiple
Number of Profiles=7
Profile Names=10-year,25-year,50-year,1pct_min,100-year,1pct_plu,500-year
River Rch & RM= Massey T1,Reach-1,8997
     357     459     538     313     625    1247     841
River Rch & RM= Massey T1,Reach-1,5658
     728     980    1185     710    1417    2827    2024
Boundary for River Rch & Prof#=Massey T1,Reach-1,1
Up Type=0
Dn Type=3
Dn Slope=0.005
Boundary for River Rch & Prof#=Massey T1,Reach-1,2
Up Type=0
Dn Type=3
Dn Slope=0.005
Boundary for River Rch & Prof#=Massey T1,Reach-1,3
Up Type=0
Dn Type=3
Dn Slope=0.005
Boundary for River Rch & Prof#=Massey T1,Reach-1,4
Up Type=0
Dn Type=3
Dn Slope=0.005
Boundary for River Rch & Prof#=Massey T1,Reach-1,5
Up Type=0
Dn Type=3
Dn Slope=0.005
Boundary for River Rch & Prof#=Massey T1,Reach-1,6
Up Type=0
Dn Type=3
Dn Slope=0.005
Boundary for River Rch & Prof#=Massey T1,Reach-1,7
Up Type=0
Dn Type=3
Dn Slope=0.005

--- Massey T1.g01 (geometry) ---

Geom Title=Existing Conditions

River Reach=Massey T1,Reach-1
Reach XY= 30
      2718276.00      6912111.00      2718268.01      6911757.66
      2718081.83      6911563.30      2718022.38      6911162.50
      2717685.15      6910667.73      2717720.55      6910458.01
      2717434.14      6910267.06      2717375.71      6910140.82
      2717424.38      6910017.02      2717339.41      6909924.50
      2717176.00      6910003.50      2717034.02      6909917.34
      2716883.33      6909611.10      2716966.87      6909354.26
      2716733.75      6909167.45      2716567.86      6908804.94
      2716381.47      6908613.45      2716325.72      6908390.82
      2716329.04      6908162.42      2716618.14      6907917.17
      2716683.86      6907654.83      2716912.74      6907474.65
      2716958.79      6907327.27      2717220.94      6907163.29
      2717077.97      6906866.90      2717433.86      6906254.17
      2717579.62      6906303.51      2717669.50      6906118.63
      2717870.55      6906114.01      2717976.00      6905561.00

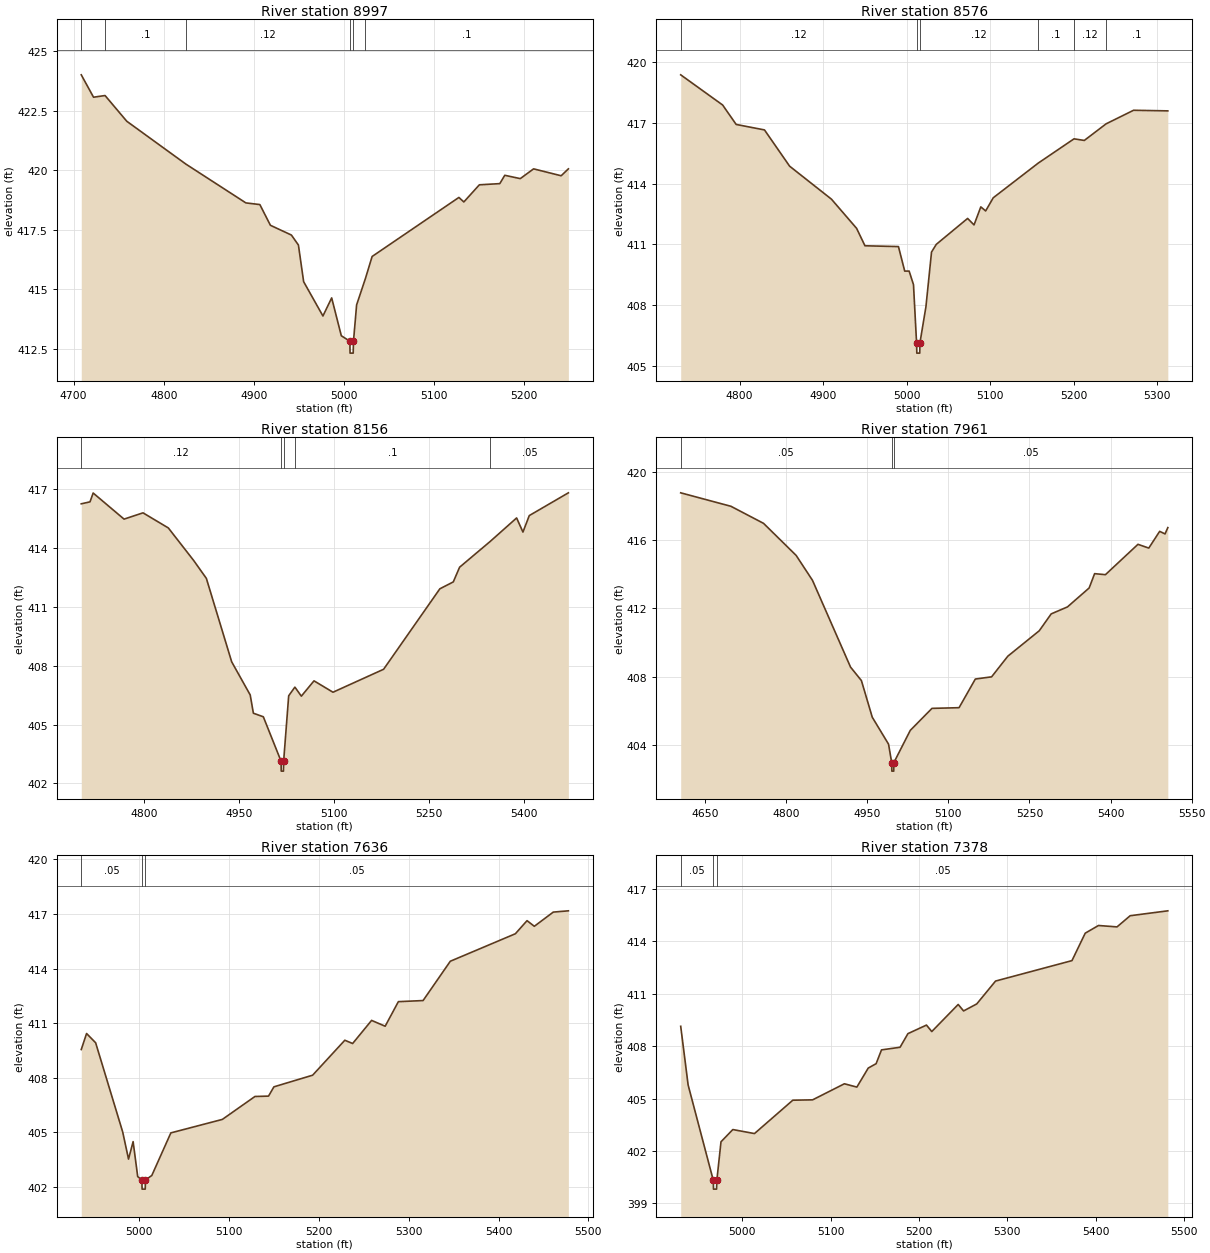
Type RM Length L Ch R = 1,8997,421,421,421
BEGIN DESCRIPTION:
Massey T1 13.0
END DESCRIPTION:
XS GIS Cut Line= 3
      2718525.98      6912210.99      2718276.00      6912061.00
      2718051.19      6912168.25
#Sta/Elev= 30
  4708.5  424.00  4722.1  423.06  4734.9  423.13  4759.0  422.05  4824.6  420.25
  4891.2  418.62  4906.7  418.55  4918.4  417.68  4941.7  417.27  4949.5  416.85
  4955.3  415.31  4976.7  413.87  4986.4  414.63  4997.1  413.04  5006.6  412.81
  5006.8  412.31  5010.3  412.31  5010.6  412.81  5014.1  414.34  5023.9  415.45
  5031.3  416.37  5127.6  418.85  5133.1  418.66  5150.3  419.38  5173.0  419.43
  5178.5  419.78  5195.7  419.64  5210.5  420.05  5241.1  419.76  5249.1  420.05
#Mann=6,-1,0
  4708.5    0.12       0  4734.9     0.1       0  4824.6    0.12       0
  5006.6    0.07       0  5010.6    0.12       0  5023.9     0.1       0
Bank Sta=5006.6,5010.6
Exp/Cntr=0.3,0.1

Type RM Length L Ch R = 1,8576,420,420,420
BEGIN DESCRIPTION:
Massey T1 12.0
END DESCRIPTION:
XS GIS Cut Line= 3
      2718476.02      6911711.00      2718206.16      6911691.00
      2718051.22      6911962.50
#Sta/Elev= 30
  4729.4  419.37  4779.6  417.88  4795.8  416.92  4829.7  416.65  4859.8  414.86
  4909.9  413.23  4940.0  411.79  4950.0  410.93  4990.1  410.89  4997.6  409.68
  5002.9  409.68  5008.1  409.01  5011.8  406.13  5012.1  405.63  5015.6  405.63
  5015.8  406.13  5023.0  407.92  5029.7  410.62  5035.4  411.00  5072.9  412.28
  5080.6  411.96  5088.7  412.85  5094.5  412.65  5103.6  413.30  5157.4  415.01
  5200.3  416.21  5212.6  416.13  5238.7  416.95  5271.6  417.62  5312.6  417.59
#Mann=6,-1,0
  4729.4    0.12       0  5011.8    0.07       0  5015.8    0.12       0
  5157.4     0.1       0  5200.3    0.12       0  5238.7     0.1       0
Bank Sta=5011.8,5015.8
Exp/Cntr=0.3,0.1

Type RM Length L Ch R = 1,8156,195,195,195
BEGIN DESCRIPTION:
Massey T1 11.0
END DESCRIPTION:
XS GIS Cut Line= 3
      2718373.52      6911366.59      2718074.15      6911354.89
      2717604.21      6911339.46
#Sta/Elev= 30
  4700.4  416.25  4714.2  416.35  4719.2  416.80  4768.0  415.47  4798.0  415.79
  4838.0  415.02  4878.1  413.36  4898.1  412.45  4938.1  408.20  4967.4  406.51
  4972.4  405.58  4988.1  405.40  5016.2  403.13  5016.4  402.63  5019.9  402.63
  5020.2  403.13  5028.2  406.47  5038.0  406.91  5048.2  406.45  5068.2  407.23
  5098.2  406.65  5178.2  407.82  5267.1  411.92  5288.3  412.27  5298.3  413.02
  5346.9  414.34  5388.4  415.53  5398.4  414.81  5408.4  415.65  5470.2  416.81
#Mann=5,-1,0
  4700.4    0.12       0  5016.2    0.07       0  5020.2    0.12       0
  5038.0     0.1       0  5346.9    0.05       0
Bank Sta=5016.2,5020.2
Exp/Cntr=0.3,0.1

Type RM Length L Ch R = 1,7961,325,325,325
BEGIN DESCRIPTION:
Massey T1 10.0
END DESCRIPTION:
XS GIS Cut Line= 3
      2718418.40      6911216.63      2718025.48      6911176.22
      2717520.92      6911213.15
#Sta/Elev= 30
  4605.0  418.78  4697.9  417.99  4758.2  416.99  4818.5  415.11  4848.7  413.65
  4919.1  408.56  4939.2  407.77  4959.3  405.62  4989.4  404.04  4995.2  402.96
  4995.5  402.46  4999.0  402.46  4999.2  402.96  5029.6  404.85  5069.7  406.14
  5119.8  406.18  5149.9  407.86  5180.0  407.99  5210.0  409.20  5268.1  410.69
  5290.2  411.68  5320.3  412.09  5360.4  413.20  5370.5  414.04  5390.5  413.98
  5450.7  415.76  5470.7  415.54  5490.8  416.52  5500.8  416.37  5505.9  416.74
#Mann=3,-1,0
  4605.0    0.05       0  4995.2    0.04       0  4999.2    0.05       0
Bank Sta=4995.2,4999.2
Exp/Cntr=0.3,0.1

Type RM Length L Ch R = 1,7636,258,258,258
BEGIN DESCRIPTION:
Massey T1 9.0
END DESCRIPTION:
XS GIS Cut Line= 3
      2717931.91      6910911.51      2717867.84      6910904.95
      2717467.41      6911165.44
#Sta/Elev= 30
  4935.6  409.55  4941.5  410.43  4951.6  409.92  4981.7  405.02  4988.2  403.53
  4993.3  404.49  4998.4  402.57  5003.0  402.38  5003.3  401.88  5006.8  401.88
  5007.0  402.38  5014.1  402.63  5035.3  404.97  5092.6  405.71  5128.9  406.97
  5144.0  406.99  5150.0  407.50  5193.1  408.14  5228.9  410.06  5237.6  409.88
  5258.7  411.15  5273.8  410.83  5288.5  412.18  5316.0  412.24  5346.3  414.40
  5418.7  415.91  5431.7  416.63  5439.8  416.32  5460.9  417.10  5477.7  417.17
#Mann=3,-1,0
  4935.6    0.05       0  5003.0    0.04       0  5007.0    0.05       0
Bank Sta=5003,5007
Exp/Cntr=0.3,0.1

Type RM Length L Ch R = 1,7378,307,307,307
BEGIN DESCRIPTION:
Mapping XS f68c79db
END DESCRIPTION:
XS GIS Cut Line= 3
      2717784.30      6910687.98      2717721.36      6910698.83
      2717447.93      6911102.47
#Sta/Elev= 30
  4930.4  409.14  4938.8  405.78  4967.3  400.32  4967.5  399.82  4971.0  399.82
  4971.3  400.32  4976.0  402.53  4989.4  403.23  5013.9  403.00  5057.3  404.91
  5079.7  404.93  5115.7  405.85  5129.8  405.66  5142.7  406.75  5151.6  407.00
  5157.7  407.79  5178.7  407.94  5187.6  408.72  5208.6  409.21  5214.6  408.84
  5244.5  410.39  5250.6  410.02  5265.5  410.42  5286.8  411.73  5373.3  412.90
  5388.3  414.47  5403.3  414.91  5424.3  414.83  5439.2  415.47  5481.8  415.75
#Mann=3,-1,0
  4930.4    0.05       0  4967.3    0.04       0  4971.3    0.05       0
Bank Sta=4967.3,4971.3
Exp/Cntr=0.3,0.1

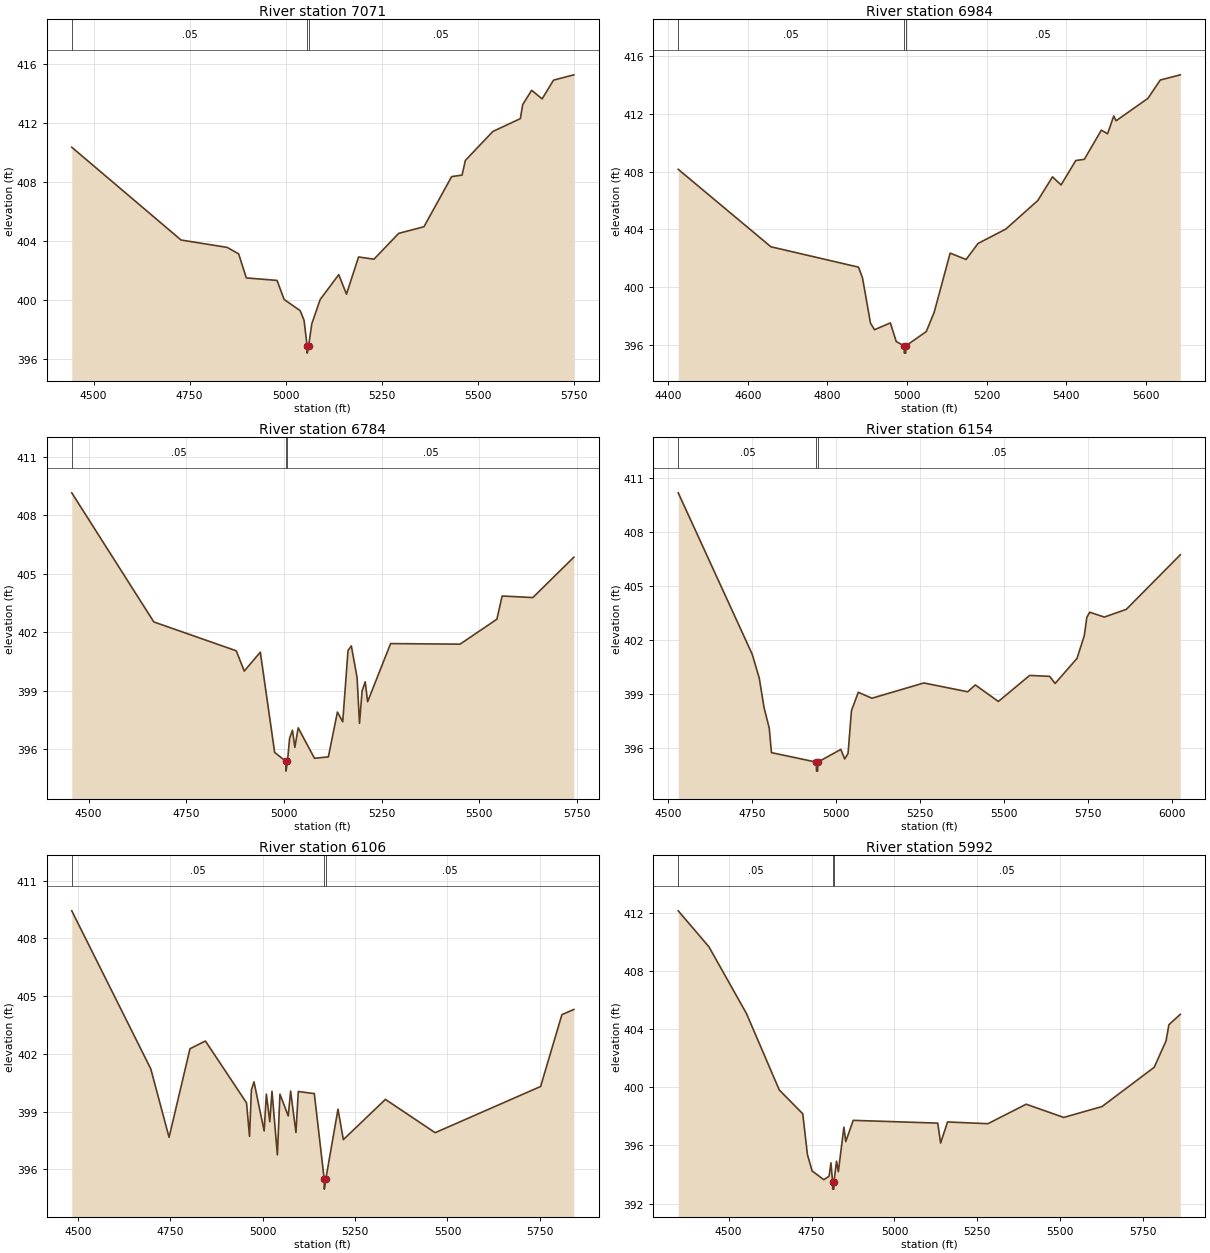
Type RM Length L Ch R = 1,7071,87,87,87
BEGIN DESCRIPTION:
Mapping XS 7fd3ef08
END DESCRIPTION:
XS GIS Cut Line= 5
      2717709.70      6909876.48      2717699.74      6910432.77
      2717676.97      6910658.56      2717681.14      6910729.39
      2717421.95      6911101.19
#Sta/Elev= 30
  4443.2  410.34  4727.8  404.05  4847.8  403.55  4877.8  403.11  4897.8  401.48
  4977.8  401.31  4996.2  400.02  5038.0  399.26  5048.1  398.61  5056.1  396.88
  5056.4  396.38  5060.1  396.88  5068.2  398.36  5090.0  400.01  5138.5  401.70
  5158.6  400.38  5190.1  402.90  5230.2  402.75  5294.6  404.50  5360.4  404.95
  5432.5  408.35  5459.5  408.45  5468.3  409.45  5539.8  411.41  5611.4  412.28
  5617.5  413.23  5640.8  414.20  5668.1  413.62  5697.8  414.89  5750.7  415.25
#Mann=3,-1,0
  4443.2    0.05       0  5056.1    0.05       0  5060.1    0.05       0
Bank Sta=5056.1,5060.1
Exp/Cntr=0.3,0.1

Type RM Length L Ch R = 1,6984,200,200,200
BEGIN DESCRIPTION:
Mapping XS f01bd1fe
END DESCRIPTION:
XS GIS Cut Line= 4
      2717657.61      6909878.29      2717629.84      6910449.44
      2717612.48      6910737.64      2717407.62      6911083.12
#Sta/Elev= 30
  4424.9  408.16  4657.9  402.80  4878.1  401.39  4888.2  400.64  4908.2  397.52
  4918.2  397.06  4958.2  397.53  4973.0  396.24  4993.0  395.94  4993.3  395.44
  4996.8  395.44  4997.0  395.94  5048.4  396.93  5068.4  398.27  5108.5  402.36
  5148.6  401.92  5178.6  403.03  5248.7  404.03  5328.8  406.00  5365.8  407.64
  5387.3  407.08  5424.3  408.77  5445.7  408.85  5488.6  410.87  5504.2  410.62
  5519.8  411.85  5525.7  411.52  5605.6  413.07  5636.8  414.34  5687.1  414.70
#Mann=3,-1,0
  4424.9    0.05       0  4993.0    0.05       0  4997.0    0.05       0
Bank Sta=4993,4997
Exp/Cntr=0.3,0.1

Type RM Length L Ch R = 1,6784,630,630,630
BEGIN DESCRIPTION:
Mapping XS 57497952
END DESCRIPTION:
XS GIS Cut Line= 3
      2717608.22      6909790.95      2717486.70      6910316.11
      2717048.31      6910919.43
#Sta/Elev= 30
  4456.8  409.16  4666.8  402.54  4877.7  401.06  4898.2  400.02  4939.3  400.99
  4976.0  395.85  5004.8  395.39  5005.0  394.89  5008.8  395.39  5014.2  396.57
  5021.5  396.99  5027.7  396.11  5036.2  397.11  5077.9  395.55  5113.4  395.62
  5136.6  397.92  5150.2  397.42  5163.7  401.07  5172.2  401.31  5186.9  399.69
  5193.1  397.34  5199.7  399.00  5207.7  399.47  5213.9  398.45  5272.7  401.43
  5450.4  401.40  5544.7  402.68  5558.1  403.87  5636.7  403.79  5741.6  405.86
#Mann=3,-1,0
  4456.8    0.05       0  5004.8    0.04       0  5008.8    0.05       0
Bank Sta=5004.8,5008.8
Exp/Cntr=0.3,0.1

Type RM Length L Ch R = 1,6154,48,48,48
BEGIN DESCRIPTION:
Mapping XS dfb55ae4
END DESCRIPTION:
XS GIS Cut Line= 6
      2717496.66      6909610.83      2717306.57      6909803.52
      2717223.24      6909931.13      2717207.62      6909993.63
      2717191.99      6910089.98      2716751.87      6910884.28
#Sta/Elev= 30
  4530.5  410.20  4750.3  401.22  4771.5  399.88  4785.6  398.25  4801.2  397.09
  4807.8  395.73  4941.4  395.20  4941.7  394.70  4945.2  394.70  4945.4  395.20
  5014.1  395.91  5025.5  395.38  5035.6  395.69  5045.7  398.07  5066.0  399.09
  5106.5  398.76  5260.9  399.61  5391.4  399.12  5414.0  399.50  5482.6  398.58
  5575.7  400.03  5635.2  399.98  5651.3  399.58  5716.5  400.98  5738.2  402.25
  5745.6  403.26  5754.3  403.55  5797.8  403.28  5863.0  403.71  6023.7  406.75
#Mann=3,-1,0
  4530.5    0.05       0  4941.4    0.05       0  4945.4    0.05       0
Bank Sta=4941.4,4945.4
Exp/Cntr=0.3,0.1

Type RM Length L Ch R = 1,6106,114,114,114
BEGIN DESCRIPTION:
Mapping XS 4f26f638
END DESCRIPTION:
XS GIS Cut Line= 6
      2717462.10      6909594.78      2717210.39      6909855.17
      2717190.86      6909896.40      2717177.84      6909996.23
      2717151.80      6910037.46      2716655.17      6910666.39
#Sta/Elev= 30
  4483.4  409.43  4697.3  401.22  4746.7  397.67  4803.3  402.27  4845.1  402.67
  4956.3  399.46  4964.4  397.72  4969.5  400.14  4976.5  400.55  5004.0  398.00
  5010.0  399.91  5019.3  398.48  5025.2  400.06  5039.8  396.76  5046.7  399.91
  5069.2  398.78  5075.6  400.07  5090.0  397.92  5096.4  400.05  5139.7  399.94
  5166.6  395.48  5166.8  394.98  5170.6  395.48  5203.8  399.13  5218.3  397.55
  5332.1  399.64  5466.7  397.91  5752.1  400.31  5809.7  404.04  5842.0  404.31
#Mann=3,-1,0
  4483.4    0.05       0  5166.6   0.035       0  5170.6    0.05       0
Bank Sta=5166.6,5170.6
Exp/Cntr=0.3,0.1

Type RM Length L Ch R = 1,5992,334,334,334
BEGIN DESCRIPTION:
Mapping XS 67e23e2c
END DESCRIPTION:
XS GIS Cut Line= 4
      2717489.04      6909463.24      2717166.12      6909773.14
      2717077.58      6909950.22      2716573.30      6910657.26
#Sta/Elev= 30
  4348.0  412.13  4440.5  409.66  4553.7  405.07  4652.7  399.81  4723.5  398.17
  4737.6  395.37  4751.8  394.24  4787.0  393.64  4802.9  393.88  4808.5  394.80
  4813.5  393.49  4813.8  392.99  4817.3  392.99  4817.5  393.49  4825.3  394.91
  4830.8  394.19  4847.6  397.25  4853.2  396.26  4875.6  397.72  5130.6  397.53
  5139.2  396.16  5160.1  397.61  5281.8  397.49  5397.3  398.83  5510.4  397.92
  5626.0  398.67  5783.3  401.37  5818.9  403.18  5827.6  404.30  5862.0  405.01
#Mann=3,-1,0
  4348.0    0.05       0  4813.5   0.035       0  4817.5    0.05       0
Bank Sta=4813.5,4817.5
Exp/Cntr=0.3,0.1

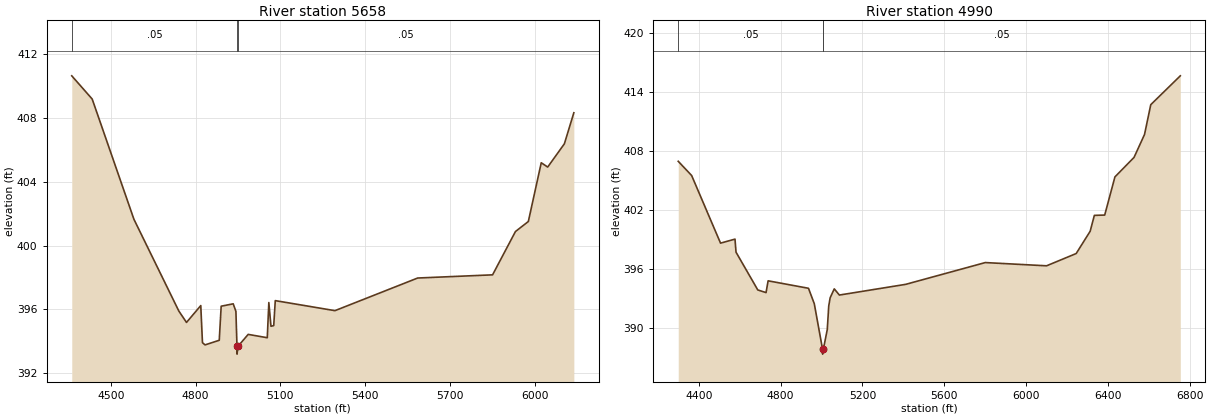
Type RM Length L Ch R = 1,5658,668,668,668
BEGIN DESCRIPTION:
Mapping XS a6d7ee08
END DESCRIPTION:
XS GIS Cut Line= 5
      2717450.93      6909366.78      2717058.49      6909475.45
      2716970.39      6909608.49      2716930.61      6909680.31
      2716452.57      6910701.38
#Sta/Elev= 30
  4362.1  410.66  4434.4  409.20  4582.0  401.65  4740.8  395.89  4768.0  395.17
  4818.5  396.23  4824.5  393.90  4833.6  393.76  4883.9  394.05  4890.7  396.19
  4933.2  396.34  4942.8  395.87  4946.6  393.68  4946.8  393.18  4950.6  393.68
  4986.3  394.42  5053.8  394.21  5059.3  396.42  5066.9  394.93  5076.6  394.97
  5082.1  396.54  5293.2  395.91  5585.9  397.96  5850.9  398.16  5931.8  400.88
  5977.4  401.51  6023.1  405.20  6045.9  404.93  6104.9  406.39  6138.4  408.34
#Mann=3,-1,0
  4362.1    0.05       0  4946.6    0.04       0  4950.6    0.05       0
Bank Sta=4946.6,4950.6
Exp/Cntr=0.3,0.1

Type RM Length L Ch R = 1,4990,0,0,0
BEGIN DESCRIPTION:
Massey T1 5.0
END DESCRIPTION:
XS GIS Cut Line= 4
      2717400.98      6909186.00      2716805.49      6909100.73
      2716692.84      6909217.62      2716346.19      6910872.30
#Sta/Elev= 30
  4299.7  406.95  4365.3  405.50  4506.5  398.61  4577.2  399.02  4582.2  397.69
  4688.6  393.84  4729.0  393.57  4739.1  394.77  4936.5  394.01  4964.8  392.44
  5005.2  387.80  5005.5  387.30  5009.2  387.80  5028.3  389.80  5035.5  392.21
  5042.4  393.04  5062.5  393.95  5087.5  393.32  5411.6  394.41  5800.8  396.63
  6100.4  396.30  6245.1  397.55  6313.5  399.82  6334.0  401.44  6384.6  401.47
  6434.6  405.36  6528.1  407.35  6579.2  409.68  6609.8  412.72  6754.2  415.66
#Mann=3,-1,0
  4299.7    0.05       0  5005.2    0.04       0  5009.2    0.05       0
Bank Sta=5005.2,5009.2
Exp/Cntr=0.3,0.1

Chan Stop Cuts=-1