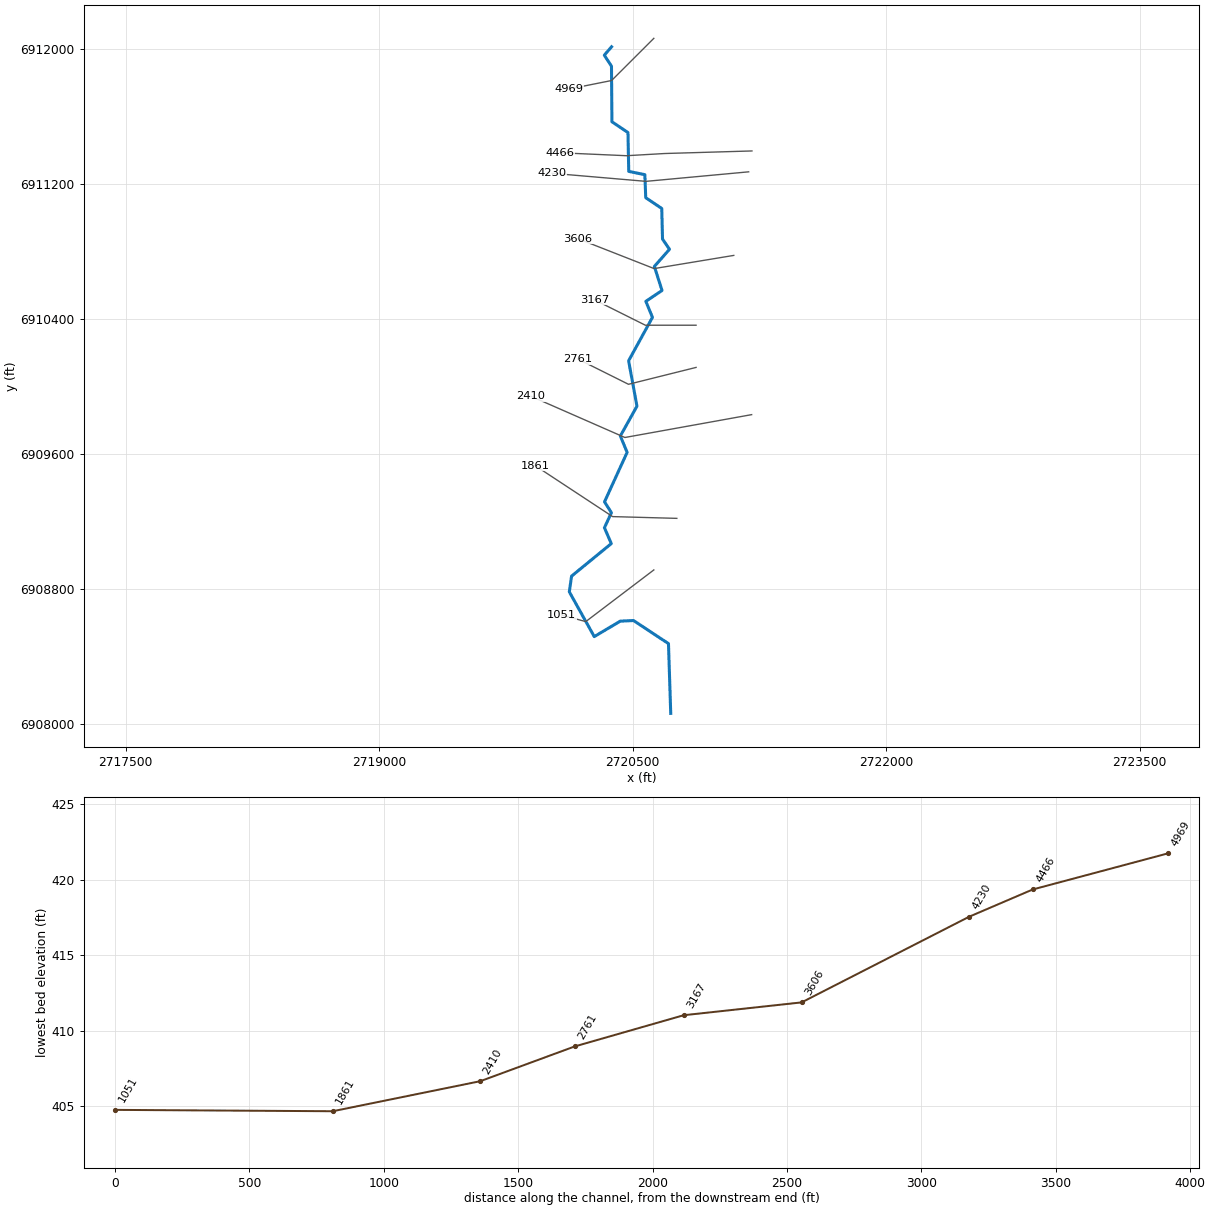
--- Massey T3.prj (project) ---

Proj Title=Massey T3 Base Level Engineering
Current Plan=p01
Default Exp/Contr=0.3,0.1
English Units
Geom File=g01
Flow File=f01
Plan File=p01
BEGIN DESCRIPTION:
Massey T3
END DESCRIPTION:

--- Massey T3.p01 (plan) ---

Plan Title=Multiple Run
Short Identifier=Multiple
Geom File=g01
Flow File=f01
Subcritical Flow
K Sum by GR= 0
Std Step Tol= 0.01
Critical Tol= 0.01
Num of Std Step Trials= 20
Max Error Tol= 0.3
Flow Tol Ratio= 0.001
Split Flow NTrial= 30
Split Flow Tol= 0.02
Split Flow Ratio= 0.02
Log Output Level= 0
Friction Slope Method= 1
Unsteady Friction Slope Method= 2
Unsteady Bridges Friction Slope Method= 1
Parabolic Critical Depth
Global Vel Dist=  1 , 1 , 1
Global Log Level= 0
CheckData=True
Encroach Param= -1, 0, 0, 0
BEGIN DESCRIPTION:
Multiple Run
END DESCRIPTION:

--- Massey T3.f01 (steady flow) ---

Flow Title=Multiple
Number of Profiles=7
Profile Names=10-year,25-year,50-year,1pct_min,100-year,1pct_plu,500-year
River Rch & RM= Massey T3,Reach-1,4969
     288     365     424     244     488     973     644
Boundary for River Rch & Prof#=Massey T3,Reach-1,1
Up Type=0
Dn Type=3
Dn Slope=0.005
Boundary for River Rch & Prof#=Massey T3,Reach-1,2
Up Type=0
Dn Type=3
Dn Slope=0.005
Boundary for River Rch & Prof#=Massey T3,Reach-1,3
Up Type=0
Dn Type=3
Dn Slope=0.005
Boundary for River Rch & Prof#=Massey T3,Reach-1,4
Up Type=0
Dn Type=3
Dn Slope=0.005
Boundary for River Rch & Prof#=Massey T3,Reach-1,5
Up Type=0
Dn Type=3
Dn Slope=0.005
Boundary for River Rch & Prof#=Massey T3,Reach-1,6
Up Type=0
Dn Type=3
Dn Slope=0.005
Boundary for River Rch & Prof#=Massey T3,Reach-1,7
Up Type=0
Dn Type=3
Dn Slope=0.005

--- Massey T3.g01 (geometry) ---

Geom Title=Existing Conditions

River Reach=Massey T3,Reach-1
Reach XY= 30
      2720376.00      6912011.00      2720332.91      6911961.14
      2720375.40      6911895.85      2720378.01      6911566.68
      2720472.90      6911502.69      2720477.55      6911272.55
      2720572.99      6911253.00      2720578.02      6911116.70
      2720672.90      6911052.69      2720677.39      6910871.44
      2720718.67      6910810.90      2720629.15      6910709.36
      2720674.43      6910566.86      2720578.70      6910502.49
      2720617.92      6910407.72      2720476.80      6910150.30
      2720526.10      6909881.10      2720427.84      6909704.88
      2720467.93      6909607.69      2720334.10      6909314.29
      2720375.02      6909250.36      2720333.62      6909161.00
      2720374.35      6909067.04      2720139.33      6908874.33
      2720125.89      6908781.10      2720273.46      6908515.96
      2720427.50      6908607.53      2720505.90      6908611.11
      2720712.64      6908474.34      2720726.00      6908061.00

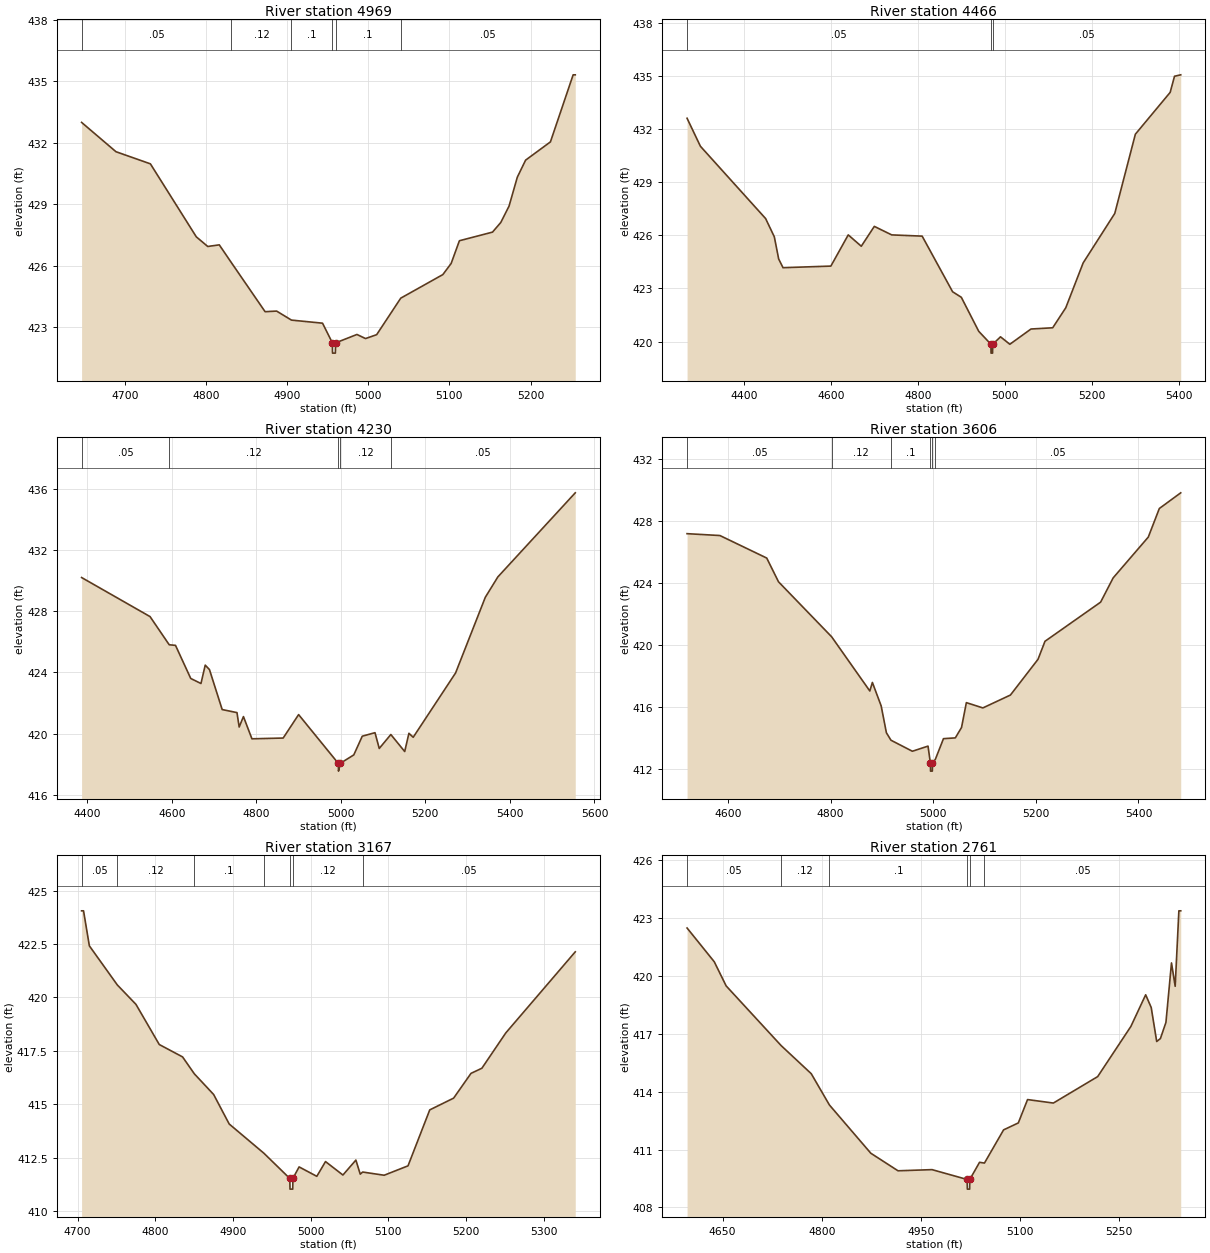
Type RM Length L Ch R = 1,4969,503,503,503
BEGIN DESCRIPTION:
Massey T3 9.0
END DESCRIPTION:
XS GIS Cut Line= 3
      2720625.98      6912060.98      2720376.00      6911811.00
      2720125.97      6911760.99
#Sta/Elev= 30
  4646.6  432.99  4689.0  431.56  4731.4  430.97  4788.0  427.41  4802.1  426.94
  4816.3  427.02  4831.1  426.16  4872.8  423.76  4887.0  423.79  4905.3  423.35
  4943.6  423.20  4955.7  422.24  4955.9  421.74  4959.4  421.74  4959.7  422.24
  4986.0  422.65  4996.6  422.45  5010.3  422.64  5040.0  424.42  5091.9  425.57
  5102.1  426.11  5112.3  427.22  5153.1  427.64  5163.3  428.11  5173.5  428.91
  5183.7  430.32  5193.9  431.15  5224.5  432.04  5252.5  435.31  5255.1  435.31
#Mann=6,-1,0
  4646.6    0.05       0  4831.1    0.12       0  4905.3     0.1       0
  4955.7    0.07       0  4959.7     0.1       0  5040.0    0.05       0
Bank Sta=4955.7,4959.7
Exp/Cntr=0.3,0.1

Type RM Length L Ch R = 1,4466,236,236,236
BEGIN DESCRIPTION:
Mapping XS e1e016ad
END DESCRIPTION:
XS GIS Cut Line= 4
      2721206.73      6911393.66      2720690.25      6911378.47
      2720464.56      6911365.45      2720071.71      6911382.81
#Sta/Elev= 30
  4268.6  432.60  4299.3  431.02  4449.4  426.94  4469.4  425.91  4479.4  424.66
  4489.4  424.17  4599.5  424.26  4639.5  426.02  4669.5  425.38  4699.5  426.50
  4739.5  426.02  4809.6  425.95  4879.7  422.81  4899.7  422.50  4939.8  420.58
  4967.9  419.85  4968.1  419.35  4971.6  419.35  4971.9  419.85  4989.9  420.27
  5011.4  419.85  5060.0  420.71  5110.0  420.78  5140.1  421.91  5180.1  424.44
  5252.8  427.23  5300.2  431.70  5380.3  434.06  5390.3  434.97  5404.6  435.05
#Mann=3,-1,0
  4268.6    0.05       0  4967.9    0.05       0  4971.9    0.05       0
Bank Sta=4967.9,4971.9
Exp/Cntr=0.3,0.1

Type RM Length L Ch R = 1,4230,624,624,624
BEGIN DESCRIPTION:
Mapping XS 93949c9d
END DESCRIPTION:
XS GIS Cut Line= 3
      2721187.23      6911269.96      2720579.58      6911213.54
      2720023.99      6911261.28
#Sta/Elev= 30
  4386.7  430.19  4548.6  427.64  4594.0  425.80  4608.9  425.76  4644.9  423.60
  4669.1  423.27  4679.2  424.47  4689.2  424.18  4719.3  421.57  4754.3  421.37
  4759.5  420.43  4769.6  421.11  4789.7  419.66  4863.6  419.71  4900.1  421.24
  4994.2  418.05  4994.5  417.55  4998.2  418.05  5030.7  418.61  5050.7  419.83
  5080.8  420.06  5090.9  419.03  5118.3  419.94  5151.1  418.83  5161.1  420.02
  5171.2  419.76  5271.5  423.96  5341.8  428.90  5371.5  430.23  5554.6  435.72
#Mann=5,-1,0
  4386.7    0.05       0  4594.0    0.12       0  4994.2    0.07       0
  4998.2    0.12       0  5118.3    0.05       0
Bank Sta=4994.2,4998.2
Exp/Cntr=0.3,0.1

Type RM Length L Ch R = 1,3606,439,439,439
BEGIN DESCRIPTION:
Mapping XS 5201c800
END DESCRIPTION:
XS GIS Cut Line= 3
      2721099.14      6910774.74      2720627.75      6910696.61
      2720177.22      6910873.70
#Sta/Elev= 30
  4520.5  427.16  4584.5  427.04  4675.7  425.59  4698.7  424.06  4802.2  420.52
  4876.6  417.03  4881.6  417.58  4898.7  416.07  4908.9  414.34  4917.8  413.86
  4959.5  413.15  4990.0  413.48  4994.7  412.37  4994.9  411.87  4998.4  411.87
  4998.7  412.37  5004.4  412.64  5020.1  413.96  5043.2  414.01  5055.3  414.68
  5064.7  416.28  5096.9  415.94  5150.6  416.77  5204.3  419.07  5217.9  420.23
  5326.3  422.75  5350.7  424.31  5419.2  426.94  5440.7  428.78  5482.4  429.79
#Mann=6,-1,0
  4520.5    0.05       0  4802.2    0.12       0  4917.8     0.1       0
  4994.7    0.07       0  4998.7     0.1       0  5004.4    0.05       0
Bank Sta=4994.7,4998.7
Exp/Cntr=0.3,0.1

Type RM Length L Ch R = 1,3167,406,406,406
BEGIN DESCRIPTION:
Massey T3 5.0
END DESCRIPTION:
XS GIS Cut Line= 3
      2720876.04      6910361.00      2720576.00      6910361.00
      2720275.96      6910511.02
#Sta/Elev= 30
  4705.2  424.05  4707.7  424.05  4715.2  422.41  4751.2  420.58  4775.2  419.67
  4805.2  417.79  4835.2  417.21  4850.3  416.42  4875.2  415.45  4895.2  414.07
  4939.9  412.70  4973.2  411.52  4973.5  411.02  4977.0  411.02  4977.2  411.52
  4985.2  412.06  5008.0  411.62  5019.2  412.31  5041.6  411.68  5058.3  412.38
  5063.9  411.72  5067.0  411.82  5094.7  411.67  5125.4  412.11  5153.4  414.73
  5184.1  415.28  5206.5  416.44  5220.5  416.68  5251.2  418.33  5340.7  422.13
#Mann=7,-1,0
  4705.2    0.05       0  4751.2    0.12       0  4850.3     0.1       0
  4939.9    0.12       0  4973.2    0.07       0  4977.2    0.12       0
  5067.0    0.05       0
Bank Sta=4973.2,4977.2
Exp/Cntr=0.3,0.1

Type RM Length L Ch R = 1,2761,351,351,351
BEGIN DESCRIPTION:
Massey T3 4.0
END DESCRIPTION:
XS GIS Cut Line= 3
      2720875.96      6910110.99      2720476.00      6910011.00
      2720175.98      6910161.01
#Sta/Elev= 30
  4596.1  422.48  4637.3  420.73  4655.3  419.48  4738.5  416.39  4784.2  414.93
  4811.7  413.31  4874.4  410.81  4915.6  409.90  4967.1  409.96  5020.3  409.45
  5020.6  408.95  5024.1  408.95  5024.3  409.45  5039.1  410.34  5046.5  410.30
  5075.5  412.02  5097.8  412.38  5111.8  413.59  5150.9  413.41  5218.0  414.78
  5268.3  417.38  5290.7  419.02  5299.1  418.36  5307.4  416.60  5313.0  416.75
  5321.4  417.59  5329.8  420.67  5335.4  419.46  5341.0  423.37  5343.8  423.37
#Mann=6,-1,0
  4596.1    0.05       0  4738.5    0.12       0  4811.7     0.1       0
  5020.3    0.07       0  5024.3     0.1       0  5046.5    0.05       0
Bank Sta=5020.3,5024.3
Exp/Cntr=0.3,0.1

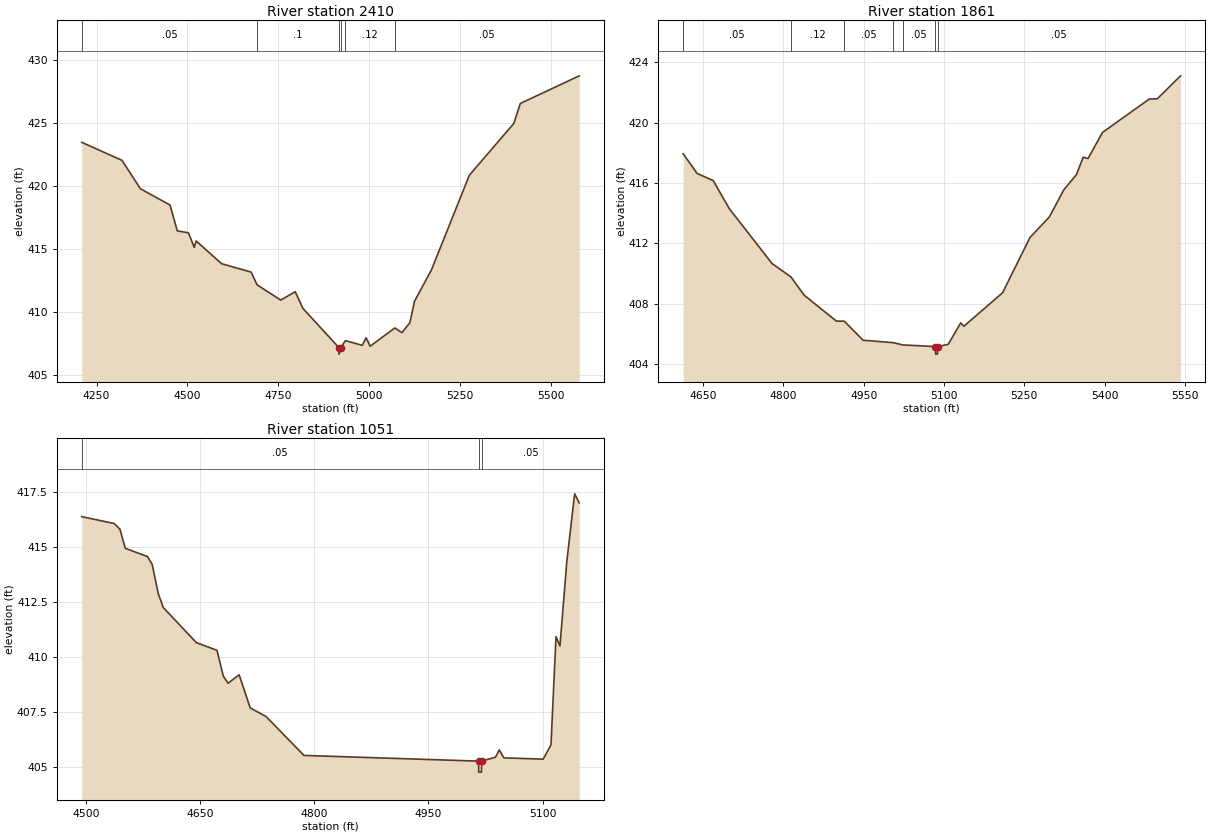
Type RM Length L Ch R = 1,2410,549,549,549
BEGIN DESCRIPTION:
Mapping XS e7760acb
END DESCRIPTION:
XS GIS Cut Line= 3
      2721204.82      6909831.15      2720454.85      6909695.74
      2719899.28      6909939.77
#Sta/Elev= 30
  4209.3  423.49  4319.9  422.06  4370.7  419.80  4452.0  418.51  4472.3  416.45
  4502.8  416.30  4518.9  415.14  4523.9  415.65  4594.2  413.84  4675.5  413.17
  4691.7  412.16  4756.8  410.95  4796.8  411.61  4817.8  410.29  4917.4  407.15
  4917.7  406.65  4921.4  407.15  4934.9  407.72  4981.1  407.35  4991.7  407.95
  5002.9  407.28  5070.8  408.73  5090.3  408.36  5112.1  409.14  5124.9  410.85
  5171.6  413.35  5276.0  420.88  5398.2  424.99  5416.1  426.58  5578.2  428.78
#Mann=6,-1,0
  4209.3    0.05       0  4691.7     0.1       0  4917.4    0.07       0
  4921.4     0.1       0  4934.9    0.12       0  5070.8    0.05       0
Bank Sta=4917.4,4921.4
Exp/Cntr=0.3,0.1

Type RM Length L Ch R = 1,1861,810,810,810
BEGIN DESCRIPTION:
Mapping XS 01fa444d
END DESCRIPTION:
XS GIS Cut Line= 3
      2720762.17      6909216.57      2720381.93      6909226.99
      2719923.61      6909529.07
#Sta/Elev= 30
  4612.6  417.94  4638.8  416.63  4668.8  416.16  4698.8  414.30  4778.8  410.66
  4813.9  409.78  4838.9  408.56  4898.9  406.85  4913.8  406.84  4948.9  405.58
  5004.8  405.42  5023.0  405.27  5084.0  405.16  5084.2  404.66  5087.7  404.66
  5088.0  405.16  5107.9  405.31  5131.2  406.73  5137.2  406.51  5209.5  408.73
  5260.7  412.39  5296.8  413.75  5323.9  415.55  5347.4  416.55  5360.0  417.71
  5369.1  417.62  5396.1  419.35  5483.5  421.56  5498.6  421.58  5541.9  423.10
#Mann=7,-1,0
  4612.6    0.05       0  4813.9    0.12       0  4913.8    0.05       0
  5004.8    0.12       0  5023.0    0.05       0  5084.0    0.03       0
  5088.0    0.05       0
Bank Sta=5084,5088
Exp/Cntr=0.3,0.1

Type RM Length L Ch R = 1,1051,0,0,0
BEGIN DESCRIPTION:
Massey T3 1.0
END DESCRIPTION:
XS GIS Cut Line= 3
      2720626.00      6908911.00      2720223.27      6908604.83
      2720080.24      6908643.62
#Sta/Elev= 30
  4494.1  416.37  4536.7  416.06  4544.3  415.80  4551.3  414.93  4580.4  414.56
  4586.6  414.21  4594.6  412.88  4601.2  412.24  4644.8  410.64  4671.9  410.29
  4680.2  409.12  4686.5  408.79  4701.0  409.18  4715.6  407.67  4736.4  407.28
  4786.3  405.51  5015.9  405.25  5016.1  404.75  5019.6  404.75  5019.9  405.25
  5038.1  405.43  5043.2  405.76  5049.0  405.40  5100.8  405.34  5111.1  405.99
  5117.7  410.91  5122.9  410.49  5131.9  414.33  5142.2  417.41  5148.2  417.00
#Mann=3,-1,0
  4494.1    0.05       0  5015.9    0.03       0  5019.9    0.05       0
Bank Sta=5015.9,5019.9
Exp/Cntr=0.3,0.1

Chan Stop Cuts=-1