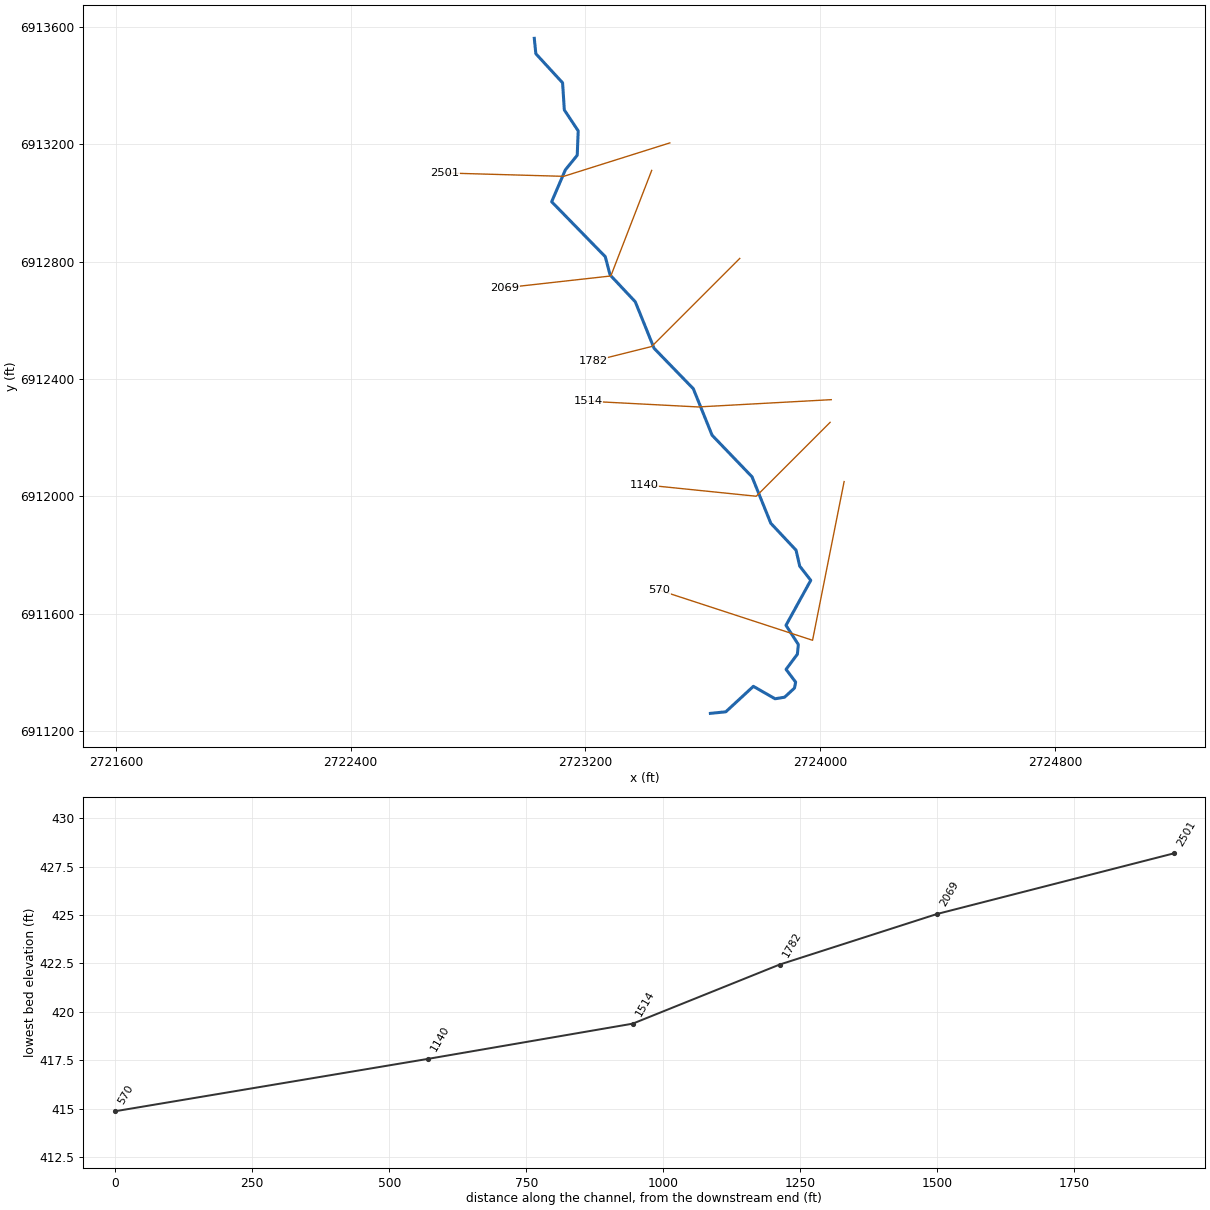
--- Massey T4.prj (project) ---

Proj Title=Massey T4 Base Level Engineering
Current Plan=p01
Default Exp/Contr=0.3,0.1
English Units
Geom File=g01
Flow File=f01
Plan File=p01
BEGIN DESCRIPTION:
Massey T4
END DESCRIPTION:

--- Massey T4.p01 (plan) ---

Plan Title=Multiple Run
Short Identifier=Multiple
Geom File=g01
Flow File=f01
Subcritical Flow
K Sum by GR= 0
Std Step Tol= 0.01
Critical Tol= 0.01
Num of Std Step Trials= 20
Max Error Tol= 0.3
Flow Tol Ratio= 0.001
Split Flow NTrial= 30
Split Flow Tol= 0.02
Split Flow Ratio= 0.02
Log Output Level= 0
Friction Slope Method= 1
Unsteady Friction Slope Method= 2
Unsteady Bridges Friction Slope Method= 1
Parabolic Critical Depth
Global Vel Dist=  1 , 1 , 1
Global Log Level= 0
CheckData=True
Encroach Param= -1, 0, 0, 0
BEGIN DESCRIPTION:
Multiple Run
END DESCRIPTION:

--- Massey T4.f01 (steady flow) ---

Flow Title=Multiple
Number of Profiles=7
Profile Names=10-year,25-year,50-year,1pct_min,100-year,1pct_plu,500-year
River Rch & RM= Massey T4,Reach-1,2501
     238     297     342     196     392     781     510
Boundary for River Rch & Prof#=Massey T4,Reach-1,1
Up Type=0
Dn Type=3
Dn Slope=0.005
Boundary for River Rch & Prof#=Massey T4,Reach-1,2
Up Type=0
Dn Type=3
Dn Slope=0.005
Boundary for River Rch & Prof#=Massey T4,Reach-1,3
Up Type=0
Dn Type=3
Dn Slope=0.005
Boundary for River Rch & Prof#=Massey T4,Reach-1,4
Up Type=0
Dn Type=3
Dn Slope=0.005
Boundary for River Rch & Prof#=Massey T4,Reach-1,5
Up Type=0
Dn Type=3
Dn Slope=0.005
Boundary for River Rch & Prof#=Massey T4,Reach-1,6
Up Type=0
Dn Type=3
Dn Slope=0.005
Boundary for River Rch & Prof#=Massey T4,Reach-1,7
Up Type=0
Dn Type=3
Dn Slope=0.005

--- Massey T4.g01 (geometry) ---

Geom Title=Existing Conditions

River Reach=Massey T4,Reach-1
Reach XY= 30
      2723026.00      6913561.00      2723031.33      6913508.49
      2723122.39      6913409.50      2723128.36      6913316.98
      2723175.62      6913245.73      2723172.32      6913162.58
      2723132.09      6913113.17      2723085.11      6913004.27
      2723267.84      6912817.05      2723284.18      6912754.96
      2723370.15      6912663.29      2723434.14      6912504.94
      2723567.86      6912367.06      2723631.83      6912208.70
      2723767.86      6912067.06      2723831.85      6911908.71
      2723917.86      6911817.04      2723930.45      6911762.65
      2723967.98      6911714.31      2723883.56      6911561.00
      2723925.71      6911495.64      2723922.38      6911462.65
      2723883.84      6911410.90      2723916.47      6911367.47
      2723912.50      6911347.17      2723878.83      6911316.11
      2723846.31      6911310.76      2723772.60      6911353.19
      2723678.52      6911266.35      2723626.00      6911261.00

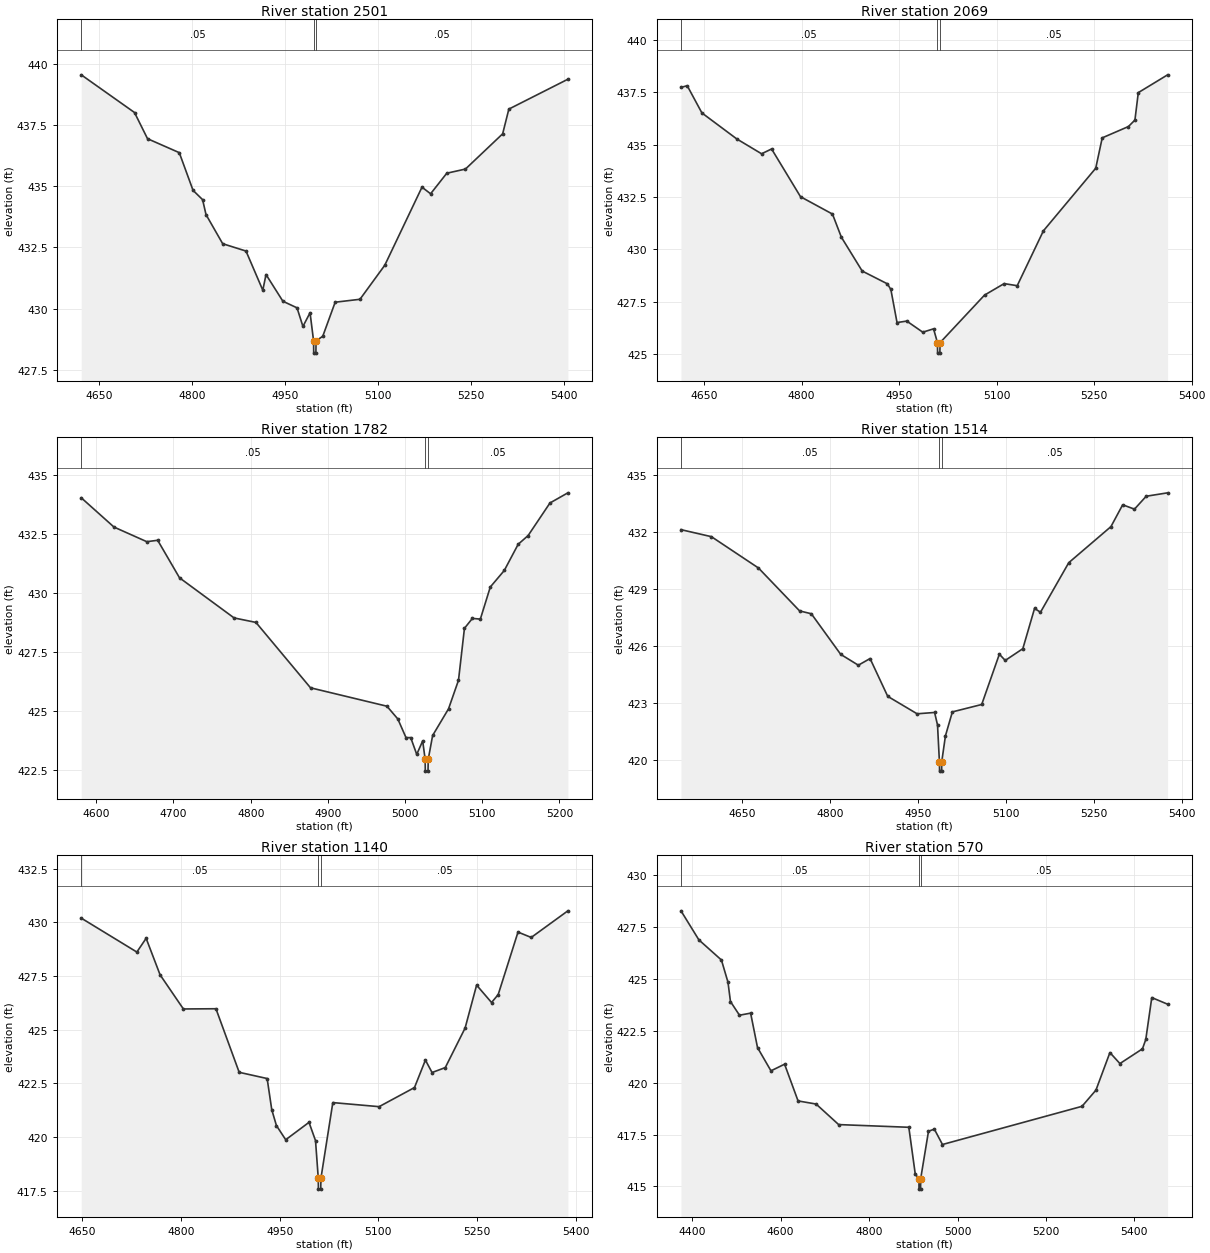
Type RM Length L Ch R = 1,2501,432,432,432
BEGIN DESCRIPTION:
Massey T4 5.0
END DESCRIPTION:
XS GIS Cut Line= 3
      2723487.92      6913204.75      2723126.35      6913090.79
      2722720.82      6913102.32
#Sta/Elev= 30
  4620.9  439.55  4706.8  438.01  4727.8  436.94  4779.0  436.37  4801.2  434.83
  4816.6  434.45  4822.1  433.84  4849.0  432.65  4886.6  432.35  4913.7  430.75
  4918.9  431.39  4946.1  430.30  4968.9  430.03  4978.4  429.27  4989.9  429.83
  4995.6  428.68  4995.8  428.18  4999.3  428.18  4999.6  428.68  5010.4  428.87
  5030.4  430.26  5070.4  430.38  5110.4  431.77  5170.4  434.96  5184.3  434.69
  5210.4  435.53  5240.5  435.70  5300.5  437.14  5310.5  438.15  5405.7  439.37
#Mann=3,-1,0
  4620.9    0.05       0  4995.6    0.04       0  4999.6    0.05       0
Bank Sta=4995.6,4999.6
Exp/Cntr=0.3,0.1

Type RM Length L Ch R = 1,2069,287,287,287
BEGIN DESCRIPTION:
Massey T4 4.0
END DESCRIPTION:
XS GIS Cut Line= 3
      2723426.01      6913111.03      2723286.80      6912751.33
      2722926.05      6912711.01
#Sta/Elev= 30
  4614.3  437.74  4623.9  437.82  4646.5  436.52  4700.1  435.28  4738.3  434.57
  4753.7  434.80  4798.2  432.52  4847.4  431.69  4861.0  430.59  4893.1  428.97
  4931.8  428.36  4937.2  428.09  4946.7  426.51  4961.7  426.58  4986.3  426.05
  5002.9  426.21  5008.9  425.55  5009.1  425.05  5012.6  425.05  5012.9  425.55
  5081.3  427.82  5111.5  428.37  5131.6  428.27  5171.9  430.89  5252.4  433.88
  5262.4  435.33  5302.7  435.87  5312.7  436.18  5317.9  437.49  5363.0  438.34
#Mann=3,-1,0
  4614.3    0.05       0  5008.9    0.04       0  5012.9    0.05       0
Bank Sta=5008.9,5012.9
Exp/Cntr=0.3,0.1

Type RM Length L Ch R = 1,1782,268,268,268
BEGIN DESCRIPTION:
Massey T4 3.0
END DESCRIPTION:
XS GIS Cut Line= 3
      2723726.01      6912811.01      2723426.00      6912511.00
      2723226.03      6912461.01
#Sta/Elev= 30
  4580.5  434.02  4622.9  432.78  4665.4  432.16  4679.5  432.22  4707.8  430.63
  4778.5  428.93  4806.8  428.74  4877.5  425.97  4976.5  425.19  4990.6  424.65
  5001.2  423.86  5007.3  423.86  5015.1  423.15  5022.8  423.72  5026.0  422.94
  5026.2  422.44  5029.7  422.44  5030.0  422.94  5035.7  423.95  5056.3  425.08
  5069.2  426.29  5076.9  428.49  5087.2  428.91  5097.5  428.88  5110.4  430.24
  5128.5  430.94  5146.5  432.05  5159.4  432.42  5187.7  433.80  5210.9  434.23
#Mann=3,-1,0
  4580.5    0.05       0  5026.0    0.04       0  5030.0    0.05       0
Bank Sta=5026,5030
Exp/Cntr=0.3,0.1

Type RM Length L Ch R = 1,1514,374,374,374
BEGIN DESCRIPTION:
Massey T4 2.0
END DESCRIPTION:
XS GIS Cut Line= 3
      2724037.86      6912329.89      2723584.44      6912305.07
      2723209.55      6912324.60
#Sta/Elev= 30
  4545.9  432.11  4597.8  431.74  4678.0  430.09  4748.1  427.83  4768.1  427.68
  4818.2  425.54  4848.2  424.97  4868.2  425.32  4898.3  423.33  4948.4  422.41
  4978.2  422.48  4983.2  421.82  4986.4  419.89  4986.7  419.39  4990.2  419.39
  4990.4  419.89  4996.7  421.25  5008.5  422.51  5058.5  422.90  5088.6  425.55
  5098.6  425.22  5128.6  425.84  5148.6  427.96  5158.7  427.76  5206.9  430.37
  5278.8  432.27  5298.8  433.42  5318.9  433.19  5338.9  433.87  5375.4  434.05
#Mann=3,-1,0
  4545.9    0.05       0  4986.4    0.04       0  4990.4    0.05       0
Bank Sta=4986.4,4990.4
Exp/Cntr=0.3,0.1

Type RM Length L Ch R = 1,1140,570,570,570
BEGIN DESCRIPTION:
Mapping XS 500fd602
END DESCRIPTION:
XS GIS Cut Line= 3
      2724033.88      6912252.57      2723782.17      6912000.85
      2723400.64      6912039.87
#Sta/Elev= 30
  4648.4  430.19  4732.9  428.61  4747.0  429.25  4768.2  427.55  4803.6  425.96
  4853.1  425.97  4888.4  423.01  4930.9  422.72  4937.9  421.27  4945.0  420.53
  4959.1  419.87  4994.5  420.68  5004.4  419.83  5008.6  418.07  5008.8  417.57
  5012.3  417.57  5012.6  418.07  5030.7  421.60  5101.0  421.41  5154.8  422.30
  5171.4  423.58  5181.5  423.00  5201.6  423.23  5231.7  425.07  5249.2  427.07
  5271.9  426.26  5282.0  426.63  5312.1  429.54  5332.2  429.29  5387.9  430.53
#Mann=3,-1,0
  4648.4    0.05       0  5008.6    0.04       0  5012.6    0.05       0
Bank Sta=5008.6,5012.6
Exp/Cntr=0.3,0.1

Type RM Length L Ch R = 1,570,0,0,0
BEGIN DESCRIPTION:
Massey T4 1.0
END DESCRIPTION:
XS GIS Cut Line= 3
      2724081.65      6912050.76      2723974.12      6911510.08
      2723451.95      6911680.66
#Sta/Elev= 30
  4374.6  428.28  4415.1  426.88  4466.1  425.91  4480.9  424.84  4486.5  423.91
  4506.9  423.25  4532.1  423.35  4547.7  421.69  4578.1  420.57  4608.9  420.89
  4639.4  419.12  4680.2  418.97  4731.2  417.98  4889.9  417.85  4904.5  415.59
  4912.7  415.37  4913.0  414.87  4916.5  414.87  4916.7  415.37  4934.4  417.66
  4947.6  417.76  4966.0  417.02  5281.6  418.86  5313.1  419.64  5344.7  421.45
  5367.3  420.92  5418.3  421.63  5425.8  422.08  5439.4  424.10  5475.2  423.78
#Mann=3,-1,0
  4374.6    0.05       0  4912.7    0.04       0  4916.7    0.05       0
Bank Sta=4912.7,4916.7
Exp/Cntr=0.3,0.1

Chan Stop Cuts=-1