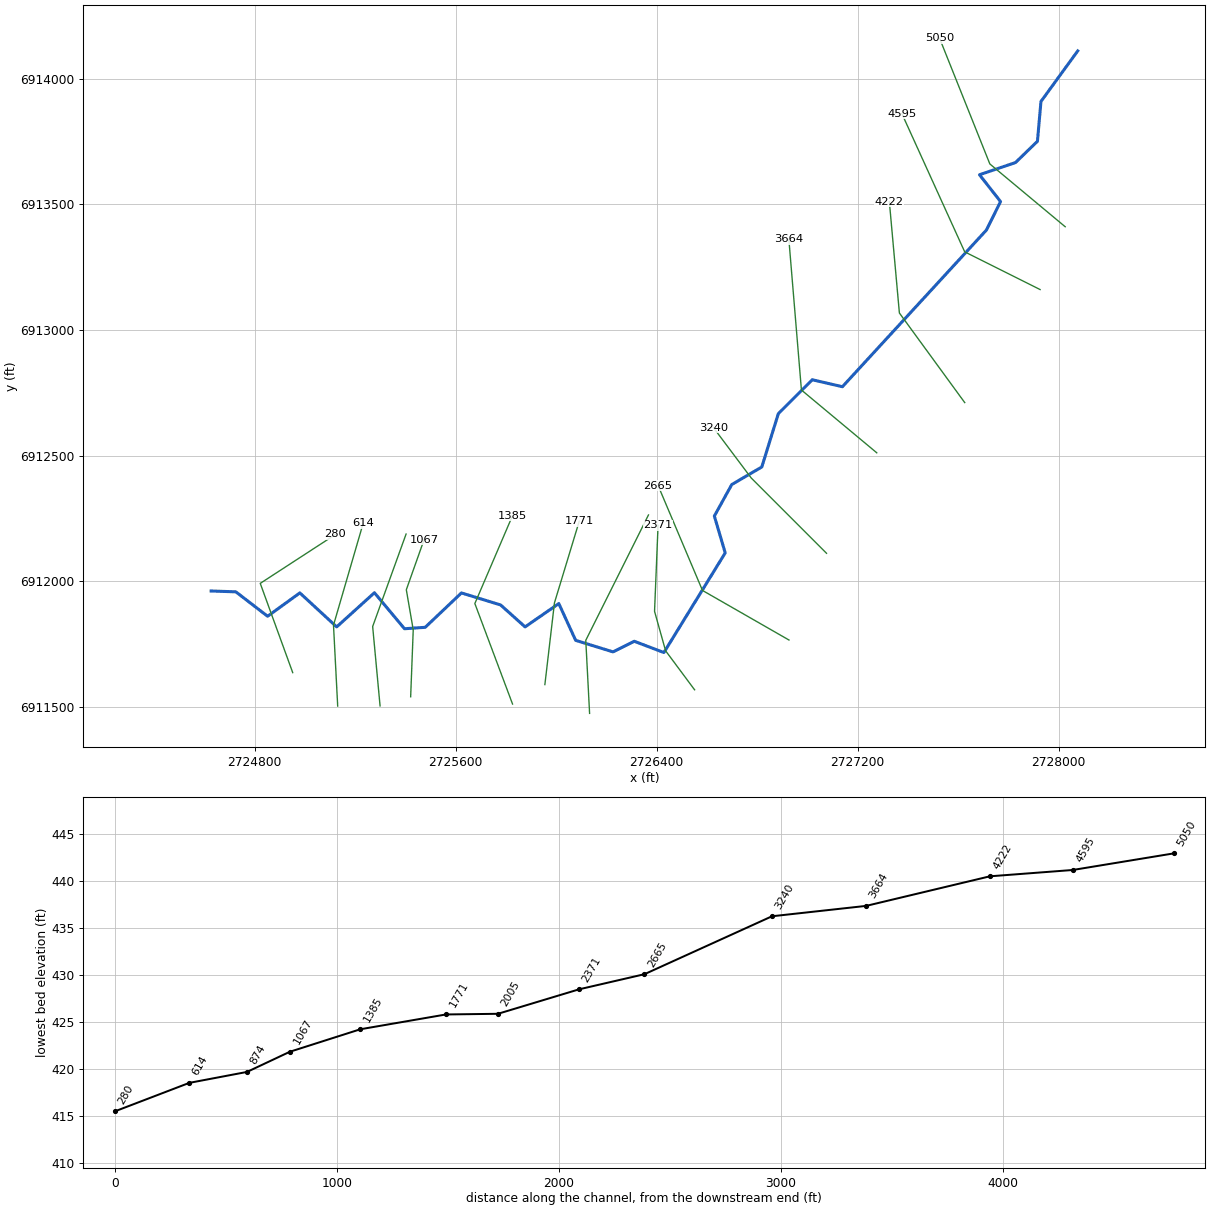
--- Massey T5.prj (project) ---

Proj Title=Massey T5 Base Level Engineering
Current Plan=p01
Default Exp/Contr=0.3,0.1
English Units
Geom File=g01
Flow File=f01
Plan File=p01
Y Axis Title=Elevation
X Axis Title(PF)=Main Channel Distance
X Axis Title(XS)=Station
BEGIN DESCRIPTION:
Massey T5
END DESCRIPTION:
DSS Export Rating Curves= 0
DSS Export Rating Curve Sorted= 0
DSS Export Volume Flow Curves= 0
DXF OffsetX= 0
DXF OffsetY= 0
DXF ScaleX= 1
DXF ScaleY= 10

--- Massey T5.p01 (plan) ---

Plan Title=Multiple Run
Short Identifier=Multiple
Geom File=g01
Flow File=f01
Subcritical Flow
K Sum by GR= 0
Std Step Tol= 0.01
Critical Tol= 0.01
Num of Std Step Trials= 20
Max Error Tol= 0.3
Flow Tol Ratio= 0.001
Split Flow NTrial= 30
Split Flow Tol= 0.02
Split Flow Ratio= 0.02
Log Output Level= 0
Friction Slope Method= 1
Unsteady Friction Slope Method= 2
Unsteady Bridges Friction Slope Method= 1
Parabolic Critical Depth
Global Vel Dist=  1 , 1 , 1
Global Log Level= 0
CheckData=True
Encroach Param= -1, 0, 0, 0
BEGIN DESCRIPTION:
Multiple Run
END DESCRIPTION:

--- Massey T5.f01 (steady flow) ---

Flow Title=Multiple
Program Version=4.10
Number of Profiles= 7
Profile Names=10-year,25-year,50-year,1pct_min,100-year,1pct_plu,500-year
River Rch & RM=Massey T5,Reach-1         ,5050
     402     521     614     359     717    1431     976
Boundary for River Rch & Prof#=Massey T5,Reach-1         , 1
Up Type= 0
Dn Type= 3
Dn Slope=0.00804
Boundary for River Rch & Prof#=Massey T5,Reach-1         , 2
Up Type= 0
Dn Type= 3
Dn Slope=0.00804
Boundary for River Rch & Prof#=Massey T5,Reach-1         , 3
Up Type= 0
Dn Type= 3
Dn Slope=0.00804
Boundary for River Rch & Prof#=Massey T5,Reach-1         , 4
Up Type= 0
Dn Type= 3
Dn Slope=0.00804
Boundary for River Rch & Prof#=Massey T5,Reach-1         , 5
Up Type= 0
Dn Type= 3
Dn Slope=0.00804
Boundary for River Rch & Prof#=Massey T5,Reach-1         , 6
Up Type= 0
Dn Type= 3
Dn Slope=0.00804
Boundary for River Rch & Prof#=Massey T5,Reach-1         , 7
Up Type= 0
Dn Type= 3
Dn Slope=0.00804
DSS Import GetInterval= 0
DSS Import GetPeak= 0
DSS Import FillOption= 0

--- Massey T5.g01 (geometry) ---

Geom Title=Existing Conditions
Program Version=4.10

River Reach=Massey T5       ,Reach-1
Reach XY= 30
        2728076.        6914111.      2727929.54      6913909.53
      2727915.53      6913751.18      2727828.44      6913666.52
      2727684.83      6913617.99      2727768.69      6913511.09
       2727712.4      6913397.79      2727139.21      6912774.14
      2727019.27      6912801.85      2726884.14      6912667.06
      2726818.25      6912454.55      2726698.86      6912384.84
      2726629.34      6912259.28      2726672.66      6912112.72
      2726428.55      6911715.99      2726310.59      6911760.83
      2726226.01      6911718.59      2726077.26      6911764.51
      2726010.22      6911910.93        2725876.       6911818.1
      2725778.43      6911905.45      2725622.58      6911953.21
      2725478.42       6911816.4      2725395.95      6911810.74
      2725276.21      6911954.02        2725126.      6911818.07
      2724979.34       6911953.4        2724851.      6911860.42
      2724724.59       6911957.6        2724626.        6911961.

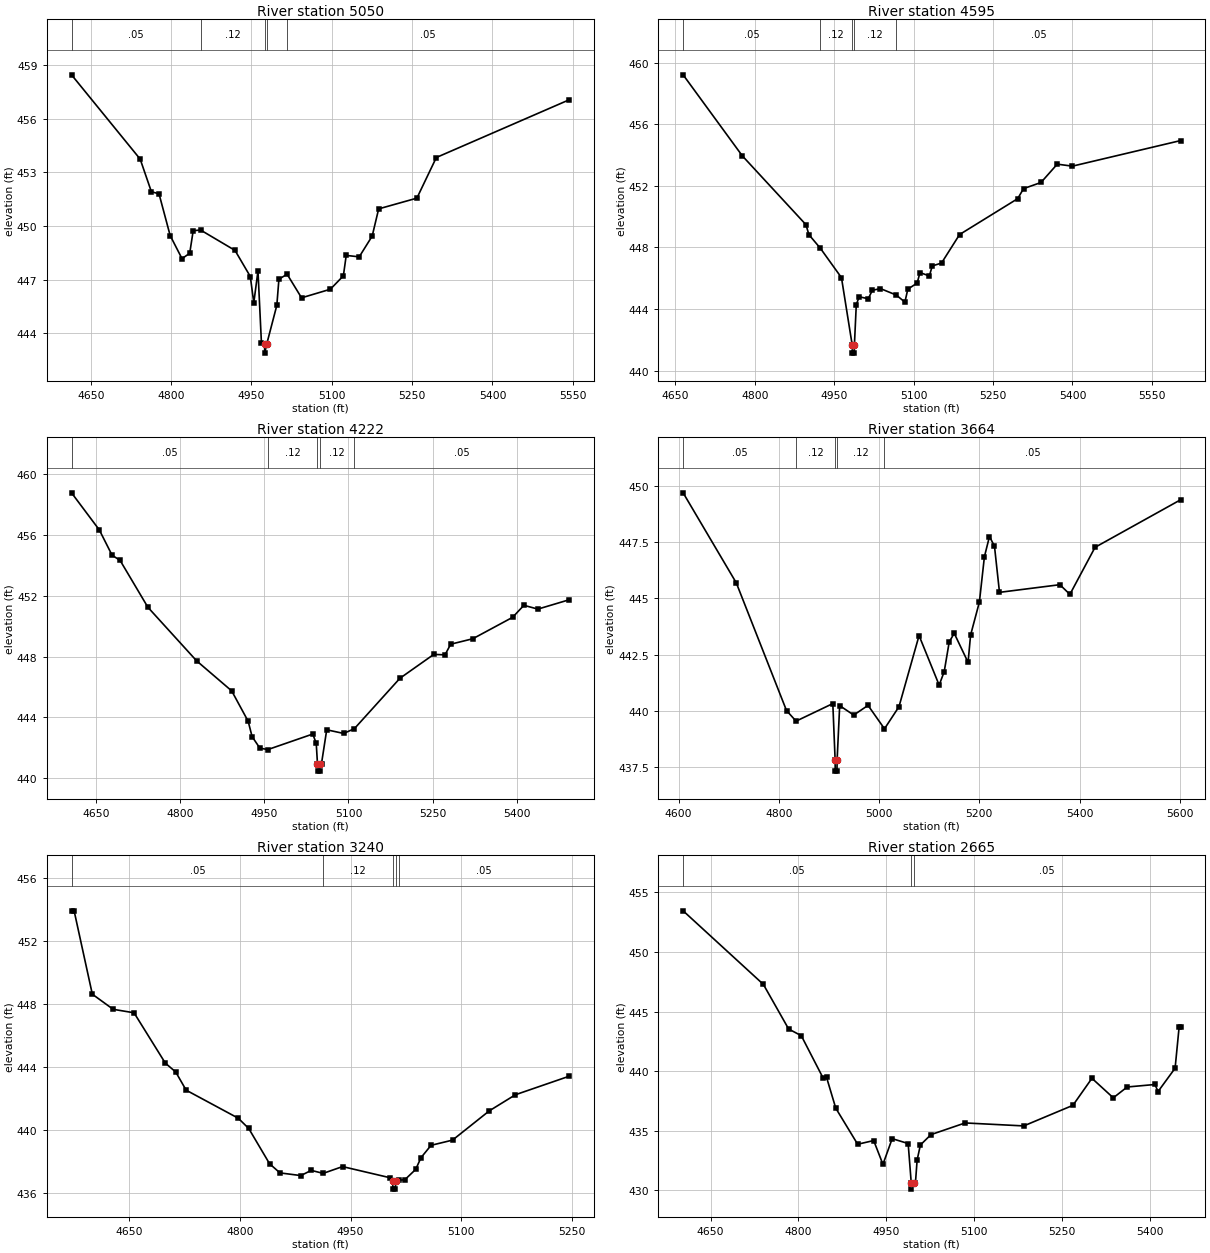
Type RM Length L Ch R = 1 ,5050    ,455,455,455
BEGIN DESCRIPTION:
Massey T5 10.0
END DESCRIPTION:
XS GIS Cut Line= 3
      2728026.01      6913410.99        2727726.        6913661.
      2727526.02      6914160.96
#Sta/Elev= 30
  4613.9  458.45  4742.1  453.74    4763  451.92  4777.3   451.8  4798.1  449.47
  4820.2  448.18  4834.6  448.48  4841.1  449.74  4854.8  449.78  4919.2  448.64
  4947.8  447.18  4954.3  445.71  4962.1   447.5  4968.6  443.44  4974.4   443.4
  4974.7   442.9  4978.4   443.4  4997.3  445.57  5001.2  447.03  5016.5  447.31
  5043.5  445.99  5097.3  446.47  5121.6  447.22  5126.9  448.36  5151.2  448.28
  5175.4  449.44  5187.5  450.96  5258.9  451.56  5295.2  453.83  5542.9  457.05
#Mann= 5 ,-1 , 0
  4613.9     .05       0  4854.8     .12       0  4974.4     .07       0
  4978.4     .12       0  5016.5     .05       0
Bank Sta=4974.4,4978.4
XS Rating Curve= 0 ,0
Exp/Cntr=0.3,0.1

Type RM Length L Ch R = 1 ,4595    ,373,373,373
BEGIN DESCRIPTION:
Massey T5 9.0
END DESCRIPTION:
XS GIS Cut Line= 3
      2727926.03      6913160.99        2727626.        6913311.
        2727376.      6913861.01
#Sta/Elev= 30
  4664.6  459.21  4776.4  453.95  4896.6  449.48  4902.2  448.83  4923.8  447.95
  4963.7  446.04  4984.1  441.64  4984.3  441.14  4987.8  441.14  4988.1  441.64
  4991.7  444.29  4997.2   444.8  5014.3  444.67    5022  445.22  5037.4  445.33
  5067.3  444.91  5083.5  444.45    5089  445.29  5106.6  445.69  5112.1  446.37
  5129.7  446.15  5135.2   446.8  5152.7  446.99  5186.8  448.84  5296.6  451.17
  5307.6  451.82  5340.6  452.22  5371.3  453.41  5399.9  453.28  5604.2  454.94
#Mann= 5 ,-1 , 0
  4664.6     .05       0  4923.8     .12       0  4984.1     .07       0
  4988.1     .12       0  5067.3     .05       0
Bank Sta=4984.1,4988.1
XS Rating Curve= 0 ,0
Exp/Cntr=0.3,0.1

Type RM Length L Ch R = 1 ,4222    ,558,558,558
BEGIN DESCRIPTION:
Massey T5 8.0
END DESCRIPTION:
XS GIS Cut Line= 3
        2727626.      6912711.01      2727365.98      6913067.59
        2727326.      6913510.98
#Sta/Elev= 30
  4606.4  458.78  4655.9  456.34  4678.6  454.68    4693  454.33  4742.5  451.25
  4829.2  447.73  4891.8  445.75  4921.2  443.75  4928.2  442.74  4942.1  441.98
  4956.4  441.89  5036.3  442.91  5042.5   442.3  5044.7  440.97    5045  440.47
  5048.5  440.47  5048.7  440.97  5051.9  440.97  5061.2  443.19  5091.3  442.95
  5110.4  443.26  5191.7  446.58    5252  448.15    5272  448.12  5282.1  448.82
  5321.6  449.18  5392.5  450.59  5412.6  451.38  5437.5  451.13  5492.9  451.74
#Mann= 5 ,-1 , 0
  4606.4     .05       0  4956.4     .12       0  5044.7     .07       0
  5048.7     .12       0  5110.4     .05       0
Bank Sta=5044.7,5048.7
XS Rating Curve= 0 ,0
Exp/Cntr=0.3,0.1

Type RM Length L Ch R = 1 ,3664    ,424,424,424
BEGIN DESCRIPTION:
Massey T5 7.0
END DESCRIPTION:
XS GIS Cut Line= 3
        2727276.        6912511.        2726976.        6912761.
        2726926.        6913361.
#Sta/Elev= 30
    4609  449.69  4715.1  445.69  4815.3  440.02  4834.4  439.55  4907.7  440.33
  4912.3  437.83  4912.5  437.33    4916  437.33  4916.3  437.83  4921.4  440.24
  4949.4  439.82    4978  440.25  5010.8  439.21  5039.7  440.19  5079.8  443.35
  5119.9  441.15    5130  441.75    5140  443.07    5150  443.45  5177.6  442.16
  5182.6  443.37  5200.2  444.84  5210.2  446.85  5220.3  447.75  5230.3  447.32
  5240.3  445.27  5360.8  445.61  5380.8  445.18    5431  447.27  5601.6  449.38
#Mann= 5 ,-1 , 0
    4609     .05       0  4834.4     .12       0  4912.3     .07       0
  4916.3     .12       0  5010.8     .05       0
Bank Sta=4912.3,4916.3
XS Rating Curve= 0 ,0
Exp/Cntr=0.3,0.1

Type RM Length L Ch R = 1 ,3240    ,575,575,575
BEGIN DESCRIPTION:
Massey T5 6.0
END DESCRIPTION:
XS GIS Cut Line= 3
      2727075.97      6912111.03        2726776.        6912411.
      2726625.59      6912611.54
#Sta/Elev= 30
  4571.4  453.89  4574.9  453.89  4599.6   448.6  4627.9  447.64  4656.2  447.42
  4698.6  444.23  4712.8  443.66  4726.9  442.51  4797.6  440.73  4811.8  440.08
  4840.1  437.84  4854.2  437.26  4882.5  437.09  4896.6  437.42  4912.8  437.23
  4939.1  437.66  5002.9  436.96  5007.2  436.73  5007.4  436.23  5010.9  436.23
  5011.2  436.73  5015.9   436.8  5023.7  436.83  5038.3  437.48  5045.6  438.23
  5059.2  439.01  5088.3  439.34  5138.3   441.2  5173.7  442.22  5246.3  443.39
#Mann= 5 ,-1 , 0
  4571.4     .05       0  4912.8     .12       0  5007.2     .07       0
  5011.2     .12       0  5015.9     .05       0
Bank Sta=5007.2,5011.2
XS Rating Curve= 0 ,0
Exp/Cntr=0.3,0.1

Type RM Length L Ch R = 1 ,2665    ,294,294,294
BEGIN DESCRIPTION:
Massey T5 5.0
END DESCRIPTION:
XS GIS Cut Line= 3
      2726926.44       6911765.8       2726582.1      6911963.19
      2726405.62      6912380.39
#Sta/Elev= 30
  4603.1  453.46  4740.2  447.28  4783.4  443.53    4805  442.97  4842.3  439.41
  4848.1  439.48  4863.9  436.88  4901.3  433.85  4928.7  434.16  4944.5  432.16
  4960.3  434.32  4987.6  433.91  4992.9  430.58  4993.1  430.08  4996.9  430.58
    5000  430.58  5002.9  432.52  5008.5  433.79  5026.6  434.66  5084.9  435.64
  5185.1  435.39  5269.1  437.12  5301.6  439.39  5338.1  437.75  5361.8  438.66
  5409.2  438.87  5414.6  438.28  5443.7  440.24  5450.6  443.71    5453  443.71
#Mann= 3 ,-1 , 0
  4603.1     .05       0  4992.9     .04       0  4996.9     .05       0
Bank Sta=4992.9,4996.9
XS Rating Curve= 0 ,0
Exp/Cntr=0.3,0.1

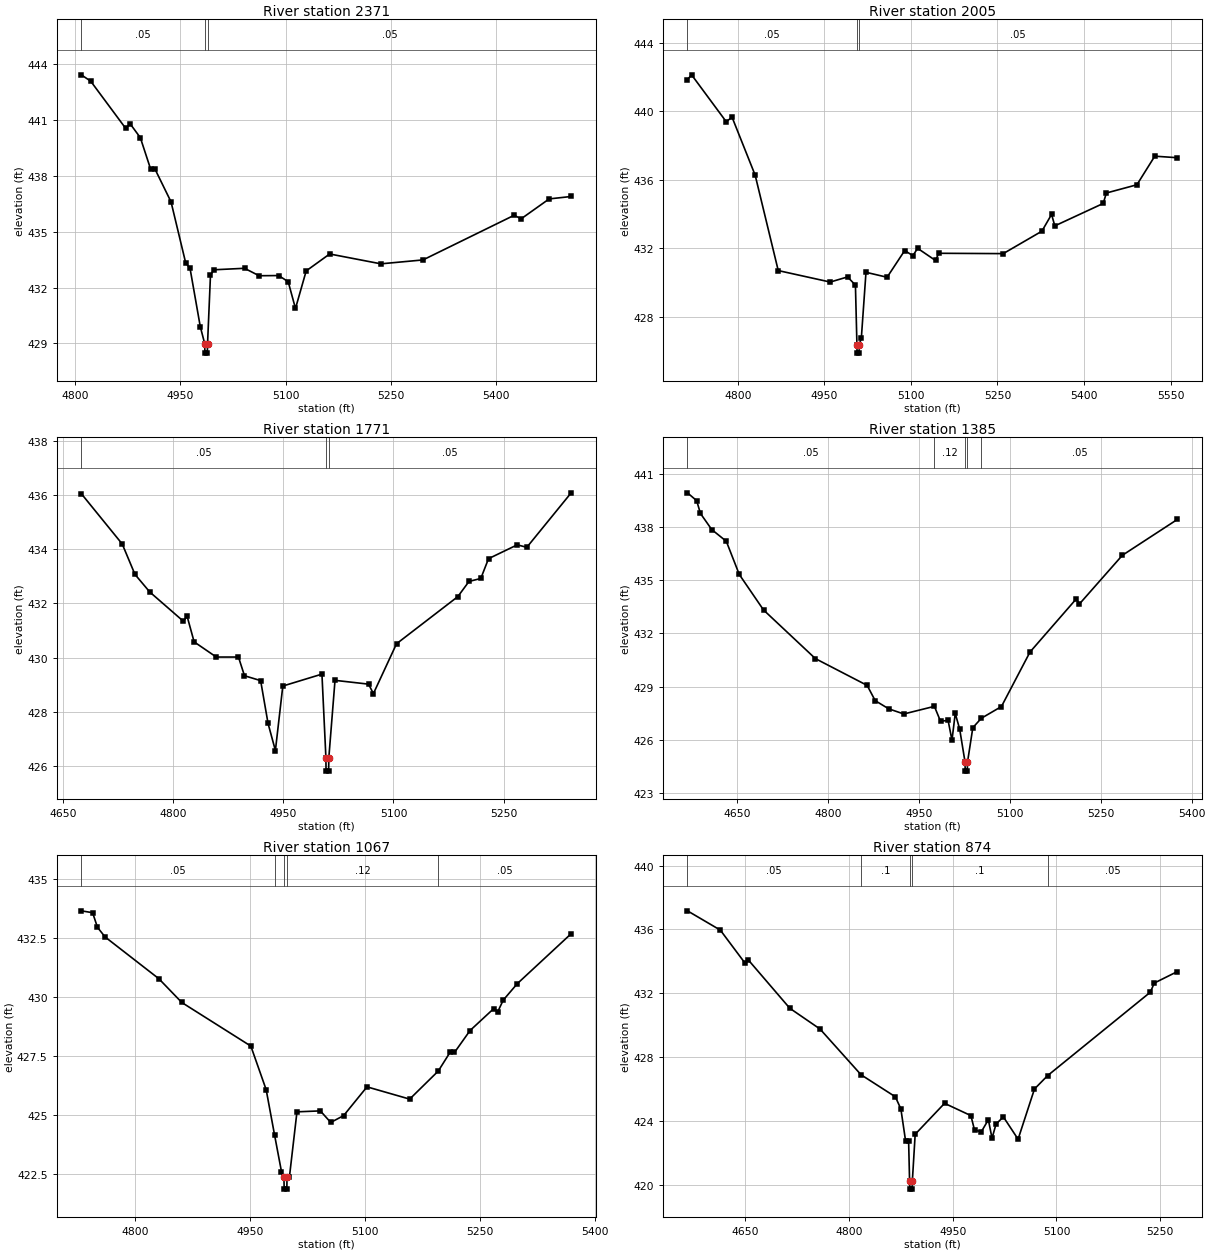
Type RM Length L Ch R = 1 ,2371    ,366,366,366
BEGIN DESCRIPTION:
Mapping XS 97117317
END DESCRIPTION:
XS GIS Cut Line= 4
      2726550.75      6911567.65      2726435.32      6911722.99
      2726391.33      6911879.98       2726405.3      6912222.33
#Sta/Elev= 30
  4808.4  443.44  4821.8   443.1  4871.8  440.56  4878.1  440.81  4892.7  440.06
  4907.3  438.38  4913.5  438.38  4936.5  436.61  4957.4  433.33  4963.6  433.04
  4978.2  429.91  4984.6  428.98  4984.8  428.48  4988.3  428.48  4988.6  428.98
  4992.8  432.68  4997.6  432.96  5041.4  433.04  5062.2  432.64  5090.1  432.65
  5103.7  432.32  5114.1  430.88  5129.4   432.9  5162.9  433.81    5236  433.28
  5296.1  433.49  5426.2  435.89  5436.2   435.7  5476.2  436.77  5507.6   436.9
#Mann= 3 ,-1 , 0
  4808.4     .05       0  4984.6     .04       0  4988.6     .05       0
Bank Sta=4984.6,4988.6
XS Rating Curve= 0 ,0
Exp/Cntr=0.3,0.1

Type RM Length L Ch R = 1 ,2005    ,234,234,234
BEGIN DESCRIPTION:
Mapping XS 88e469ff
END DESCRIPTION:
XS GIS Cut Line= 3
      2726132.77       6911473.8      2726117.58      6911764.58
      2726367.13      6912263.69
#Sta/Elev= 30
  4712.6  441.85  4719.8  442.13  4779.9  439.39  4789.9  439.66    4830  436.27
    4870   430.7  4960.1  430.03  4990.2  430.33  5003.8  429.85  5006.4  426.38
  5006.7  425.88  5010.2  425.88  5010.4  426.38    5014  426.74  5022.1   430.6
  5058.7  430.31  5089.2  431.87  5103.4  431.57  5111.6     432  5142.6  431.29
  5148.2  431.71    5260  431.69    5327     433  5343.8  433.98  5349.4  433.31
  5433.3  434.62  5438.8  435.23  5491.7  435.71  5522.7  437.38  5561.8  437.29
#Mann= 3 ,-1 , 0
  4712.6     .05       0  5006.4     .04       0  5010.4     .05       0
Bank Sta=5006.4,5010.4
XS Rating Curve= 0 ,0
Exp/Cntr=0.3,0.1

Type RM Length L Ch R = 1 ,1771    ,386,386,386
BEGIN DESCRIPTION:
Mapping XS 2afa4284
END DESCRIPTION:
XS GIS Cut Line= 3
      2725954.75      6911588.36      2725992.93      6911913.94
      2726091.59      6912238.78
#Sta/Elev= 30
  4674.8  436.05  4730.6  434.19  4747.9  433.07  4768.1  432.42  4813.9  431.34
  4818.9  431.53  4828.5  430.58  4858.7  430.02  4888.9  430.02  4897.1  429.33
  4919.1  429.15  4929.2  427.57  4939.2  426.57  4949.3  428.95  5002.6  429.39
    5008  426.31  5008.2  425.81  5011.7  425.81    5012  426.31  5020.4  429.16
  5066.1  429.02  5072.7  428.67  5104.2  430.51  5187.7  432.25  5202.9  432.81
    5219  432.92  5229.5  433.65  5268.6  434.16  5281.7  434.07  5342.1  436.08
#Mann= 3 ,-1 , 0
  4674.8     .05       0    5008     .04       0    5012     .05       0
Bank Sta=5008,5012
XS Rating Curve= 0 ,0
Exp/Cntr=0.3,0.1

Type RM Length L Ch R = 1 ,1385    ,318,318,318
BEGIN DESCRIPTION:
Massey T5 3.0
END DESCRIPTION:
XS GIS Cut Line= 3
      2725826.01      6911510.98        2725676.        6911911.
        2725826.      6912260.99
#Sta/Elev= 30
  4568.4  439.92  4583.6  439.48  4589.8  438.76  4608.5  437.85  4632.5  437.19
  4653.9  435.32  4693.9  433.32  4779.4  430.58  4864.8  429.07  4878.1  428.21
  4900.4  427.75  4925.3  427.46  4975.7  427.89  4985.8  427.05  4998.3   427.1
  5004.7  425.98  5010.1  427.49  5017.4  426.61  5026.3  424.74  5026.5  424.24
    5030  424.24  5030.3  424.74  5039.1  426.69  5053.2  427.22  5086.3  427.88
  5133.4  430.95  5209.6  433.94    5215  433.66  5285.7   436.4  5376.4  438.42
#Mann= 5 ,-1 , 0
  4568.4     .05       0  4975.7     .12       0  5026.3     .07       0
  5030.3     .12       0  5053.2     .05       0
Bank Sta=5026.3,5030.3
XS Rating Curve= 0 ,0
Exp/Cntr=0.3,0.1

Type RM Length L Ch R = 1 ,1067    ,193,193,193
BEGIN DESCRIPTION:
Mapping XS 07e811de
END DESCRIPTION:
XS GIS Cut Line= 4
      2725420.48      6911539.88      2725430.73       6911806.4
      2725403.18      6911965.94      2725473.66      6912164.59
#Sta/Elev= 30
  4729.5  433.66  4744.3  433.58  4750.6  432.96  4760.6  432.55  4830.7  430.78
  4860.7  429.77  4950.8  427.92  4970.8  426.07  4981.8  424.14  4990.8  422.59
    4994  422.35  4994.3  421.85  4997.8  421.85    4998  422.35  5001.1  422.35
    5011  425.13  5041.5  425.17  5055.1  424.68  5071.9  424.97  5102.4  426.19
  5158.1  425.67  5195.4  426.86  5211.3  427.68  5216.6  427.65  5236.9  428.58
  5267.8  429.51  5273.1  429.38  5280.2  429.87  5298.6  430.57  5368.9  432.69
#Mann= 5 ,-1 , 0
  4729.5     .05       0  4981.8     .12       0    4994     .07       0
    4998     .12       0  5195.4     .05       0
Bank Sta=4994,4998
XS Rating Curve= 0 ,0
Exp/Cntr=0.3,0.1

Type RM Length L Ch R = 1 ,874     ,260,260,260
BEGIN DESCRIPTION:
Mapping XS ea4c9e3c
END DESCRIPTION:
XS GIS Cut Line= 3
      2725298.71      6911503.59       2725269.2      6911819.56
      2725402.28      6912187.69
#Sta/Elev= 30
  4566.1  437.16  4613.7  435.95  4648.9  433.91    4654  434.09  4714.2  431.05
  4757.9  429.75  4817.3  426.88  4866.9   425.5  4874.9  424.74  4881.7  422.74
  4886.1  422.74  4887.5  420.21  4887.8  419.71  4891.3  419.71  4891.5  420.21
  4895.6  423.15  4938.1  425.09  4976.2  424.32  4981.5  423.41  4991.3  423.31
  5001.5  424.06  5006.8   422.9  5012.6  423.79  5023.2  424.24  5044.5  422.84
  5068.2  425.99  5087.3  426.83  5235.9  432.06  5241.5  432.63  5274.9  433.35
#Mann= 5 ,-1 , 0
  4566.1     .05       0  4817.3      .1       0  4887.5     .05       0
  4891.5      .1       0  5087.3     .05       0
Bank Sta=4887.5,4891.5
XS Rating Curve= 0 ,0
Exp/Cntr=0.3,0.1

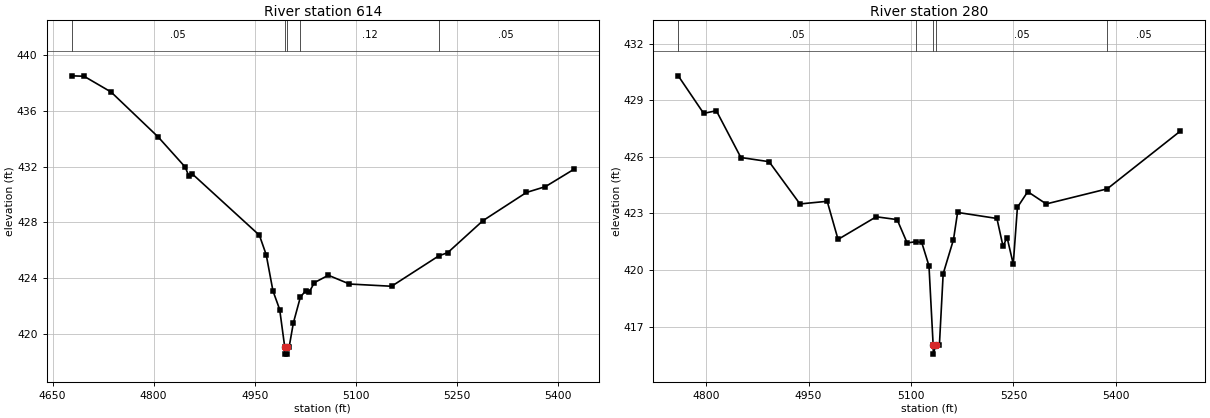
Type RM Length L Ch R = 1 ,614     ,334,334,334
BEGIN DESCRIPTION:
Mapping XS 76bb6f40
END DESCRIPTION:
XS GIS Cut Line= 3
      2725130.01      6911502.82      2725113.31      6911824.95
      2725231.51      6912230.73
#Sta/Elev= 30
  4678.5  438.52  4696.7  438.49  4736.8  437.36  4806.8  434.13  4846.9  431.97
  4852.2  431.33  4857.2  431.49    4957  427.08  4967.1  425.68  4977.1  423.09
  4987.1  421.75  4994.6  419.05  4994.8  418.55  4998.3  418.55  4998.6  419.05
  5001.1  419.05  5007.4  420.79  5017.8  422.64  5025.8  423.11    5031  423.01
  5038.6  423.68  5059.3  424.21  5090.7  423.58  5153.2  423.42  5223.2   425.6
  5236.5  425.83  5288.6  428.12  5353.3  430.15  5381.6  430.57  5423.7  431.81
#Mann= 5 ,-1 , 0
  4678.5     .05       0  4994.6     .04       0  4998.6     .05       0
  5017.8     .12       0  5223.2     .05       0
Bank Sta=4994.6,4998.6
XS Rating Curve= 0 ,0
Exp/Cntr=0.3,0.1

Type RM Length L Ch R = 1 ,280     ,0,0,0
BEGIN DESCRIPTION:
Massey T5 1.0
END DESCRIPTION:
XS GIS Cut Line= 3
      2724950.99      6911636.02      2724821.75      6911991.31
      2725121.09      6912185.91
#Sta/Elev= 30
  4759.2  430.29  4796.4   428.3    4815  428.44  4850.9  425.96  4892.2  425.74
  4937.4   423.5  4977.3  423.64  4993.2  421.62  5049.1  422.82  5079.7  422.67
  5094.4  421.43  5106.7   421.5  5115.7  421.46  5126.3  420.22  5132.4  416.04
  5132.7  415.54  5136.4  416.04  5141.6  416.04  5147.1   419.8  5162.2  421.61
  5168.2  423.05  5225.8  422.73  5234.7  421.26  5240.7  421.72  5249.7  420.31
  5255.8  423.32  5270.9  424.15    5298   423.5  5387.3   424.3  5494.3  427.36
#Mann= 5 ,-1 , 0
  4759.2     .05       0  5106.7     .05       0  5132.4     .04       0
  5136.4     .05       0  5387.3     .05       0
Bank Sta=5132.4,5136.4
XS Rating Curve= 0 ,0
Exp/Cntr=0.3,0.1

Chan Stop Cuts=-1
Use User Specified Reach Order=0
Composite Channel Slope=5