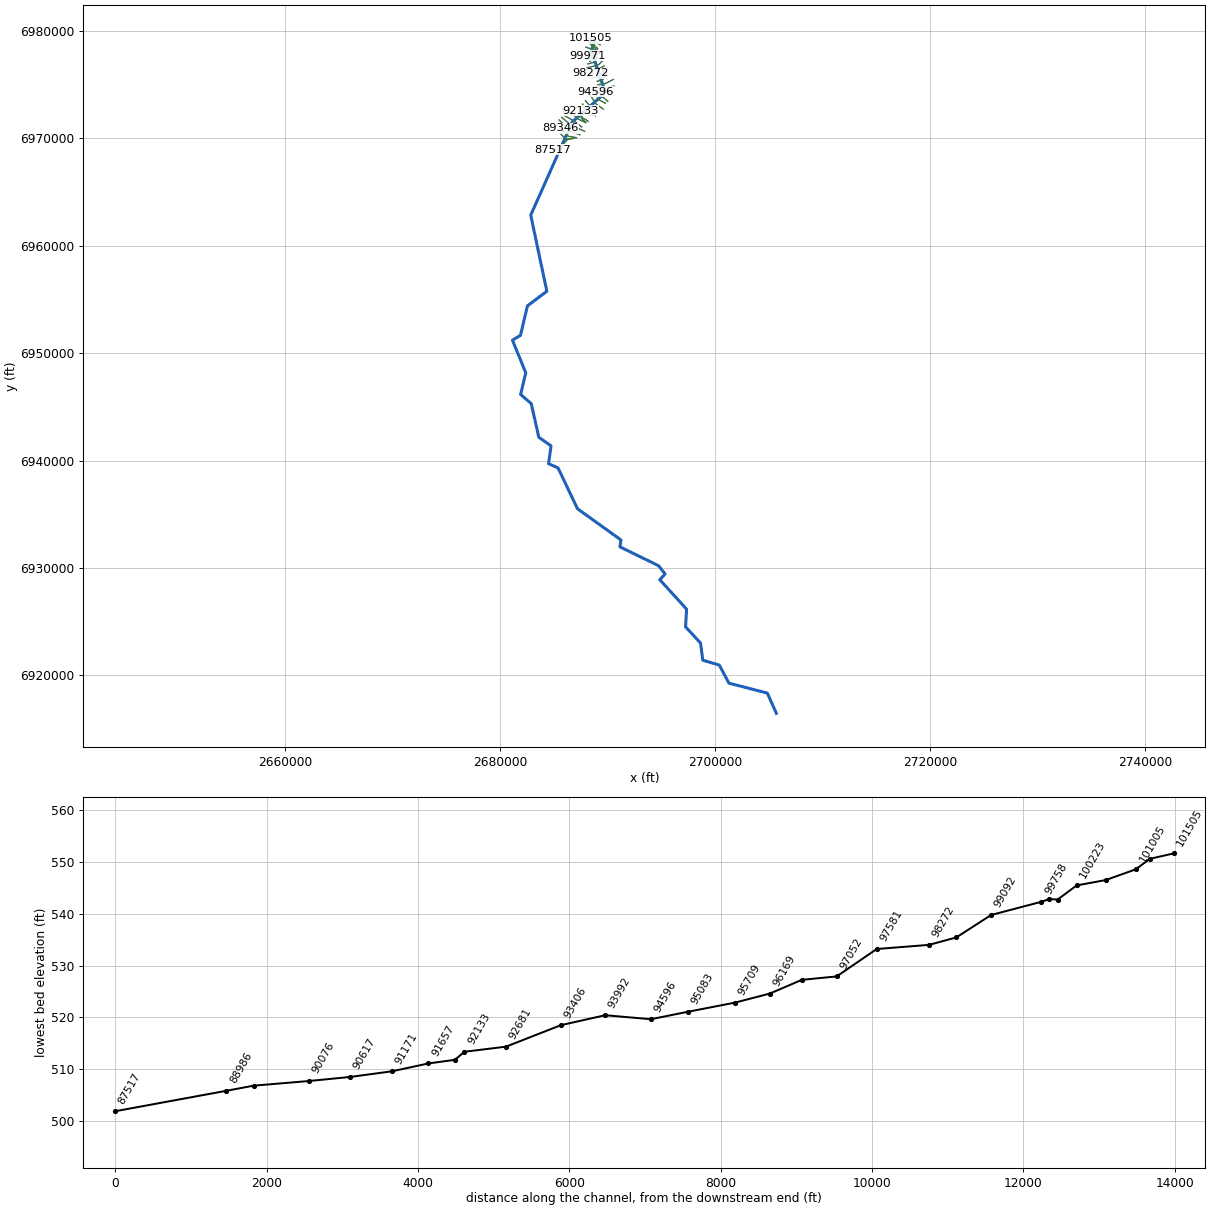
--- Muddy Cedar Creek.prj (project) ---

Proj Title=Muddy Cedar Creek Base Level Engineering
Current Plan=p01
Default Exp/Contr=0.3,0.1
English Units
Geom File=g01
Flow File=f01
Plan File=p01
Y Axis Title=Elevation
X Axis Title(PF)=Main Channel Distance
X Axis Title(XS)=Station
BEGIN DESCRIPTION:
Muddy Cedar Creek
END DESCRIPTION:
DSS Export Rating Curves= 0
DSS Export Rating Curve Sorted= 0
DSS Export Volume Flow Curves= 0
DXF OffsetX= 0
DXF OffsetY= 0
DXF ScaleX= 1
DXF ScaleY= 10

--- Muddy Cedar Creek.p01 (plan) ---

Plan Title=Multiple Run
Short Identifier=Multiple
Geom File=g01
Flow File=f01
Subcritical Flow
K Sum by GR= 0
Std Step Tol= 0.01
Critical Tol= 0.01
Num of Std Step Trials= 20
Max Error Tol= 0.3
Flow Tol Ratio= 0.001
Split Flow NTrial= 30
Split Flow Tol= 0.02
Split Flow Ratio= 0.02
Log Output Level= 0
Friction Slope Method= 1
Unsteady Friction Slope Method= 2
Unsteady Bridges Friction Slope Method= 1
Parabolic Critical Depth
Global Vel Dist=  1 , 1 , 1
Global Log Level= 0
CheckData=True
Encroach Param= -1, 0, 0, 0
BEGIN DESCRIPTION:
Multiple Run
END DESCRIPTION:

--- Muddy Cedar Creek.f01 (steady flow) ---

Flow Title=Multiple
Program Version=4.10
Number of Profiles= 7
Profile Names=10-year,25-year,50-year,1pct_min,100-year,1pct_plu,500-year
River Rch & RM=Muddy Cedar Cree,Reach-1         ,101505
     469     618     736     435     868    1733    1207
River Rch & RM=Muddy Cedar Cree,Reach-1         ,99971
     845    1149    1398     844    1683    3359    2437
River Rch & RM=Muddy Cedar Cree,Reach-1         ,96591
     972    1333    1630     987    1970    3931    2878
River Rch & RM=Muddy Cedar Cree,Reach-1         ,91657
    1716    2399    2972    1818    3627    7236    5407
River Rch & RM=Muddy Cedar Cree,Reach-1         ,84850
    2136    2995    3716    2274    4538    9055    6774
River Rch & RM=Muddy Cedar Cree,Reach-1         ,82618
    2834    4017    5020    3092    6169   12310    9327
River Rch & RM=Muddy Cedar Cree,Reach-1         ,78893
    3253    4624    5790    3571    7126   14217   10802
River Rch & RM=Muddy Cedar Cree,Reach-1         ,71656
    3676    5290    6681    4159    8297   16555   12806
River Rch & RM=Muddy Cedar Cree,Reach-1         ,69114
    3986    5742    7258    4519    9017   17991   13927
River Rch & RM=Muddy Cedar Cree,Reach-1         ,64713
    4106    5909    7464    4644    9265   18487   14286
River Rch & RM=Muddy Cedar Cree,Reach-1         ,61542
    4531    6537    8271    5153   10281   20513   15895
River Rch & RM=Muddy Cedar Cree,Reach-1         ,54394
    5285    7654    9710    6063   12097   24136   18786
River Rch & RM=Muddy Cedar Cree,Reach-1         ,51791
    5449    7890   10008    6247   12465   24871   19348
River Rch & RM=Muddy Cedar Cree,Reach-1         ,48313
    5831    8455   10735    6707   13382   26701   20803
River Rch & RM=Muddy Cedar Cree,Reach-1         ,44317
    6056    8779   11144    6960   13887   27708   21572
River Rch & RM=Muddy Cedar Cree,Reach-1         ,39874
    6348    9199   11674    7288   14542   29015   22570
River Rch & RM=Muddy Cedar Cree,Reach-1         ,34413
    6399    9259   11739    7320   14606   29142   22616
River Rch & RM=Muddy Cedar Cree,Reach-1         ,23293
    6507    9416   11938    7445   14854   29637   23001
River Rch & RM=Muddy Cedar Cree,Reach-1         ,20244
    6783    9798   12412    7732   15428   30783   23834
River Rch & RM=Muddy Cedar Cree,Reach-1         ,18321
    6531    9431   11941    7435   14835   29600   22901
River Rch & RM=Muddy Cedar Cree,Reach-1         ,11115
    6819    9837   12449    7747   15458   30842   23829
River Rch & RM=Muddy Cedar Cree,Reach-1         ,9529
    6640    9589   12142    7560   15084   30097   23285
River Rch & RM=Muddy Cedar Cree,Reach-1         ,8992
    6936   10005   12661    7878   15720   31365   24228
River Rch & RM=Muddy Cedar Cree,Reach-1         ,5877
    6876    9903   12518    7781   15525   30977   23874
Boundary for River Rch & Prof#=Muddy Cedar Cree,Reach-1         , 1
Up Type= 0
Dn Type= 3
Dn Slope=0.00068
Boundary for River Rch & Prof#=Muddy Cedar Cree,Reach-1         , 2
Up Type= 0
Dn Type= 3
Dn Slope=0.00068
Boundary for River Rch & Prof#=Muddy Cedar Cree,Reach-1         , 3
Up Type= 0
Dn Type= 3
Dn Slope=0.00068
Boundary for River Rch & Prof#=Muddy Cedar Cree,Reach-1         , 4
Up Type= 0
Dn Type= 3
Dn Slope=0.00068
Boundary for River Rch & Prof#=Muddy Cedar Cree,Reach-1         , 5
Up Type= 0
Dn Type= 3
Dn Slope=0.00068
Boundary for River Rch & Prof#=Muddy Cedar Cree,Reach-1         , 6
Up Type= 0
Dn Type= 3
Dn Slope=0.00068
Boundary for River Rch & Prof#=Muddy Cedar Cree,Reach-1         , 7
Up Type= 0
Dn Type= 3
Dn Slope=0.00068
DSS Import GetInterval= 0
DSS Import GetPeak= 0
DSS Import FillOption= 0

--- Muddy Cedar Creek.g01 (geometry) ---

Geom Title=Existing Conditions
Program Version=4.10

River Reach=Muddy Cedar Cree,Reach-1
Reach XY= 30
        2688776.        6979261.      2688476.87      6978121.33
      2689772.57      6974262.23      2686681.48      6971513.44
      2682827.06      6962850.56        2684326.        6955761.
        2682526.        6954411.      2681867.05       6951654.3
      2681128.05      6951205.14      2682368.44        6948161.
      2681882.96      6946157.66      2682873.04      6945303.49
      2683579.07       6942169.3       2684718.4      6941364.34
      2684484.85      6939703.96      2685367.86      6939317.06
        2687176.        6935511.      2691221.21      6932605.41
      2691119.78      6931968.74      2694720.38      6930206.28
      2695325.94      6929440.97      2694833.46      6928904.99
        2697326.        6926161.      2697227.68      6924516.52
      2698621.05      6923013.58      2698831.17      6921415.59
      2700370.91      6920955.56      2701269.27      6919269.97
      2704836.24      6918350.66        2705676.        6916461.

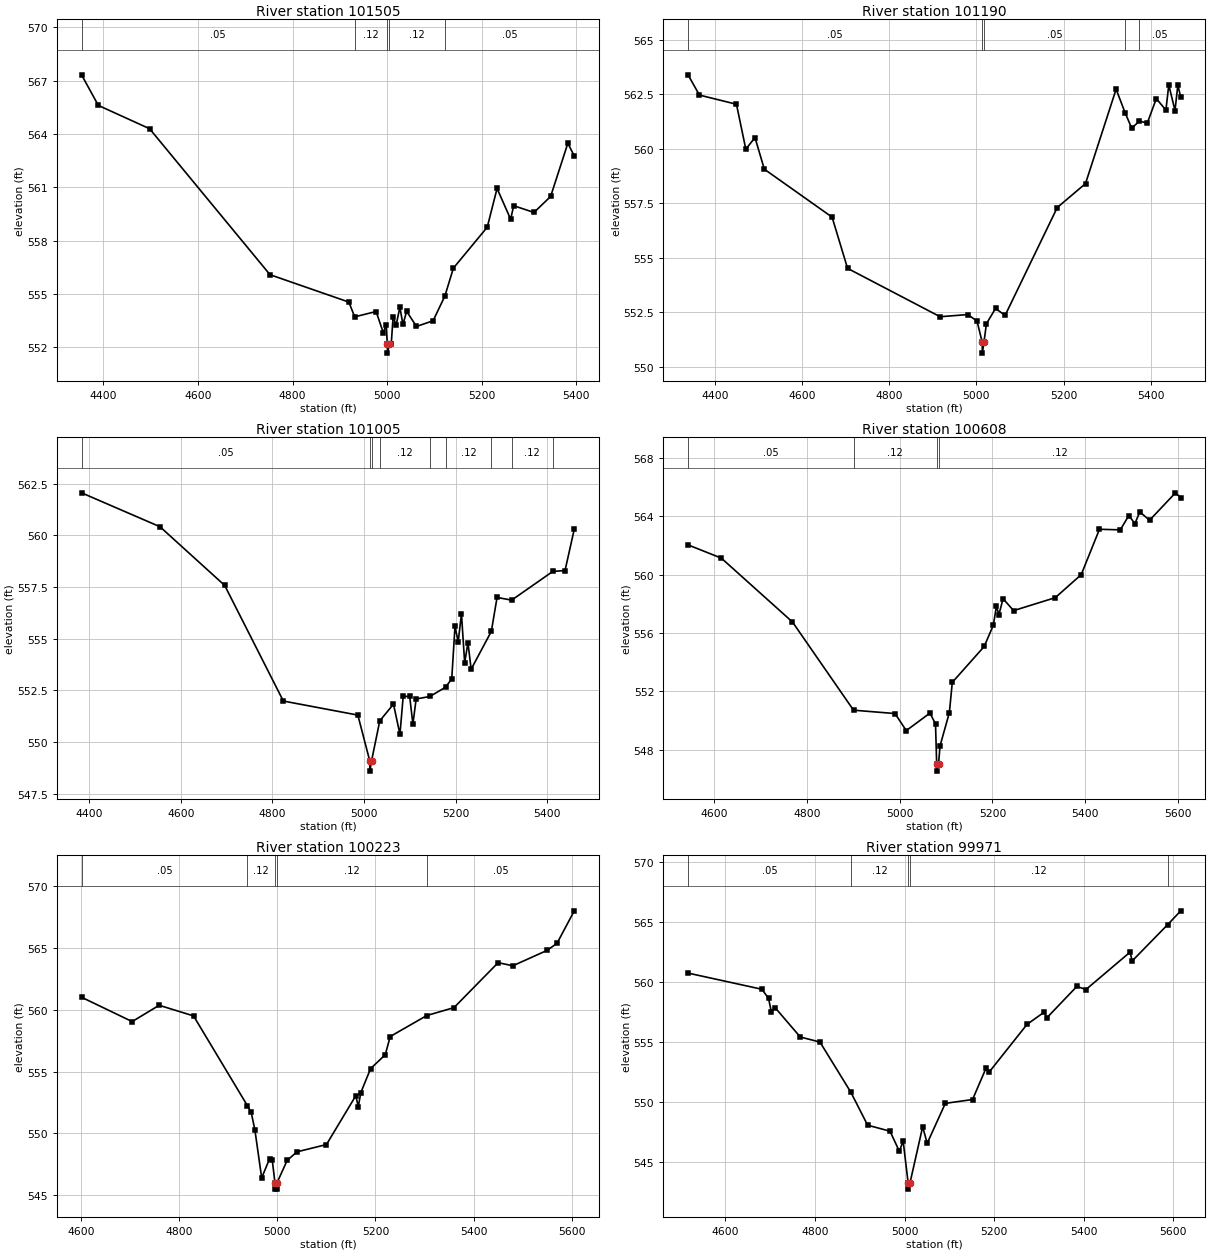
Type RM Length L Ch R = 1 ,101505  ,315,315,315
BEGIN DESCRIPTION:
Muddy Cedar Creek 127.0
END DESCRIPTION:
XS GIS Cut Line= 3
      2689275.97      6978711.02        2688726.        6979061.
        2688426.        6979311.
#Sta/Elev= 30
  4353.7  567.32  4389.2   565.6  4497.6  564.29  4752.4  556.08  4919.2  554.54
  4931.5  553.71  4976.8  554.01    4992  552.82    4998  553.25  5000.6  552.17
  5000.9  551.67  5004.6  552.17  5008.8  552.17  5012.7  553.69  5019.3  553.26
  5027.1  554.25  5033.6  553.28  5041.4  554.02  5062.2  553.17  5097.4  553.49
  5122.3  554.88  5140.3  556.45  5211.9  558.75  5232.7  560.93  5261.4   559.2
  5267.9  559.96  5310.8  559.58    5346  560.48  5382.4  563.47  5396.1  562.75
#Mann= 5 ,-1 , 0
  4353.7     .05       0  4931.5     .12       0  5000.6     .07       0
  5004.6     .12       0  5122.3     .05       0
Bank Sta=5000.6,5004.6
XS Rating Curve= 0 ,0
Exp/Cntr=0.3,0.1

Type RM Length L Ch R = 1 ,101190  ,185,185,185
BEGIN DESCRIPTION:
Muddy Cedar Creek 126.0
END DESCRIPTION:
XS GIS Cut Line= 3
      2689054.96      6978352.68      2688570.27      6978814.65
      2688220.62      6979114.35
#Sta/Elev= 30
  4338.8  563.39    4365  562.46  4449.9  562.04  4471.3  559.98  4492.4  560.51
  4513.8  559.06  4669.2  556.86  4704.7  554.51    4917  552.29  4980.5  552.39
  5001.6  552.09  5013.5  551.12  5013.8  550.62  5017.5  551.12  5023.2  551.97
  5044.1  552.67    5066  552.35  5185.6   557.3  5250.4   558.4  5320.6  562.73
    5341  561.66  5356.4  560.94  5374.1  561.27    5392  561.17  5412.8   562.3
  5434.8  561.77  5441.4  562.93  5455.6  561.75  5462.2  562.92  5468.9  562.35
#Mann= 5 ,-1 , 0
  4338.8     .05       0  5013.5     .03       0  5017.5     .05       0
    5341     .12       0  5374.1     .05       0
Bank Sta=5013.5,5017.5
XS Rating Curve= 0 ,0
Exp/Cntr=0.3,0.1

Type RM Length L Ch R = 1 ,101005  ,397,397,397
BEGIN DESCRIPTION:
Muddy Cedar Creek 125.0
END DESCRIPTION:
XS GIS Cut Line= 3
      2688989.85      6978232.91      2688494.75      6978667.25
      2688200.85       6978964.6
#Sta/Elev= 30
  4382.9  562.06  4554.3  560.42  4695.7  557.58  4823.8  551.99  4986.6  551.31
  5012.6   549.1  5012.8   548.6  5016.6   549.1  5034.5  551.03  5064.5  551.84
  5078.6  550.38  5085.7  552.22  5099.9  552.21  5106.9  550.87    5114  552.09
  5143.9  552.21  5178.4  552.66  5191.8  553.07  5198.9  555.61  5205.9  554.85
    5213  556.21    5220  553.84  5227.2  554.81  5234.2  553.53  5278.3  555.36
  5290.8     557  5322.7  556.87  5412.7  558.26  5439.3   558.3  5459.6  560.31
#Mann= 9 ,-1 , 0
  4382.9     .05       0  5012.6     .03       0  5016.6     .05       0
  5034.5     .12       0  5143.9     .05       0  5178.4     .12       0
  5278.3     .05       0  5322.7     .12       0  5412.7     .05       0
Bank Sta=5012.6,5016.6
XS Rating Curve= 0 ,0
Exp/Cntr=0.3,0.1

Type RM Length L Ch R = 1 ,100608  ,385,385,385
BEGIN DESCRIPTION:
Muddy Cedar Creek 124.0
END DESCRIPTION:
XS GIS Cut Line= 3
      2688976.34      6978212.52      2688457.72      6978323.19
      2687952.11      6978490.28
#Sta/Elev= 30
  4543.5  562.04  4615.4  561.13  4768.8  556.75  4900.5   550.7    4990  550.47
  5014.2   549.3  5065.3   550.5  5077.3  549.76  5079.8  547.02  5080.1  546.52
  5083.8  547.02  5087.1  548.25  5107.2  550.54  5113.5  552.61  5182.3  555.07
    5202  556.53  5208.7  557.83    5214  557.25    5223  558.35  5245.7  557.53
  5335.7  558.42  5391.6     560  5430.9  563.11  5475.8  563.07  5494.3  564.05
  5507.4   563.5  5517.9   564.3    5539  563.73  5594.8  565.61  5606.3  565.28
#Mann= 4 ,-1 , 0
  4543.5     .05       0  4900.5     .12       0  5079.8     .07       0
  5083.8     .12       0
Bank Sta=5079.8,5083.8
XS Rating Curve= 0 ,0
Exp/Cntr=0.3,0.1

Type RM Length L Ch R = 1 ,100223  ,252,252,252
BEGIN DESCRIPTION:
Muddy Cedar Creek 123.0
END DESCRIPTION:
XS GIS Cut Line= 3
      2688989.65      6978161.72      2688616.43      6978020.67
      2688010.73       6978040.2
#Sta/Elev= 30
  4600.5  561.02  4703.7  559.05  4758.8  560.37  4828.9  559.51  4938.6  552.25
  4946.5   551.7    4954  550.28  4967.9  546.39  4984.2  547.96  4989.5  547.81
    4995  545.98  4995.3  545.48  4998.8  545.48    4999  545.98  5019.9  547.81
  5039.9   548.5    5100  549.09  5159.9  553.05  5164.9  552.15    5170  553.29
    5190  555.24    5220  556.37    5230  557.84  5304.6  559.54  5360.1  560.18
  5450.1  563.82  5480.2  563.57  5550.2  564.82  5570.2  565.39  5605.5  568.02
#Mann= 5 ,-1 , 0
  4600.5     .05       0  4938.6     .12       0    4995     .07       0
    4999     .12       0  5304.6     .05       0
Bank Sta=4995,4999
XS Rating Curve= 0 ,0
Exp/Cntr=0.3,0.1

Type RM Length L Ch R = 1 ,99971   ,108,108,108
BEGIN DESCRIPTION:
Muddy Cedar Creek 122.0
END DESCRIPTION:
XS GIS Cut Line= 3
      2689064.37      6978073.81      2688675.99        6977786.
      2688066.96      6977688.38
#Sta/Elev= 30
  4516.6  560.75  4681.7   559.4  4696.4  558.64  4702.6  557.52    4711  557.87
  4767.3  555.42  4811.2     555  4880.1  550.82  4917.6  548.07  4967.6  547.57
  4988.5  545.89  4996.9  546.76  5008.1  543.24  5008.4  542.74  5012.1  543.24
  5040.5  547.94  5050.6  546.56  5091.1  549.89  5151.9  550.21  5182.3  552.85
  5188.4  552.47  5273.4  556.47  5312.4  557.51  5317.5  557.01  5384.8  559.64
  5405.1  559.38  5503.4  562.49  5508.5  561.77  5587.3  564.78  5616.8  565.94
#Mann= 5 ,-1 , 0
  4516.6     .05       0  4880.1     .12       0  5008.1     .07       0
  5012.1     .12       0  5587.3     .05       0
Bank Sta=5008.1,5012.1
XS Rating Curve= 0 ,0
Exp/Cntr=0.3,0.1

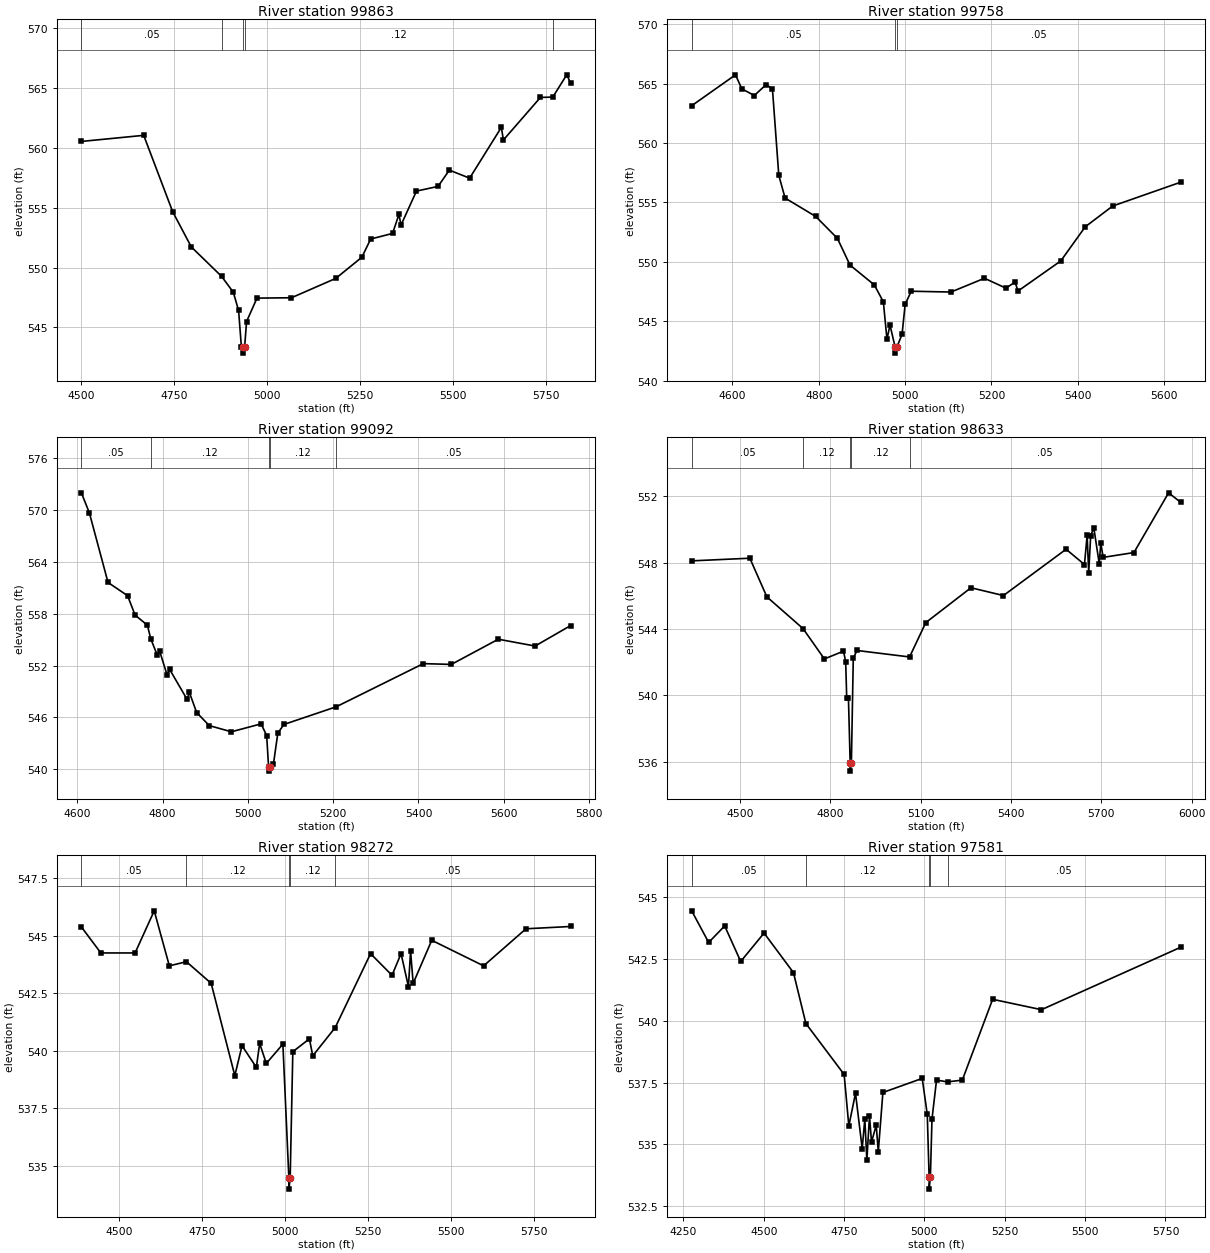
Type RM Length L Ch R = 1 ,99863   ,105,105,105
BEGIN DESCRIPTION:
Muddy Cedar Creek 121.0
END DESCRIPTION:
XS GIS Cut Line= 3
      2689095.76      6978027.63      2688595.79      6977577.67
      2688007.03      6977323.79
#Sta/Elev= 30
  4501.4  560.55  4668.8  561.06  4746.5  554.68  4796.6  551.73  4877.9  549.27
  4909.4  547.94  4923.6  546.42  4931.1  543.37  4935.8  543.35  4936.1  542.85
  4939.8  543.35    4945  545.49    4973  547.45  5065.6  547.48  5184.7   549.1
  5254.7  550.87  5278.3  552.39  5337.2  552.86  5354.3  554.46  5359.7  553.55
  5401.3   556.4  5459.2  556.79  5489.6  558.15  5544.1  557.48  5629.3  561.73
  5634.7  560.67  5734.2  564.23  5767.4  564.26  5804.8  566.12  5815.2  565.44
#Mann= 5 ,-1 , 0
  4501.4     .05       0  4877.9     .12       0  4935.8     .07       0
  4939.8     .12       0  5767.4     .05       0
Bank Sta=4935.8,4939.8
XS Rating Curve= 0 ,0
Exp/Cntr=0.3,0.1

Type RM Length L Ch R = 1 ,99758   ,666,666,666
BEGIN DESCRIPTION:
Muddy Cedar Creek 120.0
END DESCRIPTION:
XS GIS Cut Line= 3
       2689172.9       6977906.1      2688803.13      6977633.55
      2688327.46      6977156.14
#Sta/Elev= 30
  4505.6  563.14  4607.1  565.74  4621.8  564.56  4650.8     564  4678.1  564.92
  4692.7  564.55  4707.4  557.28    4722  555.37    4793  553.82  4843.1  551.98
  4872.4  549.73  4928.7  548.06  4949.6  546.64    4958  543.48    4965  544.69
  4976.9  542.82  4977.1  542.32  4980.9  542.82    4993  543.91  5000.1  546.42
  5014.2  547.53  5106.2  547.46  5183.9  548.62  5233.4  547.79  5254.6  548.29
  5261.7  547.55  5360.7  550.08  5417.3  552.95  5480.9   554.7  5638.9  556.71
#Mann= 3 ,-1 , 0
  4505.6     .05       0  4976.9     .03       0  4980.9     .05       0
Bank Sta=4976.9,4980.9
XS Rating Curve= 0 ,0
Exp/Cntr=0.3,0.1

Type RM Length L Ch R = 1 ,99092   ,459,459,459
BEGIN DESCRIPTION:
Muddy Cedar Creek 119.0
END DESCRIPTION:
XS GIS Cut Line= 3
      2688993.54      6977508.15      2688814.12      6977104.12
      2688131.99      6976924.35
#Sta/Elev= 30
  4609.3  572.02  4628.1  569.69  4671.8  561.63  4717.6   560.1  4735.4  557.84
  4764.1  556.68  4772.2  555.07  4787.4   553.2  4792.8  553.69  4810.6  550.86
  4816.1  551.57  4857.2  548.08  4862.6  548.89  4879.7  546.55  4909.2  545.04
  4961.1  544.32  5030.9  545.24  5043.9  543.88  5048.4  540.26  5048.6  539.76
  5052.4  540.26  5059.8  540.58  5070.1  544.17  5084.4  545.17  5207.1  547.22
  5411.4  552.22  5477.1  552.13  5587.2  555.05  5673.5  554.26  5756.8  556.63
#Mann= 5 ,-1 , 0
  4609.3     .05       0  4772.2     .12       0  5048.4     .07       0
  5052.4     .12       0  5207.1     .05       0
Bank Sta=5048.4,5052.4
XS Rating Curve= 0 ,0
Exp/Cntr=0.3,0.1

Type RM Length L Ch R = 1 ,98633   ,361,361,361
BEGIN DESCRIPTION:
Mapping XS ba1aa3e4
END DESCRIPTION:
XS GIS Cut Line= 3
      2689487.44      6977202.69      2689115.92      6976841.59
      2688046.46      6976556.87
#Sta/Elev= 30
  4339.6   548.1  4532.8  548.26  4589.4  545.93  4709.4  544.02  4780.3  542.19
  4843.8  542.66    4851  542.03  4854.5  539.86  4860.2  539.86    4866  535.93
  4866.2  535.43    4870  535.93  4876.3  542.24  4888.7   542.7  5063.3  542.31
  5117.1  544.38  5267.2  546.48    5375  546.01  5583.1   548.8  5644.1  547.88
    5653  549.64  5658.2  547.38  5664.8  549.62  5675.1   550.1  5693.2  547.93
  5698.3  549.18  5706.2  548.31  5808.4   548.6  5923.5   552.2  5964.4  551.62
#Mann= 5 ,-1 , 0
  4339.6     .05       0  4709.4     .12       0    4866     .07       0
    4870     .12       0  5063.3     .05       0
Bank Sta=4866,4870
XS Rating Curve= 0 ,0
Exp/Cntr=0.3,0.1

Type RM Length L Ch R = 1 ,98272   ,691,691,691
BEGIN DESCRIPTION:
Mapping XS 75e73030
END DESCRIPTION:
XS GIS Cut Line= 4
       2689647.2      6976740.91      2689195.78      6976487.43
      2688904.12       6976490.9       2688390.6       6976067.6
#Sta/Elev= 30
  4385.2  545.38  4443.9  544.25  4547.1  544.25  4604.8  546.08  4650.4  543.69
  4701.9  543.87  4776.5  542.93  4847.8  538.92  4869.5  540.22  4912.7  539.28
  4922.7  540.32  4942.7  539.45  4992.7  540.29  5010.7  534.49    5011  533.99
  5014.7  534.49  5022.7  539.96  5072.7  540.52  5082.7  539.78  5150.5  541.01
    5257  544.22  5321.7  543.28    5349  544.22  5371.2  542.79  5377.7  544.32
  5385.5  542.93  5441.5   544.8  5597.9  543.69  5725.6   545.3  5860.1   545.4
#Mann= 5 ,-1 , 0
  4385.2     .05       0  4701.9     .12       0  5010.7     .07       0
  5014.7     .12       0  5150.5     .05       0
Bank Sta=5010.7,5014.7
XS Rating Curve= 0 ,0
Exp/Cntr=0.3,0.1

Type RM Length L Ch R = 1 ,97581   ,529,529,529
BEGIN DESCRIPTION:
Mapping XS 25965999
END DESCRIPTION:
XS GIS Cut Line= 3
      2689720.12      6976431.91      2689275.64      6975852.01
      2688525.66      6975598.54
#Sta/Elev= 30
  4275.8  544.45  4328.7  543.17  4378.5  543.84  4428.4   542.4    4501  543.55
  4592.5  541.95  4631.2  539.89  4750.2  537.83  4764.8  535.75  4785.6  537.07
  4806.4  534.83  4814.6  536.03  4820.9  534.35  4829.1  536.15  4835.4  535.09
    4850  535.78  4856.5  534.71  4870.8   537.1  4993.2  537.67  5008.9  536.21
  5014.6  533.69  5014.9  533.19  5018.6  533.69  5023.6  536.03  5037.7   537.6
  5072.1  537.53  5117.9   537.6  5212.3  540.87  5364.2  540.45  5798.1  542.98
#Mann= 5 ,-1 , 0
  4275.8     .05       0  4631.2     .12       0  5014.6     .07       0
  5018.6     .12       0  5072.1     .05       0
Bank Sta=5014.6,5018.6
XS Rating Curve= 0 ,0
Exp/Cntr=0.3,0.1

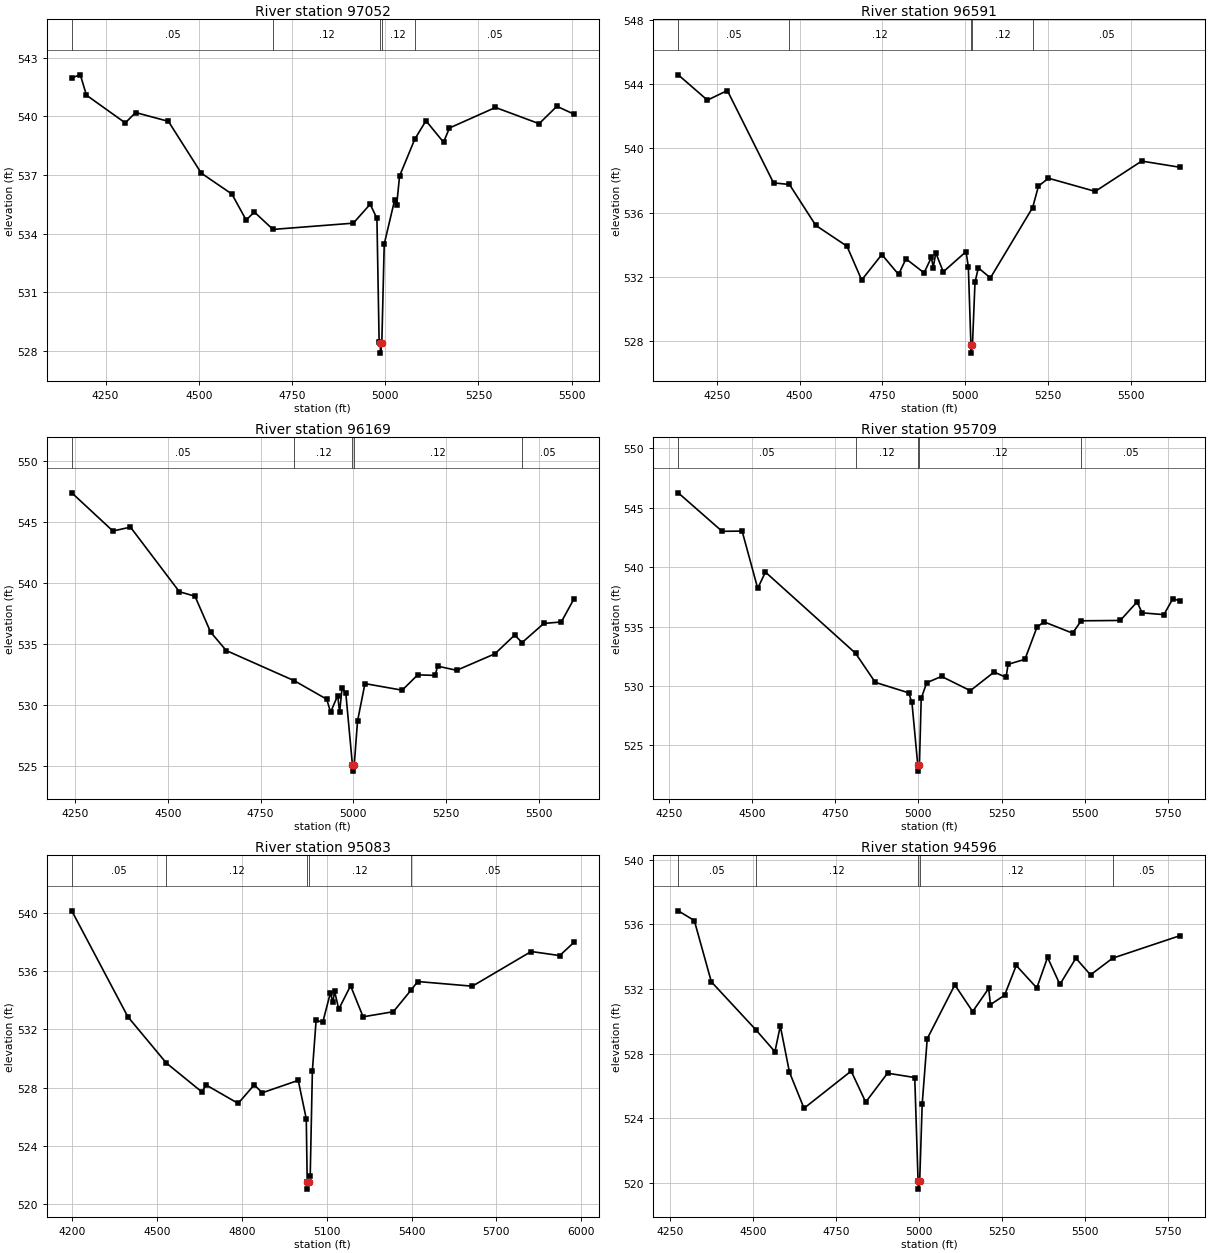
Type RM Length L Ch R = 1 ,97052   ,461,461,461
BEGIN DESCRIPTION:
Mapping XS 199ebf4b
END DESCRIPTION:
XS GIS Cut Line= 3
      2689911.08      6976157.61      2689529.12      6975438.82
      2689011.78      6975313.82
#Sta/Elev= 30
  4159.5  541.98  4182.5  542.13  4198.8  541.09  4302.9  539.67  4330.7   540.2
  4418.6  539.75  4506.7   537.1  4588.8  536.03  4627.1   534.7    4649  535.11
    4699  534.22  4914.4  534.54  4959.7  535.51  4977.7  534.78  4983.6  528.47
  4986.8  528.39    4987  527.89  4990.8  528.39  4997.3  533.47  5025.5  535.75
  5030.7  535.47  5038.4  536.95  5079.3  538.84  5109.2  539.78  5156.3  538.68
  5172.2  539.41  5295.6  540.46  5412.6  539.63  5460.2  540.52  5505.7  540.12
#Mann= 5 ,-1 , 0
  4159.5     .05       0    4699     .12       0  4986.8     .07       0
  4990.8     .12       0  5079.3     .05       0
Bank Sta=4986.8,4990.8
XS Rating Curve= 0 ,0
Exp/Cntr=0.3,0.1

Type RM Length L Ch R = 1 ,96591   ,422,422,422
BEGIN DESCRIPTION:
Mapping XS e7271b6b
END DESCRIPTION:
XS GIS Cut Line= 3
       2690497.9      6975477.03      2689740.92      6975088.12
      2689081.25      6975001.32
#Sta/Elev= 30
  4133.7  544.59  4221.8  543.01    4282  543.61  4421.5  537.85  4469.6  537.75
    4549   535.2  4643.3   533.9  4687.7  531.79  4748.6  533.38  4799.1  532.14
  4821.6  533.11  4876.1  532.24  4898.3   533.2  4903.9  532.57  4911.6  533.49
  4934.1   532.3  5002.9  533.56  5009.9  532.61  5017.7  527.73  5018.1  527.23
  5022.3  527.73    5030  531.65  5040.1  532.55  5076.5  531.92  5204.1  536.31
  5221.7  537.65  5251.9  538.14  5393.1  537.32  5533.5  539.21  5650.1  538.82
#Mann= 5 ,-1 , 0
  4133.7     .05       0  4469.6     .12       0  5017.7     .07       0
  5022.3     .12       0  5204.1     .05       0
Bank Sta=5017.7,5022.3
XS Rating Curve= 0 ,0
Exp/Cntr=0.3,0.1

Type RM Length L Ch R = 1 ,96169   ,460,460,460
BEGIN DESCRIPTION:
Mapping XS 69bdef00
END DESCRIPTION:
XS GIS Cut Line= 3
      2690563.84      6974872.85      2689820.78      6974695.76
       2689249.4      6974834.28
#Sta/Elev= 30
  4241.7  547.38  4352.5  544.25  4399.7  544.57  4531.3  539.28  4573.4  538.91
  4615.5  535.97  4657.6  534.46  4841.2  531.98  4928.2  530.47  4938.5  529.41
  4957.7  530.77  4962.8  529.39  4969.4  531.38  4979.6  530.94  4997.4  525.08
    4998  524.58  5002.2  525.08  5011.1  528.68  5031.1  531.75  5131.4  531.21
  5173.2  532.47  5220.1  532.42  5226.6  533.18    5278  532.84  5380.9  534.19
  5434.3  535.73  5454.1  535.11  5512.7  536.68  5559.7   536.8  5593.5  538.67
#Mann= 5 ,-1 , 0
  4241.7     .05       0  4841.2     .12       0  4997.4     .07       0
  5002.2     .12       0  5454.1     .05       0
Bank Sta=4997.4,5002.2
XS Rating Curve= 0 ,0
Exp/Cntr=0.3,0.1

Type RM Length L Ch R = 1 ,95709   ,626,626,626
BEGIN DESCRIPTION:
Mapping XS ade47794
END DESCRIPTION:
XS GIS Cut Line= 3
      2690497.82      6974348.54      2689765.23      6974310.34
      2689126.33      6974751.32
#Sta/Elev= 30
  4277.7  546.25  4409.7  543.01  4469.8  543.03  4516.7  538.21  4539.9  539.58
  4810.9  532.75  4870.3   530.3  4970.5  529.42  4980.5  528.61  4998.1  523.33
  4998.7  522.83    5003  523.33  5008.4  528.95  5024.9  530.27  5069.5   530.8
  5156.1   529.6  5227.7  531.17  5263.6  530.72  5269.7  531.82  5320.4  532.24
  5356.2  534.92  5377.1   535.4  5463.7  534.44  5489.4  535.48    5607  535.51
  5657.7  537.07  5672.6  536.15  5738.2     536  5765.2  537.34  5787.6  537.14
#Mann= 5 ,-1 , 0
  4277.7     .05       0  4810.9     .12       0  4998.1     .07       0
    5003     .12       0  5489.4     .05       0
Bank Sta=4998.1,5003
XS Rating Curve= 0 ,0
Exp/Cntr=0.3,0.1

Type RM Length L Ch R = 1 ,95083   ,487,487,487
BEGIN DESCRIPTION:
Mapping XS 96c5be6c
END DESCRIPTION:
XS GIS Cut Line= 3
      2689990.96      6973445.73      2689362.45      6974001.32
       2688820.9      6974765.03
#Sta/Elev= 30
  4198.8  540.14  4397.2  532.87  4533.2   529.7  4659.2  527.71  4673.2   528.2
    4787  526.93  4843.9   528.2  4872.4  527.66  4999.5  528.51  5027.9  525.87
  5031.2  521.55  5031.8  521.05  5036.1  521.55  5041.8  521.93  5049.5  529.18
  5062.7  532.64  5086.1  532.49  5113.1  534.51  5121.8  533.86  5127.9  534.64
  5142.7  533.39  5184.5     535  5228.8  532.87  5335.8  533.22  5397.8  534.69
    5422  535.29  5615.1  534.97  5823.1  537.35    5924  537.07  5973.9  537.97
#Mann= 5 ,-1 , 0
  4198.8     .05       0  4533.2     .12       0  5031.2     .07       0
  5036.1     .12       0  5397.8     .05       0
Bank Sta=5031.2,5036.1
XS Rating Curve= 0 ,0
Exp/Cntr=0.3,0.1

Type RM Length L Ch R = 1 ,94596   ,604,604,604
BEGIN DESCRIPTION:
Mapping XS 1a4fc9b8
END DESCRIPTION:
XS GIS Cut Line= 3
      2689768.66       6973268.7      2689129.81      6973612.43
      2688834.66      6974341.61
#Sta/Elev= 30
  4275.1  536.83  4323.5  536.23  4374.8  532.44  4508.1  529.49  4566.3  528.12
  4582.5  529.71  4610.1  526.85  4653.9  524.62  4795.9  526.92  4839.7     525
  4905.5  526.79  4987.4  526.52  4997.4  520.12    4998  519.62  5002.3  520.12
  5009.8  524.87    5025  528.92  5108.1  532.25  5161.8   530.6    5210  532.03
  5215.4  531.03  5257.9  531.61  5293.1  533.45    5355  532.06  5387.4  533.95
  5424.5  532.28  5472.7   533.9  5516.8  532.87  5583.2   533.9  5787.2   535.3
#Mann= 5 ,-1 , 0
  4275.1     .05       0  4508.1     .12       0  4997.4     .07       0
  5002.3     .12       0  5583.2     .05       0
Bank Sta=4997.4,5002.3
XS Rating Curve= 0 ,0
Exp/Cntr=0.3,0.1

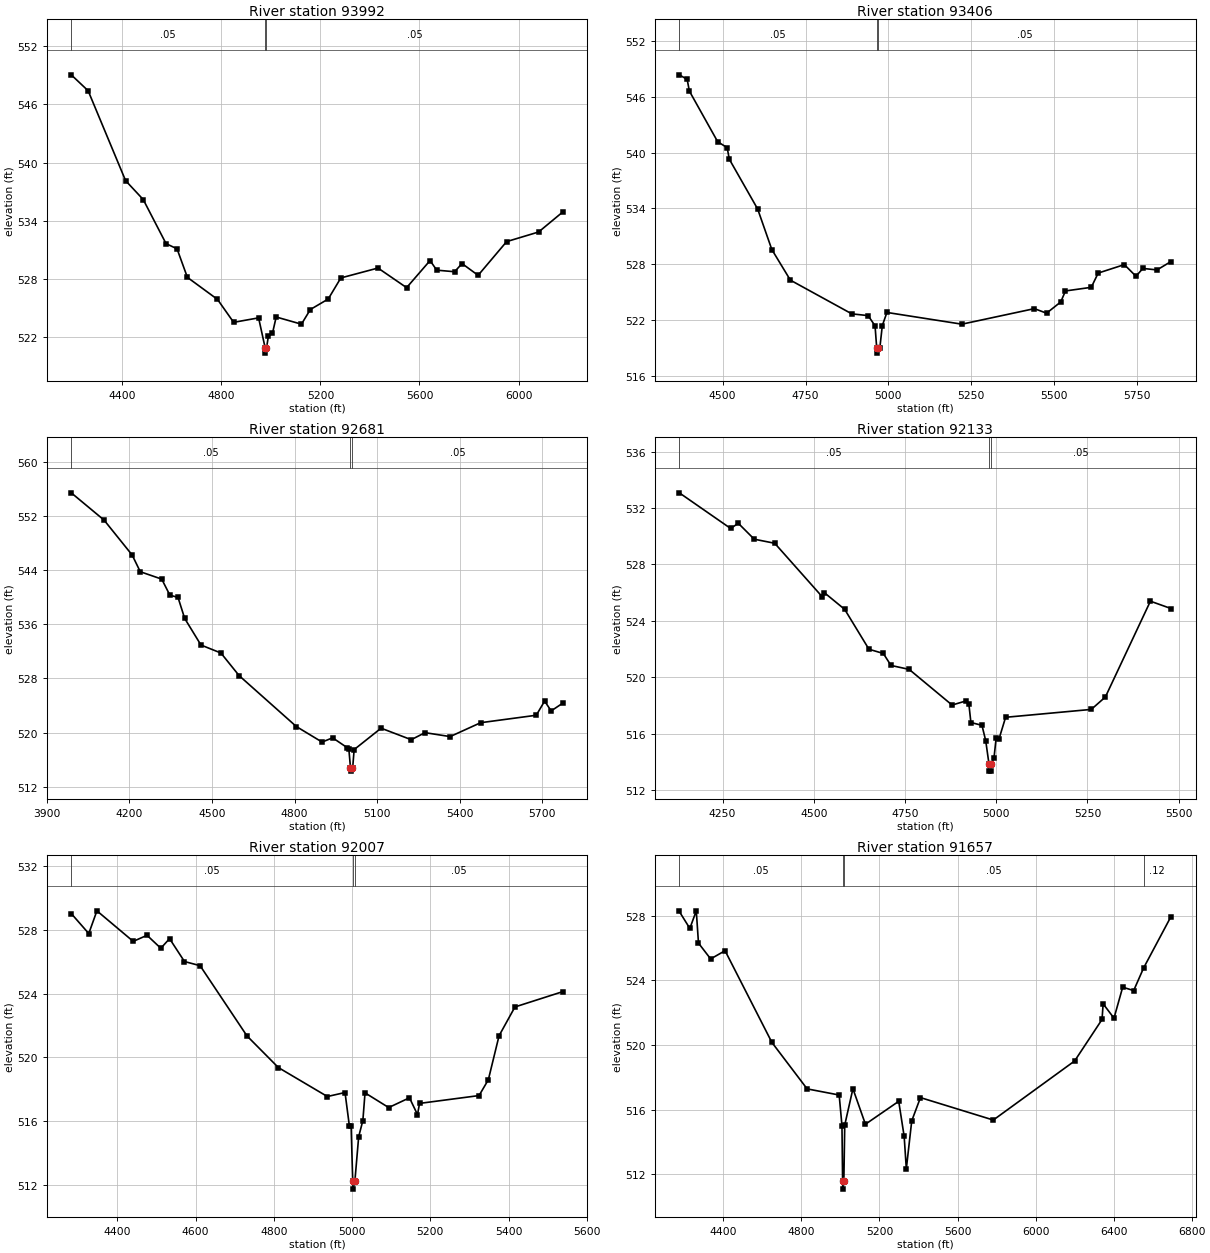
Type RM Length L Ch R = 1 ,93992   ,586,586,586
BEGIN DESCRIPTION:
Mapping XS 3d9a8edd
END DESCRIPTION:
XS GIS Cut Line= 3
      2689565.77       6972725.8      2688914.75      6973190.19
      2688255.03      6974175.44
#Sta/Elev= 30
  4193.7  549.04  4261.9   547.4  4413.1  538.15  4484.4   536.2  4576.6  531.66
  4620.9  531.13  4662.7  528.19  4784.3  525.92  4849.5  523.56  4950.3  524.02
  4977.1  520.89  4977.7  520.39  4982.1  520.89  4989.8  522.13  5006.4  522.44
  5021.3  524.11  5123.3  523.37  5159.3  524.88  5231.4  525.96  5282.4  528.13
  5432.5  529.15    5548  527.13  5642.7  529.92  5669.7  528.93  5741.8  528.77
  5771.8  529.61  5836.8   528.4  5951.9  531.87    6081  532.86  6179.1  534.93
#Mann= 3 ,-1 , 0
  4193.7     .05       0  4977.1     .04       0  4982.1     .05       0
Bank Sta=4977.1,4982.1
XS Rating Curve= 0 ,0
Exp/Cntr=0.3,0.1

Type RM Length L Ch R = 1 ,93406   ,725,725,725
BEGIN DESCRIPTION:
Mapping XS d59ef5c0
END DESCRIPTION:
XS GIS Cut Line= 3
      2688948.58      6972440.21      2688469.44      6972856.86
      2687912.78      6973496.75
#Sta/Elev= 30
  4369.2  548.36  4392.9  547.87  4399.5  546.62    4485  541.17  4513.5  540.54
  4520.1  539.29  4605.6  533.94  4648.3  529.59  4704.3   526.3  4889.5  522.68
  4938.9  522.49  4959.7  521.39  4964.8  518.96  4965.5  518.46    4970  518.96
    4974  518.98  4981.6  521.42  4995.5  522.83  5221.7  521.57  5440.4  523.24
  5477.1  522.75  5519.9  523.96  5534.1  525.14    5612  525.53  5632.8  527.06
  5711.7  527.97  5746.8  526.72  5767.7  527.56  5810.4   527.4  5852.3   528.3
#Mann= 3 ,-1 , 0
  4369.2     .05       0  4964.8     .04       0    4970     .05       0
Bank Sta=4964.8,4970
XS Rating Curve= 0 ,0
Exp/Cntr=0.3,0.1

Type RM Length L Ch R = 1 ,92681   ,548,548,548
BEGIN DESCRIPTION:
Mapping XS e2719a48
END DESCRIPTION:
XS GIS Cut Line= 3
      2688872.56      6972092.02      2687924.65      6972472.22
      2687659.01      6973190.99
#Sta/Elev= 30
  3988.2   555.4  4107.4  551.38  4209.6  546.22  4239.2  543.75  4317.2  542.66
  4346.8  540.29  4376.4  539.96  4400.6  536.86  4459.8  532.93  4532.4  531.75
  4598.6  528.41  4806.8  520.89  4900.3   518.6  4938.6  519.23  4992.4  517.75
  4997.7  517.51  5003.5  514.81  5004.2  514.31  5008.7  514.81  5011.5  514.81
  5016.8  517.49  5114.8  520.65  5224.4  518.95  5274.5  519.99  5365.8  519.41
  5476.8  521.46    5679  522.56  5709.4  524.65  5733.2   523.2  5775.8  524.36
#Mann= 3 ,-1 , 0
  3988.2     .05       0  5003.5     .04       0  5008.7     .05       0
Bank Sta=5003.5,5008.7
XS Rating Curve= 0 ,0
Exp/Cntr=0.3,0.1

Type RM Length L Ch R = 1 ,92133   ,126,126,126
BEGIN DESCRIPTION:
Mapping XS 5d878f45
END DESCRIPTION:
XS GIS Cut Line= 6
      2688174.34      6971581.86      2687931.03      6971766.05
       2687727.5      6971839.45      2687619.61      6971953.93
      2687428.06      6972474.39      2687421.21      6972587.22
#Sta/Elev= 30
  4131.4  533.08  4272.2  530.55    4293  530.92  4336.7  529.79  4392.9   529.5
  4523.2   525.7  4528.6     526  4584.6  524.81  4651.1  521.98  4690.5  521.68
  4711.5  520.83  4761.3  520.55  4878.9  518.02  4916.9  518.31    4925  518.07
  4930.5  516.78  4960.8  516.58  4971.1  515.49  4980.1  513.83  4980.9  513.33
  4984.8  513.33  4985.6  513.83  4993.8  514.27  4999.6  515.66  5007.6  515.62
  5025.6  517.15  5260.4  517.71    5299  518.59  5422.4  525.39  5478.7  524.87
#Mann= 3 ,-1 , 0
  4131.4     .05       0  4980.1     .03       0  4985.6     .05       0
Bank Sta=4980.1,4985.6
XS Rating Curve= 0 ,0
Exp/Cntr=0.3,0.1

Type RM Length L Ch R = 1 ,92007   ,350,350,350
BEGIN DESCRIPTION:
Mapping XS b84d89d1
END DESCRIPTION:
XS GIS Cut Line= 6
      2687954.38       6971506.8      2687614.59      6971784.98
      2687475.41      6972023.46      2687363.02      6972340.46
      2687345.41      6972441.37      2687354.12      6972542.84
#Sta/Elev= 30
  4282.4     529  4327.2  527.75    4348  529.17  4440.8  527.26  4476.1  527.64
  4511.3  526.83  4533.7  527.43  4571.8     526  4611.7  525.74  4731.5  521.35
  4811.8  519.37    4937  517.56  4982.1  517.81  4993.4  515.69  4997.7  515.69
  5001.8  512.27  5002.6  511.77  5007.3  512.27    5017  515.05  5027.7  516.06
  5033.2  517.79  5093.7  516.87  5146.8  517.48  5167.3  516.43  5172.6  517.13
  5324.7  517.62  5348.4  518.61  5375.8  521.36  5416.4  523.16  5538.9  524.12
#Mann= 3 ,-1 , 0
  4282.4     .05       0  5001.8     .04       0  5007.3     .05       0
Bank Sta=5001.8,5007.3
XS Rating Curve= 0 ,0
Exp/Cntr=0.3,0.1

Type RM Length L Ch R = 1 ,91657   ,486,486,486
BEGIN DESCRIPTION:
Mapping XS d0cb205c
END DESCRIPTION:
XS GIS Cut Line= 5
      2687934.81      6971466.53      2687222.08      6971803.94
      2687140.95      6971899.12      2687006.18      6972038.12
      2685745.49      6972675.09
#Sta/Elev= 30
  4174.1  528.27  4228.1  527.22  4261.1  528.31  4272.4  526.31  4334.8  525.33
  4408.6  525.84  4648.5  520.16  4829.2  517.28  4993.4   516.9  5007.7  515.01
  5011.1  511.57  5012.1  511.07  5017.4  511.57    5022  515.04  5063.9  517.29
    5128  515.09  5298.6  516.51  5326.5  514.34  5337.6  512.33  5365.4   515.3
    5410  516.74  5783.4  515.35  6200.3  519.01  6340.7  521.58  6346.3  522.55
  6401.9  521.66  6446.5  523.58  6502.8  523.37  6553.7  524.77  6693.8  527.95
#Mann= 4 ,-1 , 0
  4174.1     .05       0  5011.1     .04       0  5017.4     .05       0
  6553.7     .12       0
Bank Sta=5011.1,5017.4
XS Rating Curve= 0 ,0
Exp/Cntr=0.3,0.1

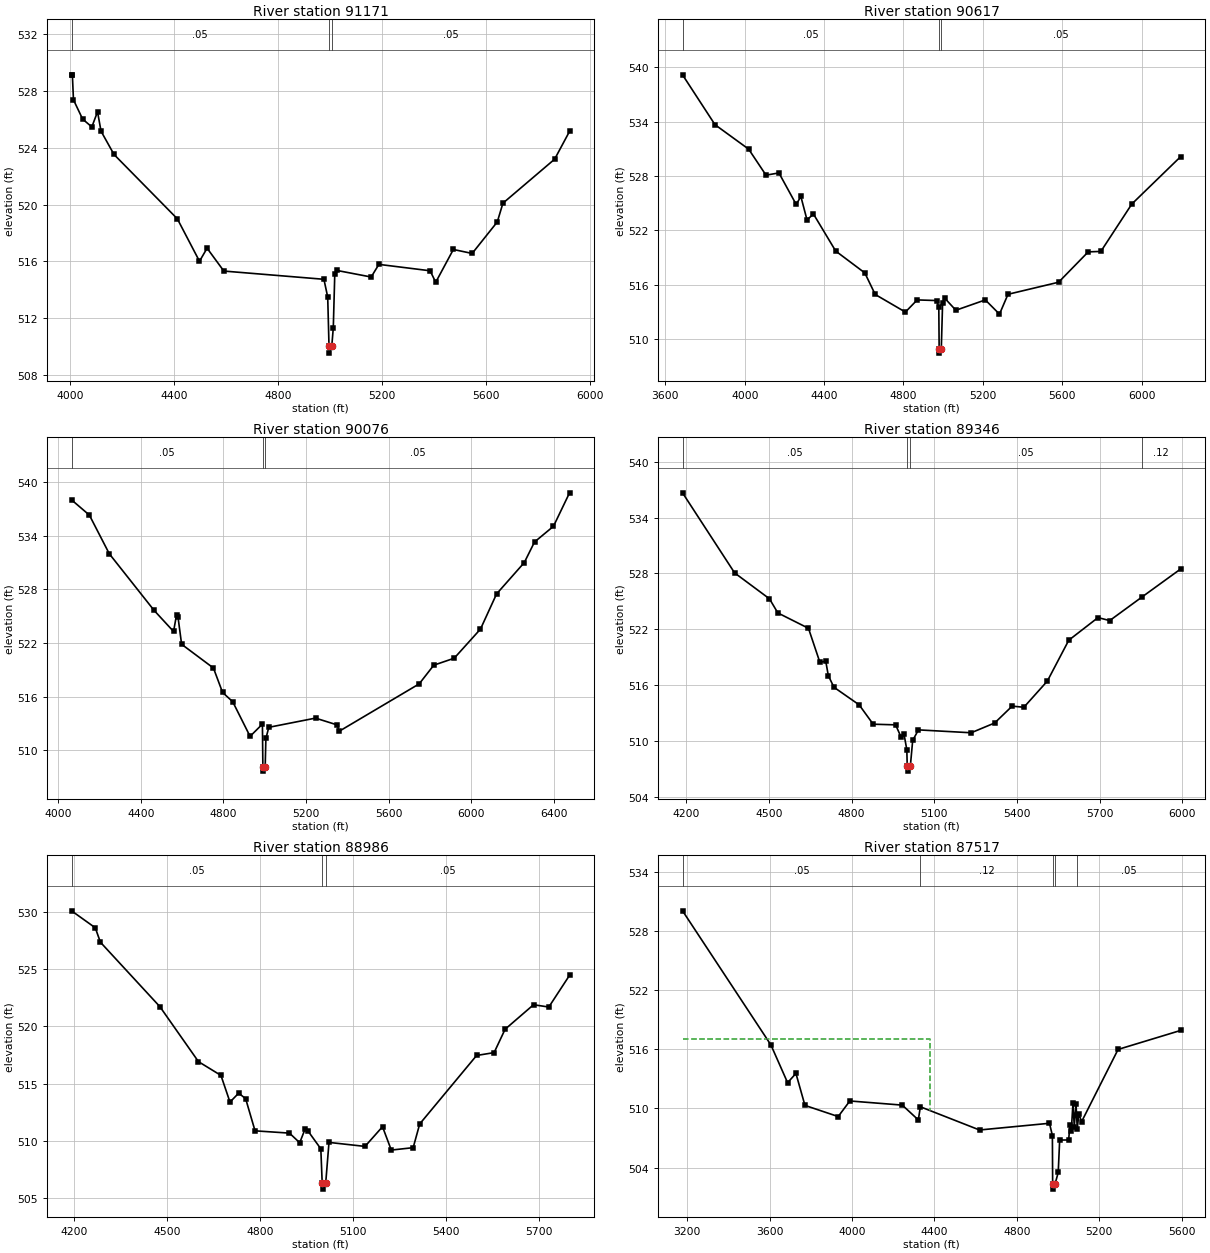
Type RM Length L Ch R = 1 ,91171   ,554,554,554
BEGIN DESCRIPTION:
Muddy Cedar Creek 107.0
END DESCRIPTION:
XS GIS Cut Line= 3
        2687576.        6971061.        2686776.        6971661.
      2685975.98      6972111.01
#Sta/Elev= 30
  4004.5  529.14  4007.6  529.14  4011.8  527.38  4047.2  526.02  4082.6  525.47
  4104.5  526.54    4118  525.17    4168  523.53  4411.8     519  4497.2  516.01
  4526.4  516.93    4591  515.32  4976.4  514.74    4991  513.49    4996  510.04
  4997.5  509.54  5006.7  510.04  5012.5  511.32  5018.2   515.1  5027.4  515.36
  5158.4   514.9  5188.1  515.79  5385.4  515.34    5407  514.53  5474.9  516.84
  5547.3  516.56  5644.1  518.78  5665.8   520.1    5865   523.2  5922.4  525.16
#Mann= 3 ,-1 , 0
  4004.5     .05       0    4996     .04       0  5006.7     .05       0
Bank Sta=4996,5006.7
XS Rating Curve= 0 ,0
Exp/Cntr=0.3,0.1

Type RM Length L Ch R = 1 ,90617   ,541,541,541
BEGIN DESCRIPTION:
Muddy Cedar Creek 106.0
END DESCRIPTION:
XS GIS Cut Line= 3
      2687832.08       6970661.6      2686625.72      6971181.18
      2685712.31      6971953.26
#Sta/Elev= 30
  3686.5  539.15  3850.1  533.65  4019.8  530.95  4107.2  528.08  4172.2  528.33
  4259.3  524.85  4282.8  525.73  4313.7  523.15  4346.4  523.79  4458.4  519.71
    4605   517.3  4657.5  514.92  4809.5  512.98    4869  514.32    4967  514.25
  4977.9  513.53  4979.7  508.95  4981.2  508.45  4990.5  508.95  4997.1     514
  5006.8  514.53    5064  513.18  5212.3  514.32  5283.7  512.75  5326.6  514.94
  5581.5  516.27  5730.9  519.62  5794.6  519.67  5950.7   524.9    6196  530.11
#Mann= 3 ,-1 , 0
  3686.5     .05       0  4979.7     .03       0  4990.5     .05       0
Bank Sta=4979.7,4990.5
XS Rating Curve= 0 ,0
Exp/Cntr=0.3,0.1

Type RM Length L Ch R = 1 ,90076   ,730,730,730
BEGIN DESCRIPTION:
Muddy Cedar Creek 105.0
END DESCRIPTION:
XS GIS Cut Line= 3
      2687396.32      6970332.09       2686524.3      6970671.67
        2685476.        6971711.
#Sta/Elev= 30
  4064.2  538.01  4150.4  536.31    4247  531.98  4463.9  525.65  4558.2  523.29
  4572.7  525.16  4579.7  524.92  4597.2  521.86  4751.4   519.2  4795.6  516.47
  4844.6  515.44  4928.8  511.56  4988.6  512.93  4990.8  508.17  4992.4  507.67
    5002  508.17  5005.4  511.32  5019.5  512.57  5245.8   513.6  5351.9  512.83
    5359  512.11  5747.9  517.43  5818.6  519.52  5917.6   520.3  6044.8  523.56
  6122.7  527.49    6257     531  6306.5   533.3  6398.4  535.06  6476.2   538.8
#Mann= 3 ,-1 , 0
  4064.2     .05       0  4990.8     .03       0    5002     .05       0
Bank Sta=4990.8,5002
XS Rating Curve= 0 ,0
Exp/Cntr=0.3,0.1

Type RM Length L Ch R = 1 ,89346   ,360,360,360
BEGIN DESCRIPTION:
Muddy Cedar Creek 103.0
END DESCRIPTION:
XS GIS Cut Line= 3
      2687075.97      6970061.01        2686276.        6970211.
      2685609.15      6970947.03
#Sta/Elev= 30
  4186.4  536.66  4375.4  528.06  4501.8  525.28  4532.3  523.76  4643.4  522.11
  4684.9  518.45  4706.1  518.58  4715.4  517.03  4735.8  515.78  4827.3  513.89
  4878.2  511.81  4959.6  511.74    4980  510.39  4990.1  510.74  5000.3  509.07
  5001.8  507.27  5003.4  506.77    5013  507.27  5021.6  510.07  5042.5   511.2
  5233.8  510.89    5319  511.94  5382.5  513.75  5425.1  513.63  5510.2  516.44
    5588  520.83  5694.1  523.26  5736.6  522.94  5852.7  525.45  5993.5  528.47
#Mann= 4 ,-1 , 0
  4186.4     .05       0  5001.8     .03       0    5013     .05       0
  5852.7     .12       0
Bank Sta=5001.8,5013
XS Rating Curve= 0 ,0
Exp/Cntr=0.3,0.1

Type RM Length L Ch R = 1 ,88986   ,1469,1469,1469
BEGIN DESCRIPTION:
Muddy Cedar Creek 102.0
END DESCRIPTION:
XS GIS Cut Line= 3
      2686921.68      6970040.77       2686098.7      6969910.68
      2685560.19      6970469.83
#Sta/Elev= 30
  4190.8  530.08  4267.4   528.6    4284  527.34  4476.3  521.71    4601  516.91
  4673.6  515.71  4702.8  513.38  4730.9  514.16  4753.4  513.68  4783.8  510.87
  4895.1  510.67  4928.2  509.83  4945.7  511.04  4955.9  510.82  4996.4   509.3
  5000.9  506.28  5002.4  505.78  5012.1  506.28  5022.8  509.86  5139.2  509.51
  5195.8  511.23  5224.1  509.19  5294.9   509.4    5316  511.47  5499.9  517.45
  5556.5   517.7    5592  519.74  5683.9  521.88  5733.3  521.68  5800.3  524.45
#Mann= 3 ,-1 , 0
  4190.8     .05       0  5000.9     .03       0  5012.1     .05       0
Bank Sta=5000.9,5012.1
XS Rating Curve= 0 ,0
Exp/Cntr=0.3,0.1

Type RM Length L Ch R = 1 ,87517   ,134,134,134
BEGIN DESCRIPTION:
Mapping XS 00ddf01c
END DESCRIPTION:
XS GIS Cut Line= 6
       2686890.4      6970002.57       2686279.3       6969912.3
      2685428.61      6969044.24      2685348.75      6968985.21
      2685213.33       6968936.6      2684873.02      6968943.55
#Sta/Elev= 30
  3177.9  530.02  3606.9  516.43  3687.8  512.61  3728.2  513.55    3772  510.31
  3933.3  509.18  3989.8  510.76  4244.4  510.34  4322.2  508.84  4332.1  510.17
  4619.2  507.82  4958.7   508.5  4972.8  507.26  4974.1  502.33  4975.7  501.83
  4985.5  502.33  5001.1  503.52  5008.1   506.8  5051.6  506.81  5058.2  508.35
  5064.4   507.7  5072.8  510.58    5079  508.15  5087.4  510.47  5090.3   509.3
  5093.6  507.96  5101.3  509.48  5114.5  508.66  5291.6  515.98  5594.6   517.9
#Mann= 5 ,-1 , 0
  3177.9     .05       0  4332.1     .12       0  4974.1     .07       0
  4985.5     .12       0  5090.3     .05       0
#XS Ineff= 2 , 0
       0    4378     517               0
Permanent Ineff=
       F       F
Bank Sta=4974.1,4985.5
XS Rating Curve= 0 ,0
Exp/Cntr=0.3,0.1