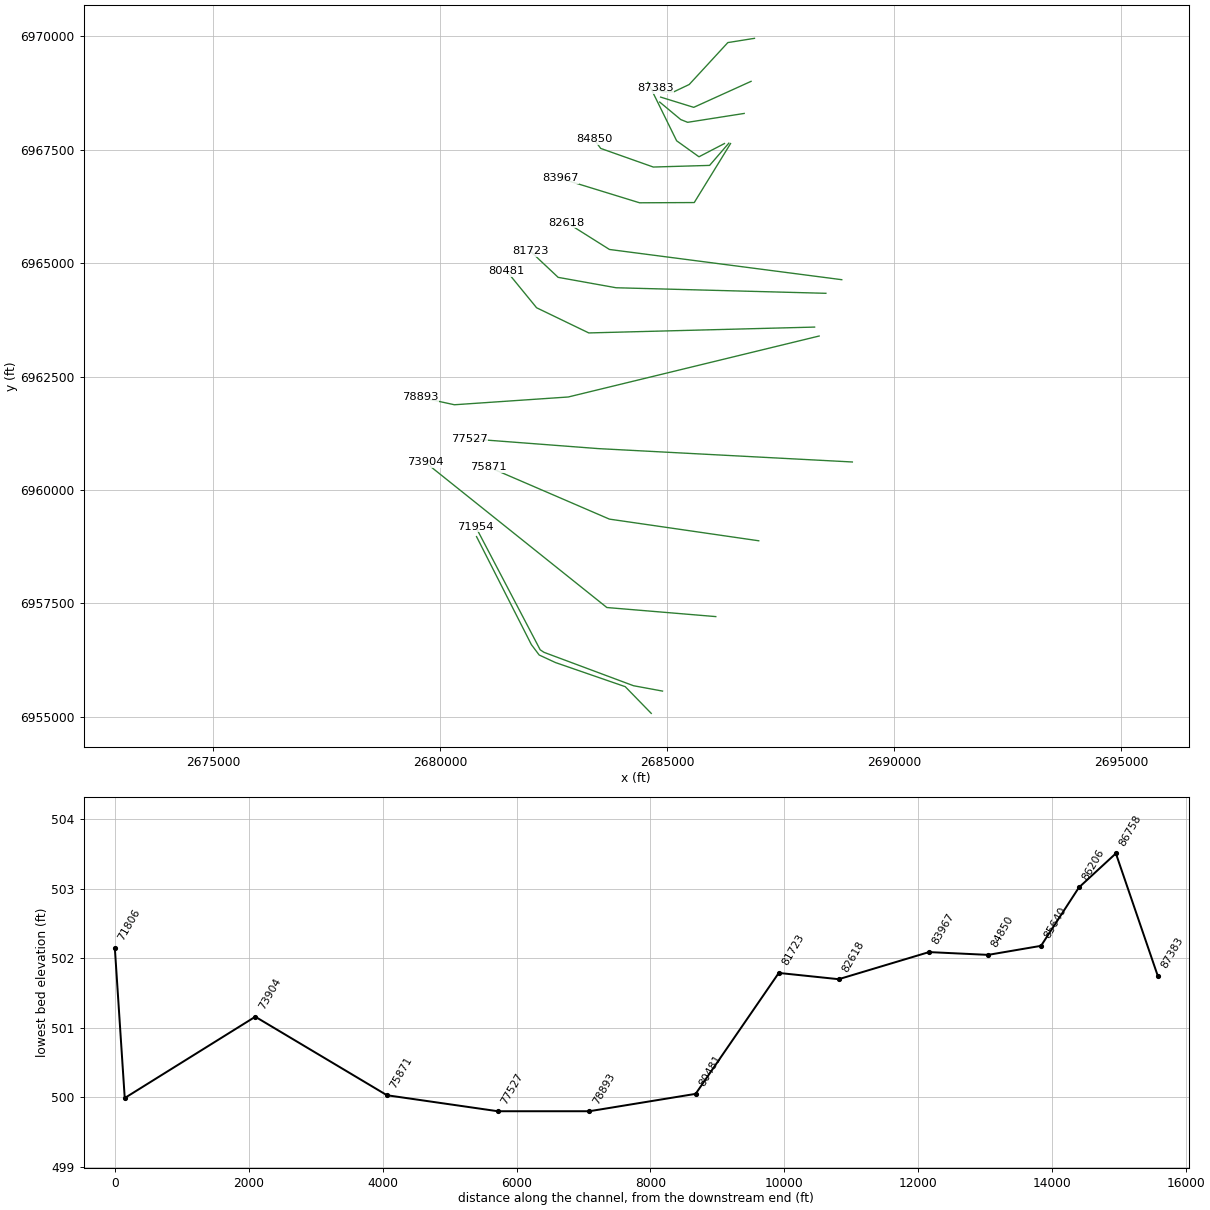
HEC-RAS study Muddy Cedar Creek.prj: Muddy Cedar Creek Base Level Engineering

--- Muddy Cedar Creek.g01 (geometry) --- (continued)

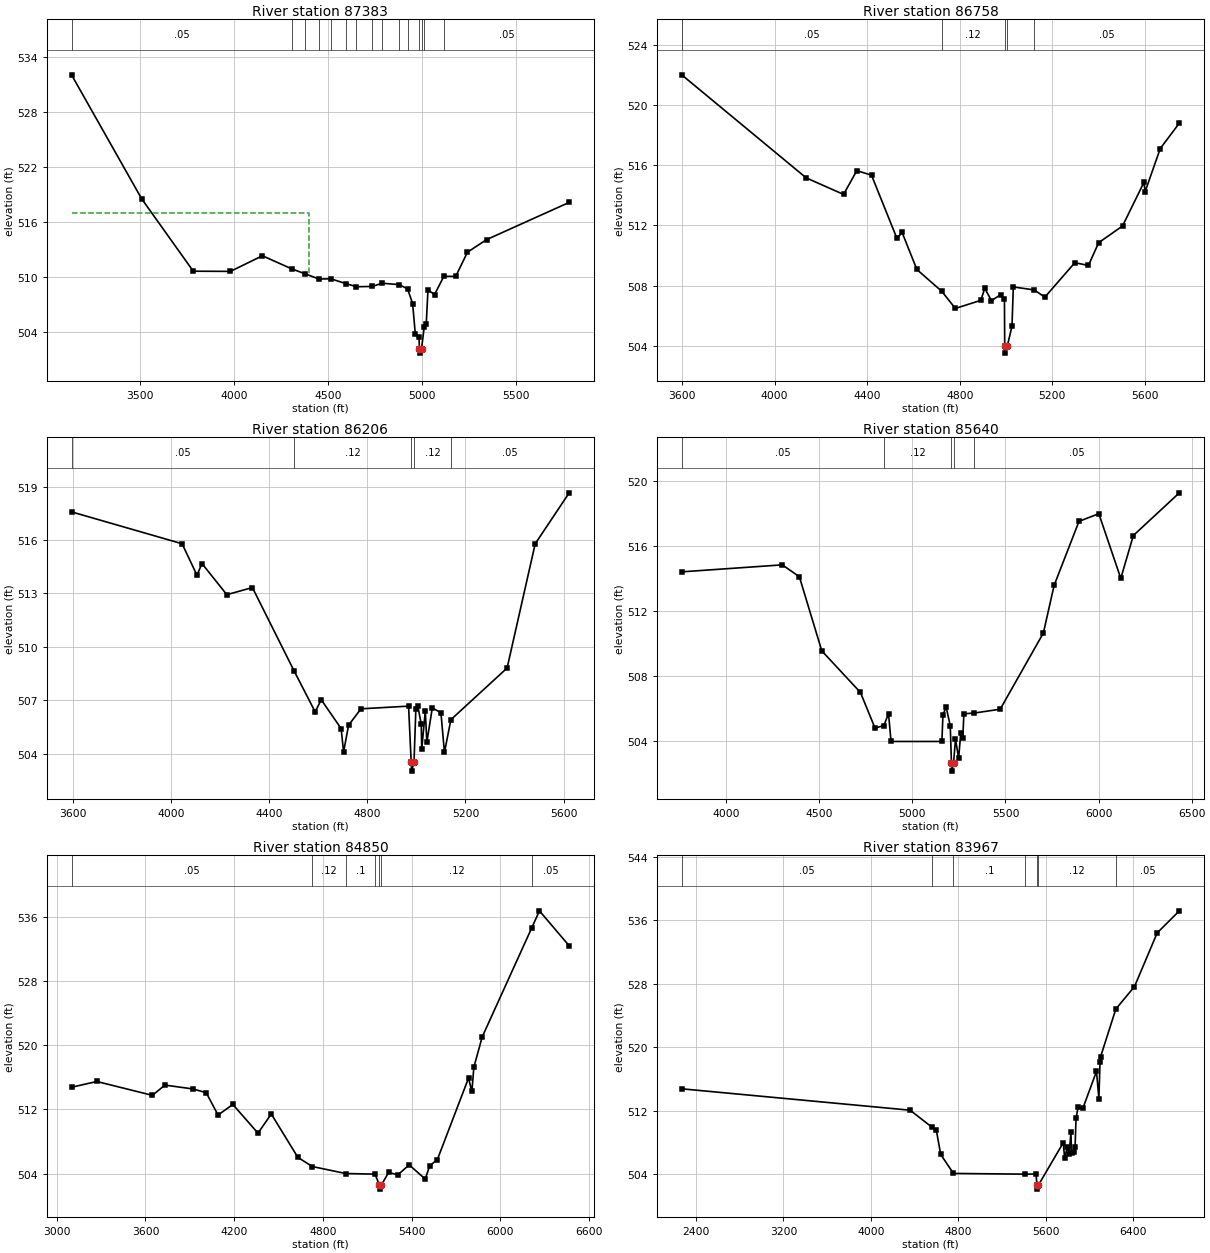
Type RM Length L Ch R = 1 ,87383   ,625,625,625
BEGIN DESCRIPTION:
Mapping XS 5ab3fbf6
END DESCRIPTION:
XS GIS Cut Line= 6
       2686927.7      6969955.17      2686340.94      6969861.43
      2685490.24      6968937.82      2685146.49      6968774.62
      2684906.91       6968778.1      2684747.18      6968857.96
#Sta/Elev= 30
  3134.8  532.05    3508  518.55  3782.6  510.67  3980.5  510.65  4150.6  512.35
  4308.3  510.91    4379  510.38  4450.8  509.82  4515.1  509.84  4593.2  509.33
  4651.1  508.98  4735.7  509.01  4787.2  509.36  4878.1  509.21  4923.2  508.75
  4950.2  507.13  4964.4  503.81  4984.1   503.5  4986.2  502.25  4987.8  501.75
  4997.6  502.25    5012  504.63  5022.6  504.96  5031.8  508.63  5066.9  508.13
  5116.4  510.12  5179.3   510.1  5241.9  512.74  5343.9  514.11  5783.4  518.16
#Mann= 15 ,-1 , 0
  3134.8     .05       0  4308.3     .12       0    4379     .05       0
  4450.8     .12       0  4515.1     .05       0  4593.2     .12       0
  4651.1     .05       0  4735.7     .12       0  4787.2     .05       0
  4878.1     .12       0  4923.2     .05       0  4986.2     .03       0
  4997.6     .05       0    5012     .12       0  5116.4     .05       0
#XS Ineff= 2 , 0
       0  4397.9     517               0
Permanent Ineff=
       F       F
Bank Sta=4986.2,4997.6
XS Rating Curve= 0 ,0
Exp/Cntr=0.3,0.1

Type RM Length L Ch R = 1 ,86758   ,552,552,552
BEGIN DESCRIPTION:
Mapping XS b05fe88d
END DESCRIPTION:
XS GIS Cut Line= 3
      2686852.79      6969007.28      2685589.72      6968434.35
      2684860.78      6968659.97
#Sta/Elev= 30
  3598.9  522.01  4136.7  515.16  4298.1  514.06  4355.5  515.64  4418.9  515.34
  4528.7  511.14  4551.1  511.53  4614.9  509.07  4722.4  507.62  4781.3  506.48
  4891.1  507.02  4908.4  507.82    4937     507  4977.6   507.4  4993.2  507.08
  4994.4  504.01    4996  503.51  5005.9  504.01  5025.8  505.29  5031.6  507.91
  5122.2  507.71  5167.7  507.23  5297.2  509.52  5356.1  509.34  5400.2  510.85
  5503.3  511.96  5595.9  514.86  5601.2  514.25  5666.4  517.11  5748.9   518.8
#Mann= 5 ,-1 , 0
  3598.9     .05       0  4722.4     .12       0  4994.4     .07       0
  5005.9     .12       0  5122.2     .05       0
Bank Sta=4994.4,5005.9
XS Rating Curve= 0 ,0
Exp/Cntr=0.3,0.1

Type RM Length L Ch R = 1 ,86206   ,566,566,566
BEGIN DESCRIPTION:
Mapping XS 1b77e6b5
END DESCRIPTION:
XS GIS Cut Line= 4
      2686700.83       6968299.8      2685455.17      6968104.48
      2685303.26      6968165.25      2684839.89      6968550.67
#Sta/Elev= 30
  3595.5  517.58  4045.8  515.79  4106.5  514.02  4126.7  514.68    4228  512.93
  4332.2  513.33  4501.6  508.66  4587.8  506.35  4612.6  507.03  4693.6  505.41
  4703.7   504.1    4724   505.6  4774.6  506.52  4968.4  506.67    4979  503.52
  4980.6  503.02  4990.5  503.52    4998  506.49  5006.3  506.65    5020  505.66
    5022  504.25  5036.4  506.38  5042.9  504.65    5065  506.57  5100.2   506.3
  5114.5  504.07  5140.7  505.91  5369.7  508.81  5484.2  515.79  5622.7  518.65
#Mann= 5 ,-1 , 0
  3595.5     .05       0  4501.6     .12       0    4979     .07       0
  4990.5     .12       0  5140.7     .05       0
Bank Sta=4979,4990.5
XS Rating Curve= 0 ,0
Exp/Cntr=0.3,0.1

Type RM Length L Ch R = 1 ,85640   ,790,790,790
BEGIN DESCRIPTION:
Mapping XS b1b8cff2
END DESCRIPTION:
XS GIS Cut Line= 4
      2686267.24      6967637.02      2685705.21      6967344.75
      2685212.77      6967697.62      2684580.58      6968984.85
#Sta/Elev= 30
  3760.7  514.41  4301.1  514.84  4392.8  514.11  4513.3  509.56  4720.9  507.01
  4799.2  504.82  4846.7  504.98  4871.9   505.7  4885.3     504  5158.5     504
  5164.1  505.61    5181  506.13  5203.5  504.96  5209.7  502.68  5211.2  502.18
  5221.2  502.68  5231.5  504.14  5248.4  502.98    5260  504.54  5270.9  504.23
  5276.5   505.7  5329.4  505.74  5471.7  505.98  5703.7  510.66  5761.3  513.58
    5895  517.51  6001.5  517.98  6119.5  514.01  6186.9  516.64  6434.1  519.26
#Mann= 5 ,-1 , 0
  3760.7     .05       0  4846.7     .12       0  5209.7     .07       0
  5221.2     .12       0  5329.4     .05       0
Bank Sta=5209.7,5221.2
XS Rating Curve= 0 ,0
Exp/Cntr=0.3,0.1

Type RM Length L Ch R = 1 ,84850   ,883,883,883
BEGIN DESCRIPTION:
Mapping XS 08e863a1
END DESCRIPTION:
XS GIS Cut Line= 5
      2686363.04      6967644.95      2685939.35      6967154.97
      2684698.66      6967118.72      2683539.96      6967529.23
      2683393.71      6967730.56
#Sta/Elev= 30
  3099.9  514.77  3270.8  515.49    3647  513.76  3731.5  515.04  3921.1  514.56
  4011.1  514.09  4091.2   511.3  4191.2  512.62  4361.3  509.04  4451.3  511.43
  4631.4  506.01  4729.5  504.87  4954.6     504  5153.5  503.92  5182.7  502.55
  5184.5  502.05  5195.7  502.55  5245.6  504.14  5307.4  503.83  5384.2  505.08
  5492.7  503.31  5523.6  504.98  5574.8  505.73  5785.7  515.91  5808.6  514.25
  5821.9  517.28  5878.3  521.05  6212.3  534.62  6265.5   536.8    6467  532.43
#Mann= 7 ,-1 , 0
  3099.9     .05       0  4729.5     .12       0  4954.6      .1       0
  5153.5     .12       0  5182.7     .07       0  5195.7     .12       0
  6212.3     .05       0
Bank Sta=5182.7,5195.7
XS Rating Curve= 0 ,0
Exp/Cntr=0.3,0.1

Type RM Length L Ch R = 1 ,83967   ,1349,1349,1349
BEGIN DESCRIPTION:
Mapping XS cedf2968
END DESCRIPTION:
XS GIS Cut Line= 4
      2686401.02      6967636.04        2685601.        6966336.
      2684396.39      6966330.84       2682651.9      6966867.93
#Sta/Elev= 30
  2268.9  514.75  4360.4  512.05  4561.8  509.89  4600.4  509.52  4640.4  506.46
  4757.3  504.07    5415  503.98  5513.1     504  5521.5  502.59  5523.4  502.09
  5534.6  502.59  5762.1  507.94  5774.7  506.04    5800  507.41  5816.5  506.49
  5832.7  509.28  5837.9  506.59  5858.4  506.76  5870.6  507.37  5879.3  511.05
  5898.1   512.4  5942.1  512.29  6066.7  516.96  6088.6  513.51    6099  518.19
  6104.7  518.82  6243.9  524.82  6414.5  527.65  6622.2  534.42  6825.3  537.21
#Mann= 7 ,-1 , 0
  2268.9     .05       0  4561.8     .12       0  4757.3      .1       0
    5415     .12       0  5521.5     .07       0  5534.6     .12       0
  6243.9     .05       0
Bank Sta=5521.5,5534.6
XS Rating Curve= 0 ,0
Exp/Cntr=0.3,0.1

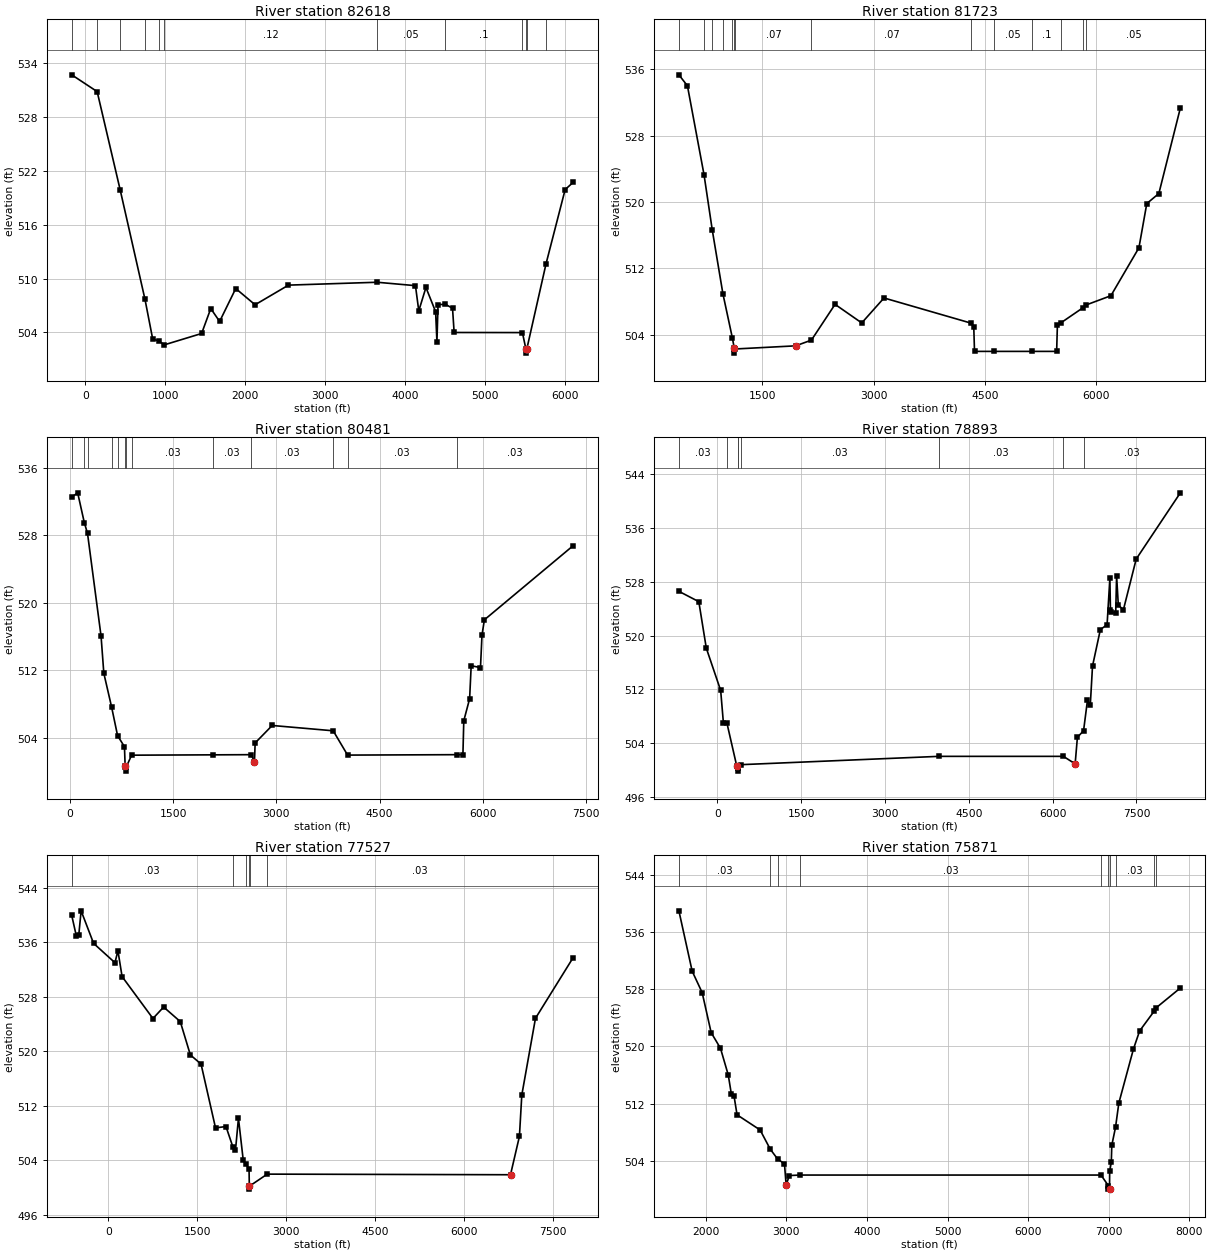
Type RM Length L Ch R = 1 ,82618   ,895,895,895
BEGIN DESCRIPTION:
Mapping XS 735a4324
END DESCRIPTION:
XS GIS Cut Line= 3
      2688851.02        6964636.      2683733.09      6965302.13
      2682790.72      6965895.66
#Sta/Elev= 30
  -169.5  532.72   148.6  530.85   438.3  519.83   746.9   507.7     844  503.25
   917.6  503.08   987.9  502.62  1455.8  503.89  1570.1  506.67    1681  505.23
  1882.7   508.9  2124.7  507.09  2542.7  509.28    3652   509.6  4131.5  509.22
  4173.1  506.41  4262.6  509.02  4383.6  506.32  4400.3  502.95  4413.9  507.11
  4506.9  507.14  4595.4   506.7  4615.5     504  5469.8  503.99  5512.6   502.2
  5514.4   501.7  5525.8   502.2  5766.1  511.68  6004.5  519.93  6105.3  520.74
#Mann= 12 ,-1 , 0
  -169.5     .05       0   148.6     .12       0   438.3     .05       0
   746.9     .12       0   917.6      .1       0   987.9     .12       0
    3652     .05       0  4506.9      .1       0  5469.8     .07       0
  5512.6     .05       0  5525.8     .01       0  5766.1     .05       0
Bank Sta=5512.6,5525.8
XS Rating Curve= 0 ,0
Exp/Cntr=0.3,0.1

Type RM Length L Ch R = 1 ,81723   ,1242,1242,1242
BEGIN DESCRIPTION:
Mapping XS 520e9e48
END DESCRIPTION:
XS GIS Cut Line= 4
      2688501.04        6964336.      2683878.93      6964458.38
      2682602.89      6964687.54      2681989.66      6965264.39
#Sta/Elev= 30
   373.3  535.34   488.4  534.02   712.3   523.3   823.4  516.63   967.3  508.93
  1094.1  503.64  1118.6  502.45  1119.6  502.29  1121.5  501.79  1132.9  502.29
  1948.9  502.67  2160.7  503.36  2479.1  507.67  2839.2  505.43  3139.3  508.44
  4318.9  505.39  4349.7  504.96  4359.7     502  4617.7     502  5132.4     502
  5467.4     502  5477.5  505.16  5524.5  505.44  5825.4  507.28  5868.9  507.61
  6198.9  508.71  6576.9  514.49  6682.9  519.82  6845.5  521.03  7135.4  531.34
#Mann= 14 ,-1 , 0
   373.3     .05       0   712.3     .12       0   823.4     .05       0
   967.3      .1       0  1094.1     .07       0  1119.6     .03       0
  1132.9     .07       0  2160.7     .07       0  4318.9      .1       0
  4617.7     .05       0  5132.4      .1       0  5524.5     .05       0
  5825.4      .1       0  5868.9     .05       0
Bank Sta=1118.6,1948.9
XS Rating Curve= 0 ,0
Exp/Cntr=0.3,0.1

Type RM Length L Ch R = 1 ,80481   ,1588,1588,1588
BEGIN DESCRIPTION:
Mapping XS 64aca41f
END DESCRIPTION:
XS GIS Cut Line= 4
       2688252.4       6963591.6      2683277.68      6963462.67
      2682128.24      6964017.22      2681470.23      6964822.58
#Sta/Elev= 30
    23.6  532.53     110  533.03   206.7  529.49     253  528.22   450.1  516.04
   490.2  511.65   602.7  507.67   690.1  504.26   790.3  502.94   800.3  500.63
   803.6  500.55   805.5  500.05   816.9  500.55   894.1  501.94  2078.7  501.98
  2633.7     502  2680.9  501.17  2690.9  503.39  2938.8  505.46  3825.9  504.83
  4035.3  501.95    5621     502  5712.4     502  5725.1  506.02    5810  508.63
  5832.6  512.54  5967.8  512.32    5990  516.18  6024.6  517.98  7316.2  526.77
#Mann= 13 ,-1 , 0
    23.6     .03       0   206.7     .03       0     253     .03       0
   602.7     .03       0   690.1     .03       0   803.6     .03       0
   816.9     .03       0   894.1     .03       0  2078.7     .03       0
  2633.7     .03       0  3825.9     .03       0  4035.3     .03       0
    5621     .03       0
Bank Sta=800.3,2680.9
XS Rating Curve= 0 ,0
Exp/Cntr=0.3,0.1

Type RM Length L Ch R = 1 ,78893   ,1366,1366,1366
BEGIN DESCRIPTION:
Mapping XS 396a2cd6
END DESCRIPTION:
XS GIS Cut Line= 4
       2688352.5       6963394.6      2682825.99      6962050.99
      2680318.28      6961879.72      2679563.93      6962043.63
#Sta/Elev= 30
  -687.5  526.58  -330.9  525.04  -197.1  518.12    60.2  511.81   108.7  507.01
   171.7  506.97   348.3  500.54   362.7   500.3   364.6   499.8   376.1   500.3
   415.9  500.76  3964.4     502    6193     502  6403.2  500.88  6443.3  504.83
  6553.7  505.82  6623.8  510.36  6673.9  509.61    6714  515.45  6854.3  520.88
  6974.6  521.61  7024.7  528.55  7034.7  523.79  7044.7  523.48  7128.9  523.34
    7145  528.89    7175  524.58  7265.3  523.79  7495.8  531.39  8285.5  541.25
#Mann= 8 ,-1 , 0
  -687.5     .03       0   171.7     .03       0   362.7     .03       0
   376.1     .03       0   415.9     .03       0  3964.4     .03       0
    6193     .03       0  6553.7     .03       0
Bank Sta=348.3,6403.2
XS Rating Curve= 0 ,0
Exp/Cntr=0.3,0.1

Type RM Length L Ch R = 1 ,77527   ,1656,1656,1656
BEGIN DESCRIPTION:
Mapping XS daab9c4d
END DESCRIPTION:
XS GIS Cut Line= 3
      2689084.04      6960618.49      2683488.74      6960913.24
      2680641.55      6961130.25
#Sta/Elev= 30
  -619.3  539.93  -541.2   536.9  -501.1  537.02    -461  540.61  -250.8  535.84
   109.7     533   159.8  534.76   229.9  530.97   750.6  524.82   930.9   526.5
  1211.3  524.37  1381.5  519.48  1561.8  518.14  1805.9  508.78  1982.3  508.98
  2098.8  505.99  2142.6  505.49  2192.6  510.19  2272.7  504.11  2312.5  503.52
  2371.4   502.8  2376.1   500.3    2378   499.8  2389.6   500.3  2678.1     502
  6781.7  501.91  6932.1  507.53  6972.2  513.59  7202.9  524.85  7839.2  533.76
#Mann= 6 ,-1 , 0
  -619.3     .03       0  2098.8     .03       0  2312.5     .03       0
  2376.1     .03       0  2389.6     .03       0  2678.1     .03       0
Bank Sta=2376.1,6781.7
XS Rating Curve= 0 ,0
Exp/Cntr=0.3,0.1

Type RM Length L Ch R = 1 ,75871   ,1967,1967,1967
BEGIN DESCRIPTION:
Mapping XS cbabc1ed
END DESCRIPTION:
XS GIS Cut Line= 3
      2687021.73      6958881.99      2683731.79      6959359.42
      2681075.59      6960505.23
#Sta/Elev= 30
  1669.3  538.98  1834.1  530.53    1958  527.53  2069.2  521.94    2185  519.74
  2281.4  516.01  2320.3   513.3  2352.1  513.13  2390.5  510.43  2676.3  508.31
  2802.1  505.62  2892.4  504.26  2978.6  503.56  2998.8  500.62  3039.2  501.93
  3170.7     502  6902.9     502  6992.8  500.53  6994.8  500.03  7008.4  500.03
  7010.4  502.53  7030.6  503.81  7036.6  506.16  7083.2  508.71  7123.7  512.07
  7305.6  519.66  7381.6  522.17  7565.3  524.99  7579.3  525.34  7886.5  528.18
#Mann= 10 ,-1 , 0
  1669.3     .03       0  2802.1     .03       0  2892.4     .03       0
  3170.7     .03       0  6902.9     .03       0  6992.8     .03       0
  7010.4     .03       0  7083.2     .03       0  7565.3     .03       0
  7579.3     .03       0
Bank Sta=2998.8,7008.4
XS Rating Curve= 0 ,0
Exp/Cntr=0.3,0.1

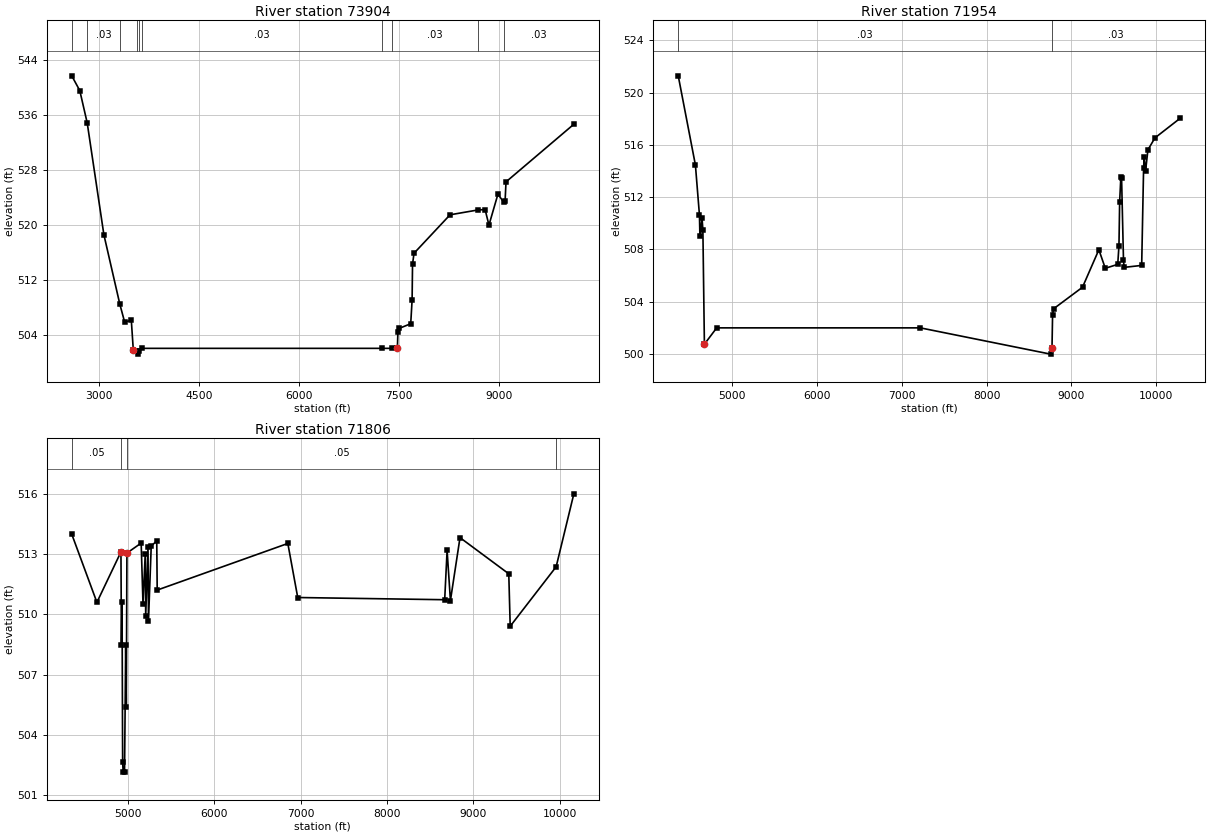
Type RM Length L Ch R = 1 ,73904   ,1950,1950,1950
BEGIN DESCRIPTION:
Muddy Cedar Creek 87.0
END DESCRIPTION:
XS GIS Cut Line= 3
      2686075.97        6957211.        2683676.        6957411.
      2679675.99      6960611.01
#Sta/Elev= 30
  2591.6  541.63    2712  539.48  2823.2  534.78  3073.2  518.53  3311.8  508.45
  3384.3  505.83  3484.7  506.08  3514.8  501.72  3575.7  501.66  3577.7  501.16
  3594.3  501.66  3643.6     502  7252.3     502  7393.4     502  7475.5  502.01
  7483.5  504.35  7504.3  504.91  7675.6  505.58  7696.4  509.04  7702.8  514.24
  7725.2  515.83  8265.5  521.42  8686.6  522.13  8791.3  522.18    8849  519.92
  8983.4  524.41  9070.7  523.26  9090.7  523.37  9105.1  526.21 10122.4  534.59
#Mann= 10 ,-1 , 0
  2591.6     .03       0  2823.2     .03       0  3311.8     .03       0
  3575.7     .03       0  3594.3     .03       0  3643.6     .03       0
  7252.3     .03       0  7393.4     .03       0  8686.6     .03       0
  9070.7     .03       0
Bank Sta=3514.8,7475.5
XS Rating Curve= 0 ,0
Exp/Cntr=0.3,0.1

Type RM Length L Ch R = 1 ,71954   ,148,148,148
BEGIN DESCRIPTION:
Mapping XS 767359eb
END DESCRIPTION:
XS GIS Cut Line= 5
      2684901.91      6955569.49      2684263.04      6955687.54
      2682290.82      6956423.65      2682207.49      6956479.21
      2680783.87      6959194.49
#Sta/Elev= 30
  4363.5  521.29  4566.1  514.46  4613.6  510.64  4619.1  509.05  4644.1  510.41
  4654.2   509.5    4672  500.75    4817     502  7218.5     502  8753.9  499.99
  8771.3  500.49    8778     503  8789.9  503.46  9130.9  505.11  9323.8  507.98
  9399.7  506.56  9546.4  506.86  9560.8  508.29    9569  511.67  9582.9  513.51
  9591.6  513.49  9614.2  507.19  9621.4  506.63  9828.7  506.78  9851.3  514.21
  9858.4   515.1  9873.9  513.98  9902.5  515.63  9985.1  516.54 10284.3  518.05
#Mann= 2 ,-1 , 0
  4363.5     .03       0  8771.3     .03       0
Bank Sta=4672,8771.3
XS Rating Curve= 0 ,0
Exp/Cntr=0.3,0.1

Type RM Length L Ch R = 1 ,71806   ,150,150,150
BEGIN DESCRIPTION:
Mapping XS 3c8102b6
END DESCRIPTION:
XS GIS Cut Line= 6
      2684653.67      6955078.17      2684080.75      6955666.71
      2682544.29      6956197.96      2682184.92      6956364.63
      2682013.04      6956593.79      2680804.71      6958973.99
#Sta/Elev= 30
  4355.2  513.99  4645.9   510.6  4923.9  513.11  4929.3   508.5  4936.4  510.63
  4943.4  502.65  4949.9  502.15  4965.3  502.15  4978.8  508.48  4985.9  505.39
  4992.9  513.05  5157.7  513.55  5178.6  510.54  5204.8  513.02    5210  509.92
  5236.7  513.34    5242  509.65  5273.9   513.4  5337.8  513.66    5343  511.21
  6853.5  513.53    6968  510.84  8667.3  510.73  8695.1  513.18  8733.7  510.69
  8844.3  513.82  9408.3  512.02  9424.8  509.41  9956.1  512.37 10160.7     516
#Mann= 4 ,-1 , 0
  4355.2     .05       0  4923.9     .04       0  4992.9     .05       0
  9956.1     .12       0
Bank Sta=4923.9,4992.9
XS Rating Curve= 0 ,0
Exp/Cntr=0.3,0.1