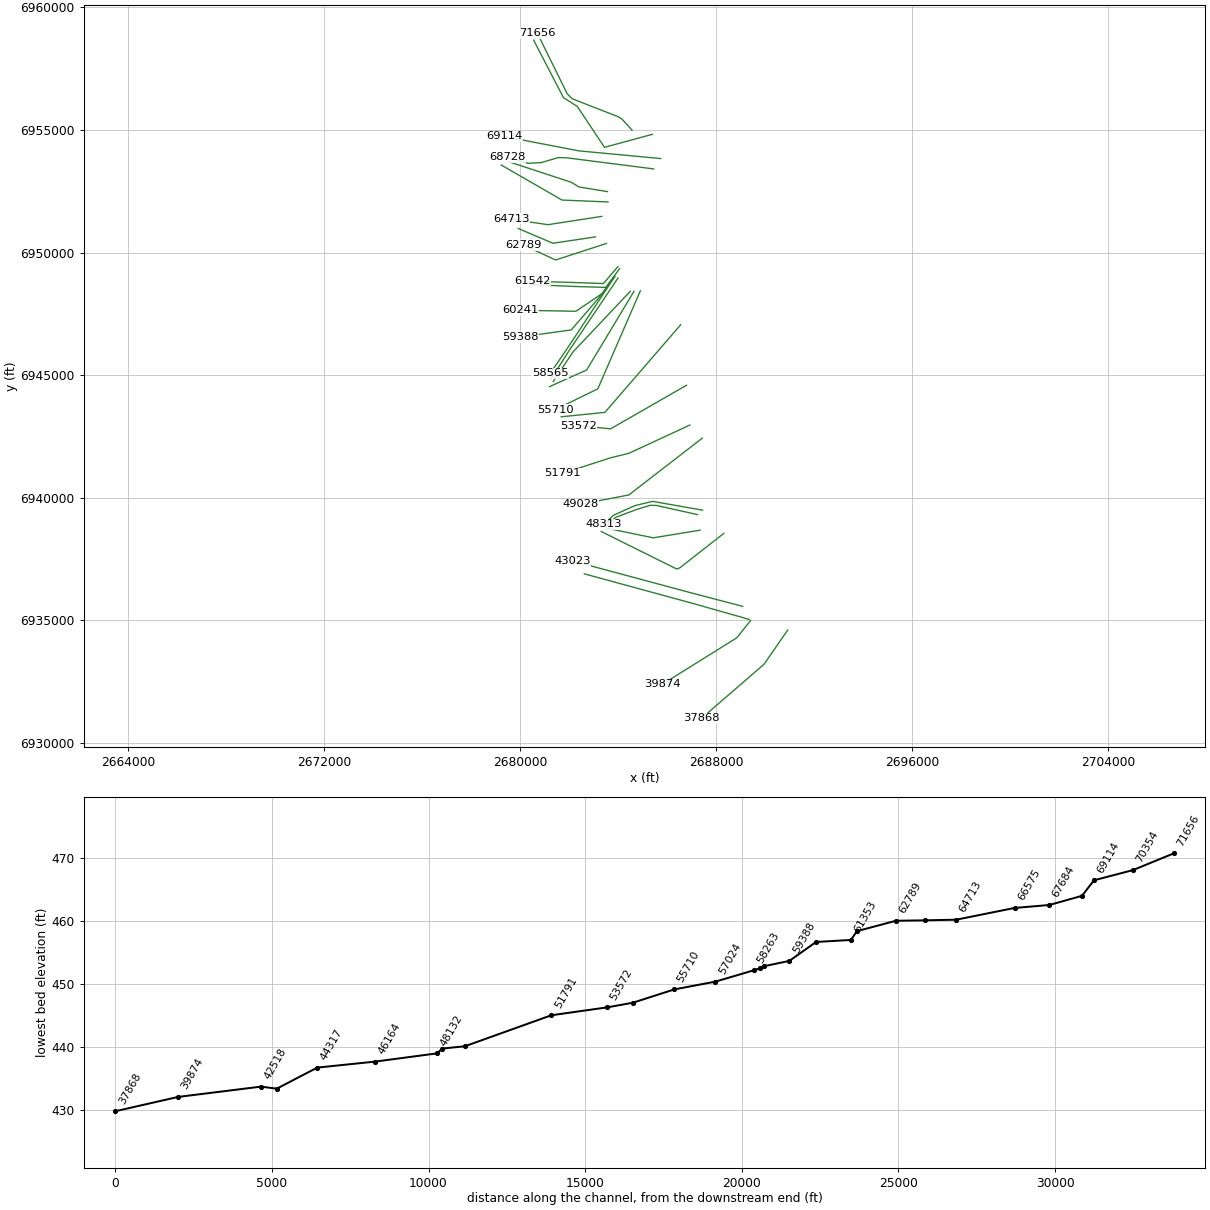
HEC-RAS study Muddy Cedar Creek.prj: Muddy Cedar Creek Base Level Engineering

--- Muddy Cedar Creek.g01 (geometry) --- (continued)

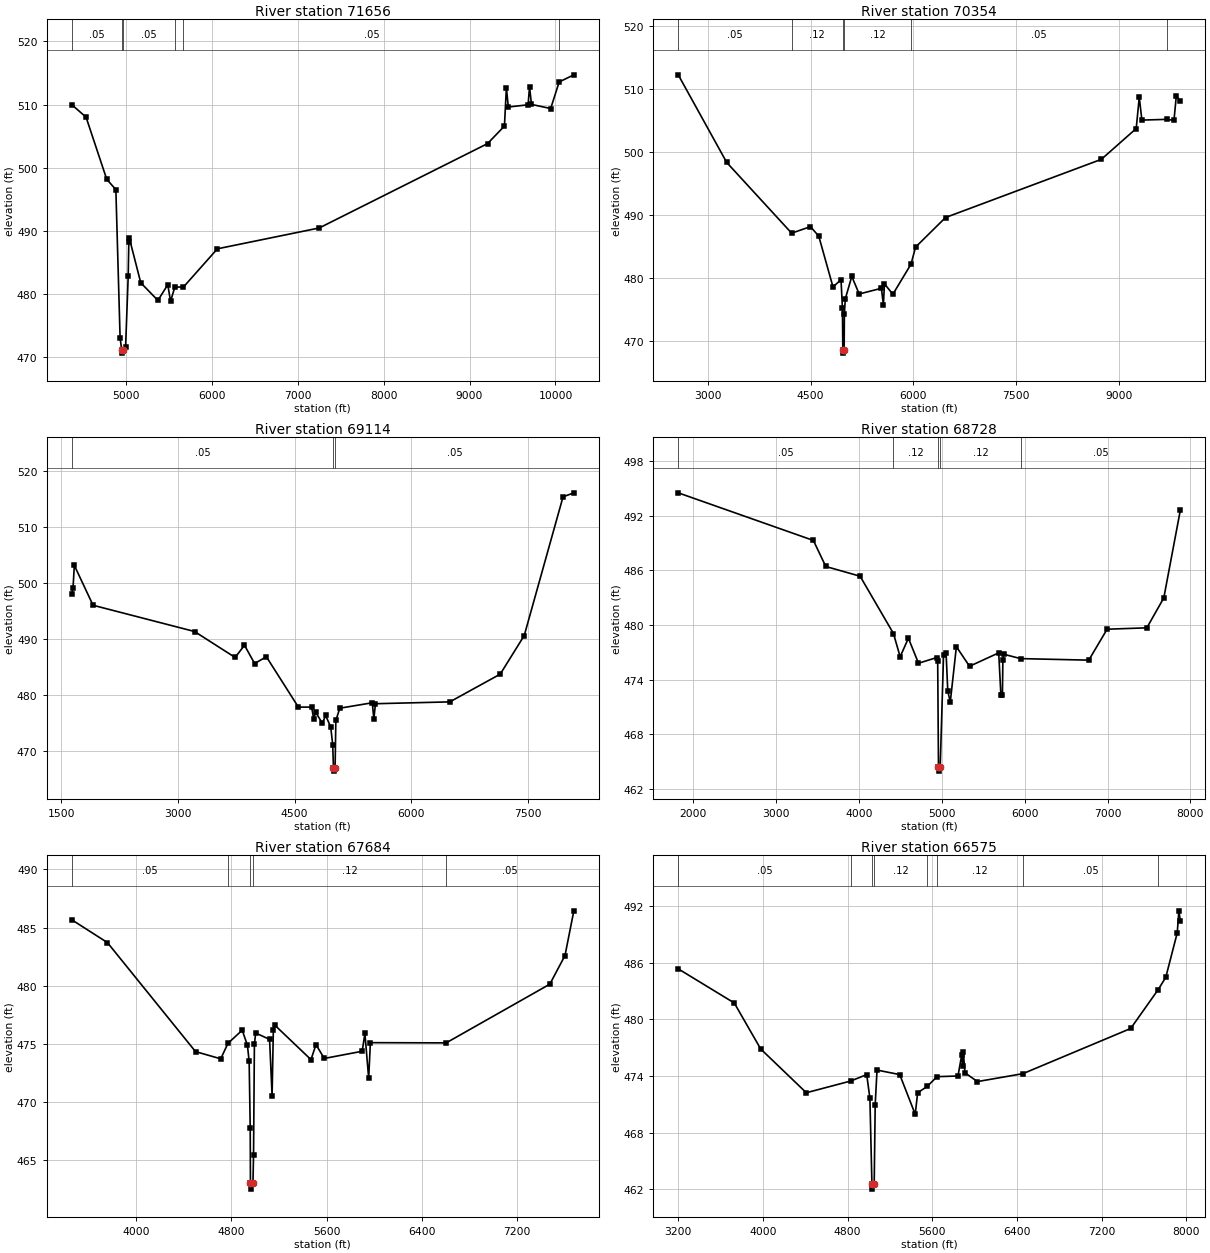
Type RM Length L Ch R = 1 ,71656   ,1302,1302,1302
BEGIN DESCRIPTION:
Mapping XS c5d079c7
END DESCRIPTION:
XS GIS Cut Line= 6
       2684554.7      6954994.84      2684138.04      6955453.17
      2683976.58      6955546.92        2682112.      6956276.09
      2681908.88      6956479.21      2680695.33      6958942.75
#Sta/Elev= 30
  4371.7  509.98  4538.1     508  4778.6  498.17  4884.7  496.55  4934.1  473.09
  4952.7  471.18  4954.7  470.68  4972.1  471.18    4998  471.68  5028.2  482.81
  5035.3  488.22    5041   488.9  5174.3  481.81  5373.8  479.02    5489   481.5
  5521.1  478.87  5570.8  481.13  5671.6  481.14  6066.1  487.18  7251.5  490.48
  9209.5  503.82  9406.1   506.6  9428.6  512.67    9451  509.61  9681.2  509.96
  9698.1  512.81  9720.6  510.02  9944.1  509.37 10042.6  513.57 10213.6   514.7
#Mann= 6 ,-1 , 0
  4371.7     .05       0  4952.7     .04       0  4972.1     .05       0
  5570.8     .12       0  5671.6     .05       0 10042.6     .12       0
Bank Sta=4952.7,4972.1
XS Rating Curve= 0 ,0
Exp/Cntr=0.3,0.1

Type RM Length L Ch R = 1 ,70354   ,1240,1240,1240
BEGIN DESCRIPTION:
Mapping XS f1a40477
END DESCRIPTION:
XS GIS Cut Line= 5
      2685381.53      6954822.09      2683431.13      6954293.27
      2682321.64      6955961.41       2681757.4      6956319.49
      2680542.12      6958663.25
#Sta/Elev= 30
  2566.5  512.23  3274.6  498.31    4223  487.08  4497.3  488.12  4619.1   486.6
  4826.5  478.54  4943.8  479.69  4964.8  475.16  4970.2  468.53  4972.2  468.03
  4989.6  468.53  4992.9   474.3  5006.9  476.66    5101  480.22  5209.1  477.42
  5533.4  478.33    5563  475.74  5578.1  479.03  5701.3  477.38  5966.9  482.18
    6032  484.86  6470.8  489.57  8746.1  498.81    9255   503.7  9299.6  508.67
  9337.8  505.04  9706.6  505.16  9806.5  504.99  9841.1  508.93  9899.1  508.03
#Mann= 6 ,-1 , 0
  2566.5     .05       0    4223     .12       0  4970.2     .07       0
  4989.6     .12       0  5966.9     .05       0  9706.6     .12       0
Bank Sta=4970.2,4989.6
XS Rating Curve= 0 ,0
Exp/Cntr=0.3,0.1

Type RM Length L Ch R = 1 ,69114   ,386,386,386
BEGIN DESCRIPTION:
Mapping XS f68a4034
END DESCRIPTION:
XS GIS Cut Line= 3
      2685728.72      6953834.68      2682375.89      6954149.35
      2679339.31      6954734.97
#Sta/Elev= 30
  1633.8   498.1  1649.8  499.12  1666.7   503.2  1907.7  496.07  3213.4  491.38
  3735.7  486.74  3856.2  488.92  3986.8  485.65  4137.5  486.87  4549.3  477.87
    4720  477.86  4748.3  475.65  4770.2  476.98  4857.1  474.99  4900.8  476.37
  4965.8  474.29  4991.2  471.15    5001  466.92  5003.1  466.42  5021.9  466.92
  5031.6  475.48  5082.7  477.67  5500.3  478.64  5520.7  475.73    5541  478.47
  6498.3   478.8  7146.9  483.76  7455.7  490.66  7954.7  515.45  8093.9  516.17
#Mann= 3 ,-1 , 0
  1633.8     .05       0    5001     .03       0  5021.9     .05       0
Bank Sta=5001,5021.9
XS Rating Curve= 0 ,0
Exp/Cntr=0.3,0.1

Type RM Length L Ch R = 1 ,68728   ,1044,1044,1044
BEGIN DESCRIPTION:
Mapping XS 6511d9a3
END DESCRIPTION:
XS GIS Cut Line= 6
      2685435.86      6953411.29      2681908.09      6953862.67
      2681553.92      6953876.56      2680845.59      6953668.23
      2680317.81      6953640.45       2679479.3      6953889.76
#Sta/Elev= 30
  1816.7  494.52  3448.4  489.29  3598.2  486.43  4012.5  485.36  4415.7  479.06
    4496  476.51  4595.8  478.55  4717.6   475.8  4939.2  476.43  4949.3  476.03
  4958.9  464.45    4961  463.95  4979.9  464.45  5020.1  476.73  5050.6  476.98
  5070.9  472.76  5101.4  471.53  5175.1  477.62  5333.7  475.47  5686.2  476.94
  5712.6  472.28  5730.9  472.28  5736.5   476.2  5746.9  476.79  5949.9  476.31
  6773.8  476.14    6995  479.54  7474.7  479.69  7679.4  482.98  7878.8   492.6
#Mann= 5 ,-1 , 0
  1816.7     .05       0  4415.7     .12       0  4958.9     .07       0
  4979.9     .12       0  5949.9     .05       0
Bank Sta=4958.9,4979.9
XS Rating Curve= 0 ,0
Exp/Cntr=0.3,0.1

Type RM Length L Ch R = 1 ,67684   ,1109,1109,1109
BEGIN DESCRIPTION:
Mapping XS a09bf362
END DESCRIPTION:
XS GIS Cut Line= 4
        2683551.        6952486.       2682394.2      6952673.44
      2682076.49      6952866.15      2679540.53      6953699.32
#Sta/Elev= 30
  3462.6  485.67  3761.5  483.71    4501  474.33  4712.5  473.71  4773.7  475.05
  4892.8  476.17  4936.5  474.87    4951  473.48  4959.9  467.74  4961.8     463
  4963.9   462.5  4982.9     463  4987.8  465.47    4995  474.97  5005.9  475.93
  5122.4  475.38  5143.4  470.53    5154  476.18  5167.8  476.59  5469.7  473.64
  5511.8  474.93  5581.3  473.74  5899.4  474.36  5922.3  475.89  5953.9  472.02
  5968.2   475.1  6604.1  475.08  7473.7  480.13    7601  482.59  7675.4  486.44
#Mann= 5 ,-1 , 0
  3462.6     .05       0  4773.7     .12       0  4961.8     .07       0
  4982.9     .12       0  6604.1     .05       0
Bank Sta=4961.8,4982.9
XS Rating Curve= 0 ,0
Exp/Cntr=0.3,0.1

Type RM Length L Ch R = 1 ,66575   ,1862,1862,1862
BEGIN DESCRIPTION:
Mapping XS 25fdda31
END DESCRIPTION:
XS GIS Cut Line= 3
      2683574.74      6952063.93      2681696.28      6952140.89
      2679217.15      6953571.42
#Sta/Elev= 30
  3199.5  485.34  3728.7  481.73  3978.5  476.86  4409.3  472.23  4828.4  473.47
  4979.7  474.15  5009.8  471.65  5029.1  462.53  5031.2  462.03  5050.4  462.53
  5059.8  470.98  5077.2  474.63  5291.7  474.15  5437.8  469.95  5460.9  472.23
  5551.9   472.9  5643.2  473.93  5841.9     474  5876.5   476.2  5886.2  475.02
    5892  476.58  5907.7  474.34  6025.5  473.41  6455.5  474.25  7473.1  479.03
  7733.4  483.15  7804.6  484.45  7912.6  489.14  7928.4  491.48  7941.8  490.41
#Mann= 8 ,-1 , 0
  3199.5     .05       0  4828.4     .12       0  5029.1     .07       0
  5050.4     .12       0  5551.9     .05       0  5643.2     .12       0
  6455.5     .05       0  7733.4     .12       0
Bank Sta=5029.1,5050.4
XS Rating Curve= 0 ,0
Exp/Cntr=0.3,0.1

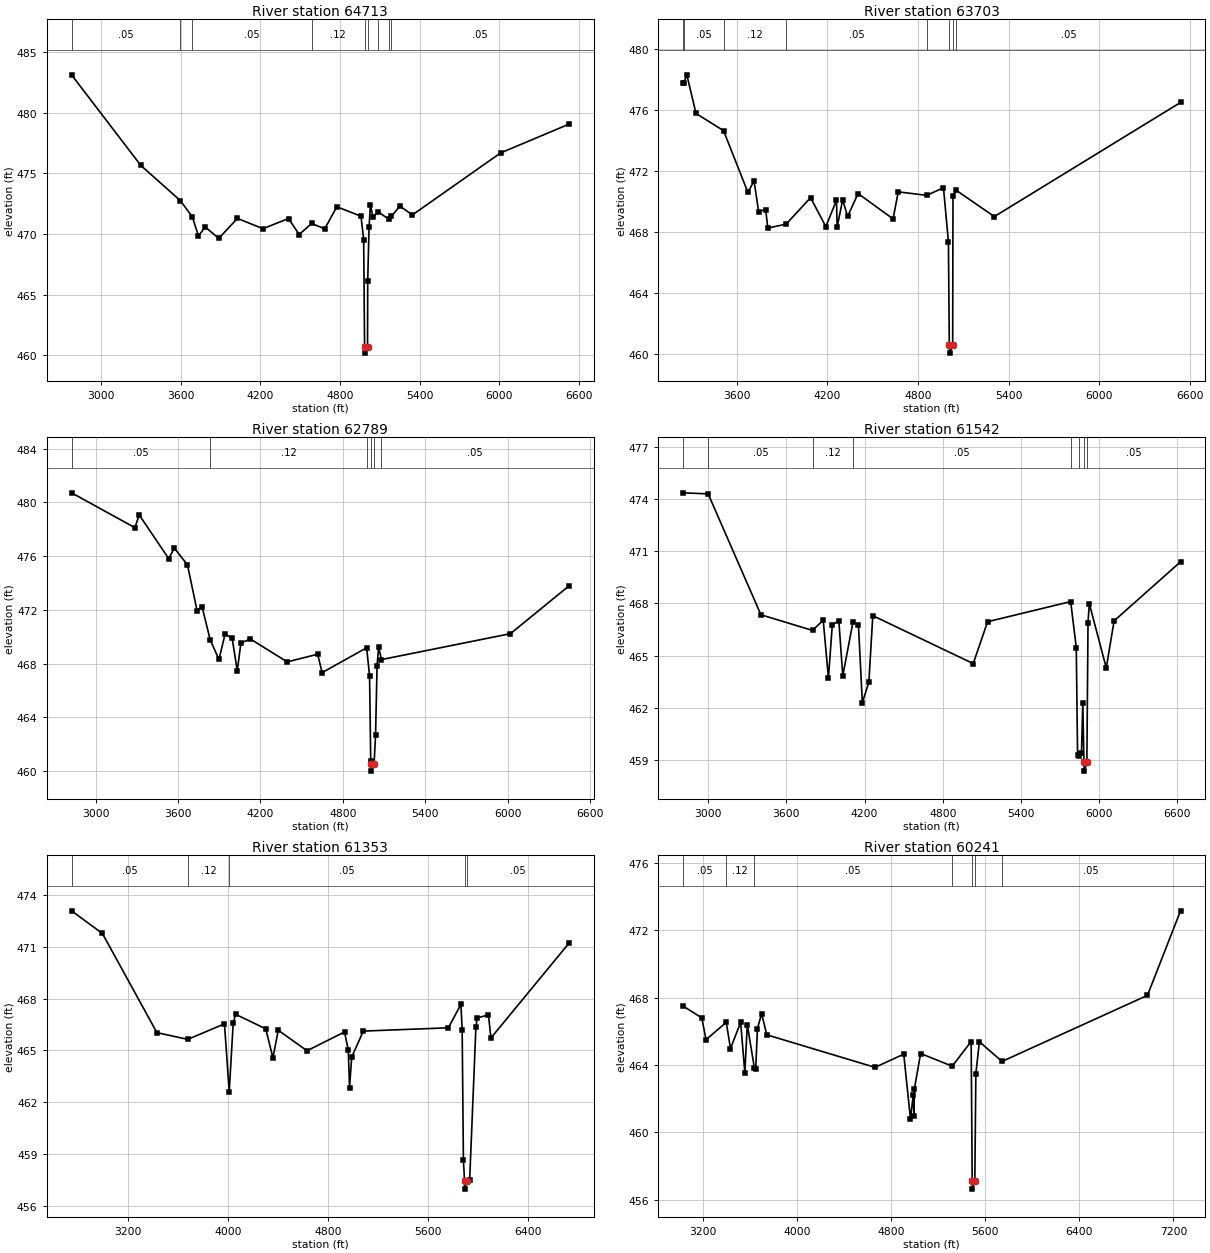
Type RM Length L Ch R = 1 ,64713   ,1010,1010,1010
BEGIN DESCRIPTION:
Mapping XS 6cbe91fa
END DESCRIPTION:
XS GIS Cut Line= 4
      2683321.29      6951474.22      2681125.59        6951136.
        2680101.        6951286.      2679620.51      6951387.49
#Sta/Elev= 30
  2778.4  483.14  3299.8  475.67  3598.8  472.75  3688.5  471.41  3734.8  469.84
  3785.4  470.58  3887.5  469.64  4028.3  471.29  4220.5  470.44  4413.3  471.28
  4493.7  469.96  4586.9  470.87  4685.9  470.43    4777  472.25  4959.1  471.47
  4979.3  469.54  4986.1  460.67  4988.4  460.17  5008.4  460.67  5009.7  466.13
  5019.8  470.54  5029.9   472.4  5050.1  471.37  5086.5  471.85  5168.4  471.22
  5187.6  471.46  5252.2   472.3  5346.7  471.58  6010.2  476.69  6526.6  479.07
#Mann= 9 ,-1 , 0
  2778.4     .05       0  3598.8     .12       0  3688.5     .05       0
  4586.9     .12       0  4986.1     .07       0  5008.4     .12       0
  5086.5     .05       0  5168.4     .12       0  5187.6     .05       0
Bank Sta=4986.1,5008.4
XS Rating Curve= 0 ,0
Exp/Cntr=0.3,0.1

Type RM Length L Ch R = 1 ,63703   ,914,914,914
BEGIN DESCRIPTION:
Mapping XS 7aacc499
END DESCRIPTION:
XS GIS Cut Line= 3
      2683060.87      6950637.41      2681326.49        6950377.
      2679910.41      6950980.91
#Sta/Elev= 30
  3245.5  477.76  3249.7  477.76  3270.6  478.31  3331.3  475.78  3513.7  474.65
  3675.1   470.6  3715.6  471.36  3745.9  469.35  3792.6  469.48  3806.6  468.27
  3927.6  468.52  4089.7  470.26  4190.8  468.36  4260.9  470.08    4266  468.35
  4302.1  470.12    4335  469.03  4404.1  470.53  4635.8  468.87  4670.2  470.64
  4858.8  470.41  4969.5  470.91  5002.3  467.37  5008.1  460.57  5010.3  460.07
  5030.4  460.57  5032.5  470.39  5055.5  470.73  5306.2  469.02  6538.8   476.5
#Mann= 8 ,-1 , 0
  3245.5     .12       0  3249.7     .05       0  3513.7     .12       0
  3927.6     .05       0  4858.8     .12       0  5008.1     .07       0
  5030.4     .12       0  5055.5     .05       0
Bank Sta=5008.1,5030.4
XS Rating Curve= 0 ,0
Exp/Cntr=0.3,0.1

Type RM Length L Ch R = 1 ,62789   ,1247,1247,1247
BEGIN DESCRIPTION:
Mapping XS a7f7a6b6
END DESCRIPTION:
XS GIS Cut Line= 3
      2683508.33      6950368.82      2681435.86       6949694.7
      2680129.74      6950303.53
#Sta/Elev= 30
  2825.6  480.71  3286.4  478.12  3318.3  479.06  3532.6  475.82  3573.9  476.59
  3669.3  475.35  3738.8  471.95    3776  472.21  3834.2  469.78  3898.5  468.31
  3942.7   470.2  3994.3   469.9  4031.5  467.47  4058.2  469.54  4127.3  469.83
  4394.9  468.13  4616.9   468.7  4648.8  467.33  4973.1  469.18  4994.3  467.09
  5002.9  460.72  5004.7   460.5  5006.9     460    5027   460.5  5037.9  462.66
  5048.9  467.85  5060.4  469.22  5080.8   468.3  6019.8  470.23    6446  473.79
#Mann= 6 ,-1 , 0
  2825.6     .05       0  3834.2     .12       0  4973.1     .05       0
  5004.7     .03       0    5027     .05       0  5080.8     .05       0
Bank Sta=5004.7,5027
XS Rating Curve= 0 ,0
Exp/Cntr=0.3,0.1

Type RM Length L Ch R = 1 ,61542   ,189,189,189
BEGIN DESCRIPTION:
Mapping XS 83044af9
END DESCRIPTION:
XS GIS Cut Line= 4
      2683983.05        6949426.      2683387.16      6948733.09
      2682109.43      6948777.71      2680486.66      6948826.21
#Sta/Elev= 30
  2807.6  474.37  3000.3  474.31    3405  467.35  3800.9  466.45  3882.8  467.04
  3922.8  463.71  3952.8  466.79  4002.8  466.99  4032.8  463.83  4111.2  466.94
  4152.9  466.77  4182.9   462.3    4233  463.47    4263   467.3  5033.4  464.54
  5143.5  466.95  5780.8  468.11  5823.8  465.46  5833.8  459.26  5840.9  459.21
  5863.8  459.41  5873.8  462.28  5882.7  458.85  5884.9  458.35    5905  458.85
  5913.8   466.9  5923.8  467.99  6053.9  464.29  6113.9     467  6623.5   470.4
#Mann= 8 ,-1 , 0
  2807.6     .12       0  3000.3     .05       0  3800.9     .12       0
  4111.2     .05       0  5780.8     .12       0  5840.9     .05       0
  5882.7     .04       0    5905     .05       0
Bank Sta=5882.7,5905
XS Rating Curve= 0 ,0
Exp/Cntr=0.3,0.1

Type RM Length L Ch R = 1 ,61353   ,1112,1112,1112
BEGIN DESCRIPTION:
Mapping XS 758d51be
END DESCRIPTION:
XS GIS Cut Line= 4
      2684046.04      6949336.49      2683483.82       6948576.5
       2682186.3      6948614.41      2680451.88      6948692.54
#Sta/Elev= 30
  2749.4  473.09    2996  471.78  3432.3  466.03  3678.9  465.64  3972.7  466.54
  4010.6  462.61  4042.7   466.6  4062.7  467.09  4302.8  466.25  4360.2  464.57
  4402.9  466.17    4633  464.98  4933.1  466.07  4963.1  465.01  4973.1  462.85
  4990.5  464.61  5083.2  466.12  5763.9  466.31    5864  467.67    5874   466.2
    5884  458.63  5892.9  457.46  5895.1  456.96  5915.2  457.46  5934.1  457.51
  5984.1  466.38  5994.1  466.88  6084.2  467.06  6104.2  465.72    6729  471.22
#Mann= 5 ,-1 , 0
  2749.4     .05       0  3678.9     .12       0  4010.6     .05       0
  5892.9     .04       0  5915.2     .05       0
Bank Sta=5892.9,5915.2
XS Rating Curve= 0 ,0
Exp/Cntr=0.3,0.1

Type RM Length L Ch R = 1 ,60241   ,853,853,853
BEGIN DESCRIPTION:
Mapping XS 62b73ed1
END DESCRIPTION:
XS GIS Cut Line= 4
       2683724.9      6948883.85      2683332.12      6948323.98
      2682264.92      6947601.45       2680004.6      6947643.12
#Sta/Elev= 30
  3027.3   467.5  3187.1  466.79  3222.9   465.5  3395.3  466.53  3431.2  464.97
  3517.5  466.53  3553.2  463.54  3574.1  466.39  3634.6  463.82  3645.6  463.74
  3660.4  466.16  3696.1  467.04    3740  465.79  4660.6  463.86  4905.4  464.64
  4962.5  460.81  4986.2  462.23  4992.3  460.98  4996.3   462.6  5048.9  464.68
  5317.8  463.93    5479  465.39  5487.9  457.14  5490.1  456.64  5510.2  457.14
    5519  463.48    5549  465.38  5741.6  464.21  6979.3  468.13  7260.7  473.14
#Mann= 7 ,-1 , 0
  3027.3     .05       0  3395.3     .12       0  3634.6     .05       0
  5317.8     .12       0  5487.9     .04       0  5510.2     .12       0
  5741.6     .05       0
Bank Sta=5487.9,5510.2
XS Rating Curve= 0 ,0
Exp/Cntr=0.3,0.1

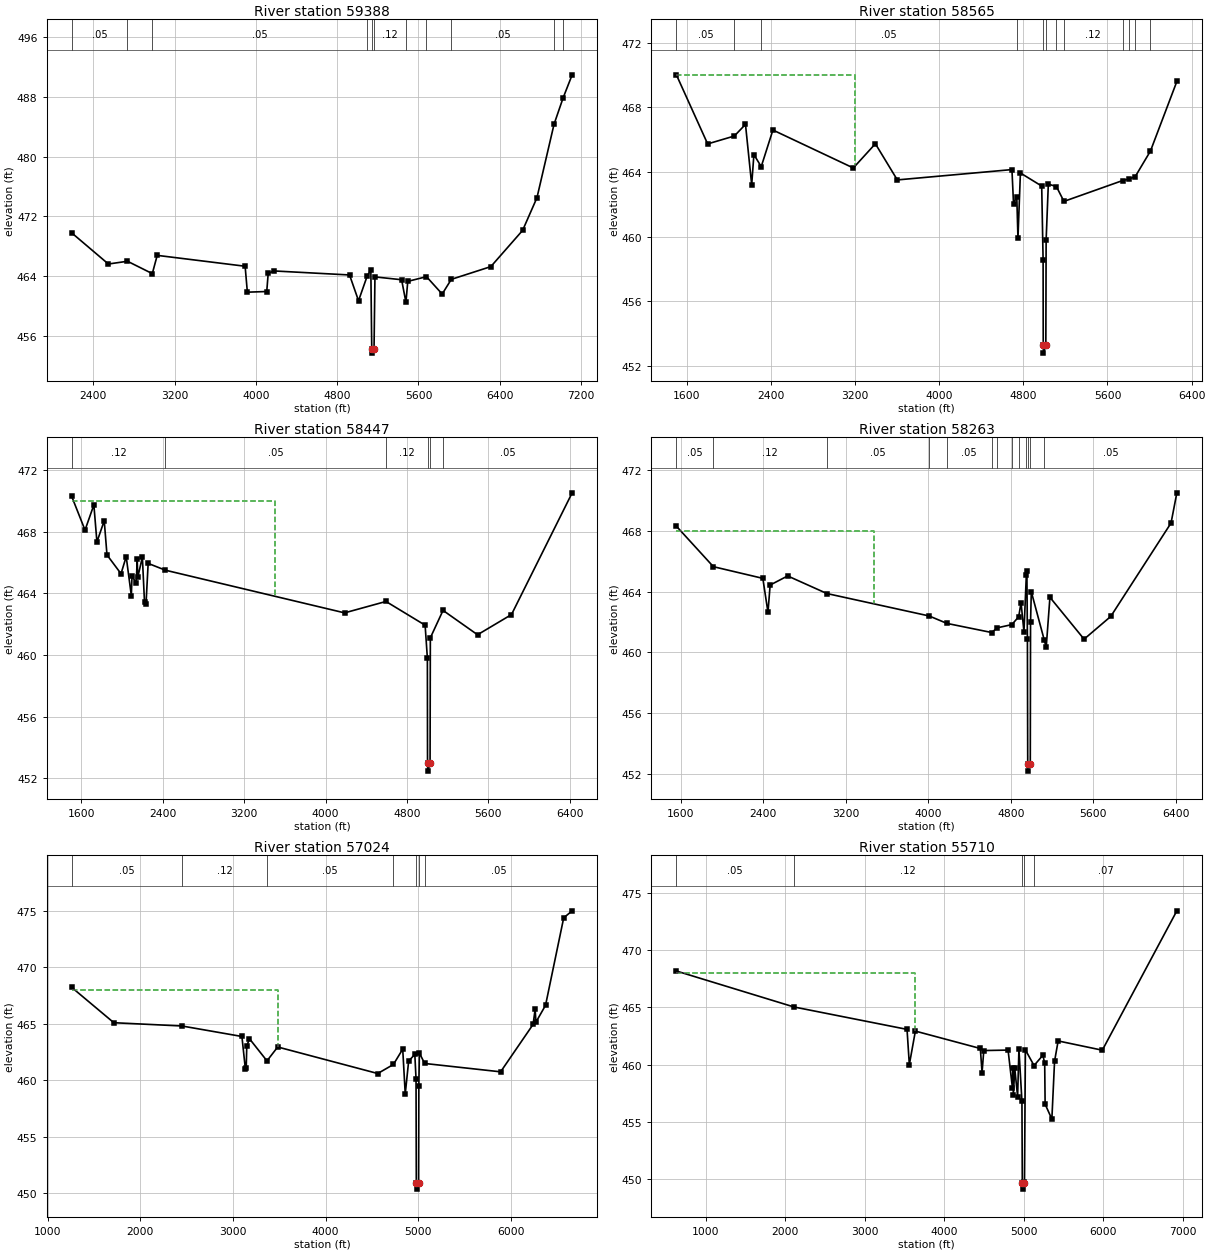
Type RM Length L Ch R = 1 ,59388   ,823,823,823
BEGIN DESCRIPTION:
Mapping XS 6060ba5a
END DESCRIPTION:
XS GIS Cut Line= 4
      2683837.62      6949031.07      2683340.53      6948309.55
      2682076.03      6946841.01       2679982.8      6946549.71
#Sta/Elev= 30
  2185.9  469.78  2547.2   465.6  2735.3  465.97  2979.5  464.31    3028  466.76
  3893.5   465.3  3915.5  461.82  4106.4  461.91  4120.6  464.34  4177.7  464.67
  4921.6  464.13  5010.1  460.67  5095.7     464  5131.3  464.79  5140.3  454.14
  5142.5  453.64  5162.7  454.14  5171.7  463.87  5434.2  463.49  5476.8  460.46
  5494.8  463.27  5679.2   463.9  5833.7  461.57  5923.4  463.54  6312.6  465.25
  6625.5  470.11  6766.9   474.5  6934.9  484.35  7024.5   487.9  7113.4  490.99
#Mann= 11 ,-1 , 0
  2185.9     .05       0  2735.3     .12       0  2979.5     .05       0
  5095.7     .12       0  5140.3     .03       0  5162.7     .12       0
  5476.8     .05       0  5679.2     .12       0  5923.4     .05       0
  6934.9     .12       0  7024.5     .05       0
Bank Sta=5140.3,5162.7
XS Rating Curve= 0 ,0
Exp/Cntr=0.3,0.1

Type RM Length L Ch R = 1 ,58565   ,118,118,118
BEGIN DESCRIPTION:
Mapping XS 44c57f53
END DESCRIPTION:
XS GIS Cut Line= 3
       2683858.5      6949028.89       2681926.5      6946106.21
      2681218.53      6945071.56
#Sta/Elev= 30
  1502.3  470.02  1799.5  465.74  2053.2  466.23  2159.1  466.95  2218.1  463.21
  2239.1  465.08  2308.7  464.33  2419.7   466.6  3184.1  464.25  3393.8  465.75
  3602.4  463.51  4691.9  464.15    4707  462.03  4737.9  462.48  4749.1  459.89
  4772.3  463.94  4974.8  463.13  4988.1  458.56  4989.4  453.28  4991.8  452.78
  5014.1  453.28  5016.9  459.78  5037.8  463.25  5114.5   463.1  5186.2  462.18
  5743.6  463.47  5807.2  463.57  5864.2  463.72  6008.6   465.3  6259.5  469.61
#Mann= 12 ,-1 , 0
  1502.3     .05       0  2053.2     .12       0  2308.7     .05       0
  4737.9     .12       0  4989.4     .07       0  5014.1     .12       0
  5114.5     .05       0  5186.2     .12       0  5743.6     .05       0
  5807.2     .12       0  5864.2     .05       0  6008.6     .12       0
#XS Ineff= 2 , 0
       0    3200     470               0
Permanent Ineff=
       F       F
Bank Sta=4989.4,5014.1
XS Rating Curve= 0 ,0
Exp/Cntr=0.3,0.1

Type RM Length L Ch R = 1 ,58447   ,184,184,184
BEGIN DESCRIPTION:
Mapping XS feb15f7c
END DESCRIPTION:
XS GIS Cut Line= 3
      2683982.76      6948956.95      2682029.63      6946061.11
      2681264.01        6944858.
#Sta/Elev= 30
  1504.8   470.3  1635.9  468.11  1722.8  469.75  1752.8  467.34  1824.7  468.72
  1851.7   466.5  1989.6  465.28  2040.6  466.39    2091  463.86  2097.6  465.12
  2139.6  464.67  2148.5  466.22  2154.5  465.05  2199.5  466.36  2220.5  463.42
  2235.4  463.33  2256.4  465.95  2425.3  465.51  4187.1  462.74  4593.8  463.48
  4978.6  461.94  5000.8   459.8  5002.3  452.97  5004.8  452.47  5027.2  452.97
    5030  461.12  5154.6   462.9  5493.9  461.32  5827.5  462.63  6423.8  470.53
#Mann= 6 ,-1 , 0
  1504.8     .12       0  2425.3     .05       0  4593.8     .12       0
  5002.3     .07       0  5027.2     .12       0  5154.6     .05       0
#XS Ineff= 2 , 0
       0    3500     470               0
Permanent Ineff=
       F       F
Bank Sta=5002.3,5027.2
XS Rating Curve= 0 ,0
Exp/Cntr=0.3,0.1

Type RM Length L Ch R = 1 ,58263   ,1239,1239,1239
BEGIN DESCRIPTION:
Mapping XS 6c0560ac
END DESCRIPTION:
XS GIS Cut Line= 3
      2684484.78       6948417.6      2682144.51      6945938.43
      2681339.98      6944738.57
#Sta/Elev= 30
  1557.6  468.31  1916.5  465.64  2396.1  464.87  2445.8  462.63  2466.9  464.43
  2636.8  465.03  3017.2  463.87  4009.5  462.39  4181.6   461.9    4615   461.3
  4670.3  461.61  4810.9  461.82  4877.6  462.34  4900.3  463.27  4928.6  461.35
  4951.6  465.07  4956.9  465.37  4962.1  460.89  4965.1  452.66  4967.6  452.16
    4990  452.66  4992.5  461.98  4999.9  463.99  5124.8  460.82  5144.4  460.32
  5180.5  463.62  5511.7  460.86  5770.5  462.36  6355.1  468.52  6411.5  470.51
#Mann= 13 ,-1 , 0
  1557.6     .05       0  1916.5     .12       0  3017.2     .05       0
  4009.5     .12       0  4181.6     .05       0    4615     .12       0
  4670.3     .05       0  4810.9     .12       0  4877.6     .05       0
  4951.6     .12       0  4965.1     .07       0    4990     .12       0
  5124.8     .05       0
#XS Ineff= 2 , 0
       0  3471.4     468               0
Permanent Ineff=
       F       F
Bank Sta=4965.1,4990
XS Rating Curve= 0 ,0
Exp/Cntr=0.3,0.1

Type RM Length L Ch R = 1 ,57024   ,1314,1314,1314
BEGIN DESCRIPTION:
Mapping XS 7fc4d0a1
END DESCRIPTION:
XS GIS Cut Line= 3
      2684635.81      6948415.84      2682705.27      6945207.53
      2681191.37      6944526.97
#Sta/Elev= 30
  1259.1  468.22  1714.3  465.09  2449.7   464.8  3097.3  463.87  3134.2  461.02
  3143.8  461.11  3149.7  463.03  3178.8  463.67  3367.8  461.71  3483.8  462.94
  4563.7  460.59    4733  461.39  4833.7  462.75  4860.9  458.77  4897.8   461.7
  4964.4  462.28  4977.4  460.11  4980.5  450.85    4983  450.35  5005.4  450.85
  5007.7  459.45  5013.6  462.41  5070.6  461.48  5890.7  460.74  6241.6  464.94
  6263.5  466.28  6272.2  465.14  6375.8  466.63    6572  474.38  6663.3     475
#Mann= 7 ,-1 , 0
  1259.1     .05       0  2449.7     .12       0  3367.8     .05       0
    4733     .12       0  4980.5     .07       0  5005.4     .12       0
  5070.6     .05       0
#XS Ineff= 2 , 0
       0  3483.8     468               0
Permanent Ineff=
       F       F
Bank Sta=4980.5,5005.4
XS Rating Curve= 0 ,0
Exp/Cntr=0.3,0.1

Type RM Length L Ch R = 1 ,55710   ,1316,1316,1316
BEGIN DESCRIPTION:
Mapping XS 101ba66a
END DESCRIPTION:
XS GIS Cut Line= 3
      2684894.94      6948436.25      2683158.83      6944434.52
      2681422.74      6943592.52
#Sta/Elev= 30
   633.1  468.17  2110.4  465.03  3532.7  463.07  3561.6  459.99  3637.4  462.92
    4454   461.4  4475.8   459.3  4497.6  461.22  4802.8  461.26  4857.3  457.98
  4863.4  459.68  4868.9   457.3  4886.9  459.66  4922.7   457.2  4939.3  461.33
  4977.2  456.78  4981.9  449.61  4984.4  449.11  5006.9  449.61  5009.3  449.73
  5020.6  461.28  5129.3  459.91  5240.6  460.81  5263.2  460.11  5268.7  456.53
  5353.4  455.23  5387.3  460.29  5432.3  462.06  5987.5  461.25  6924.7  473.43
#Mann= 5 ,-1 , 0
   633.1     .05       0  2110.4     .12       0  4981.9     .07       0
  5006.9     .12       0  5129.3     .07       0
#XS Ineff= 2 , 0
       0  3637.4     468               0
Permanent Ineff=
       F       F
Bank Sta=4981.9,5006.9
XS Rating Curve= 0 ,0
Exp/Cntr=0.3,0.1

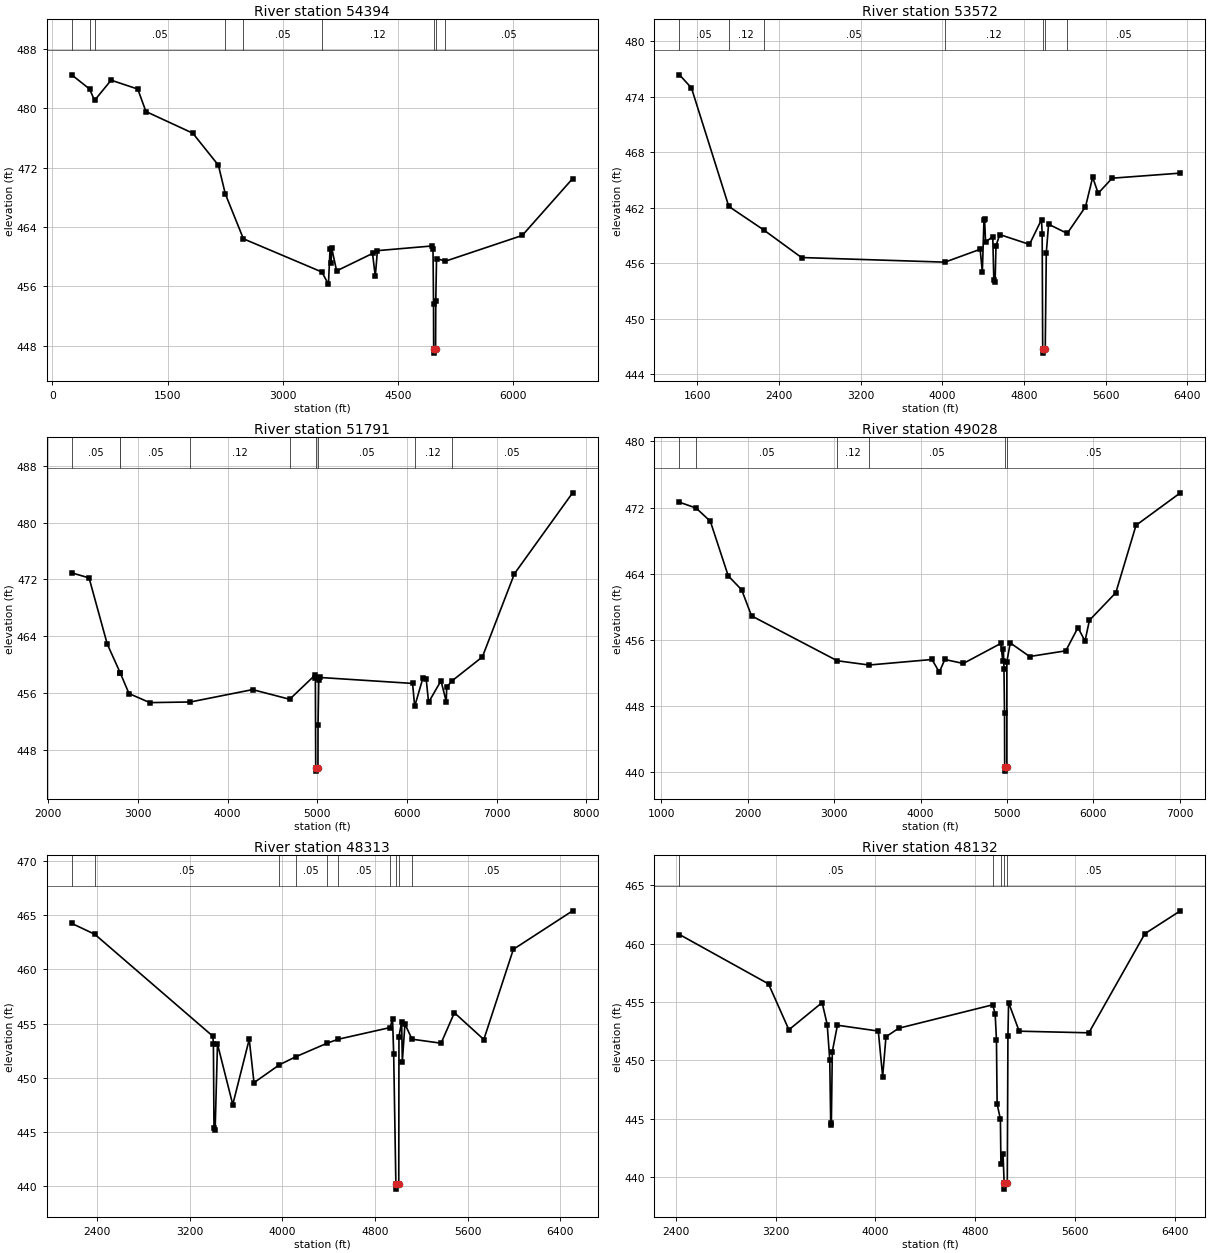
Type RM Length L Ch R = 1 ,54394   ,822,822,822
BEGIN DESCRIPTION:
Mapping XS f84cc466
END DESCRIPTION:
XS GIS Cut Line= 3
      2686540.22      6947049.76      2683448.76      6943475.32
      2681664.03      6943294.76
#Sta/Elev= 30
   251.7  484.54   483.9  482.63   549.1  481.09   764.7  483.82  1111.3  482.62
  1217.7  479.59  1827.5  476.67  2160.9  472.35  2250.5   468.5  2486.3  462.43
  3507.8  457.95  3593.4  456.29  3614.2  461.04  3628.5  459.13  3635.1  461.21
  3699.8   458.1  4167.1  460.45  4203.2  457.36  4230.7  460.83  4940.3  461.46
  4954.5  461.07  4961.1  453.66  4962.9  447.51  4965.4  447.01  4987.9  447.51
  4990.4  454.02  5000.4  459.77  5116.2  459.41  6116.1  462.88  6771.4  470.54
#Mann= 9 ,-1 , 0
   251.7     .05       0   483.9     .12       0   549.1     .05       0
  2250.5     .12       0  2486.3     .05       0  3507.8     .12       0
  4962.9     .07       0  4987.9     .12       0  5116.2     .05       0
Bank Sta=4962.9,4987.9
XS Rating Curve= 0 ,0
Exp/Cntr=0.3,0.1

Type RM Length L Ch R = 1 ,53572   ,1781,1781,1781
BEGIN DESCRIPTION:
Mapping XS af044a83
END DESCRIPTION:
XS GIS Cut Line= 3
      2686777.74      6944581.22      2683680.53      6942803.45
      2682350.99        6942936.
#Sta/Elev= 30
  1425.1  476.37  1542.4  474.95  1908.2  462.14  2249.5   459.6  2620.6  456.61
  4025.8  456.11  4370.7   457.5  4392.3  455.04  4408.1  460.68  4413.9   460.8
  4423.9  458.29  4494.4  458.87  4504.5  454.23  4517.2  453.93    4526   457.9
  4563.3  459.09  4853.9  458.03  4971.9  460.71  4978.4   459.2  4983.5  446.77
    4986  446.27  5008.5  446.77  5018.9  457.12    5041  460.21  5224.1  459.22
  5402.8   462.1  5473.1  465.29  5527.2  463.56  5664.1  465.19  6332.4  465.74
#Mann= 7 ,-1 , 0
  1425.1     .05       0  1908.2     .12       0  2249.5     .05       0
  4025.8     .12       0  4983.5     .07       0  5008.5     .12       0
  5224.1     .05       0
Bank Sta=4983.5,5008.5
XS Rating Curve= 0 ,0
Exp/Cntr=0.3,0.1

Type RM Length L Ch R = 1 ,51791   ,2763,2763,2763
BEGIN DESCRIPTION:
Mapping XS b8fc5207
END DESCRIPTION:
XS GIS Cut Line= 4
      2686915.24      6942957.95      2684423.93      6941803.45
      2683673.93      6941619.42      2681709.44      6940981.93
#Sta/Elev= 30
  2261.9  472.92  2455.4  472.21  2657.8  462.91  2802.9  458.84  2803.5  458.82
  2900.3  455.94  3131.8  454.66  3585.1  454.75    4278  456.49  4691.7  455.13
  4972.4  458.51  4977.9  458.06  4981.9  445.52  4984.4  445.02  5006.9  445.52
  5007.7  451.54  5015.9  457.88  5026.2   458.2  6061.6  457.36  6084.8  454.12
  6175.9  458.08  6213.1  457.99  6239.9   454.7  6378.3  457.73  6436.9  454.81
  6442.2  456.83  6499.1   457.7  6839.6  461.09  7197.1   472.8  7845.3  484.18
#Mann= 9 ,-1 , 0
  2261.9     .05       0  2802.9     .12       0  2803.5     .05       0
  3585.1     .12       0  4691.7     .05       0  4981.9     .07       0
  5006.9     .05       0  6084.8     .12       0  6499.1     .05       0
Bank Sta=4981.9,5006.9
XS Rating Curve= 0 ,0
Exp/Cntr=0.3,0.1

Type RM Length L Ch R = 1 ,49028   ,715,715,715
BEGIN DESCRIPTION:
Muddy Cedar Creek 61.0
END DESCRIPTION:
XS GIS Cut Line= 3
      2687424.18      6942423.81      2684423.93      6940105.31
      2682451.96       6939722.4
#Sta/Elev= 30
  1208.3  472.64  1400.4  471.94  1565.4  470.34  1772.8  463.73  1928.5  462.04
  2042.6  458.89  3034.8  453.46  3403.2  452.94  4131.9  453.61    4217  452.09
  4281.3  453.61    4495  453.13  4930.7  455.56  4951.5  453.41  4959.5  454.84
    4966  452.48  4972.3   447.1  4974.3   440.6  4976.8   440.1  4999.3   440.6
  4999.4  453.32  5038.6  455.62  5263.3  453.97  5681.9  454.66    5823  457.47
  5904.5  455.84  5955.4  458.35  6261.1  461.69  6495.3  469.85  7008.8  473.78
#Mann= 6 ,-1 , 0
  1208.3     .12       0  1400.4     .05       0  3034.8     .12       0
  3403.2     .05       0  4974.3     .07       0  4999.3     .05       0
Bank Sta=4974.3,4999.3
XS Rating Curve= 0 ,0
Exp/Cntr=0.3,0.1

Type RM Length L Ch R = 1 ,48313   ,181,181,181
BEGIN DESCRIPTION:
Muddy Cedar Creek 60.0
END DESCRIPTION:
XS GIS Cut Line= 5
      2687435.87      6939483.85      2685394.17      6939843.23
      2684668.14      6939667.81      2683808.87      6939281.19
      2683385.26      6938909.66
#Sta/Elev= 30
    2180  464.25  2378.9  463.25  3398.3  453.85  3403.6  453.16  3408.7  445.34
  3418.6  445.21  3438.9  453.12  3570.9  447.54  3713.1  453.56  3754.3  449.56
  3973.7  451.21  4115.1  451.95  4381.5  453.18  4479.2  453.56  4928.5  454.64
  4950.8  455.42  4960.5   452.2  4979.4  440.24  4981.9  439.74  5004.4  440.24
  5006.1   453.8  5029.3  455.19  5035.2  451.51  5057.9  454.97  5118.8  453.57
  5369.8   453.2  5484.8  456.01    5739  453.54  5994.1  461.86  6505.7  465.41
#Mann= 10 ,-1 , 0
    2180     .12       0  2378.9     .05       0  3973.7     .12       0
  4115.1     .05       0  4381.5     .12       0  4479.2     .05       0
  4928.5     .12       0  4979.4     .07       0  5004.4     .12       0
  5118.8     .05       0
Bank Sta=4979.4,5004.4
XS Rating Curve= 0 ,0
Exp/Cntr=0.3,0.1

Type RM Length L Ch R = 1 ,48132   ,1968,1968,1968
BEGIN DESCRIPTION:
Mapping XS 5beb67a2
END DESCRIPTION:
XS GIS Cut Line= 6
      2687232.67      6939301.58      2685550.42      6939676.56
      2685290.01      6939681.77      2684717.09      6939504.69
      2683883.76      6939186.98      2683477.51      6938827.61
#Sta/Elev= 30
    2428  460.78  3142.3  456.55  3305.7  452.62  3572.1  454.95  3613.1  453.07
  3633.5  450.01    3641  444.63  3646.1  444.45    3654  450.75    3695  453.01
  4022.9  452.51  4057.9   448.6  4084.3  452.02    4186  452.75  4940.6  454.76
  4960.2     454  4970.7  451.76    4976  446.26  5002.4  444.96  5006.5  441.09
  5023.6  441.96  5032.5  439.47    5035  438.97  5057.5  439.47  5062.7  452.06
    5068  454.95  5152.9   452.5  5711.9  452.36  6161.3  460.85    6446  462.81
#Mann= 5 ,-1 , 0
    2428     .05       0  4940.6     .12       0  5006.5     .05       0
  5032.5     .07       0  5057.5     .05       0
Bank Sta=5032.5,5057.5
XS Rating Curve= 0 ,0
Exp/Cntr=0.3,0.1

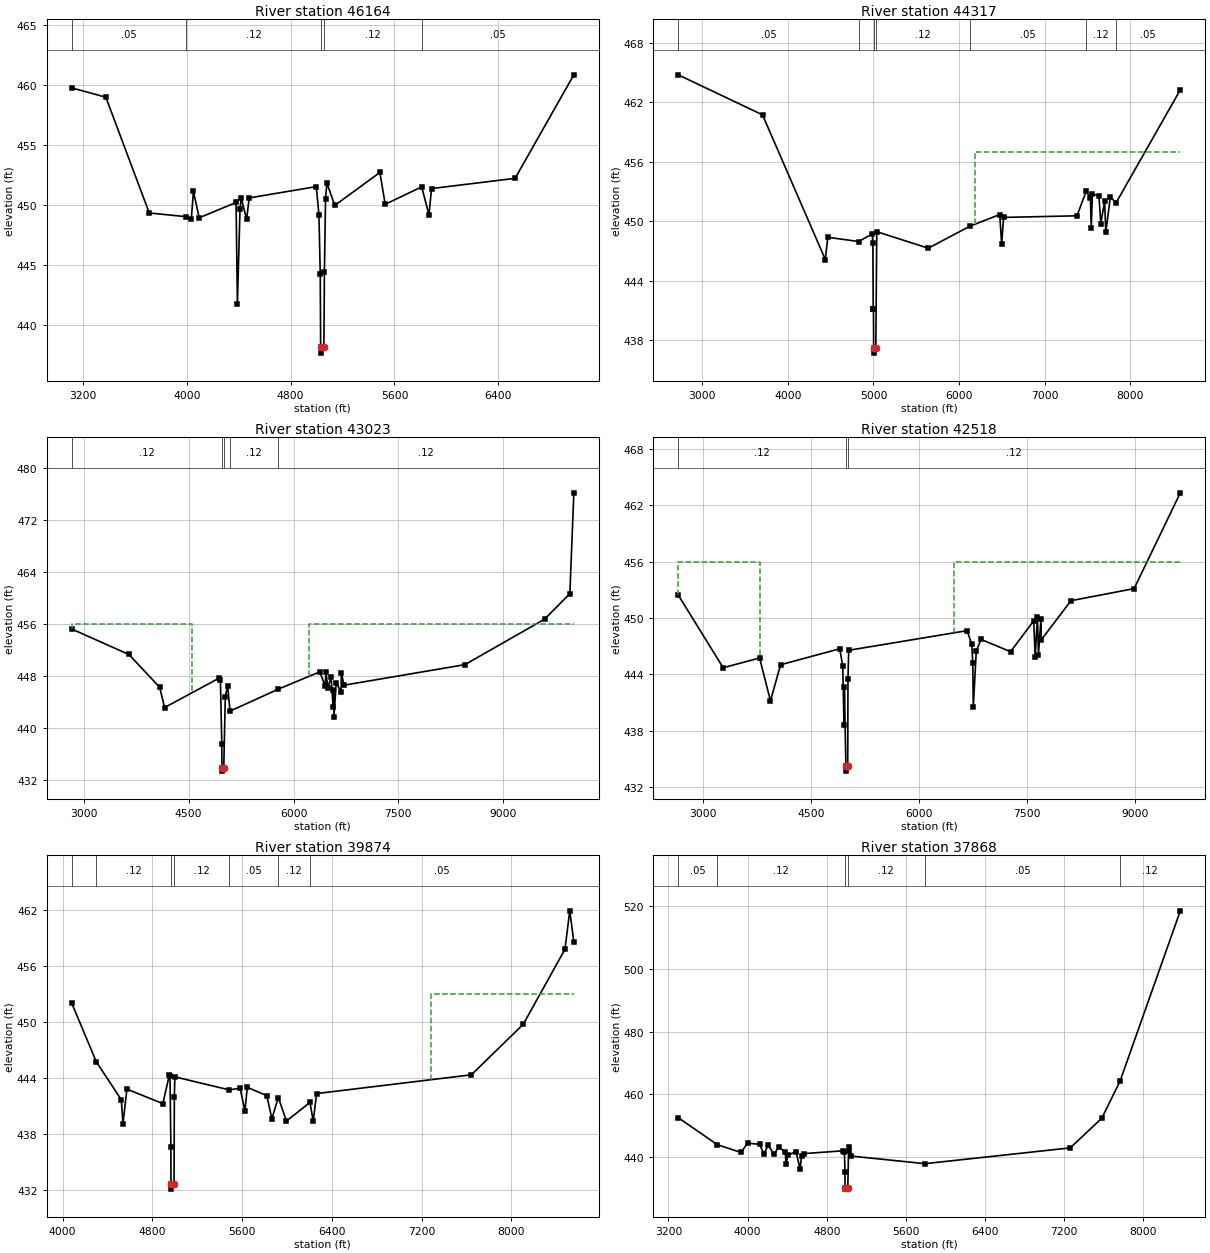
Type RM Length L Ch R = 1 ,46164   ,1847,1847,1847
BEGIN DESCRIPTION:
Mapping XS 08298f16
END DESCRIPTION:
XS GIS Cut Line= 3
      2687334.96      6938667.35      2685423.47      6938354.84
      2683532.87      6938745.46
#Sta/Elev= 30
  3114.1  459.73  3376.5  458.96  3710.9  449.33    3995  449.02  4035.1  448.85
  4051.2  451.12  4095.9  448.93  4379.6   450.2  4389.8  441.79    4410  449.62
  4419.6  450.57  4460.7   448.8  4480.9  450.58  4997.7  451.52    5018  449.17
  5028.1  444.24  5031.1  438.17  5033.6  437.67  5056.1  438.17  5060.2  444.42
  5068.8  450.47    5079  451.81  5140.3  449.96  5487.5   452.7  5528.3  450.05
  5809.7   451.5  5865.3  449.19  5885.7  451.36    6529  452.21  6981.5  460.82
#Mann= 5 ,-1 , 0
  3114.1     .05       0    3995     .12       0  5031.1     .07       0
  5056.1     .12       0  5809.7     .05       0
Bank Sta=5031.1,5056.1
XS Rating Curve= 0 ,0
Exp/Cntr=0.3,0.1

Type RM Length L Ch R = 1 ,44317   ,1294,1294,1294
BEGIN DESCRIPTION:
Muddy Cedar Creek 59.0
END DESCRIPTION:
XS GIS Cut Line= 4
      2688301.03      6938536.02      2686506.22      6937131.09
      2686385.03      6937079.62      2683294.82      6938614.81
#Sta/Elev= 30
  2720.7  464.75  3704.5  460.72  4437.8  446.15  4466.7  448.39  4828.2  447.96
  4986.6  448.74    4993  447.79    4997   441.2    5000   441.2  5002.1  437.22
  5004.6  436.72  5027.4  437.22  5038.4  448.95  5639.6  447.29  6125.2   449.5
  6474.1  450.68  6496.5  447.67  6518.9  450.39  7375.8  450.55  7482.5  453.01
  7532.7  452.39  7542.4  449.29  7555.1  452.75  7631.8  452.58  7654.1  449.76
  7698.8  452.06  7711.9  448.91  7765.8  452.46  7831.9  451.86  8582.2  463.24
#Mann= 7 ,-1 , 0
  2720.7     .05       0  4828.2     .12       0  5002.1     .07       0
  5027.4     .12       0  6125.2     .05       0  7482.5     .12       0
  7831.9     .05       0
#XS Ineff= 2 , 0
       0                  6182.8       0     457
Permanent Ineff=
       F       F
Bank Sta=5002.1,5027.4
XS Rating Curve= 0 ,0
Exp/Cntr=0.3,0.1

Type RM Length L Ch R = 1 ,43023   ,505,505,505
BEGIN DESCRIPTION:
Muddy Cedar Creek 54.0
END DESCRIPTION:
XS GIS Cut Line= 3
      2689072.54      6935559.27      2686970.59       6936108.8
      2682132.18      6937409.91
#Sta/Elev= 30
  2827.4  455.21  3645.1   451.3  4084.8  446.27  4155.3  443.15  4932.4  447.65
  4953.8  447.39  4973.7  437.59  4976.3  433.88  4978.8  433.38  5001.9  433.88
    5024  444.79  5056.5   446.5  5091.6   442.6  5783.7  445.98  6376.2  448.64
  6450.9  446.47  6464.8  448.61  6490.9  446.12  6537.3  447.91  6565.6  443.29
  6570.8  445.86  6578.8  441.75  6610.8  446.98  6680.3  445.54  6685.5  448.49
  6720.3  446.58  8451.4  449.74  9592.1  456.73  9953.1  460.64 10010.3  476.14
#Mann= 5 ,-1 , 0
  2827.4     .12       0  4976.3     .07       0  5001.9     .12       0
  5091.6     .12       0  5783.7     .12       0
#XS Ineff= 2 , 0
       0  4554.6     456  6221.5       0     456
Permanent Ineff=
       F       F
Bank Sta=4976.3,5001.9
XS Rating Curve= 0 ,0
Exp/Cntr=0.3,0.1

Type RM Length L Ch R = 1 ,42518   ,2644,2644,2644
BEGIN DESCRIPTION:
Mapping XS d9cf2727
END DESCRIPTION:
XS GIS Cut Line= 3
       2689334.8      6935026.14      2687073.51       6935668.5
      2682610.53      6936884.41
#Sta/Elev= 30
    2654  452.45  3278.7  444.71  3784.3  445.75  3935.5  441.19  4076.2  445.03
  4898.2  446.73  4939.8  444.89  4957.2  438.65  4962.4   442.7  4983.5   434.2
    4986   433.7  5009.1   434.2  5012.5  443.56  5022.9  446.57  6667.4  448.66
    6733   447.2  6746.9  445.21  6753.8  440.53  6795.2  446.48    6861  447.73
    7272  446.42  7593.3  449.71    7614  445.84  7645.1  450.12  7659.4  446.12
    7694  449.94  7699.2  447.69  8110.5  451.85  8988.5  453.14  9630.4  463.34
#Mann= 3 ,-1 , 0
    2654     .12       0  4983.5     .07       0  5009.1     .12       0
#XS Ineff= 2 , 0
       0  3784.3     456    6484       0     456
Permanent Ineff=
       F       F
Bank Sta=4983.5,5009.1
XS Rating Curve= 0 ,0
Exp/Cntr=0.3,0.1

Type RM Length L Ch R = 1 ,39874   ,2006,2006,2006
BEGIN DESCRIPTION:
Mapping XS adb595b8
END DESCRIPTION:
XS GIS Cut Line= 3
      2689395.56      6934982.73      2688826.99      6934270.93
      2685801.04      6932386.03
#Sta/Elev= 30
  4081.7  451.99  4300.9   445.7  4523.5  441.65  4537.9  439.06  4573.2  442.79
  4893.4  441.23    4951  444.27  4957.4  444.14  4965.4  436.54  4966.3  432.57
  4968.9  432.07  4993.4  432.57  4996.2  441.99  5000.9   444.1  5486.9   442.7
  5582.7  442.89  5625.2  440.44  5646.4  442.98  5819.9  442.09  5865.7  439.63
  5923.6  441.88  5995.3  439.36  6205.5  441.36  6234.1  439.36  6264.8  442.31
  7644.4  444.32  8106.9  449.74  8478.7  457.77  8521.2  461.89  8557.7  458.55
#Mann= 7 ,-1 , 0
  4081.7     .05       0  4300.9     .12       0  4966.3     .07       0
  4993.4     .12       0  5486.9     .05       0  5923.6     .12       0
  6205.5     .05       0
#XS Ineff= 2 , 0
       0                    7288       0     453
Permanent Ineff=
       F       F
Bank Sta=4966.3,4993.4
XS Rating Curve= 0 ,0
Exp/Cntr=0.3,0.1

Type RM Length L Ch R = 1 ,37868   ,1182,1182,1182
BEGIN DESCRIPTION:
Mapping XS 8b51ee6b
END DESCRIPTION:
XS GIS Cut Line= 3
      2690909.46       6934591.9      2689944.19      6933196.08
      2687389.84      6930988.78
#Sta/Elev= 30
  3299.7  452.58  3694.4  443.96  3934.5  441.47  4000.1  444.44  4122.4  444.08
  4164.3  440.92  4208.9  443.82  4265.7  440.96  4316.4  443.19  4381.9  441.64
    4388  437.77  4408.9  440.65  4489.4  441.74  4531.3  436.27  4546.1  440.39
  4567.1  441.11  4963.8  442.01  4978.6  441.73  4984.8  435.18    4985   430.3
  4987.8   429.8  5012.8   430.3  5020.8  442.01  5027.5  443.26  5048.3  440.33
  5792.5  437.91  7260.7  442.94  7579.9  452.41  7763.6  464.19  8372.7  518.46
#Mann= 6 ,-1 , 0
  3299.7     .05       0  3694.4     .12       0    4985     .07       0
  5012.8     .12       0  5792.5     .05       0  7763.6     .12       0
Bank Sta=4985,5012.8
XS Rating Curve= 0 ,0
Exp/Cntr=0.3,0.1