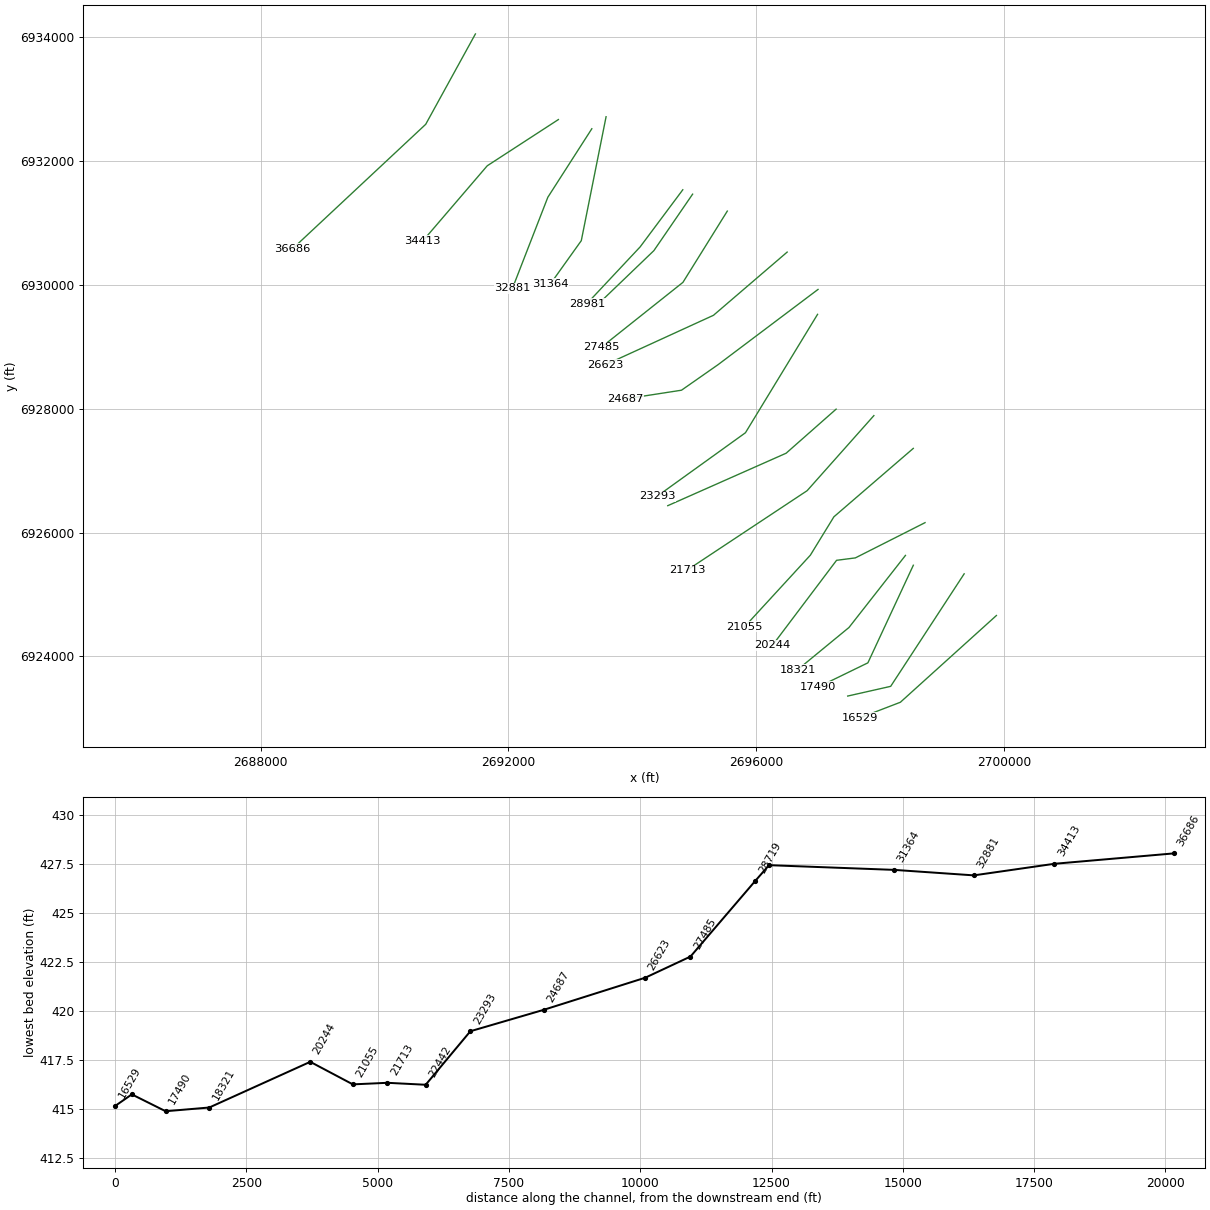
HEC-RAS study Muddy Cedar Creek.prj: Muddy Cedar Creek Base Level Engineering

--- Muddy Cedar Creek.g01 (geometry) --- (continued)

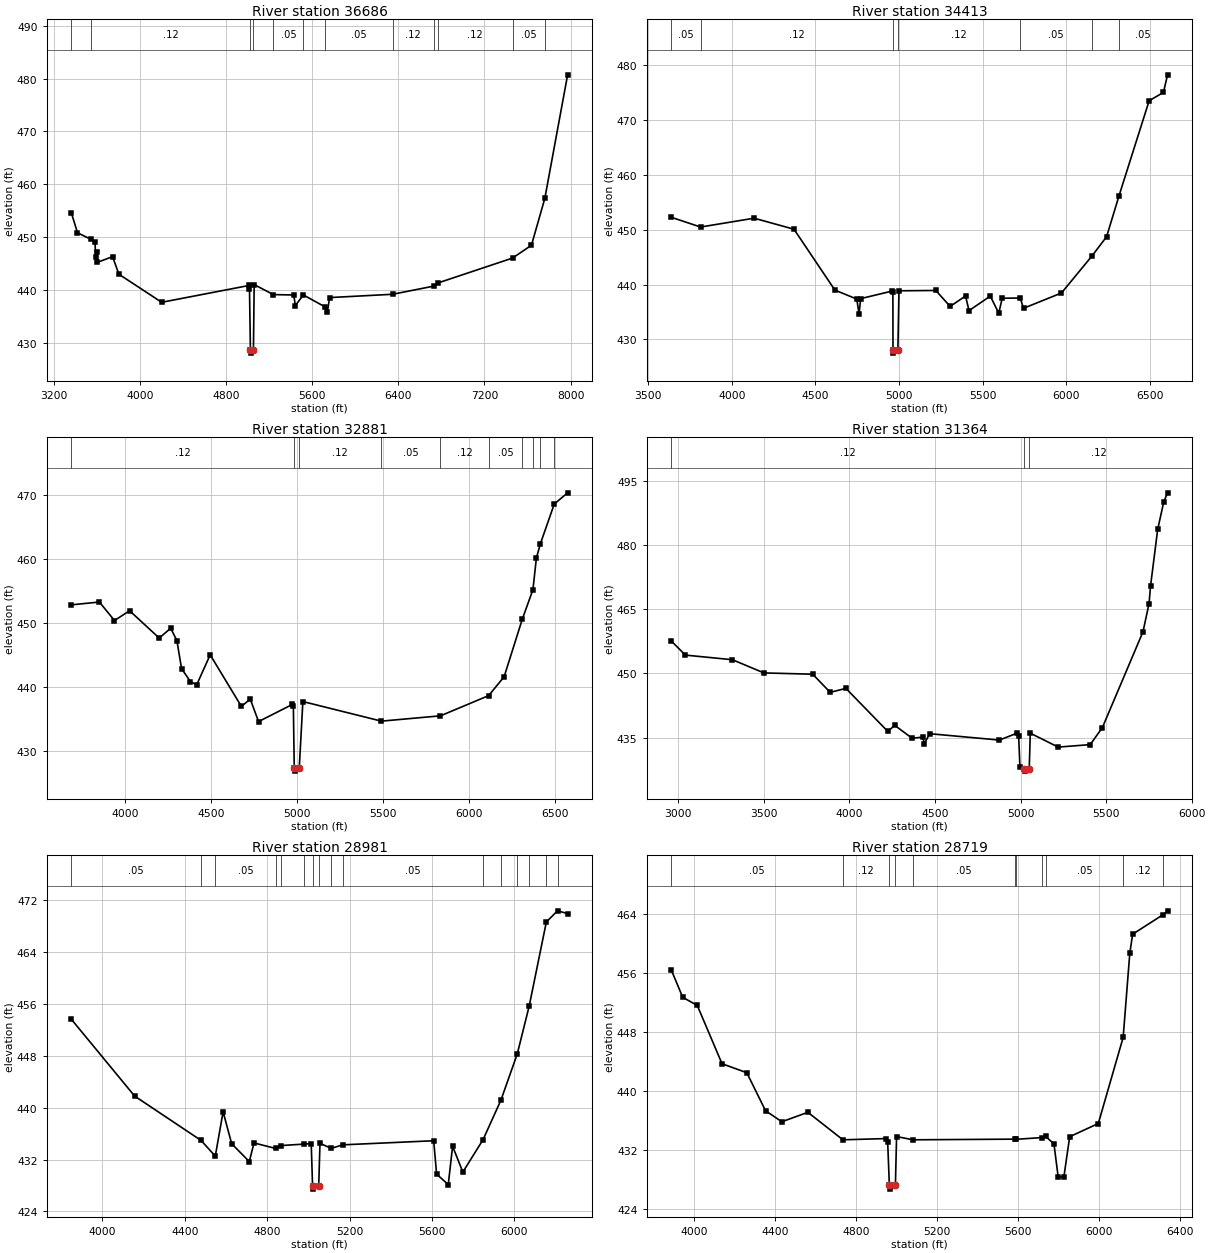
Type RM Length L Ch R = 1 ,36686   ,2273,2273,2273
BEGIN DESCRIPTION:
Mapping XS 1dd428ae
END DESCRIPTION:
XS GIS Cut Line= 3
      2691466.74      6934047.09      2690664.67      6932588.79
      2688513.63      6930578.37
#Sta/Elev= 30
  3364.1  454.51    3420  450.83  3541.9   449.6  3582.9  448.99  3588.6  446.26
  3598.9  447.22  3604.6  445.22  3745.7   446.3  3804.7  442.97  4202.3  437.66
    5012  440.84  5017.7  440.14  5026.4  428.54  5029.1  428.04  5054.2  428.54
  5061.3  441.01  5238.9  439.12  5429.2  439.04  5443.3  437.03  5518.4  439.05
  5721.3  436.77  5740.3  435.74  5761.8  438.55  6347.9  439.18  6728.6  440.72
  6766.6  441.31  7460.8  446.03  7636.7  448.45  7761.3  457.35  7972.7  480.71
#Mann= 12 ,-1 , 0
  3364.1     .05       0  3541.9     .12       0  5026.4     .07       0
  5054.2     .12       0  5238.9     .05       0  5518.4     .12       0
  5721.3     .05       0  6347.9     .12       0  6728.6     .05       0
  6766.6     .12       0  7460.8     .05       0  7761.3     .12       0
Bank Sta=5026.4,5054.2
XS Rating Curve= 0 ,0
Exp/Cntr=0.3,0.1

Type RM Length L Ch R = 1 ,34413   ,1532,1532,1532
BEGIN DESCRIPTION:
Mapping XS 1c8d4e71
END DESCRIPTION:
XS GIS Cut Line= 3
      2692806.17      6932665.61       2691657.8      6931919.44
      2690616.92      6930705.08
#Sta/Elev= 30
  3638.2  452.26  3812.5  450.49  4133.2   452.1  4371.7  450.09  4616.3     439
  4747.5  437.36  4761.2  434.61  4770.4  437.44  4957.6  438.81  4963.5  438.69
  4964.1  428.01  4966.9  427.51  4993.3  428.01  4999.8  438.87  5220.4  438.93
    5306  436.02  5398.2  437.92  5419.1  435.26  5546.4   437.9  5596.9  434.79
  5617.7  437.51  5725.3  437.56  5745.1  435.68  5972.3  438.47  6155.5  445.24
  6242.3  448.73  6316.5  456.17  6496.9   473.5  6582.5  475.03  6607.1  478.23
#Mann= 7 ,-1 , 0
  3638.2     .05       0  3812.5     .12       0  4964.1     .07       0
  4993.3     .12       0  5725.3     .05       0  6155.5     .12       0
  6316.5     .05       0
Bank Sta=4964.1,4993.3
XS Rating Curve= 0 ,0
Exp/Cntr=0.3,0.1

Type RM Length L Ch R = 1 ,32881   ,1517,1517,1517
BEGIN DESCRIPTION:
Mapping XS caa4941a
END DESCRIPTION:
XS GIS Cut Line= 3
      2693345.83      6932517.35       2692636.1      6931411.87
      2692065.91      6929944.78
#Sta/Elev= 30
  3686.3   452.9  3848.8  453.34  3936.7  450.45  4024.5  451.98    4197  447.71
  4263.7  449.24  4299.9  447.31  4327.1  442.93  4378.6  440.92    4415   440.4
  4493.6  445.09  4675.2  437.03  4726.8  438.17  4775.2  434.66  4971.9  437.34
  4977.8  437.04  4982.9  427.42  4985.8  426.92  5012.1  427.42  5033.1  437.79
  5490.2  434.73    5834  435.56  6114.6  438.72  6204.5  441.67    6310  450.64
  6372.1  455.27  6392.3  460.23    6416  462.48  6496.2  468.65    6574   470.4
#Mann= 10 ,-1 , 0
  3686.3     .12       0  4982.9     .07       0  5012.1     .12       0
  5490.2     .05       0    5834     .12       0  6114.6     .05       0
    6310     .12       0  6372.1     .05       0    6416     .12       0
  6496.2     .05       0
Bank Sta=4982.9,5012.1
XS Rating Curve= 0 ,0
Exp/Cntr=0.3,0.1

Type RM Length L Ch R = 1 ,31364   ,2383,2383,2383
BEGIN DESCRIPTION:
Muddy Cedar Creek 35.0
END DESCRIPTION:
XS GIS Cut Line= 3
        2693576.        6932711.        2693176.        6930711.
      2692676.02      6930011.03
#Sta/Elev= 30
  2959.3  457.55  3040.9  454.29  3316.2  453.21  3499.8  450.13  3785.3  449.83
  3887.3  445.59  3979.1  446.52  4223.9  436.48  4264.6  437.89  4366.6  434.86
  4427.8  435.15    4438  433.62  4468.6  435.94  4876.5  434.45  4978.5  436.05
  4988.7  435.47  4996.4  428.08  5020.9   427.7  5023.8   427.2  5050.7   427.7
  5056.7  436.06  5220.1  432.81  5406.9  433.39  5478.2  437.37  5715.4  459.73
    5751  466.33  5759.6  470.42  5801.4  483.64    5837   490.1  5859.1  492.18
#Mann= 3 ,-1 , 0
  2959.3     .12       0  5020.9     .07       0  5050.7     .12       0
Bank Sta=5020.9,5050.7
XS Rating Curve= 0 ,0
Exp/Cntr=0.3,0.1

Type RM Length L Ch R = 1 ,28981   ,262,262,262
BEGIN DESCRIPTION:
Muddy Cedar Creek 32.0
END DESCRIPTION:
XS GIS Cut Line= 3
      2694813.92      6931532.18      2694125.75      6930610.43
      2693265.34      6929692.82
#Sta/Elev= 30
  3849.7  453.57  4156.2  441.77  4478.6  434.94  4547.8  432.52  4585.6  439.35
  4627.3  434.43  4712.8  431.68  4735.7  434.55    4841   433.7  4868.5  434.15
    4976  434.37  5013.4  434.45  5019.9  427.94  5022.8  427.44  5049.8  427.94
  5055.9  434.49  5110.8  433.72  5166.6  434.26  5607.8  434.89    5622  429.75
  5678.6  428.14  5699.6  434.04  5749.4  430.07  5847.5  435.06  5934.3  441.15
  6013.5  448.26  6071.5  455.64  6154.6  468.57  6208.8  470.29  6257.9  469.87
#Mann= 16 ,-1 , 0
  3849.7     .05       0  4478.6     .12       0  4547.8     .05       0
    4841     .12       0  4868.5     .05       0    4976     .12       0
  5019.9     .07       0  5049.8     .12       0  5110.8     .12       0
  5166.6     .05       0  5847.5     .12       0  5934.3     .05       0
  6013.5     .12       0  6071.5     .05       0  6154.6     .12       0
  6208.8     .05       0
Bank Sta=5019.9,5049.8
XS Rating Curve= 0 ,0
Exp/Cntr=0.3,0.1

Type RM Length L Ch R = 1 ,28719   ,1234,1234,1234
BEGIN DESCRIPTION:
Mapping XS 689ec2a9
END DESCRIPTION:
XS GIS Cut Line= 3
      2694972.79       6931461.9       2694347.8      6930550.45
      2693375.61      6929617.32
#Sta/Elev= 30
  3886.9  456.33  3942.8  452.66  4014.6  451.56  4137.1  443.65  4259.6  442.43
  4352.3  437.27  4432.9  435.78  4561.5  437.06  4734.7  433.33    4950   433.5
    4956  433.04  4964.3  427.14  4967.2  426.64  4994.2  427.14    5000  433.77
    5082  433.33  5583.4  433.42  5592.2   433.4  5717.6  433.63  5737.1  433.78
    5778  432.78  5799.1  428.23  5827.4  428.35  5855.7  433.75  5997.2  435.54
  6120.1  447.22  6152.9  458.63    6167  461.22  6316.9  463.86  6339.6  464.39
#Mann= 11 ,-1 , 0
  3886.9     .05       0  4734.7     .12       0  4964.3     .07       0
  4994.2     .12       0    5082     .05       0  5583.4     .12       0
  5592.2     .05       0  5717.6     .12       0  5737.1     .05       0
  6120.1     .12       0  6316.9     .05       0
Bank Sta=4964.3,4994.2
XS Rating Curve= 0 ,0
Exp/Cntr=0.3,0.1

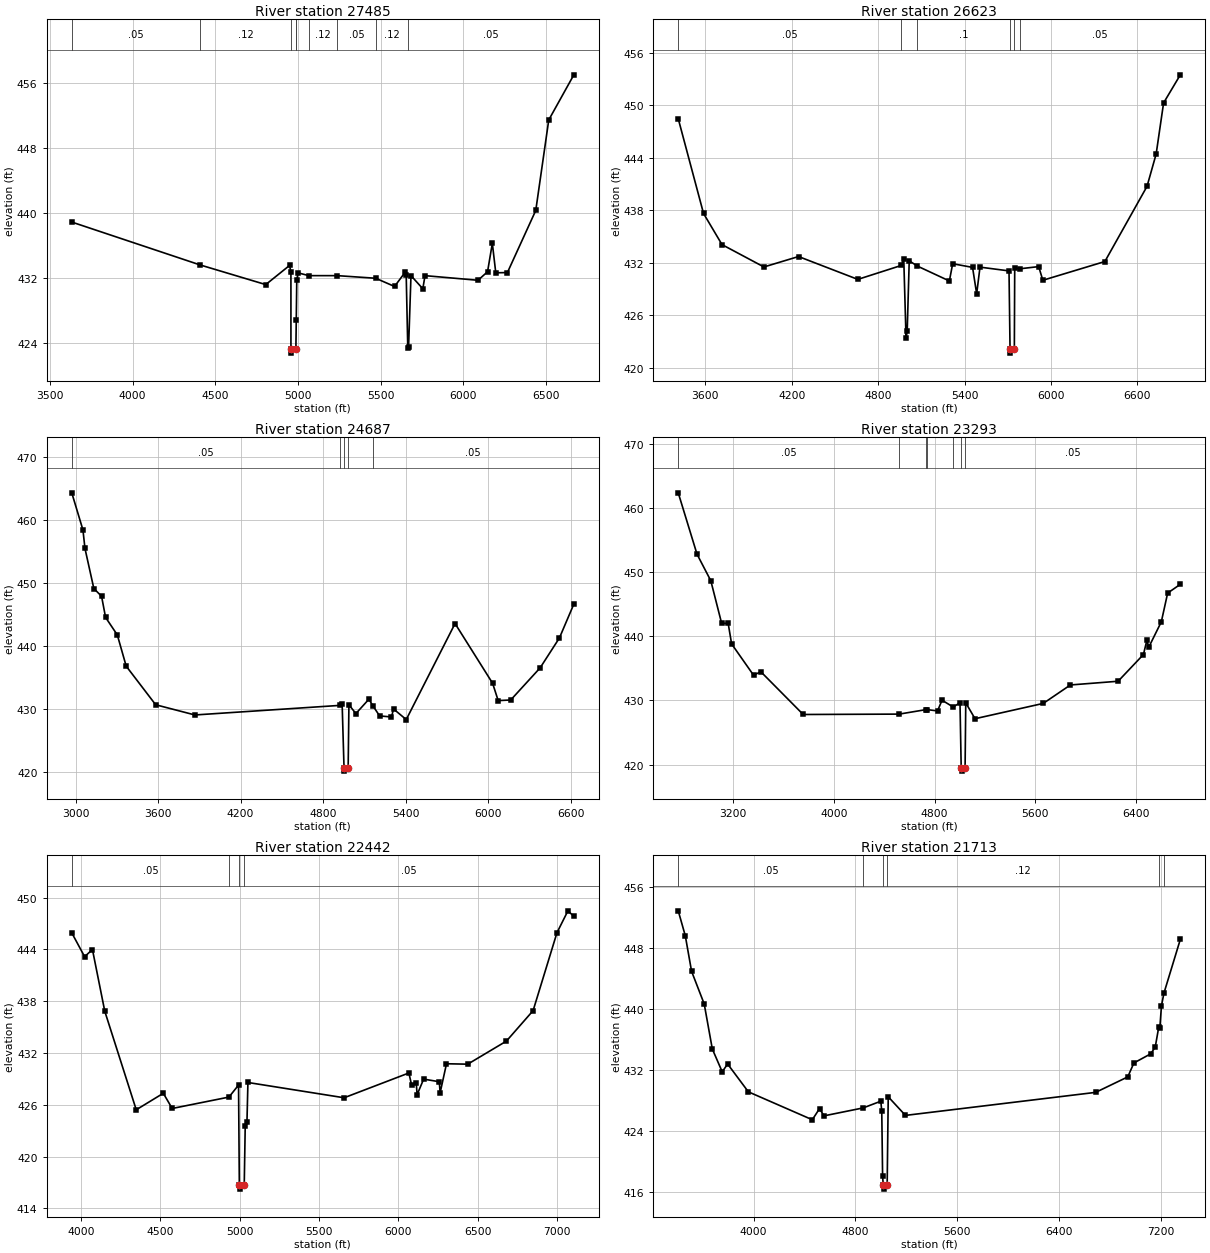
Type RM Length L Ch R = 1 ,27485   ,862,862,862
BEGIN DESCRIPTION:
Mapping XS 4006955a
END DESCRIPTION:
XS GIS Cut Line= 3
       2695532.7      6931188.48      2694816.55      6930038.29
      2693501.43      6928992.28
#Sta/Elev= 30
  3632.1   438.9  4409.1  433.62  4804.8  431.21  4948.5  433.56    4957  432.77
  4957.1  423.28    4960  422.78    4987  423.28  4989.3  426.91  4992.4   431.8
  5000.4  432.65  5065.7  432.31  5237.6  432.31  5469.2  431.99  5583.5  430.98
  5647.5  432.73  5653.9  432.38  5663.4  423.46  5668.4  423.58  5682.8  432.31
  5754.4   430.7  5767.7  432.31    6088  431.74  6145.7  432.79  6174.6  436.29
  6195.4  432.66  6265.8  432.69  6437.2  440.33  6515.7  451.46  6667.4  457.01
#Mann= 9 ,-1 , 0
  3632.1     .05       0  4409.1     .12       0  4957.1     .07       0
    4987     .12       0  4989.3      .1       0  5065.7     .12       0
  5237.6     .05       0  5469.2     .12       0  5663.4     .05       0
Bank Sta=4957.1,4987
XS Rating Curve= 0 ,0
Exp/Cntr=0.3,0.1

Type RM Length L Ch R = 1 ,26623   ,1936,1936,1936
BEGIN DESCRIPTION:
Mapping XS 1f5f31bc
END DESCRIPTION:
XS GIS Cut Line= 3
      2696498.74      6930526.55      2695309.53      6929506.61
       2693564.7      6928707.98
#Sta/Elev= 30
  3412.1  448.47  3587.7  437.65  3716.1  434.09    4007  431.54  4247.3  432.73
  4658.9  430.12    4962  431.72  4977.8  432.44  4993.7  423.38  5001.7  424.22
  5015.7  432.24  5072.3  431.64  5294.4  429.94  5317.4  431.91  5455.4  431.49
  5483.9  428.47    5507  431.52  5708.5  431.09  5715.6   422.2  5718.5   421.7
  5745.5   422.2  5748.1  431.42  5782.7  431.33  5914.6  431.58  5943.2  430.02
  6373.9  432.16  6666.5  440.74    6730  444.44  6781.6  450.27  6897.7  453.48
#Mann= 6 ,-1 , 0
  3412.1     .05       0    4962     .12       0  5072.3      .1       0
  5715.6     .07       0  5745.5      .1       0  5782.7     .05       0
Bank Sta=5715.6,5745.5
XS Rating Curve= 0 ,0
Exp/Cntr=0.3,0.1

Type RM Length L Ch R = 1 ,24687   ,1394,1394,1394
BEGIN DESCRIPTION:
Mapping XS 11c535be
END DESCRIPTION:
XS GIS Cut Line= 4
      2696997.02      6929924.14      2695382.45      6928708.87
      2694793.57      6928297.46      2693892.28      6928157.94
#Sta/Elev= 30
  2972.3  464.26  3053.6  458.36  3068.2  455.43  3132.8  449.06    3189  447.83
  3218.1  444.48  3303.5  441.69  3368.1  436.73  3582.5   430.6  3867.8  428.98
  4921.6   430.5  4938.6  430.68  4952.2  420.56  4955.1  420.06  4982.3  420.56
  4987.8   430.6  5038.4   429.2  5133.4  431.49  5160.9  430.47  5211.1  428.83
  5297.4  428.66  5312.2  429.93  5404.7  428.25  5759.6   443.5  6032.8  434.01
  6073.3  431.26  6164.4  431.36  6378.3  436.46  6518.5  441.21  6623.5  446.59
#Mann= 5 ,-1 , 0
  2972.3     .05       0  4921.6      .1       0  4952.2     .07       0
  4982.3      .1       0  5160.9     .05       0
#XS Ineff= 2 , 0
       0                  5759.6       0   443.5
Permanent Ineff=
       F       F
Bank Sta=4952.2,4982.3
XS Rating Curve= 0 ,0
Exp/Cntr=0.3,0.1

Type RM Length L Ch R = 1 ,23293   ,851,851,851
BEGIN DESCRIPTION:
Muddy Cedar Creek 26.0
END DESCRIPTION:
XS GIS Cut Line= 3
       2696989.5      6929522.22      2695825.44      6927610.78
      2694400.97      6926585.98
#Sta/Elev= 30
    2762  462.41  2911.4  452.83    3021  448.69    3107  442.05  3159.3  442.02
  3186.4  438.83  3360.8  433.95  3419.1  434.48  3755.8  427.81  4519.3  427.87
  4735.5  428.58  4742.3  428.57  4824.1  428.37  4859.9  430.04  4948.3  428.98
  5002.7  429.64  5012.3  419.47  5015.3  418.97  5043.2  419.47  5048.6  429.63
  5122.2  427.15  5664.8  429.54  5880.8  432.42  6260.1     433  6461.4  437.17
  6489.9  439.46  6503.1  438.28  6603.8  442.28  6654.1  446.76  6754.8  448.13
#Mann= 7 ,-1 , 0
    2762     .05       0  4519.3     .12       0  4735.5     .05       0
  4742.3     .12       0  4948.3     .05       0  5012.3     .05       0
  5043.2     .05       0
Bank Sta=5012.3,5043.2
XS Rating Curve= 0 ,0
Exp/Cntr=0.3,0.1

Type RM Length L Ch R = 1 ,22442   ,729,729,729
BEGIN DESCRIPTION:
Mapping XS a8be776a
END DESCRIPTION:
XS GIS Cut Line= 3
        2697289.      6927991.94      2696481.69      6927280.12
      2694571.94      6926433.75
#Sta/Elev= 30
  3942.1  445.92  4023.1  443.16  4072.4  443.99  4150.2  436.84  4348.5  425.43
  4519.2  427.34  4575.2  425.58  4932.9   426.9  4993.5  428.29  4998.5  416.74
  5001.5  416.24  5029.4  416.74  5035.6  423.56  5046.5  423.98  5052.6  428.59
    5659  426.82  6067.2  429.69    6085  428.26  6113.7  428.57  6119.2  427.17
  6160.3  428.98  6258.9  428.68  6264.4   427.4  6304.4  430.76  6438.2  430.71
    6682  433.38  6850.4  436.91    7001  445.94    7070  448.47  7107.3  447.83
#Mann= 4 ,-1 , 0
  3942.1     .05       0  4932.9     .12       0  4998.5     .07       0
  5029.4     .05       0
Bank Sta=4998.5,5029.4
XS Rating Curve= 0 ,0
Exp/Cntr=0.3,0.1

Type RM Length L Ch R = 1 ,21713   ,658,658,658
BEGIN DESCRIPTION:
Mapping XS 3777341d
END DESCRIPTION:
XS GIS Cut Line= 3
      2697898.08      6927887.19      2696821.68      6926676.24
      2694881.58      6925391.52
#Sta/Elev= 30
  3407.7  452.84  3463.2  449.57  3512.5  444.91    3612  440.62  3675.6  434.72
  3753.3  431.73    3796  432.75    3959   429.1  4461.6  425.44  4518.5   426.9
  4553.6  425.95  4861.2  426.99  5000.1  427.87  5007.7  426.59  5014.3  418.11
  5019.3  416.84  5022.3  416.34  5050.2  416.84  5058.6  428.45    5194  426.01
  6689.2  429.03  6941.7  431.06  6990.1  432.89  7121.6  434.08  7157.6  434.96
  7185.4  437.61  7193.6  437.44  7206.7   440.4  7226.2  442.05  7354.8  449.09
#Mann= 6 ,-1 , 0
  3407.7     .05       0  4861.2     .12       0  5019.3     .07       0
  5050.2     .12       0  7185.4     .12       0  7226.2      .1       0
Bank Sta=5019.3,5050.2
XS Rating Curve= 0 ,0
Exp/Cntr=0.3,0.1

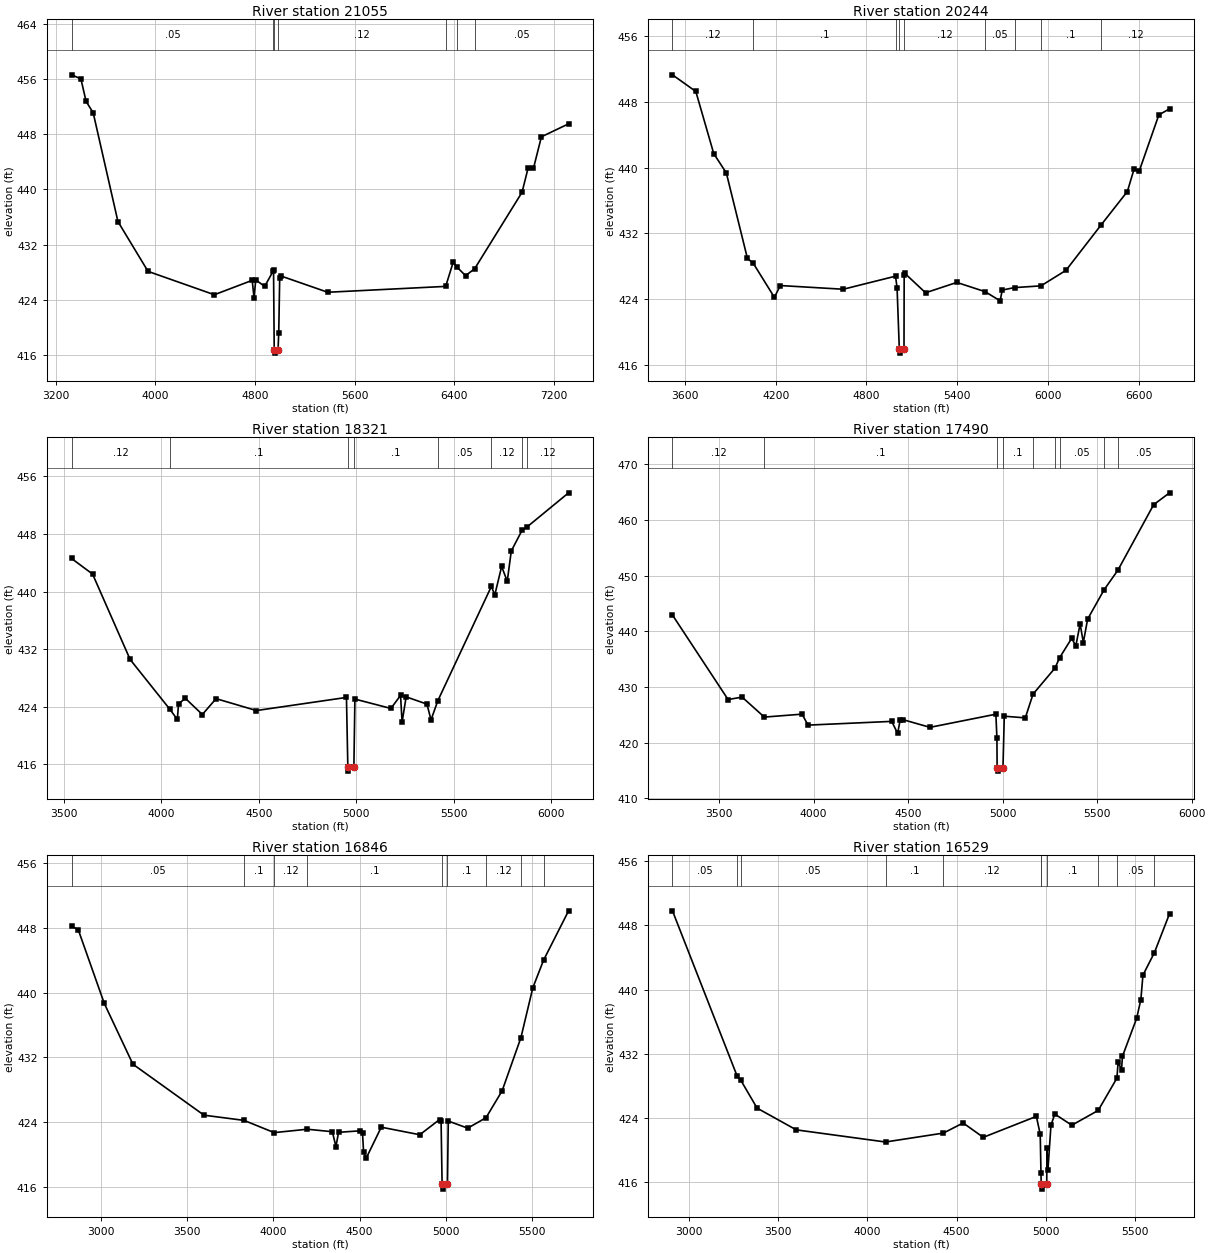
Type RM Length L Ch R = 1 ,21055   ,811,811,811
BEGIN DESCRIPTION:
Mapping XS 3d95a2a8
END DESCRIPTION:
XS GIS Cut Line= 4
      2698534.28      6927358.26      2697253.04       6926254.1
      2696872.83      6925634.31      2695810.65      6924478.41
#Sta/Elev= 30
  3328.4  456.63  3403.6  456.05  3445.3  452.78  3502.3  451.12  3700.9  435.34
  3942.3  428.12  4474.4  424.73  4778.3  426.82  4792.6   424.3  4806.8  426.88
  4878.1  425.94  4947.9  428.21  4949.4   428.3  4954.8  416.76  4957.8  416.26
  4985.7  416.76  4991.1  419.25  4998.8  427.19  5005.4  427.47  5384.1  425.09
  6330.6  425.94  6390.8  429.45  6420.1  428.76    6490   427.5  6562.7  428.49
  6943.2  439.59  6992.5  443.15  7035.1  443.08  7098.6  447.64  7316.7  449.52
#Mann= 7 ,-1 , 0
  3328.4     .05       0  4947.9     .12       0  4954.8     .05       0
  4985.7     .12       0  6330.6     .12       0  6420.1      .1       0
  6562.7     .05       0
Bank Sta=4954.8,4985.7
XS Rating Curve= 0 ,0
Exp/Cntr=0.3,0.1

Type RM Length L Ch R = 1 ,20244   ,1923,1923,1923
BEGIN DESCRIPTION:
Mapping XS 115abe36
END DESCRIPTION:
XS GIS Cut Line= 4
      2698723.85      6926159.54      2697599.75      6925590.98
      2697295.93      6925551.92      2696259.83      6924177.67
#Sta/Elev= 30
  3517.7   451.3  3672.2  449.27  3790.6  441.71  3873.9  439.35  4013.5  428.94
    4052  428.35  4191.8   424.2  4230.7  425.64  4647.1  425.19  4992.7  426.78
    5003  425.38  5017.8  417.91  5020.8  417.41  5048.8  417.91    5050  426.88
  5055.1  427.11  5191.5  424.76    5398  426.02  5584.5   424.9  5684.8  423.78
  5698.5  425.09  5779.6  425.39  5954.3   425.6  6119.9  427.49  6354.4  433.07
  6525.9  437.09  6569.6  439.78    6605  439.61  6734.1  446.42  6804.8  447.16
#Mann= 9 ,-1 , 0
  3517.7     .12       0    4052      .1       0  4992.7     .12       0
  5017.8     .07       0  5048.8     .12       0  5584.5     .05       0
  5779.6     .12       0  5954.3      .1       0  6354.4     .12       0
Bank Sta=5017.8,5048.8
XS Rating Curve= 0 ,0
Exp/Cntr=0.3,0.1

Type RM Length L Ch R = 1 ,18321   ,831,831,831
BEGIN DESCRIPTION:
Mapping XS b85d5b57
END DESCRIPTION:
XS GIS Cut Line= 3
      2698407.89      6925630.88      2697496.45      6924467.72
      2696667.48      6923786.31
#Sta/Elev= 30
  3538.7   444.6  3646.8  442.43  3839.4  430.58  4042.9  423.68  4081.7  422.25
    4088  424.45  4123.3  425.17  4210.1  422.94  4280.6  425.14  4487.6  423.49
  4949.6  425.31  4956.7  415.68  4959.7  415.08  4987.7  415.68    4993  425.08
  5177.7  423.78  5227.2  425.59  5235.1  421.87  5255.9  425.39  5362.8  424.38
  5383.6  422.19  5418.6  424.86  5693.3  440.72  5710.8  439.53    5746  443.49
  5774.7  441.43  5795.5  445.64  5852.5   448.6  5874.9  448.94  6089.5  453.71
#Mann= 8 ,-1 , 0
  3538.7     .12       0  4042.9      .1       0  4956.7     .07       0
  4987.7      .1       0  5418.6     .05       0  5693.3     .12       0
  5852.5      .1       0  5874.9     .12       0
Bank Sta=4956.7,4987.7
XS Rating Curve= 0 ,0
Exp/Cntr=0.3,0.1

Type RM Length L Ch R = 1 ,17490   ,644,644,644
BEGIN DESCRIPTION:
Mapping XS ebf5a8cb
END DESCRIPTION:
XS GIS Cut Line= 3
      2698535.21      6925472.59      2697801.72      6923897.11
      2696999.92      6923507.05
#Sta/Elev= 30
  3253.4  442.91  3547.6  427.74  3621.7  428.18  3739.4  424.59  3939.1  425.12
  3970.4  423.15  4413.4  423.82  4444.5  421.66  4457.5  423.98  4472.9  424.13
  4615.7  422.75  4964.3  425.11  4969.8  420.78  4970.8  415.49  4973.8  414.89
  5001.8  415.49  5008.7  424.75  5119.9  424.45  5160.8  428.71  5276.9  433.39
  5301.5  435.25  5364.8  438.71  5387.4  437.41  5409.9  441.32  5426.9  437.98
  5449.5  442.17  5536.8  447.45  5609.7  450.96  5798.9  462.72  5882.9  464.85
#Mann= 9 ,-1 , 0
  3253.4     .12       0  3739.4      .1       0  4970.8     .07       0
  5001.8      .1       0  5160.8     .05       0  5276.9      .1       0
  5301.5     .05       0  5536.8     .12       0  5609.7     .05       0
Bank Sta=4970.8,5001.8
XS Rating Curve= 0 ,0
Exp/Cntr=0.3,0.1

Type RM Length L Ch R = 1 ,16846   ,317,317,317
BEGIN DESCRIPTION:
Muddy Cedar Creek 17.0
END DESCRIPTION:
XS GIS Cut Line= 3
      2699355.55      6925333.76      2698169.51      6923517.76
      2697476.01        6923361.
#Sta/Elev= 30
    2831  448.19    2870  447.75  3020.8  438.66  3186.7  431.16  3598.7  424.87
  3830.6  424.23  4005.2  422.72    4197  423.14  4342.1  422.83  4363.1     421
  4378.3  422.76    4502  422.94  4517.1  422.68  4523.1  420.35  4538.2  419.56
  4625.7  423.39  4848.9  422.46  4963.5  424.33  4972.2  424.21  4978.2  416.35
  4981.2  415.75  5009.2  416.35  5013.9  424.15  5126.6  423.27  5232.7  424.56
    5326  427.88  5434.6  434.42  5503.9  440.59  5566.2     444    5711  450.08
#Mann= 9 ,-1 , 0
    2831     .05       0  3830.6      .1       0  4005.2     .12       0
    4197      .1       0  4978.2     .07       0  5009.2      .1       0
  5232.7     .12       0  5434.6     .05       0  5566.2     .12       0
Bank Sta=4978.2,5009.2
XS Rating Curve= 0 ,0
Exp/Cntr=0.3,0.1

Type RM Length L Ch R = 1 ,16529   ,775,775,775
BEGIN DESCRIPTION:
Muddy Cedar Creek 16.0
END DESCRIPTION:
XS GIS Cut Line= 3
      2699875.99      6924660.99        2698326.        6923261.
      2697675.97      6923010.99
#Sta/Elev= 30
  2907.5  449.82    3270  429.23  3290.9   428.7  3381.6  425.25  3601.3  422.54
  4101.3  421.03  4425.5  422.14  4536.2   423.4    4649  421.61  4946.5  424.22
  4968.1  421.99  4972.3  417.14  4973.5  415.76  4976.5  415.16  5004.5  415.76
  5005.8   420.3  5011.1   417.5  5028.3  423.12  5049.7  424.51  5145.1  423.12
  5292.9  424.96    5398  428.99  5404.4  430.97  5423.6  430.04    5429  431.71
  5508.3  436.43  5531.9  438.76  5543.6  441.81  5608.2  444.63  5692.6  449.46
#Mann= 11 ,-1 , 0
  2907.5     .05       0    3270     .12       0  3290.9     .05       0
  4101.3      .1       0  4425.5     .12       0  4972.3      .1       0
  4973.5     .07       0  5004.5      .1       0  5292.9     .12       0
    5398     .05       0  5608.2     .12       0
Bank Sta=4973.5,5004.5
XS Rating Curve= 0 ,0
Exp/Cntr=0.3,0.1