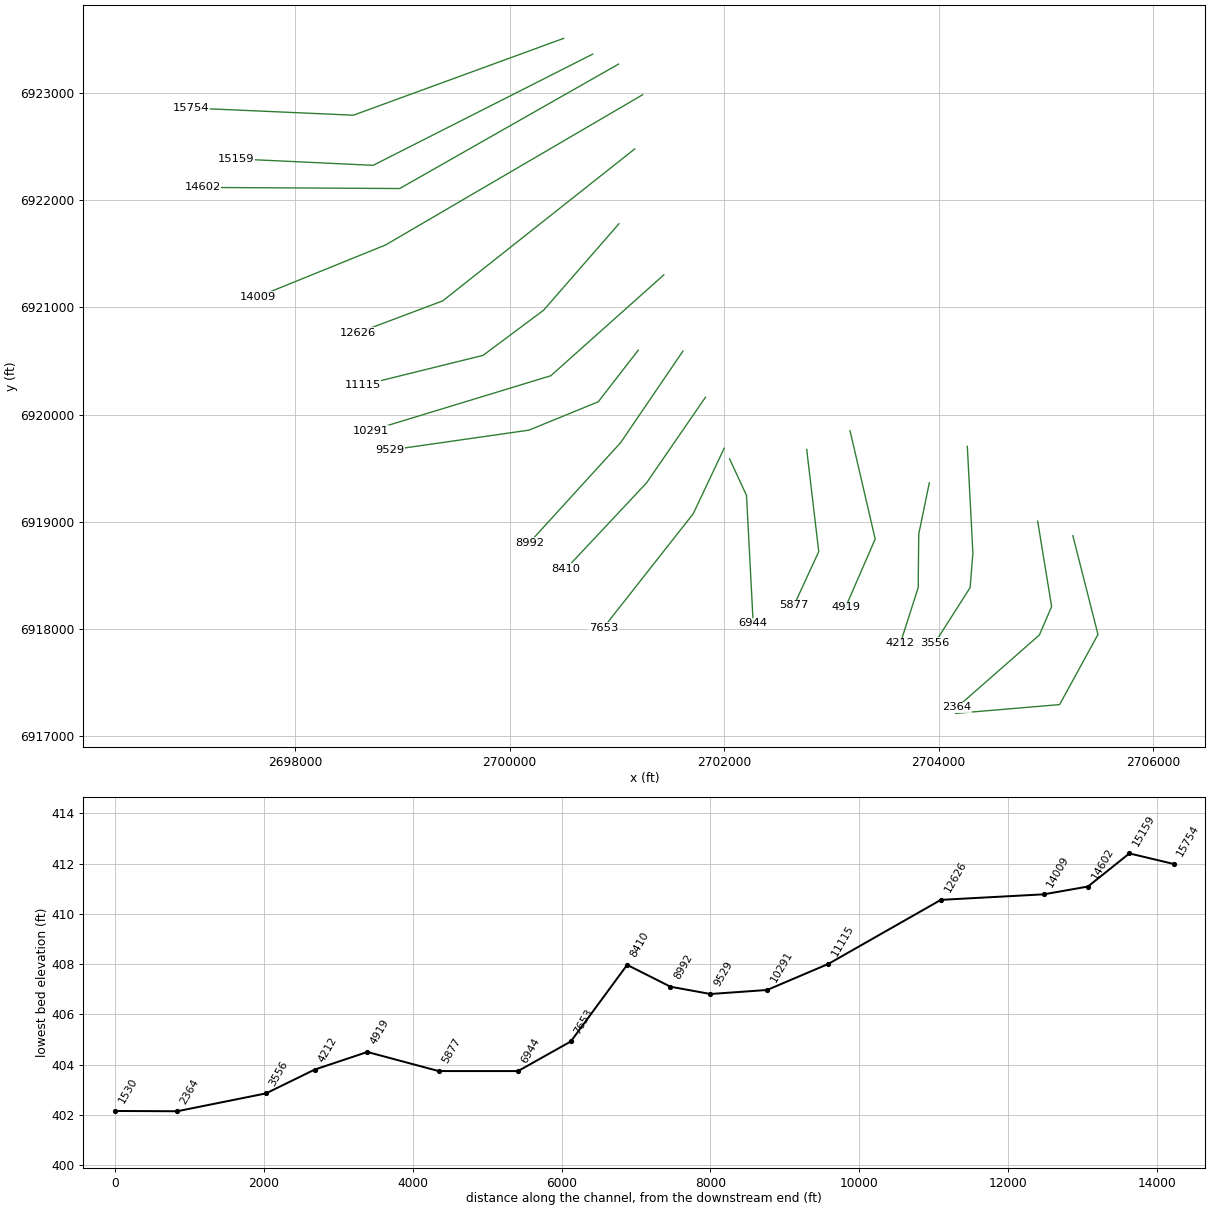
HEC-RAS study Muddy Cedar Creek.prj: Muddy Cedar Creek Base Level Engineering

--- Muddy Cedar Creek.g01 (geometry) --- (continued)

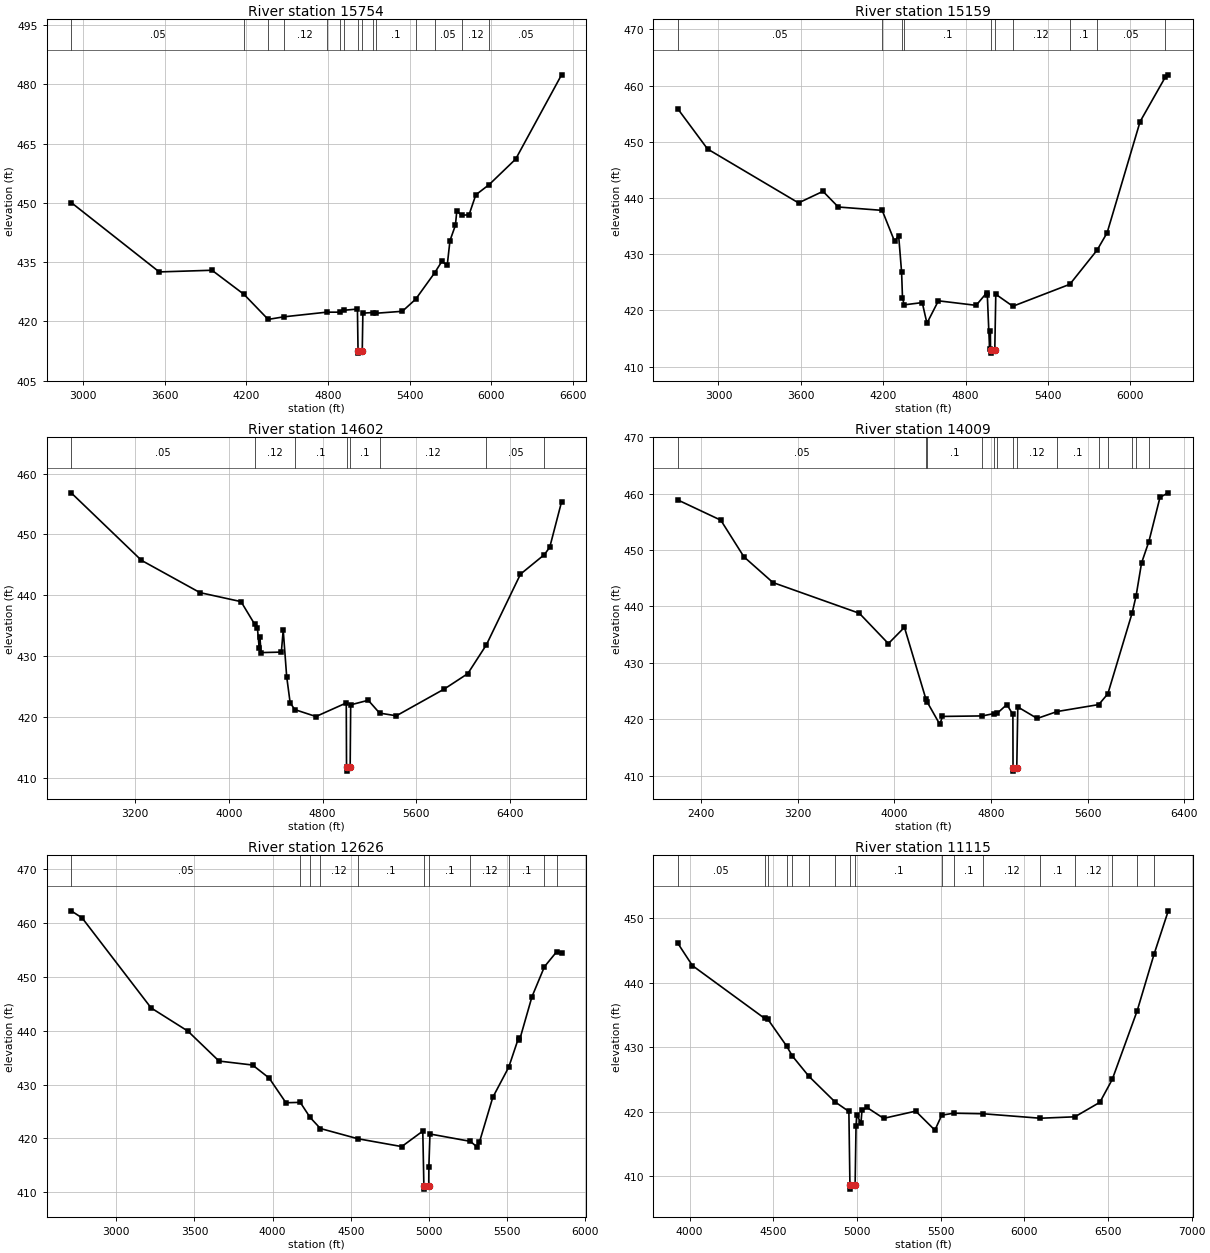
Type RM Length L Ch R = 1 ,15754   ,595,595,595
BEGIN DESCRIPTION:
Muddy Cedar Creek 15.0
END DESCRIPTION:
XS GIS Cut Line= 3
       2700504.3      6923511.42      2698542.06      6922793.95
      2697026.04        6922861.
#Sta/Elev= 30
  2910.7  450.08  3558.4  432.53  3946.4  432.95  4181.9  426.85  4359.4  420.52
  4474.4  421.17    4790  422.35  4888.5  422.35  4917.7  422.83  5016.1  423.14
  5020.6  412.59  5023.6  411.99  5051.6  412.59  5056.1   422.1  5130.8  422.26
  5153.2  422.08  5346.4  422.57  5444.2  425.62  5584.6  432.32  5636.7  435.17
  5676.7  434.24  5696.7  440.43  5736.8  444.33  5746.8  447.85    5783  446.88
  5836.9  446.96  5886.9  452.03  5984.8  454.61  6180.1  461.07  6517.5  482.38
#Mann= 15 ,-1 , 0
  2910.7     .05       0  4181.9     .12       0  4359.4      .1       0
  4474.4     .12       0    4790      .1       0  4888.5     .12       0
  4917.7      .1       0  5020.6     .07       0  5051.6      .1       0
  5130.8     .12       0  5153.2      .1       0  5444.2     .12       0
  5584.6     .05       0    5783     .12       0  5984.8     .05       0
Bank Sta=5020.6,5051.6
XS Rating Curve= 0 ,0
Exp/Cntr=0.3,0.1

Type RM Length L Ch R = 1 ,15159   ,557,557,557
BEGIN DESCRIPTION:
Muddy Cedar Creek 14.0
END DESCRIPTION:
XS GIS Cut Line= 3
       2700773.7      6923363.72      2698726.13      6922326.04
      2697451.04        6922386.
#Sta/Elev= 30
  2704.5  455.85  2920.6  448.73  3583.1  439.14  3761.3   441.2  3872.7  438.41
  4192.6  437.81  4282.6  432.31  4312.5   433.3    4334   426.8  4340.4  422.29
  4352.1     421  4484.4   421.4  4518.5  417.73    4602  421.72  4876.8  420.91
  4952.8  423.12  4958.4  422.73    4975  413.07  4980.6  416.36  4981.8  413.01
  4984.8  412.41  5012.8  413.01  5020.1  422.88  5144.3  420.75  5559.5  424.66
    5758  430.74    5831  433.82  6071.3  453.61  6254.1  461.49  6276.5  461.93
#Mann= 10 ,-1 , 0
  2704.5     .05       0  4192.6      .1       0    4334     .05       0
  4352.1      .1       0  4981.8     .07       0  5012.8      .1       0
  5144.3     .12       0  5559.5      .1       0    5758     .05       0
  6254.1     .12       0
Bank Sta=4981.8,5012.8
XS Rating Curve= 0 ,0
Exp/Cntr=0.3,0.1

Type RM Length L Ch R = 1 ,14602   ,593,593,593
BEGIN DESCRIPTION:
Mapping XS 06efccf7
END DESCRIPTION:
XS GIS Cut Line= 3
       2701015.5      6923270.86       2698973.8      6922109.38
      2697135.28       6922119.8
#Sta/Elev= 30
  2653.7  456.85  3253.6  445.75  3753.7  440.44    4104  438.96  4219.7  435.27
  4243.8  434.67  4259.6  431.28  4265.4   433.1  4275.3  430.58  4448.4  430.66
  4464.3  434.28  4493.9  426.63  4523.4  422.34  4562.9  421.21  4743.9  420.07
  5002.7   422.3    5005  411.69    5008  411.09    5036  411.69  5040.5  421.99
  5190.5  422.74  5287.4  420.63  5430.5  420.19  5840.5   424.6  6040.5  427.12
  6199.6  431.87  6490.5  443.48  6694.7  446.69  6740.5  447.91  6841.2  455.37
#Mann= 8 ,-1 , 0
  2653.7     .05       0  4219.7     .12       0  4562.9      .1       0
    5005     .07       0    5036      .1       0  5287.4     .12       0
  6199.6     .05       0  6694.7     .12       0
Bank Sta=5005,5036
XS Rating Curve= 0 ,0
Exp/Cntr=0.3,0.1

Type RM Length L Ch R = 1 ,14009   ,1383,1383,1383
BEGIN DESCRIPTION:
Mapping XS bcd03b08
END DESCRIPTION:
XS GIS Cut Line= 3
      2701239.41      6922984.38      2698843.59      6921583.34
       2697650.9      6921098.97
#Sta/Elev= 30
  2205.6  458.86  2560.9  455.28  2752.6  448.78  2993.1  444.22  3708.8  438.77
  3949.3  433.39  4082.4  436.28  4260.4  423.55  4272.5  422.97  4375.7  419.07
  4397.2  420.48  4727.7  420.57  4820.8  420.97  4853.1  421.07  4931.1  422.59
    4981  420.83  4982.1  411.38  4985.1  410.78  5013.1  411.38  5021.6  422.16
  5182.3  420.12  5347.7  421.35  5692.2  422.58  5767.6  424.49  5969.8  438.89
  6001.8  441.87  6046.9  447.69  6107.6  451.49  6199.9  459.34  6268.3  460.13
#Mann= 14 ,-1 , 0
  2205.6     .05       0  4260.4     .12       0  4272.5      .1       0
  4727.7     .12       0  4820.8      .1       0  4853.1     .12       0
  4982.1     .07       0  5013.1     .12       0  5347.7      .1       0
  5692.2     .12       0  5767.6      .1       0  5969.8     .05       0
  6001.8      .1       0  6107.6     .12       0
Bank Sta=4982.1,5013.1
XS Rating Curve= 0 ,0
Exp/Cntr=0.3,0.1

Type RM Length L Ch R = 1 ,12626   ,1511,1511,1511
BEGIN DESCRIPTION:
Muddy Cedar Creek 10.0
END DESCRIPTION:
XS GIS Cut Line= 3
      2701166.49      6922479.16        2699376.        6921061.
      2698579.51      6920761.01
#Sta/Elev= 30
    2712   462.3  2782.2  460.97  3222.9  444.25  3458.4  439.93  3657.1  434.37
  3871.9  433.63  3977.6  431.21    4085  426.62  4176.5  426.69  4239.5  423.89
  4305.3  421.83  4544.5  419.93  4825.4  418.47    4960  421.35    4967  411.16
    4970  410.56    4998  411.16  4998.8  414.71  5005.9  420.81  5264.6  419.44
    5306   418.4  5322.2   419.3  5407.5  427.62  5509.5  433.23  5572.7  438.71
  5578.1  438.21    5658  446.33  5737.8  451.91  5816.1   454.7  5847.2  454.46
#Mann= 11 ,-1 , 0
    2712     .05       0  4176.5     .12       0  4239.5      .1       0
  4305.3     .12       0  4544.5      .1       0    4967     .07       0
    4998      .1       0  5264.6     .12       0  5509.5      .1       0
  5737.8     .12       0  5816.1      .1       0
Bank Sta=4967,4998
XS Rating Curve= 0 ,0
Exp/Cntr=0.3,0.1

Type RM Length L Ch R = 1 ,11115   ,824,824,824
BEGIN DESCRIPTION:
Mapping XS 0cd4a069
END DESCRIPTION:
XS GIS Cut Line= 4
      2701018.81      6921780.26      2700315.67      6920972.95
      2699751.43      6920551.95      2698629.17      6920274.63
#Sta/Elev= 30
  3929.6   446.1  4016.2  442.66  4447.3  434.49  4466.9  434.35  4579.8  430.17
  4613.6  428.64  4712.4   425.5  4867.7  421.55  4951.4  420.05  4957.7  408.61
  4960.7  408.01  4988.7  408.61  4994.1  417.72  4998.2  419.56  5023.5  418.23
  5029.7   420.2  5058.9  420.68    5159  418.98  5350.8   420.1  5465.5  417.15
  5506.3  419.47    5578  419.78  5755.1  419.69  6094.9     419    6302  419.22
  6451.4  421.47  6525.3  425.01  6673.9  435.62  6775.3  444.43  6860.2  451.15
#Mann= 17 ,-1 , 0
  3929.6     .05       0  4447.3      .1       0  4466.9     .05       0
  4579.8      .1       0  4613.6     .05       0  4712.4     .12       0
  4867.7      .1       0  4957.7     .07       0  4988.7      .1       0
  5506.3     .12       0    5578      .1       0  5755.1     .12       0
  6094.9      .1       0    6302     .12       0  6525.3      .1       0
  6673.9     .05       0  6775.3      .1       0
Bank Sta=4957.7,4988.7
XS Rating Curve= 0 ,0
Exp/Cntr=0.3,0.1

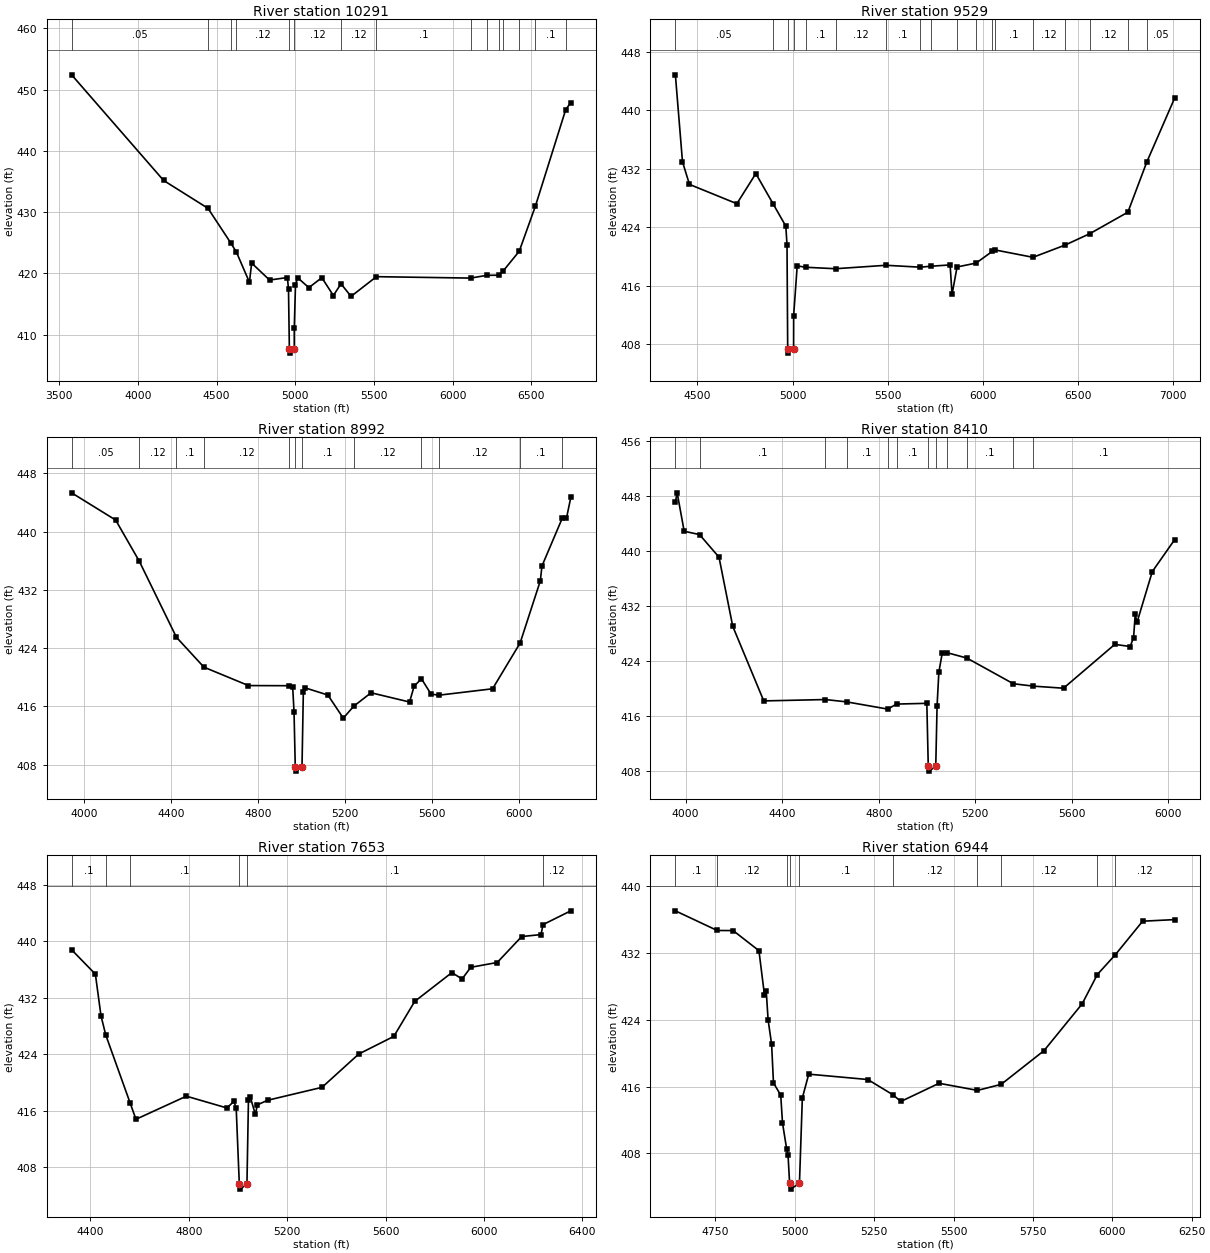
Type RM Length L Ch R = 1 ,10291   ,762,762,762
BEGIN DESCRIPTION:
Mapping XS f948c497
END DESCRIPTION:
XS GIS Cut Line= 3
      2701438.05      6921303.67      2700383.38      6920361.84
      2698703.72       6919849.7
#Sta/Elev= 30
  3579.6   452.4  4163.6  435.16  4445.5  430.61  4590.9  424.93  4626.5  423.44
  4708.7  418.54  4722.9  421.67  4836.6   418.9  4949.9  419.31  4956.9  417.41
  4962.4  407.57  4965.4  406.97  4993.4  407.57  4993.6  411.09  5001.3  418.14
  5015.3  419.27  5086.2  417.66  5168.6  419.29  5241.8  416.37  5290.3  418.29
    5354  416.23  5515.2  419.45  6113.8  419.22  6216.6  419.67  6293.2  419.69
  6319.3  420.35  6422.1   423.6  6524.9  430.97  6717.3  446.72  6749.6  447.87
#Mann= 15 ,-1 , 0
  3579.6     .05       0  4445.5     .12       0  4590.9      .1       0
  4626.5     .12       0  4962.4     .07       0  4993.4     .12       0
  5290.3     .12       0  5515.2      .1       0  6113.8     .05       0
  6216.6     .12       0  6293.2     .05       0  6319.3     .12       0
  6422.1     .05       0  6524.9      .1       0  6717.3     .05       0
Bank Sta=4962.4,4993.4
XS Rating Curve= 0 ,0
Exp/Cntr=0.3,0.1

Type RM Length L Ch R = 1 ,9529    ,537,537,537
BEGIN DESCRIPTION:
Mapping XS 7b405074
END DESCRIPTION:
XS GIS Cut Line= 4
      2701199.32      6920600.52      2700826.08      6920118.79
      2700179.38      6919854.03      2698879.17      6919667.67
#Sta/Elev= 30
  4384.8  444.86  4422.1  432.98  4458.7  429.88  4707.7  427.24  4807.3  431.36
  4897.6  427.24  4964.8  424.17  4971.1  421.64  4974.7  407.41  4977.7  406.81
  5005.7  407.41    5006  411.94  5024.6  418.74  5068.7  418.55  5226.1  418.35
  5491.2  418.82    5671  418.56    5726  418.69  5827.7  418.87  5837.9  414.84
  5864.3  418.59    5964  419.12  6049.4  420.72  6063.6  420.92    6263  419.91
  6431.4  421.58    6562  423.15  6761.4  426.08  6861.1  432.96  7006.5  441.65
#Mann= 18 ,-1 , 0
  4384.8     .05       0  4897.6     .12       0  4974.7     .07       0
  5005.7     .12       0  5068.7      .1       0  5226.1     .12       0
  5491.2      .1       0    5671     .12       0    5726      .1       0
  5864.3     .12       0    5964      .1       0  6049.4     .12       0
  6063.6      .1       0    6263     .12       0  6431.4      .1       0
    6562     .12       0  6761.4      .1       0  6861.1     .05       0
Bank Sta=4974.7,5005.7
XS Rating Curve= 0 ,0
Exp/Cntr=0.3,0.1

Type RM Length L Ch R = 1 ,8992    ,582,582,582
BEGIN DESCRIPTION:
Mapping XS 8ecd32a1
END DESCRIPTION:
XS GIS Cut Line= 3
        2701616.      6920591.85      2701034.42      6919736.84
      2700184.78      6918804.58
#Sta/Elev= 30
    3943  445.32  4145.5  441.58  4254.1  435.93  4424.8  425.49  4551.3  421.38
  4756.2  418.85  4943.4  418.83  4959.6  418.61  4965.7  415.24  4971.4   407.7
  4974.4   407.1  5002.4   407.7  5008.5  417.92  5015.3  418.55  5121.4  417.55
  5192.3  414.37    5240  416.01    5320  417.86    5497  416.59    5518  418.77
  5551.7  419.78  5595.7  417.68  5632.2  417.53  5878.8  418.41  6005.4   424.7
  6098.4  433.25  6105.8  435.27  6198.8  441.81  6218.6  441.85  6238.4  444.68
#Mann= 12 ,-1 , 0
    3943     .05       0  4254.1     .12       0  4424.8      .1       0
  4551.3     .12       0  4943.4      .1       0  4971.4     .07       0
  5002.4      .1       0    5240     .12       0  5551.7     .05       0
  5632.2     .12       0  6005.4      .1       0  6198.8     .12       0
Bank Sta=4971.4,5002.4
XS Rating Curve= 0 ,0
Exp/Cntr=0.3,0.1

Type RM Length L Ch R = 1 ,8410    ,757,757,757
BEGIN DESCRIPTION:
Muddy Cedar Creek 5.0
END DESCRIPTION:
XS GIS Cut Line= 3
        2701826.        6920161.        2701276.        6919361.
      2700526.01      6918561.01
#Sta/Elev= 30
  3957.9  447.18  3965.3  448.48  3994.3  442.89    4058   442.4  4138.6  439.11
  4195.4  429.06  4323.9  418.19  4578.9  418.39  4667.3  418.05  4837.4     417
  4873.8  417.73  4999.3  417.84  5005.3  408.67  5008.3  407.97  5036.3  408.67
  5041.8  417.49  5049.1  422.37  5063.3  425.18  5083.2  425.21  5165.1  424.43
  5357.7  420.69  5440.9  420.34  5565.4  420.04  5777.9  426.42  5841.4  426.11
  5855.6  427.39  5862.4   430.8  5869.7  429.61  5933.2  437.02  6025.3  441.64
#Mann= 12 ,-1 , 0
  3957.9     .05       0    4058      .1       0  4578.9     .12       0
  4667.3      .1       0  4837.4     .12       0  4873.8      .1       0
  5005.3     .07       0  5036.3      .1       0  5083.2     .12       0
  5165.1      .1       0  5357.7     .12       0  5440.9      .1       0
Bank Sta=5005.3,5036.3
XS Rating Curve= 0 ,0
Exp/Cntr=0.3,0.1

Type RM Length L Ch R = 1 ,7653    ,709,709,709
BEGIN DESCRIPTION:
Muddy Cedar Creek 4.0
END DESCRIPTION:
XS GIS Cut Line= 3
        2702001.      6919686.01      2701712.18      6919074.26
      2700875.98      6918010.98
#Sta/Elev= 30
  4323.5  438.78  4420.1  435.33  4442.9  429.43  4462.4  426.71  4560.9  417.15
    4585   414.8    4790  418.07  4954.9   416.4  4983.2  417.34  4992.5  416.37
  5005.2  405.62  5008.2  404.92  5036.2  405.62  5042.3  417.46  5049.6  417.97
  5070.4  415.49  5078.5  416.84  5120.1  417.49  5341.4  419.32  5490.6  424.03
  5633.3  426.53  5718.3  431.48  5869.2  435.55  5910.8  434.65    5946   436.3
  6053.6  436.98    6153  440.65  6231.6  440.93  6239.8  442.34  6352.7  444.29
#Mann= 6 ,-1 , 0
  4323.5      .1       0  4462.4     .12       0  4560.9      .1       0
  5005.2     .07       0  5036.2      .1       0  6239.8     .12       0
Bank Sta=5005.2,5036.2
XS Rating Curve= 0 ,0
Exp/Cntr=0.3,0.1

Type RM Length L Ch R = 1 ,6944    ,1067,1067,1067
BEGIN DESCRIPTION:
Muddy Cedar Creek 3.0
END DESCRIPTION:
XS GIS Cut Line= 3
      2702051.02      6919585.96      2702208.96      6919244.96
      2702271.35      6918050.59
#Sta/Elev= 30
  4624.2     437  4755.9  434.65    4806  434.64  4887.3  432.24  4904.7  426.95
  4910.2  427.47  4916.2  423.96  4927.2  421.07  4933.1  416.44    4956  414.96
  4961.5  411.65  4974.8  408.49  4978.9  407.85  4983.9  404.44  4986.9  403.74
  5014.9  404.44    5024  414.64  5044.1  417.48    5230  416.84  5308.6  415.03
  5334.4  414.22  5454.6  416.39  5575.5  415.54    5650  416.26    5785  420.29
  5905.2  425.89  5952.9  429.39  6009.9  431.77  6095.5  435.76    6196  435.95
#Mann= 10 ,-1 , 0
  4624.2      .1       0  4755.9     .12       0  4974.8      .1       0
  4983.9     .07       0  5014.9      .1       0  5308.6     .12       0
  5575.5      .1       0    5650     .12       0  5952.9      .1       0
  6009.9     .12       0
Bank Sta=4983.9,5014.9
XS Rating Curve= 0 ,0
Exp/Cntr=0.3,0.1

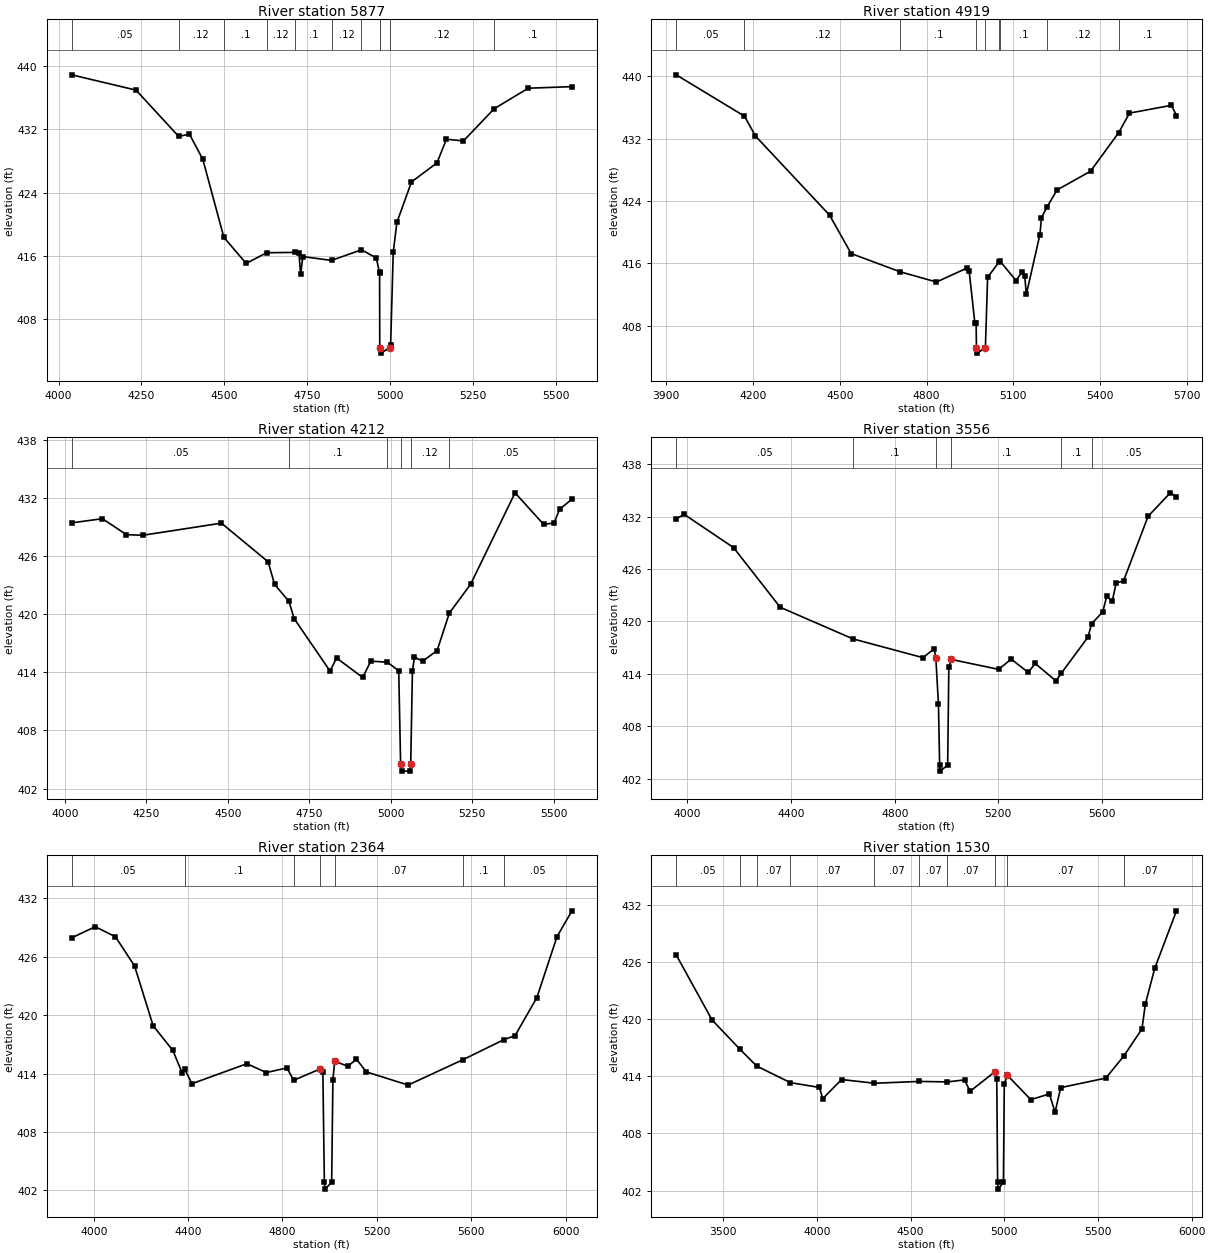
Type RM Length L Ch R = 1 ,5877    ,958,958,958
BEGIN DESCRIPTION:
Muddy Cedar Creek 2.0
END DESCRIPTION:
XS GIS Cut Line= 3
      2702770.48      6919673.88      2702882.69      6918719.95
      2702652.71      6918221.11
#Sta/Elev= 30
  4039.5  438.86  4233.7  436.93  4362.4  431.09  4394.8  431.38  4435.1  428.21
  4498.8  418.35    4566  415.06  4627.9  416.41  4713.8  416.45  4725.4  416.33
  4730.4  413.73  4737.2  415.92  4823.7  415.44    4914  416.78  4958.7  415.75
  4968.5  413.92  4968.7  413.88  4969.2  404.44  4972.2  403.74  5000.2  404.44
    5002  404.73  5009.9  416.47  5020.9  420.23  5064.9  425.34  5141.9  427.75
  5170.4  430.73  5221.8  430.52  5314.5  434.58  5417.3  437.17  5549.3  437.37
#Mann= 11 ,-1 , 0
  4039.5     .05       0  4362.4     .12       0  4498.8      .1       0
  4627.9     .12       0  4713.8      .1       0  4823.7     .12       0
    4914      .1       0  4968.5     .12       0  4969.2     .07       0
  5000.2     .12       0  5314.5      .1       0
Bank Sta=4969.2,5000.2
XS Rating Curve= 0 ,0
Exp/Cntr=0.3,0.1

Type RM Length L Ch R = 1 ,4919    ,707,707,707
BEGIN DESCRIPTION:
Mapping XS d38aba34
END DESCRIPTION:
XS GIS Cut Line= 3
      2703174.85       6919847.8      2703409.22      6918837.42
      2703133.17      6918201.99
#Sta/Elev= 30
  3934.2  440.19  4170.3  434.89  4208.1  432.35  4464.7  422.19  4539.2  417.27
  4709.5  414.92  4834.3  413.62  4938.6  415.39  4947.2  415.05    4967  408.36
  4971.4  408.36  4972.4   405.2  4975.4   404.5  5003.4   405.2  5011.1  414.22
  5051.4  416.23  5053.9   416.3  5109.2  413.81    5131  414.94  5139.5  414.38
    5145  412.04  5191.9   419.7  5197.4  421.89  5216.3  423.22    5251  425.42
    5367  427.83  5464.5  432.78  5501.7  435.28  5646.7  436.28  5664.2  434.97
#Mann= 9 ,-1 , 0
  3934.2     .05       0  4170.3     .12       0  4709.5      .1       0
  4972.4     .07       0  5003.4      .1       0  5051.4     .12       0
  5053.9      .1       0  5216.3     .12       0  5464.5      .1       0
Bank Sta=4972.4,5003.4
XS Rating Curve= 0 ,0
Exp/Cntr=0.3,0.1

Type RM Length L Ch R = 1 ,4212    ,656,656,656
BEGIN DESCRIPTION:
Mapping XS f80fb0bc
END DESCRIPTION:
XS GIS Cut Line= 4
      2703914.42      6919363.46      2703815.47       6918884.3
      2703810.26       6918384.3        2703644.      6917864.75
#Sta/Elev= 30
  4020.8  429.43  4115.2  429.86  4188.9  428.21  4239.2  428.15  4480.2   429.4
  4623.4  425.41  4643.4  423.07  4687.4  421.32  4703.4  419.54  4813.4  414.13
  4833.4  415.48  4913.4  413.47  4938.6  415.16  4989.6  415.04  5024.1  414.15
  5029.9   404.5  5032.9   403.8  5057.9   403.8  5060.9   404.5  5066.1   414.1
  5072.3  415.57  5097.6  415.15  5141.9  416.25  5179.3  420.11  5244.6  423.09
    5381  432.53  5468.7  429.27  5500.8  429.42  5517.5  430.83  5555.6  431.88
#Mann= 6 ,-1 , 0
  4020.8     .05       0  4687.4      .1       0  4989.6     .12       0
  5029.9     .07       0  5060.9     .12       0  5179.3     .05       0
Bank Sta=5029.9,5060.9
XS Rating Curve= 0 ,0
Exp/Cntr=0.3,0.1

Type RM Length L Ch R = 1 ,3556    ,1192,1192,1192
BEGIN DESCRIPTION:
Mapping XS 46310f4a
END DESCRIPTION:
XS GIS Cut Line= 4
      2704268.59      6919701.97      2704320.67      6918707.21
      2704294.63       6918384.3      2703966.49      6917868.64
#Sta/Elev= 30
  3956.4  431.76  3987.4  432.26  4177.7  428.46  4357.9  421.62  4638.5     418
  4908.7  415.85  4952.5  416.86  4958.8  415.79  4968.8  410.51  4973.4  403.55
  4976.4  402.85  5004.4  403.55  5008.9  414.83    5019  415.64  5200.9  414.51
  5249.7  415.68  5315.3  414.16  5342.4  415.18  5422.6  413.18  5442.6  414.05
  5545.6  418.18  5560.4  419.75  5603.1  421.09  5618.4  422.88  5639.5  422.29
  5654.8  424.39  5683.4  424.65  5778.2  432.05  5863.9  434.73  5887.7   434.3
#Mann= 6 ,-1 , 0
  3956.4     .05       0  4638.5      .1       0  4958.8     .07       0
    5019      .1       0  5442.6      .1       0  5560.4     .05       0
Bank Sta=4958.8,5019
XS Rating Curve= 0 ,0
Exp/Cntr=0.3,0.1

Type RM Length L Ch R = 1 ,2364    ,834,834,834
BEGIN DESCRIPTION:
Mapping XS 93f61da8
END DESCRIPTION:
XS GIS Cut Line= 4
      2704924.84      6919004.08      2705055.05      6918207.21
      2704940.47      6917941.59       2704171.2      6917265.89
#Sta/Elev= 30
  3906.6  427.93  4006.4  429.07  4092.1  428.04  4173.2  425.04    4252   418.9
  4335.3  416.38  4374.8  414.07  4385.2  414.48  4416.3  412.96  4649.4  415.01
  4731.7   414.1  4818.8  414.58  4847.6  413.31  4960.4  414.48  4971.3  414.16
  4977.6  402.84  4980.6  402.14  5008.6  402.84  5013.8  413.37  5021.4  415.27
  5077.4  414.74  5113.5  415.48  5155.7  414.17  5332.7  412.82  5563.8  415.41
  5738.8  417.48  5786.2   417.9  5878.3  421.79  5963.7  428.05  6027.2   430.7
#Mann= 7 ,-1 , 0
  3906.6     .05       0  4385.2      .1       0  4847.6     .07       0
  4960.4     .05       0  5021.4     .07       0  5563.8      .1       0
  5738.8     .05       0
Bank Sta=4960.4,5021.4
XS Rating Curve= 0 ,0
Exp/Cntr=0.3,0.1

Type RM Length L Ch R = 1 ,1530    ,0,0,0
BEGIN DESCRIPTION:
Mapping XS 43bfd994
END DESCRIPTION:
XS GIS Cut Line= 4
      2705252.96      6918868.68      2705487.34       6917946.8
      2705129.31      6917292.04      2704160.21      6917210.28
#Sta/Elev= 30
  3249.1  426.73  3440.8  419.89  3587.7  416.86  3678.8  415.06    3859  413.32
  4013.8  412.82  4030.9  411.63  4131.4  413.65  4307.1  413.26  4546.7  413.45
  4696.5   413.4  4788.2  413.61  4817.3  412.41  4950.7  414.48  4959.9  413.75
  4964.5  402.85  4967.5  402.15  4995.5  402.85  5000.1  413.21  5016.8  414.09
  5141.5  411.54  5240.9  412.14    5271  410.21  5301.1   412.8    5542   413.8
  5637.4   416.1  5734.9  418.96  5752.7  421.55  5802.9  425.31  5919.1  431.35
#Mann= 10 ,-1 , 0
  3249.1     .05       0  3587.7      .1       0  3678.8     .07       0
    3859     .07       0  4307.1     .07       0  4546.7     .07       0
  4696.5     .07       0  4950.7     .05       0  5016.8     .07       0
  5637.4     .07       0
Bank Sta=4950.7,5016.8
XS Rating Curve= 0 ,0
Exp/Cntr=0.3,0.1

Chan Stop Cuts=-1
Use User Specified Reach Order=0
Composite Channel Slope=5