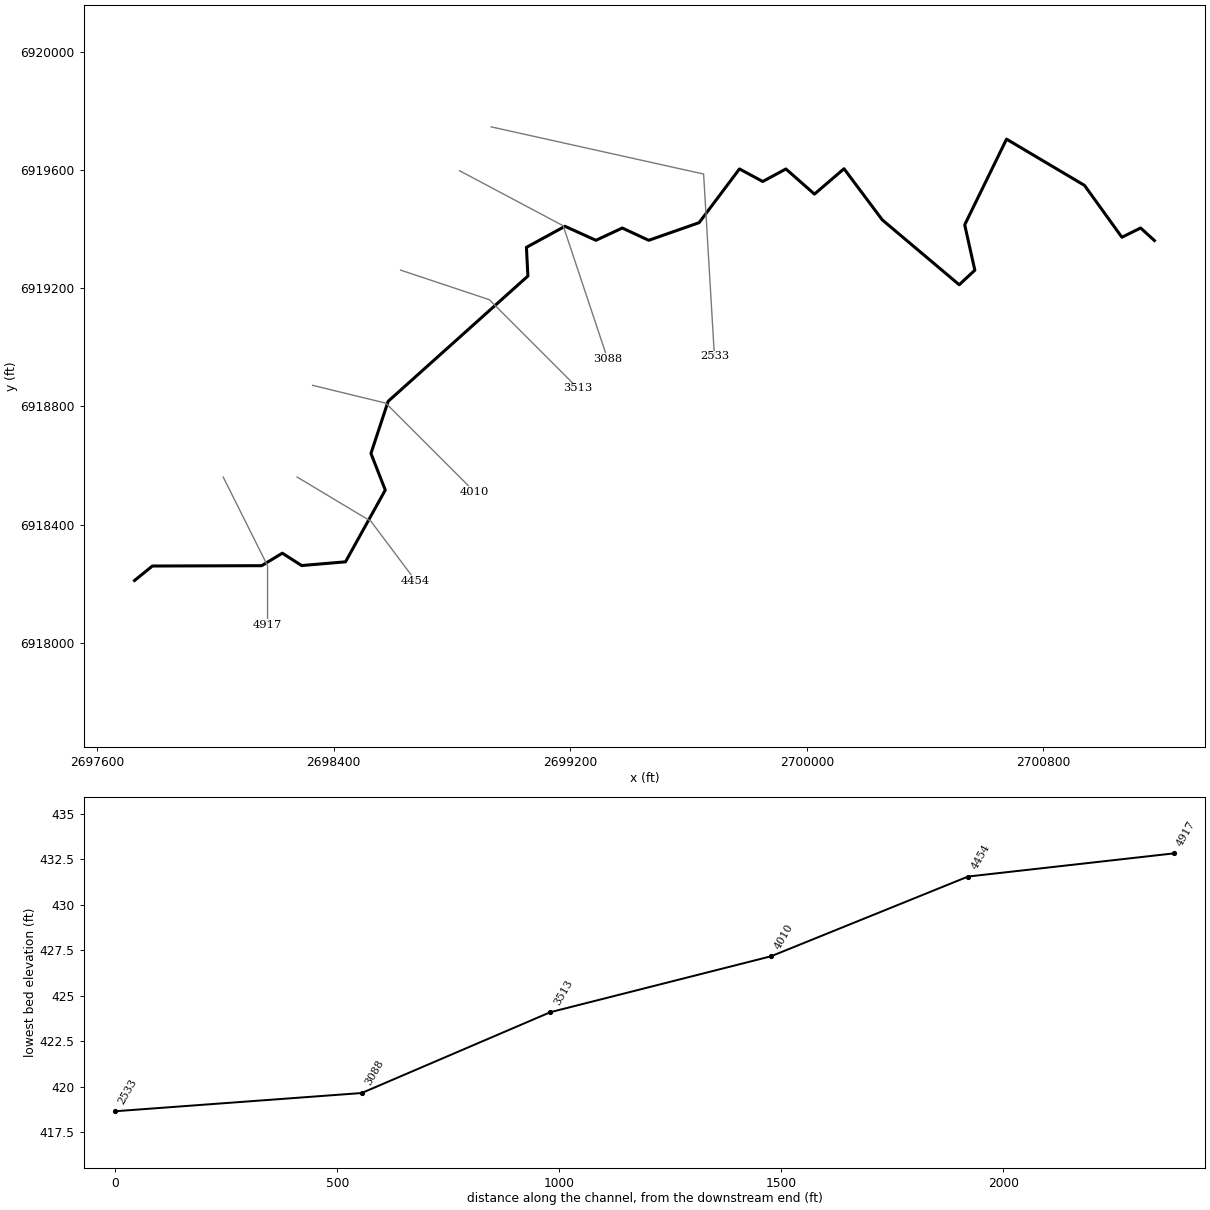
--- Muddy T1.prj (project) ---

Proj Title=Muddy T1 Base Level Engineering
Current Plan=p01
Default Exp/Contr=0.3,0.1
English Units
Geom File=g01
Flow File=f01
Plan File=p01
BEGIN DESCRIPTION:
Muddy T1
END DESCRIPTION:

--- Muddy T1.p01 (plan) ---

Plan Title=Multiple Run
Short Identifier=Multiple
Geom File=g01
Flow File=f01
Subcritical Flow
K Sum by GR= 0
Std Step Tol= 0.01
Critical Tol= 0.01
Num of Std Step Trials= 20
Max Error Tol= 0.3
Flow Tol Ratio= 0.001
Split Flow NTrial= 30
Split Flow Tol= 0.02
Split Flow Ratio= 0.02
Log Output Level= 0
Friction Slope Method= 1
Unsteady Friction Slope Method= 2
Unsteady Bridges Friction Slope Method= 1
Parabolic Critical Depth
Global Vel Dist=  1 , 1 , 1
Global Log Level= 0
CheckData=True
Encroach Param= -1, 0, 0, 0
BEGIN DESCRIPTION:
Multiple Run
END DESCRIPTION:

--- Muddy T1.f01 (steady flow) ---

Flow Title=Multiple
Number of Profiles=7
Profile Names=10-year,25-year,50-year,1pct_min,100-year,1pct_plu,500-year
River Rch & RM= Muddy T1,Reach-1,4917
     602     806     971     580    1158    2310    1645
Boundary for River Rch & Prof#=Muddy T1,Reach-1,1
Up Type=0
Dn Type=3
Dn Slope=0.005
Boundary for River Rch & Prof#=Muddy T1,Reach-1,2
Up Type=0
Dn Type=3
Dn Slope=0.005
Boundary for River Rch & Prof#=Muddy T1,Reach-1,3
Up Type=0
Dn Type=3
Dn Slope=0.005
Boundary for River Rch & Prof#=Muddy T1,Reach-1,4
Up Type=0
Dn Type=3
Dn Slope=0.005
Boundary for River Rch & Prof#=Muddy T1,Reach-1,5
Up Type=0
Dn Type=3
Dn Slope=0.005
Boundary for River Rch & Prof#=Muddy T1,Reach-1,6
Up Type=0
Dn Type=3
Dn Slope=0.005
Boundary for River Rch & Prof#=Muddy T1,Reach-1,7
Up Type=0
Dn Type=3
Dn Slope=0.005

--- Muddy T1.g01 (geometry) ---

Geom Title=Existing Conditions

River Reach=Muddy T1,Reach-1
Reach XY= 30
      2697726.00      6918211.00      2697786.40      6918260.04
      2698156.02      6918261.18      2698226.00      6918303.44
      2698291.17      6918261.64      2698439.67      6918274.22
      2698574.20      6918517.11      2698525.72      6918640.82
      2698583.86      6918817.17      2699056.64      6919240.96
      2699051.64      6919337.99      2699182.11      6919409.20
      2699286.70      6919361.84      2699376.00      6919403.38
      2699465.29      6919361.81      2699635.81      6919421.51
      2699772.34      6919603.28      2699851.00      6919560.79
      2699929.41      6919603.15      2700026.00      6919518.12
      2700126.01      6919603.91      2700255.58      6919430.77
      2700515.64      6919211.53      2700568.55      6919260.72
      2700534.23      6919414.23      2700675.75      6919704.02
      2700939.57      6919547.53      2701065.98      6919372.15
      2701129.33      6919403.48      2701176.00      6919361.00

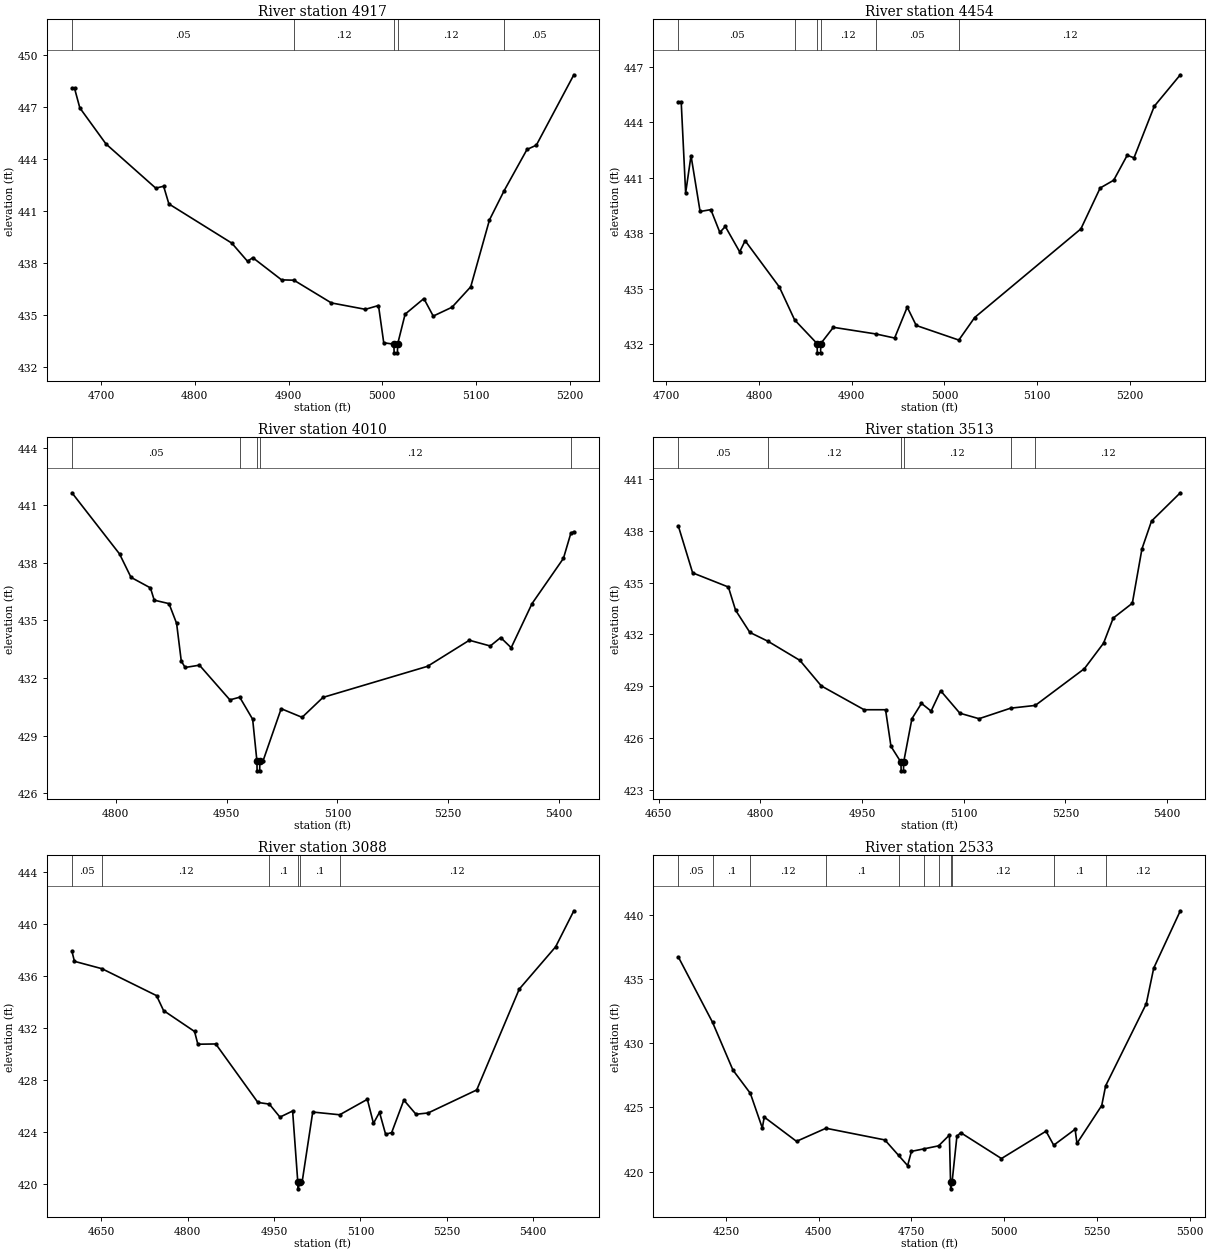
Type RM Length L Ch R = 1,4917,463,463,463
BEGIN DESCRIPTION:
Muddy T1 7.0
END DESCRIPTION:
XS GIS Cut Line= 3
      2698026.00      6918561.00      2698176.00      6918261.00
      2698176.00      6918061.01
#Sta/Elev= 30
  4668.9  448.06  4671.7  448.06  4677.3  446.94  4705.2  444.86  4758.3  442.31
  4766.7  442.42  4772.3  441.40  4839.4  439.14  4856.2  438.09  4861.8  438.30
  4892.5  437.02  4905.7  437.00  4945.6  435.69  4981.9  435.32  4995.9  435.54
  5001.5  433.39  5012.3  433.31  5012.6  432.81  5016.1  432.81  5016.3  433.31
  5024.3  435.04  5044.3  435.94  5054.3  434.93  5074.3  435.44  5094.3  436.62
  5114.3  440.48  5129.9  442.16  5154.3  444.54  5164.3  444.79  5204.3  448.85
#Mann=5,-1,0
  4668.9    0.05       0  4905.7    0.12       0  5012.3    0.07       0
  5016.3    0.12       0  5129.9    0.05       0
Bank Sta=5012.3,5016.3
Exp/Cntr=0.3,0.1

Type RM Length L Ch R = 1,4454,444,444,444
BEGIN DESCRIPTION:
Muddy T1 6.0
END DESCRIPTION:
XS GIS Cut Line= 3
      2698275.96      6918561.02      2698526.00      6918411.00
      2698676.00      6918210.99
#Sta/Elev= 30
  4713.0  445.11  4716.0  445.11  4720.8  440.18  4726.6  442.20  4736.4  439.18
  4748.0  439.28  4757.7  438.05  4763.6  438.37  4779.1  437.00  4785.0  437.60
  4821.9  435.10  4838.4  433.32  4862.6  432.04  4862.9  431.54  4866.4  431.54
  4866.6  432.04  4880.2  432.92  4926.1  432.56  4946.3  432.34  4959.9  434.01
  4969.6  433.02  5015.6  432.23  5032.7  433.45  5147.3  438.24  5168.1  440.45
  5182.7  440.87  5197.3  442.22  5204.6  442.08  5226.5  444.87  5254.6  446.57
#Mann=6,-1,0
  4713.0    0.05       0  4838.4    0.12       0  4862.6    0.03       0
  4866.6    0.12       0  4926.1    0.05       0  5015.6    0.12       0
Bank Sta=4862.6,4866.6
Exp/Cntr=0.3,0.1

Type RM Length L Ch R = 1,4010,497,497,497
BEGIN DESCRIPTION:
Muddy T1 5.0
END DESCRIPTION:
XS GIS Cut Line= 3
      2698328.38      6918871.21      2698576.00      6918811.00
      2698876.00      6918511.00
#Sta/Elev= 30
  4740.8  441.66  4805.2  438.47  4820.7  437.25  4847.0  436.70  4852.1  436.06
  4872.1  435.88  4882.4  434.85  4888.7  432.89  4893.9  432.55  4913.3  432.67
  4954.5  430.86  4967.8  431.00  4985.3  429.85  4991.1  427.66  4991.3  427.16
  4994.8  427.16  4995.1  427.66  4999.2  427.66  5023.9  430.40  5052.2  429.95
  5080.5  430.99  5221.9  432.61  5278.5  433.97  5306.8  433.67  5320.9  434.11
  5335.1  433.58  5363.3  435.88  5405.8  438.24  5415.9  439.56  5419.9  439.63
#Mann=5,-1,0
  4740.8    0.05       0  4967.8    0.12       0  4991.1    0.07       0
  4995.1    0.12       0  5415.9    0.05       0
Bank Sta=4991.1,4995.1
Exp/Cntr=0.3,0.1

Type RM Length L Ch R = 1,3513,425,425,425
BEGIN DESCRIPTION:
Muddy T1 4.0
END DESCRIPTION:
XS GIS Cut Line= 3
      2698626.04      6919260.99      2698926.00      6919161.00
      2699226.03      6918860.97
#Sta/Elev= 30
  4679.0  438.26  4700.0  435.56  4752.7  434.74  4763.3  433.40  4784.4  432.11
  4811.0  431.60  4858.2  430.49  4889.8  429.01  4953.0  427.63  4984.6  427.63
  4992.6  425.51  5007.3  424.59  5007.6  424.09  5011.1  424.09  5011.3  424.59
  5023.5  427.11  5037.6  428.00  5051.8  427.55  5065.9  428.73  5094.2  427.43
  5122.5  427.11  5169.1  427.72  5205.5  427.88  5278.0  430.01  5306.3  431.49
  5320.5  432.94  5348.7  433.80  5362.9  436.95  5377.0  438.56  5419.5  440.20
#Mann=6,-1,0
  4679.0    0.05       0  4811.0    0.12       0  5007.3    0.07       0
  5011.3    0.12       0  5169.1     0.1       0  5205.5    0.12       0
Bank Sta=5007.3,5011.3
Exp/Cntr=0.3,0.1

Type RM Length L Ch R = 1,3088,555,555,555
BEGIN DESCRIPTION:
Muddy T1 3.0
END DESCRIPTION:
XS GIS Cut Line= 3
      2698825.58      6919597.16      2699176.00      6919411.00
      2699325.99      6918961.04
#Sta/Elev= 30
  4599.4  437.93  4603.7  437.16  4651.6  436.59  4746.2  434.52  4758.4  433.37
  4812.2  431.76  4817.9  430.78  4849.0  430.80  4922.1  426.30  4942.0  426.17
  4960.4  425.17  4982.4  425.64  4991.4  420.15  4991.6  419.65  4995.4  420.15
  4998.8  420.15  5017.3  425.56  5064.1  425.35  5112.1  426.54  5122.7  424.69
  5133.2  425.54  5143.8  423.85  5154.3  423.98  5175.4  426.48  5196.5  425.39
  5217.6  425.49  5301.9  427.26  5375.7  435.02  5438.9  438.28  5470.5  441.05
#Mann=6,-1,0
  4599.4    0.05       0  4651.6    0.12       0  4942.0     0.1       0
  4991.4    0.07       0  4995.4     0.1       0  5064.1    0.12       0
Bank Sta=4991.4,4995.4
Exp/Cntr=0.3,0.1

Type RM Length L Ch R = 1,2533,0,0,0
BEGIN DESCRIPTION:
Muddy T1 2.0
END DESCRIPTION:
XS GIS Cut Line= 3
      2698932.37      6919745.59      2699651.00      6919586.00
      2699687.62      6918969.33
#Sta/Elev= 30
  4121.3  436.70  4213.4  431.62  4268.4  427.90  4315.3  426.09  4347.6  423.39
  4352.8  424.24  4439.9  422.35  4519.3  423.37  4678.2  422.46  4715.4  421.25
  4739.6  420.46  4749.9  421.57  4784.6  421.77  4823.2  422.00  4852.3  422.84
  4855.4  419.15  4855.7  418.65  4859.4  419.15  4872.5  422.73  4882.5  423.03
  4992.7  421.01  5112.9  423.14  5133.7  422.05  5191.4  423.29  5196.4  422.19
  5263.2  425.14  5273.8  426.68  5383.4  433.07  5403.4  435.84  5475.2  440.31
#Mann=11,-1,0
  4121.3    0.05       0  4213.4     0.1       0  4315.3    0.12       0
  4519.3     0.1       0  4715.4    0.12       0  4784.6     0.1       0
  4823.2    0.12       0  4855.4    0.07       0  4859.4    0.12       0
  5133.7     0.1       0  5273.8    0.12       0
Bank Sta=4855.4,4859.4
Exp/Cntr=0.3,0.1

Chan Stop Cuts=-1