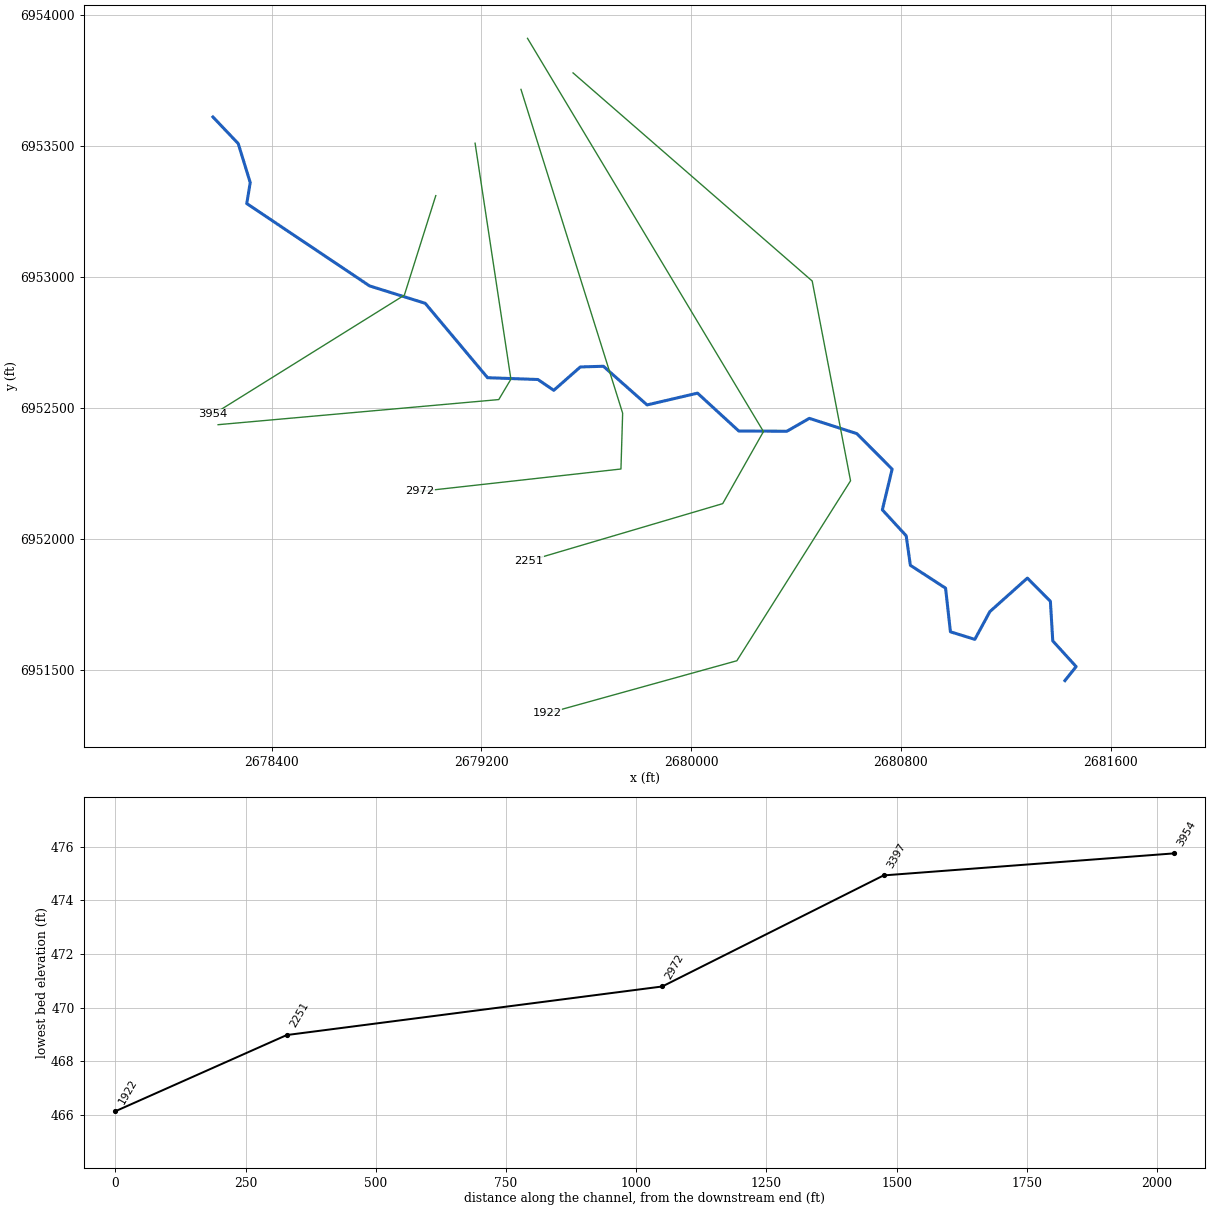
--- Muddy T10.prj (project) ---

Proj Title=Muddy T10 Base Level Engineering
Current Plan=p01
Default Exp/Contr=0.3,0.1
English Units
Geom File=g01
Flow File=f01
Plan File=p01
Y Axis Title=Elevation
X Axis Title(PF)=Main Channel Distance
X Axis Title(XS)=Station
BEGIN DESCRIPTION:
Muddy T10
END DESCRIPTION:
DSS Export Rating Curves= 0
DSS Export Rating Curve Sorted= 0
DSS Export Volume Flow Curves= 0
DXF OffsetX= 0
DXF OffsetY= 0
DXF ScaleX= 1
DXF ScaleY= 10

--- Muddy T10.p01 (plan) ---

Plan Title=Multiple Run
Short Identifier=Multiple
Geom File=g01
Flow File=f01
Subcritical Flow
K Sum by GR= 0
Std Step Tol= 0.01
Critical Tol= 0.01
Num of Std Step Trials= 20
Max Error Tol= 0.3
Flow Tol Ratio= 0.001
Split Flow NTrial= 30
Split Flow Tol= 0.02
Split Flow Ratio= 0.02
Log Output Level= 0
Friction Slope Method= 1
Unsteady Friction Slope Method= 2
Unsteady Bridges Friction Slope Method= 1
Parabolic Critical Depth
Global Vel Dist=  1 , 1 , 1
Global Log Level= 0
CheckData=True
Encroach Param= -1, 0, 0, 0
BEGIN DESCRIPTION:
Multiple Run
END DESCRIPTION:

--- Muddy T10.f01 (steady flow) ---

Flow Title=Multiple
Number of Profiles=7
Profile Names=10-year,25-year,50-year,1pct_min,100-year,1pct_plu,500-year
River Rch & RM= Muddy T10,Reach-1,3954
     647     871    1053     631    1260    2514    1802
Boundary for River Rch & Prof#=Muddy T10,Reach-1,1
Up Type=0
Dn Type=3
Dn Slope=0.005
Boundary for River Rch & Prof#=Muddy T10,Reach-1,2
Up Type=0
Dn Type=3
Dn Slope=0.005
Boundary for River Rch & Prof#=Muddy T10,Reach-1,3
Up Type=0
Dn Type=3
Dn Slope=0.005
Boundary for River Rch & Prof#=Muddy T10,Reach-1,4
Up Type=0
Dn Type=3
Dn Slope=0.005
Boundary for River Rch & Prof#=Muddy T10,Reach-1,5
Up Type=0
Dn Type=3
Dn Slope=0.005
Boundary for River Rch & Prof#=Muddy T10,Reach-1,6
Up Type=0
Dn Type=3
Dn Slope=0.005
Boundary for River Rch & Prof#=Muddy T10,Reach-1,7
Up Type=0
Dn Type=3
Dn Slope=0.005

--- Muddy T10.g01 (geometry) ---

Geom Title=Existing Conditions
Program Version=4.10

River Reach=Muddy T10       ,Reach-1
Reach XY= 30
        2678176.        6953611.      2678272.44      6953509.52
      2678318.19      6953360.89      2678305.02      6953280.79
      2678773.58      6952966.54      2678985.71      6952900.25
      2679223.55      6952616.46      2679415.57      6952609.61
       2679476.1      6952568.33       2679577.5      6952657.52
      2679665.52      6952660.07      2679832.03      6952512.62
       2680024.5      6952557.54      2680181.85      6952413.06
       2680365.5      6952412.24        2680451.       6952461.4
      2680632.17      6952403.14      2680766.87      6952267.74
      2680729.47       6952112.5      2680820.46      6952013.42
      2680836.39       6951900.9      2680970.63       6951813.7
      2680989.23      6951647.19      2681082.31      6951618.34
      2681139.64       6951724.2      2681282.69      6951852.05
      2681370.53      6951763.48      2681379.56      6951612.47
      2681468.73      6951514.33        2681426.        6951461.

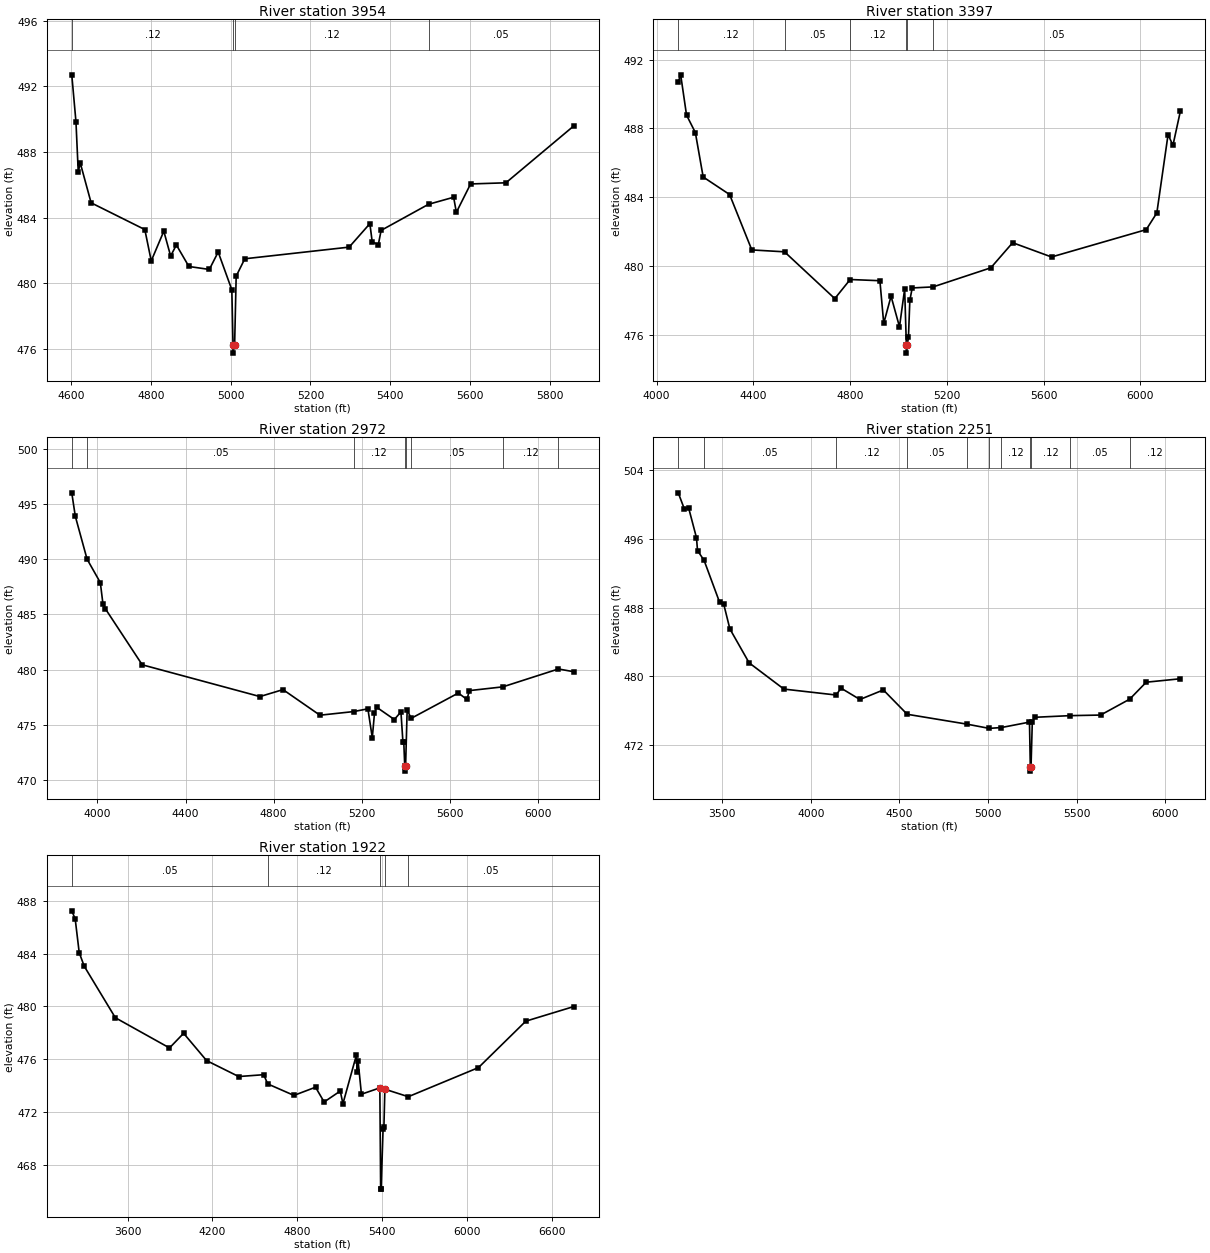
Type RM Length L Ch R = 1 ,3954    ,557,557,557
BEGIN DESCRIPTION:
Muddy T10 5.0
END DESCRIPTION:
XS GIS Cut Line= 3
        2679026.        6953311.      2678906.11      6952931.27
      2678176.04      6952476.19
#Sta/Elev= 30
  4601.8  492.71  4612.3  489.85    4618  486.81  4623.2  487.33  4650.3  484.91
  4784.9  483.28    4801  481.37  4832.5  483.18  4849.6  481.67    4864  482.34
  4895.4  481.03  4946.6  480.85  4968.8  481.91    5003  479.61    5006  476.25
  5006.2  475.75    5010  476.25  5013.9  480.44  5035.5   481.5  5297.1  482.21
    5349  483.64  5354.9  482.53  5370.2  482.36  5377.2  483.23    5496  484.82
    5559  485.25  5565.8  484.33  5601.5  486.06    5690  486.13  5860.3   489.6
#Mann= 4 ,-1 , 0
  4601.8     .12       0    5006     .07       0    5010     .12       0
    5496     .05       0
Bank Sta=5006,5010
XS Rating Curve= 0 ,0
Exp/Cntr=0.3,0.1

Type RM Length L Ch R = 1 ,3397    ,425,425,425
BEGIN DESCRIPTION:
Muddy T10 4.0
END DESCRIPTION:
XS GIS Cut Line= 4
      2679176.01      6953510.96      2679312.58      6952610.86
      2679266.31      6952533.06      2678195.61      6952437.22
#Sta/Elev= 30
  4089.6   490.7  4099.7  491.11  4123.9  488.77  4160.4  487.75  4192.7  485.17
    4302  484.15  4393.8  480.93    4529  480.82  4736.9   478.1  4800.5  479.21
  4923.4  479.14  4939.2  476.66  4969.5  478.24  5004.4  476.46  5025.8  478.66
  5032.7  475.43    5033  474.93  5036.7  475.43  5041.4  475.84  5047.2     478
    5057  478.72  5143.2  478.78    5382  479.89  5472.3  481.35    5633  480.52
  6024.5  482.11  6068.4  483.08  6114.9  487.64    6135  487.01  6165.5  488.98
#Mann= 6 ,-1 , 0
  4089.6     .12       0    4529     .05       0  4800.5     .12       0
  5032.7     .07       0  5036.7     .12       0  5143.2     .05       0
Bank Sta=5032.7,5036.7
XS Rating Curve= 0 ,0
Exp/Cntr=0.3,0.1

Type RM Length L Ch R = 1 ,2972    ,721,721,721
BEGIN DESCRIPTION:
Muddy T10 3.0
END DESCRIPTION:
XS GIS Cut Line= 4
      2679351.03      6953716.24      2679738.83      6952481.12
      2679732.37      6952268.17      2678964.74       6952182.6
#Sta/Elev= 30
  3883.2  496.02  3899.2   493.9  3952.6  490.01  4012.9  487.88  4024.9  485.93
  4035.4  485.52  4203.1  480.43  4737.7  477.55  4842.5  478.18  5010.2  475.86
  5163.9  476.19  5227.9  476.44  5247.9  473.82  5257.9  476.04  5267.9  476.58
    5348  475.47    5378  476.16  5386.9  473.47  5390.8  473.47  5395.2  471.29
  5395.5  470.79  5399.2  471.29  5406.3  476.37    5424  475.57  5638.7  477.87
  5677.6  477.29    5689  478.09  5840.7  478.43  6093.1  480.05  6163.2   479.8
#Mann= 8 ,-1 , 0
  3883.2     .12       0  3952.6     .05       0  5163.9     .12       0
  5395.2     .05       0  5399.2     .12       0    5424     .05       0
  5840.7     .12       0  6093.1     .05       0
Bank Sta=5395.2,5399.2
XS Rating Curve= 0 ,0
Exp/Cntr=0.3,0.1

Type RM Length L Ch R = 1 ,2251    ,329,329,329
BEGIN DESCRIPTION:
Muddy T10 2.0
END DESCRIPTION:
XS GIS Cut Line= 4
      2679375.98      6953911.03        2680276.        6952411.
      2680120.45      6952136.07       2679381.4      6951917.84
#Sta/Elev= 30
  3250.5  501.34  3285.5  499.44  3308.8  499.62  3353.6  496.11  3359.4  494.63
  3396.6  493.48  3483.8  488.63  3507.1  488.42  3542.1  485.52  3650.9  481.57
  3847.2  478.52  4142.2  477.83  4169.9  478.63  4276.8  477.31    4409  478.42
  4543.7  475.59  4882.1  474.44  5006.9  473.95  5076.1  474.05  5234.4  474.68
  5239.1  469.48  5239.4  468.98  5243.1  469.48  5250.3  474.69  5264.1  475.24
  5461.9  475.43  5636.1   475.5  5800.5  477.35  5893.8  479.32  6086.3  479.72
#Mann= 11 ,-1 , 0
  3250.5     .12       0  3396.6     .05       0  4142.2     .12       0
  4543.7     .05       0  4882.1     .12       0  5006.9     .05       0
  5076.1     .12       0  5239.1     .07       0  5243.1     .12       0
  5461.9     .05       0  5800.5     .12       0
Bank Sta=5239.1,5243.1
XS Rating Curve= 0 ,0
Exp/Cntr=0.3,0.1

Type RM Length L Ch R = 1 ,1922    ,0,0,0
BEGIN DESCRIPTION:
Mapping XS 22bdb4d6
END DESCRIPTION:
XS GIS Cut Line= 5
      2679549.72      6953779.13       2680461.9      6952985.26
      2680608.21       6952223.2      2680174.47      6951536.75
      2679451.04      6951336.01
#Sta/Elev= 30
    3206  487.25  3230.1  486.64  3258.6  484.08  3293.9  483.05    3514  479.14
  3896.6  476.85  3996.4  477.96  4158.7  475.89  4385.6  474.68  4562.2  474.82
  4590.7  474.12    4776  473.25  4928.7  473.87  4989.3  472.75  5103.4  473.58
  5122.2  472.62  5217.5  476.31  5223.4  475.05  5229.4  475.85    5253  473.34
  5383.1  473.82  5388.7  466.14  5392.2  466.14  5405.8  470.69  5411.7  470.82
  5418.6  473.72  5584.1  473.15  6080.2  475.36  6414.5  478.88    6754  479.99
#Mann= 5 ,-1 , 0
    3206     .05       0  4590.7     .12       0  5383.1     .07       0
  5418.6     .12       0  5584.1     .05       0
Bank Sta=5383.1,5418.6
XS Rating Curve= 0 ,0
Exp/Cntr=0.3,0.1

Chan Stop Cuts=-1
Use User Specified Reach Order=0
Composite Channel Slope=5