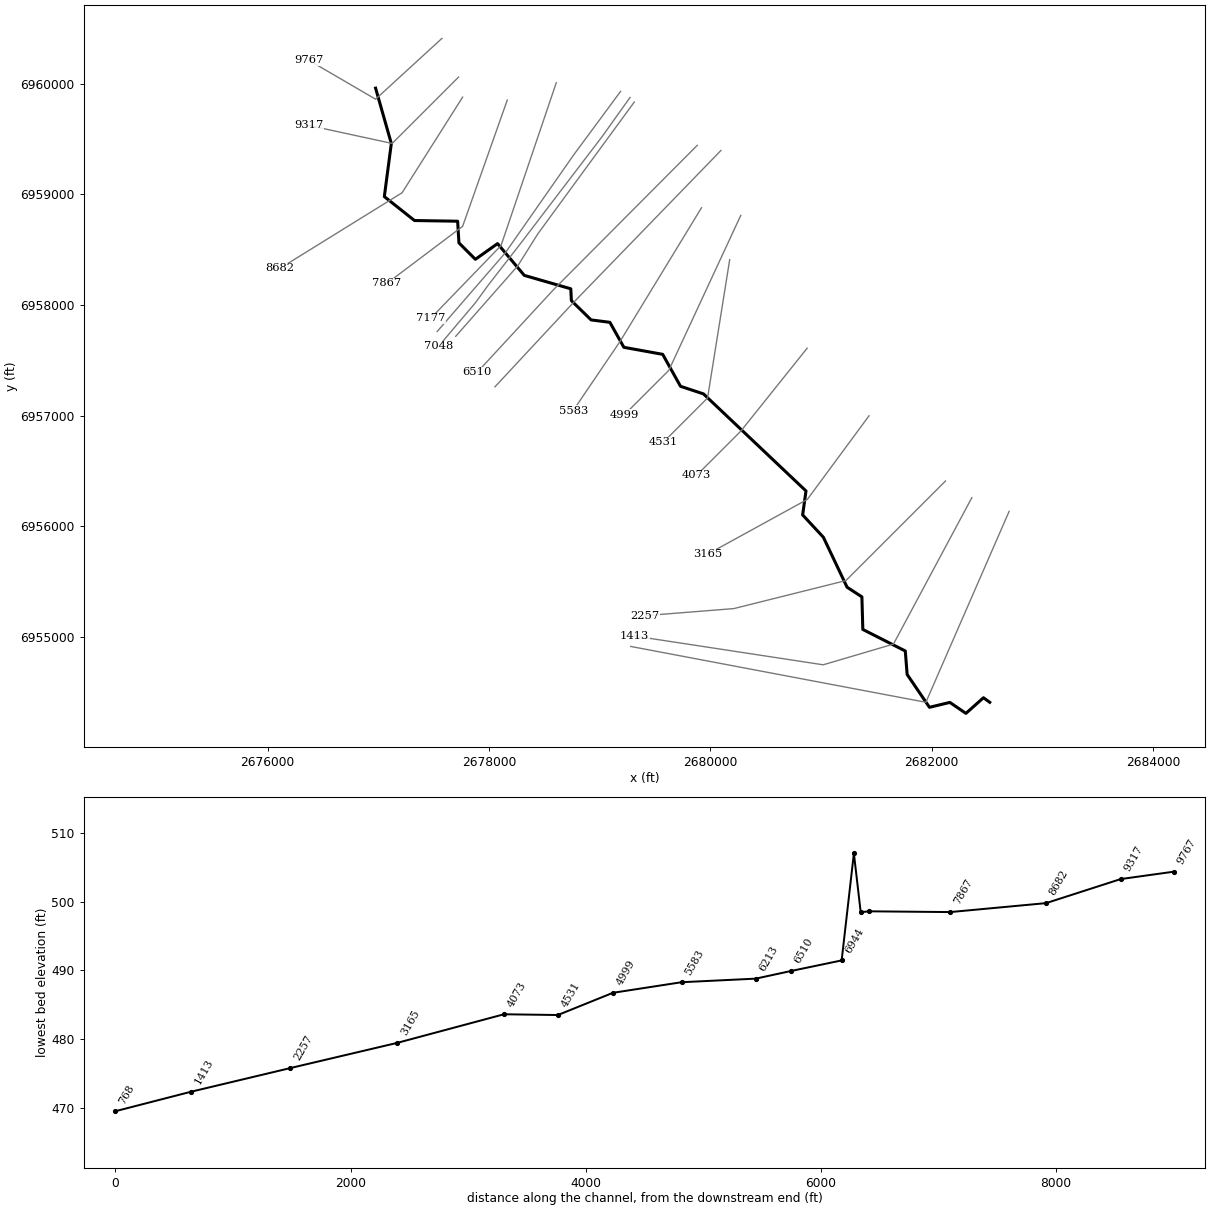
--- Muddy T11.prj (project) ---

Proj Title=Muddy T11 Base Level Engineering
Current Plan=p01
Default Exp/Contr=0.3,0.1
English Units
Geom File=g01
Flow File=f01
Plan File=p01
Y Axis Title=Elevation
X Axis Title(PF)=Main Channel Distance
X Axis Title(XS)=Station
BEGIN DESCRIPTION:
Muddy T11
END DESCRIPTION:
DSS Export Rating Curves= 0
DSS Export Rating Curve Sorted= 0
DSS Export Volume Flow Curves= 0
DXF OffsetX= 0
DXF OffsetY= 0
DXF ScaleX= 1
DXF ScaleY= 10

--- Muddy T11.p01 (plan) ---

Plan Title=Multiple Run
Short Identifier=Multiple
Geom File=g01
Flow File=f01
Subcritical Flow
K Sum by GR= 0
Std Step Tol= 0.01
Critical Tol= 0.01
Num of Std Step Trials= 20
Max Error Tol= 0.3
Flow Tol Ratio= 0.001
Split Flow NTrial= 30
Split Flow Tol= 0.02
Split Flow Ratio= 0.02
Log Output Level= 0
Friction Slope Method= 1
Unsteady Friction Slope Method= 2
Unsteady Bridges Friction Slope Method= 1
Parabolic Critical Depth
Global Vel Dist=  1 , 1 , 1
Global Log Level= 0
CheckData=True
Encroach Param= -1, 0, 0, 0
BEGIN DESCRIPTION:
Multiple Run
END DESCRIPTION:

--- Muddy T11.f01 (steady flow) ---

Flow Title=Multiple
Number of Profiles=7
Profile Names=10-year,25-year,50-year,1pct_min,100-year,1pct_plu,500-year
River Rch & RM= Muddy T11,Reach-1,9767
     551     733     880     524    1046    2087    1475
River Rch & RM= Muddy T11,Reach-1,7867
     989    1359    1664    1010    2014    4019    2951
Boundary for River Rch & Prof#=Muddy T11,Reach-1,1
Up Type=0
Dn Type=3
Dn Slope=0.005
Boundary for River Rch & Prof#=Muddy T11,Reach-1,2
Up Type=0
Dn Type=3
Dn Slope=0.005
Boundary for River Rch & Prof#=Muddy T11,Reach-1,3
Up Type=0
Dn Type=3
Dn Slope=0.005
Boundary for River Rch & Prof#=Muddy T11,Reach-1,4
Up Type=0
Dn Type=3
Dn Slope=0.005
Boundary for River Rch & Prof#=Muddy T11,Reach-1,5
Up Type=0
Dn Type=3
Dn Slope=0.005
Boundary for River Rch & Prof#=Muddy T11,Reach-1,6
Up Type=0
Dn Type=3
Dn Slope=0.005
Boundary for River Rch & Prof#=Muddy T11,Reach-1,7
Up Type=0
Dn Type=3
Dn Slope=0.005

--- Muddy T11.g01 (geometry) ---

Geom Title=Existing Conditions
Program Version=4.10

River Reach=Muddy T11       ,Reach-1
Reach XY= 30
        2676976.        6959961.      2677118.21       6959460.9
      2677055.07      6958980.93       2677327.5      6958764.61
      2677717.55      6958758.33      2677729.16      6958562.65
      2677877.68      6958414.08      2678078.27      6958555.95
      2678319.66      6958269.02      2678740.11      6958147.63
      2678745.31      6958040.66      2678923.54      6957866.46
      2679093.22      6957844.76      2679219.79       6957618.8
      2679570.42      6957555.42      2679731.61      6957266.59
      2679939.63      6957197.68      2680865.53       6956320.8
      2680835.15      6956104.27      2681022.47      6955902.51
      2681236.65      6955451.01      2681370.64       6955363.7
      2681379.07       6955069.3      2681762.78      6954874.67
      2681779.55      6954662.47      2681981.28       6954365.7
      2682165.52      6954410.06      2682310.64      6954310.89
      2682469.33      6954452.23        2682526.        6954411.

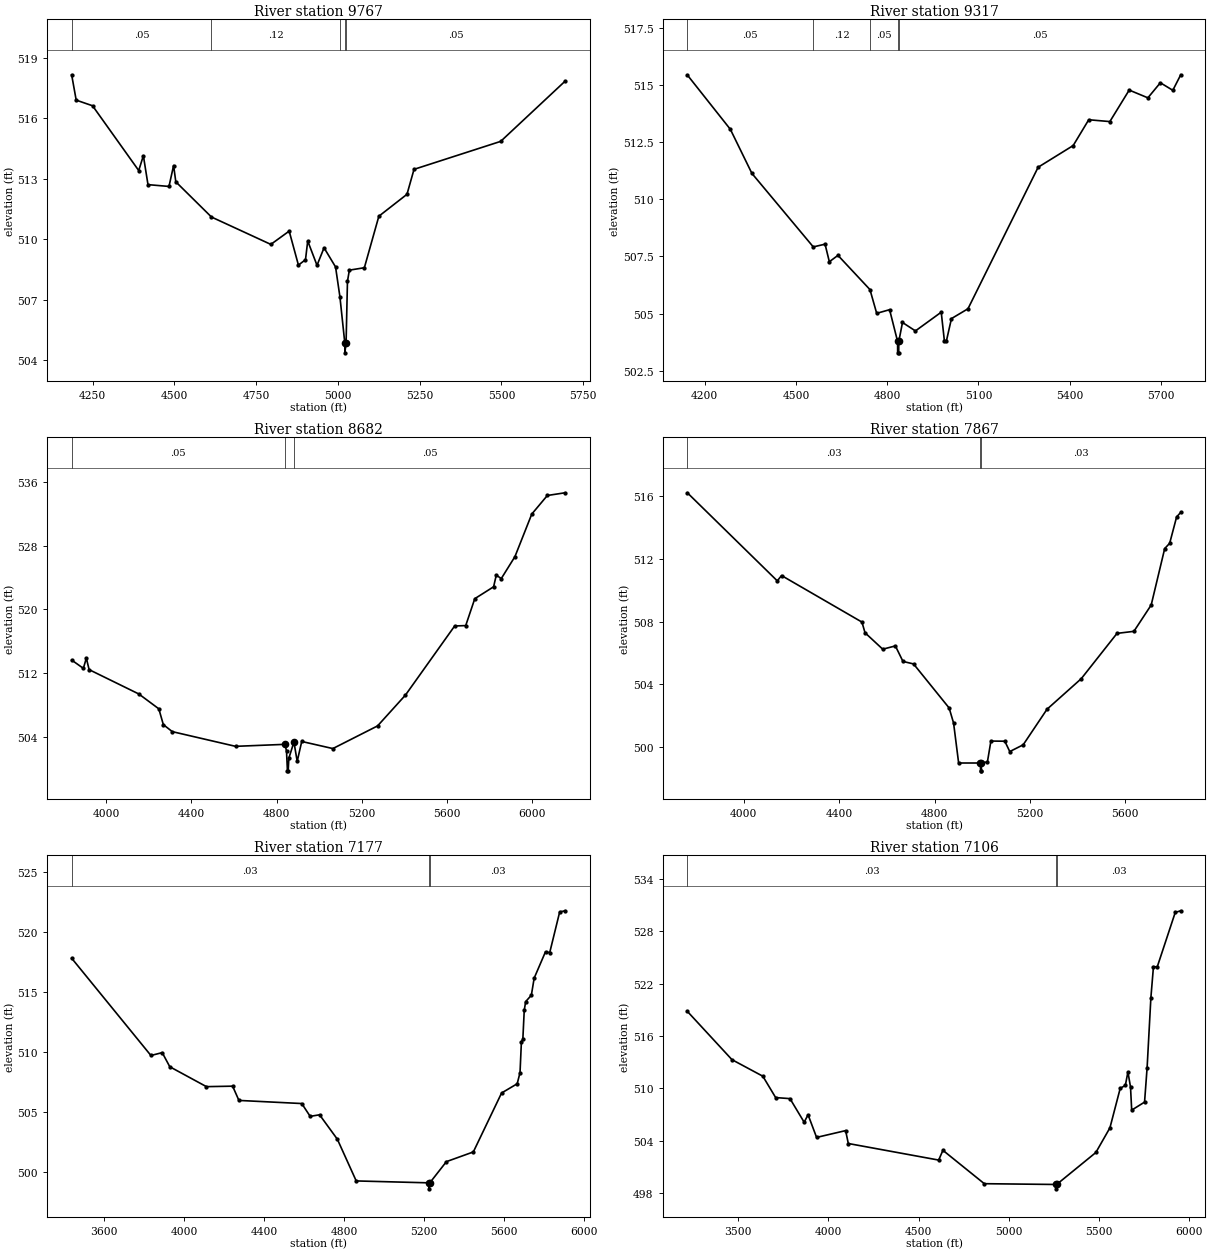
Type RM Length L Ch R = 1 ,9767    ,450,450,450
BEGIN DESCRIPTION:
Muddy T11 19.0
END DESCRIPTION:
XS GIS Cut Line= 3
      2677576.03      6960411.03        2676976.        6959861.
      2676376.01        6960211.
#Sta/Elev= 30
  4185.9  518.17  4199.8  516.91  4249.8  516.63    4391  513.41  4405.2  514.15
  4419.3  512.71  4483.5  512.62  4497.6  513.66  4504.4  512.85  4613.4   511.1
  4794.9  509.74    4851   510.4  4879.3  508.71  4900.9  508.98  4907.7  509.91
  4936.1   508.7  4957.6  509.57  4992.8  508.62  5006.2  507.13    5021  504.85
  5021.3  504.35    5025  504.85  5029.2   507.9    5035  508.46  5080.9  508.58
  5125.2  511.14  5211.2  512.23  5232.7  513.47  5497.7  514.86  5694.5  517.85
#Mann= 5 ,-1 , 0
  4185.9     .05       0  4613.4     .12       0  5006.2     .05       0
    5021     .07       0    5025     .05       0
Bank Sta=5021,5025
XS Rating Curve= 0 ,0
Exp/Cntr=0.3,0.1

Type RM Length L Ch R = 1 ,9317    ,635,635,635
BEGIN DESCRIPTION:
Muddy T11 18.0
END DESCRIPTION:
XS GIS Cut Line= 3
      2677726.01      6960061.01        2677126.        6959461.
      2676370.49      6959624.75
#Sta/Elev= 30
  4143.2  515.45  4284.6  513.07  4355.4  511.14  4557.1  507.92  4595.8  508.04
  4609.9  507.27  4638.2  507.55  4743.4  506.05  4765.5  505.01  4807.9  505.17
  4834.2  503.78  4834.4  503.28  4837.9  503.28  4838.2  503.78  4850.3  504.61
  4892.8  504.24  4977.6  505.06  4988.2  503.78  4994.3  503.78  5011.2  504.78
  5065.5  505.21  5296.1  511.41  5411.3  512.36  5462.4  513.49  5531.8  513.41
  5595.4  514.79  5656.8  514.45  5697.8  515.11  5738.7  514.78  5764.8  515.46
#Mann= 5 ,-1 , 0
  4143.2     .05       0  4557.1     .12       0  4743.4     .05       0
  4834.2     .03       0  4838.2     .05       0
Bank Sta=4834.2,4838.2
XS Rating Curve= 0 ,0
Exp/Cntr=0.3,0.1

Type RM Length L Ch R = 1 ,8682    ,815,815,815
BEGIN DESCRIPTION:
Mapping XS 5932d910
END DESCRIPTION:
XS GIS Cut Line= 3
      2677762.42      6959879.41      2677215.55       6959015.7
      2676110.86      6958331.69
#Sta/Elev= 30
  3836.1  513.66  3891.2  512.62  3905.2   513.9  3918.3  512.46  4152.2  509.41
  4246.3  507.55  4267.5  505.57  4309.8  504.69  4607.3  502.85  4840.3   503.1
  4847.2  502.22  4851.4  499.78  4854.9  499.78  4858.2  501.37    4882  503.39
  4897.4  500.97  4918.7  503.46  5065.2  502.57  5275.6  505.41  5406.7  509.27
  5638.3  517.93  5690.3  517.98  5732.9  521.35  5821.5  522.84  5834.1   524.3
  5857.6  523.87  5921.9  526.62  6001.1  531.95  6074.4  534.28  6157.7  534.62
#Mann= 3 ,-1 , 0
  3836.1     .05       0  4840.3     .03       0    4882     .05       0
Bank Sta=4840.3,4882
XS Rating Curve= 0 ,0
Exp/Cntr=0.3,0.1

Type RM Length L Ch R = 1 ,7867    ,690,690,690
BEGIN DESCRIPTION:
Mapping XS a919dbd1
END DESCRIPTION:
XS GIS Cut Line= 3
      2678166.08       6959853.4      2677762.42      6958711.88
      2677077.06      6958195.69
#Sta/Elev= 30
  3763.6  516.22  4140.7   510.6  4158.6  510.94  4495.7  507.97  4508.6  507.29
  4582.9  506.24  4635.9  506.45  4667.7  505.46  4712.1   505.3  4861.3  502.49
  4879.9  501.53  4901.1  498.98  4992.7  498.98    4993  498.48  4996.5  498.48
  4996.7  498.98  5021.8  499.05  5036.4  500.38  5094.7  500.37  5115.5  499.71
  5171.7  500.14  5271.7  502.41  5415.3  504.36  5565.2  507.25    5636  507.38
  5708.5  509.06  5765.1  512.66    5786     513  5815.1  514.68  5832.4  514.97
#Mann= 3 ,-1 , 0
  3763.6     .03       0  4992.7     .03       0  4996.7     .03       0
Bank Sta=4992.7,4996.7
XS Rating Curve= 0 ,0
Exp/Cntr=0.3,0.1

Type RM Length L Ch R = 1 ,7177    ,71,71,71
BEGIN DESCRIPTION:
Mapping XS 415fc86b
END DESCRIPTION:
XS GIS Cut Line= 3
      2678608.78      6960009.63      2678109.64      6958538.27
      2677475.93      6957882.85
#Sta/Elev= 30
  3439.1  517.84  3835.2  509.72  3891.7  509.96  3929.5  508.78  4112.6  507.12
  4243.5  507.16  4274.9  505.97  4588.9  505.71  4630.9  504.64  4677.9  504.77
  4766.8  502.73    4861  499.25  5224.7  499.09    5225  498.59  5228.7  499.09
  5311.6  500.86  5446.2  501.67  5587.4  506.59  5665.3  507.36  5679.5  508.29
  5686.4  510.87  5693.6  511.08  5700.6   513.5  5707.8  514.22  5736.1  514.75
  5750.2  516.18  5806.8  518.38  5827.9  518.31  5877.6   521.7  5904.5   521.8
#Mann= 3 ,-1 , 0
  3439.1     .03       0  5224.7     .03       0  5228.7     .03       0
Bank Sta=5224.7,5228.7
XS Rating Curve= 0 ,0
Exp/Cntr=0.3,0.1

Type RM Length L Ch R = 1 ,7106    ,58,58,58
BEGIN DESCRIPTION:
Mapping XS 55bd3dbf
END DESCRIPTION:
XS GIS Cut Line= 4
      2679190.09      6959931.74      2678764.43      6959355.23
      2678148.71      6958473.17      2677532.38      6957761.35
#Sta/Elev= 30
  3218.6  518.82  3465.8  513.28  3636.9  511.38  3707.9  508.93  3787.3  508.81
  3865.9   506.1  3887.5  506.96  3934.7  504.36  4095.6  505.14  4110.5  503.66
  4611.2  501.76  4634.7  502.88  4864.1  499.05  5260.8  498.96  5261.1  498.46
  5264.8  498.96  5482.2  502.63  5560.1  505.46  5617.1  509.99  5645.6  510.33
  5659.8  511.87  5674.1  510.16  5680.7  507.49    5752  508.41  5766.2  512.38
  5787.1  520.41  5801.3  523.95  5822.2  523.92    5922  530.17  5952.5  530.36
#Mann= 3 ,-1 , 0
  3218.6     .03       0  5260.8     .03       0  5264.8     .03       0
Bank Sta=5260.8,5264.8
XS Rating Curve= 0 ,0
Exp/Cntr=0.3,0.1

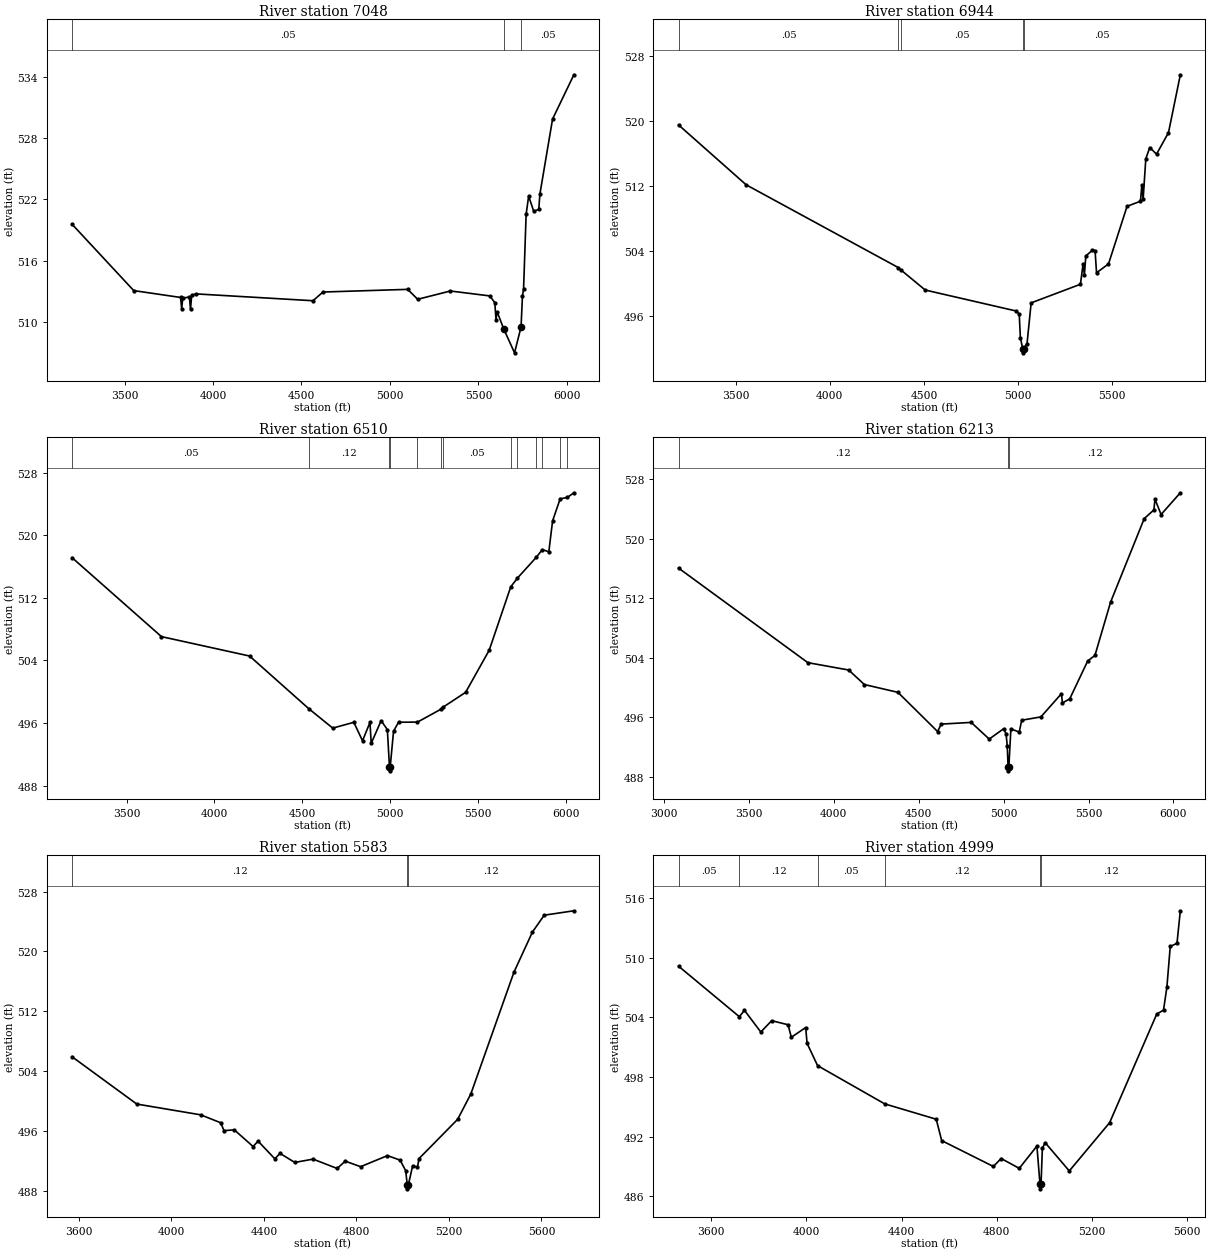
Type RM Length L Ch R = 1 ,7048    ,104,104,104
BEGIN DESCRIPTION:
Mapping XS e49f5474
END DESCRIPTION:
XS GIS Cut Line= 6
      2679275.42      6959876.78      2679025.44      6959526.12
      2678299.75      6958574.73      2677992.17      6958178.25
      2677878.84      6958022.23      2677546.83       6957629.9
#Sta/Elev= 30
  3203.6  519.57  3552.1  513.09  3816.7  512.42    3823  511.34  3829.3  512.36
  3866.6  512.46  3872.9  511.25  3879.6  512.63  3901.9  512.77    4565   512.1
  4621.7  512.95  5100.5  513.21  5156.7  512.24  5341.6  513.05  5564.2  512.57
  5592.6  511.91  5599.3  510.26  5605.9  511.02  5642.2  509.38  5704.1  507.01
    5741  509.54  5748.8  512.53  5755.3  513.28  5769.6  520.53  5783.9  522.32
  5812.5  520.84    5841  521.02  5847.6  522.53    5919  529.84  6039.4  534.17
#Mann= 3 ,-1 , 0
  3203.6     .05       0  5642.2     .03       0    5741     .05       0
Bank Sta=5642.2,5741
XS Rating Curve= 0 ,0
Exp/Cntr=0.3,0.1

Type RM Length L Ch R = 1 ,6944    ,434,434,434
BEGIN DESCRIPTION:
Mapping XS ccc6b077
END DESCRIPTION:
XS GIS Cut Line= 4
      2679313.66      6959835.18      2678442.11      6958644.17
      2678261.55      6958355.98      2677700.01      6957718.18
#Sta/Elev= 30
  3196.5   519.5  3555.7  512.13  4364.2  501.94  4379.6  501.62  4506.9  499.18
  4991.7  496.59  5006.5  496.18  5012.4  493.32    5025  491.95  5025.3  491.45
  5029.2  491.95  5047.9  492.59  5069.7   497.6  5331.6  499.89  5345.8  502.43
  5352.5  501.02  5360.1  503.38  5395.2  504.07  5409.4  504.02    5417   501.3
  5480.6  502.39  5579.2  509.48  5650.4  510.11    5658  512.13  5664.6  510.35
  5678.8  515.33  5699.7  516.72  5735.8   515.9  5799.3  518.55  5862.2  525.67
#Mann= 5 ,-1 , 0
  3196.5     .05       0  4364.2     .12       0  4379.6     .05       0
    5025     .03       0  5029.2     .05       0
Bank Sta=5025,5029.2
XS Rating Curve= 0 ,0
Exp/Cntr=0.3,0.1

Type RM Length L Ch R = 1 ,6510    ,297,297,297
BEGIN DESCRIPTION:
Mapping XS 8d24319f
END DESCRIPTION:
XS GIS Cut Line= 3
      2679882.94      6959444.18      2678586.06      6958142.09
      2677893.36      6957392.09
#Sta/Elev= 30
  3188.7  517.14  3697.9  507.05  4199.9  504.57  4536.8  497.85  4673.7  495.36
  4793.9   496.1  4843.4  493.74  4885.9  496.09  4892.9  493.41  4949.5  496.31
  4984.9  495.17  4996.9   490.4  4997.2   489.9  5001.1   490.4  5020.2  494.97
  5048.5  496.11  5156.6  496.13  5288.2  497.75  5302.7  498.04  5430.7  499.93
  5565.1  505.31  5687.6   513.4  5725.6  514.52  5833.2  517.18  5867.8  518.17
  5904.7  517.89  5926.3  521.84  5969.4  524.66  6010.1  524.83  6047.4  525.43
#Mann= 13 ,-1 , 0
  3188.7     .05       0  4536.8     .12       0  4996.9     .07       0
  5001.1     .12       0  5156.6     .05       0  5288.2     .12       0
  5302.7     .05       0  5687.6     .12       0  5725.6     .05       0
  5833.2     .12       0  5867.8     .05       0  5969.4     .12       0
  6010.1     .05       0
Bank Sta=4996.9,5001.1
XS Rating Curve= 0 ,0
Exp/Cntr=0.3,0.1

Type RM Length L Ch R = 1 ,6213    ,630,630,630
BEGIN DESCRIPTION:
Mapping XS 84ad3f0c
END DESCRIPTION:
XS GIS Cut Line= 3
      2680096.51      6959397.33      2678757.94      6958017.09
      2678054.79      6957261.86
#Sta/Elev= 30
    3086  516.05  3847.4  503.34  4087.9  502.35    4180   500.4  4377.8  499.35
  4611.4  494.08  4632.5  495.08  4809.2  495.31  4915.4  493.07  5000.3  494.46
  5014.5  493.79  5021.4  492.19  5026.5   489.3  5026.9   488.8  5030.9   489.3
  5042.9  494.44  5092.2  494.01  5106.4   495.6  5219.7  496.05  5339.9  499.15
  5346.8  497.93  5389.3  498.47  5495.3  503.57  5537.8  504.31  5630.2  511.49
    5828   522.7  5884.7  523.86  5891.5   525.3  5927.2  523.25  6040.6  526.17
#Mann= 3 ,-1 , 0
    3086     .12       0  5026.5     .07       0  5030.9     .12       0
Bank Sta=5026.5,5030.9
XS Rating Curve= 0 ,0
Exp/Cntr=0.3,0.1

Type RM Length L Ch R = 1 ,5583    ,584,584,584
BEGIN DESCRIPTION:
Mapping XS 3fa35a60
END DESCRIPTION:
XS GIS Cut Line= 3
      2679921.12      6958879.91      2679185.02       6957671.6
      2678761.41       6957046.6
#Sta/Elev= 30
  3570.5  505.93  3850.3  499.61  4126.8  498.17  4213.2  497.11  4227.5  496.05
  4271.8  496.17  4353.4  493.93  4374.7  494.66  4447.4  492.29  4469.6  493.02
  4533.5  491.81  4612.9  492.25  4716.8     491  4751.9  491.98  4818.2  491.24
  4934.4  492.72  4988.8  492.12  5013.3   490.7    5020  488.78  5020.4  488.28
  5024.5  488.78  5043.2  491.36  5064.2  491.18  5070.7  492.32  5237.9  497.57
  5294.8  500.95  5481.4  517.24  5561.4  522.61  5612.3  524.85  5740.4  525.44
#Mann= 3 ,-1 , 0
  3570.5     .12       0    5020     .07       0  5024.5     .12       0
Bank Sta=5020,5024.5
XS Rating Curve= 0 ,0
Exp/Cntr=0.3,0.1

Type RM Length L Ch R = 1 ,4999    ,468,468,468
BEGIN DESCRIPTION:
Muddy T11 8.0
END DESCRIPTION:
XS GIS Cut Line= 3
      2680276.01      6958811.01        2679626.        6957411.
      2679226.02      6957011.02
#Sta/Elev= 30
  3462.7  509.13  3718.3  504.05  3739.8  504.69  3808.5  502.51  3854.3  503.65
    3923  503.24  3936.8  501.98  3997.2  502.96    4003  501.37  4047.1  499.13
  4329.6  495.28  4545.9  493.74  4568.8  491.59    4786  488.99  4818.8  489.79
  4894.9   488.8  4969.1  491.04  4981.9  487.24  4982.4  486.74  4986.5  487.24
    4992   490.8  5003.5  491.39  5105.2  488.54  5274.9   493.4  5472.9  504.32
  5501.2  504.71  5515.4  507.01  5529.5  511.11  5557.8  511.43  5571.9   514.7
#Mann= 6 ,-1 , 0
  3462.7     .05       0  3718.3     .12       0  4047.1     .05       0
  4329.6     .12       0  4981.9     .07       0  4986.5     .12       0
Bank Sta=4981.9,4986.5
XS Rating Curve= 0 ,0
Exp/Cntr=0.3,0.1

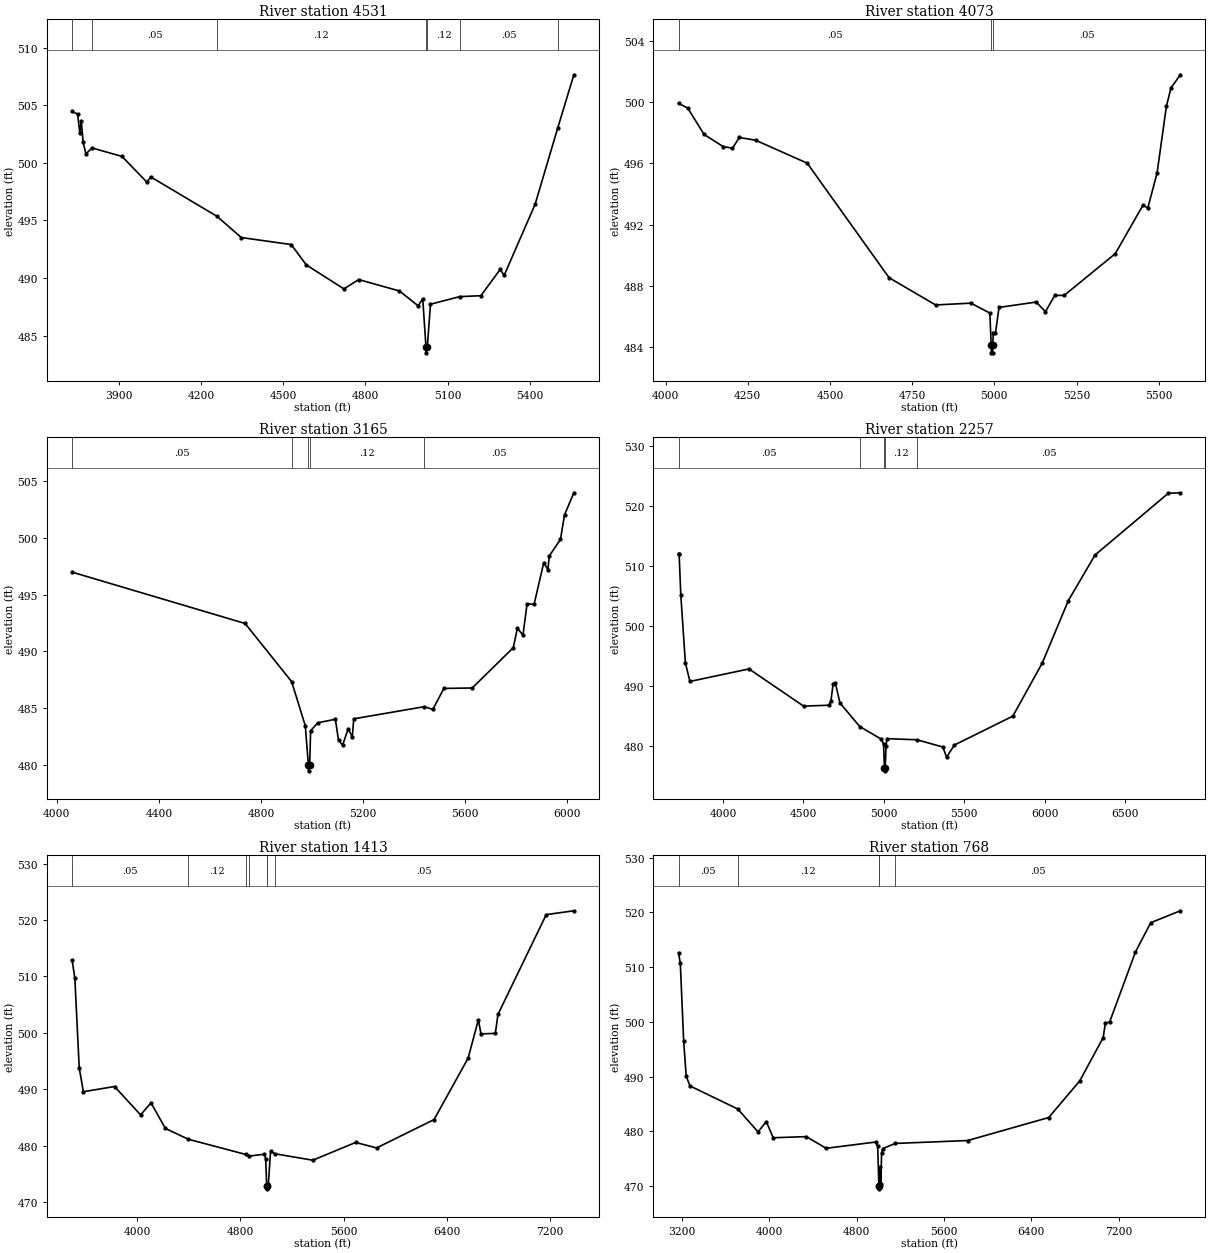
Type RM Length L Ch R = 1 ,4531    ,458,458,458
BEGIN DESCRIPTION:
Muddy T11 7.0
END DESCRIPTION:
XS GIS Cut Line= 3
        2680176.      6958410.98        2679976.        6957161.
      2679575.97      6956760.97
#Sta/Elev= 30
  3729.2  504.48  3749.4  504.23  3757.7  502.56  3762.7  503.67  3769.7  501.78
  3779.8  500.78  3801.8   501.3  3911.5  500.56  4002.6  498.32  4015.9  498.79
  4257.7  495.37  4346.9  493.52  4529.2  492.91  4584.3  491.14  4721.6  489.06
  4775.4  489.87  4924.2  488.88  4992.5  487.59  5009.2  488.21    5021  484.01
  5021.5  483.51  5025.8  484.01  5037.5  487.73  5144.1  488.39  5221.4  488.47
  5292.1  490.76  5306.2  490.23  5419.3   496.4  5501.9  503.03  5560.8  507.65
#Mann= 7 ,-1 , 0
  3729.2     .12       0  3801.8     .05       0  4257.7     .12       0
    5021     .07       0  5025.8     .12       0  5144.1     .05       0
  5501.9     .12       0
Bank Sta=5021,5025.8
XS Rating Curve= 0 ,0
Exp/Cntr=0.3,0.1

Type RM Length L Ch R = 1 ,4073    ,908,908,908
BEGIN DESCRIPTION:
Muddy T11 6.0
END DESCRIPTION:
XS GIS Cut Line= 3
      2680876.03      6957611.03        2680276.        6956861.
        2679876.        6956461.
#Sta/Elev= 30
  4039.5  499.93  4067.6  499.62  4117.2   497.9  4174.8  497.11  4203.6     497
  4224.4   497.7  4274.1  497.52  4430.9  496.02  4679.9  488.53  4821.5  486.75
  4928.8  486.87  4986.4  486.22  4990.4  484.12    4991  483.62  4994.7  483.62
  4995.2  484.12  4996.8  484.92  5003.5  484.92  5014.2  486.59  5127.3  486.94
  5155.6  486.31  5183.9  487.38  5212.1  487.37  5367.7   490.1  5452.6  493.29
  5466.7  493.08    5495  495.38  5523.3  499.74  5537.4  500.95  5565.7   501.8
#Mann= 3 ,-1 , 0
  4039.5     .05       0  4990.4     .04       0  4995.2     .05       0
Bank Sta=4990.4,4995.2
XS Rating Curve= 0 ,0
Exp/Cntr=0.3,0.1

Type RM Length L Ch R = 1 ,3165    ,908,908,908
BEGIN DESCRIPTION:
Mapping XS 641d105c
END DESCRIPTION:
XS GIS Cut Line= 3
      2681435.05      6956999.76      2680877.73      6956244.52
      2679976.66      6955749.71
#Sta/Elev= 30
  4059.9  496.99    4738  492.46  4920.4  487.33    4974  483.43  4986.1  479.96
  4986.7  479.46  4991.1  479.96  4994.8     483  5023.3   483.7  5091.8  484.01
  5104.1  482.17  5120.2  481.72    5142  483.17  5158.1  482.45  5163.8  484.05
  5440.6  485.12  5473.6  484.88  5517.2  486.73    5628  486.77  5789.1  490.32
  5805.2  492.05    5827  491.42  5843.1  494.19  5870.6  494.15  5908.5  497.82
  5924.6   497.2  5930.3  498.42  5973.9  499.87    5990  502.05  6026.5  503.99
#Mann= 5 ,-1 , 0
  4059.9     .05       0  4920.4     .12       0  4986.1     .07       0
  4991.1     .12       0  5440.6     .05       0
Bank Sta=4986.1,4991.1
XS Rating Curve= 0 ,0
Exp/Cntr=0.3,0.1

Type RM Length L Ch R = 1 ,2257    ,844,844,844
BEGIN DESCRIPTION:
Muddy T11 2.0
END DESCRIPTION:
XS GIS Cut Line= 4
      2682125.99      6956410.99        2681226.        6955511.
      2680212.92      6955257.73      2679411.39        6955194.
#Sta/Elev= 30
  3722.8  512.06  3726.3  512.06  3736.9  505.16  3765.2  493.86  3793.5  490.72
  4161.2  492.81  4500.6   486.6  4656.2  486.75  4670.3  487.41  4684.5  490.33
  4698.6  490.41  4726.9  487.13  4850.1  483.19  4981.4  481.13  4998.2  480.27
  5003.3   476.3    5004   475.8  5008.4   476.3  5013.6  479.91  5018.8  481.17
  5204.8  480.99  5366.7  479.78  5389.8  478.09  5438.8  480.11  5802.2  484.93
  5985.1  493.79  6147.1   504.2  6313.3  511.82  6769.1  522.13  6843.9  522.21
#Mann= 5 ,-1 , 0
  3722.8     .05       0  4850.1     .12       0  5003.3     .07       0
  5008.4     .12       0  5204.8     .05       0
Bank Sta=5003.3,5008.4
XS Rating Curve= 0 ,0
Exp/Cntr=0.3,0.1

Type RM Length L Ch R = 1 ,1413    ,645,645,645
BEGIN DESCRIPTION:
Mapping XS 13e82cb9
END DESCRIPTION:
XS GIS Cut Line= 4
      2682364.13        6956260.       2681655.8      6954937.08
      2681021.01      6954749.84      2679314.47      6955010.04
#Sta/Elev= 30
  3494.8  512.95  3516.3  509.68  3550.4  493.76  3582.5  489.57  3823.7  490.49
  4026.1  485.46  4106.2   487.6  4217.8  483.07  4395.3  481.15  4841.2  478.45
  4865.4  478.15  4984.8   478.5  4995.4  477.61    5003  472.86  5003.7  472.36
  5008.2  472.86    5016  473.25  5033.1  478.98  5066.1  478.58  5360.1  477.43
  5692.6  480.58  5854.5  479.61  6299.9  484.63  6564.1  495.52  6643.5  502.32
  6663.7  499.82    6775   499.9  6795.2  503.26  7169.5  520.95  7383.5  521.63
#Mann= 7 ,-1 , 0
  3494.8     .05       0  4395.3     .12       0  4841.2     .05       0
  4865.4     .12       0    5003     .07       0  5008.2     .12       0
  5066.1     .05       0
Bank Sta=5003,5008.2
XS Rating Curve= 0 ,0
Exp/Cntr=0.3,0.1

Type RM Length L Ch R = 1 ,768     ,0,0,0
BEGIN DESCRIPTION:
Muddy T11 1.0
END DESCRIPTION:
XS GIS Cut Line= 3
      2682700.99      6956135.97      2681948.92        6954411.
      2679281.45       6954915.8
#Sta/Elev= 30
  3168.1  512.64  3184.4  510.68  3214.9  496.53  3238.3  490.11  3272.7  488.31
  3711.2  484.09  3896.3  479.92    3972  481.79  4035.3  478.85  4339.7  479.05
    4520  476.92  4974.3  478.07  4992.3  477.28  5003.6  470.02  5004.4  469.52
  5008.9  470.02  5015.7  473.54  5021.1  470.35  5028.1  475.98    5039  476.87
  5153.6  477.81  5816.2  478.34  6559.1  482.54  6844.1  489.25  7057.8  497.13
  7078.2  499.79  7117.1  499.98    7353  512.74  7493.6  518.11  7764.7  520.29
#Mann= 5 ,-1 , 0
  3168.1     .05       0  3711.2     .12       0  5003.6     .07       0
  5008.9     .12       0  5153.6     .05       0
Bank Sta=5003.6,5008.9
XS Rating Curve= 0 ,0
Exp/Cntr=0.3,0.1

Chan Stop Cuts=-1
Use User Specified Reach Order=0
Composite Channel Slope=5