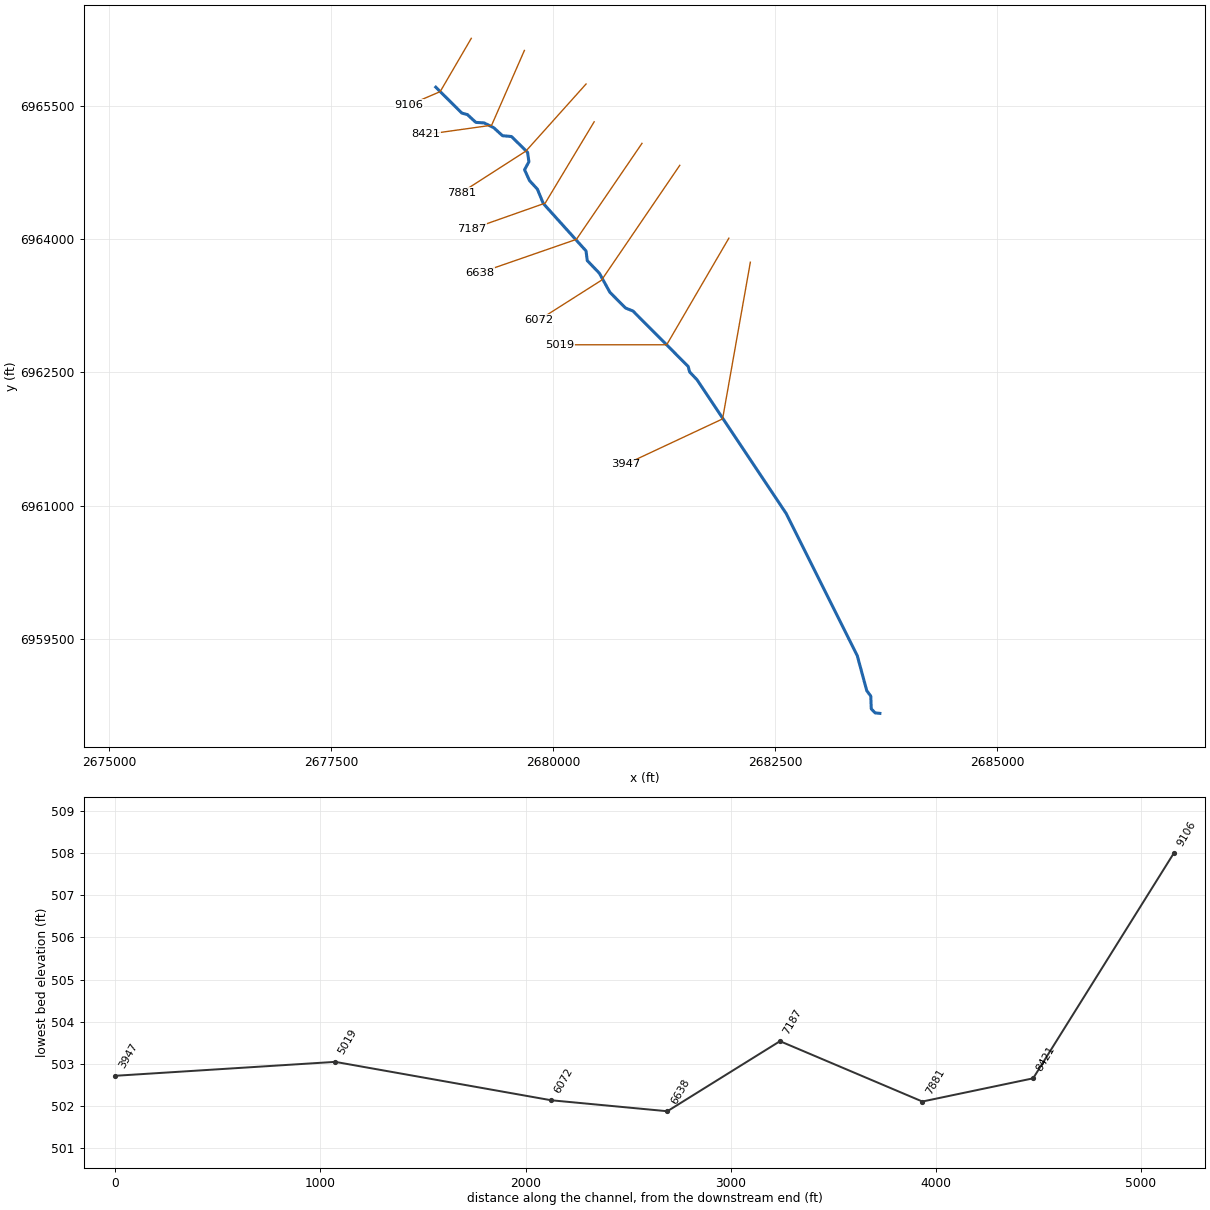
--- Muddy T12.prj (project) ---

Proj Title=Muddy T12 Base Level Engineering
Current Plan=p01
Default Exp/Contr=0.3,0.1
English Units
Geom File=g01
Flow File=f01
Plan File=p01
BEGIN DESCRIPTION:
Muddy T12
END DESCRIPTION:

--- Muddy T12.p01 (plan) ---

Plan Title=Multiple Run
Short Identifier=Multiple
Geom File=g01
Flow File=f01
Subcritical Flow
K Sum by GR= 0
Std Step Tol= 0.01
Critical Tol= 0.01
Num of Std Step Trials= 20
Max Error Tol= 0.3
Flow Tol Ratio= 0.001
Split Flow NTrial= 30
Split Flow Tol= 0.02
Split Flow Ratio= 0.02
Log Output Level= 0
Friction Slope Method= 1
Unsteady Friction Slope Method= 2
Unsteady Bridges Friction Slope Method= 1
Parabolic Critical Depth
Global Vel Dist=  1 , 1 , 1
Global Log Level= 0
CheckData=True
Encroach Param= -1, 0, 0, 0
BEGIN DESCRIPTION:
Multiple Run
END DESCRIPTION:

--- Muddy T12.f01 (steady flow) ---

Flow Title=Multiple
Number of Profiles=7
Profile Names=10-year,25-year,50-year,1pct_min,100-year,1pct_plu,500-year
River Rch & RM= Muddy T12,Reach-1,9106
     695     943    1145     691    1378    2749    1992
River Rch & RM= Muddy T12,Reach-1,7187
     843    1142    1385     832    1660    3313    2386
Boundary for River Rch & Prof#=Muddy T12,Reach-1,1
Up Type=0
Dn Type=3
Dn Slope=0.005
Boundary for River Rch & Prof#=Muddy T12,Reach-1,2
Up Type=0
Dn Type=3
Dn Slope=0.005
Boundary for River Rch & Prof#=Muddy T12,Reach-1,3
Up Type=0
Dn Type=3
Dn Slope=0.005
Boundary for River Rch & Prof#=Muddy T12,Reach-1,4
Up Type=0
Dn Type=3
Dn Slope=0.005
Boundary for River Rch & Prof#=Muddy T12,Reach-1,5
Up Type=0
Dn Type=3
Dn Slope=0.005
Boundary for River Rch & Prof#=Muddy T12,Reach-1,6
Up Type=0
Dn Type=3
Dn Slope=0.005
Boundary for River Rch & Prof#=Muddy T12,Reach-1,7
Up Type=0
Dn Type=3
Dn Slope=0.005

--- Muddy T12.g01 (geometry) ---

Geom Title=Existing Conditions

River Reach=Muddy T12,Reach-1
Reach XY= 30
      2678676.00      6965711.00      2678969.95      6965419.16
      2679032.04      6965402.82      2679127.50      6965314.62
      2679220.03      6965308.67      2679328.29      6965255.15
      2679427.50      6965164.63      2679528.43      6965155.48
      2679709.60      6964977.75      2679724.88      6964871.55
      2679675.71      6964781.17      2679731.84      6964658.71
      2679820.15      6964563.29      2679886.76      6964401.32
      2680368.14      6963867.17      2680381.52      6963758.57
      2680517.84      6963617.05      2680636.78      6963401.32
      2680812.79      6963224.63      2680896.09      6963191.21
      2681517.84      6962567.05      2681534.18      6962504.96
      2681617.82      6962417.04      2682620.15      6960913.29
      2683422.17      6959309.42      2683528.36      6958916.98
      2683573.73      6958855.06      2683579.38      6958712.27
      2683623.05      6958666.13      2683676.00      6958661.00

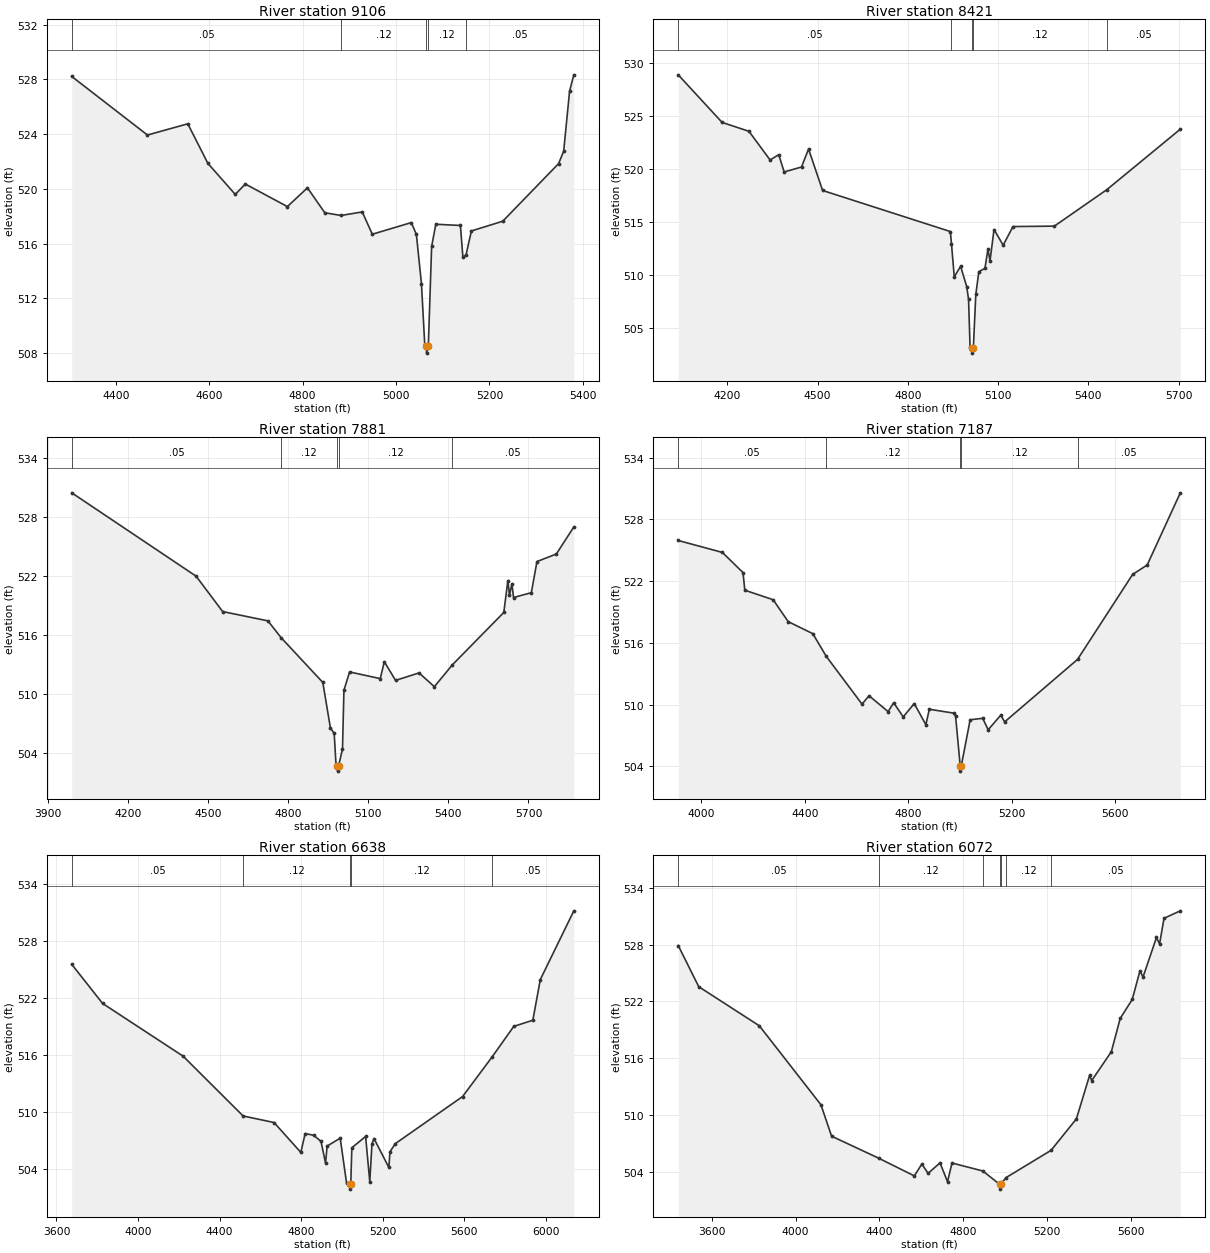
Type RM Length L Ch R = 1,9106,685,685,685
BEGIN DESCRIPTION:
Muddy T12 12.0
END DESCRIPTION:
XS GIS Cut Line= 3
      2679075.99      6966260.98      2678726.00      6965661.00
      2678375.98      6965510.99
#Sta/Elev= 30
  4305.4  528.21  4467.5  523.93  4553.9  524.75  4596.9  521.86  4655.6  519.59
  4677.1  520.35  4767.2  518.70  4810.2  520.07  4847.4  518.25  4882.1  518.05
  4927.6  518.31  4949.1  516.68  5032.6  517.53  5043.5  516.67  5054.4  513.06
  5061.6  508.52  5065.1  508.49  5065.3  507.99  5069.1  508.49  5076.2  515.79
  5085.2  517.41  5137.8  517.32  5143.2  514.98  5150.0  515.19  5161.4  516.92
  5228.5  517.63  5348.1  521.84  5359.0  522.74  5371.7  527.15  5380.8  528.33
#Mann=5,-1,0
  4305.4    0.05       0  4882.1    0.12       0  5065.1    0.07       0
  5069.1    0.12       0  5150.0    0.05       0
Bank Sta=5065.1,5069.1
Exp/Cntr=0.3,0.1

Type RM Length L Ch R = 1,8421,540,540,540
BEGIN DESCRIPTION:
Mapping XS 354887cb
END DESCRIPTION:
XS GIS Cut Line= 3
      2679673.98      6966124.50      2679305.06      6965282.48
      2678562.92      6965178.32
#Sta/Elev= 30
  4036.7  528.87  4182.4  524.39  4271.8  523.55  4342.0  520.85  4370.8  521.35
  4388.7  519.72  4446.4  520.19  4469.8  521.88  4516.5  517.98  4941.2  514.11
  4944.8  512.97  4954.1  509.84  4975.2  510.84  4995.4  508.93  5001.6  507.74
  5006.6  503.25  5013.6  503.16  5013.9  502.66  5017.6  503.16  5025.7  508.19
  5035.8  510.33  5056.0  510.64  5066.1  512.46  5072.9  511.35  5086.3  514.30
  5116.6  512.82  5149.2  514.58  5286.8  514.62  5461.4  518.06  5705.4  523.75
#Mann=5,-1,0
  4036.7    0.05       0  4944.8    0.12       0  5013.6    0.07       0
  5017.6    0.12       0  5461.4    0.05       0
Bank Sta=5013.6,5017.6
Exp/Cntr=0.3,0.1

Type RM Length L Ch R = 1,7881,694,694,694
BEGIN DESCRIPTION:
Mapping XS ebcc0ab6
END DESCRIPTION:
XS GIS Cut Line= 3
      2680368.41      6965746.87      2679691.35      6964991.69
      2678962.17      6964522.93
#Sta/Elev= 30
  3989.0  530.45  4454.9  521.96  4554.3  518.36  4724.0  517.41  4773.0  515.71
  4929.6  511.14  4958.0  506.51  4972.2  505.96  4978.9  502.81  4984.4  502.61
  4984.7  502.11  4988.4  502.61  5003.3  504.36  5008.7  510.35  5029.9  512.21
  5144.8  511.53  5160.0  513.25  5202.2  511.35  5290.1  512.11  5347.5  510.71
  5414.8  512.93  5607.7  518.27  5622.9  521.52  5628.9  520.03  5638.1  521.19
  5644.1  519.79  5710.8  520.28  5731.9  523.45  5804.6  524.22  5870.1  526.98
#Mann=5,-1,0
  3989.0    0.05       0  4773.0    0.12       0  4984.4    0.07       0
  4988.4    0.12       0  5414.8    0.05       0
Bank Sta=4984.4,4988.4
Exp/Cntr=0.3,0.1

Type RM Length L Ch R = 1,7187,549,549,549
BEGIN DESCRIPTION:
Mapping XS bc3d33fe
END DESCRIPTION:
XS GIS Cut Line= 3
      2680459.59      6965321.58      2679908.36      6964405.75
      2679085.17      6964115.46
#Sta/Elev= 30
  3910.3  525.94  4081.2  524.78  4160.8  522.82  4167.8  521.11  4277.3  520.19
  4335.6  518.06  4430.8  516.89  4483.0  514.68  4621.1  510.05  4648.3  510.86
  4722.1  509.32  4743.5  510.18  4780.4  508.81  4823.1  510.10  4868.1  508.05
  4881.4  509.55  4976.5  509.17  4983.1  508.85  5000.9  504.04  5001.2  503.54
  5004.9  504.04  5039.3  508.53  5087.8  508.67  5109.0  507.56  5157.8  508.98
  5172.6  508.32  5454.6  514.39  5667.9  522.65  5724.0  523.56  5852.1  530.57
#Mann=5,-1,0
  3910.3    0.05       0  4483.0    0.12       0  5000.9    0.07       0
  5004.9    0.12       0  5454.6    0.05       0
Bank Sta=5000.9,5004.9
Exp/Cntr=0.3,0.1

Type RM Length L Ch R = 1,6638,566,566,566
BEGIN DESCRIPTION:
Mapping XS c5cade58
END DESCRIPTION:
XS GIS Cut Line= 3
      2680997.75      6965078.46      2680259.92      6963997.76
      2679170.74      6963620.24
#Sta/Elev= 30
  3675.2  525.57  3826.3  521.45  4221.1  515.89  4515.2  509.59  4666.8  508.90
  4798.2  505.75  4819.3  507.74  4861.2  507.55  4897.1  506.91  4919.3  504.62
  4927.0  506.42  4991.2  507.25  5022.3  502.52  5038.8  502.38  5039.1  501.88
  5042.8  502.38  5048.2  506.24  5115.7  507.43  5136.1  502.66  5146.9  506.67
  5157.2  507.20  5229.7  504.16  5235.0  505.81  5260.9  506.67  5591.2  511.64
  5736.1  515.82  5842.0  519.03  5935.4  519.68  5972.2  523.97  6136.5  531.21
#Mann=5,-1,0
  3675.2    0.05       0  4515.2    0.12       0  5038.8    0.07       0
  5042.8    0.12       0  5736.1    0.05       0
Bank Sta=5038.8,5042.8
Exp/Cntr=0.3,0.1

Type RM Length L Ch R = 1,6072,1053,1053,1053
BEGIN DESCRIPTION:
Mapping XS 09d4e5b7
END DESCRIPTION:
XS GIS Cut Line= 3
      2681423.13      6964831.12      2680542.04      6963537.69
      2679839.95      6963091.30
#Sta/Elev= 30
  3440.1  527.90  3537.9  523.55  3827.4  519.41  4121.4  511.06  4172.2  507.74
  4397.2  505.41  4567.2  503.54  4603.1  504.79  4633.0  503.81  4689.9  504.92
  4725.8  502.92  4747.0  504.90  4894.1  504.06  4975.1  502.64  4975.4  502.14
  4979.2  502.64  5005.2  503.36  5220.0  506.24  5341.0  509.57  5404.5  514.20
  5413.8  513.61  5507.8  516.67  5550.1  520.19  5607.7  522.20  5644.1  525.20
  5659.3  524.58  5723.3  528.75  5738.1  528.07  5759.3  530.78  5837.1  531.57
#Mann=7,-1,0
  3440.1    0.05       0  4397.2    0.12       0  4894.1     0.1       0
  4975.1    0.07       0  4979.2     0.1       0  5005.2    0.12       0
  5220.0    0.05       0
Bank Sta=4975.1,4979.2
Exp/Cntr=0.3,0.1

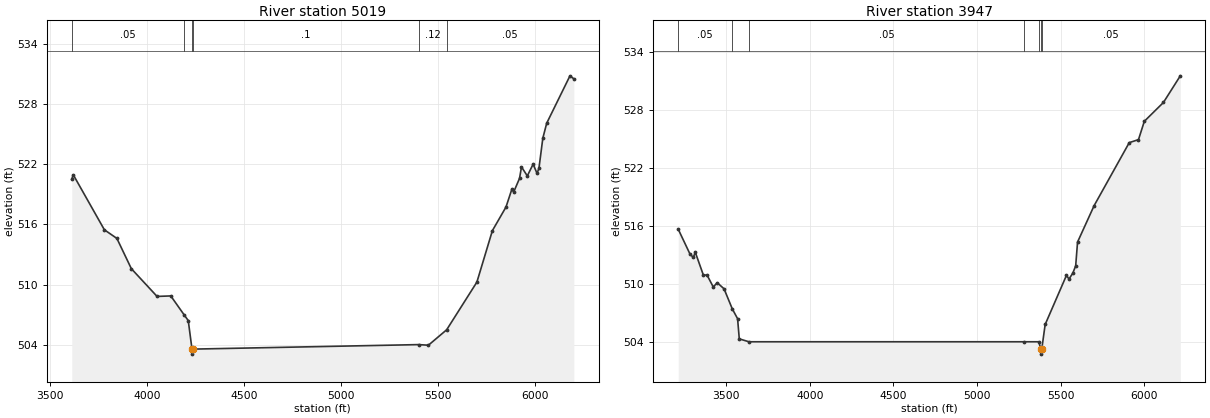
Type RM Length L Ch R = 1,5019,1072,1072,1072
BEGIN DESCRIPTION:
Muddy T12 3.0
END DESCRIPTION:
XS GIS Cut Line= 3
      2681975.98      6964010.97      2681276.00      6962811.00
      2680076.01      6962811.00
#Sta/Elev= 30
  3610.8  520.51  3618.6  520.95  3779.0  515.46  3843.5  514.60  3918.0  511.58
  4050.7  508.81  4121.4  508.86  4192.1  506.92  4211.5  506.40  4230.8  503.55
  4231.2  503.05  4235.3  503.55  5399.6  504.00  5450.0  503.94  5544.1  505.48
  5700.0  510.24  5780.0  515.38  5850.0  517.73  5880.0  519.49  5890.0  519.24
  5920.0  520.60  5930.0  521.74  5960.0  520.84  5990.0  522.01  6010.0  521.10
  6020.0  521.59  6040.0  524.60  6060.0  526.10  6180.0  530.83  6200.0  530.53
#Mann=6,-1,0
  3610.8    0.05       0  4192.1     0.1       0  4230.8    0.07       0
  4235.3     0.1       0  5399.6    0.12       0  5544.1    0.05       0
Bank Sta=4230.8,4235.3
Exp/Cntr=0.3,0.1

Type RM Length L Ch R = 1,3947,0,0,0
BEGIN DESCRIPTION:
Mapping XS fb28096a
END DESCRIPTION:
XS GIS Cut Line= 3
      2682217.91      6963740.31      2681905.41      6961976.41
      2680809.61      6961463.19
#Sta/Elev= 30
  3213.3  515.66  3283.7  513.08  3304.0  512.73  3314.7  513.30  3363.7  510.90
  3385.3  510.92  3422.8  509.67  3446.2  510.12  3487.0  509.49  3536.4  507.41
  3568.1  506.39  3578.2  504.30  3636.2  504.00  5280.1  504.00  5368.5  504.00
  5381.6  503.22  5382.1  502.72  5386.3  503.22  5406.8  505.79  5534.1  510.88
  5549.3  510.50  5572.1  511.11  5589.3  511.87  5600.4  514.33  5699.7  518.11
  5909.5  524.63  5964.7  524.94  5999.6  526.84  6113.8  528.79  6214.7  531.55
#Mann=7,-1,0
  3213.3    0.05       0  3536.4     0.1       0  3636.2    0.05       0
  5280.1     0.1       0  5368.5    0.05       0  5381.6    0.03       0
  5386.3    0.05       0
Bank Sta=5381.6,5386.3
Exp/Cntr=0.3,0.1

Chan Stop Cuts=-1