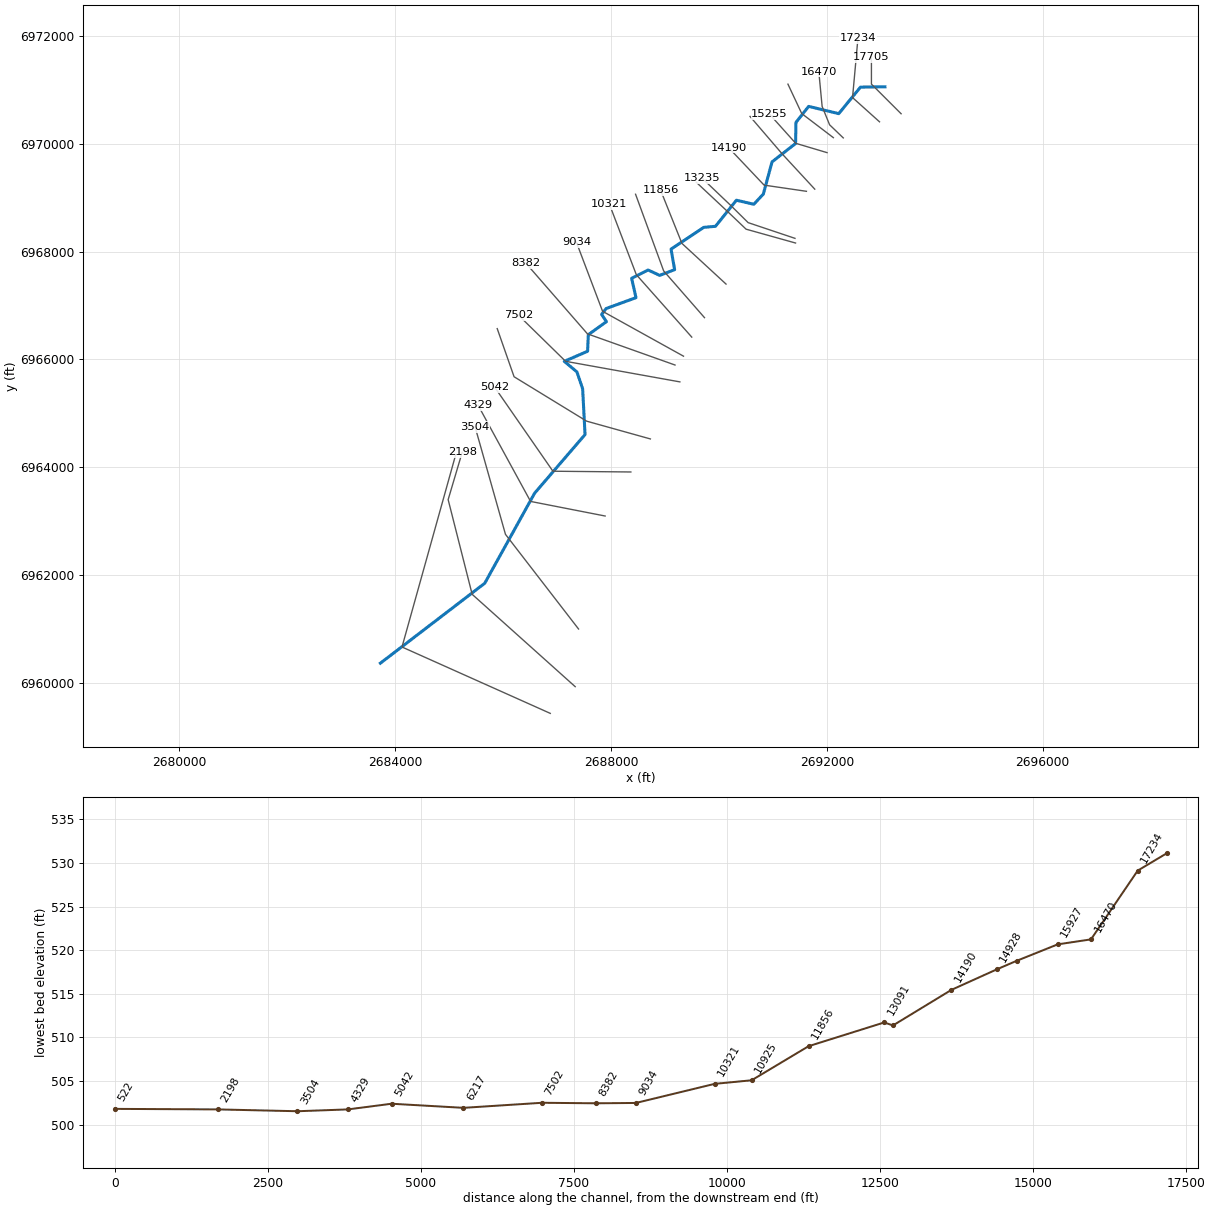
--- Muddy T13.prj (project) ---

Proj Title=Muddy T13 Base Level Engineering
Current Plan=p01
Default Exp/Contr=0.3,0.1
English Units
Geom File=g01
Flow File=f01
Plan File=p01
BEGIN DESCRIPTION:
Muddy T13
END DESCRIPTION:

--- Muddy T13.p01 (plan) ---

Plan Title=Multiple Run
Short Identifier=Multiple
Geom File=g01
Flow File=f01
Subcritical Flow
K Sum by GR= 0
Std Step Tol= 0.01
Critical Tol= 0.01
Num of Std Step Trials= 20
Max Error Tol= 0.3
Flow Tol Ratio= 0.001
Split Flow NTrial= 30
Split Flow Tol= 0.02
Split Flow Ratio= 0.02
Log Output Level= 0
Friction Slope Method= 1
Unsteady Friction Slope Method= 2
Unsteady Bridges Friction Slope Method= 1
Parabolic Critical Depth
Global Vel Dist=  1 , 1 , 1
Global Log Level= 0
CheckData=True
Encroach Param= -1, 0, 0, 0
BEGIN DESCRIPTION:
Multiple Run
END DESCRIPTION:

--- Muddy T13.f01 (steady flow) ---

Flow Title=Multiple
Number of Profiles=7
Profile Names=10-year,25-year,50-year,1pct_min,100-year,1pct_plu,500-year
River Rch & RM= Muddy T13,Reach-1,17705
     745    1010    1227     739    1475    2943    2131
River Rch & RM= Muddy T13,Reach-1,15255
     890    1216    1483     897    1789    3570    2603
River Rch & RM= Muddy T13,Reach-1,11856
    1454    2034    2521    1545    3083    6151    4612
River Rch & RM= Muddy T13,Reach-1,6217
    1435    1992    2456    1496    2985    5956    4413
Boundary for River Rch & Prof#=Muddy T13,Reach-1,1
Up Type=0
Dn Type=3
Dn Slope=0.005
Boundary for River Rch & Prof#=Muddy T13,Reach-1,2
Up Type=0
Dn Type=3
Dn Slope=0.005
Boundary for River Rch & Prof#=Muddy T13,Reach-1,3
Up Type=0
Dn Type=3
Dn Slope=0.005
Boundary for River Rch & Prof#=Muddy T13,Reach-1,4
Up Type=0
Dn Type=3
Dn Slope=0.005
Boundary for River Rch & Prof#=Muddy T13,Reach-1,5
Up Type=0
Dn Type=3
Dn Slope=0.005
Boundary for River Rch & Prof#=Muddy T13,Reach-1,6
Up Type=0
Dn Type=3
Dn Slope=0.005
Boundary for River Rch & Prof#=Muddy T13,Reach-1,7
Up Type=0
Dn Type=3
Dn Slope=0.005

--- Muddy T13.g01 (geometry) ---

Geom Title=Existing Conditions

River Reach=Muddy T13,Reach-1
Reach XY= 30
      2693076.00      6971061.00      2692623.56      6971055.48
      2692219.95      6970562.58      2691662.32      6970697.73
      2691427.11      6970399.26      2691420.55      6970008.53
      2690983.75      6969667.45      2690822.59      6969069.44
      2690646.09      6968880.42      2690323.54      6968955.55
      2689935.73      6968471.76      2689719.27      6968451.85
      2689112.19      6968047.77      2689178.77      6967666.36
      2688901.03      6967560.50      2688686.69      6967660.24
      2688381.56      6967505.38      2688462.68      6967146.88
      2687909.21      6966944.56      2687825.41      6966836.00
      2687915.05      6966700.98      2687579.04      6966459.58
      2687565.48      6966151.21      2687133.58      6965964.35
      2687368.30      6965767.47      2687473.76      6965455.07
      2687518.19      6964604.81      2686584.16      6963517.05
      2685659.36      6961844.32      2683726.00      6960361.00

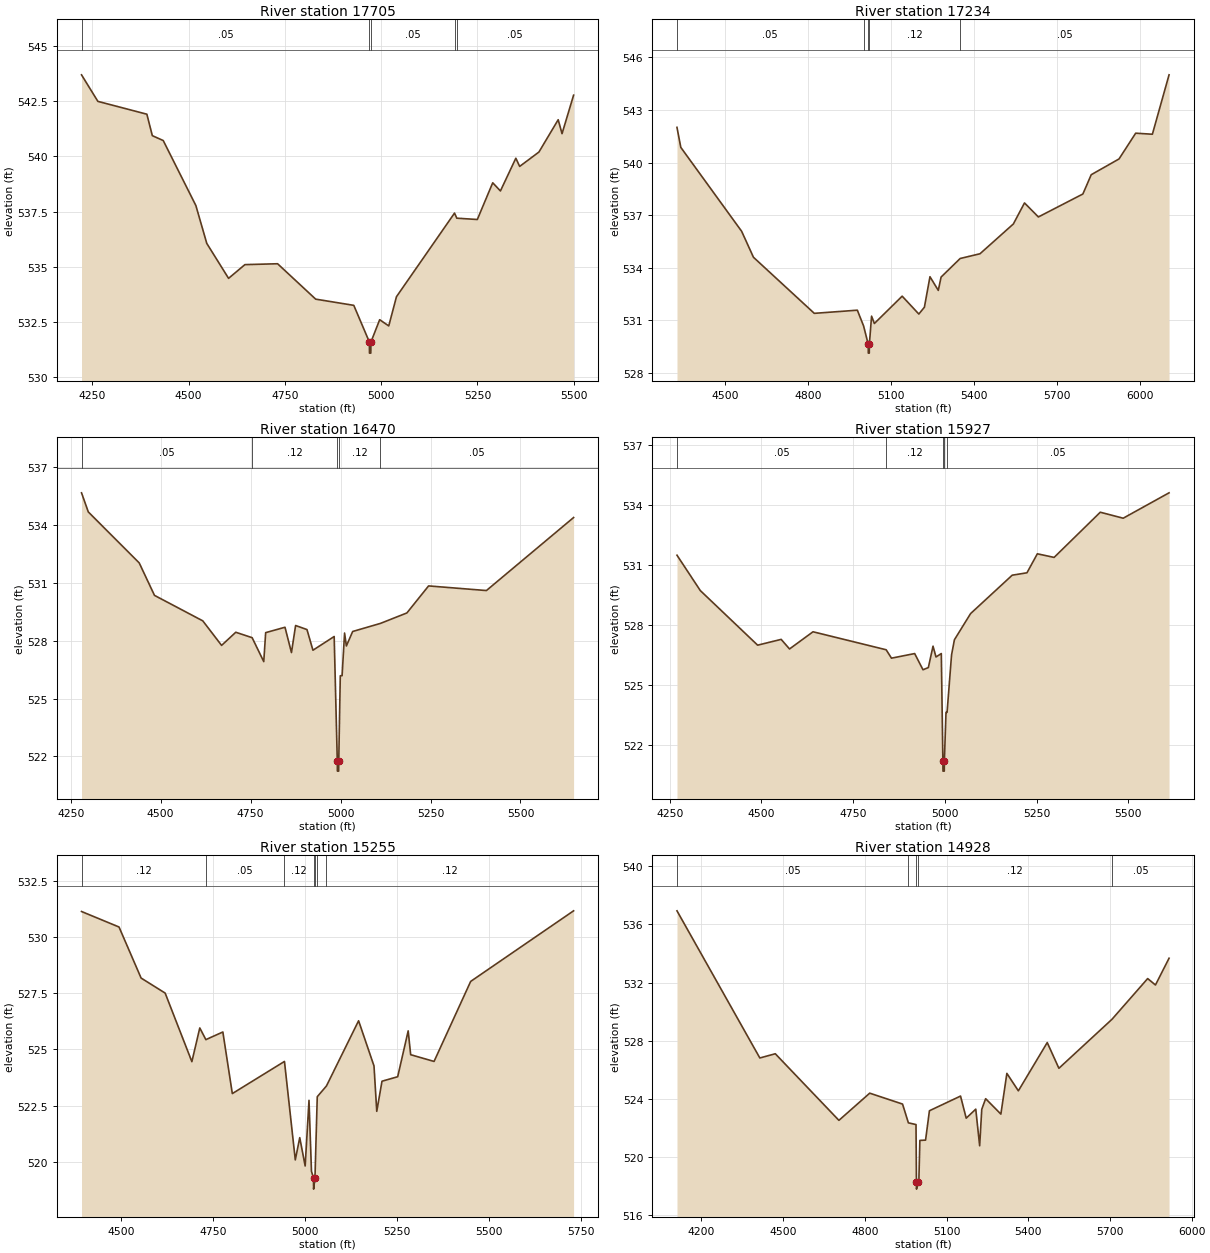
Type RM Length L Ch R = 1,17705,471,471,471
BEGIN DESCRIPTION:
Muddy T13 29.0
END DESCRIPTION:
XS GIS Cut Line= 3
      2693376.03      6970560.97      2692826.00      6971111.00
      2692826.00      6971611.04
#Sta/Elev= 30
  4221.7  543.68  4264.2  542.48  4391.4  541.90  4405.6  540.93  4433.9  540.71
  4518.7  537.77  4547.0  536.06  4603.6  534.48  4646.0  535.10  4730.9  535.14
  4829.8  533.54  4928.8  533.26  4969.3  531.60  4969.5  531.10  4973.0  531.10
  4973.3  531.60  4996.0  532.61  5019.6  532.33  5039.6  533.65  5190.4  537.43
  5196.3  537.20  5249.6  537.14  5289.6  538.80  5309.6  538.43  5349.6  539.91
  5359.6  539.54  5409.6  540.19  5459.6  541.65  5469.6  541.02  5499.6  542.76
#Mann=5,-1,0
  4221.7    0.05       0  4969.3    0.04       0  4973.3    0.05       0
  5190.4    0.12       0  5196.3    0.05       0
Bank Sta=4969.3,4973.3
Exp/Cntr=0.3,0.1

Type RM Length L Ch R = 1,17234,764,764,764
BEGIN DESCRIPTION:
Muddy T13 28.0
END DESCRIPTION:
XS GIS Cut Line= 3
      2692976.01      6970410.99      2692476.00      6970861.00
      2692576.00      6971960.96
#Sta/Elev= 30
  4327.3  542.01  4341.1  540.87  4560.9  536.08  4603.5  534.60  4823.2  531.40
  4978.7  531.58  5001.3  530.68  5018.1  529.63  5018.3  529.13  5021.8  529.13
  5022.1  529.63  5030.1  531.24  5040.2  530.82  5140.6  532.38  5200.8  531.36
  5220.9  531.75  5241.0  533.49  5271.1  532.71  5281.2  533.47  5350.1  534.53
  5421.7  534.80  5542.2  536.50  5582.4  537.70  5632.6  536.90  5793.3  538.21
  5823.4  539.31  5923.8  540.21  5984.0  541.68  6044.3  541.62  6104.5  545.01
#Mann=5,-1,0
  4327.3    0.05       0  5001.3    0.12       0  5018.1    0.03       0
  5022.1    0.12       0  5350.1    0.05       0
Bank Sta=5018.1,5022.1
Exp/Cntr=0.3,0.1

Type RM Length L Ch R = 1,16470,543,543,543
BEGIN DESCRIPTION:
Mapping XS 1d4d518b
END DESCRIPTION:
XS GIS Cut Line= 4
      2692304.06      6970112.41      2692050.59      6970356.10
      2691912.30      6970697.54      2691850.85      6971342.22
#Sta/Elev= 30
  4280.0  535.65  4298.9  534.66  4440.4  532.02  4482.8  530.34  4617.1  529.02
  4669.3  527.75  4708.7  528.43  4754.2  528.15  4786.5  526.91  4791.8  528.41
  4845.5  528.69  4863.5  527.38  4875.0  528.78  4906.6  528.57  4923.2  527.50
  4982.2  528.21  4990.9  521.74  4991.2  521.24  4994.7  521.24  4994.9  521.74
  4999.2  526.18  5004.2  526.18  5011.1  528.39  5016.1  527.72  5033.6  528.47
  5110.9  528.89  5184.3  529.43  5244.6  530.83  5405.3  530.59  5647.6  534.37
#Mann=5,-1,0
  4280.0    0.05       0  4754.2    0.12       0  4990.9    0.07       0
  4994.9    0.12       0  5110.9    0.05       0
Bank Sta=4990.9,4994.9
Exp/Cntr=0.3,0.1

Type RM Length L Ch R = 1,15927,672,672,672
BEGIN DESCRIPTION:
Mapping XS 1b712df7
END DESCRIPTION:
XS GIS Cut Line= 3
      2692120.72      6970116.80      2691534.75      6970563.87
      2691278.67      6971110.75
#Sta/Elev= 30
  4270.0  531.47  4333.6  529.70  4489.8  526.97  4553.9  527.26  4576.7  526.78
  4640.7  527.64  4840.0  526.74  4854.5  526.32  4917.7  526.55  4940.4  525.74
  4955.0  525.85  4967.7  526.92  4975.8  526.38  4990.3  526.55  4994.6  521.17
  4994.9  520.67  4998.4  520.67  4998.6  521.17  5003.1  523.61  5006.0  523.61
  5018.2  526.48  5026.0  527.24  5070.1  528.55  5183.5  530.47  5223.7  530.59
  5252.0  531.54  5297.7  531.36  5423.5  533.62  5485.9  533.32  5610.9  534.59
#Mann=5,-1,0
  4270.0    0.05       0  4840.0    0.12       0  4994.6    0.07       0
  4998.6    0.12       0  5006.0    0.05       0
Bank Sta=4994.6,4998.6
Exp/Cntr=0.3,0.1

Type RM Length L Ch R = 1,15255,327,327,327
BEGIN DESCRIPTION:
Mapping XS bc307dca
END DESCRIPTION:
XS GIS Cut Line= 3
      2692003.54      6969839.03      2691421.90      6970012.66
      2690935.76      6970555.22
#Sta/Elev= 30
  4393.6  531.13  4495.4  530.44  4555.3  528.17  4620.6  527.50  4693.1  524.45
  4714.6  525.95  4731.1  525.43  4777.2  525.77  4802.9  523.03  4944.4  524.46
  4973.8  520.08  4985.9  521.07  5000.6  519.81  5011.0  522.73  5017.7  519.57
  5023.2  519.28  5023.5  518.78  5027.2  519.28  5033.4  522.89  5058.4  523.37
  5145.6  526.27  5187.4  524.26  5194.9  522.24  5209.1  523.58  5251.7  523.78
  5280.2  525.82  5286.9  524.76  5350.4  524.46  5449.8  528.02  5729.1  531.16
#Mann=7,-1,0
  4393.6    0.12       0  4731.1    0.05       0  4944.4    0.12       0
  5023.2    0.07       0  5027.2    0.12       0  5033.4    0.05       0
  5058.4    0.12       0
Bank Sta=5023.2,5027.2
Exp/Cntr=0.3,0.1

Type RM Length L Ch R = 1,14928,738,738,738
BEGIN DESCRIPTION:
Muddy T13 23.0
END DESCRIPTION:
XS GIS Cut Line= 3
      2691775.98      6969161.02      2691176.00      6969811.00
      2690576.01      6970510.98
#Sta/Elev= 30
  4110.5  536.93  4414.7  526.81  4471.4  527.10  4705.0  522.52  4818.1  524.39
  4938.6  523.64  4960.0  522.35  4988.0  522.23  4989.6  518.29  4989.9  517.79
  4993.8  518.29  4998.4  518.29  5002.2  521.14  5023.1  521.16  5037.3  523.18
  5151.5  524.19  5172.3  522.67  5207.4  523.29  5221.7  520.77  5229.4  523.28
  5243.7  524.01  5299.6  522.95  5321.6  525.75  5363.8  524.55  5469.8  527.87
  5512.6  526.10  5707.5  529.47  5838.5  532.27  5867.1  531.83  5917.0  533.67
#Mann=5,-1,0
  4110.5    0.05       0  4960.0    0.12       0  4989.6    0.07       0
  4993.8    0.12       0  5707.5    0.05       0
Bank Sta=4989.6,4993.8
Exp/Cntr=0.3,0.1

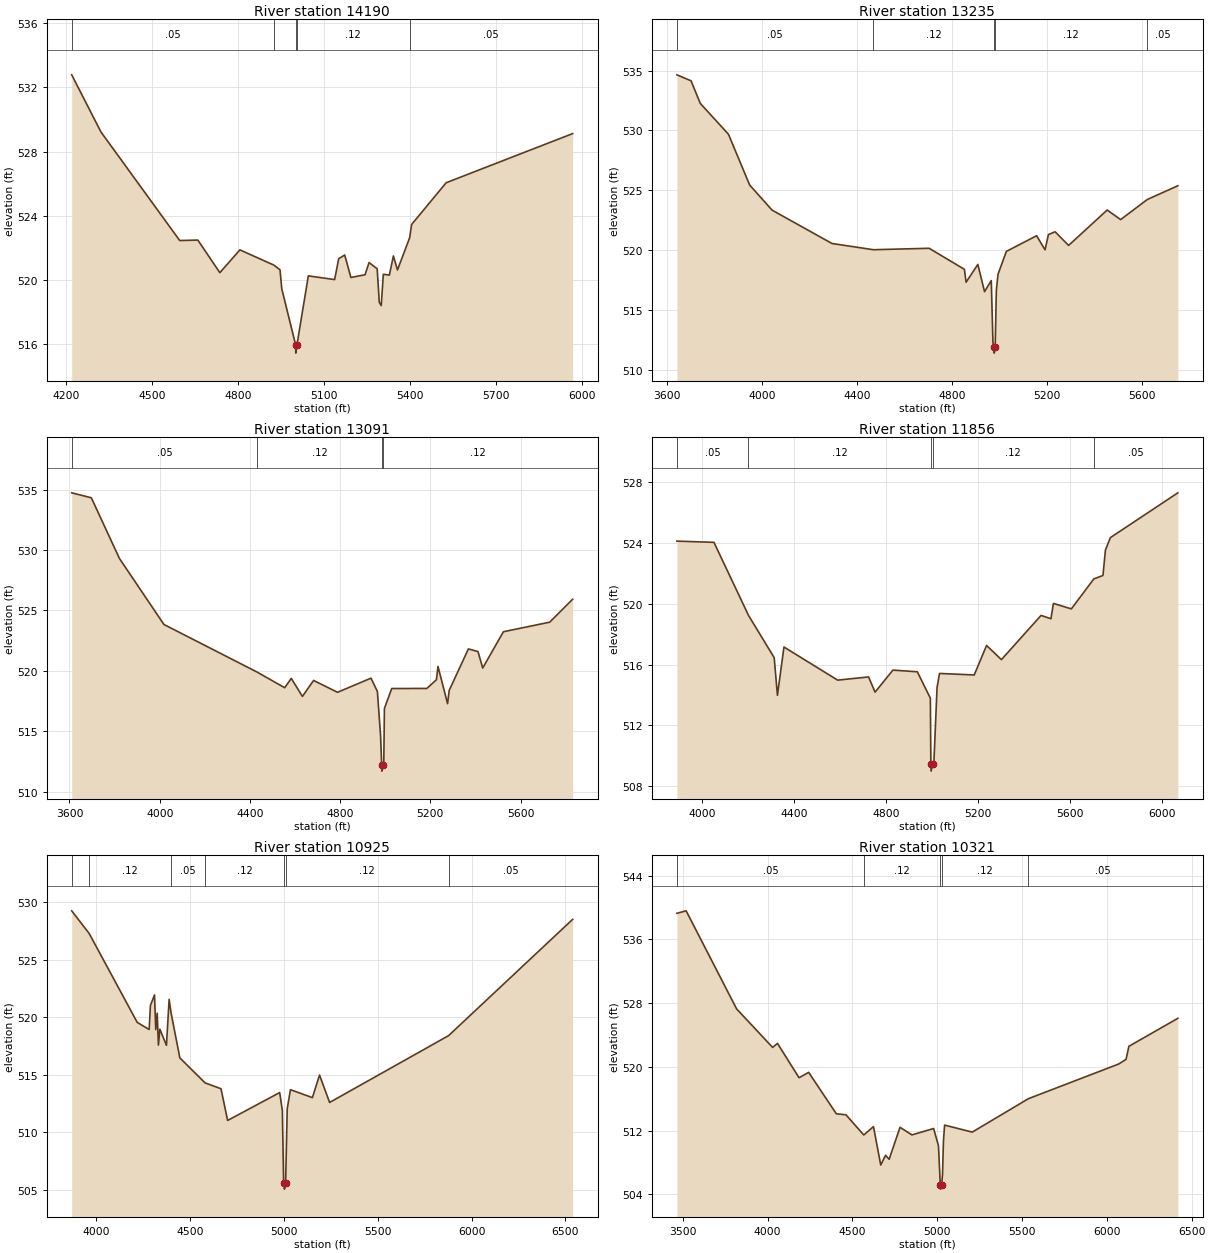
Type RM Length L Ch R = 1,14190,955,955,955
BEGIN DESCRIPTION:
Mapping XS 9f7cd0f3
END DESCRIPTION:
XS GIS Cut Line= 3
      2691621.55      6969121.17      2690836.83      6969235.75
      2690180.80      6969929.97
#Sta/Elev= 30
  4219.3  532.78  4321.4  529.22  4596.3  522.46  4659.5  522.49  4736.3  520.46
  4806.2  521.88  4925.0  520.93  4946.2  520.64  4952.5  519.45  5000.9  515.95
  5001.3  515.45  5005.3  515.95  5045.1  520.26  5136.9  520.03  5151.1  521.33
  5172.1  521.56  5193.6  520.16  5242.9  520.33  5257.1  521.09  5285.4  520.70
  5292.7  518.61  5299.5  518.41  5306.8  520.36  5327.9  520.31  5342.0  521.50
  5356.2  520.63  5398.6  522.63  5405.5  523.46  5526.1  526.06  5967.5  529.12
#Mann=5,-1,0
  4219.3    0.05       0  4925.0    0.12       0  5000.9    0.07       0
  5005.3    0.12       0  5398.6    0.05       0
Bank Sta=5000.9,5005.3
Exp/Cntr=0.3,0.1

Type RM Length L Ch R = 1,13235,144,144,144
BEGIN DESCRIPTION:
Mapping XS feae70b6
END DESCRIPTION:
XS GIS Cut Line= 4
      2691409.32      6968247.78      2690541.23      6968539.45
      2690221.79      6968855.42      2689683.61      6969369.30
#Sta/Elev= 30
  3642.4  534.65  3701.8  534.15  3740.8  532.26  3859.4  529.68  3948.7  525.43
  4043.2  523.33  4295.4  520.54  4469.8  520.02  4704.4  520.14  4852.9  518.38
  4860.0  517.30  4909.5  518.79  4937.7  516.51  4966.0  517.44  4973.1  512.25
  4977.8  511.87  4978.3  511.37  4982.5  511.87  4987.3  516.60  4994.3  517.96
  5029.5  519.88  5156.9  521.19  5192.4  520.01  5206.6  521.29  5234.9  521.52
  5291.5  520.38  5454.1  523.34  5510.7  522.54  5622.9  524.22  5751.6  525.37
#Mann=5,-1,0
  3642.4    0.05       0  4469.8    0.12       0  4977.8    0.07       0
  4982.5    0.12       0  5622.9    0.05       0
Bank Sta=4977.8,4982.5
Exp/Cntr=0.3,0.1

Type RM Length L Ch R = 1,13091,1235,1235,1235
BEGIN DESCRIPTION:
Mapping XS a39dba9a
END DESCRIPTION:
XS GIS Cut Line= 4
      2691419.73      6968160.97      2690503.04      6968417.92
      2690187.07      6968720.01      2689580.18      6969288.75
#Sta/Elev= 30
  3609.9  534.73  3696.9  534.32  3821.5  529.30  4018.8  523.84  4432.1  519.90
  4554.2  518.61  4583.3  519.38  4632.7  517.89  4682.3  519.21  4788.4  518.23
  4936.8  519.40  4965.1  518.30  4979.3  514.63  4984.2  512.21  4984.7  511.71
  4988.9  512.21  4993.4  512.28  4996.3  516.89  5028.6  518.54  5184.4  518.55
  5226.9  519.27  5233.8  520.37  5276.3  517.29  5283.6  518.39  5368.6  521.82
  5411.1  521.60  5432.1  520.24  5523.9  523.24  5729.1  524.03  5830.8  525.93
#Mann=4,-1,0
  3609.9    0.05       0  4432.1    0.12       0  4984.2    0.07       0
  4988.9    0.12       0
Bank Sta=4984.2,4988.9
Exp/Cntr=0.3,0.1

Type RM Length L Ch R = 1,11856,931,931,931
BEGIN DESCRIPTION:
Mapping XS d4c0b542
END DESCRIPTION:
XS GIS Cut Line= 3
      2690131.51      6967398.71      2689313.80      6968153.92
      2688917.97      6969143.49
#Sta/Elev= 30
  3890.3  524.13  4051.4  524.05  4201.4  519.25  4313.4  516.46  4327.5  513.98
  4355.9  517.16  4589.5  514.98  4723.9  515.19  4752.2  514.19  4829.9  515.64
  4936.0  515.53  4992.7  513.79  4994.8  509.49  4996.0  508.99  5002.2  509.49
  5008.3  509.64  5021.8  514.49  5032.5  515.42  5183.4  515.32  5237.2  517.26
  5301.8  516.33  5474.2  519.24  5517.2  519.02  5528.0  520.03  5606.0  519.67
  5703.5  521.64  5743.4  521.87  5754.2  523.54  5775.7  524.36  6069.2  527.31
#Mann=5,-1,0
  3890.3    0.05       0  4201.4    0.12       0  4994.8    0.07       0
  5002.2    0.12       0  5703.5    0.05       0
Bank Sta=4994.8,5002.2
Exp/Cntr=0.3,0.1

Type RM Length L Ch R = 1,10925,604,604,604
BEGIN DESCRIPTION:
Mapping XS f0ea8b0f
END DESCRIPTION:
XS GIS Cut Line= 3
      2689732.21      6966775.43      2688975.26      6967643.50
      2688454.65      6969066.51
#Sta/Elev= 30
  3871.5  529.23  3964.3  527.27  4220.3  519.55  4283.9  518.93  4290.5  521.01
  4312.3  521.93  4319.0  518.92  4326.6  520.34  4333.2  517.58  4340.8  518.96
  4375.9  517.56  4390.2  521.55  4400.6  520.36  4447.2  516.47  4581.5  514.30
  4666.4  513.79  4701.6  511.04  4978.8  513.46  4993.0  511.91  4999.7  505.66
  5002.9  505.58  5004.1  505.08  5010.4  505.58  5018.9  512.05  5036.1  513.71
  5152.9  513.02  5191.0  514.98  5244.5  512.60  5878.1  518.40  6538.5  528.49
#Mann=7,-1,0
  3871.5    0.05       0  3964.3    0.12       0  4400.6    0.05       0
  4581.5    0.12       0  5002.9    0.07       0  5010.4    0.12       0
  5878.1    0.05       0
Bank Sta=5002.9,5010.4
Exp/Cntr=0.3,0.1

Type RM Length L Ch R = 1,10321,1287,1287,1287
BEGIN DESCRIPTION:
Mapping XS 6b463c87
END DESCRIPTION:
XS GIS Cut Line= 3
      2689496.08      6966414.35      2688468.32      6967574.06
      2687968.42      6968886.27
#Sta/Elev= 30
  3465.0  539.26  3519.3  539.57  3817.0  527.27  4029.5  522.44  4057.9  522.95
  4185.0  518.64  4241.9  519.31  4405.0  514.12  4461.9  513.99  4566.8  511.46
  4624.1  512.51  4666.8  507.69  4695.2  508.92  4716.5  508.41  4780.5  512.42
  4850.8  511.47  4978.7  512.27  5007.2  510.12  5018.2  505.17  5019.4  504.67
  5025.9  505.17  5031.3  506.56  5036.6  510.67  5043.4  512.70  5206.5  511.82
  5537.5  516.01  6069.9  520.36  6113.5  520.95  6130.1  522.58  6418.8  526.09
#Mann=5,-1,0
  3465.0    0.05       0  4566.8    0.12       0  5018.2    0.07       0
  5025.9    0.12       0  5537.5    0.05       0
Bank Sta=5018.2,5025.9
Exp/Cntr=0.3,0.1

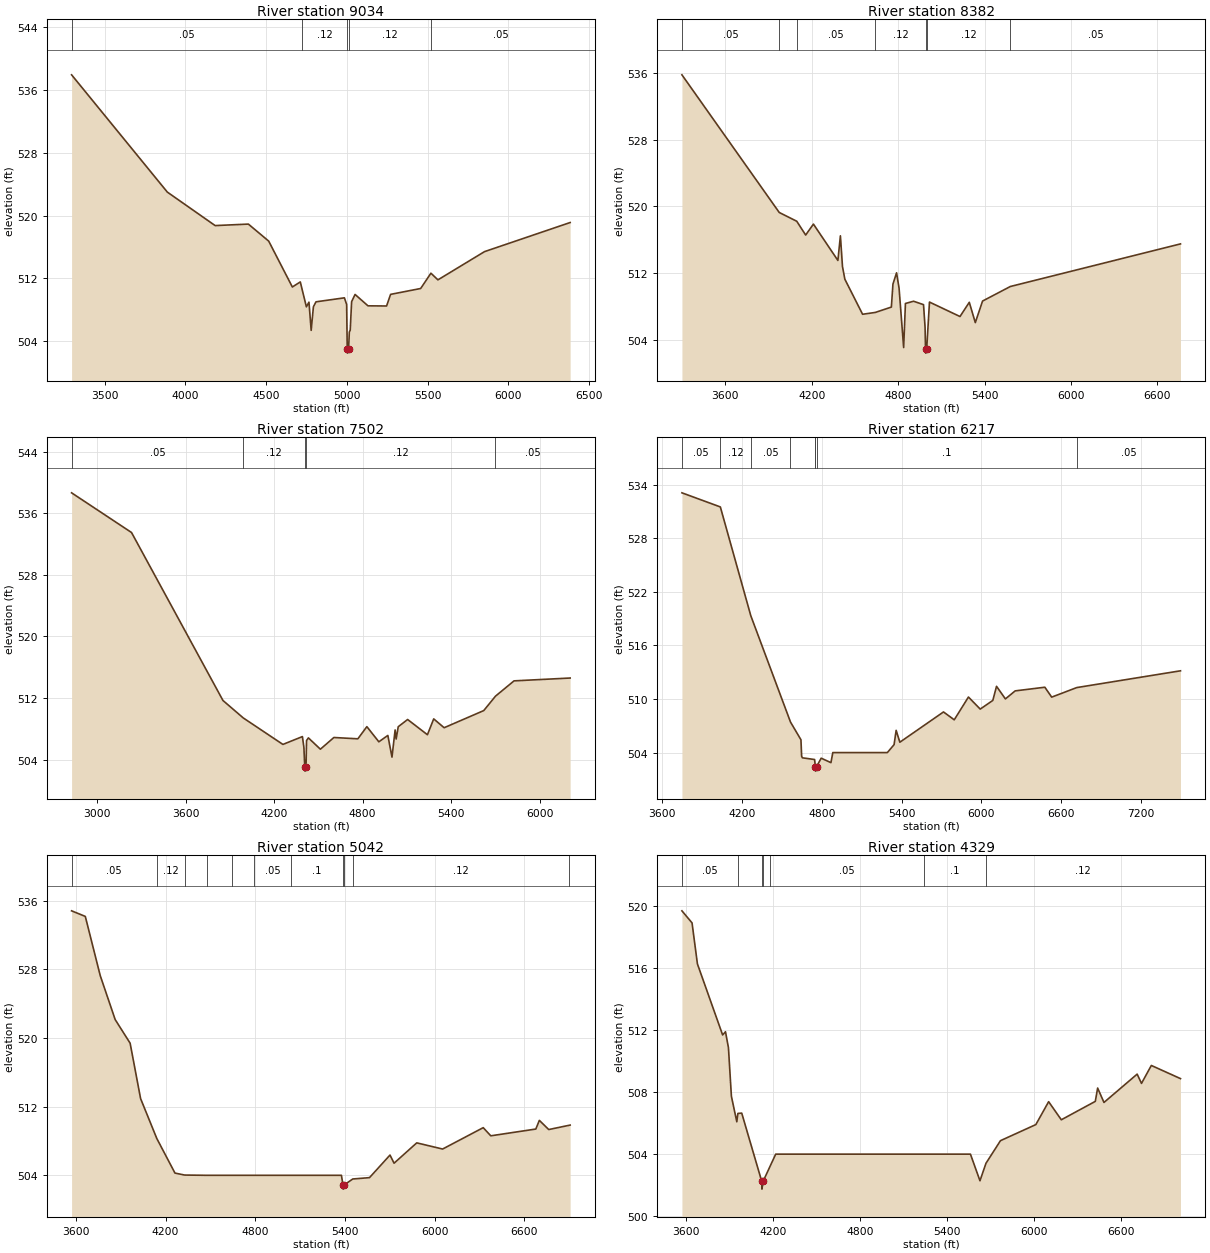
Type RM Length L Ch R = 1,9034,652,652,652
BEGIN DESCRIPTION:
Mapping XS 657ade46
END DESCRIPTION:
XS GIS Cut Line= 3
      2689343.30      6966060.18      2687843.32      6966893.50
      2687357.64      6968177.07
#Sta/Elev= 30
  3294.6  537.96  3887.6  523.01  4183.8  518.74  4389.7  518.93  4515.6  516.76
  4662.1  510.91  4711.3  511.56  4724.8  510.42  4749.0  508.38  4765.0  508.98
  4778.7  505.38  4792.5  508.39  4808.5  509.02  4984.6  509.53  4998.4  508.68
  5002.1  502.98  5003.3  502.48  5010.2  502.98  5015.1  505.18  5020.5  505.40
  5029.2  509.04  5050.6  509.96  5130.5  508.51  5245.8  508.49  5270.6  509.97
  5456.9  510.72  5520.5  512.67  5563.8  511.82  5852.5  515.42  6382.9  519.13
#Mann=5,-1,0
  3294.6    0.05       0  4724.8    0.12       0  5002.1    0.07       0
  5010.2    0.12       0  5520.5    0.05       0
Bank Sta=5002.1,5010.2
Exp/Cntr=0.3,0.1

Type RM Length L Ch R = 1,8382,880,880,880
BEGIN DESCRIPTION:
Mapping XS 7e49ec54
END DESCRIPTION:
XS GIS Cut Line= 3
      2689185.89      6965895.98      2687563.35      6966474.58
      2686422.48      6967786.48
#Sta/Elev= 30
  3298.7  535.74  3974.3  519.27  4095.9  518.22  4157.7  516.57  4211.6  517.88
  4381.5  513.53  4398.9  516.48  4413.3  512.81  4429.7  511.29  4552.9  507.09
  4641.6  507.31  4752.7  507.95  4763.7  510.70  4788.8  512.05  4806.2  510.21
  4838.0  503.11  4850.4  508.38  4906.7  508.65  4976.0  508.24  4986.7  505.53
  4989.8  502.94  4991.0  502.44  4997.9  502.94  5017.3  508.55  5229.1  506.82
  5293.7  508.52  5335.5  506.09  5385.8  508.67  5578.4  510.41  6759.9  515.51
#Mann=7,-1,0
  3298.7    0.05       0  3974.3    0.12       0  4095.9    0.05       0
  4641.6    0.12       0  4989.8    0.07       0  4997.9    0.12       0
  5578.4    0.05       0
Bank Sta=4989.8,4997.9
Exp/Cntr=0.3,0.1

Type RM Length L Ch R = 1,7502,1285,1285,1285
BEGIN DESCRIPTION:
Mapping XS 7b028a11
END DESCRIPTION:
XS GIS Cut Line= 3
      2689275.94      6965582.92      2687157.90      6965964.86
      2686281.15      6966824.25
#Sta/Elev= 30
  2827.5  538.67  3233.9  533.51  3853.7  511.68  3991.5  509.41  4260.2  505.97
  4392.3  506.99  4402.4  505.58  4408.4  503.00  4409.7  502.50  4416.8  503.00
  4420.2  506.47  4432.9  506.82  4514.2  505.35  4605.7  506.87  4768.2  506.70
  4829.2  508.28  4910.5  506.31  4971.5  507.14  4999.5  504.32  5020.8  507.85
  5027.8  506.67  5041.9  508.27  5105.6  509.21  5239.9  507.23  5282.4  509.29
  5353.1  508.14  5621.8  510.37  5701.1  512.24  5826.9  514.23  6207.4  514.60
#Mann=5,-1,0
  2827.5    0.05       0  3991.5    0.12       0  4408.4    0.07       0
  4416.8    0.12       0  5701.1    0.05       0
Bank Sta=4408.4,4416.8
Exp/Cntr=0.3,0.1

Type RM Length L Ch R = 1,6217,1175,1175,1175
BEGIN DESCRIPTION:
Mapping XS 5ae352e6
END DESCRIPTION:
XS GIS Cut Line= 4
      2688729.11      6964523.88      2687548.52      6964853.75
      2686203.04      6965678.40      2685890.78      6966571.80
#Sta/Elev= 30
  3747.8  533.10  4036.8  531.52  4265.7  519.34  4564.5  507.42  4643.2  505.43
  4648.3  503.58  4654.3  503.41  4745.8  503.22  4751.6  502.42  4752.8  501.92
  4760.5  502.42  4795.3  503.37  4868.8  502.87  4882.8  504.00  5293.2  504.00
  5343.8  504.89  5359.2  506.49  5387.1  505.16  5715.5  508.55  5796.2  507.67
  5903.1  510.22  5991.6  508.87  6086.4  509.84  6114.3  511.42  6181.1  510.01
  6254.6  510.91  6477.8  511.32  6529.3  510.21  6717.7  511.28  7498.1  513.16
#Mann=8,-1,0
  3747.8    0.05       0  4036.8    0.12       0  4265.7    0.05       0
  4564.5    0.12       0  4745.8     0.1       0  4751.6    0.07       0
  4760.5     0.1       0  6717.7    0.05       0
Bank Sta=4751.6,4760.5
Exp/Cntr=0.3,0.1

Type RM Length L Ch R = 1,5042,713,713,713
BEGIN DESCRIPTION:
Mapping XS 2193bf61
END DESCRIPTION:
XS GIS Cut Line= 3
      2688367.65      6963910.46      2686923.18      6963924.35
      2685846.79      6965479.91
#Sta/Elev= 30
  3571.3  534.81  3663.0  534.16  3763.0  527.26  3863.0  522.14  3963.0  519.39
  4033.0  512.94  4141.2  508.30  4263.0  504.26  4327.5  504.03  4474.7  504.00
  4644.9  504.00  4792.1  504.00  5041.3  504.00  5376.9  504.00  5387.2  502.89
  5388.5  502.39  5396.4  502.89  5452.8  503.57  5564.8  503.73  5702.0  506.36
  5729.2  505.41  5881.0  507.78  6054.0  507.06  6325.7  509.55  6376.4  508.60
  6677.8  509.39  6701.4  510.40  6764.2  509.33  6898.8  509.82  6907.5  509.85
#Mann=11,-1,0
  3571.3    0.05       0  4141.2    0.12       0  4327.5     0.1       0
  4474.7    0.05       0  4644.9     0.1       0  4792.1    0.05       0
  5041.3     0.1       0  5387.2    0.03       0  5396.4     0.1       0
  5452.8    0.12       0  6898.8    0.05       0
Bank Sta=5387.2,5396.4
Exp/Cntr=0.3,0.1

Type RM Length L Ch R = 1,4329,825,825,825
BEGIN DESCRIPTION:
Mapping XS 41660bdc
END DESCRIPTION:
XS GIS Cut Line= 3
      2687890.88      6963092.85      2686508.90      6963363.69
      2685537.31      6965147.25
#Sta/Elev= 30
  3569.2  519.72  3639.0  518.94  3676.1  516.29  3850.0  511.70  3869.7  511.91
  3890.1  510.88  3910.5  507.74  3947.8  506.09  3955.2  506.63  3981.8  506.65
  4119.8  502.24  4121.1  501.74  4129.1  502.24  4173.5  503.14  4216.2  504.00
  5241.2  504.00  5559.6  504.00  5625.2  502.28  5666.7  503.41  5766.6  504.87
  6010.7  505.91  6099.0  507.39  6186.4  506.22  6420.9  507.41  6437.0  508.27
  6480.7  507.34  6709.6  509.17  6739.5  508.57  6807.4  509.73  7008.5  508.88
#Mann=7,-1,0
  3569.2    0.05       0  3955.2     0.1       0  4119.8    0.03       0
  4129.1     0.1       0  4173.5    0.05       0  5241.2     0.1       0
  5666.7    0.12       0
Bank Sta=4119.8,4129.1
Exp/Cntr=0.3,0.1

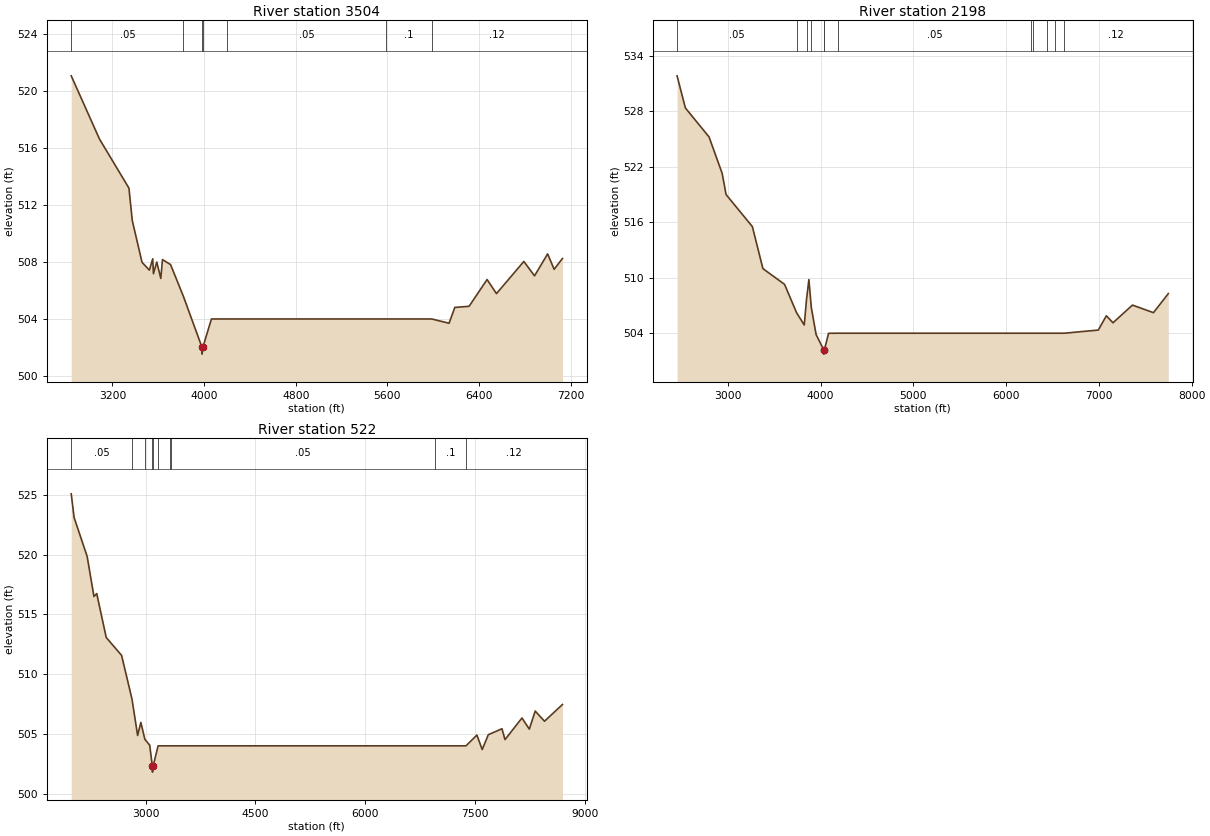
Type RM Length L Ch R = 1,3504,1306,1306,1306
BEGIN DESCRIPTION:
Mapping XS 7290c403
END DESCRIPTION:
XS GIS Cut Line= 3
      2687397.81      6960995.61      2686043.62      6962752.58
      2685481.12      6964745.64
#Sta/Elev= 30
  2839.8  521.08  3086.5  516.64  3343.8  513.19  3372.9  510.91  3458.0  507.98
  3522.3  507.43  3551.3  508.23  3557.6  507.18  3586.6  508.00  3622.0  506.85
  3636.5  508.17  3707.1  507.82  3819.7  505.58  3980.6  502.03  3981.9  501.53
  3989.9  502.03  4064.1  504.00  4197.2  504.00  5588.1  504.00  5987.3  504.00
  6138.8  503.70  6189.0  504.81  6313.7  504.89  6470.8  506.77  6552.7  505.78
  6791.7  508.04  6885.2  507.03  6999.5  508.57  7056.2  507.49  7129.0  508.25
#Mann=7,-1,0
  2839.8    0.05       0  3819.7     0.1       0  3980.6    0.03       0
  3989.9     0.1       0  4197.2    0.05       0  5588.1     0.1       0
  5987.3    0.12       0
Bank Sta=3980.6,3989.9
Exp/Cntr=0.3,0.1

Type RM Length L Ch R = 1,2198,1676,1676,1676
BEGIN DESCRIPTION:
Mapping XS 44c13c24
END DESCRIPTION:
XS GIS Cut Line= 4
      2687335.97      6959924.75      2685426.21      6961639.19
      2684981.34      6963397.00      2685241.38      6964274.64
#Sta/Elev= 30
  2453.4  531.81  2542.9  528.34  2797.8  525.21  2939.1  521.28  2981.7  518.98
  3265.0  515.52  3378.6  510.98  3611.9  509.28  3741.7  506.21  3824.1  504.89
  3848.5  507.64  3874.2  509.80  3900.4  506.77  3952.0  503.85  4032.4  502.24
  4033.8  501.74  4042.0  502.24  4086.5  503.99  4193.1  504.00  6266.5  504.00
  6287.1  504.00  6442.6  504.00  6526.7  504.00  6627.1  504.00  6993.7  504.34
  7080.3  505.88  7152.0  505.13  7361.9  507.04  7588.2  506.22  7748.4  508.28
#Mann=12,-1,0
  2453.4    0.05       0  3741.7    0.12       0  3848.5    0.05       0
  3900.4     0.1       0  4032.4    0.03       0  4042.0     0.1       0
  4193.1    0.05       0  6266.5     0.1       0  6287.1    0.05       0
  6442.6     0.1       0  6526.7    0.05       0  6627.1    0.12       0
Bank Sta=4032.4,4042
Exp/Cntr=0.3,0.1

Type RM Length L Ch R = 1,522,0,0,0
BEGIN DESCRIPTION:
Muddy T13 1.0
END DESCRIPTION:
XS GIS Cut Line= 3
      2686874.12      6959428.88      2684126.00      6960661.00
      2685120.24      6964227.62
#Sta/Elev= 30
  1982.6  525.09  2021.7  523.11  2200.4  519.85  2293.1  516.50  2331.2  516.74
  2460.8  513.07  2671.0  511.57  2813.6  507.90  2890.1  504.87  2934.2  505.96
  2989.0  504.55  3055.5  504.05  3091.4  502.30  3092.8  501.80  3101.4  502.30
  3170.3  504.00  3328.7  504.00  3347.3  504.00  6958.3  504.00  7378.2  504.00
  7527.3  504.90  7600.0  503.69  7683.0  504.93  7869.9  505.43  7911.4  504.52
  8143.1  506.33  8243.6  505.40  8324.4  506.91  8451.3  506.06  8696.9  507.46
#Mann=10,-1,0
  1982.6    0.05       0  2813.6    0.12       0  2989.0     0.1       0
  3091.4    0.03       0  3101.4     0.1       0  3170.3    0.05       0
  3328.7     0.1       0  3347.3    0.05       0  6958.3     0.1       0
  7378.2    0.12       0
Bank Sta=3091.4,3101.4
Exp/Cntr=0.3,0.1

Chan Stop Cuts=-1