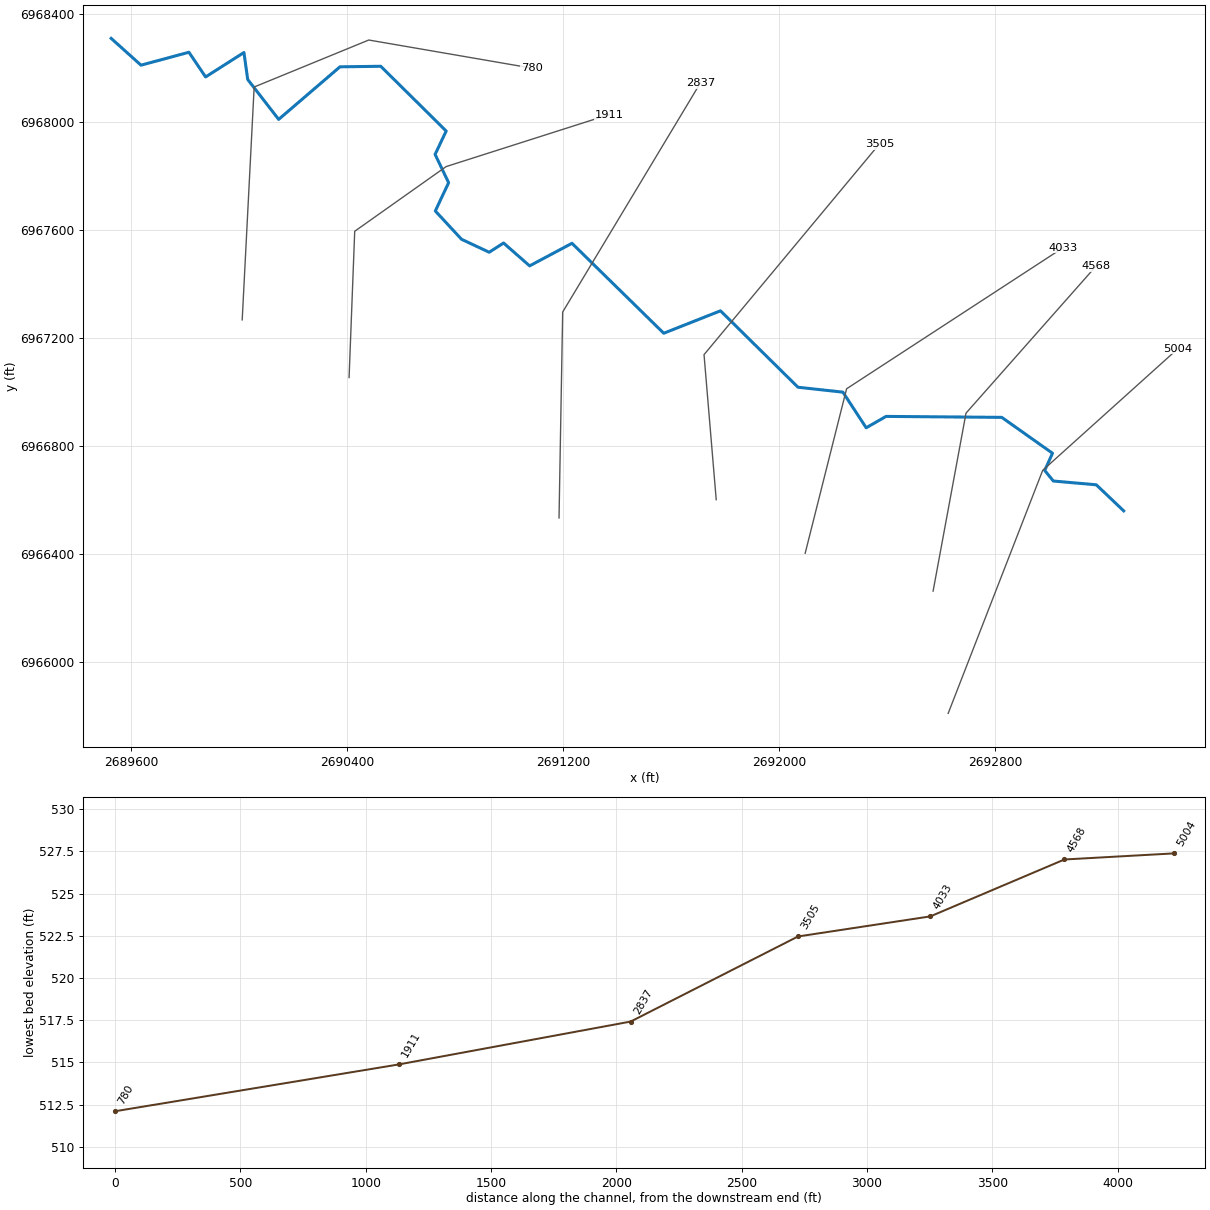
--- Muddy T13_1.prj (project) ---

Proj Title=Muddy T13_1 Base Level Engineering
Current Plan=p01
Default Exp/Contr=0.3,0.1
English Units
Geom File=g01
Flow File=f01
Plan File=p01
Y Axis Title=Elevation
X Axis Title(PF)=Main Channel Distance
X Axis Title(XS)=Station
BEGIN DESCRIPTION:
Muddy T13_1
END DESCRIPTION:
DSS Export Rating Curves= 0
DSS Export Rating Curve Sorted= 0
DSS Export Volume Flow Curves= 0
DXF OffsetX= 0
DXF OffsetY= 0
DXF ScaleX= 1
DXF ScaleY= 10

--- Muddy T13_1.p01 (plan) ---

Plan Title=Multiple Run
Short Identifier=Multiple
Geom File=g01
Flow File=f01
Subcritical Flow
K Sum by GR= 0
Std Step Tol= 0.01
Critical Tol= 0.01
Num of Std Step Trials= 20
Max Error Tol= 0.3
Flow Tol Ratio= 0.001
Split Flow NTrial= 30
Split Flow Tol= 0.02
Split Flow Ratio= 0.02
Log Output Level= 0
Friction Slope Method= 1
Unsteady Friction Slope Method= 2
Unsteady Bridges Friction Slope Method= 1
Parabolic Critical Depth
Global Vel Dist=  1 , 1 , 1
Global Log Level= 0
CheckData=True
Encroach Param= -1, 0, 0, 0
BEGIN DESCRIPTION:
Multiple Run
END DESCRIPTION:

--- Muddy T13_1.f01 (steady flow) ---

Flow Title=Multiple
Number of Profiles=7
Profile Names=10-year,25-year,50-year,1pct_min,100-year,1pct_plu,500-year
River Rch & RM= Muddy T13_1,Reach-1,5004
     654     881    1064     639    1275    2543    1825
River Rch & RM= Muddy T13_1,Reach-1,3505
     782    1062    1290     778    1552    3097    2243
Boundary for River Rch & Prof#=Muddy T13_1,Reach-1,1
Up Type=0
Dn Type=3
Dn Slope=0.005
Boundary for River Rch & Prof#=Muddy T13_1,Reach-1,2
Up Type=0
Dn Type=3
Dn Slope=0.005
Boundary for River Rch & Prof#=Muddy T13_1,Reach-1,3
Up Type=0
Dn Type=3
Dn Slope=0.005
Boundary for River Rch & Prof#=Muddy T13_1,Reach-1,4
Up Type=0
Dn Type=3
Dn Slope=0.005
Boundary for River Rch & Prof#=Muddy T13_1,Reach-1,5
Up Type=0
Dn Type=3
Dn Slope=0.005
Boundary for River Rch & Prof#=Muddy T13_1,Reach-1,6
Up Type=0
Dn Type=3
Dn Slope=0.005
Boundary for River Rch & Prof#=Muddy T13_1,Reach-1,7
Up Type=0
Dn Type=3
Dn Slope=0.005

--- Muddy T13_1.g01 (geometry) ---

Geom Title=Existing Conditions
Program Version=4.10

River Reach=Muddy T13_1     ,Reach-1
Reach XY= 30
        2693276.        6966561.      2693174.55      6966657.51
      2693015.49      6966671.48      2692983.46      6966710.76
      2693012.36      6966774.36      2692824.45      6966907.25
      2692395.98      6966910.81      2692322.33      6966868.69
      2692236.12      6967000.65      2692069.81      6967018.82
      2691782.74      6967301.87      2691572.58      6967218.79
      2691232.73      6967551.89      2691075.91      6967468.31
      2690979.34      6967552.98      2690926.09      6967518.77
       2690823.7       6967566.8       2690726.6      6967671.62
      2690775.89      6967776.39      2690725.81       6967881.2
      2690766.85      6967967.73      2690524.53      6968207.47
      2690373.55      6968205.55      2690146.43      6968010.82
      2690031.78      6968158.71      2690017.83      6968258.54
       2689875.8      6968168.03      2689814.13      6968259.45
      2689636.62      6968211.55        2689526.        6968311.

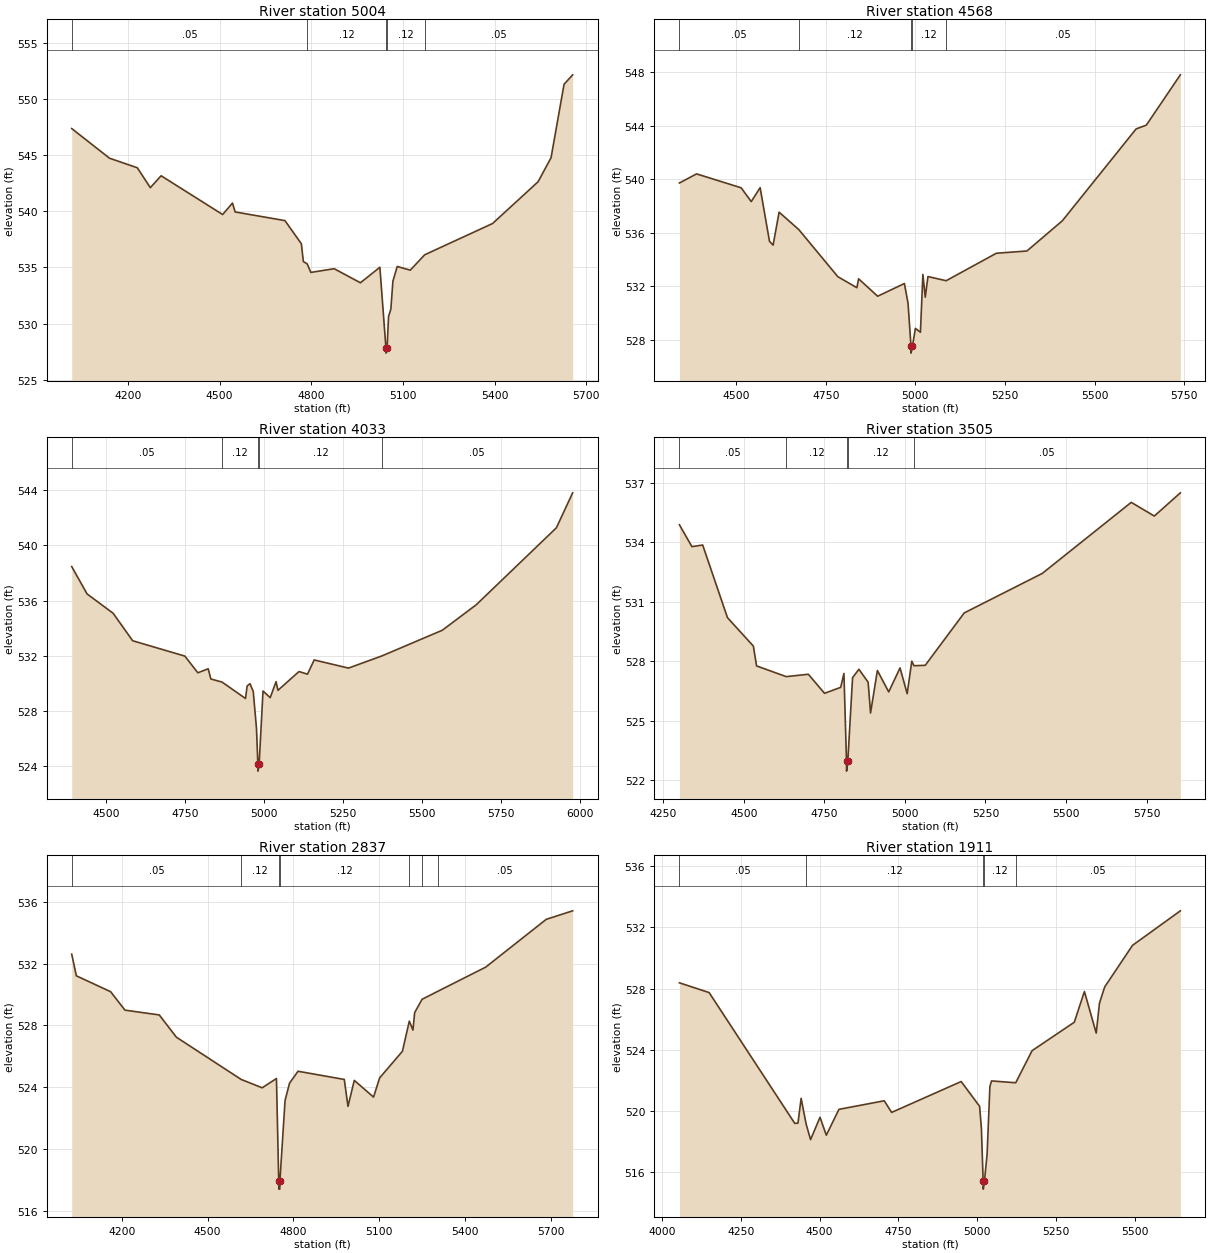
Type RM Length L Ch R = 1 ,5004    ,436,436,436
BEGIN DESCRIPTION:
Muddy T13_1 7.0
END DESCRIPTION:
XS GIS Cut Line= 3
      2692625.99      6965810.97        2692976.        6966711.
      2693476.02      6967161.02
#Sta/Elev= 30
  4016.6  547.36  4140.4  544.72  4231.2  543.87  4273.8   542.1    4309  543.16
  4510.2  539.71  4542.4  540.73  4551.2  539.94    4714  539.17  4767.7  537.11
  4774.2  535.53  4786.8  535.32  4798.7  534.56    4875  534.89  4960.8  533.64
  5024.5  535.02  5044.2  527.88  5044.4  527.38  5048.2  527.88  5052.9  530.65
  5060.4  531.29  5067.1  533.78  5081.3  535.09  5123.9  534.76  5171.1  536.13
    5393  538.91  5541.7  542.62  5584.3  544.76  5626.9   551.3    5655  552.14
#Mann= 5 ,-1 , 0
  4016.6     .05       0  4786.8     .12       0  5044.2     .07       0
  5048.2     .12       0  5171.1     .05       0
Bank Sta=5044.2,5048.2
XS Rating Curve= 0 ,0
Exp/Cntr=0.3,0.1

Type RM Length L Ch R = 1 ,4568    ,535,535,535
BEGIN DESCRIPTION:
Mapping XS 8157bd66
END DESCRIPTION:
XS GIS Cut Line= 3
      2692570.19      6966264.01      2692692.03      6966922.84
      2693173.63      6967467.45
#Sta/Elev= 30
    4342  539.73  4389.8  540.41  4514.2  539.37  4542.3  538.34  4567.1  539.38
  4593.2  535.37  4603.3  535.09    4620  537.55  4674.9  536.25  4783.8  532.73
  4836.8  531.91  4841.8  532.57  4894.8  531.27  4969.4  532.22  4979.6  530.74
  4987.8  527.52    4988  527.02  4991.8  527.52    5000  528.87  5014.1  528.58
  5020.9   532.9  5027.6   531.2  5035.1  532.74  5085.9  532.43  5225.8  534.48
  5311.1  534.65    5410  536.91  5615.6  543.77    5644  544.05    5739  547.81
#Mann= 5 ,-1 , 0
    4342     .05       0  4674.9     .12       0  4987.8     .07       0
  4991.8     .12       0  5085.9     .05       0
Bank Sta=4987.8,4991.8
XS Rating Curve= 0 ,0
Exp/Cntr=0.3,0.1

Type RM Length L Ch R = 1 ,4033    ,528,528,528
BEGIN DESCRIPTION:
Mapping XS b9a57409
END DESCRIPTION:
XS GIS Cut Line= 3
      2692096.35       6966403.9      2692249.78       6967013.1
      2693051.62      6967535.64
#Sta/Elev= 30
  4392.3  538.46  4440.9  536.48  4523.4  535.08  4585.2  533.09  4750.2  531.98
  4791.5  530.77  4824.2  531.06  4832.7  530.32  4867.9   530.1  4942.3  528.91
  4947.5  529.82  4956.5  529.98  4966.8  529.42  4977.1  526.73  4981.4  524.15
  4981.7  523.65  4985.4  524.15  4997.7  529.45  5020.5  528.97    5039  530.13
    5045   529.5  5111.5  530.86  5138.5  530.67  5159.6   531.7  5268.3  531.11
  5373.8  531.99  5565.1  533.85  5672.7   535.7  5926.2  541.27  5977.6   543.8
#Mann= 5 ,-1 , 0
  4392.3     .05       0  4867.9     .12       0  4981.4     .07       0
  4985.4     .12       0  5373.8     .05       0
Bank Sta=4981.4,4985.4
XS Rating Curve= 0 ,0
Exp/Cntr=0.3,0.1

Type RM Length L Ch R = 1 ,3505    ,668,668,668
BEGIN DESCRIPTION:
Mapping XS 372b2247
END DESCRIPTION:
XS GIS Cut Line= 3
      2691766.92      6966602.43      2691721.79      6967139.45
      2692371.32      6967919.79
#Sta/Elev= 30
  4300.4  534.87  4339.1  533.77  4372.6  533.85  4449.5  530.19  4529.8  528.76
  4539.8  527.76  4631.8  527.22  4700.4  527.34  4750.6  526.38  4800.7  526.68
  4810.8  527.38  4818.8  522.96    4819  522.46  4822.8  522.96  4837.6  527.17
  4857.3  527.59  4885.9  526.94  4893.4  525.39  4914.6  527.53  4949.7  526.45
  4984.9  527.66    5007  526.36  5021.3     528  5027.9  527.77    5063  527.79
    5184  530.43  5426.2  532.42  5702.2     536  5773.8  535.31  5854.6  536.48
#Mann= 5 ,-1 , 0
  4300.4     .05       0  4631.8     .12       0  4818.8     .07       0
  4822.8     .12       0  5027.9     .05       0
Bank Sta=4818.8,4822.8
XS Rating Curve= 0 ,0
Exp/Cntr=0.3,0.1

Type RM Length L Ch R = 1 ,2837    ,926,926,926
BEGIN DESCRIPTION:
Mapping XS 6059246a
END DESCRIPTION:
XS GIS Cut Line= 3
      2691184.77      6966534.77      2691198.31       6967297.4
      2691708.25      6968145.79
#Sta/Elev= 30
  4024.9  532.61  4041.1  531.21  4161.2  530.18  4211.2  528.99  4331.2  528.68
  4391.2  527.24  4617.8  524.51  4691.2  523.97  4741.2  524.57  4749.2  517.92
  4749.5  517.42    4753  517.42  4753.2  517.92  4771.3  523.15    4787  524.27
  4816.7  525.04  4978.5  524.51  4991.5  522.77  5013.5  524.45  5080.9  523.37
  5102.2  524.61  5181.9  526.33    5206  528.28  5218.8   527.7  5224.7  528.83
  5250.6  529.69  5304.9   530.2  5473.3  531.77  5685.1  534.86  5777.5  535.41
#Mann= 7 ,-1 , 0
  4024.9     .05       0  4617.8     .12       0  4749.2     .07       0
  4753.2     .12       0    5206     .05       0  5250.6     .12       0
  5304.9     .05       0
Bank Sta=4749.2,4753.2
XS Rating Curve= 0 ,0
Exp/Cntr=0.3,0.1

Type RM Length L Ch R = 1 ,1911    ,1131,1131,1131
BEGIN DESCRIPTION:
Mapping XS 64bdb1e0
END DESCRIPTION:
XS GIS Cut Line= 4
      2690407.25      6967054.82      2690428.08      6967596.45
      2690766.62      6967836.03      2691370.77      6968028.73
#Sta/Elev= 30
  4054.6  528.38    4149  527.74    4421  519.18  4431.1   519.2  4441.1  520.82
  4457.1  519.13  4471.1  518.12  4501.1  519.58  4521.1  518.41  4561.2   520.1
  4705.1  520.66  4728.5   519.9  4949.4  521.92  5007.9   520.3  5013.7  518.83
  5019.2  515.38  5019.5  514.88  5023.2  515.38  5031.7  517.16  5040.6  521.59
  5045.8  521.96  5122.6  521.84  5174.6  523.94  5308.6   525.8  5340.8  527.81
  5378.3  525.09  5388.6  527.05  5405.2  528.11  5493.5  530.83  5645.5  533.09
#Mann= 5 ,-1 , 0
  4054.6     .05       0  4457.1     .12       0  5019.2     .07       0
  5023.2     .12       0  5122.6     .05       0
Bank Sta=5019.2,5023.2
XS Rating Curve= 0 ,0
Exp/Cntr=0.3,0.1

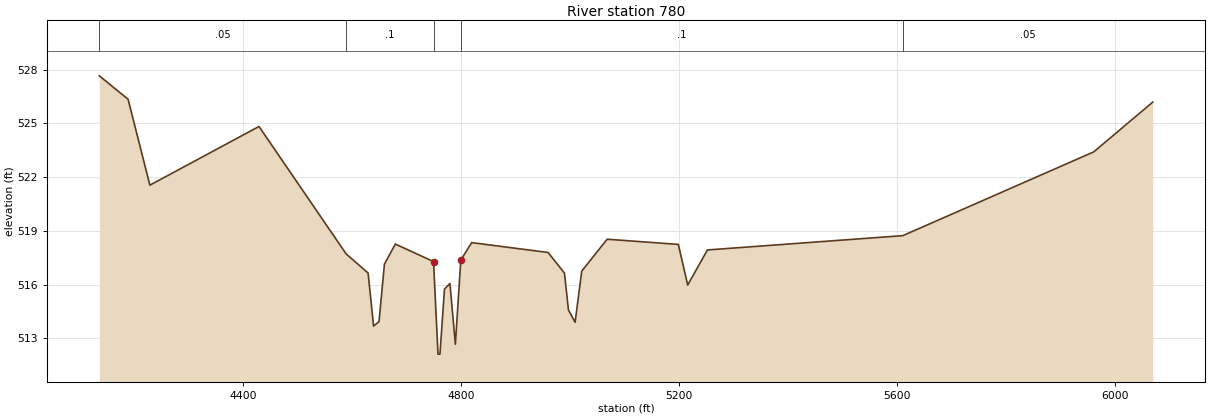
Type RM Length L Ch R = 1 ,780     ,0,0,0
BEGIN DESCRIPTION:
Mapping XS ea33e4df
END DESCRIPTION:
XS GIS Cut Line= 4
      2690011.41      6967268.28      2690055.68      6968130.74
      2690480.16      6968304.78       2691082.7      6968200.89
#Sta/Elev= 30
  4136.4  527.66  4189.2  526.35  4229.2  521.55  4429.5  524.83  4589.5  517.71
  4629.8  516.64  4639.8  513.68  4649.8  513.92  4659.8  517.14  4679.8  518.26
  4749.9  517.28  4758.1  512.11  4761.7  512.11    4770  515.74    4780  516.06
    4790  512.66    4800  517.37    4820  518.34  4960.2  517.79  4990.2  516.64
  4997.6  514.58  5009.8  513.89    5022  516.75  5068.6  518.53  5199.3  518.24
  5216.5  515.97  5252.7  517.93  5611.4  518.73  5961.9  523.41  6070.2  526.19
#Mann= 5 ,-1 , 0
  4136.4     .05       0  4589.5      .1       0  4749.9     .05       0
    4800      .1       0  5611.4     .05       0
Bank Sta=4749.9,4800
XS Rating Curve= 0 ,0
Exp/Cntr=0.3,0.1

Chan Stop Cuts=-1
Use User Specified Reach Order=0
Composite Channel Slope=5