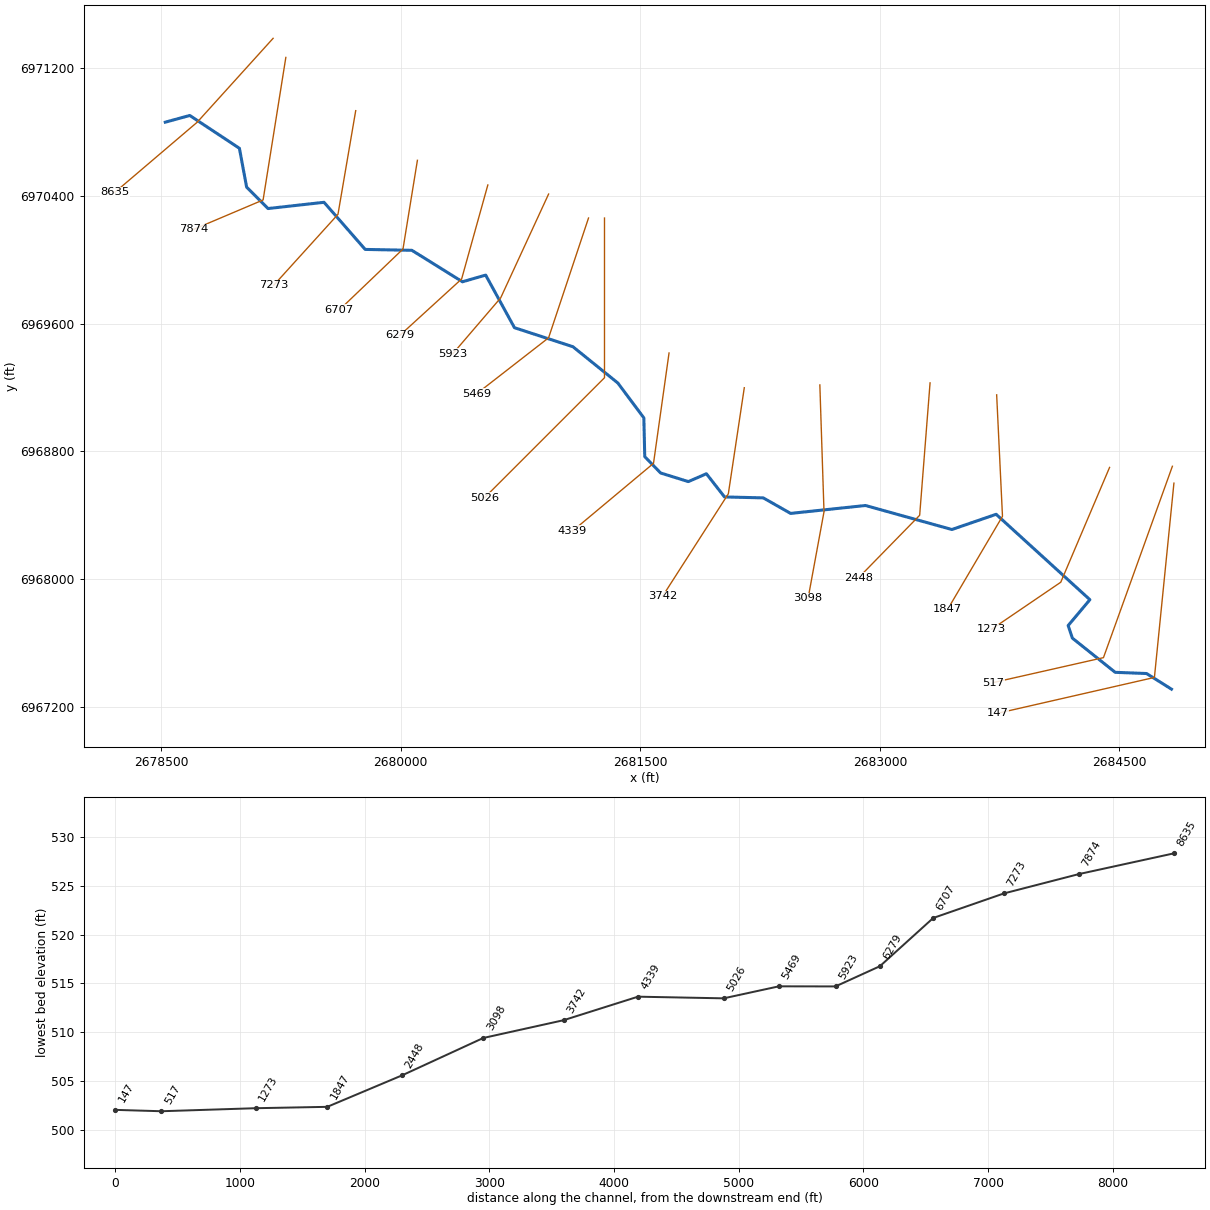
--- Muddy T14.prj (project) ---

Proj Title=Muddy T14 Base Level Engineering
Current Plan=p01
Default Exp/Contr=0.3,0.1
English Units
Geom File=g01
Flow File=f01
Plan File=p01
BEGIN DESCRIPTION:
Muddy T14
END DESCRIPTION:

--- Muddy T14.p01 (plan) ---

Plan Title=Multiple Run
Short Identifier=Multiple
Geom File=g01
Flow File=f01
Subcritical Flow
K Sum by GR= 0
Std Step Tol= 0.01
Critical Tol= 0.01
Num of Std Step Trials= 20
Max Error Tol= 0.3
Flow Tol Ratio= 0.001
Split Flow NTrial= 30
Split Flow Tol= 0.02
Split Flow Ratio= 0.02
Log Output Level= 0
Friction Slope Method= 1
Unsteady Friction Slope Method= 2
Unsteady Bridges Friction Slope Method= 1
Parabolic Critical Depth
Global Vel Dist=  1 , 1 , 1
Global Log Level= 0
CheckData=True
Encroach Param= -1, 0, 0, 0
BEGIN DESCRIPTION:
Multiple Run
END DESCRIPTION:

--- Muddy T14.f01 (steady flow) ---

Flow Title=Multiple
Number of Profiles=7
Profile Names=10-year,25-year,50-year,1pct_min,100-year,1pct_plu,500-year
River Rch & RM= Muddy T14,Reach-1,8635
     438     574     682     402     802    1600    1108
River Rch & RM= Muddy T14,Reach-1,7874
     737     998    1211     728    1453    2900    2093
River Rch & RM= Muddy T14,Reach-1,6279
     996    1365    1669    1010    2016    4023    2942
Boundary for River Rch & Prof#=Muddy T14,Reach-1,1
Up Type=0
Dn Type=3
Dn Slope=0.005
Boundary for River Rch & Prof#=Muddy T14,Reach-1,2
Up Type=0
Dn Type=3
Dn Slope=0.005
Boundary for River Rch & Prof#=Muddy T14,Reach-1,3
Up Type=0
Dn Type=3
Dn Slope=0.005
Boundary for River Rch & Prof#=Muddy T14,Reach-1,4
Up Type=0
Dn Type=3
Dn Slope=0.005
Boundary for River Rch & Prof#=Muddy T14,Reach-1,5
Up Type=0
Dn Type=3
Dn Slope=0.005
Boundary for River Rch & Prof#=Muddy T14,Reach-1,6
Up Type=0
Dn Type=3
Dn Slope=0.005
Boundary for River Rch & Prof#=Muddy T14,Reach-1,7
Up Type=0
Dn Type=3
Dn Slope=0.005

--- Muddy T14.g01 (geometry) ---

Geom Title=Existing Conditions

River Reach=Muddy T14,Reach-1
Reach XY= 30
      2678526.00      6970861.00      2678679.33      6970903.02
      2678990.09      6970697.60      2679035.30      6970454.33
      2679169.33      6970320.30      2679519.95      6970359.35
      2679777.70      6970064.36      2680070.07      6970058.75
      2680386.69      6969861.75      2680532.07      6969903.52
      2680712.28      6969574.23      2681078.30      6969455.17
      2681359.50      6969228.05      2681522.46      6969009.54
      2681528.05      6968766.84      2681627.48      6968664.61
      2681801.01      6968610.61      2681913.99      6968659.82
      2682027.45      6968514.53      2682270.07      6968508.76
      2682441.21      6968411.51      2682910.29      6968460.97
      2683450.96      6968310.68      2683728.29      6968405.90
      2684315.18      6967871.32      2684179.10      6967709.35
      2684205.37      6967630.77      2684473.55      6967416.46
      2684670.15      6967408.94      2684826.00      6967311.00

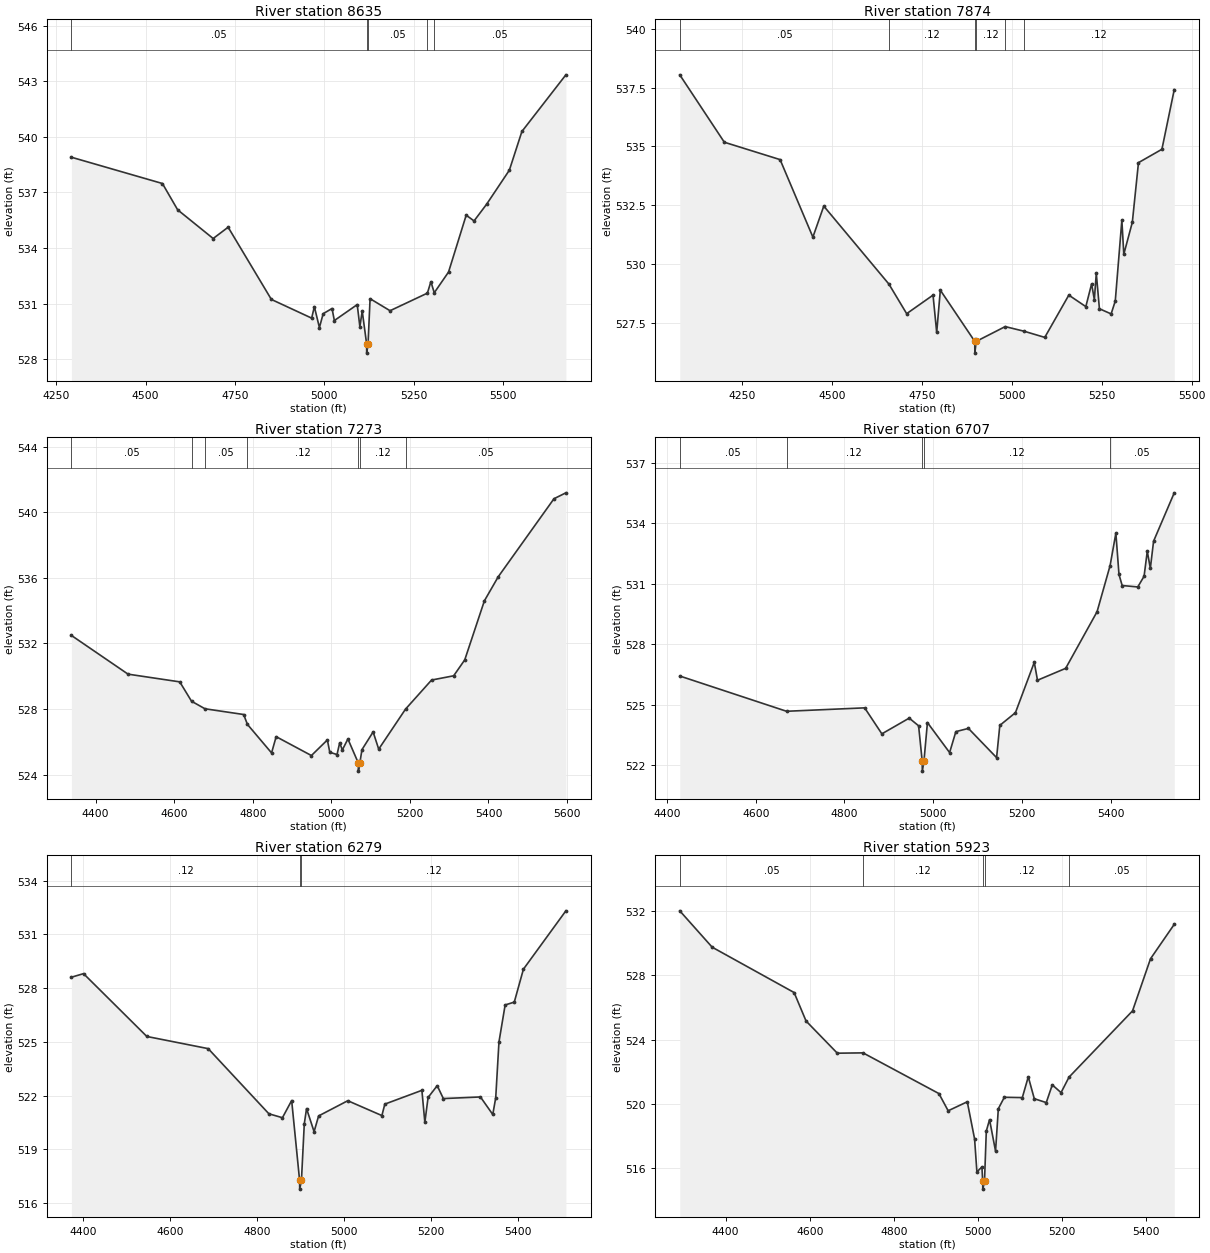
Type RM Length L Ch R = 1,8635,761,761,761
BEGIN DESCRIPTION:
Muddy T14 16.0
END DESCRIPTION:
XS GIS Cut Line= 3
      2679201.03      6971386.03      2678726.00      6970861.00
      2678211.35      6970422.74
#Sta/Elev= 30
  4292.3  538.90  4547.1  537.48  4589.7  536.06  4689.1  534.51  4731.0  535.12
  4852.0  531.22  4964.8  530.21  4972.3  530.83  4986.5  529.70  4997.0  530.45
  5021.8  530.73  5028.3  530.08  5092.3  530.94  5099.7  529.75  5106.3  530.59
  5118.6  528.82  5118.8  528.32  5122.6  528.82  5128.3  531.26  5184.2  530.61
  5288.7  531.56  5298.5  532.18  5307.9  531.58  5347.9  532.70  5397.3  535.77
  5419.3  535.46  5454.4  536.36  5518.1  538.20  5553.2  540.29  5676.3  543.35
#Mann=5,-1,0
  4292.3    0.05       0  5118.6    0.03       0  5122.6    0.05       0
  5288.7    0.12       0  5307.9    0.05       0
Bank Sta=5118.6,5122.6
Exp/Cntr=0.3,0.1

Type RM Length L Ch R = 1,7874,601,601,601
BEGIN DESCRIPTION:
Mapping XS b1a28a7d
END DESCRIPTION:
XS GIS Cut Line= 3
      2679280.81      6971266.54      2679138.45      6970374.14
      2678704.44      6970190.12
#Sta/Elev= 30
  4076.5  538.05  4200.4  535.18  4355.5  534.44  4446.7  531.14  4477.0  532.46
  4658.1  529.14  4707.5  527.88  4780.8  528.67  4791.0  527.08  4801.1  528.88
  4896.9  526.70  4897.1  526.20  4900.9  526.70  4981.5  527.33  5034.6  527.13
  5091.5  526.87  5158.4  528.67  5205.7  528.18  5221.8  529.15  5229.4  528.48
  5234.8  529.60  5243.5  528.09  5276.1  527.87  5287.6  528.42  5305.9  531.86
  5311.3  530.41  5335.0  531.77  5352.1  534.31  5417.3  534.88  5451.6  537.42
#Mann=6,-1,0
  4076.5    0.05       0  4658.1    0.12       0  4896.9    0.03       0
  4900.9    0.12       0  4981.5    0.05       0  5034.6    0.12       0
Bank Sta=4896.9,4900.9
Exp/Cntr=0.3,0.1

Type RM Length L Ch R = 1,7273,566,566,566
BEGIN DESCRIPTION:
Mapping XS 33a3f183
END DESCRIPTION:
XS GIS Cut Line= 3
      2679718.31      6970933.18      2679607.20      6970283.86
      2679204.39      6969839.39
#Sta/Elev= 30
  4338.5  532.49  4482.7  530.13  4614.3  529.66  4644.3  528.48  4678.5  528.02
  4777.0  527.67  4786.5  527.07  4848.0  525.33  4859.7  526.32  4949.4  525.17
  4990.0  526.12  4996.2  525.37  5014.6  525.23  5021.4  525.95  5028.1  525.51
  5042.3  526.18  5068.7  524.72  5069.0  524.22  5072.7  524.72  5078.1  525.53
  5106.5  526.61  5120.7  525.56  5189.0  528.00  5255.2  529.77  5311.5  530.03
  5339.7  531.00  5389.7  534.60  5424.8  536.06  5566.8  540.82  5597.1  541.18
#Mann=7,-1,0
  4338.5    0.05       0  4644.3    0.12       0  4678.5    0.05       0
  4786.5    0.12       0  5068.7    0.07       0  5072.7    0.12       0
  5189.0    0.05       0
Bank Sta=5068.7,5072.7
Exp/Cntr=0.3,0.1

Type RM Length L Ch R = 1,6707,428,428,428
BEGIN DESCRIPTION:
Mapping XS 73bbf697
END DESCRIPTION:
XS GIS Cut Line= 3
      2680104.60      6970622.45      2680014.32      6970066.85
      2679615.55      6969685.42
#Sta/Elev= 30
  4428.8  526.43  4669.5  524.68  4845.6  524.85  4884.4  523.56  4946.0  524.34
  4967.2  523.96  4975.3  522.21  4975.6  521.71  4979.3  522.21  4987.1  524.12
  5037.1  522.63  5051.2  523.67  5079.5  523.83  5143.0  522.38  5150.3  523.98
  5185.5  524.61  5228.0  527.11  5235.2  526.22  5298.7  526.81  5369.5  529.62
  5398.9  531.91  5411.9  533.52  5418.9  531.47  5426.1  530.92  5461.3  530.85
  5475.5  531.38  5482.7  532.62  5489.6  531.77  5496.9  533.12  5543.5  535.52
#Mann=5,-1,0
  4428.8    0.05       0  4669.5    0.12       0  4975.3    0.07       0
  4979.3    0.12       0  5398.9    0.05       0
Bank Sta=4975.3,4979.3
Exp/Cntr=0.3,0.1

Type RM Length L Ch R = 1,6279,356,356,356
BEGIN DESCRIPTION:
Mapping XS e8b32f1f
END DESCRIPTION:
XS GIS Cut Line= 3
      2680545.57      6970467.90      2680381.50      6969879.35
      2679993.96      6969525.62
#Sta/Elev= 30
  4373.4  528.61  4401.3  528.81  4546.7  525.30  4687.6  524.62  4827.0  520.98
  4858.1  520.76  4879.3  521.72  4897.5  517.27  4897.8  516.77  4901.8  517.27
  4908.3  520.42  4913.5  521.27  4930.8  519.98  4941.2  520.86  5008.2  521.71
  5086.5  520.88  5093.3  521.52  5178.4  522.29  5185.2  520.50  5192.6  521.89
  5213.6  522.55  5227.7  521.83  5312.9  521.92  5341.2  520.94  5348.0  521.88
  5355.4  524.99  5369.6  527.06  5390.6  527.22  5411.6  529.06  5509.1  532.32
#Mann=3,-1,0
  4373.4    0.12       0  4897.5    0.07       0  4901.8    0.12       0
Bank Sta=4897.5,4901.8
Exp/Cntr=0.3,0.1

Type RM Length L Ch R = 1,5923,454,454,454
BEGIN DESCRIPTION:
Muddy T14 11.0
END DESCRIPTION:
XS GIS Cut Line= 3
      2680926.02      6970411.03      2680626.00      6969761.00
      2680326.00      6969411.01
#Sta/Elev= 30
  4290.7  532.00  4367.8  529.74  4562.9  526.92  4591.3  525.15  4665.7  523.15
  4726.9  523.17  4907.5  520.64  4929.5  519.57  4975.0  520.13  4992.4  517.82
  4997.9  515.77  5009.9  516.08  5011.6  515.20  5012.0  514.70  5016.0  515.20
  5020.3  518.31  5028.0  519.02  5042.3  517.06  5048.9  519.70  5063.2  520.41
  5106.0  520.39  5120.2  521.68  5134.5  520.32  5163.0  520.08  5177.3  521.18
  5198.2  520.70  5217.1  521.66  5368.3  525.78  5411.1  529.02  5467.6  531.16
#Mann=5,-1,0
  4290.7    0.05       0  4726.9    0.12       0  5011.6    0.07       0
  5016.0    0.12       0  5217.1    0.05       0
Bank Sta=5011.6,5016
Exp/Cntr=0.3,0.1

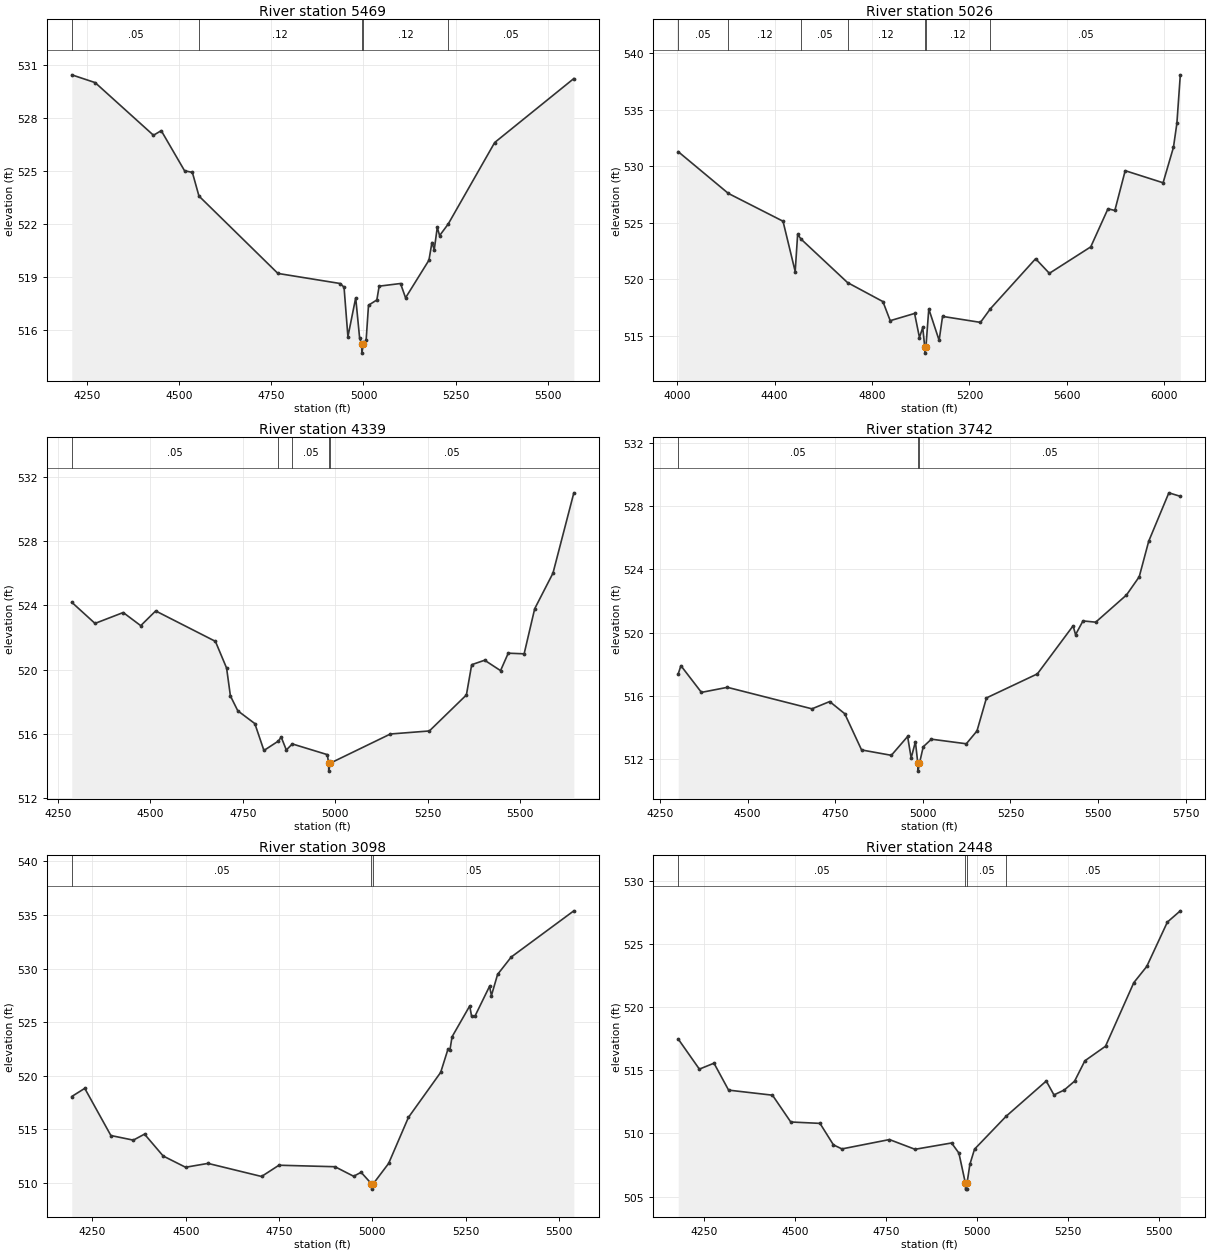
Type RM Length L Ch R = 1,5469,443,443,443
BEGIN DESCRIPTION:
Muddy T14 10.0
END DESCRIPTION:
XS GIS Cut Line= 3
      2681176.01      6970261.03      2680926.00      6969511.00
      2680475.99      6969160.99
#Sta/Elev= 30
  4209.4  530.46  4272.7  530.02  4430.8  527.04  4451.9  527.30  4515.1  525.03
  4536.2  524.94  4554.1  523.60  4768.1  519.22  4936.8  518.65  4947.3  518.44
  4957.8  515.64  4978.9  517.84  4989.5  515.57  4995.2  515.21  4995.6  514.71
  4999.6  515.21  5007.2  515.45  5013.6  517.42  5036.2  517.72  5042.5  518.50
  5100.4  518.65  5114.0  517.84  5177.4  519.97  5185.5  520.97  5191.8  520.57
  5200.0  521.83  5206.3  521.36  5229.7  522.02  5355.6  526.63  5570.1  530.25
#Mann=5,-1,0
  4209.4    0.05       0  4554.1    0.12       0  4995.2    0.07       0
  4999.6    0.12       0  5229.7    0.05       0
Bank Sta=4995.2,4999.6
Exp/Cntr=0.3,0.1

Type RM Length L Ch R = 1,5026,687,687,687
BEGIN DESCRIPTION:
Muddy T14 9.0
END DESCRIPTION:
XS GIS Cut Line= 3
      2681276.00      6970260.99      2681276.00      6969261.00
      2680526.03      6968511.03
#Sta/Elev= 30
  4004.8  531.30  4210.4  527.61  4434.8  525.15  4484.8  520.70  4494.8  523.98
  4509.2  523.56  4699.7  519.72  4844.8  518.04  4874.8  516.35  4974.8  516.99
  4994.8  514.86  5008.3  515.75  5016.7  513.98  5017.1  513.48  5021.2  513.98
  5033.1  517.39  5075.5  514.61  5089.6  516.73  5245.2  516.20  5286.2  517.41
  5471.5  521.83  5528.0  520.54  5697.8  522.88  5768.5  526.25  5796.7  526.10
  5839.2  529.62  5994.7  528.55  6037.2  531.68  6051.3  533.80  6065.4  538.10
#Mann=7,-1,0
  4004.8    0.05       0  4210.4    0.12       0  4509.2    0.05       0
  4699.7    0.12       0  5016.7    0.07       0  5021.2    0.12       0
  5286.2    0.05       0
Bank Sta=5016.7,5021.2
Exp/Cntr=0.3,0.1

Type RM Length L Ch R = 1,4339,597,597,597
BEGIN DESCRIPTION:
Mapping XS cc2782ad
END DESCRIPTION:
XS GIS Cut Line= 3
      2681680.11      6969415.80      2681582.89      6968724.83
      2681075.96      6968301.23
#Sta/Elev= 30
  4287.0  524.20  4349.9  522.88  4426.2  523.56  4473.6  522.74  4514.0  523.66
  4675.6  521.76  4705.9  520.09  4716.2  518.35  4736.2  517.42  4782.3  516.62
  4806.9  514.94  4846.1  515.53  4853.6  515.78  4867.5  514.97  4883.6  515.35
  4978.5  514.68  4981.8  514.15  4982.3  513.65  4986.5  514.15  5149.1  515.97
  5254.5  516.16  5354.7  518.41  5369.0  520.30  5404.1  520.58  5447.1  519.93
  5467.9  521.02  5510.9  520.98  5539.5  523.80  5588.9  526.02  5645.4  531.04
#Mann=5,-1,0
  4287.0    0.05       0  4846.1    0.12       0  4883.6    0.05       0
  4981.8    0.03       0  4986.5    0.05       0
Bank Sta=4981.8,4986.5
Exp/Cntr=0.3,0.1

Type RM Length L Ch R = 1,3742,644,644,644
BEGIN DESCRIPTION:
Mapping XS cafa5cdf
END DESCRIPTION:
XS GIS Cut Line= 3
      2682151.30      6969198.47      2682051.47      6968534.38
      2681640.09      6967893.50
#Sta/Elev= 30
  4301.8  517.39  4309.4  517.91  4368.0  516.22  4442.1  516.54  4683.5  515.18
  4734.1  515.64  4777.1  514.87  4825.1  512.58  4910.1  512.24  4956.5  513.43
  4966.7  512.07  4978.8  513.10  4985.6  511.74  4986.2  511.24  4990.4  511.74
  5001.1  512.78  5024.4  513.26  5124.1  512.97  5154.5  513.78  5181.6  515.87
  5326.9  517.39  5428.9  520.43  5435.9  519.87  5457.1  520.74  5493.4  520.66
  5581.3  522.38  5617.6  523.53  5644.7  525.78  5702.2  528.84  5734.9  528.62
#Mann=3,-1,0
  4301.8    0.05       0  4985.6    0.03       0  4990.4    0.05       0
Bank Sta=4985.6,4990.4
Exp/Cntr=0.3,0.1

Type RM Length L Ch R = 1,3098,650,650,650
BEGIN DESCRIPTION:
Mapping XS cf63ac10
END DESCRIPTION:
XS GIS Cut Line= 3
      2682624.39      6969215.78      2682650.43      6968421.53
      2682550.80      6967880.10
#Sta/Elev= 30
  4194.6  518.06  4229.4  518.82  4299.4  514.42  4359.5  513.99  4389.5  514.55
  4439.5  512.51  4499.5  511.46  4559.6  511.82  4703.1  510.60  4749.7  511.65
  4899.8  511.51  4949.8  510.62  4969.8  510.99  4997.5  509.92  4998.1  509.42
  5002.4  509.92  5043.6  511.82  5096.6  516.11  5183.0  520.31  5202.7  522.49
  5207.8  522.40  5213.5  523.63  5260.8  526.51  5265.9  525.54  5274.5  525.53
  5313.9  528.34  5319.0  527.48  5335.5  529.45  5372.0  531.07  5539.8  535.38
#Mann=3,-1,0
  4194.6    0.05       0  4997.5    0.03       0  5002.4    0.05       0
Bank Sta=4997.5,5002.4
Exp/Cntr=0.3,0.1

Type RM Length L Ch R = 1,2448,601,601,601
BEGIN DESCRIPTION:
Mapping XS 2e755690
END DESCRIPTION:
XS GIS Cut Line= 3
      2683314.49      6969228.80      2683249.38      6968399.83
      2682867.47      6968009.24
#Sta/Elev= 30
  4179.9  517.47  4237.9  515.09  4278.0  515.56  4318.1  513.43  4438.5  513.03
  4488.7  510.91  4568.9  510.80  4605.8  509.10  4629.1  508.78  4759.5  509.52
  4829.7  508.75  4930.0  509.25  4950.1  508.45  4967.7  506.10  4968.3  505.60
  4972.0  505.60  4972.6  506.10  4980.2  507.56  4993.0  508.76  5079.6  511.36
  5189.8  514.15  5211.0  513.05  5239.3  513.44  5267.6  514.14  5295.8  515.75
  5352.4  516.90  5430.1  521.93  5465.6  523.21  5522.2  526.72  5557.7  527.61
#Mann=4,-1,0
  4179.9    0.05       0  4967.7    0.07       0  4972.6    0.05       0
  5079.6    0.05       0
Bank Sta=4967.7,4972.6
Exp/Cntr=0.3,0.1

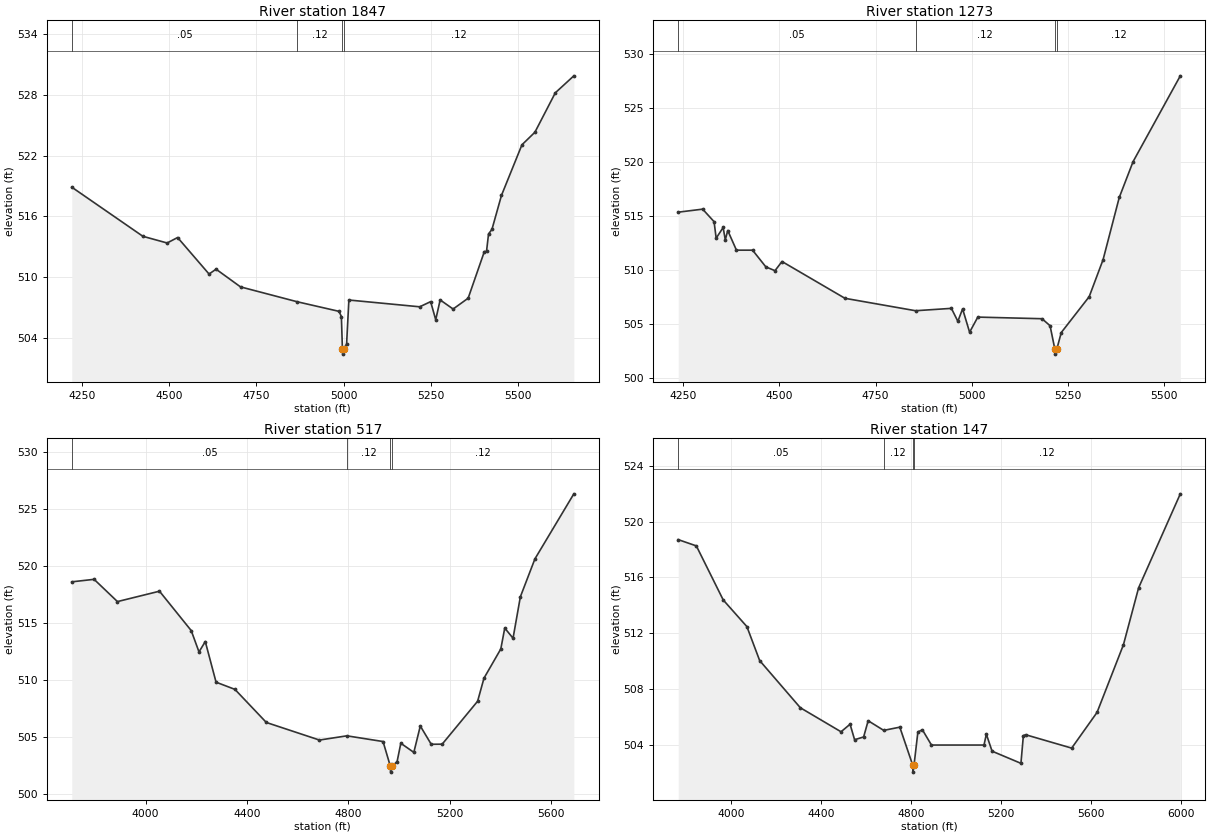
Type RM Length L Ch R = 1,1847,574,574,574
BEGIN DESCRIPTION:
Mapping XS 7fca905c
END DESCRIPTION:
XS GIS Cut Line= 3
      2683731.44      6969153.89      2683767.90      6968393.47
      2683424.15      6967810.12
#Sta/Elev= 30
  4221.3  518.88  4425.1  514.02  4494.5  513.36  4524.5  513.90  4614.6  510.29
  4634.7  510.77  4704.7  509.02  4867.0  507.55  4986.9  506.60  4993.7  506.09
  4996.7  502.87  4997.6  502.37  5002.3  502.87  5008.7  503.40  5015.2  507.72
  5218.1  507.05  5249.4  507.56  5264.0  505.77  5276.7  507.73  5313.8  506.83
  5356.9  507.90  5403.3  512.51  5409.5  512.52  5415.3  514.25  5425.1  514.71
  5452.4  518.07  5511.0  523.07  5548.1  524.31  5606.6  528.21  5659.7  529.89
#Mann=4,-1,0
  4221.3    0.05       0  4867.0    0.12       0  4996.7    0.07       0
  5002.3    0.12       0
Bank Sta=4996.7,5002.3
Exp/Cntr=0.3,0.1

Type RM Length L Ch R = 1,1273,756,756,756
BEGIN DESCRIPTION:
Mapping XS b96a254c
END DESCRIPTION:
XS GIS Cut Line= 3
      2684438.39      6968699.37      2684132.83      6967980.62
      2683700.28      6967686.48
#Sta/Elev= 30
  4237.2  515.38  4300.6  515.66  4330.3  514.50  4335.7  512.97  4353.9  513.96
  4359.4  512.81  4365.8  513.68  4388.4  511.86  4430.3  511.86  4464.8  510.31
  4488.5  509.96  4506.7  510.81  4670.3  507.40  4853.6  506.25  4946.7  506.47
  4963.5  505.27  4975.8  506.42  4994.0  504.26  5015.3  505.66  5182.1  505.51
  5203.0  504.86  5215.2  502.73  5216.0  502.23  5220.8  502.73  5232.1  504.23
  5304.6  507.55  5340.7  510.98  5382.7  516.74  5418.6  520.06  5541.3  528.01
#Mann=4,-1,0
  4237.2    0.05       0  4853.6    0.12       0  5215.2    0.07       0
  5220.8    0.12       0
Bank Sta=5215.2,5220.8
Exp/Cntr=0.3,0.1

Type RM Length L Ch R = 1,517,370,370,370
BEGIN DESCRIPTION:
Mapping XS 9d31e24e
END DESCRIPTION:
XS GIS Cut Line= 3
      2684831.71      6968706.59      2684400.19      6967508.40
      2683710.15      6967352.36
#Sta/Elev= 30
  3708.6  518.59  3796.7  518.81  3888.8  516.86  4054.7  517.77  4179.9  514.32
  4210.6  512.45  4235.4  513.36  4277.9  509.80  4352.3  509.17  4476.3  506.27
  4685.8  504.73  4794.1  505.10  4936.8  504.60  4965.8  502.42  4966.8  501.92
  4971.6  502.42  4992.3  502.85  5006.9  504.45  5058.2  503.65  5083.8  505.96
  5126.9  504.36  5170.1  504.37  5309.9  508.13  5335.0  510.15  5401.4  512.71
  5417.0  514.54  5449.7  513.65  5478.6  517.28  5536.0  520.60  5689.6  526.30
#Mann=4,-1,0
  3708.6    0.05       0  4794.1    0.12       0  4965.8    0.07       0
  4971.6    0.12       0
Bank Sta=4965.8,4971.6
Exp/Cntr=0.3,0.1

Type RM Length L Ch R = 1,147,0,0,0
BEGIN DESCRIPTION:
Muddy T14 1.0
END DESCRIPTION:
XS GIS Cut Line= 3
      2684841.36      6968601.15      2684719.23      6967384.44
      2683735.25      6967159.44
#Sta/Elev= 30
  3763.8  518.71  3844.4  518.26  3963.8  514.39  4069.1  512.48  4125.8  510.05
  4306.7  506.67  4487.6  504.95  4527.8  505.49  4547.9  504.38  4588.1  504.58
  4608.2  505.74  4677.4  505.05  4748.9  505.28  4806.3  502.56  4807.2  502.06
  4812.1  502.56  4829.3  504.94  4849.4  505.09  4889.6  504.00  5123.3  504.00
  5133.6  504.78  5159.1  503.56  5287.4  502.69  5298.2  504.67  5307.9  504.74
  5513.0  503.78  5625.9  506.34  5743.1  511.18  5810.6  515.26  5996.0  521.99
#Mann=4,-1,0
  3763.8    0.05       0  4677.4    0.12       0  4806.3    0.07       0
  4812.1    0.12       0
Bank Sta=4806.3,4812.1
Exp/Cntr=0.3,0.1

Chan Stop Cuts=-1