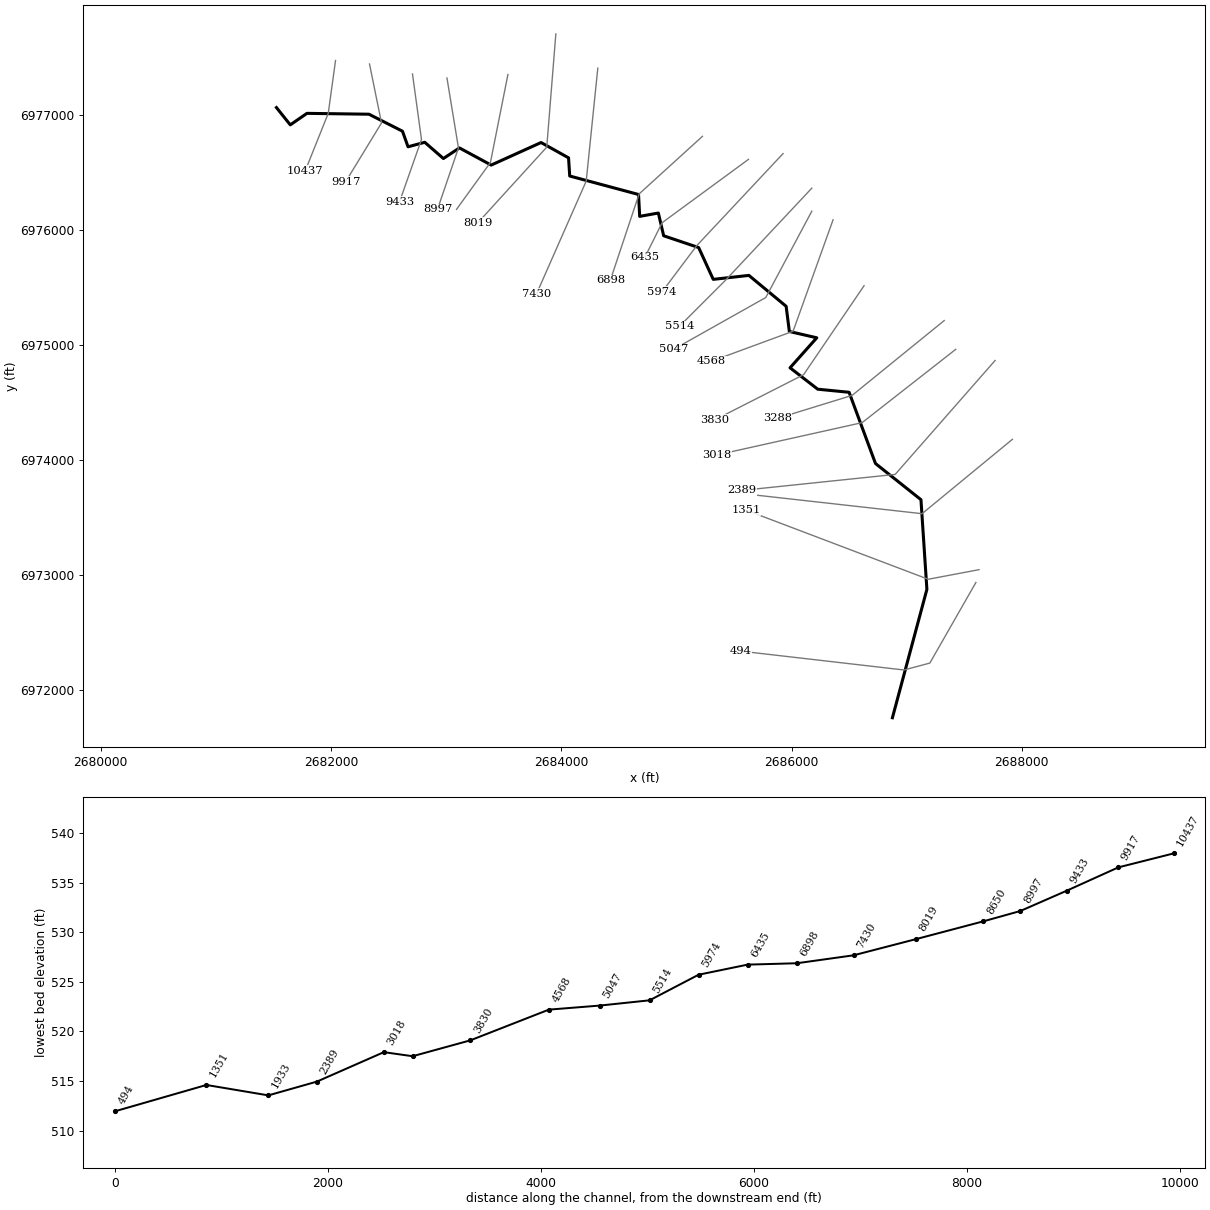
--- Muddy T15.prj (project) ---

Proj Title=Muddy T15 Base Level Engineering
Current Plan=p01
Default Exp/Contr=0.3,0.1
English Units
Geom File=g01
Flow File=f01
Plan File=p01
BEGIN DESCRIPTION:
Muddy T15
END DESCRIPTION:

--- Muddy T15.p01 (plan) ---

Plan Title=Multiple Run
Short Identifier=Multiple
Geom File=g01
Flow File=f01
Subcritical Flow
K Sum by GR= 0
Std Step Tol= 0.01
Critical Tol= 0.01
Num of Std Step Trials= 20
Max Error Tol= 0.3
Flow Tol Ratio= 0.001
Split Flow NTrial= 30
Split Flow Tol= 0.02
Split Flow Ratio= 0.02
Log Output Level= 0
Friction Slope Method= 1
Unsteady Friction Slope Method= 2
Unsteady Bridges Friction Slope Method= 1
Parabolic Critical Depth
Global Vel Dist=  1 , 1 , 1
Global Log Level= 0
CheckData=True
Encroach Param= -1, 0, 0, 0
BEGIN DESCRIPTION:
Multiple Run
END DESCRIPTION:

--- Muddy T15.f01 (steady flow) ---

Flow Title=Multiple
Number of Profiles=7
Profile Names=10-year,25-year,50-year,1pct_min,100-year,1pct_plu,500-year
River Rch & RM= Muddy T15,Reach-1,10437
     572     761     912     543    1083    2160    1524
River Rch & RM= Muddy T15,Reach-1,8019
     950    1299    1586     959    1913    3817    2783
River Rch & RM= Muddy T15,Reach-1,5047
    1006    1375    1677    1012    2019    4029    2930
Boundary for River Rch & Prof#=Muddy T15,Reach-1,1
Up Type=0
Dn Type=3
Dn Slope=0.005
Boundary for River Rch & Prof#=Muddy T15,Reach-1,2
Up Type=0
Dn Type=3
Dn Slope=0.005
Boundary for River Rch & Prof#=Muddy T15,Reach-1,3
Up Type=0
Dn Type=3
Dn Slope=0.005
Boundary for River Rch & Prof#=Muddy T15,Reach-1,4
Up Type=0
Dn Type=3
Dn Slope=0.005
Boundary for River Rch & Prof#=Muddy T15,Reach-1,5
Up Type=0
Dn Type=3
Dn Slope=0.005
Boundary for River Rch & Prof#=Muddy T15,Reach-1,6
Up Type=0
Dn Type=3
Dn Slope=0.005
Boundary for River Rch & Prof#=Muddy T15,Reach-1,7
Up Type=0
Dn Type=3
Dn Slope=0.005

--- Muddy T15.g01 (geometry) ---

Geom Title=Existing Conditions

River Reach=Muddy T15,Reach-1
Reach XY= 30
      2681526.00      6977061.00      2681646.21      6976910.71
      2681791.04      6977010.65      2682329.41      6977003.19
      2682620.75      6976855.55      2682668.94      6976720.00
      2682814.12      6976759.47      2682976.08      6976618.30
      2683115.36      6976710.43      2683391.16      6976561.38
      2683824.44      6976757.26      2684063.09      6976624.35
      2684073.24      6976466.45      2684670.97      6976305.92
      2684681.03      6976115.93      2684843.17      6976144.90
      2684889.23      6975947.33      2685193.17      6975844.89
      2685319.79      6975568.80      2685629.43      6975603.21
      2685953.00      6975334.82      2685980.93      6975116.03
      2686219.03      6975061.25      2685986.82      6974800.68
      2686227.53      6974614.73      2686499.83      6974588.01
      2686729.07      6973969.28      2687123.93      6973655.14
      2687175.49      6972876.21      2686876.00      6971761.00

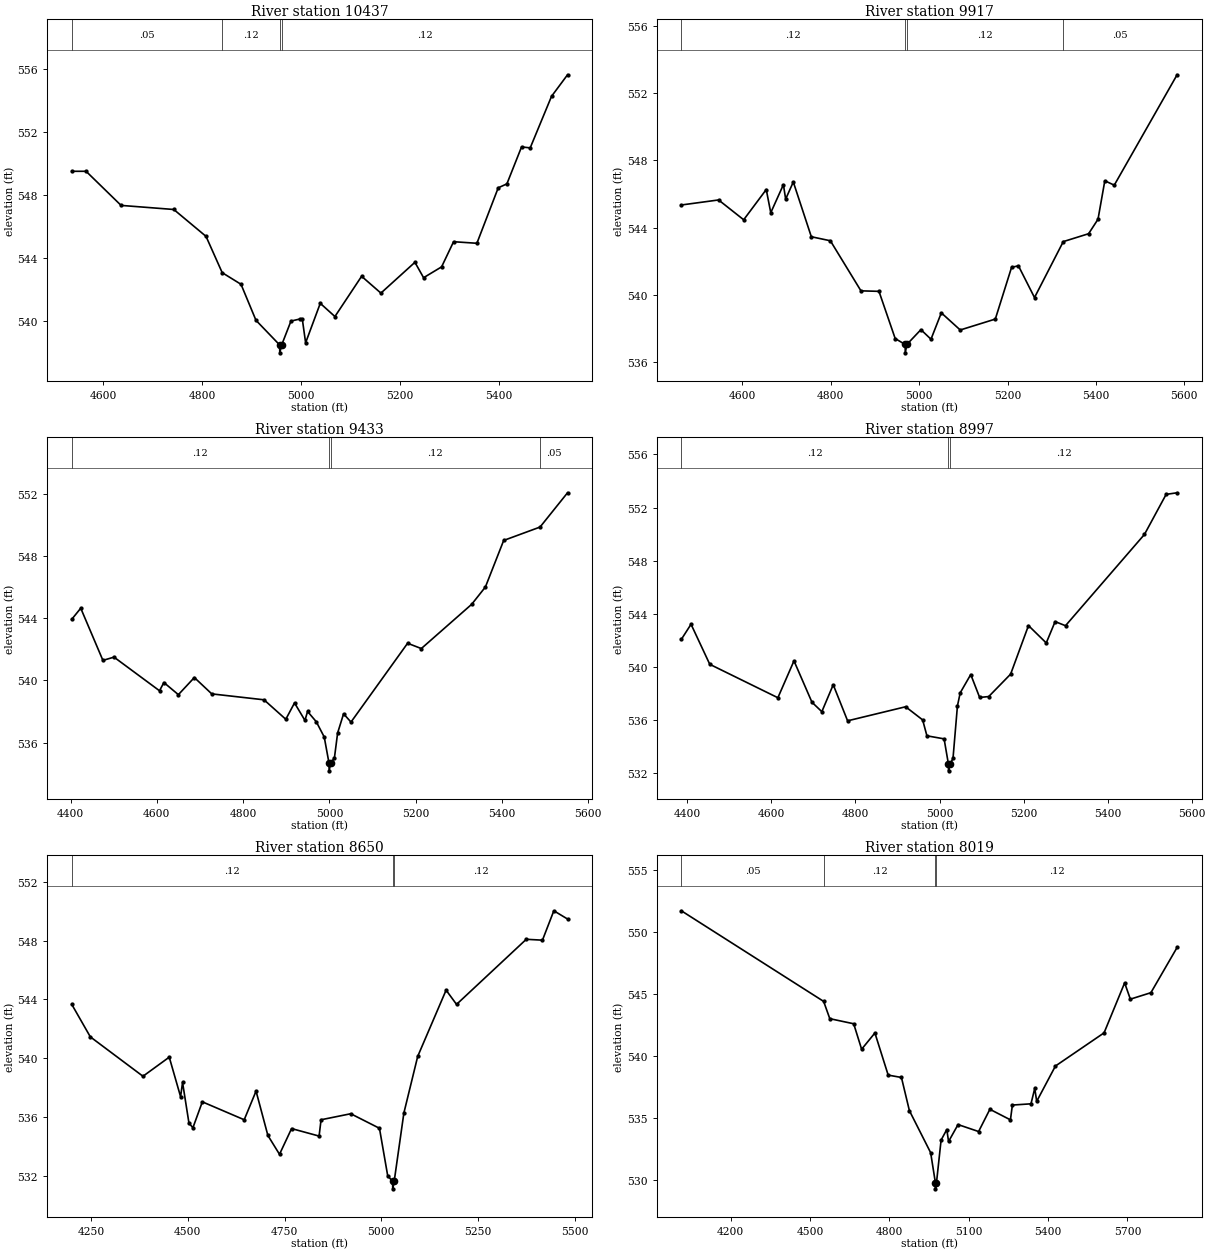
Type RM Length L Ch R = 1,10437,520,520,520
BEGIN DESCRIPTION:
Muddy T15 17.0
END DESCRIPTION:
XS GIS Cut Line= 3
      2682039.20      6977469.65      2681976.00      6977011.00
      2681776.00      6976511.00
#Sta/Elev= 30
  4537.1  549.51  4566.0  549.51  4636.7  547.34  4743.2  547.08  4808.3  545.37
  4841.0  543.06  4879.0  542.32  4909.2  540.03  4957.1  538.46  4957.3  537.96
  4961.1  538.46  4979.9  539.98  4997.6  540.11  5002.8  540.11  5009.5  538.60
  5039.1  541.11  5068.7  540.27  5122.6  542.83  5161.6  541.76  5230.3  543.72
  5247.8  542.74  5284.2  543.43  5308.4  545.03  5355.5  544.93  5398.6  548.46
  5416.1  548.71  5445.7  551.06  5463.2  551.00  5506.3  554.28  5538.6  555.65
#Mann=4,-1,0
  4537.1    0.05       0  4841.0    0.12       0  4957.1    0.07       0
  4961.1    0.12       0
Bank Sta=4957.1,4961.1
Exp/Cntr=0.3,0.1

Type RM Length L Ch R = 1,9917,484,484,484
BEGIN DESCRIPTION:
Mapping XS c59bf53c
END DESCRIPTION:
XS GIS Cut Line= 3
      2682334.33      6977439.31      2682438.50      6976927.12
      2682126.33      6976415.51
#Sta/Elev= 30
  4461.6  545.35  4545.9  545.65  4602.7  544.47  4653.8  546.27  4664.0  544.89
  4692.6  546.56  4697.7  545.70  4715.0  546.72  4755.8  543.46  4798.9  543.22
  4868.1  540.24  4908.9  540.21  4945.6  537.40  4968.1  537.05  4968.4  536.55
  4972.1  537.05  5003.8  537.93  5026.6  537.36  5050.0  538.93  5092.8  537.91
  5172.2  538.56  5209.0  541.64  5224.5  541.73  5260.9  539.84  5326.0  543.17
  5383.3  543.64  5404.6  544.50  5420.0  546.79  5441.4  546.53  5583.6  553.10
#Mann=4,-1,0
  4461.6    0.12       0  4968.1    0.07       0  4972.1    0.12       0
  5326.0    0.05       0
Bank Sta=4968.1,4972.1
Exp/Cntr=0.3,0.1

Type RM Length L Ch R = 1,9433,436,436,436
BEGIN DESCRIPTION:
Mapping XS 6be2006f
END DESCRIPTION:
XS GIS Cut Line= 3
      2682707.60      6977352.50      2682785.72      6976783.89
      2682594.76      6976241.37
#Sta/Elev= 30
  4402.8  543.93  4423.6  544.64  4475.0  541.29  4500.7  541.50  4606.2  539.34
  4616.3  539.87  4649.9  539.09  4686.9  540.19  4727.3  539.14  4848.4  538.76
  4898.9  537.51  4919.1  538.56  4943.2  537.44  4949.4  538.01  4969.6  537.35
  4988.0  536.37  4999.0  534.70  4999.3  534.20  5003.0  534.70  5011.6  535.03
  5019.0  536.63  5032.8  537.86  5050.0  537.33  5181.2  542.39  5213.0  542.05
  5329.7  544.89  5361.5  546.00  5403.9  548.99  5488.2  549.85  5551.9  552.05
#Mann=4,-1,0
  4402.8    0.12       0  4999.0    0.07       0  5003.0    0.12       0
  5488.2    0.05       0
Bank Sta=4999,5003
Exp/Cntr=0.3,0.1

Type RM Length L Ch R = 1,8997,347,347,347
BEGIN DESCRIPTION:
Mapping XS e2382a7e
END DESCRIPTION:
XS GIS Cut Line= 3
      2683007.08      6977317.77      2683106.91      6976710.11
      2682924.62      6976176.28
#Sta/Elev= 30
  4385.5  542.06  4408.6  543.20  4453.2  540.18  4615.3  537.66  4653.6  540.44
  4696.4  537.32  4719.9  536.61  4747.0  538.64  4781.2  535.92  4919.3  536.98
  4959.8  535.99  4970.0  534.79  5010.9  534.56  5021.2  532.65  5021.4  532.15
  5025.2  532.65  5032.1  533.10  5042.6  537.04  5049.2  538.03  5074.3  539.41
  5095.5  537.68  5117.1  537.75  5169.2  539.44  5211.7  543.10  5254.0  541.79
  5275.1  543.40  5299.8  543.09  5487.7  549.97  5539.3  552.99  5565.4  553.11
#Mann=3,-1,0
  4385.5    0.12       0  5021.2    0.07       0  5025.2    0.12       0
Bank Sta=5021.2,5025.2
Exp/Cntr=0.3,0.1

Type RM Length L Ch R = 1,8650,631,631,631
BEGIN DESCRIPTION:
Mapping XS 8d18b79f
END DESCRIPTION:
XS GIS Cut Line= 3
      2683536.58      6977348.08      2683384.68      6976584.24
      2683090.27      6976177.26
#Sta/Elev= 30
  4200.2  543.66  4248.2  541.45  4384.2  538.77  4452.1  540.07  4481.4  537.38
  4486.5  538.35  4503.1  535.57  4513.3  535.27  4537.6  537.03  4645.8  535.81
  4676.4  537.76  4707.0  534.74  4737.0  533.46  4768.2  535.21  4839.3  534.70
  4844.4  535.81  4921.1  536.22  4995.3  535.23  5016.6  532.00  5029.3  531.61
  5029.6  531.11  5033.3  531.61  5058.4  536.27  5094.1  540.12  5167.5  544.63
  5194.5  543.66  5374.7  548.09  5416.5  548.03  5445.9  550.03  5481.3  549.47
#Mann=3,-1,0
  4200.2    0.12       0  5029.3    0.07       0  5033.3    0.12       0
Bank Sta=5029.3,5033.3
Exp/Cntr=0.3,0.1

Type RM Length L Ch R = 1,8019,589,589,589
BEGIN DESCRIPTION:
Muddy T15 12.0
END DESCRIPTION:
XS GIS Cut Line= 3
      2683952.68      6977700.36      2683873.82      6976717.12
      2683276.02      6976061.02
#Sta/Elev= 30
  4013.6  551.69  4551.5  544.40  4574.8  543.01  4665.1  542.60  4695.1  540.55
  4745.3  541.86  4795.5  538.47  4845.6  538.28  4875.7  535.61  4956.0  532.23
  4973.9  529.82  4974.3  529.32  4978.1  529.82  4995.5  533.24  5017.0  534.09
  5023.8  533.13  5059.6  534.49  5137.3  533.93  5179.9  535.72  5257.6  534.87
  5265.0  536.06  5335.3  536.16  5349.5  537.40  5356.9  536.36  5427.7  539.20
  5611.6  541.87  5689.3  545.89  5710.9  544.58  5788.6  545.10  5887.6  548.74
#Mann=4,-1,0
  4013.6    0.05       0  4551.5    0.12       0  4973.9    0.07       0
  4978.1    0.12       0
Bank Sta=4973.9,4978.1
Exp/Cntr=0.3,0.1

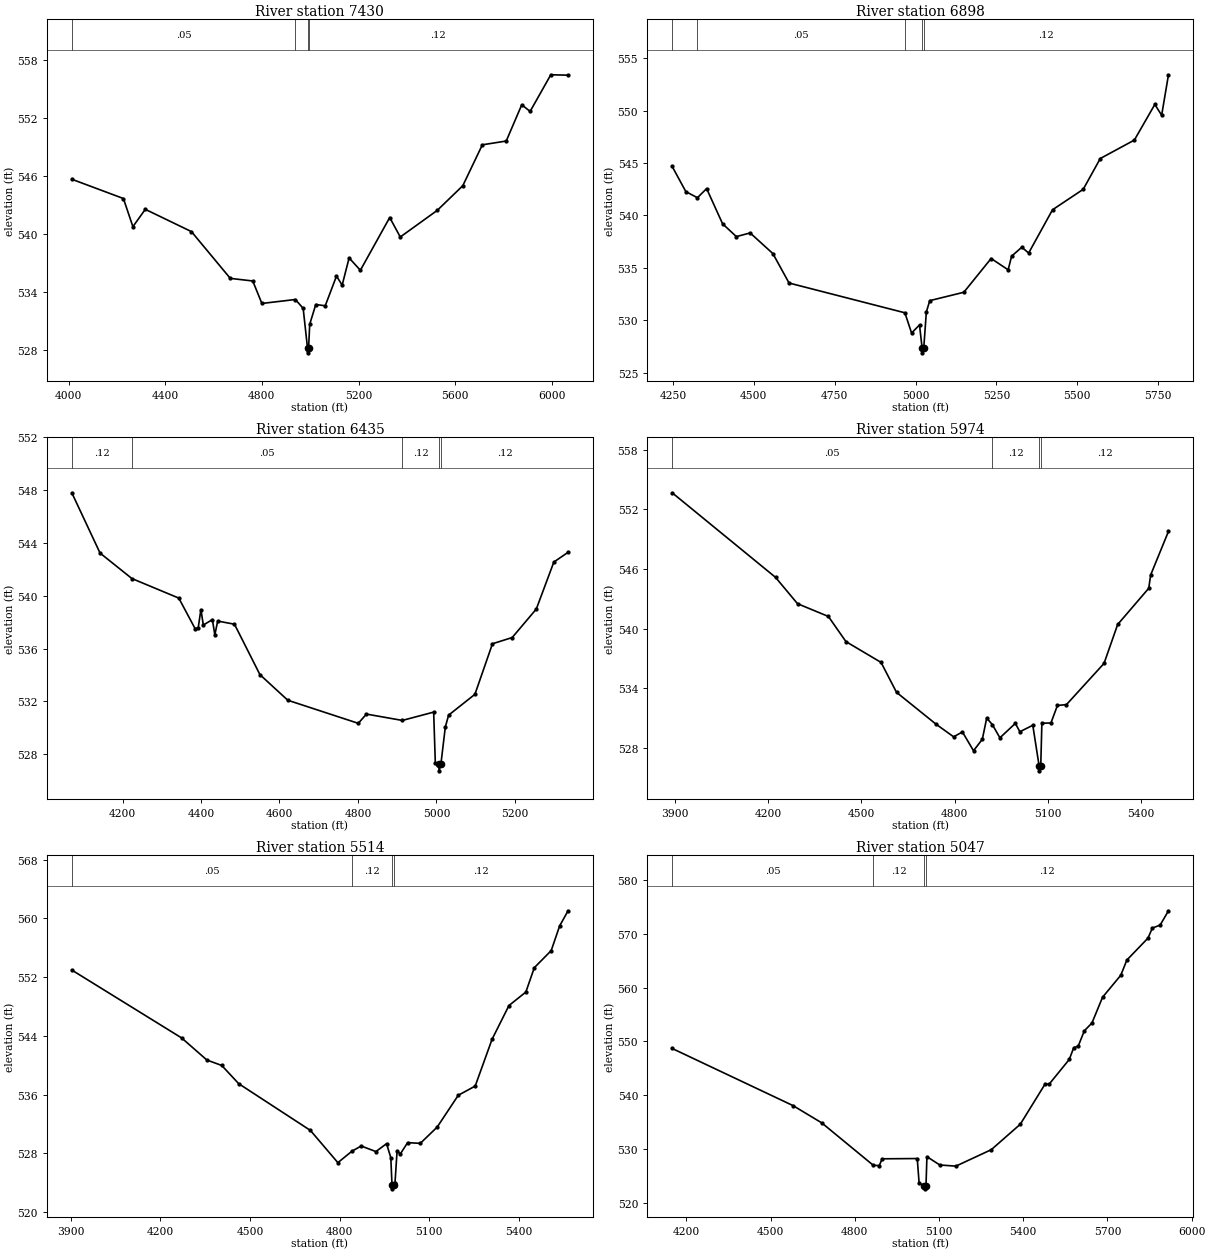
Type RM Length L Ch R = 1,7430,532,532,532
BEGIN DESCRIPTION:
Muddy T15 11.0
END DESCRIPTION:
XS GIS Cut Line= 3
      2684317.27      6977403.49      2684216.48      6976422.15
      2683786.19      6975445.54
#Sta/Elev= 30
  4013.5  545.68  4227.1  543.68  4266.4  540.76  4317.6  542.56  4508.6  540.25
  4669.4  535.40  4762.4  535.13  4800.1  532.80  4938.7  533.21  4971.0  532.29
  4988.9  528.18  4989.3  527.68  4993.4  528.18  4998.1  530.64  5023.1  532.69
  5062.3  532.56  5108.9  535.64  5132.3  534.70  5161.1  537.52  5207.7  536.24
  5329.1  541.71  5372.8  539.69  5525.8  542.45  5631.6  545.01  5712.5  549.25
  5811.3  549.64  5875.5  553.40  5910.1  552.71  5995.7  556.51  6067.2  556.47
#Mann=4,-1,0
  4013.5    0.05       0  4938.7    0.12       0  4988.9    0.07       0
  4993.4    0.12       0
Bank Sta=4988.9,4993.4
Exp/Cntr=0.3,0.1

Type RM Length L Ch R = 1,6898,463,463,463
BEGIN DESCRIPTION:
Muddy T15 10.0
END DESCRIPTION:
XS GIS Cut Line= 3
      2685226.00      6976811.00      2684676.00      6976311.00
      2684425.99      6975560.97
#Sta/Elev= 30
  4247.9  544.66  4290.1  542.26  4325.9  541.68  4354.3  542.55  4403.7  539.19
  4446.2  537.97  4488.8  538.32  4559.1  536.35  4609.1  533.54  4967.1  530.70
  4987.8  528.77  5012.3  529.54  5020.2  527.38  5020.9  526.88  5025.5  527.38
  5033.4  530.77  5043.9  531.86  5149.3  532.66  5233.6  535.88  5286.3  534.80
  5296.9  536.10  5328.5  536.96  5349.6  536.40  5423.4  540.53  5518.2  542.48
  5571.0  545.42  5676.4  547.18  5739.6  550.58  5760.7  549.55  5781.8  553.41
#Mann=5,-1,0
  4247.9    0.12       0  4325.9    0.05       0  4967.1    0.12       0
  5020.2    0.07       0  5025.5    0.12       0
Bank Sta=5020.2,5025.5
Exp/Cntr=0.3,0.1

Type RM Length L Ch R = 1,6435,461,461,461
BEGIN DESCRIPTION:
Muddy T15 9.0
END DESCRIPTION:
XS GIS Cut Line= 3
      2685625.98      6976610.98      2684876.00      6976061.00
      2684726.02      6975761.03
#Sta/Elev= 30
  4070.4  547.81  4142.5  543.24  4223.7  541.31  4343.2  539.83  4384.9  537.51
  4392.8  537.59  4399.6  538.96  4405.8  537.79  4428.9  538.20  4435.1  537.04
  4442.4  538.09  4485.2  537.85  4550.1  534.03  4621.1  532.09  4800.9  530.34
  4821.7  531.04  4913.2  530.56  4993.1  531.19  4997.3  527.34  5006.2  527.24
  5006.9  526.74  5011.5  527.24  5022.8  530.06  5031.2  530.96  5098.3  532.54
  5143.0  536.37  5193.3  536.84  5254.8  539.00  5299.5  542.56  5335.8  543.30
#Mann=5,-1,0
  4070.4    0.12       0  4223.7    0.05       0  4913.2    0.12       0
  5006.2    0.07       0  5011.5    0.12       0
Bank Sta=5006.2,5011.5
Exp/Cntr=0.3,0.1

Type RM Length L Ch R = 1,5974,460,460,460
BEGIN DESCRIPTION:
Muddy T15 8.0
END DESCRIPTION:
XS GIS Cut Line= 3
      2685926.01      6976661.01      2685176.00      6975861.00
      2684876.00      6975461.00
#Sta/Elev= 30
  3891.0  553.67  4223.4  545.17  4294.2  542.52  4393.4  541.24  4450.0  538.71
  4562.9  536.62  4612.7  533.61  4740.2  530.40  4796.4  529.14  4824.7  529.63
  4860.4  527.74  4888.7  528.89  4902.8  531.02  4920.9  530.37  4945.3  529.04
  4994.9  530.49  5009.5  529.65  5051.1  530.30  5071.4  526.22  5072.2  525.72
  5076.7  526.22  5080.3  530.51  5109.5  530.53  5130.3  532.29  5159.5  532.38
  5280.3  536.52  5324.1  540.43  5424.1  544.07  5430.3  545.41  5487.6  549.79
#Mann=4,-1,0
  3891.0    0.05       0  4920.9    0.12       0  5071.4    0.07       0
  5076.7    0.12       0
Bank Sta=5071.4,5076.7
Exp/Cntr=0.3,0.1

Type RM Length L Ch R = 1,5514,467,467,467
BEGIN DESCRIPTION:
Muddy T15 7.0
END DESCRIPTION:
XS GIS Cut Line= 3
      2686175.98      6976360.97      2685426.00      6975561.00
      2685026.03      6975161.03
#Sta/Elev= 30
  3903.3  552.97  4271.3  543.71  4355.8  540.70  4405.6  539.96  4462.3  537.48
  4702.6  531.10  4794.5  526.71  4841.6  528.27  4872.6  528.98  4921.9  528.22
  4957.6  529.30  4971.8  527.38  4975.8  523.64  4976.7  523.14  4981.4  523.64
  4985.9  523.99  4992.8  528.32  5003.4  527.88  5028.1  529.44  5070.6  529.34
  5127.1  531.56  5197.8  535.90  5254.4  537.15  5311.0  543.54  5367.5  548.13
  5424.1  549.97  5452.4  553.29  5509.0  555.62  5537.3  558.99  5565.5  561.05
#Mann=4,-1,0
  3903.3    0.05       0  4841.6    0.12       0  4975.8    0.07       0
  4981.4    0.12       0
Bank Sta=4975.8,4981.4
Exp/Cntr=0.3,0.1

Type RM Length L Ch R = 1,5047,479,479,479
BEGIN DESCRIPTION:
Muddy T15 6.0
END DESCRIPTION:
XS GIS Cut Line= 3
      2686175.99      6976160.99      2685776.00      6975411.00
      2684975.97      6974960.98
#Sta/Elev= 30
  4149.5  548.69  4579.8  538.08  4682.2  534.87  4866.2  526.97  4887.2  526.94
  4897.5  528.19  5022.4  528.24  5029.1  523.69  5048.0  523.11  5048.9  522.61
  5053.6  523.11  5056.9  528.59  5102.8  527.04  5160.1  526.83  5286.3  529.89
  5389.6  534.62  5477.2  542.03  5492.8  542.09  5563.9  546.65  5579.9  548.84
  5595.8  549.12  5617.5  551.96  5644.9  553.44  5682.5  558.21  5747.5  562.30
  5769.2  565.13  5844.4  569.20  5860.0  571.07  5887.7  571.62  5917.4  574.28
#Mann=4,-1,0
  4149.5    0.05       0  4866.2    0.12       0  5048.0    0.07       0
  5053.6    0.12       0
Bank Sta=5048,5053.6
Exp/Cntr=0.3,0.1

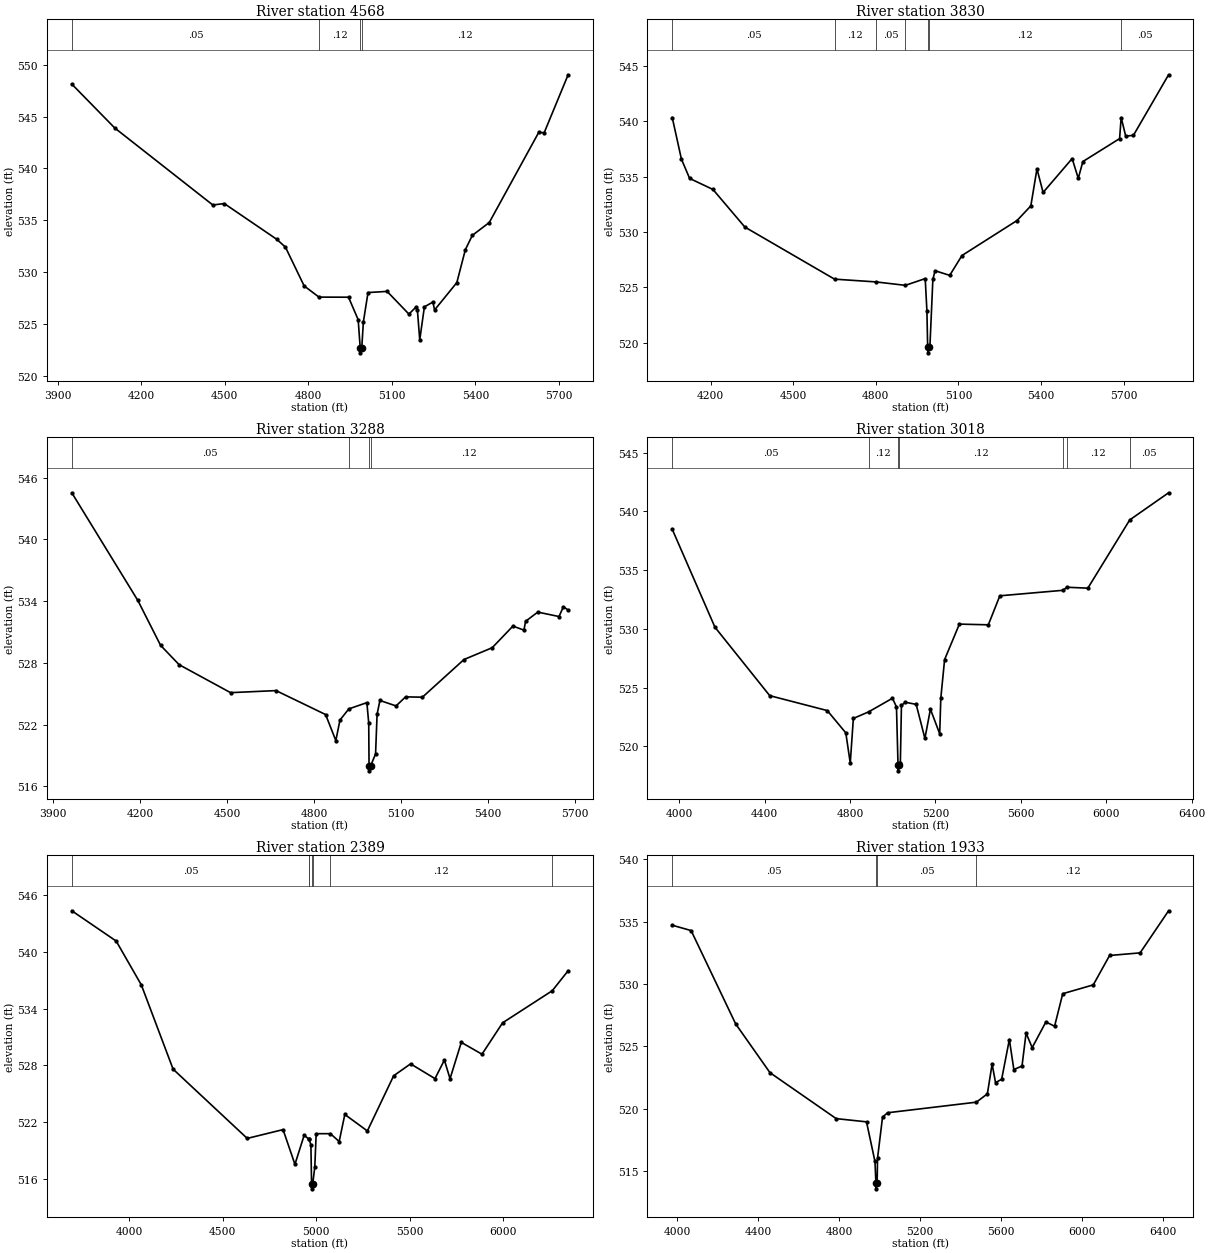
Type RM Length L Ch R = 1,4568,738,738,738
BEGIN DESCRIPTION:
Mapping XS 0ce15561
END DESCRIPTION:
XS GIS Cut Line= 3
      2686360.68      6976086.33      2686013.44      6975118.40
      2685305.98      6974857.98
#Sta/Elev= 30
  3950.9  548.14  4105.3  543.90  4457.3  536.47  4498.4  536.61  4687.3  533.15
  4718.1  532.40  4785.2  528.66  4838.4  527.58  4944.6  527.57  4979.2  525.40
  4986.5  522.70  4987.4  522.20  4992.2  522.70  4997.8  525.16  5014.5  528.02
  5083.1  528.13  5161.4  525.94  5186.6  526.61  5191.9  526.33  5200.3  523.45
  5217.0  526.64  5247.5  527.10  5253.6  526.34  5333.5  528.98  5364.0  532.15
  5389.1  533.54  5450.0  534.78  5627.4  543.47  5647.2  543.45  5733.1  549.04
#Mann=4,-1,0
  3950.9    0.05       0  4838.4    0.12       0  4986.5    0.07       0
  4992.2    0.12       0
Bank Sta=4986.5,4992.2
Exp/Cntr=0.3,0.1

Type RM Length L Ch R = 1,3830,542,542,542
BEGIN DESCRIPTION:
Mapping XS 007e61bc
END DESCRIPTION:
XS GIS Cut Line= 3
      2686629.78      6975513.39      2686104.59      6974740.79
      2685329.50      6974346.75
#Sta/Elev= 30
  4060.1  540.33  4093.4  536.58  4123.2  534.84  4208.1  533.84  4323.9  530.45
  4649.8  525.75  4800.3  525.50  4907.3  525.19  4979.4  525.80  4985.5  522.91
  4988.3  519.60  4989.2  519.10  4994.0  519.60  4996.3  519.60  5007.2  525.72
  5015.2  526.51  5068.4  526.09  5112.9  527.88  5313.1  531.04  5363.2  532.36
  5385.5  535.70  5407.8  533.57  5513.4  536.63  5535.6  534.84  5552.3  536.36
  5685.8  538.43  5691.5  540.33  5708.0  538.66  5735.9  538.72  5863.8  544.19
#Mann=7,-1,0
  4060.1    0.05       0  4649.8    0.12       0  4800.3    0.05       0
  4907.3    0.12       0  4988.3    0.07       0  4994.0    0.12       0
  5691.5    0.05       0
Bank Sta=4988.3,4994
Exp/Cntr=0.3,0.1

Type RM Length L Ch R = 1,3288,270,270,270
BEGIN DESCRIPTION:
Muddy T15 3.0
END DESCRIPTION:
XS GIS Cut Line= 3
      2687325.97      6975210.97      2686526.00      6974561.00
      2685876.01      6974361.00
#Sta/Elev= 30
  3965.4  544.53  4193.1  534.06  4271.4  529.70  4335.3  527.82  4512.7  525.10
  4669.3  525.30  4840.3  522.97  4875.5  520.44  4889.8  522.44  4920.3  523.52
  4982.5  524.13  4988.9  522.14  4990.0  518.00  4991.0  517.50  4995.8  518.00
  5012.5  519.15  5017.7  523.00  5027.5  524.34  5083.1  523.81  5115.8  524.69
  5174.0  524.66  5317.2  528.32  5414.6  529.47  5485.9  531.57  5523.8  531.18
  5529.7  532.04  5571.6  532.93  5644.8  532.50  5659.9  533.45  5676.2  533.13
#Mann=4,-1,0
  3965.4    0.05       0  4920.3    0.12       0  4990.0    0.07       0
  4995.8    0.12       0
Bank Sta=4990,4995.8
Exp/Cntr=0.3,0.1

Type RM Length L Ch R = 1,3018,629,629,629
BEGIN DESCRIPTION:
Muddy T15 2.0
END DESCRIPTION:
XS GIS Cut Line= 3
      2687425.97      6974960.98      2686612.87      6974324.32
      2685352.09      6974043.87
#Sta/Elev= 30
  3967.3  538.47  4167.1  530.14  4423.8  524.31  4693.3  523.04  4780.1  521.14
  4800.9  518.57  4815.4  522.37  4886.9  522.93  4998.6  524.09  5017.3  523.35
  5024.6  518.41  5025.6  517.91  5030.4  518.41  5035.5  518.60  5040.6  523.48
  5058.3  523.75  5109.5  523.57  5150.5  520.67  5176.3  523.16  5219.8  521.06
  5224.9  524.09  5242.7  527.38  5311.9  530.40  5447.5  530.34  5501.4  532.81
  5798.2  533.28  5814.5  533.54  5913.5  533.46  6109.7  539.27  6291.6  541.58
#Mann=7,-1,0
  3967.3    0.05       0  4886.9    0.12       0  5024.6    0.07       0
  5030.4    0.12       0  5798.2    0.05       0  5814.5    0.12       0
  6109.7    0.05       0
Bank Sta=5024.6,5030.4
Exp/Cntr=0.3,0.1

Type RM Length L Ch R = 1,2389,456,456,456
BEGIN DESCRIPTION:
Mapping XS 2efbcb79
END DESCRIPTION:
XS GIS Cut Line= 3
      2687767.93      6974864.18      2686899.87      6973874.60
      2685567.45      6973735.72
#Sta/Elev= 30
  3692.7  544.33  3930.2  541.13  4064.9  536.49  4234.8  527.59  4631.5  520.27
  4823.2  521.20  4886.8  517.53  4936.1  520.60  4962.6  520.18  4962.7  520.18
  4972.2  519.59  4975.8  515.44  4976.8  514.94  4981.8  515.44  4993.0  517.23
  5000.5  520.77  5076.8  520.77  5123.5  519.94  5153.7  522.80  5274.4  521.06
  5415.1  526.89  5505.6  528.15  5636.3  526.59  5686.6  528.55  5716.7  526.58
  5777.1  530.42  5887.7  529.17  5998.3  532.49  6263.9  535.88  6348.7  537.99
#Mann=7,-1,0
  3692.7    0.05       0  4962.6    0.12       0  4962.7    0.05       0
  4975.8    0.03       0  4981.8    0.05       0  5076.8    0.12       0
  6263.9    0.05       0
Bank Sta=4975.8,4981.8
Exp/Cntr=0.3,0.1

Type RM Length L Ch R = 1,1933,582,582,582
BEGIN DESCRIPTION:
Mapping XS 2dc2a7fe
END DESCRIPTION:
XS GIS Cut Line= 3
      2687918.08      6974179.28      2687133.38      6973533.46
      2685706.28      6973693.18
#Sta/Elev= 30
  3976.2  534.72  4069.4  534.29  4289.7  526.79  4459.0  522.88  4786.1  519.19
  4936.0  518.93  4977.7  515.75  4982.5  514.05  4983.5  513.55  4988.6  514.05
  4990.5  516.01  5015.2  519.31  5040.2  519.66  5478.9  520.51  5533.2  521.18
  5556.6  523.57  5573.5  522.08  5603.7  522.35  5641.8  525.54  5664.0  523.13
  5704.3  523.41  5724.4  526.06  5754.6  524.89  5822.2  526.95  5865.3  526.61
  5905.5  529.22  6056.5  529.93  6137.0  532.29  6287.9  532.50  6428.5  535.88
#Mann=4,-1,0
  3976.2    0.05       0  4982.5    0.03       0  4988.6    0.05       0
  5478.9    0.12       0
Bank Sta=4982.5,4988.6
Exp/Cntr=0.3,0.1

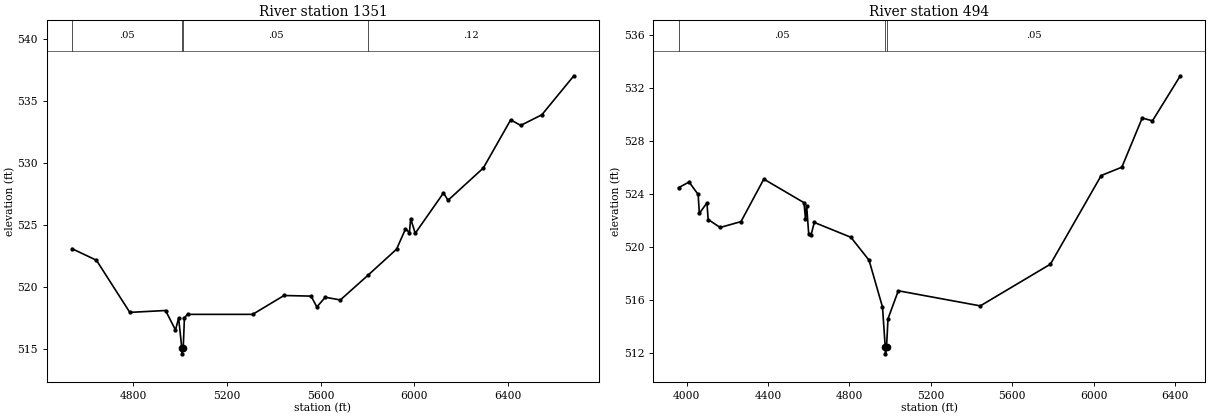
Type RM Length L Ch R = 1,1351,857,857,857
BEGIN DESCRIPTION:
Mapping XS cbb22191
END DESCRIPTION:
XS GIS Cut Line= 3
      2687628.18      6973047.35      2687187.20      6972964.01
      2685603.90      6973564.70
#Sta/Elev= 30
  4539.3  523.07  4643.3  522.14  4785.8  517.94  4938.4  518.09  4980.8  516.52
  4994.2  517.48  5007.6  515.10  5008.7  514.60  5013.9  515.10  5019.0  517.51
  5032.2  517.78  5310.2  517.78  5444.3  519.30  5559.5  519.25  5584.3  518.38
  5620.4  519.16  5684.6  518.94  5801.9  520.92  5924.6  523.03  5962.7  524.66
  5979.5  524.37  5984.9  525.49  6004.3  524.31  6124.9  527.56  6144.3  526.97
  6295.0  529.57  6411.9  533.45  6454.5  533.00  6544.9  533.86  6681.5  537.00
#Mann=4,-1,0
  4539.3    0.05       0  5007.6    0.04       0  5013.9    0.05       0
  5801.9    0.12       0
Bank Sta=5007.6,5013.9
Exp/Cntr=0.3,0.1

Type RM Length L Ch R = 1,494,0,0,0
BEGIN DESCRIPTION:
Muddy T15 1.0
END DESCRIPTION:
XS GIS Cut Line= 4
      2687600.99      6972935.99      2687201.00      6972236.00
      2686975.85      6972176.06      2685560.05      6972339.43
#Sta/Elev= 30
  3960.8  524.49  4012.6  524.92  4057.2  523.98  4063.0  522.55  4100.4  523.35
  4106.2  522.09  4165.2  521.49  4267.4  521.93  4379.7  525.14  4577.0  523.36
  4584.2  522.16  4589.9  523.14  4600.0  521.02  4611.5  520.90  4627.4  521.87
  4807.1  520.75  4896.4  519.02  4962.5  515.48  4976.0  512.45  4977.0  511.95
  4982.3  512.45  4989.5  514.60  5040.1  516.71  5442.8  515.57  5787.3  518.72
  6036.7  525.41  6138.0  526.04  6238.0  529.75  6288.3  529.54  6425.2  532.94
#Mann=3,-1,0
  3960.8    0.05       0  4976.0    0.04       0  4982.3    0.05       0
Bank Sta=4976,4982.3
Exp/Cntr=0.3,0.1

Chan Stop Cuts=-1