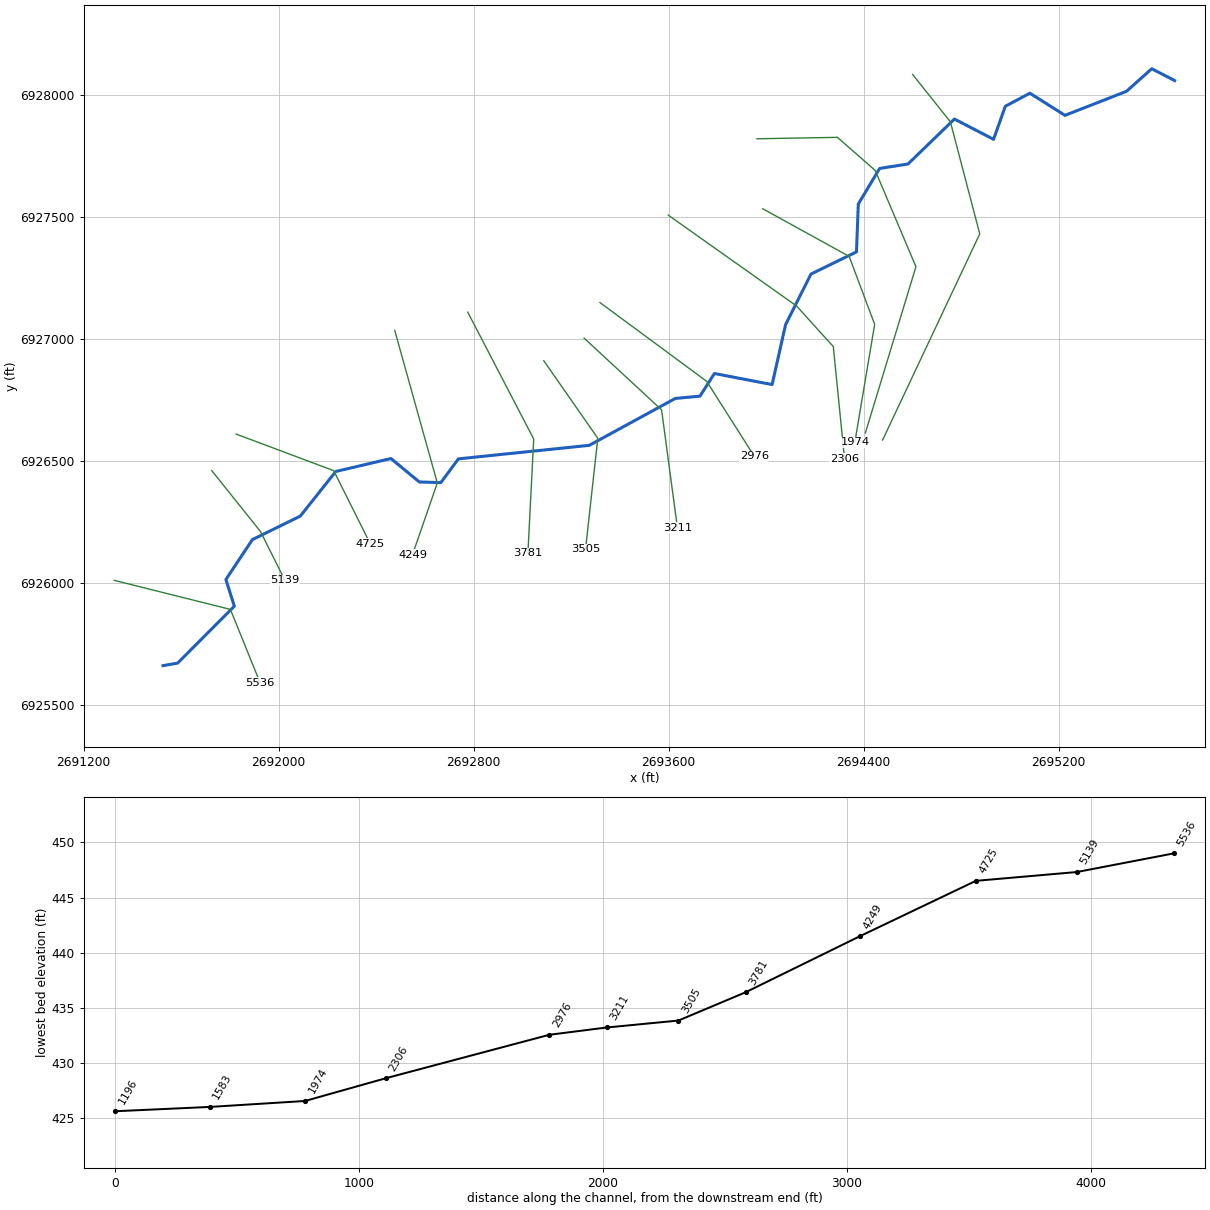
--- Muddy T2.prj (project) ---

Proj Title=Muddy T2 Base Level Engineering
Current Plan=p01
Default Exp/Contr=0.3,0.1
English Units
Geom File=g01
Flow File=f01
Plan File=p01
Y Axis Title=Elevation
X Axis Title(PF)=Main Channel Distance
X Axis Title(XS)=Station
BEGIN DESCRIPTION:
Muddy T2
END DESCRIPTION:
DSS Export Rating Curves= 0
DSS Export Rating Curve Sorted= 0
DSS Export Volume Flow Curves= 0
DXF OffsetX= 0
DXF OffsetY= 0
DXF ScaleX= 1
DXF ScaleY= 10

--- Muddy T2.p01 (plan) ---

Plan Title=Multiple Run
Short Identifier=Multiple
Geom File=g01
Flow File=f01
Subcritical Flow
K Sum by GR= 0
Std Step Tol= 0.01
Critical Tol= 0.01
Num of Std Step Trials= 20
Max Error Tol= 0.3
Flow Tol Ratio= 0.001
Split Flow NTrial= 30
Split Flow Tol= 0.02
Split Flow Ratio= 0.02
Log Output Level= 0
Friction Slope Method= 1
Unsteady Friction Slope Method= 2
Unsteady Bridges Friction Slope Method= 1
Parabolic Critical Depth
Global Vel Dist=  1 , 1 , 1
Global Log Level= 0
CheckData=True
Encroach Param= -1, 0, 0, 0
BEGIN DESCRIPTION:
Multiple Run
END DESCRIPTION:

--- Muddy T2.f01 (steady flow) ---

Flow Title=Multiple
Number of Profiles=7
Profile Names=10-year,25-year,50-year,1pct_min,100-year,1pct_plu,500-year
River Rch & RM= Muddy T2,Reach-1,5536
     741    1015    1242     755    1506    3006    2212
River Rch & RM= Muddy T2,Reach-1,3781
     885    1220    1499     914    1824    3638    2696
Boundary for River Rch & Prof#=Muddy T2,Reach-1,1
Up Type=0
Dn Type=3
Dn Slope=0.005
Boundary for River Rch & Prof#=Muddy T2,Reach-1,2
Up Type=0
Dn Type=3
Dn Slope=0.005
Boundary for River Rch & Prof#=Muddy T2,Reach-1,3
Up Type=0
Dn Type=3
Dn Slope=0.005
Boundary for River Rch & Prof#=Muddy T2,Reach-1,4
Up Type=0
Dn Type=3
Dn Slope=0.005
Boundary for River Rch & Prof#=Muddy T2,Reach-1,5
Up Type=0
Dn Type=3
Dn Slope=0.005
Boundary for River Rch & Prof#=Muddy T2,Reach-1,6
Up Type=0
Dn Type=3
Dn Slope=0.005
Boundary for River Rch & Prof#=Muddy T2,Reach-1,7
Up Type=0
Dn Type=3
Dn Slope=0.005

--- Muddy T2.g01 (geometry) ---

Geom Title=Existing Conditions
Program Version=4.10

River Reach=Muddy T2        ,Reach-1
Reach XY= 30
        2691526.        6925661.      2691585.79      6925671.51
       2691818.5      6925904.95      2691783.83       6926014.4
      2691892.49      6926178.05      2692089.22      6926274.62
      2692234.48      6926457.49      2692460.83      6926510.63
       2692577.5      6926414.47      2692665.66      6926411.89
      2692737.83      6926509.35      2693274.45      6926564.75
      2693627.59      6926757.17      2693728.66      6926766.46
      2693787.84      6926859.37      2694024.61      6926814.03
      2694079.75      6927059.45      2694184.01      6927267.38
      2694370.66      6927358.26      2694378.24      6927555.07
      2694465.89      6927700.61      2694582.17      6927718.86
      2694772.59      6927903.23      2694933.06      6927819.98
      2694981.25      6927955.56       2695082.1      6928009.25
       2695225.9      6927918.33      2695478.29      6928016.85
      2695581.97      6928109.45        2695676.        6928061.

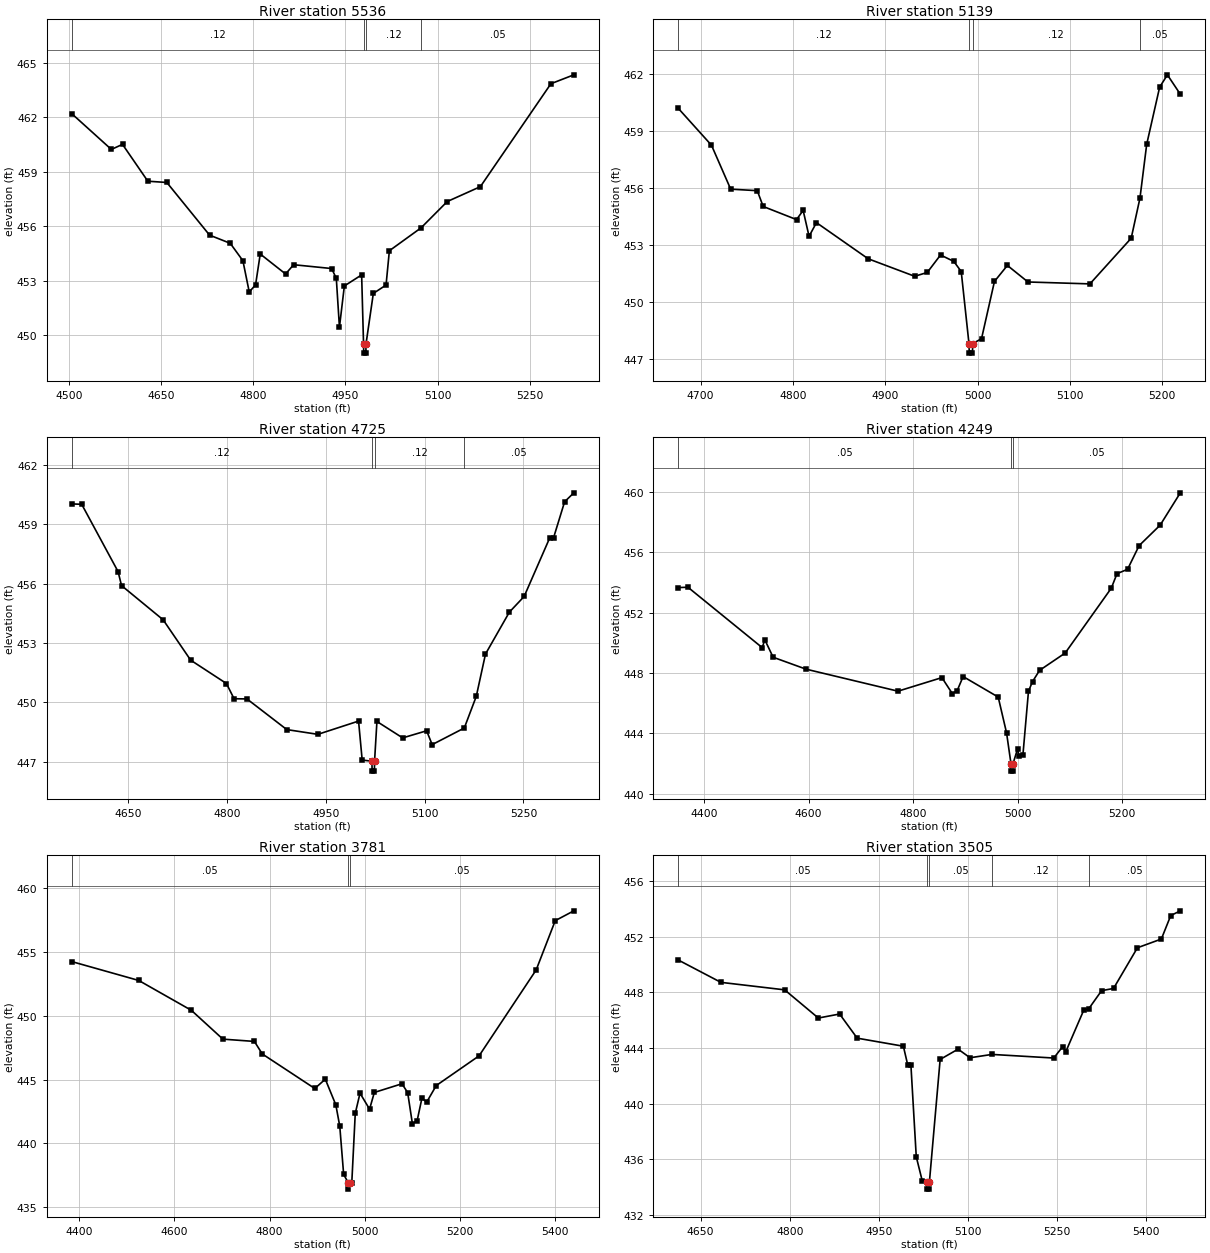
Type RM Length L Ch R = 1 ,5536    ,397,397,397
BEGIN DESCRIPTION:
Muddy T2 9.0
END DESCRIPTION:
XS GIS Cut Line= 3
        2691326.        6926011.      2691802.37      6925891.79
      2691924.45      6925590.12
#Sta/Elev= 30
    4505   462.2  4569.4  460.23  4587.5  460.51  4628.7  458.48  4659.6  458.41
  4729.1  455.51  4762.7  455.06  4783.3   454.1  4793.6  452.38  4803.9  452.77
  4811.5  454.47  4852.7  453.37  4865.8  453.88  4927.6  453.67  4935.2  453.13
  4940.3  450.44  4948.3  452.71  4976.4  453.32  4979.5  449.51  4979.8  449.01
  4983.3  449.01  4983.5  449.51  4995.4   452.3  5016.1  452.76  5021.5  454.65
    5073  455.91  5115.6  457.36  5169.5  458.18  5284.2  463.85  5321.5  464.34
#Mann= 4 ,-1 , 0
    4505     .12       0  4979.5     .07       0  4983.5     .12       0
    5073     .05       0
Bank Sta=4979.5,4983.5
XS Rating Curve= 0 ,0
Exp/Cntr=0.3,0.1

Type RM Length L Ch R = 1 ,5139    ,414,414,414
BEGIN DESCRIPTION:
Muddy T2 8.0
END DESCRIPTION:
XS GIS Cut Line= 3
      2691726.01      6926460.99        2691926.        6926211.
      2692026.02      6926010.96
#Sta/Elev= 30
  4675.7  460.19  4711.7  458.25  4732.5  455.94  4761.3  455.86  4767.7  455.03
  4803.8  454.34    4811  454.82  4817.4  453.46  4825.4  454.18  4881.4  452.28
  4931.8  451.36  4945.4  451.56  4959.8  452.48  4974.2  452.14  4982.2  451.61
  4990.6  447.82  4990.9  447.32  4994.4  447.32  4994.6  447.82  5004.2  448.08
  5018.2  451.09  5032.2  451.93  5054.5  451.06  5121.6  450.96  5166.3  453.36
  5175.8  455.47  5183.1   458.3  5197.1   461.3  5205.5  461.95  5219.5  460.93
#Mann= 4 ,-1 , 0
  4675.7     .12       0  4990.6     .07       0  4994.6     .12       0
  5175.8     .05       0
Bank Sta=4990.6,4994.6
XS Rating Curve= 0 ,0
Exp/Cntr=0.3,0.1

Type RM Length L Ch R = 1 ,4725    ,476,476,476
BEGIN DESCRIPTION:
Muddy T2 7.0
END DESCRIPTION:
XS GIS Cut Line= 3
      2691826.03      6926610.99        2692226.        6926461.
      2692376.01      6926160.98
#Sta/Elev= 30
    4564  460.03  4579.1  460.01  4634.3  456.61  4639.6   455.9  4702.8  454.17
  4744.6  452.13  4798.9  450.95  4810.5  450.18  4830.1  450.17  4890.6  448.62
  4937.8  448.38  4999.6  449.05  5005.1  447.08  5019.9  447.02  5020.2  446.52
  5023.7  446.52  5023.9  447.02  5027.5  449.03  5066.6   448.2    5103  448.56
  5111.4  447.86  5160.2   448.7  5178.4   450.3  5192.4  452.44  5228.7  454.56
  5251.1  455.35  5290.2  458.33  5295.8  458.32  5312.6  460.14  5326.6  460.59
#Mann= 4 ,-1 , 0
    4564     .12       0  5019.9     .07       0  5023.9     .12       0
  5160.2     .05       0
Bank Sta=5019.9,5023.9
XS Rating Curve= 0 ,0
Exp/Cntr=0.3,0.1

Type RM Length L Ch R = 1 ,4249    ,468,468,468
BEGIN DESCRIPTION:
Muddy T2 6.0
END DESCRIPTION:
XS GIS Cut Line= 3
      2692476.54      6927035.86      2692651.12      6926410.47
      2692549.45      6926116.55
#Sta/Elev= 30
  4350.7  453.66  4369.3  453.68  4511.2  449.68  4516.4  450.19  4532.2  449.04
  4595.1  448.25    4771  446.79    4855  447.69  4874.9  446.63    4884  446.81
  4895.6  447.76  4962.7   446.4  4978.7  444.02  4987.1  441.99  4987.3  441.49
  4990.8  441.49  4991.1  441.99  4999.8  442.97  5002.5  442.47    5010  442.58
  5020.6  446.79  5028.4  447.43  5041.8  448.17  5090.8  449.32    5179  453.62
  5189.9  454.58  5210.1  454.87  5232.2  456.44  5272.5   457.8    5311  459.94
#Mann= 3 ,-1 , 0
  4350.7     .05       0  4987.1     .04       0  4991.1     .05       0
Bank Sta=4987.1,4991.1
XS Rating Curve= 0 ,0
Exp/Cntr=0.3,0.1

Type RM Length L Ch R = 1 ,3781    ,276,276,276
BEGIN DESCRIPTION:
Muddy T2 5.0
END DESCRIPTION:
XS GIS Cut Line= 3
      2692775.98      6927111.04      2693046.64      6926590.67
      2693022.77      6926121.93
#Sta/Elev= 30
    4384  454.25  4524.9  452.77  4635.5  450.43  4701.8  448.17  4768.1  447.99
  4784.6  447.01  4895.1   444.3  4917.2  445.03  4939.3  443.02  4947.6  441.35
  4955.8  437.56  4965.5  436.91  4965.8  436.41  4969.5  436.91  4972.9  436.91
  4980.2  442.35  4990.2  443.93  5010.3  442.68  5020.3  443.99  5078.4  444.67
  5090.4  443.98  5100.4  441.53  5110.4  441.79  5120.4  443.54  5130.4  443.23
  5150.5  444.53  5240.6  446.86  5360.7   453.6  5400.8  457.46  5439.9  458.23
#Mann= 3 ,-1 , 0
    4384     .05       0  4965.5     .04       0  4969.5     .05       0
Bank Sta=4965.5,4969.5
XS Rating Curve= 0 ,0
Exp/Cntr=0.3,0.1

Type RM Length L Ch R = 1 ,3505    ,294,294,294
BEGIN DESCRIPTION:
Muddy T2 4.0
END DESCRIPTION:
XS GIS Cut Line= 3
      2693087.87      6926911.86      2693309.52      6926593.89
      2693259.31      6926139.26
#Sta/Elev= 30
  4612.4  450.34  4684.2  448.73  4791.5  448.19  4848.2  446.16    4884  446.45
  4913.6  444.71  4991.3  444.13  4998.7  442.77    5004  442.77    5013  436.17
    5023  434.45  5031.1  434.34  5031.3  433.84  5034.8  433.84  5035.1  434.34
  5053.2  443.18  5083.4  443.92  5103.5   443.3  5140.4  443.54  5244.4  443.28
  5259.6  444.11  5264.7  443.74  5294.7  446.71  5303.5  446.84  5324.9  448.13
    5345  448.29  5385.2  451.22  5425.5  451.85  5441.3  453.54  5457.4  453.88
#Mann= 5 ,-1 , 0
  4612.4     .05       0  5031.1     .04       0  5035.1     .05       0
  5140.4     .12       0  5303.5     .05       0
Bank Sta=5031.1,5035.1
XS Rating Curve= 0 ,0
Exp/Cntr=0.3,0.1

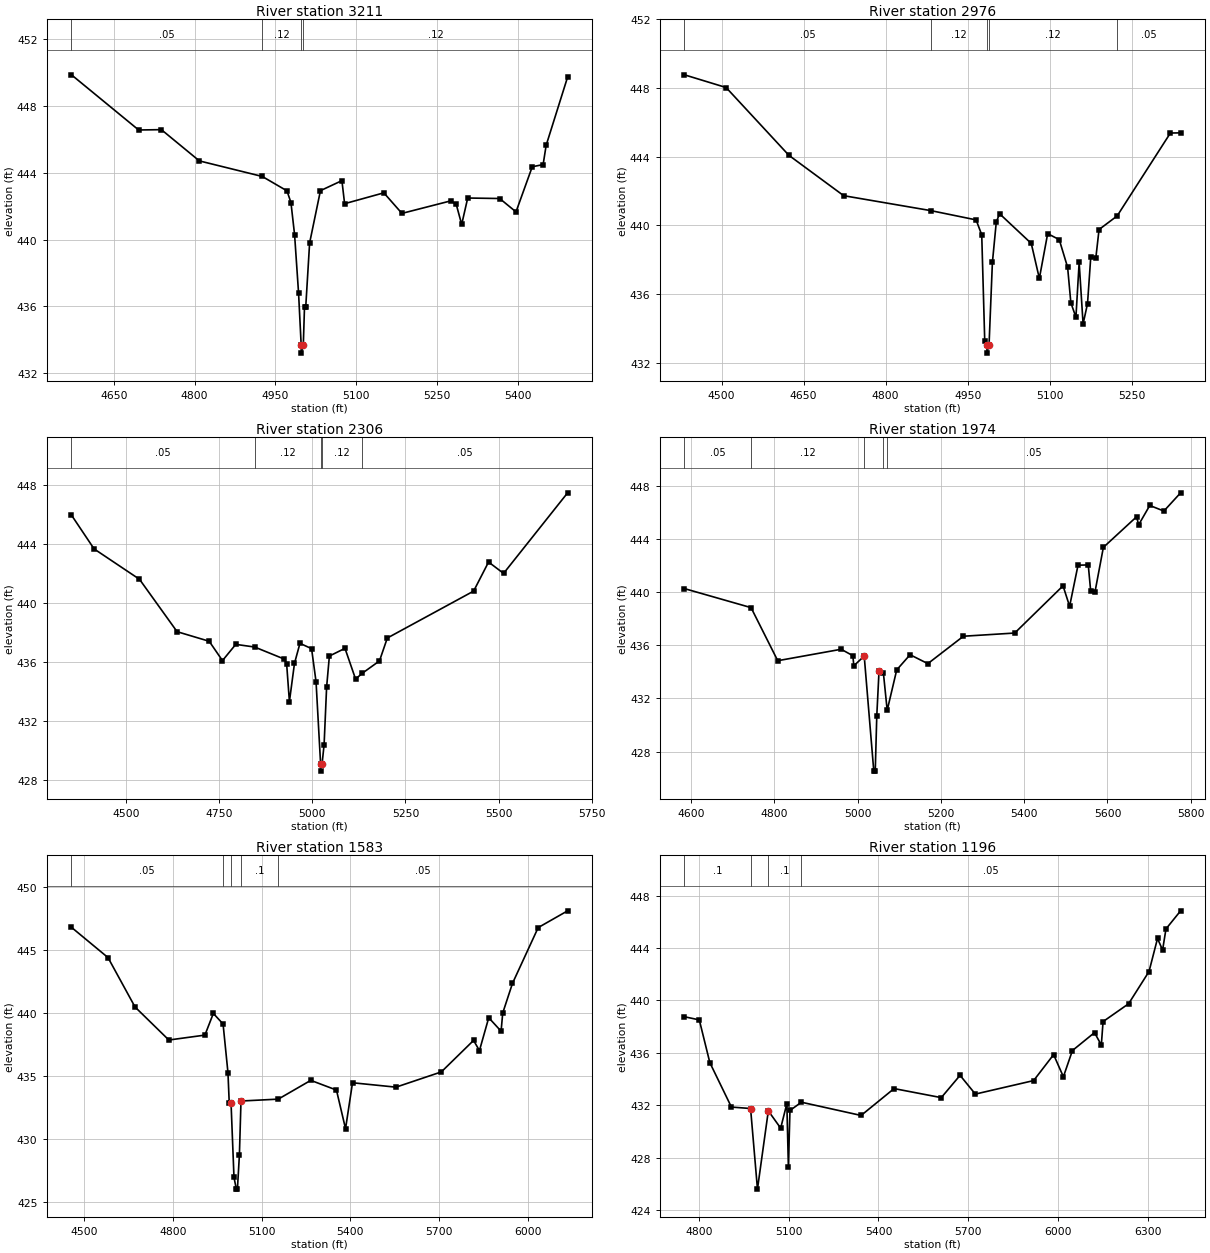
Type RM Length L Ch R = 1 ,3211    ,235,235,235
BEGIN DESCRIPTION:
Mapping XS f76e53b6
END DESCRIPTION:
XS GIS Cut Line= 3
      2693253.47       6927004.5      2693571.16      6926710.25
      2693636.26      6926225.93
#Sta/Elev= 30
  4571.4  449.86  4696.2  446.56  4738.4  446.58    4809  444.71  4925.8  443.78
  4971.7  442.92  4979.1  442.22  4985.9  440.29  4993.3  436.79  4998.1  433.71
  4998.3  433.21  5002.1  433.71  5004.3  435.97  5006.6  435.97  5013.8   439.8
  5033.9  442.93  5073.8  443.53  5078.8  442.15  5151.7   442.8  5185.3  441.57
  5276.1  442.32  5286.2  442.11  5296.3  440.91  5307.5  442.49  5366.9  442.46
  5397.2  441.66  5427.4  444.36  5447.6  444.49  5453.2  445.64  5493.1  449.73
#Mann= 4 ,-1 , 0
  4571.4     .05       0  4925.8     .12       0  4998.1     .07       0
  5002.1     .12       0
Bank Sta=4998.1,5002.1
XS Rating Curve= 0 ,0
Exp/Cntr=0.3,0.1

Type RM Length L Ch R = 1 ,2976    ,670,670,670
BEGIN DESCRIPTION:
Mapping XS a4ad0a8e
END DESCRIPTION:
XS GIS Cut Line= 3
      2693318.52      6927150.38      2693756.06      6926827.44
       2693951.2      6926520.41
#Sta/Elev= 30
    4432  448.76  4508.2  448.02  4623.1  444.07  4723.3  441.72  4882.8  440.85
  4965.5  440.31  4975.8  439.44  4981.3  433.25  4985.2  433.05  4985.4  432.55
  4989.2  433.05  4995.3  437.83  5002.4  440.18  5008.4  440.67  5066.4  438.94
  5081.2   436.9  5096.4  439.51  5117.6  439.16  5132.9  437.55  5138.8  435.49
  5148.1  434.64    5154  437.83  5161.2  434.25  5169.3  435.43  5175.2  438.13
  5184.5  438.09  5190.4  439.75  5223.5  440.54  5320.9  445.37  5339.6  445.38
#Mann= 5 ,-1 , 0
    4432     .05       0  4882.8     .12       0  4985.2     .07       0
  4989.2     .12       0  5223.5     .05       0
Bank Sta=4985.2,4989.2
XS Rating Curve= 0 ,0
Exp/Cntr=0.3,0.1

Type RM Length L Ch R = 1 ,2306    ,332,332,332
BEGIN DESCRIPTION:
Mapping XS e12da935
END DESCRIPTION:
XS GIS Cut Line= 4
      2693598.54      6927509.05      2694124.55      6927136.68
      2694275.59      6926970.02      2694321.63      6926509.91
#Sta/Elev= 30
  4353.5  445.96  4414.2  443.67  4536.1  441.61    4637  438.06  4723.2  437.41
  4758.8   436.1  4794.5   437.2  4845.2  437.02    4925   436.2  4931.1  435.87
  4938.5  433.32  4952.1  435.91  4966.8  437.27    4998  436.91    5010  434.67
  5022.2  429.11  5022.4  428.61  5026.2  429.11  5031.6  430.39  5038.4  434.31
  5045.8  436.41  5087.7  436.93  5116.1  434.85  5134.5  435.25  5180.3  436.08
  5201.3  437.63    5433  440.81  5473.1  442.78  5513.4  442.01  5685.3  447.47
#Mann= 5 ,-1 , 0
  4353.5     .05       0  4845.2     .12       0  5022.2     .07       0
  5026.2     .12       0  5134.5     .05       0
Bank Sta=5022.2,5026.2
XS Rating Curve= 0 ,0
Exp/Cntr=0.3,0.1

Type RM Length L Ch R = 1 ,1974    ,391,391,391
BEGIN DESCRIPTION:
Mapping XS c438cbe5
END DESCRIPTION:
XS GIS Cut Line= 4
      2693986.48      6927535.14      2694340.69      6927339.81
      2694445.28      6927060.92      2694364.07      6926577.95
#Sta/Elev= 30
  4583.7  440.26  4743.7  438.83  4807.8  434.84  4960.2   435.7  4988.2  435.22
  4990.7  434.46  5015.6  435.19  5038.6  426.54  5042.1  426.54  5045.8  430.71
  5051.2  434.08  5061.7  433.91  5070.8  431.11  5093.7  434.15  5125.8  435.29
  5168.5  434.62  5253.9  436.68  5377.2  436.92  5493.3  440.47  5509.1  438.93
  5529.3  442.02  5553.9  442.04  5559.8  440.05  5569.9  439.98  5590.2  443.36
    5670  445.66    5675  445.06  5701.7  446.51  5735.6  446.09  5775.8  447.46
#Mann= 5 ,-1 , 0
  4583.7     .05       0  4743.7     .12       0  5015.6     .07       0
  5061.7     .12       0  5070.8     .05       0
Bank Sta=5015.6,5051.2
XS Rating Curve= 0 ,0
Exp/Cntr=0.3,0.1

Type RM Length L Ch R = 1 ,1583    ,387,387,387
BEGIN DESCRIPTION:
Mapping XS 842fdfa2
END DESCRIPTION:
XS GIS Cut Line= 5
      2693962.54      6927822.25      2694292.44       6927828.1
      2694447.46      6927692.45      2694614.61      6927297.38
      2694407.22      6926615.86
#Sta/Elev= 30
  4457.3  446.77  4580.8  444.37  4672.2  440.45  4786.5  437.83  4908.4  438.22
  4936.9  439.94  4969.8   439.1  4986.3  435.25  4990.6  432.86  4996.7  432.86
  5006.7  426.93  5014.7     426  5018.3     426    5025  428.71  5030.4  432.99
  5156.4  433.14  5266.3  434.63  5353.1  433.86  5383.8  430.79  5407.4  434.44
  5554.3  434.09  5707.7   435.3  5816.7   437.8  5836.5  436.99  5867.9   439.6
  5909.7  438.53  5915.2  439.97  5948.1  442.32  6035.1  446.75  6134.6  448.08
#Mann= 5 ,-1 , 0
  4457.3     .05       0  4969.8      .1       0  4996.7     .05       0
  5030.4      .1       0  5156.4     .05       0
Bank Sta=4996.7,5030.4
XS Rating Curve= 0 ,0
Exp/Cntr=0.3,0.1

Type RM Length L Ch R = 1 ,1196    ,0,0,0
BEGIN DESCRIPTION:
Mapping XS 8e8cf7f4
END DESCRIPTION:
XS GIS Cut Line= 4
      2694601.01      6928085.99      2694755.97      6927891.72
       2694876.4      6927431.92      2694477.86      6926586.57
#Sta/Elev= 30
  4751.5  438.76  4801.1  438.52  4836.3  435.26  4908.4  431.87  4972.5  431.76
  4995.5  425.61  5031.8  431.58  5073.1  430.26  5093.7  432.13  5098.9   427.3
  5104.1  431.61  5142.4  432.24  5341.9  431.23  5452.2  433.28  5609.9  432.59
  5672.7  434.29  5723.8  432.86  5918.6  433.89  5985.4  435.87  6018.1  434.18
  6048.2  436.18  6122.1  437.55  6144.9   436.6  6150.7  438.39    6236  439.75
  6304.3  442.21  6332.7  444.73  6349.7  443.85    6361  445.46  6409.9  446.84
#Mann= 4 ,-1 , 0
  4751.5      .1       0  4972.5     .05       0  5031.8      .1       0
  5142.4     .05       0
Bank Sta=4972.5,5031.8
XS Rating Curve= 0 ,0
Exp/Cntr=0.3,0.1

Chan Stop Cuts=-1
Use User Specified Reach Order=0
Composite Channel Slope=5