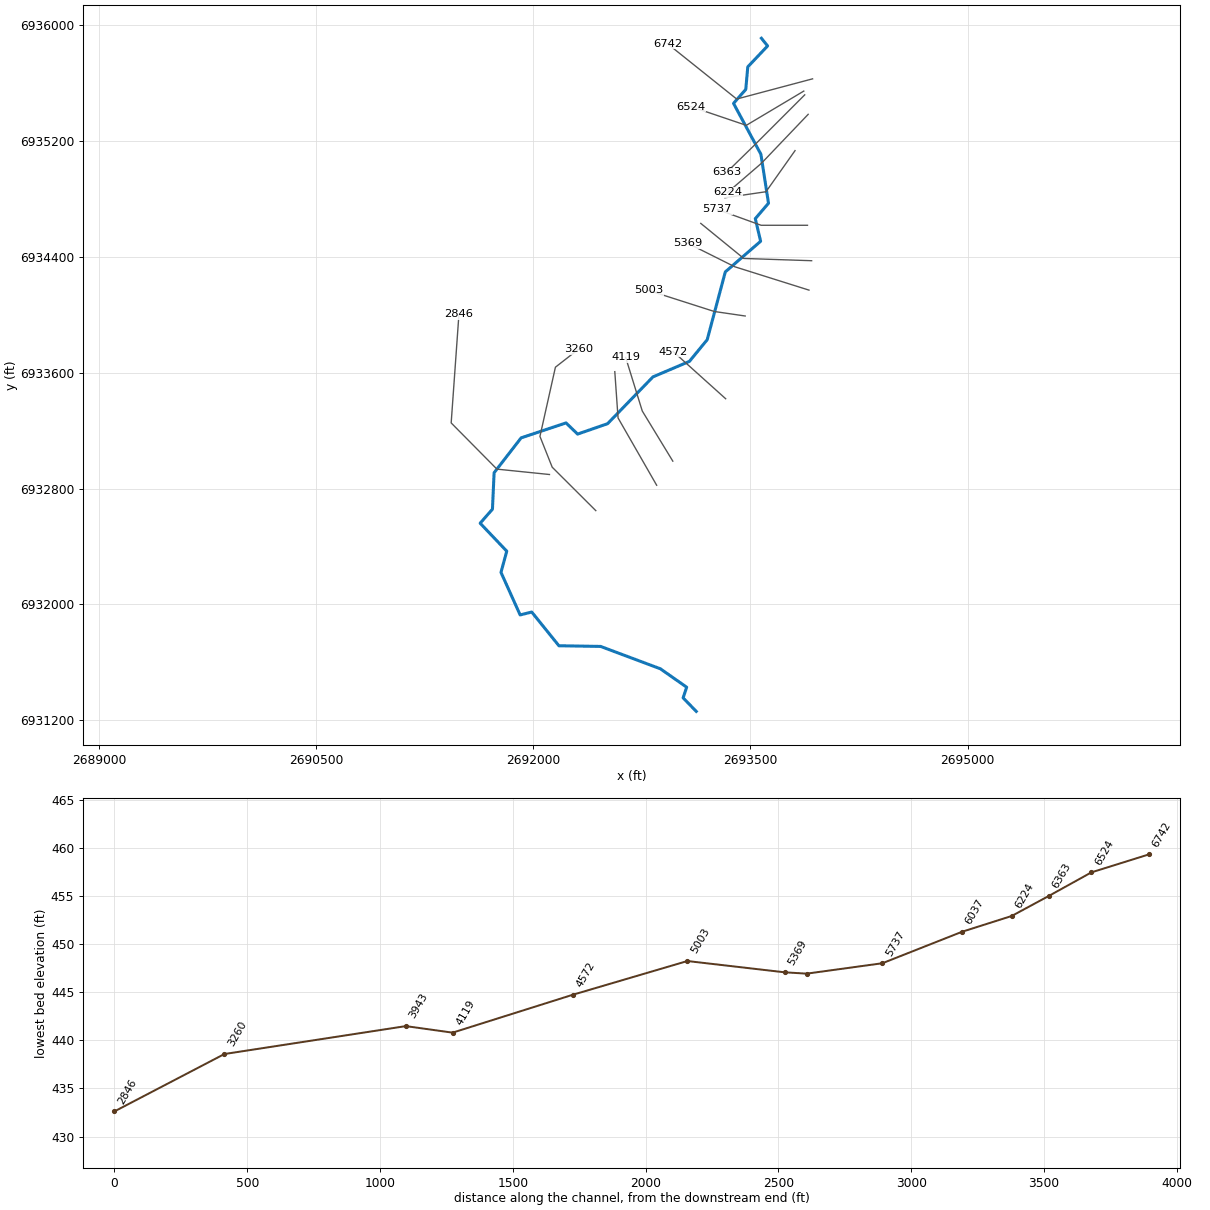
--- Muddy T3.prj (project) ---

Proj Title=Muddy T3 Base Level Engineering
Current Plan=p01
Default Exp/Contr=0.3,0.1
English Units
Geom File=g01
Flow File=f01
Plan File=p01
BEGIN DESCRIPTION:
Muddy T3
END DESCRIPTION:

--- Muddy T3.p01 (plan) ---

Plan Title=Multiple Run
Short Identifier=Multiple
Geom File=g01
Flow File=f01
Subcritical Flow
K Sum by GR= 0
Std Step Tol= 0.01
Critical Tol= 0.01
Num of Std Step Trials= 20
Max Error Tol= 0.3
Flow Tol Ratio= 0.001
Split Flow NTrial= 30
Split Flow Tol= 0.02
Split Flow Ratio= 0.02
Log Output Level= 0
Friction Slope Method= 1
Unsteady Friction Slope Method= 2
Unsteady Bridges Friction Slope Method= 1
Parabolic Critical Depth
Global Vel Dist=  1 , 1 , 1
Global Log Level= 0
CheckData=True
Encroach Param= -1, 0, 0, 0
BEGIN DESCRIPTION:
Multiple Run
END DESCRIPTION:

--- Muddy T3.f01 (steady flow) ---

Flow Title=Multiple
Number of Profiles=7
Profile Names=10-year,25-year,50-year,1pct_min,100-year,1pct_plu,500-year
River Rch & RM= Muddy T3,Reach-1,6742
     545     727     874     522    1042    2079    1478
River Rch & RM= Muddy T3,Reach-1,6037
     631     849    1026     615    1227    2448    1754
Boundary for River Rch & Prof#=Muddy T3,Reach-1,1
Up Type=0
Dn Type=3
Dn Slope=0.005
Boundary for River Rch & Prof#=Muddy T3,Reach-1,2
Up Type=0
Dn Type=3
Dn Slope=0.005
Boundary for River Rch & Prof#=Muddy T3,Reach-1,3
Up Type=0
Dn Type=3
Dn Slope=0.005
Boundary for River Rch & Prof#=Muddy T3,Reach-1,4
Up Type=0
Dn Type=3
Dn Slope=0.005
Boundary for River Rch & Prof#=Muddy T3,Reach-1,5
Up Type=0
Dn Type=3
Dn Slope=0.005
Boundary for River Rch & Prof#=Muddy T3,Reach-1,6
Up Type=0
Dn Type=3
Dn Slope=0.005
Boundary for River Rch & Prof#=Muddy T3,Reach-1,7
Up Type=0
Dn Type=3
Dn Slope=0.005

--- Muddy T3.g01 (geometry) ---

Geom Title=Existing Conditions

River Reach=Muddy T3,Reach-1
Reach XY= 30
      2693576.00      6935911.00      2693618.75      6935857.67
      2693481.81      6935713.29      2693467.98      6935557.66
      2693383.31      6935461.09      2693572.44      6935109.53
      2693624.95      6934771.44      2693533.81      6934664.41
      2693570.60      6934508.57      2693326.59      6934296.98
      2693201.60      6933828.77      2693078.63      6933678.82
      2692826.53      6933571.43      2692513.34      6933248.37
      2692306.22      6933176.62      2692226.30      6933253.80
      2691916.18      6933150.53      2691729.55      6932909.53
      2691717.98      6932657.66      2691633.09      6932561.00
      2691816.87      6932367.74      2691776.95      6932221.48
      2691909.29      6931927.38      2691989.33      6931947.35
      2692177.25      6931714.45      2692465.50      6931709.80
      2692878.29      6931555.16      2693059.77      6931428.04
      2693035.18      6931354.34      2693126.00      6931261.00

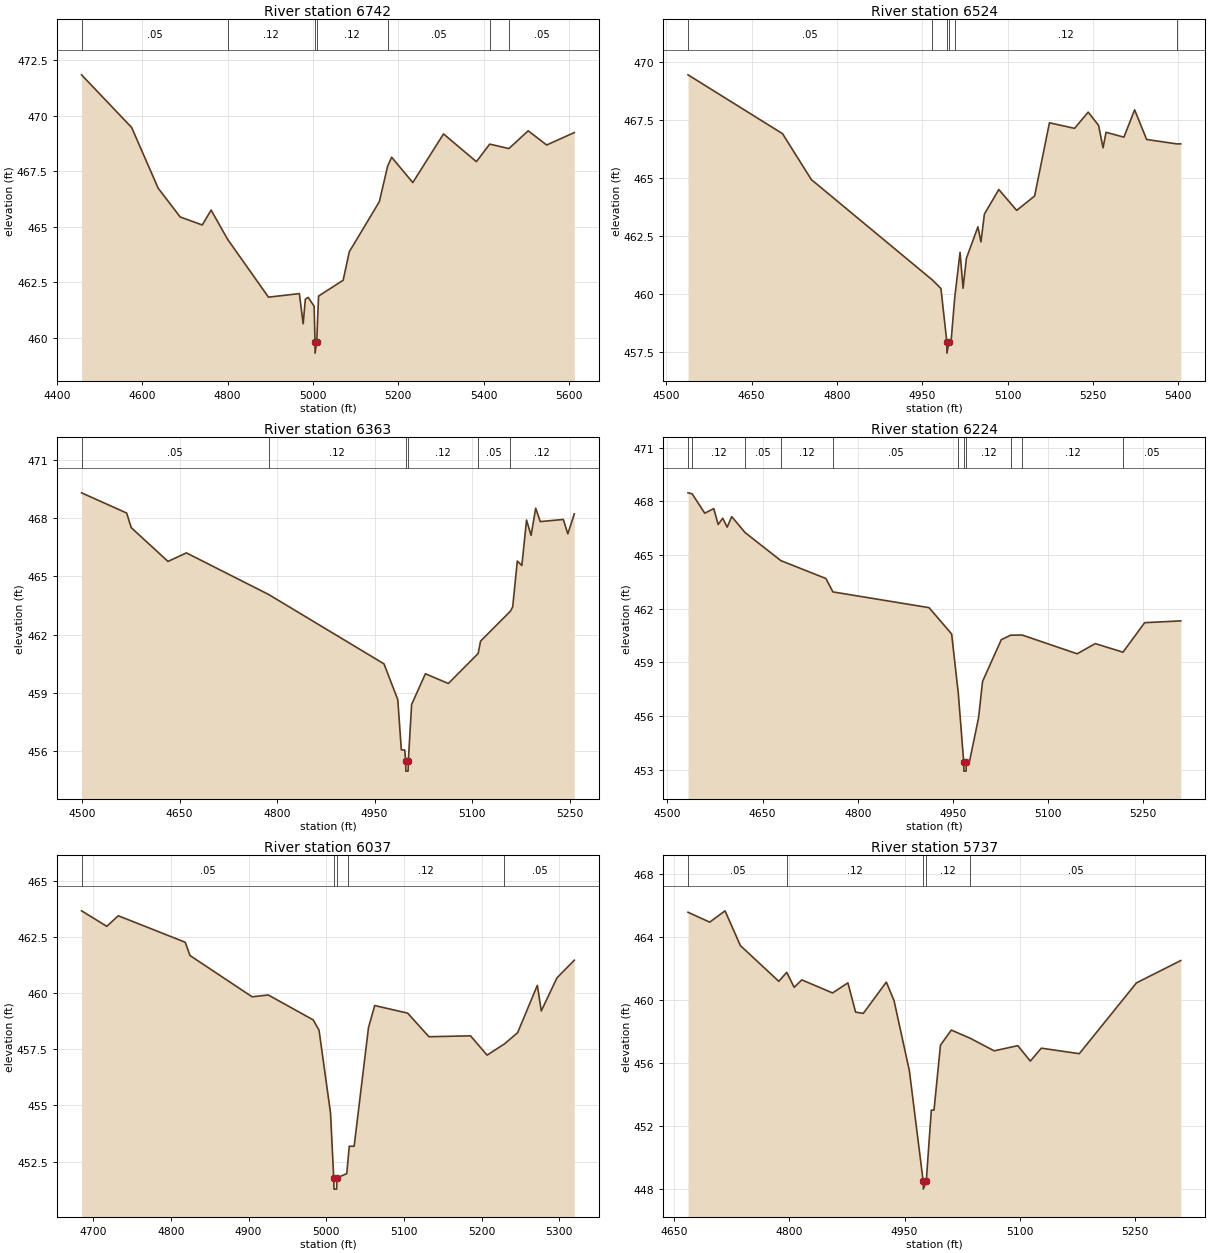
Type RM Length L Ch R = 1,6742,218,218,218
BEGIN DESCRIPTION:
Muddy T3 7.0
END DESCRIPTION:
XS GIS Cut Line= 3
      2693929.45      6935630.58      2693405.21      6935491.02
      2692926.81      6935873.65
#Sta/Elev= 30
  4457.5  471.85  4574.9  469.48  4637.0  466.75  4688.7  465.45  4740.5  465.09
  4761.2  465.76  4799.7  464.45  4895.7  461.84  4968.1  462.00  4977.0  460.64
  4982.1  461.75  4988.8  461.83  5002.7  461.43  5004.7  459.82  5004.9  459.32
  5008.7  459.82  5013.1  461.89  5070.7  462.60  5085.1  463.88  5155.6  466.14
  5175.0  467.74  5184.4  468.14  5234.0  467.00  5306.0  469.19  5383.1  467.94
  5414.2  468.73  5459.3  468.53  5504.5  469.33  5547.8  468.69  5612.6  469.25
#Mann=7,-1,0
  4457.5    0.05       0  4799.7    0.12       0  5004.7    0.07       0
  5008.7    0.12       0  5175.0    0.05       0  5414.2    0.12       0
  5459.3    0.05       0
Bank Sta=5004.7,5008.7
Exp/Cntr=0.3,0.1

Type RM Length L Ch R = 1,6524,161,161,161
BEGIN DESCRIPTION:
Mapping XS 542a71d4
END DESCRIPTION:
XS GIS Cut Line= 3
      2693868.70      6935545.96      2693471.53      6935309.39
      2693089.18      6935439.00
#Sta/Elev= 30
  4538.3  469.45  4704.4  466.91  4755.0  464.93  4967.6  460.60  4982.8  460.23
  4993.1  457.94  4993.3  457.44  4997.1  457.94  5000.6  457.94  5007.0  459.83
  5016.4  461.79  5021.7  460.24  5027.5  461.53  5047.8  462.89  5053.1  462.24
  5059.2  463.44  5084.5  464.50  5115.9  463.60  5147.4  464.22  5173.5  467.38
  5217.6  467.14  5241.6  467.84  5259.8  467.27  5267.7  466.30  5273.0  466.97
  5304.4  466.76  5323.2  467.94  5344.3  466.66  5397.1  466.47  5404.3  466.47
#Mann=6,-1,0
  4538.3    0.05       0  4967.6    0.12       0  4993.1    0.03       0
  4997.1    0.12       0  5007.0    0.12       0  5397.1    0.05       0
Bank Sta=4993.1,4997.1
Exp/Cntr=0.3,0.1

Type RM Length L Ch R = 1,6363,139,139,139
BEGIN DESCRIPTION:
Mapping XS 66d31080
END DESCRIPTION:
XS GIS Cut Line= 3
      2693875.18      6935519.90      2693523.62      6935168.34
      2693336.97      6934986.03
#Sta/Elev= 30
  4499.2  469.30  4568.6  468.26  4575.6  467.51  4632.2  465.77  4660.5  466.21
  4787.0  464.07  4964.5  460.50  4985.7  458.66  4991.2  456.07  4996.4  456.07
  4997.9  455.48  4998.1  454.98  5001.6  454.98  5001.9  455.48  5007.0  458.41
  5028.2  459.99  5063.5  459.49  5109.3  461.03  5113.1  461.67  5159.0  463.21
  5162.5  463.43  5169.6  465.79  5176.6  465.56  5183.8  467.90  5190.8  467.11
  5197.9  468.51  5204.9  467.82  5240.4  467.93  5247.3  467.19  5257.3  468.22
#Mann=6,-1,0
  4499.2    0.05       0  4787.0    0.12       0  4997.9    0.07       0
  5001.9    0.12       0  5109.3    0.05       0  5159.0    0.12       0
Bank Sta=4997.9,5001.9
Exp/Cntr=0.3,0.1

Type RM Length L Ch R = 1,6224,187,187,187
BEGIN DESCRIPTION:
Mapping XS bfa476d0
END DESCRIPTION:
XS GIS Cut Line= 3
      2693899.04      6935385.34      2693575.70      6935046.81
      2693341.88      6934845.46
#Sta/Elev= 30
  4532.5  468.47  4538.9  468.42  4558.9  467.33  4573.1  467.59  4580.0  466.70
  4587.2  467.05  4594.2  466.55  4601.4  467.14  4622.4  466.25  4678.8  464.68
  4749.8  463.68  4760.9  462.93  4912.4  462.05  4948.0  460.58  4958.5  457.27
  4967.1  453.41  4967.3  452.91  4970.8  452.91  4971.1  453.41  4976.3  453.47
  4990.4  455.88  4996.8  457.93  5026.3  460.26  5040.9  460.51  5059.1  460.52
  5145.9  459.47  5174.4  460.04  5218.1  459.56  5252.3  461.21  5309.2  461.31
#Mann=11,-1,0
  4532.5    0.05       0  4538.9    0.12       0  4622.4    0.05       0
  4678.8    0.12       0  4760.9    0.05       0  4958.5    0.12       0
  4967.1    0.07       0  4971.1    0.12       0  5040.9    0.05       0
  5059.1    0.12       0  5218.1    0.05       0
Bank Sta=4967.1,4971.1
Exp/Cntr=0.3,0.1

Type RM Length L Ch R = 1,6037,300,300,300
BEGIN DESCRIPTION:
Mapping XS e76fd8f9
END DESCRIPTION:
XS GIS Cut Line= 3
      2693808.25      6935134.65      2693607.71      6934850.77
      2693323.82      6934809.10
#Sta/Elev= 30
  4684.9  463.67  4717.4  462.98  4732.2  463.45  4818.4  462.27  4824.5  461.68
  4904.5  459.84  4925.4  459.92  4983.2  458.81  4990.7  458.35  5005.5  454.66
  5009.6  451.77  5009.9  451.27  5013.4  451.27  5013.6  451.77  5026.4  451.96
  5028.2  452.65  5029.6  453.18  5035.9  453.18  5054.4  458.47  5062.4  459.45
  5104.9  459.11  5132.2  458.06  5185.8  458.10  5207.1  457.24  5229.4  457.74
  5246.4  458.24  5271.8  460.35  5276.9  459.21  5297.0  460.68  5319.4  461.47
#Mann=5,-1,0
  4684.9    0.05       0  5009.6    0.04       0  5013.6    0.05       0
  5028.2    0.12       0  5229.4    0.05       0
Bank Sta=5009.6,5013.6
Exp/Cntr=0.3,0.1

Type RM Length L Ch R = 1,5737,285,285,285
BEGIN DESCRIPTION:
Mapping XS b530b78a
END DESCRIPTION:
XS GIS Cut Line= 3
      2693894.19      6934619.00      2693573.86      6934619.00
      2693271.78      6934728.37
#Sta/Elev= 30
  4668.1  465.60  4696.3  464.97  4716.3  465.69  4736.3  463.48  4786.3  461.21
  4796.6  461.78  4806.3  460.83  4816.3  461.30  4856.3  460.47  4876.3  461.11
  4886.3  459.25  4896.3  459.17  4926.3  461.16  4936.3  459.99  4956.3  455.53
  4974.3  448.50  4974.5  448.00  4978.3  448.50  4984.9  453.02  4988.4  453.02
  4996.8  457.15  5010.9  458.11  5035.1  457.60  5066.8  456.79  5097.5  457.12
  5113.8  456.14  5128.1  456.96  5177.6  456.61  5252.0  461.11  5309.7  462.53
#Mann=5,-1,0
  4668.1    0.05       0  4796.6    0.12       0  4974.3    0.07       0
  4978.3    0.12       0  5035.1    0.05       0
Bank Sta=4974.3,4978.3
Exp/Cntr=0.3,0.1

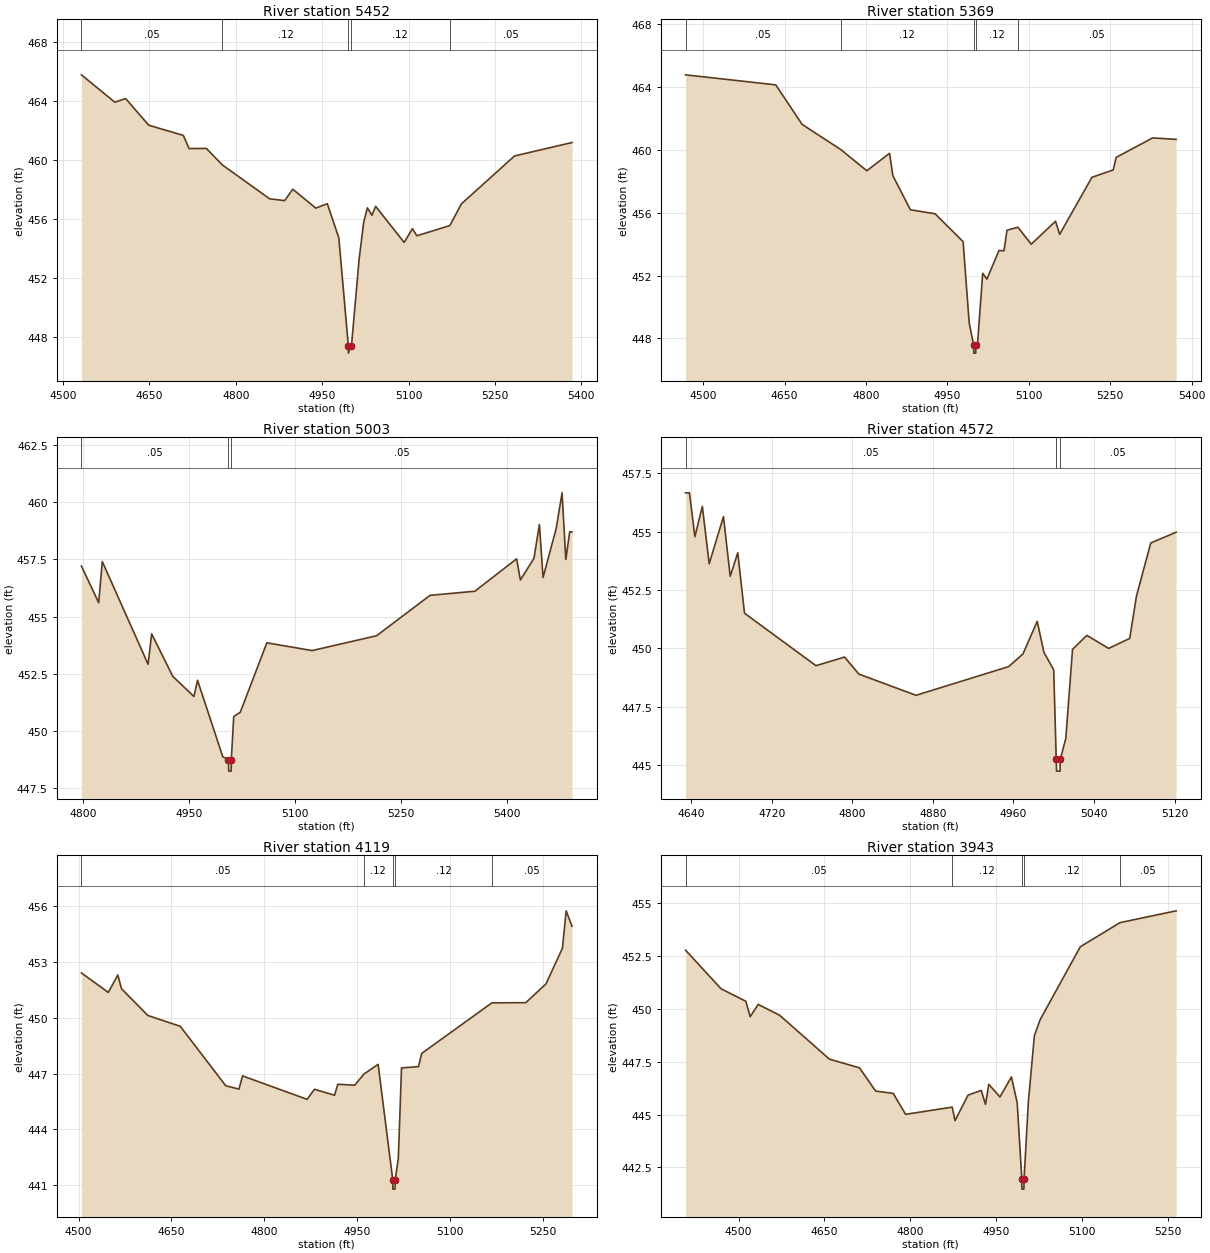
Type RM Length L Ch R = 1,5452,83,83,83
BEGIN DESCRIPTION:
Mapping XS e4fc4cef
END DESCRIPTION:
XS GIS Cut Line= 3
      2693922.86      6934374.21      2693454.06      6934389.83
      2693157.18      6934632.03
#Sta/Elev= 30
  4531.8  465.75  4589.7  463.90  4608.7  464.14  4648.7  462.34  4708.8  461.65
  4718.8  460.76  4748.8  460.77  4776.7  459.65  4858.8  457.36  4884.8  457.24
  4898.9  458.01  4938.9  456.73  4958.9  457.03  4978.9  454.72  4995.4  447.42
  4995.6  446.92  4999.4  447.42  5000.9  447.42  5014.2  453.29  5022.1  455.77
  5028.5  456.75  5036.4  456.25  5042.9  456.85  5092.4  454.41  5106.8  455.34
  5114.5  454.86  5171.7  455.55  5191.9  457.02  5284.1  460.26  5384.0  461.17
#Mann=5,-1,0
  4531.8    0.05       0  4776.7    0.12       0  4995.4    0.07       0
  4999.4    0.12       0  5171.7    0.05       0
Bank Sta=4995.4,4999.4
Exp/Cntr=0.3,0.1

Type RM Length L Ch R = 1,5369,366,366,366
BEGIN DESCRIPTION:
Mapping XS bd2096a7
END DESCRIPTION:
XS GIS Cut Line= 3
      2693904.63      6934171.07      2693391.56      6934332.54
      2693064.09      6934496.28
#Sta/Elev= 30
  4467.4  464.79  4633.7  464.15  4682.3  461.63  4753.5  460.03  4801.4  458.68
  4843.4  459.79  4849.4  458.37  4881.8  456.19  4927.2  455.94  4978.9  454.16
  4990.1  448.99  4998.3  447.56  4998.6  447.06  5002.1  447.06  5002.3  447.56
  5005.3  447.56  5015.0  452.15  5022.7  451.77  5045.0  453.60  5054.2  453.58
  5059.8  454.89  5079.9  455.08  5104.5  454.00  5149.2  455.46  5156.8  454.63
  5216.3  458.26  5255.4  458.73  5261.0  459.53  5328.1  460.77  5371.4  460.68
#Mann=5,-1,0
  4467.4    0.05       0  4753.5    0.12       0  4998.3    0.07       0
  5002.3    0.12       0  5079.9    0.05       0
Bank Sta=4998.3,5002.3
Exp/Cntr=0.3,0.1

Type RM Length L Ch R = 1,5003,431,431,431
BEGIN DESCRIPTION:
Mapping XS 5a207a9e
END DESCRIPTION:
XS GIS Cut Line= 3
      2693463.92      6933992.28      2693250.40      6934023.52
      2692794.66      6934169.36
#Sta/Elev= 30
  4798.1  457.21  4822.5  455.61  4827.6  457.41  4892.4  452.91  4897.5  454.24
  4927.4  452.38  4957.3  451.50  4962.4  452.21  4998.1  448.86  5006.2  448.73
  5006.5  448.23  5010.0  448.23  5010.2  448.73  5013.6  450.62  5022.9  450.81
  5060.5  453.85  5124.6  453.51  5215.8  454.16  5291.5  455.93  5354.9  456.11
  5414.0  457.53  5419.3  456.60  5438.5  457.55  5446.2  459.03  5451.4  456.71
  5470.0  458.86  5478.3  460.42  5483.6  457.50  5489.1  458.71  5492.4  458.71
#Mann=3,-1,0
  4798.1    0.05       0  5006.2    0.03       0  5010.2    0.05       0
Bank Sta=5006.2,5010.2
Exp/Cntr=0.3,0.1

Type RM Length L Ch R = 1,4572,453,453,453
BEGIN DESCRIPTION:
Mapping XS 5b5419ed
END DESCRIPTION:
XS GIS Cut Line= 3
      2693329.00      6933420.80      2693056.96      6933665.34
      2692966.72      6933746.85
#Sta/Elev= 30
  4634.2  456.66  4638.1  456.66  4643.5  454.78  4650.9  456.08  4657.7  453.62
  4671.9  455.64  4678.6  453.08  4686.1  454.09  4692.8  451.50  4763.8  449.25
  4792.2  449.62  4806.4  448.89  4863.2  447.98  4955.2  449.21  4969.4  449.75
  4983.6  451.15  4990.3  449.82  5000.0  449.07  5002.5  445.23  5002.8  444.73
  5006.3  444.73  5006.5  445.23  5012.0  446.13  5018.7  449.95  5032.9  450.55
  5054.6  449.99  5075.5  450.42  5082.2  452.23  5096.4  454.51  5121.6  454.97
#Mann=3,-1,0
  4634.2    0.05       0  5002.5    0.03       0  5006.5    0.05       0
Bank Sta=5002.5,5006.5
Exp/Cntr=0.3,0.1

Type RM Length L Ch R = 1,4119,176,176,176
BEGIN DESCRIPTION:
Mapping XS ed39f2ae
END DESCRIPTION:
XS GIS Cut Line= 3
      2692963.96      6932989.64      2692753.01      6933336.02
      2692638.42      6933705.81
#Sta/Elev= 30
  4504.6  452.42  4548.0  451.37  4563.4  452.31  4569.3  451.57  4611.9  450.13
  4664.2  449.55  4737.8  446.35  4759.1  446.17  4764.9  446.88  4869.2  445.62
  4881.1  446.16  4913.6  445.84  4918.8  446.43  4946.1  446.38  4961.1  446.98
  4984.0  447.50  5007.6  441.29  5007.8  440.79  5011.3  440.79  5011.6  441.29
  5016.6  442.44  5021.8  447.31  5049.2  447.38  5054.4  448.09  5167.8  450.81
  5222.6  450.82  5255.2  451.83  5281.8  453.75  5287.8  455.76  5297.3  454.93
#Mann=5,-1,0
  4504.6    0.05       0  4961.1    0.12       0  5007.6    0.07       0
  5011.6    0.12       0  5167.8    0.05       0
Bank Sta=5007.6,5011.6
Exp/Cntr=0.3,0.1

Type RM Length L Ch R = 1,3943,683,683,683
BEGIN DESCRIPTION:
Mapping XS 769f436f
END DESCRIPTION:
XS GIS Cut Line= 3
      2692852.46      6932823.03      2692585.69      6933288.09
      2692563.24      6933607.86
#Sta/Elev= 30
  4407.4  452.78  4469.5  450.95  4512.7  450.36  4520.3  449.63  4534.3  450.21
  4571.7  449.70  4658.7  447.62  4711.2  447.21  4739.4  446.11  4770.1  446.00
  4791.7  445.01  4873.1  445.35  4878.0  444.71  4900.8  445.92  4923.8  446.14
  4931.2  445.48  4937.0  446.43  4956.5  445.83  4976.5  446.78  4986.6  445.55
  4994.6  441.97  4994.8  441.47  4998.3  441.47  4998.6  441.97  5006.1  445.60
  5016.6  448.73  5026.7  449.49  5096.8  452.94  5166.1  454.08  5264.1  454.64
#Mann=5,-1,0
  4407.4    0.05       0  4873.1    0.12       0  4994.6    0.07       0
  4998.6    0.12       0  5166.1    0.05       0
Bank Sta=4994.6,4998.6
Exp/Cntr=0.3,0.1

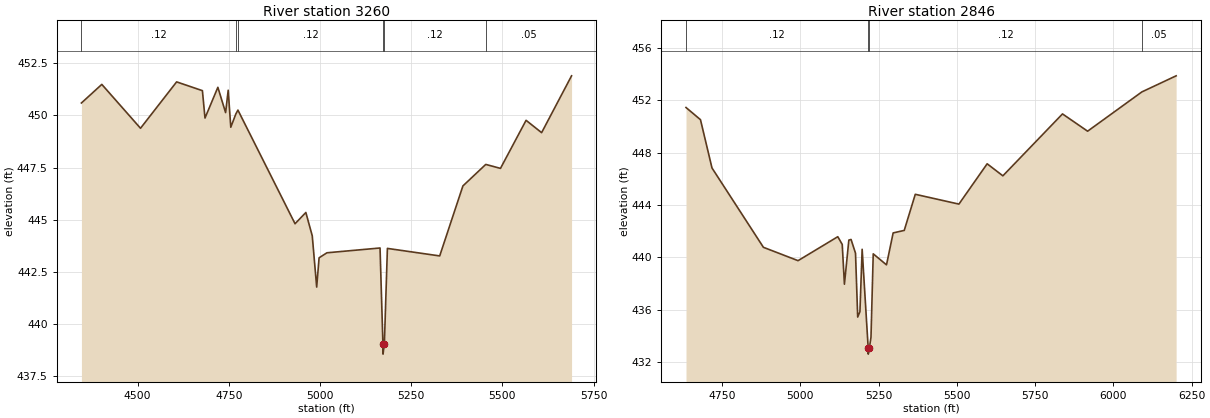
Type RM Length L Ch R = 1,3260,414,414,414
BEGIN DESCRIPTION:
Mapping XS f5b2b43d
END DESCRIPTION:
XS GIS Cut Line= 5
      2692431.90      6932647.81      2692130.80      6932947.90
      2692046.14      6933160.67      2692153.05      6933638.60
      2692310.69      6933761.62
#Sta/Elev= 30
  4345.9  450.59  4401.8  451.48  4507.9  449.38  4606.9  451.60  4677.6  451.18
  4684.7  449.87  4720.0  451.34  4741.2  450.13  4748.3  451.20  4755.4  449.43
  4769.4  450.07  4775.0  450.25  4931.6  444.81  4961.2  445.35  4978.8  444.23
  4990.9  441.78  4997.5  443.18  5019.0  443.42  5164.6  443.65  5172.5  439.07
  5172.8  438.57  5176.5  439.07  5184.8  443.63  5328.2  443.27  5391.8  446.62
  5454.5  447.65  5494.8  447.46  5565.0  449.76  5607.6  449.17  5689.7  451.89
#Mann=6,-1,0
  4345.9    0.12       0  4769.4    0.05       0  4775.0    0.12       0
  5172.5    0.07       0  5176.5    0.12       0  5454.5    0.05       0
Bank Sta=5172.5,5176.5
Exp/Cntr=0.3,0.1

Type RM Length L Ch R = 1,2846,0,0,0
BEGIN DESCRIPTION:
Muddy T3 1.0
END DESCRIPTION:
XS GIS Cut Line= 4
      2692111.92      6932897.40      2691748.91      6932934.51
      2691432.94      6933253.62      2691486.49      6934002.93
#Sta/Elev= 30
  4635.1  451.45  4681.3  450.52  4718.1  446.83  4882.3  440.77  4992.9  439.75
  5119.8  441.58  5134.0  440.99  5141.0  437.95  5155.1  441.32  5162.2  441.37
  5176.4  440.32  5183.4  435.44  5190.5  435.85  5197.6  440.62  5216.8  433.11
  5217.1  432.61  5220.8  433.11  5225.8  433.89  5233.0  440.27  5275.4  439.43
  5296.6  441.87  5332.0  442.06  5367.3  444.82  5506.6  444.07  5596.8  447.15
  5647.0  446.23  5837.4  450.96  5917.6  449.64  6090.8  452.64  6200.3  453.87
#Mann=4,-1,0
  4635.1    0.12       0  5216.8    0.07       0  5220.8    0.12       0
  6090.8    0.05       0
Bank Sta=5216.8,5220.8
Exp/Cntr=0.3,0.1

Chan Stop Cuts=-1