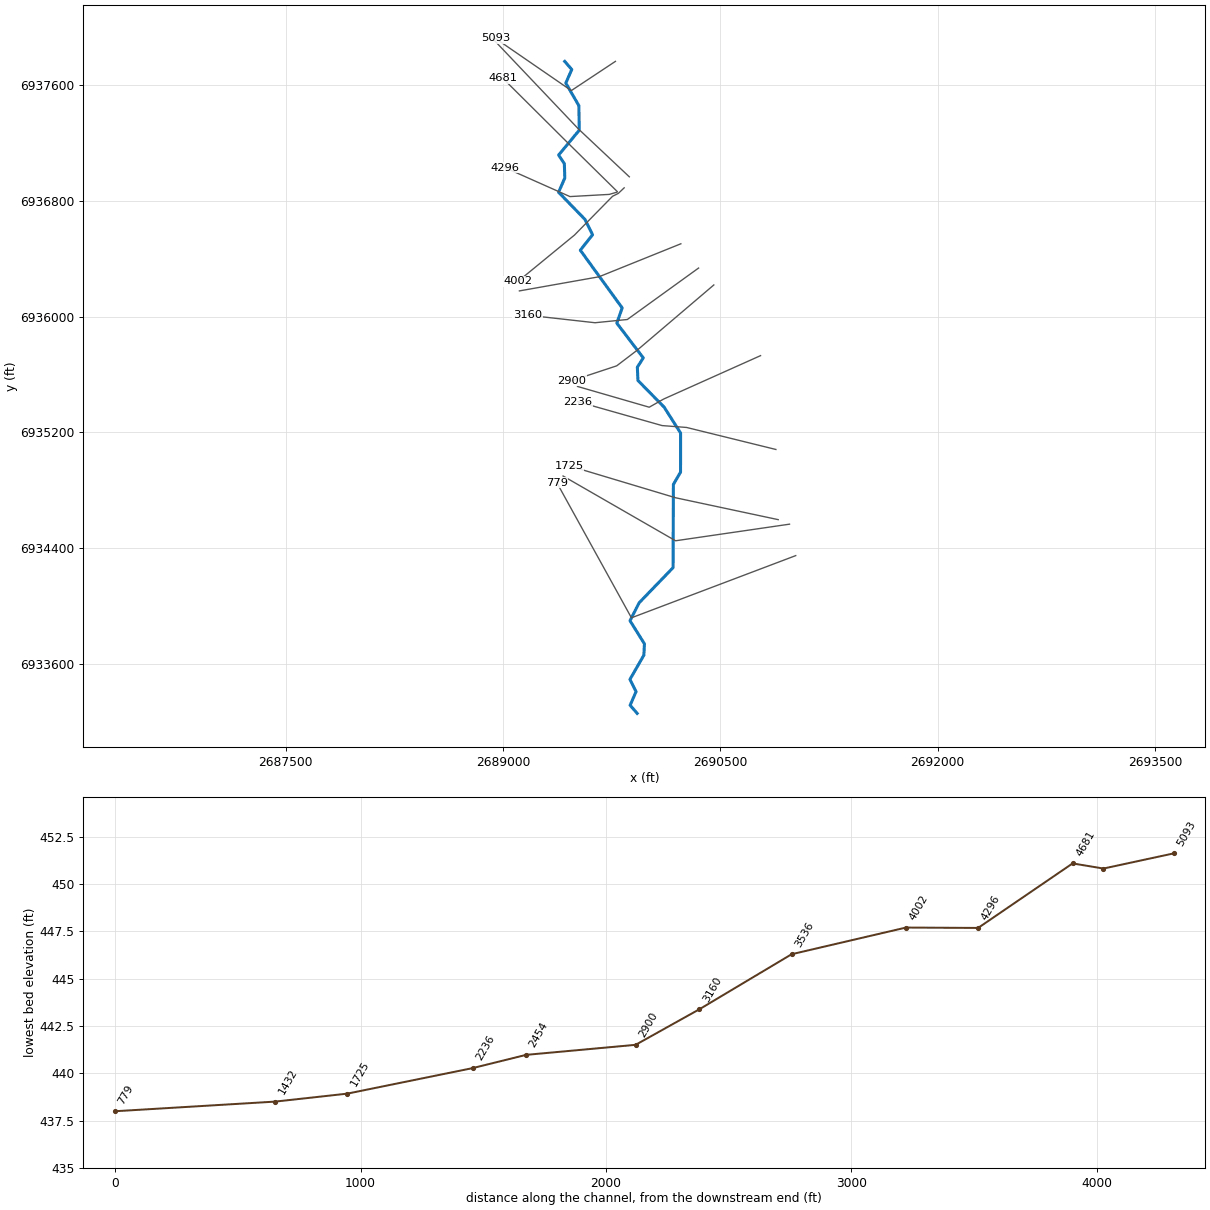
--- Muddy T4.prj (project) ---

Proj Title=Muddy T4 Base Level Engineering
Current Plan=p01
Default Exp/Contr=0.3,0.1
English Units
Geom File=g01
Flow File=f01
Plan File=p01
Y Axis Title=Elevation
X Axis Title(PF)=Main Channel Distance
X Axis Title(XS)=Station
BEGIN DESCRIPTION:
Muddy T4
END DESCRIPTION:
DSS Export Rating Curves= 0
DSS Export Rating Curve Sorted= 0
DSS Export Volume Flow Curves= 0
DXF OffsetX= 0
DXF OffsetY= 0
DXF ScaleX= 1
DXF ScaleY= 10

--- Muddy T4.p01 (plan) ---

Plan Title=Multiple Run
Short Identifier=Multiple
Geom File=g01
Flow File=f01
Subcritical Flow
K Sum by GR= 0
Std Step Tol= 0.01
Critical Tol= 0.01
Num of Std Step Trials= 20
Max Error Tol= 0.3
Flow Tol Ratio= 0.001
Split Flow NTrial= 30
Split Flow Tol= 0.02
Split Flow Ratio= 0.02
Log Output Level= 0
Friction Slope Method= 1
Unsteady Friction Slope Method= 2
Unsteady Bridges Friction Slope Method= 1
Parabolic Critical Depth
Global Vel Dist=  1 , 1 , 1
Global Log Level= 0
CheckData=True
Encroach Param= -1, 0, 0, 0
BEGIN DESCRIPTION:
Multiple Run
END DESCRIPTION:

--- Muddy T4.f01 (steady flow) ---

Flow Title=Multiple
Number of Profiles=7
Profile Names=10-year,25-year,50-year,1pct_min,100-year,1pct_plu,500-year
River Rch & RM= Muddy T4,Reach-1,5093
     472     622     742     439     876    1747    1219
River Rch & RM= Muddy T4,Reach-1,4002
     639     858    1034     619    1235    2463    1758
Boundary for River Rch & Prof#=Muddy T4,Reach-1,1
Up Type=0
Dn Type=3
Dn Slope=0.005
Boundary for River Rch & Prof#=Muddy T4,Reach-1,2
Up Type=0
Dn Type=3
Dn Slope=0.005
Boundary for River Rch & Prof#=Muddy T4,Reach-1,3
Up Type=0
Dn Type=3
Dn Slope=0.005
Boundary for River Rch & Prof#=Muddy T4,Reach-1,4
Up Type=0
Dn Type=3
Dn Slope=0.005
Boundary for River Rch & Prof#=Muddy T4,Reach-1,5
Up Type=0
Dn Type=3
Dn Slope=0.005
Boundary for River Rch & Prof#=Muddy T4,Reach-1,6
Up Type=0
Dn Type=3
Dn Slope=0.005
Boundary for River Rch & Prof#=Muddy T4,Reach-1,7
Up Type=0
Dn Type=3
Dn Slope=0.005

--- Muddy T4.g01 (geometry) ---

Geom Title=Existing Conditions
Program Version=4.10

River Reach=Muddy T4        ,Reach-1
Reach XY= 30
        2689426.        6937761.      2689474.67      6937704.94
      2689433.54        6937611.      2689523.76      6937455.07
       2689526.3      6937285.88       2689383.8      6937114.42
      2689423.54      6937055.14      2689426.46      6936955.83
      2689383.79      6936857.58      2689565.25      6936670.68
      2689618.15      6936564.23      2689533.62      6936457.67
      2689822.63      6936059.27      2689785.43      6935954.39
       2689968.2      6935714.42      2689927.27      6935650.52
       2689931.4      6935558.57      2690112.37      6935374.21
      2690225.61      6935195.84      2690225.48      6934926.22
      2690176.07      6934840.97      2690173.94      6934266.85
      2689939.62      6934024.21       2689876.7       6933900.3
      2689976.21      6933740.95      2689972.33      6933662.59
      2689876.14      6933495.59       2689918.4        6933411.
      2689877.33      6933317.06        2689926.        6933261.

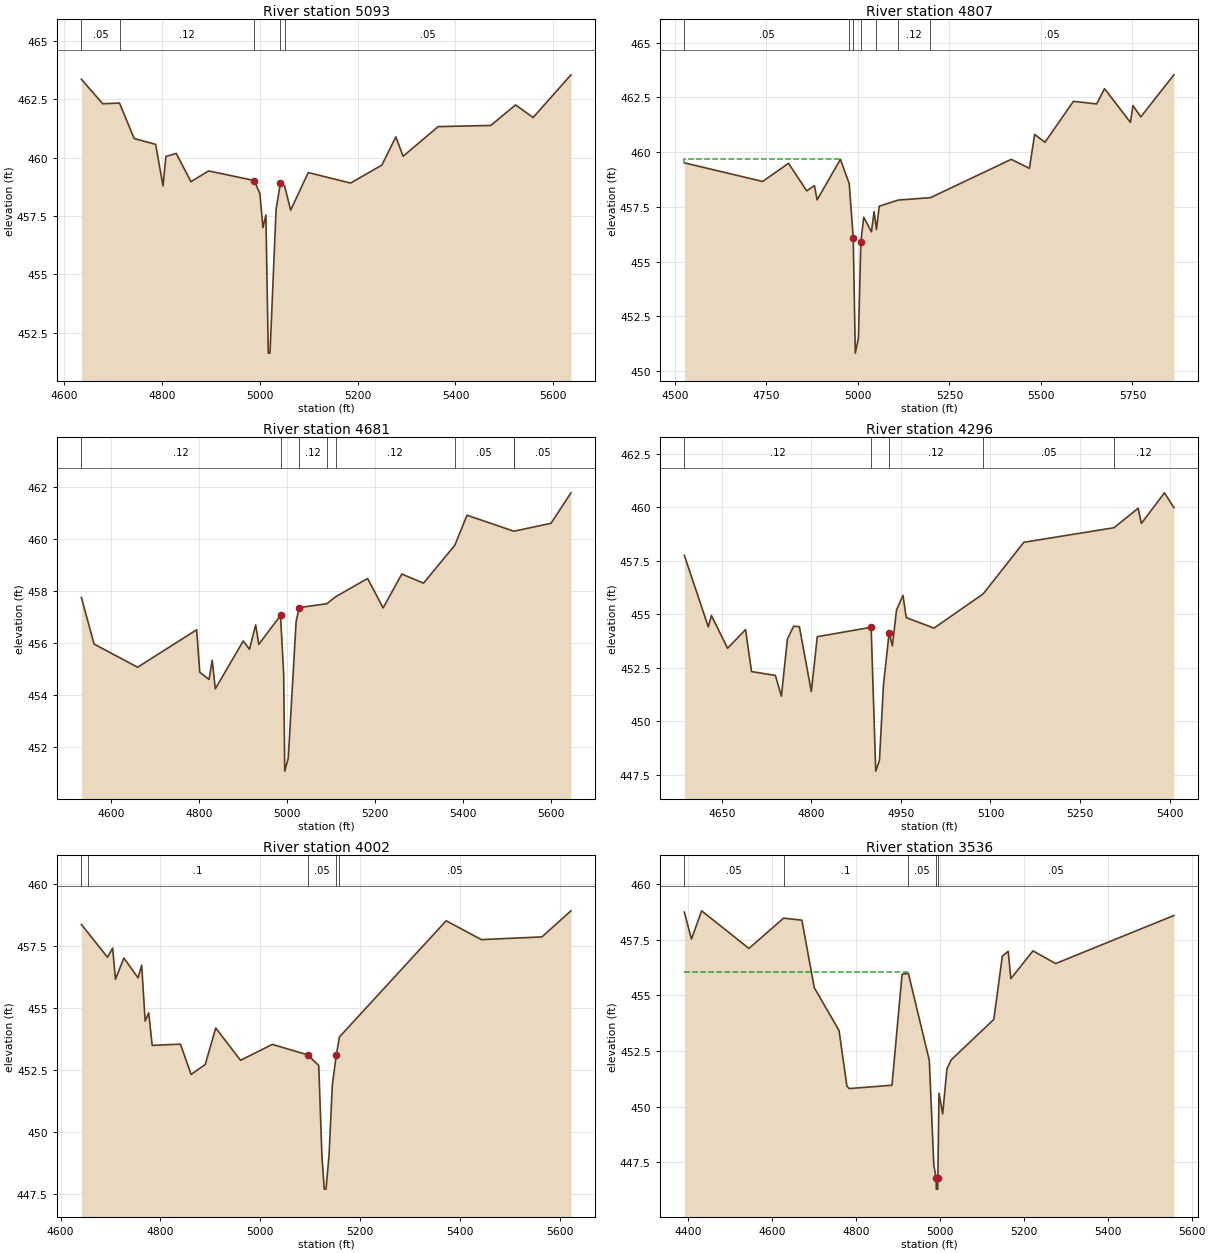
Type RM Length L Ch R = 1 ,5093    ,286,286,286
BEGIN DESCRIPTION:
Muddy T4 7.0
END DESCRIPTION:
XS GIS Cut Line= 3
      2689775.96      6937760.98      2689471.58      6937559.36
      2688947.32      6937919.95
#Sta/Elev= 30
  4634.9  463.36  4678.5  462.31  4712.9  462.34  4742.8  460.82  4786.8  460.57
  4801.8  458.79  4807.8  460.05  4828.9  460.18    4859  458.97  4895.1  459.43
  4988.3  459.02    5000  458.46  5006.2     457  5012.3  457.54  5017.2  451.62
  5020.7  451.62  5033.2   457.8  5042.1  458.91  5050.5  458.79    5063  457.75
  5098.9  459.36  5185.5  458.91  5249.5  459.68  5278.1  460.89    5293  460.06
  5364.7  461.33  5472.3  461.38    5523  462.26  5558.9  461.72  5636.3  463.55
#Mann= 5 ,-1 , 0
  4634.9     .05       0  4712.9     .12       0  4988.3     .07       0
  5042.1     .12       0  5050.5     .05       0
Bank Sta=4988.3,5042.1
XS Rating Curve= 0 ,0
Exp/Cntr=0.3,0.1

Type RM Length L Ch R = 1 ,4807    ,126,126,126
BEGIN DESCRIPTION:
Mapping XS b2ab97d2
END DESCRIPTION:
XS GIS Cut Line= 3
      2689871.78      6936964.23      2689520.19      6937294.98
      2688931.66      6937914.76
#Sta/Elev= 30
  4525.8  459.51  4739.7  458.66  4810.4  459.49  4860.2  458.23  4881.2  458.47
  4888.5  457.82  4952.1  459.67  4976.3  458.56  4987.2  456.06  4992.8  450.82
  5001.4  451.51    5008  455.91  5015.9  457.03  5036.9  456.36  5044.2  457.28
  5050.6  456.47  5058.2  457.53  5109.9  457.81  5198.1  457.92  5418.8  459.67
  5468.5  459.26  5482.7  460.81    5511  460.45  5588.7  462.32  5652.2   462.2
  5673.6   462.9  5744.4  461.36  5751.3  462.13  5772.7  461.61  5863.2  463.53
#Mann= 7 ,-1 , 0
  4525.8     .05       0  4976.3     .12       0  4987.2     .07       0
    5008     .12       0  5050.6     .05       0  5109.9     .12       0
  5198.1     .05       0
#XS Ineff= 2 , 0
       0  4952.1  459.67               0
Permanent Ineff=
       F       F
Bank Sta=4987.2,5008
XS Rating Curve= 0 ,0
Exp/Cntr=0.3,0.1

Type RM Length L Ch R = 1 ,4681    ,385,385,385
BEGIN DESCRIPTION:
Mapping XS 4068c176
END DESCRIPTION:
XS GIS Cut Line= 3
      2689788.43      6936862.68      2689455.09      6937190.81
      2688997.03      6937646.27
#Sta/Elev= 30
  4532.8  457.76  4561.7  455.97  4660.7  455.08    4795  456.52  4802.1  454.89
  4823.2  454.61  4830.4  455.35  4837.4  454.25    4901  456.09  4915.1  455.77
  4929.3  456.71  4936.4  455.96  4985.8  457.07    4993  454.81  4995.4  451.09
  5003.4  451.59  5021.3  456.84  5028.3  457.37    5091  457.52  5111.3  457.79
  5183.9  458.49  5219.2  457.36  5261.7  458.66  5311.1  458.31  5382.4  459.77
  5410.1  460.92  5515.8  460.31  5517.9  460.31  5601.1  460.61  5646.5  461.78
#Mann= 8 ,-1 , 0
  4532.8     .12       0  4985.8     .07       0  5028.3     .12       0
    5091     .05       0  5111.3     .12       0  5382.4     .05       0
  5515.8     .12       0  5517.9     .05       0
Bank Sta=4985.8,5028.3
XS Rating Curve= 0 ,0
Exp/Cntr=0.3,0.1

Type RM Length L Ch R = 1 ,4296    ,294,294,294
BEGIN DESCRIPTION:
Mapping XS 19be643e
END DESCRIPTION:
XS GIS Cut Line= 4
      2689786.17      6936858.28      2689733.74      6936842.88
      2689462.12      6936827.79      2689011.61      6937028.31
#Sta/Elev= 30
  4587.4  457.76  4627.5  454.42  4632.7  454.95  4659.8  453.42  4689.9  454.29
  4699.9  452.33  4739.9  452.15  4749.9  451.18    4760  453.85  4770.5  454.45
    4780  454.43    4800   451.4    4810  453.96  4900.2   454.4  4907.9  447.68
  4914.1  448.18  4920.8  451.69  4930.3  454.14  4935.7  453.53  4942.7  455.21
  4953.5  455.89    4959  454.85  5005.5  454.36  5087.8  455.96  5155.9  458.37
  5306.9  459.05  5347.3  459.96  5352.7  459.25  5391.4  460.68  5407.2  459.99
#Mann= 5 ,-1 , 0
  4587.4     .12       0  4900.2     .07       0  4930.3     .12       0
  5087.8     .05       0  5306.9     .12       0
Bank Sta=4900.2,4930.3
XS Rating Curve= 0 ,0
Exp/Cntr=0.3,0.1

Type RM Length L Ch R = 1 ,4002    ,466,466,466
BEGIN DESCRIPTION:
Mapping XS 64a3726e
END DESCRIPTION:
XS GIS Cut Line= 5
       2689836.3      6936888.09      2689795.79      6936849.62
      2689756.44      6936830.07      2689493.37      6936562.16
      2689102.78      6936241.88
#Sta/Elev= 30
  4641.6  458.36  4654.7  458.03  4693.9  457.04  4704.2  457.41  4709.8  456.15
  4726.6  457.01  4755.1  456.21  4762.3  456.72  4769.3  454.47  4776.4   454.8
  4783.4  453.49    4840  453.54  4861.3  452.32  4889.6  452.72  4910.7  454.19
  4960.3  452.89  5023.9  453.53  5094.6  453.11  5116.9  452.68  5123.3  449.03
    5128   447.7  5131.5   447.7  5137.6  449.09  5144.1  451.89    5152  453.09
  5158.4  453.83  5372.1  458.51  5442.6  457.75  5563.9  457.86    5622  458.91
#Mann= 5 ,-1 , 0
  4641.6     .05       0  4654.7      .1       0  5094.6     .05       0
    5152      .1       0  5158.4     .05       0
Bank Sta=5094.6,5152
XS Rating Curve= 0 ,0
Exp/Cntr=0.3,0.1

Type RM Length L Ch R = 1 ,3536    ,376,376,376
BEGIN DESCRIPTION:
Mapping XS 222fa045
END DESCRIPTION:
XS GIS Cut Line= 3
      2690227.63      6936502.04      2689662.32      6936274.19
       2689113.2      6936176.75
#Sta/Elev= 30
  4390.5  458.74  4407.5  457.53  4431.7   458.8  4544.5  457.11  4627.1  458.47
  4670.7  458.38  4700.2  455.35  4759.3  453.42  4778.1  450.92  4783.5  450.81
  4885.5  450.96  4909.6  455.95  4924.6  455.99  4974.5  452.08  4985.3  447.36
  4990.9  446.79  4991.2  446.29  4994.7  446.29  4994.9  446.79  4997.6   450.6
  5006.4  449.67  5016.6   451.7  5026.7   452.1  5128.3  453.92  5148.6  456.76
  5162.6  456.98  5168.9  455.75  5221.7     457  5275.7  456.43  5557.7  458.59
#Mann= 5 ,-1 , 0
  4390.5     .05       0  4627.1      .1       0  4924.6     .05       0
  4990.9     .04       0  4994.9     .05       0
#XS Ineff= 2 , 0
       0  4920.6  456.04               0
Permanent Ineff=
       F       F
Bank Sta=4990.9,4994.9
XS Rating Curve= 0 ,0
Exp/Cntr=0.3,0.1

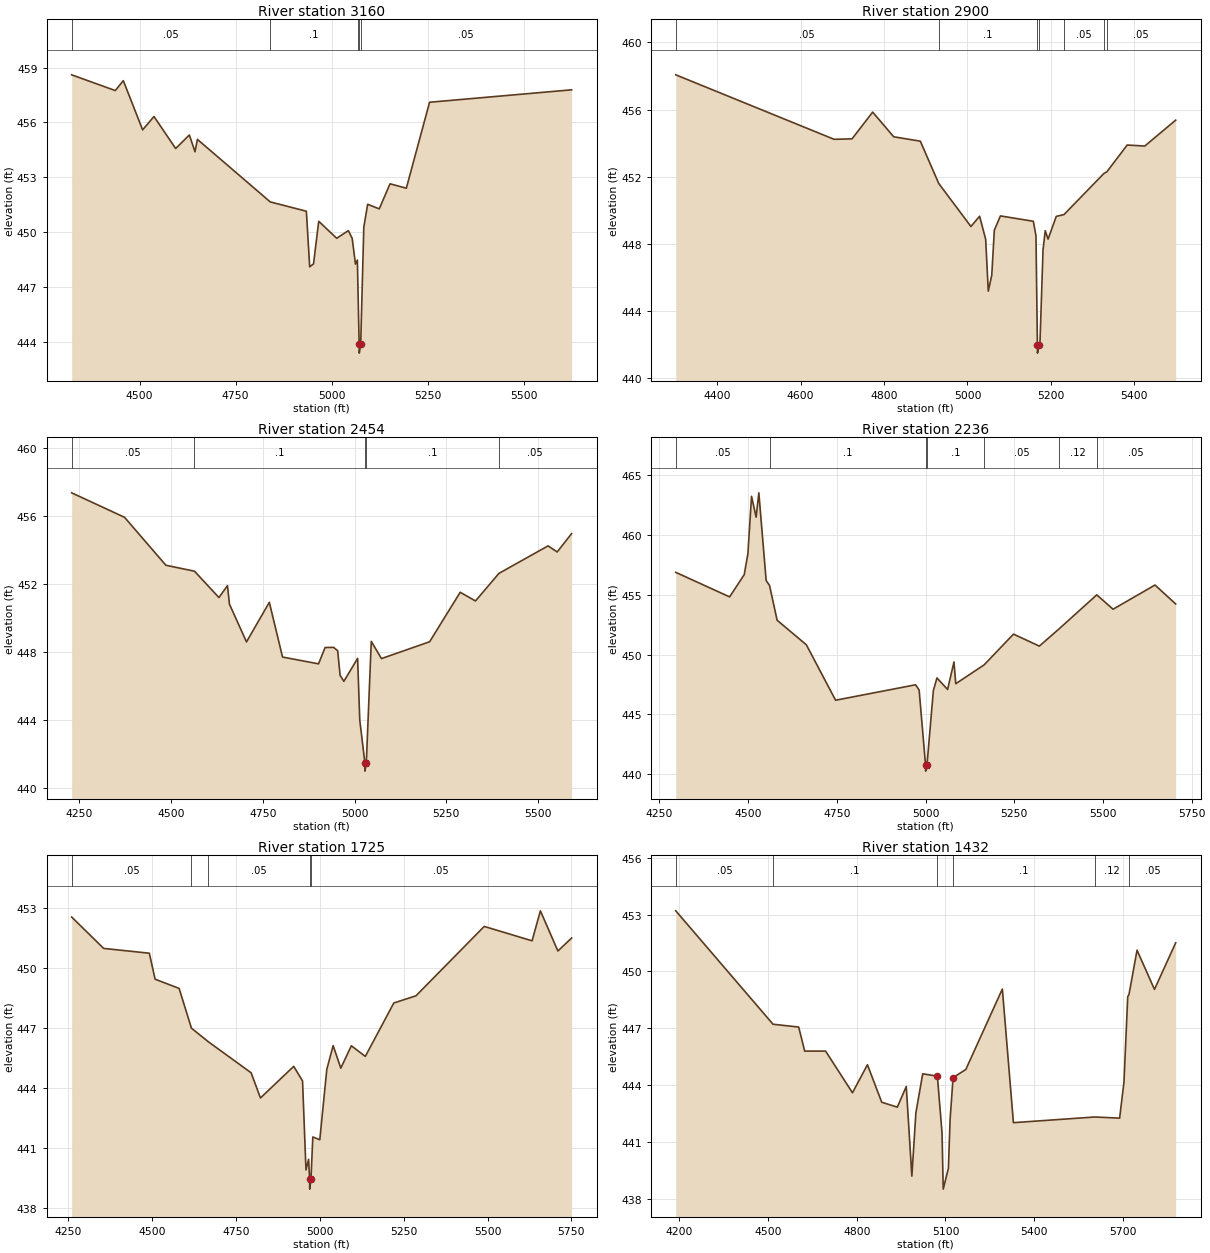
Type RM Length L Ch R = 1 ,3160    ,260,260,260
BEGIN DESCRIPTION:
Mapping XS 17003430
END DESCRIPTION:
XS GIS Cut Line= 4
       2690349.9      6936334.55      2689858.02      6935979.39
      2689635.16       6935957.1      2689169.04      6936009.22
#Sta/Elev= 30
  4323.6   458.6    4437  457.74  4457.9  458.28  4508.1  455.59  4537.6  456.32
    4594  454.57  4629.6  455.31  4644.3  454.39  4650.5  455.07  4839.9  451.65
  4933.8  451.14  4942.4   448.1  4952.4  448.26  4965.9  450.59  5012.7  449.66
  5042.9  450.08  5052.9  449.66  5061.4  448.25  5066.4  448.47  5067.1  447.77
    5071  443.88  5071.3  443.38    5075  443.88  5083.1  450.26  5093.1  451.52
  5123.3  451.27  5151.3  452.64  5193.7   452.4  5254.1   457.1  5623.3  457.78
#Mann= 5 ,-1 , 0
  4323.6     .05       0  4839.9      .1       0  5067.1     .05       0
    5071     .05       0    5075     .05       0
Bank Sta=5071,5075
XS Rating Curve= 0 ,0
Exp/Cntr=0.3,0.1

Type RM Length L Ch R = 1 ,2900    ,446,446,446
BEGIN DESCRIPTION:
Mapping XS 1b411fc8
END DESCRIPTION:
XS GIS Cut Line= 4
      2690455.05      6936217.85      2689925.02      6935766.58
       2689784.6      6935659.54      2689475.63       6935557.4
#Sta/Elev= 30
  4300.9  458.07  4680.5  454.23  4723.4  454.26  4772.8  455.85  4823.3  454.38
    4887  454.12  4931.2   451.6  5008.3  449.04  5029.1  449.65  5043.6  448.28
  5049.9  445.19  5058.2  446.14  5064.4  448.82    5079  449.67  5157.9  449.35
  5164.2  448.48  5167.6     442  5167.8   441.5  5171.6     442  5173.6     442
  5181.1  447.65  5186.4  448.79  5193.2  448.29  5212.8  449.64  5231.4  449.75
  5327.1   452.2  5333.9  452.29  5382.8  453.89  5424.9  453.83    5499  455.37
#Mann= 7 ,-1 , 0
  4300.9     .05       0  4931.2      .1       0  5167.6     .05       0
  5171.6      .1       0  5231.4     .05       0  5327.1     .12       0
  5333.9     .05       0
Bank Sta=5167.6,5171.6
XS Rating Curve= 0 ,0
Exp/Cntr=0.3,0.1

Type RM Length L Ch R = 1 ,2454    ,218,218,218
BEGIN DESCRIPTION:
Mapping XS a30815a6
END DESCRIPTION:
XS GIS Cut Line= 4
       2690777.5      6935729.99      2690109.07       6935430.5
      2690009.24      6935374.07      2689514.48      6935517.29
#Sta/Elev= 30
  4229.2  457.34  4373.3   455.9  4485.9  453.08  4563.9  452.73  4630.5  451.18
  4653.7  451.88  4659.2  450.79  4705.6  448.57  4767.8   450.9  4803.8  447.68
    4902  447.28  4919.7  448.24  4942.9  448.25  4954.1  448.05  4960.6  446.61
  4970.9  446.25  5008.4   447.6  5014.2  443.98  5028.1  441.47  5028.3  440.97
  5032.1  441.47  5045.6   448.6  5073.4  447.59  5204.6  448.58  5287.9  451.49
  5329.6  450.98  5393.3   452.6  5527.4  454.22  5552.1  453.86  5591.4  454.94
#Mann= 5 ,-1 , 0
  4229.2     .05       0  4563.9      .1       0  5028.1     .05       0
  5032.1      .1       0  5393.3     .05       0
Bank Sta=5028.1,5032.1
XS Rating Curve= 0 ,0
Exp/Cntr=0.3,0.1

Type RM Length L Ch R = 1 ,2236    ,511,511,511
BEGIN DESCRIPTION:
Mapping XS a963de35
END DESCRIPTION:
XS GIS Cut Line= 4
      2690883.41       6935082.4      2690267.06      6935234.31
      2690097.78      6935247.34      2689516.19      6935412.27
#Sta/Elev= 30
  4295.9  456.87  4447.7  454.82  4488.9  456.68  4499.2  458.42  4509.5  463.22
  4522.4  461.48  4530.1  463.51  4550.7  456.18  4560.2  455.78  4581.6  452.87
    4664  450.82  4746.4  446.19  4971.9  447.48  4981.9  447.04    5000  440.77
  5000.2  440.27    5004  440.77    5022     447  5032.1  448.05  5062.1  447.09
  5080.1  449.39  5085.1  447.57    5165  449.14  5247.8  451.71  5320.7  450.71
  5375.6  452.13  5482.6  454.99  5528.5  453.79  5646.7  455.81    5705  454.23
#Mann= 7 ,-1 , 0
  4295.9     .05       0  4560.2      .1       0    5000     .05       0
    5004      .1       0    5165     .05       0  5375.6     .12       0
  5482.6     .05       0
Bank Sta=5000,5004
XS Rating Curve= 0 ,0
Exp/Cntr=0.3,0.1

Type RM Length L Ch R = 1 ,1725    ,293,293,293
BEGIN DESCRIPTION:
Mapping XS f7eabb85
END DESCRIPTION:
XS GIS Cut Line= 3
      2690899.33      6934598.11      2690191.03      6934749.14
      2689456.91      6934969.49
#Sta/Elev= 30
    4260  452.53  4355.4  450.96  4491.6  450.72  4508.8  449.42  4580.4  448.96
  4617.2  446.97  4667.7  446.29  4795.1  444.74    4823  443.48  4922.1  445.06
  4948.5  444.33  4958.7  439.88  4966.5  440.41  4969.6  439.42  4969.8  438.92
  4973.6  439.42  4979.1  441.53  4999.9  441.39  5020.8  444.91  5039.7   446.1
  5062.6  444.97  5093.9  446.09  5135.7  445.56  5220.6  448.23  5286.7  448.59
  5490.2  452.06  5632.9  451.34  5657.7  452.84  5709.9  450.83  5750.7  451.48
#Mann= 5 ,-1 , 0
    4260     .05       0  4617.2      .1       0  4667.7     .05       0
  4969.6     .05       0  4973.6     .05       0
Bank Sta=4969.6,4973.6
XS Rating Curve= 0 ,0
Exp/Cntr=0.3,0.1

Type RM Length L Ch R = 1 ,1432    ,653,653,653
BEGIN DESCRIPTION:
Mapping XS 71f690ba
END DESCRIPTION:
XS GIS Cut Line= 3
       2690977.5      6934566.85      2690191.03      6934452.27
      2689414.48       6934899.3
#Sta/Elev= 30
  4187.9   453.2  4516.9  447.21  4603.7  447.06    4624  445.79  4694.7  445.79
  4785.6  443.59  4836.2  445.07  4884.5  443.09  4937.2  442.83  4967.5  443.92
  4986.4  439.19    5000  442.52  5023.1  444.59  5072.7  444.47  5088.5  441.46
  5092.5   438.5    5110   439.6  5115.8  442.19  5125.8  444.39  5168.9  444.82
  5292.5  449.07  5329.9  442.01    5605  442.31  5689.1  442.25  5703.9  444.17
  5716.5  448.66  5720.8  448.78    5748  451.12    5807  449.05  5878.7  451.51
#Mann= 6 ,-1 , 0
  4187.9     .05       0  4516.9      .1       0  5072.7     .05       0
  5125.8      .1       0    5605     .12       0  5720.8     .05       0
#XS Ineff= 2 , 0
       0                  5292.5       0  449.07
Permanent Ineff=
       F       F
Bank Sta=5072.7,5125.8
XS Rating Curve= 0 ,0
Exp/Cntr=0.3,0.1

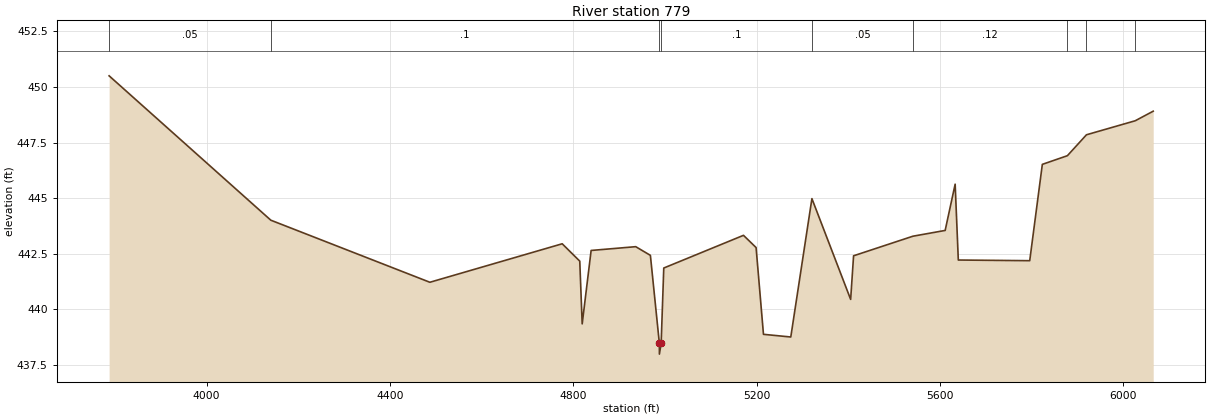
Type RM Length L Ch R = 1 ,779     ,0,0,0
BEGIN DESCRIPTION:
Muddy T4 1.0
END DESCRIPTION:
XS GIS Cut Line= 3
      2691020.45      6934349.83      2689886.49      6933920.55
      2689371.62      6934853.27
#Sta/Elev= 30
  3787.5   450.5  4140.3  444.01  4487.3  441.22    4776  442.95  4814.3  442.17
  4819.6  439.35  4839.1  442.65  4936.4  442.82  4968.4  442.43  4987.9  438.49
  4988.1  437.99  4991.9  438.49  4997.6  441.86  5171.5  443.33    5199  442.78
  5215.1  438.88  5274.7  438.76  5320.8  444.98  5405.3  440.45  5411.7  442.41
  5541.1  443.29  5611.5  443.55  5633.3  445.63  5640.2  442.22    5796  442.19
  5823.5  446.52  5878.2  446.91  5919.8  447.85  6026.2  448.48  6065.4  448.91
#Mann= 9 ,-1 , 0
  3787.5     .05       0  4140.3      .1       0  4987.9     .05       0
  4991.9      .1       0  5320.8     .05       0  5541.1     .12       0
  5878.2     .05       0  5919.8     .12       0  6026.2     .05       0
#XS Ineff= 2 , 0
       0                  5633.3       0  445.63
Permanent Ineff=
       F       F
Bank Sta=4987.9,4991.9
XS Rating Curve= 0 ,0
Exp/Cntr=0.3,0.1

Chan Stop Cuts=-1
Use User Specified Reach Order=0
Composite Channel Slope=5