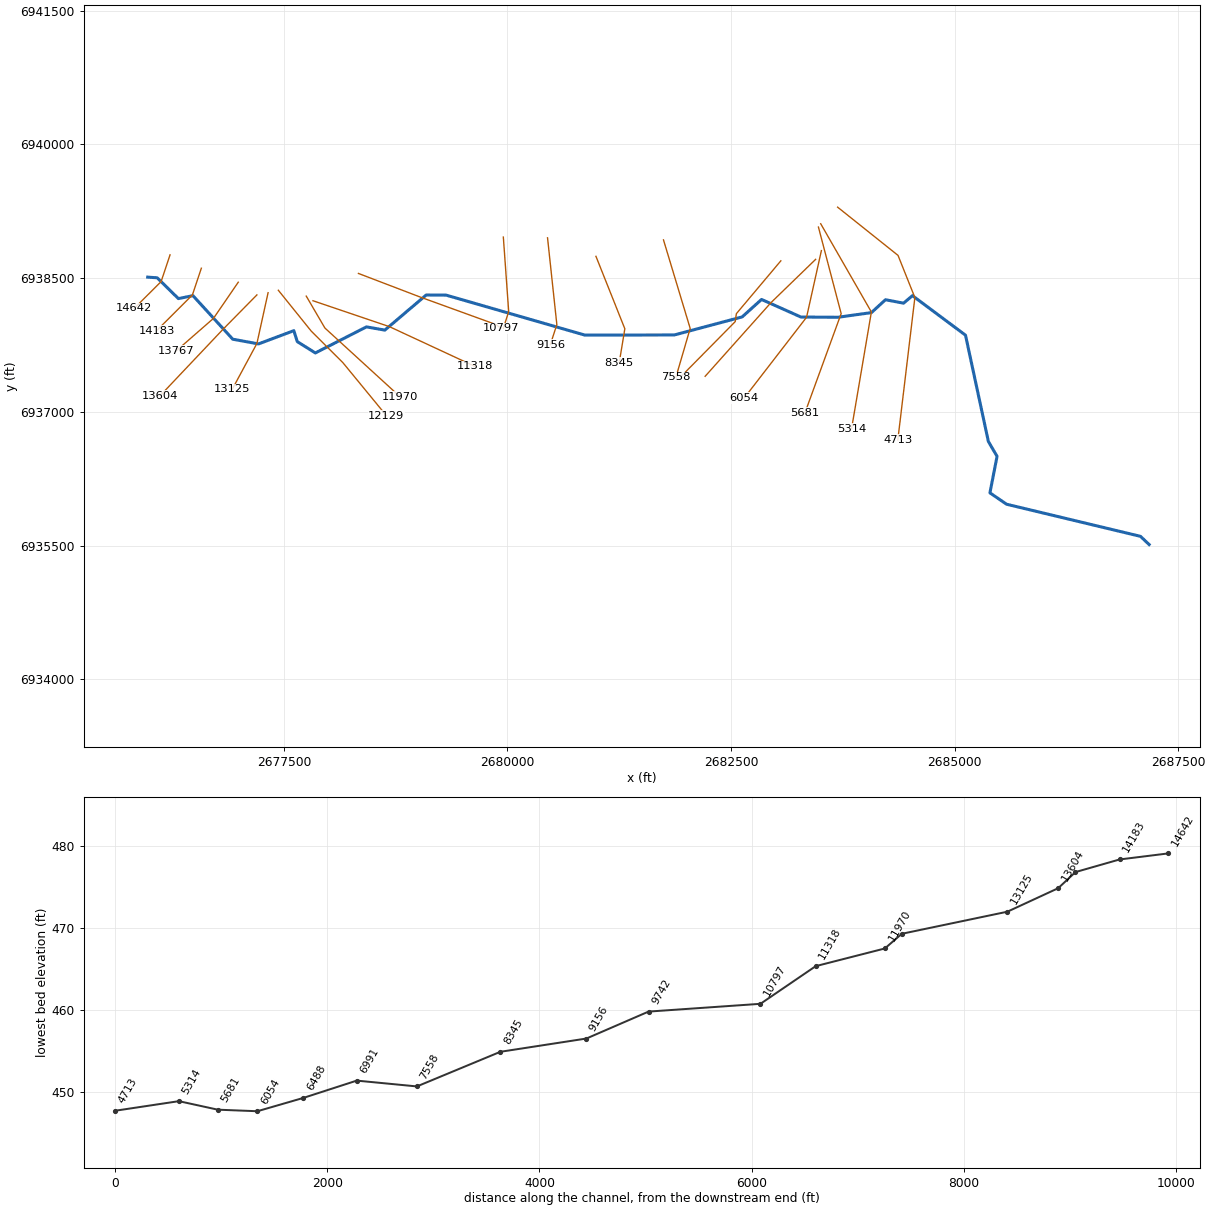
--- Muddy T5.prj (project) ---

Proj Title=Muddy T5 Base Level Engineering
Current Plan=p01
Default Exp/Contr=0.3,0.1
English Units
Geom File=g01
Flow File=f01
Plan File=p01
Y Axis Title=Elevation
X Axis Title(PF)=Main Channel Distance
X Axis Title(XS)=Station
BEGIN DESCRIPTION:
Muddy T5
END DESCRIPTION:
DSS Export Rating Curves= 0
DSS Export Rating Curve Sorted= 0
DSS Export Volume Flow Curves= 0
DXF OffsetX= 0
DXF OffsetY= 0
DXF ScaleX= 1
DXF ScaleY= 10

--- Muddy T5.p01 (plan) ---

Plan Title=Multiple Run
Short Identifier=Multiple
Geom File=g01
Flow File=f01
Subcritical Flow
K Sum by GR= 0
Std Step Tol= 0.01
Critical Tol= 0.01
Num of Std Step Trials= 20
Max Error Tol= 0.3
Flow Tol Ratio= 0.001
Split Flow NTrial= 30
Split Flow Tol= 0.02
Split Flow Ratio= 0.02
Log Output Level= 0
Friction Slope Method= 1
Unsteady Friction Slope Method= 2
Unsteady Bridges Friction Slope Method= 1
Parabolic Critical Depth
Global Vel Dist=  1 , 1 , 1
Global Log Level= 0
CheckData=True
Encroach Param= -1, 0, 0, 0
BEGIN DESCRIPTION:
Multiple Run
END DESCRIPTION:

--- Muddy T5.f01 (steady flow) ---

Flow Title=Multiple
Number of Profiles=7
Profile Names=10-year,25-year,50-year,1pct_min,100-year,1pct_plu,500-year
River Rch & RM= Muddy T5,Reach-1,14642
     570     761     915     546    1089    2173    1542
River Rch & RM= Muddy T5,Reach-1,11318
     965    1326    1625     986    1967    3925    2883
River Rch & RM= Muddy T5,Reach-1,7558
    1158    1598    1962    1192    2378    4745    3494
Boundary for River Rch & Prof#=Muddy T5,Reach-1,1
Up Type=0
Dn Type=3
Dn Slope=0.005
Boundary for River Rch & Prof#=Muddy T5,Reach-1,2
Up Type=0
Dn Type=3
Dn Slope=0.005
Boundary for River Rch & Prof#=Muddy T5,Reach-1,3
Up Type=0
Dn Type=3
Dn Slope=0.005
Boundary for River Rch & Prof#=Muddy T5,Reach-1,4
Up Type=0
Dn Type=3
Dn Slope=0.005
Boundary for River Rch & Prof#=Muddy T5,Reach-1,5
Up Type=0
Dn Type=3
Dn Slope=0.005
Boundary for River Rch & Prof#=Muddy T5,Reach-1,6
Up Type=0
Dn Type=3
Dn Slope=0.005
Boundary for River Rch & Prof#=Muddy T5,Reach-1,7
Up Type=0
Dn Type=3
Dn Slope=0.005

--- Muddy T5.g01 (geometry) ---

Geom Title=Existing Conditions
Program Version=4.10

River Reach=Muddy T5        ,Reach-1
Reach XY= 30
        2675976.        6938511.      2676082.55       6938503.4
      2676319.27      6938270.15      2676482.17      6938303.24
       2676927.3      6937814.55      2677215.29      6937761.81
      2677610.36      6937910.58      2677648.86      6937787.45
      2677851.03      6937660.49      2678422.68      6937952.96
      2678628.45      6937916.45      2679091.04      6938310.66
      2679314.03      6938309.04      2680865.81      6937860.55
      2681865.49      6937862.21       2682624.5      6938064.61
      2682841.16      6938260.64      2683281.93      6938063.24
      2683696.15      6938060.64      2684070.15      6938113.06
      2684227.47      6938257.47      2684429.42      6938218.82
      2684529.27      6938303.16      2685122.39      6937859.52
      2685378.25      6936666.93      2685475.25      6936500.32
      2685395.57       6936090.8      2685581.93      6935963.24
      2687079.34      6935603.11        2687176.        6935511.

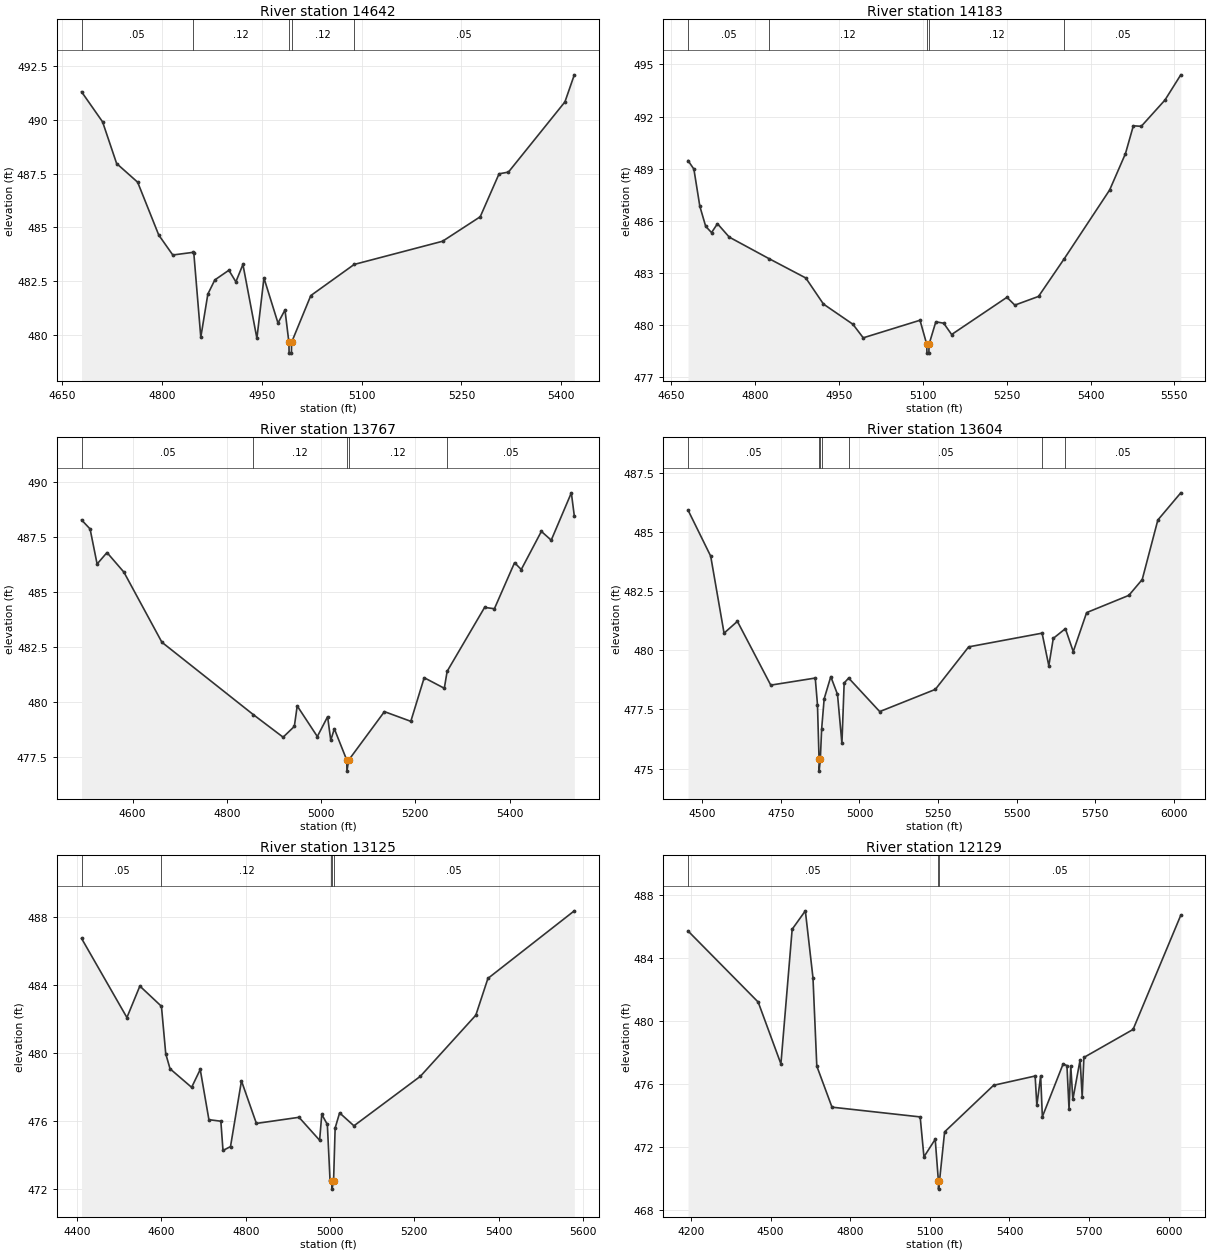
Type RM Length L Ch R = 1 ,14642   ,459,459,459
BEGIN DESCRIPTION:
Muddy T5 22.0
END DESCRIPTION:
XS GIS Cut Line= 3
      2676226.01      6938761.02        2676126.        6938461.
      2675826.01      6938161.01
#Sta/Elev= 30
  4679.1  491.31  4710.7  489.91  4731.8  487.97  4763.4   487.1  4795.1  484.64
  4816.2  483.71  4845.9  483.83  4847.8   483.8  4858.3  479.88  4868.9  481.89
  4879.4  482.55  4900.5     483    4911  482.46  4921.6  483.27  4942.6  479.83
  4953.2  482.64  4974.3  480.54  4984.8  481.15  4990.7  479.64    4991  479.14
  4994.5  479.14  4994.7  479.64  5023.6  481.82  5088.8  483.27  5221.6  484.35
  5278.2  485.49  5306.5  487.49  5320.6  487.57  5405.5  490.84  5419.6   492.1
#Mann= 5 ,-1 , 0
  4679.1     .05       0  4845.9     .12       0  4990.7     .07       0
  4994.7     .12       0  5088.8     .05       0
Bank Sta=4990.7,4994.7
XS Rating Curve= 0 ,0
Exp/Cntr=0.3,0.1

Type RM Length L Ch R = 1 ,14183   ,416,416,416
BEGIN DESCRIPTION:
Muddy T5 21.0
END DESCRIPTION:
XS GIS Cut Line= 3
      2676575.99      6938610.98        2676476.        6938311.
        2676076.        6937911.
#Sta/Elev= 30
  4679.6  489.47  4690.1  488.98  4700.7  486.85  4711.2  485.69  4721.7  485.33
  4732.3  485.84  4753.4  485.07  4824.1  483.84  4890.4  482.72    4922  481.22
  4974.7  480.06  4993.2  479.28  5094.8  480.29  5106.9   478.9  5107.2   478.4
  5110.7   478.4  5110.9   478.9  5123.1   480.2  5137.2  480.12  5151.4  479.47
  5250.4  481.61  5264.5  481.16  5306.9  481.66    5353  483.83  5434.2  487.78
  5462.5  489.87  5476.6  491.47  5490.8  491.44  5533.2  492.95  5561.5   494.4
#Mann= 5 ,-1 , 0
  4679.6     .05       0  4824.1     .12       0  5106.9     .07       0
  5110.9     .12       0    5353     .05       0
Bank Sta=5106.9,5110.9
XS Rating Curve= 0 ,0
Exp/Cntr=0.3,0.1

Type RM Length L Ch R = 1 ,13767   ,163,163,163
BEGIN DESCRIPTION:
Mapping XS 2f94de17
END DESCRIPTION:
XS GIS Cut Line= 3
       2676989.1       6938454.1       2676711.3      6938047.82
      2676294.65      6937683.25
#Sta/Elev= 30
  4491.6  488.26  4509.7  487.85  4524.6  486.26  4545.6  486.78  4581.5  485.89
  4662.1  482.71  4856.4  479.42  4919.4   478.4  4943.2  478.89  4949.3  479.82
    4992  478.43  5013.8  479.33  5020.5  478.26  5028.1  478.78  5054.5  477.36
  5054.8  476.86  5058.5  477.36  5134.4  479.56  5190.4  479.12  5218.8   481.1
  5261.5  480.62  5267.5  481.39    5347  484.29  5367.8  484.23  5410.6  486.32
  5424.8  486.01  5467.5  487.74  5488.4  487.34  5531.1  489.49  5537.4  488.44
#Mann= 5 ,-1 , 0
  4491.6     .05       0  4856.4     .12       0  5054.5     .07       0
  5058.5     .12       0  5267.5     .05       0
Bank Sta=5054.5,5058.5
XS Rating Curve= 0 ,0
Exp/Cntr=0.3,0.1

Type RM Length L Ch R = 1 ,13604   ,479,479,479
BEGIN DESCRIPTION:
Mapping XS 1322cabe
END DESCRIPTION:
XS GIS Cut Line= 3
       2677197.4      6938311.69      2676815.47      6937922.82
      2676114.05      6937179.74
#Sta/Elev= 30
  4454.9  485.94    4527  483.99  4569.5  480.73  4611.9  481.23    4718  478.53
  4859.5  478.83  4866.5  477.71  4871.6  475.39  4871.9  474.89  4875.6  475.39
  4879.8  476.67  4887.8  477.95  4908.9  478.89  4930.2  478.14  4944.3  476.06
  4951.4  478.62  4965.7  478.83  5064.5  477.41  5241.3  478.35  5347.3  480.15
  5580.8  480.73  5602.2  479.35  5616.4  480.51  5654.9  480.92  5679.9  479.95
  5722.4   481.6  5856.7  482.33  5899.2     483  5948.9  485.52  6021.8  486.67
#Mann= 7 ,-1 , 0
  4454.9     .05       0  4871.6     .03       0  4875.6     .05       0
  4879.8     .12       0  4965.7     .05       0  5580.8     .12       0
  5654.9     .05       0
Bank Sta=4871.6,4875.6
XS Rating Curve= 0 ,0
Exp/Cntr=0.3,0.1

Type RM Length L Ch R = 1 ,13125   ,996,996,996
BEGIN DESCRIPTION:
Mapping XS ca294292
END DESCRIPTION:
XS GIS Cut Line= 3
      2677322.42      6938336.05      2677197.41      6937766.57
      2676920.32      6937250.49
#Sta/Elev= 30
  4410.6  486.75  4518.2   482.1  4548.9  483.95  4600.1  482.76  4610.3  479.97
  4620.5  479.09  4671.7     478  4692.1  479.05  4712.7   476.1    4741  476.01
  4746.1  474.29  4763.9  474.52  4789.9  478.38  4825.3  475.88  4926.4  476.24
  4975.3  474.89  4980.4  476.41  4993.6  475.82    5000  472.54  5003.3  472.53
  5004.4  472.52  5004.7  472.02  5008.4  472.52  5012.1  475.61  5022.7   476.5
  5056.7  475.74  5214.3  478.65  5345.8  482.24  5374.5   484.4  5579.4  488.37
#Mann= 5 ,-1 , 0
  4410.6     .05       0  4600.1     .12       0  5003.3     .05       0
  5004.4     .07       0  5008.4     .05       0
Bank Sta=5004.4,5008.4
XS Rating Curve= 0 ,0
Exp/Cntr=0.3,0.1

Type RM Length L Ch R = 1 ,12129   ,159,159,159
BEGIN DESCRIPTION:
Mapping XS cb2529fe
END DESCRIPTION:
XS GIS Cut Line= 4
      2677436.97      6938363.83      2677805.05      6937905.46
      2678159.22      6937551.29      2678645.33      6936957.54
#Sta/Elev= 30
  4189.2  485.73  4453.5  481.21  4539.1  477.28  4581.5  485.84  4631.1  487.01
  4659.9  482.75  4674.3  477.14  4731.5  474.53  5063.7  473.91  5077.9  471.37
  5120.3  472.49  5132.4  469.82  5132.7  469.32  5136.4  469.82  5155.7  472.96
  5340.2  475.92  5496.7  476.51  5503.1  474.64  5517.5  476.52  5523.9  473.92
  5602.2  477.28  5616.5  477.17  5624.4  474.41  5630.9  477.16  5638.8  475.02
  5666.1  477.54  5673.9  475.19  5680.4  477.69  5865.6  479.47  6045.3  486.73
#Mann= 3 ,-1 , 0
  4189.2     .05       0  5132.4     .03       0  5136.4     .05       0
Bank Sta=5132.4,5136.4
XS Rating Curve= 0 ,0
Exp/Cntr=0.3,0.1

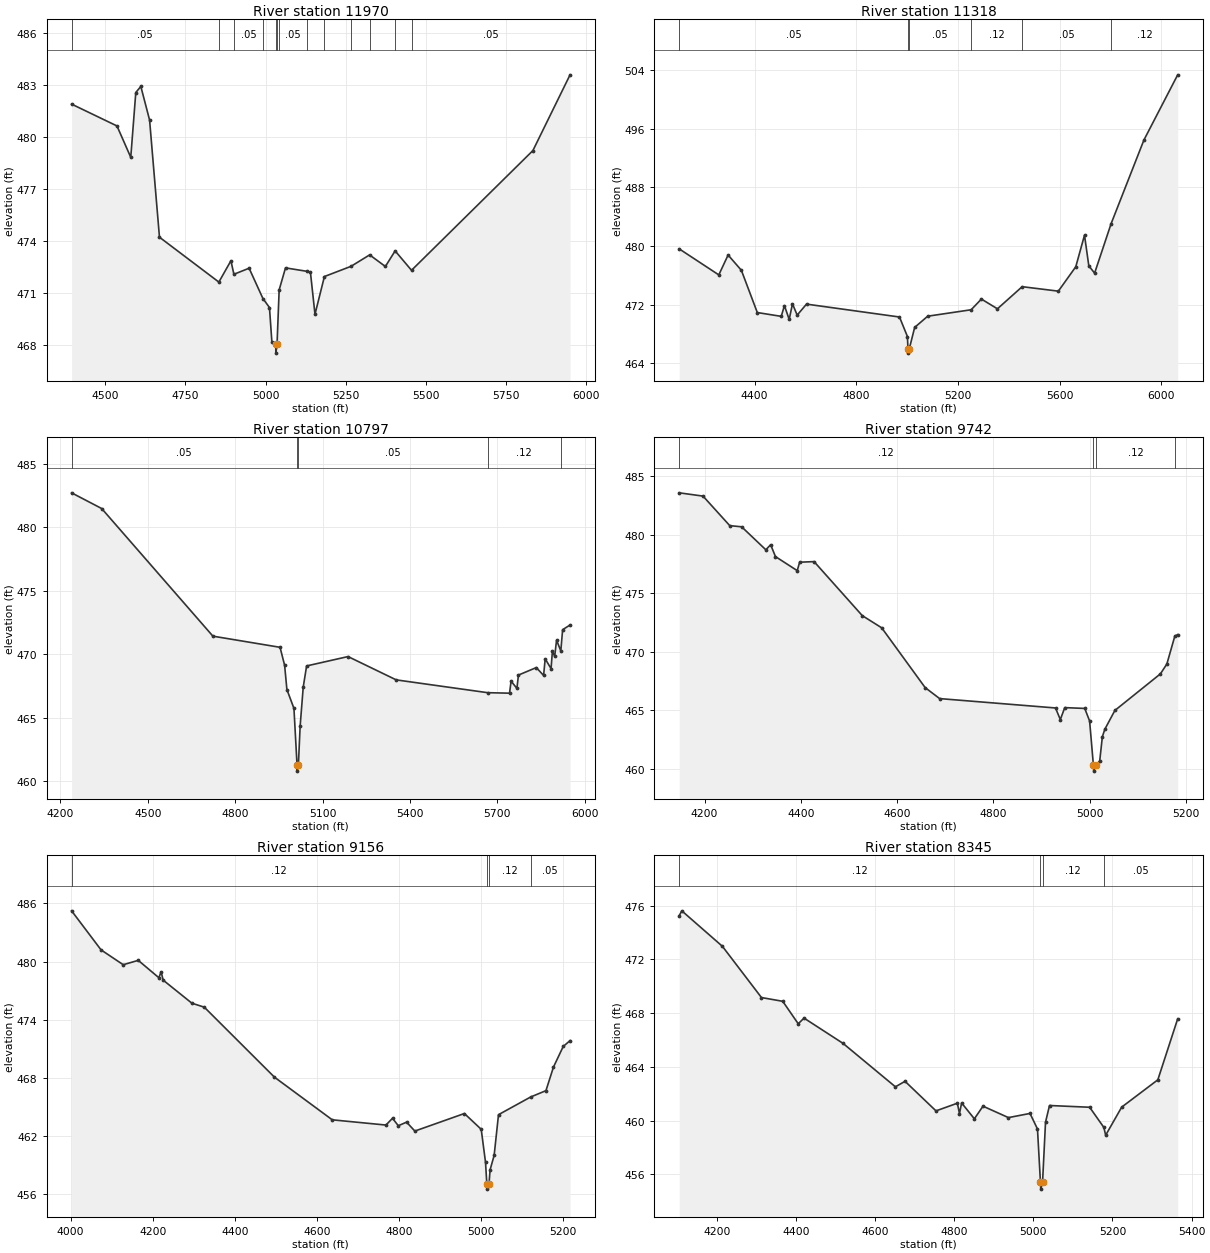
Type RM Length L Ch R = 1 ,11970   ,652,652,652
BEGIN DESCRIPTION:
Mapping XS 978cf351
END DESCRIPTION:
XS GIS Cut Line= 3
      2677749.51       6938297.8      2677957.83      6937940.18
      2678798.14      6937169.32
#Sta/Elev= 30
    4395   481.9  4536.5  480.64  4579.5  478.83  4595.2  482.57  4610.9  482.92
  4638.2  480.98    4669  474.22  4854.2  471.63  4891.8  472.86  4901.1  472.08
  4948.5  472.43  4991.6  470.68    5012  470.16  5019.4   468.2  5031.6  468.03
  5031.9  467.53  5035.6  468.03  5042.2  471.18    5062  472.45    5129  472.25
  5139.7   472.2  5153.9  469.77  5183.3  471.95  5266.4  472.54  5324.4   473.2
  5373.4  472.53  5403.8  473.43  5454.9  472.31  5833.4  479.22  5949.2  483.59
#Mann= 13 ,-1 , 0
    4395     .05       0  4854.2     .12       0  4901.1     .05       0
  4991.6     .12       0  5031.6     .07       0  5035.6     .12       0
  5042.2     .05       0    5129     .12       0  5183.3     .05       0
  5266.4     .12       0  5324.4     .05       0  5403.8     .12       0
  5454.9     .05       0
Bank Sta=5031.6,5035.6
XS Rating Curve= 0 ,0
Exp/Cntr=0.3,0.1

Type RM Length L Ch R = 1 ,11318   ,521,521,521
BEGIN DESCRIPTION:
Mapping XS e94463d8
END DESCRIPTION:
XS GIS Cut Line= 3
      2677824.17      6938246.31      2678679.18      6937955.52
      2679638.41      6937508.45
#Sta/Elev= 30
  4103.4   479.6  4259.1  476.05  4295.7  478.76  4347.9  476.68  4410.6  470.91
  4504.8  470.39  4517.3  471.85  4536.1  469.97    4549   472.1  4567.5  470.56
  4604.2  472.06  4970.1   470.3  5001.4  467.63  5003.5  465.87    5004  465.37
    5008  465.87  5029.8  468.88  5081.1  470.41  5252.1  471.29  5292.4  472.75
  5355.5  471.42  5452.9  474.44  5595.2  473.83  5663.8  477.16  5698.1  481.47
  5715.1  477.28  5737.9  476.29  5802.8  483.04  5931.9  494.46  6064.8  503.36
#Mann= 6 ,-1 , 0
  4103.4     .05       0  5003.5     .03       0    5008     .05       0
  5252.1     .12       0  5452.9     .05       0  5802.8     .12       0
Bank Sta=5003.5,5008
XS Rating Curve= 0 ,0
Exp/Cntr=0.3,0.1

Type RM Length L Ch R = 1 ,10797   ,1055,1055,1055
BEGIN DESCRIPTION:
Mapping XS 0e598e81
END DESCRIPTION:
XS GIS Cut Line= 4
      2678332.87      6938552.43      2679025.54      6938286.82
      2679875.75      6937977.56      2679926.07      6937936.03
#Sta/Elev= 30
  4238.1  482.73  4341.5  481.49  4723.4  471.42    4954  470.54  4969.7  469.12
  4977.5  467.21  5001.7  465.72  5012.3  461.27  5012.8  460.77    5017  461.27
    5023  464.33  5033.6   467.4  5045.2  469.07  5187.5  469.81  5352.9  467.97
  5666.9  466.96  5742.1  466.92  5747.4  467.87  5767.4   467.3  5772.7  468.35
  5833.9  468.94  5859.1  468.32  5864.5  469.63  5884.7  468.86  5889.3  470.23
  5897.1  469.83  5903.6   471.1  5918.2  470.26  5924.4  471.93  5949.9   472.3
#Mann= 5 ,-1 , 0
  4238.1     .05       0  5012.3     .03       0    5017     .05       0
  5666.9     .12       0  5918.2     .05       0
Bank Sta=5012.3,5017
XS Rating Curve= 0 ,0
Exp/Cntr=0.3,0.1

Type RM Length L Ch R = 1 ,9742    ,586,586,586
BEGIN DESCRIPTION:
Mapping XS 2861f4a2
END DESCRIPTION:
XS GIS Cut Line= 3
      2679953.49       6938960.3      2680013.38      6938124.32
      2679953.48      6937936.78
#Sta/Elev= 30
  4147.5  483.57  4196.9  483.29  4252.4  480.77  4277.1  480.67  4327.3  478.71
  4337.3  479.14  4347.3  478.13  4392.5  476.93  4397.5  477.65  4427.5   477.7
  4527.6  473.09  4567.9  472.05  4658.1  466.95  4688.2  466.01  4928.8  465.21
  4938.8  464.22    4948  465.24  4989.5  465.17  4999.6   464.1  5007.5  460.32
  5008.2  459.82  5012.7  460.32  5020.6  460.69  5026.1  462.76  5031.3   463.4
  5052.1     465  5146.6  468.12    5160  468.96  5176.6  471.35  5182.5  471.47
#Mann= 4 ,-1 , 0
  4147.5     .12       0  5007.5     .07       0  5012.7     .12       0
  5176.6     .05       0
Bank Sta=5007.5,5012.7
XS Rating Curve= 0 ,0
Exp/Cntr=0.3,0.1

Type RM Length L Ch R = 1 ,9156    ,811,811,811
BEGIN DESCRIPTION:
Mapping XS 4e72918e
END DESCRIPTION:
XS GIS Cut Line= 3
      2680447.76      6938952.43      2680551.93      6937978.49
      2680479.24      6937755.22
#Sta/Elev= 30
  4002.4  485.24  4074.2  481.21  4128.2  479.68  4164.8  480.13    4215  478.34
  4220.5  478.95  4225.5  478.09  4295.5  475.71  4325.7   475.3  4496.6  468.08
  4637.4  463.68  4768.2  463.14  4784.2  463.84  4798.3  463.07  4818.5  463.44
  4838.6  462.52  4959.3  464.33  5000.3   462.7  5010.8  459.29    5014  457.03
  5014.7  456.53  5019.2  457.03  5021.9  458.52  5031.8  460.01  5042.4  464.21
  5120.5  466.03    5158  466.69  5176.3  469.12  5200.1  471.25  5216.7  471.85
#Mann= 4 ,-1 , 0
  4002.4     .12       0    5014     .07       0  5019.2     .12       0
  5120.5     .05       0
Bank Sta=5014,5019.2
XS Rating Curve= 0 ,0
Exp/Cntr=0.3,0.1

Type RM Length L Ch R = 1 ,8345    ,787,787,787
BEGIN DESCRIPTION:
Mapping XS 8f16f0a2
END DESCRIPTION:
XS GIS Cut Line= 3
      2680989.43       6938744.1      2681312.34      6937931.62
      2681249.85      6937551.42
#Sta/Elev= 30
  4105.2  475.25  4111.7  475.61  4214.3  472.97    4313  469.16  4366.8  468.88
  4405.9  467.21  4420.6  467.63  4519.2  465.75  4651.5  462.52  4675.8  462.93
    4754  460.73    4808   461.3  4813.4  460.53  4818.8  461.32    4851  460.14
  4872.8  461.08  4937.1  460.23  4991.6  460.54  5010.5  459.38    5018  455.41
  5018.8  454.91  5023.3  455.41  5030.8  459.89  5040.9  461.13  5142.3     461
  5178.2   459.5  5182.8  458.92  5223.3  461.01  5314.6  463.04  5364.8  467.58
#Mann= 4 ,-1 , 0
  4105.2     .12       0    5018     .07       0  5023.3     .12       0
  5178.2     .05       0
Bank Sta=5018,5023.3
XS Rating Curve= 0 ,0
Exp/Cntr=0.3,0.1

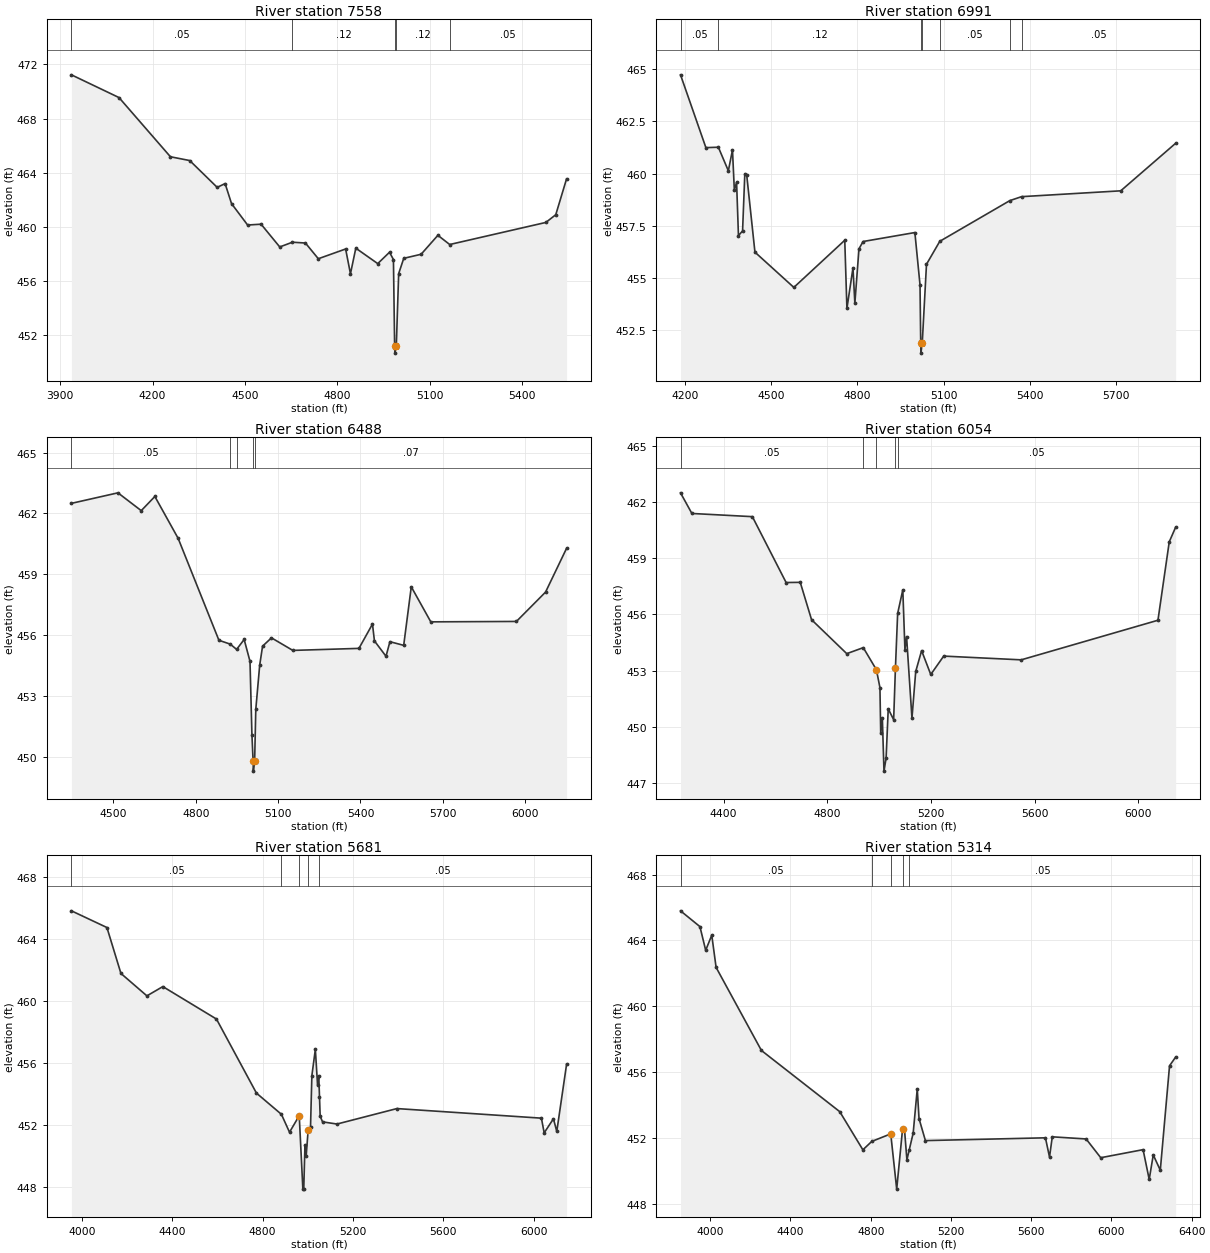
Type RM Length L Ch R = 1 ,7558    ,567,567,567
BEGIN DESCRIPTION:
Mapping XS 67d46e6e
END DESCRIPTION:
XS GIS Cut Line= 3
       2681744.5      6938929.02      2682043.12      6937935.96
      2681883.39      6937387.33
#Sta/Elev= 30
  3936.6  471.23  4091.2  469.55  4258.2  465.18  4320.9   464.9  4410.1  462.92
  4435.8   463.2  4456.7  461.72  4508.9  460.14  4552.7   460.2  4613.3  458.52
  4654.4  458.87  4696.8  458.81  4738.6  457.65  4827.3  458.37    4843  456.54
  4860.4  458.43  4931.6  457.29  4969.9  458.13  4982.6  457.59  4986.5  451.18
  4987.3  450.68  4991.9  451.18  4999.6  456.55  5016.1  457.68  5072.5  457.98
    5127  459.38  5165.4   458.7  5477.7  460.33  5509.9   460.9    5545  463.55
#Mann= 5 ,-1 , 0
  3936.6     .05       0  4654.4     .12       0  4986.5     .07       0
  4991.9     .12       0  5165.4     .05       0
Bank Sta=4986.5,4991.9
XS Rating Curve= 0 ,0
Exp/Cntr=0.3,0.1

Type RM Length L Ch R = 1 ,6991    ,503,503,503
BEGIN DESCRIPTION:
Mapping XS 249ffddd
END DESCRIPTION:
XS GIS Cut Line= 4
      2683057.24      6938694.15      2682559.58      6938100.83
       2682546.9       6938011.8      2681945.87      6937401.21
#Sta/Elev= 30
  4185.4  464.73  4273.6  461.24  4316.9  461.26  4351.7  460.13    4366  461.13
  4372.5   459.2  4380.3  459.58  4386.8  457.02  4401.1  457.25  4408.9  459.99
  4415.4  459.94  4444.1  456.23  4579.3  454.54  4756.3   456.8  4763.8  453.53
  4784.9  455.48  4791.4  453.78  4805.7  456.39    4820  456.74    5000  457.17
  5017.9  454.66  5020.3  451.89    5021  451.39  5025.7  451.89  5040.4  455.65
  5086.6  456.75    5330   458.7  5370.8  458.89  5715.6  459.17  5906.5  461.45
#Mann= 7 ,-1 , 0
  4185.4     .05       0  4316.9     .12       0  5020.3     .07       0
  5025.7     .12       0  5086.6     .05       0    5330     .12       0
  5370.8     .05       0
Bank Sta=5020.3,5025.7
XS Rating Curve= 0 ,0
Exp/Cntr=0.3,0.1

Type RM Length L Ch R = 1 ,6488    ,434,434,434
BEGIN DESCRIPTION:
Mapping XS 8a81427b
END DESCRIPTION:
XS GIS Cut Line= 3
      2683446.24      6938710.44      2682946.21       6938224.3
      2682210.55      6937398.42
#Sta/Elev= 30
  4347.2   462.5  4516.6  463.02  4601.5  462.14  4651.1  462.84    4736  460.77
  4884.4  455.74  4925.6  455.55  4948.9  455.29  4976.3  455.78  4997.6   454.7
  5004.6  451.08  5008.9  449.78  5009.8  449.28  5014.5  449.78  5018.7  452.33
  5032.9  454.51  5043.4  455.45  5075.8  455.86  5153.6  455.24  5394.4  455.34
  5443.7  456.54  5450.8  455.71    5493  454.95  5507.2  455.67  5557.4  455.49
    5585  458.38  5656.1  456.65  5967.9  456.67  6074.1  458.12  6150.6  460.28
#Mann= 5 ,-1 , 0
  4347.2     .05       0  4925.6     .12       0  4948.9     .07       0
  5008.9     .05       0  5014.5     .07       0
Bank Sta=5008.9,5014.5
XS Rating Curve= 0 ,0
Exp/Cntr=0.3,0.1

Type RM Length L Ch R = 1 ,6054    ,373,373,373
BEGIN DESCRIPTION:
Mapping XS 98fc60bd
END DESCRIPTION:
XS GIS Cut Line= 3
      2683510.51      6938808.56      2683344.73      6938060.72
      2682647.16      6937154.75
#Sta/Elev= 30
    4234  462.48  4277.8  461.38  4511.1  461.21  4641.2   457.7  4695.7  457.71
  4739.3  455.72  4875.1  453.91  4938.8  454.23  4989.5  453.05    5003   452.1
    5006   449.7  5012.3  450.48  5018.6  447.65  5026.8  448.34    5035  450.97
  5055.9  450.39  5062.7  453.12  5071.3  456.05  5091.2  457.31  5099.4  454.13
  5105.7  454.82  5126.5  450.47    5141  452.96  5163.7  454.07    5199   452.8
  5248.9  453.78  5547.8  453.58  6075.1  455.69  6118.7  459.87  6143.4  460.65
#Mann= 5 ,-1 , 0
    4234     .05       0  4938.8     .07       0  4989.5     .03       0
  5062.7     .07       0  5071.3     .05       0
Bank Sta=4989.5,5062.7
XS Rating Curve= 0 ,0
Exp/Cntr=0.3,0.1

Type RM Length L Ch R = 1 ,5681    ,367,367,367
BEGIN DESCRIPTION:
Mapping XS b380d977
END DESCRIPTION:
XS GIS Cut Line= 3
      2683477.37      6939072.98      2683731.72      6938101.94
      2683325.81      6936986.39
#Sta/Elev= 30
  3954.4  465.84  4111.5  464.76  4173.5  461.79  4288.4  460.34  4358.9  460.94
  4596.2  458.84  4773.1  454.05  4883.5  452.68  4919.4  451.52  4962.4  452.59
  4978.5  447.84  4982.4  447.84  4987.7  450.69    4993  449.96  5001.8  451.65
  5012.4  451.87  5018.3  455.18  5033.7  456.88  5043.5  454.57  5048.8  455.18
    5052  453.83    5055  452.56  5065.6  452.19  5129.5  452.05  5394.6  453.05
    6034  452.43  6046.2  451.48  6087.2  452.39    6102  451.57  6145.3  455.91
#Mann= 5 ,-1 , 0
  3954.4     .05       0  4883.5     .05       0  4962.4     .03       0
  5001.8     .05       0    5052     .05       0
Bank Sta=4962.4,5001.8
XS Rating Curve= 0 ,0
Exp/Cntr=0.3,0.1

Type RM Length L Ch R = 1 ,5314    ,601,601,601
BEGIN DESCRIPTION:
Mapping XS 88b10ea8
END DESCRIPTION:
XS GIS Cut Line= 3
       2683502.9      6939109.96      2684069.63      6938119.82
      2683848.16      6936810.88
#Sta/Elev= 30
  3851.9   465.8  3948.7  464.84  3977.4   463.4  4007.7  464.32  4029.3  462.36
  4255.2  457.31  4645.7  453.59    4761  451.27  4805.3  451.78  4899.9  452.24
  4929.6  448.88  4958.9  452.54  4968.4  452.52  4980.5  450.66    4992  451.26
  5011.8  452.29  5032.1  454.97  5040.9  453.17  5072.7  451.83  5671.1     452
  5691.4  450.83  5705.2  452.06  5873.9  451.93  5946.8  450.79  6157.9  451.28
  6188.4  449.47  6208.6  450.96  6243.7  450.03  6289.8  456.38  6320.3  456.91
#Mann= 5 ,-1 , 0
  3851.9     .05       0  4805.3     .07       0  4899.9     .03       0
  4958.9     .07       0    4992     .05       0
Bank Sta=4899.9,4958.9
XS Rating Curve= 0 ,0
Exp/Cntr=0.3,0.1

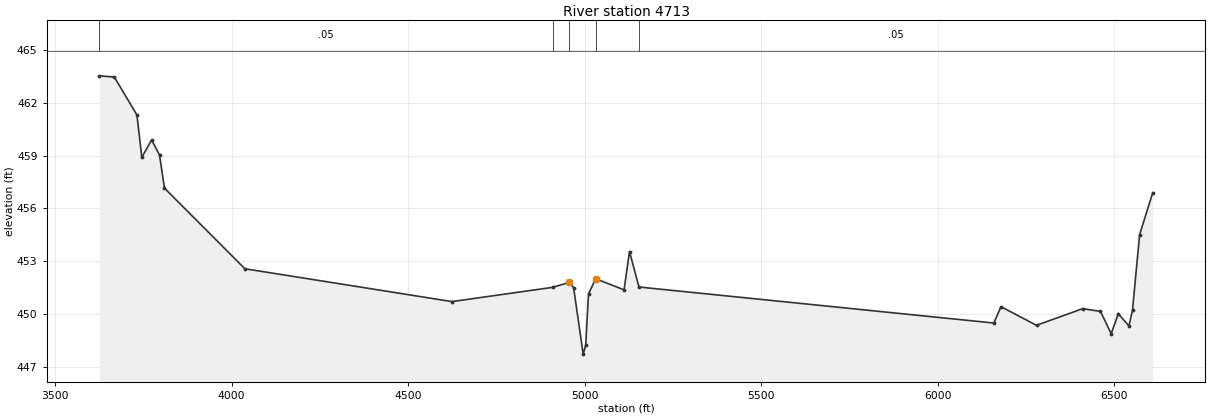
Type RM Length L Ch R = 1 ,4713    ,0,0,0
BEGIN DESCRIPTION:
Mapping XS ebe1b0a3
END DESCRIPTION:
XS GIS Cut Line= 4
       2683692.1      6939295.96      2684367.51      6938755.03
      2684556.08      6938281.84      2684365.34      6936684.09
#Sta/Elev= 30
  3625.3  463.55  3667.8  463.48  3731.8  461.32  3745.6  458.91  3773.4   459.9
  3795.8  459.04  3809.7  457.16  4037.5  452.57  4624.1   450.7  4908.9  451.51
  4955.9  451.79  4968.6   451.5  4995.8  447.71  5002.9  448.21  5010.9  451.14
  5031.1     452  5111.6  451.37    5127  453.55  5153.8  451.53    6159  449.48
  6179.2  450.41  6279.9  449.35  6410.8   450.3  6461.1  450.14  6491.4  448.87
  6511.5  450.01  6541.7  449.31  6551.8  450.22  6571.9  454.51  6609.1   456.9
#Mann= 5 ,-1 , 0
  3625.3     .05       0  4908.9     .07       0  4955.9     .03       0
  5031.1     .07       0  5153.8     .05       0
Bank Sta=4955.9,5031.1
XS Rating Curve= 0 ,0
Exp/Cntr=0.3,0.1

Chan Stop Cuts=-1
Use User Specified Reach Order=0
Composite Channel Slope=5