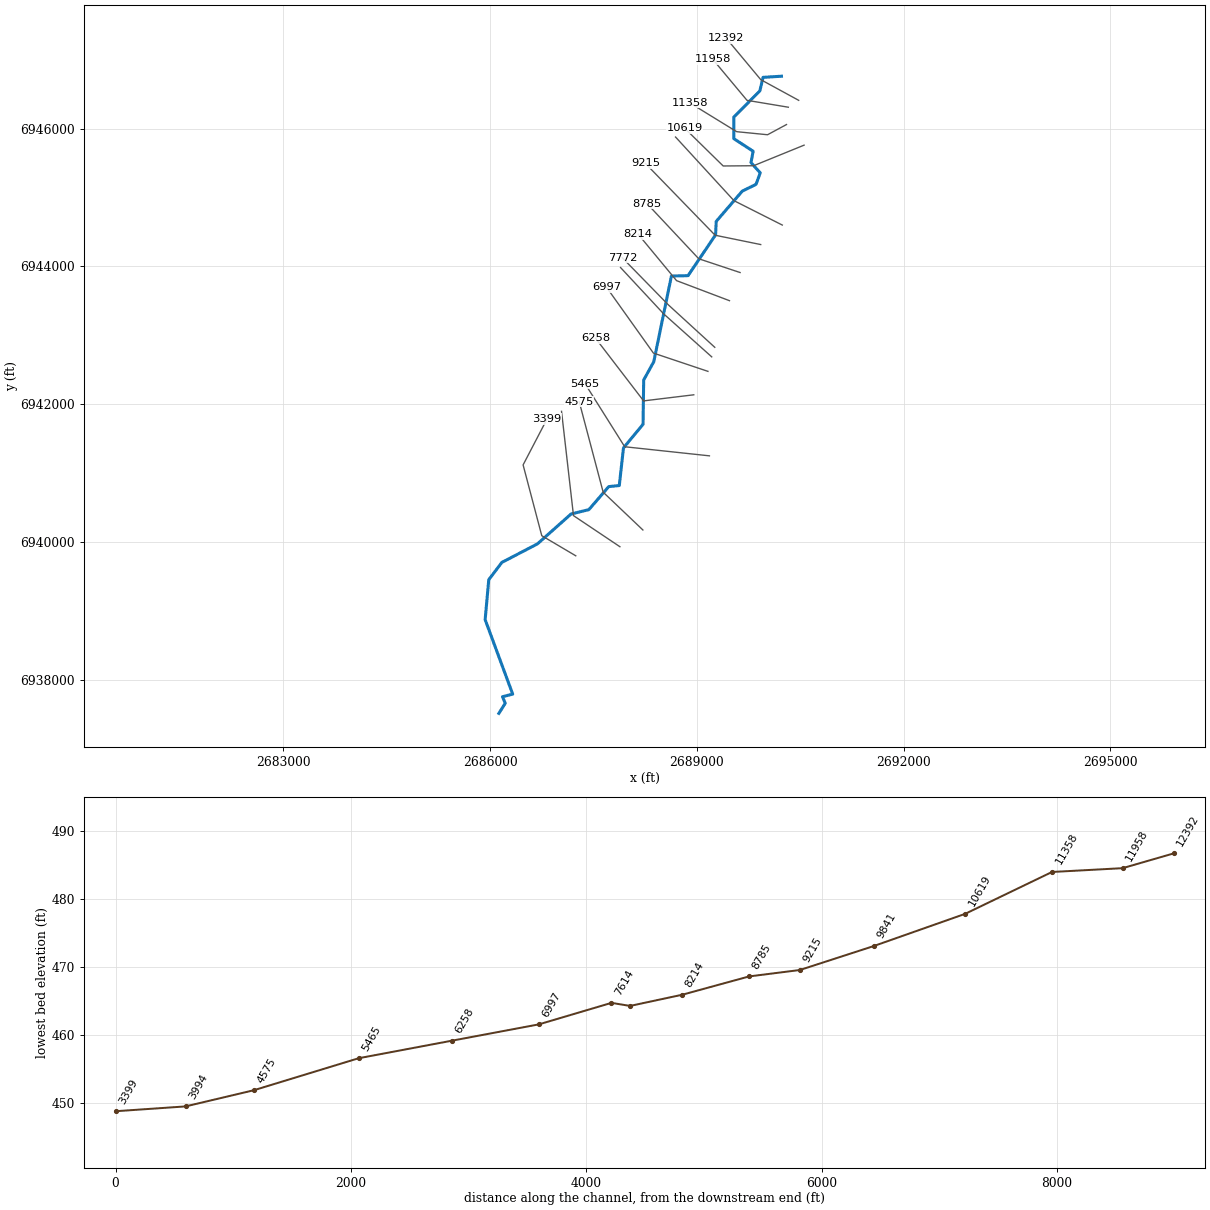
--- Muddy T6.prj (project) ---

Proj Title=Muddy T6 Base Level Engineering
Current Plan=p01
Default Exp/Contr=0.3,0.1
English Units
Geom File=g01
Flow File=f01
Plan File=p01
BEGIN DESCRIPTION:
Muddy T6
END DESCRIPTION:

--- Muddy T6.p01 (plan) ---

Plan Title=Multiple Run
Short Identifier=Multiple
Geom File=g01
Flow File=f01
Subcritical Flow
K Sum by GR= 0
Std Step Tol= 0.01
Critical Tol= 0.01
Num of Std Step Trials= 20
Max Error Tol= 0.3
Flow Tol Ratio= 0.001
Split Flow NTrial= 30
Split Flow Tol= 0.02
Split Flow Ratio= 0.02
Log Output Level= 0
Friction Slope Method= 1
Unsteady Friction Slope Method= 2
Unsteady Bridges Friction Slope Method= 1
Parabolic Critical Depth
Global Vel Dist=  1 , 1 , 1
Global Log Level= 0
CheckData=True
Encroach Param= -1, 0, 0, 0
BEGIN DESCRIPTION:
Multiple Run
END DESCRIPTION:

--- Muddy T6.f01 (steady flow) ---

Flow Title=Multiple
Number of Profiles=7
Profile Names=10-year,25-year,50-year,1pct_min,100-year,1pct_plu,500-year
River Rch & RM= Muddy T6,Reach-1,12392
     506     668     797     472     942    1879    1313
River Rch & RM= Muddy T6,Reach-1,9215
     955    1305    1592     962    1920    3831    2792
Boundary for River Rch & Prof#=Muddy T6,Reach-1,1
Up Type=0
Dn Type=3
Dn Slope=0.005
Boundary for River Rch & Prof#=Muddy T6,Reach-1,2
Up Type=0
Dn Type=3
Dn Slope=0.005
Boundary for River Rch & Prof#=Muddy T6,Reach-1,3
Up Type=0
Dn Type=3
Dn Slope=0.005
Boundary for River Rch & Prof#=Muddy T6,Reach-1,4
Up Type=0
Dn Type=3
Dn Slope=0.005
Boundary for River Rch & Prof#=Muddy T6,Reach-1,5
Up Type=0
Dn Type=3
Dn Slope=0.005
Boundary for River Rch & Prof#=Muddy T6,Reach-1,6
Up Type=0
Dn Type=3
Dn Slope=0.005
Boundary for River Rch & Prof#=Muddy T6,Reach-1,7
Up Type=0
Dn Type=3
Dn Slope=0.005

--- Muddy T6.g01 (geometry) ---

Geom Title=Existing Conditions

River Reach=Muddy T6,Reach-1
Reach XY= 30
      2690226.00      6946761.00      2689959.29      6946744.63
      2689912.47      6946547.60      2689535.01      6946168.02
      2689535.13      6945854.26      2689815.56      6945671.49
      2689783.80      6945507.58      2689918.38      6945357.67
      2689856.65      6945190.96      2689655.84      6945091.37
      2689279.07      6944652.70      2689270.53      6944458.55
      2688870.75      6943865.62      2688629.44      6943859.78
      2688373.75      6942616.93      2688227.20      6942350.50
      2688217.76      6941707.77      2687933.82      6941364.41
      2687873.09      6940818.91      2687719.81      6940803.18
      2687432.17      6940468.86      2687173.57      6940405.48
      2686686.32      6939972.11      2686169.94      6939702.86
      2685979.46      6939452.54      2685926.77      6938871.69
      2686326.55      6937790.37      2686178.52      6937752.89
      2686218.18      6937657.62      2686126.00      6937511.00

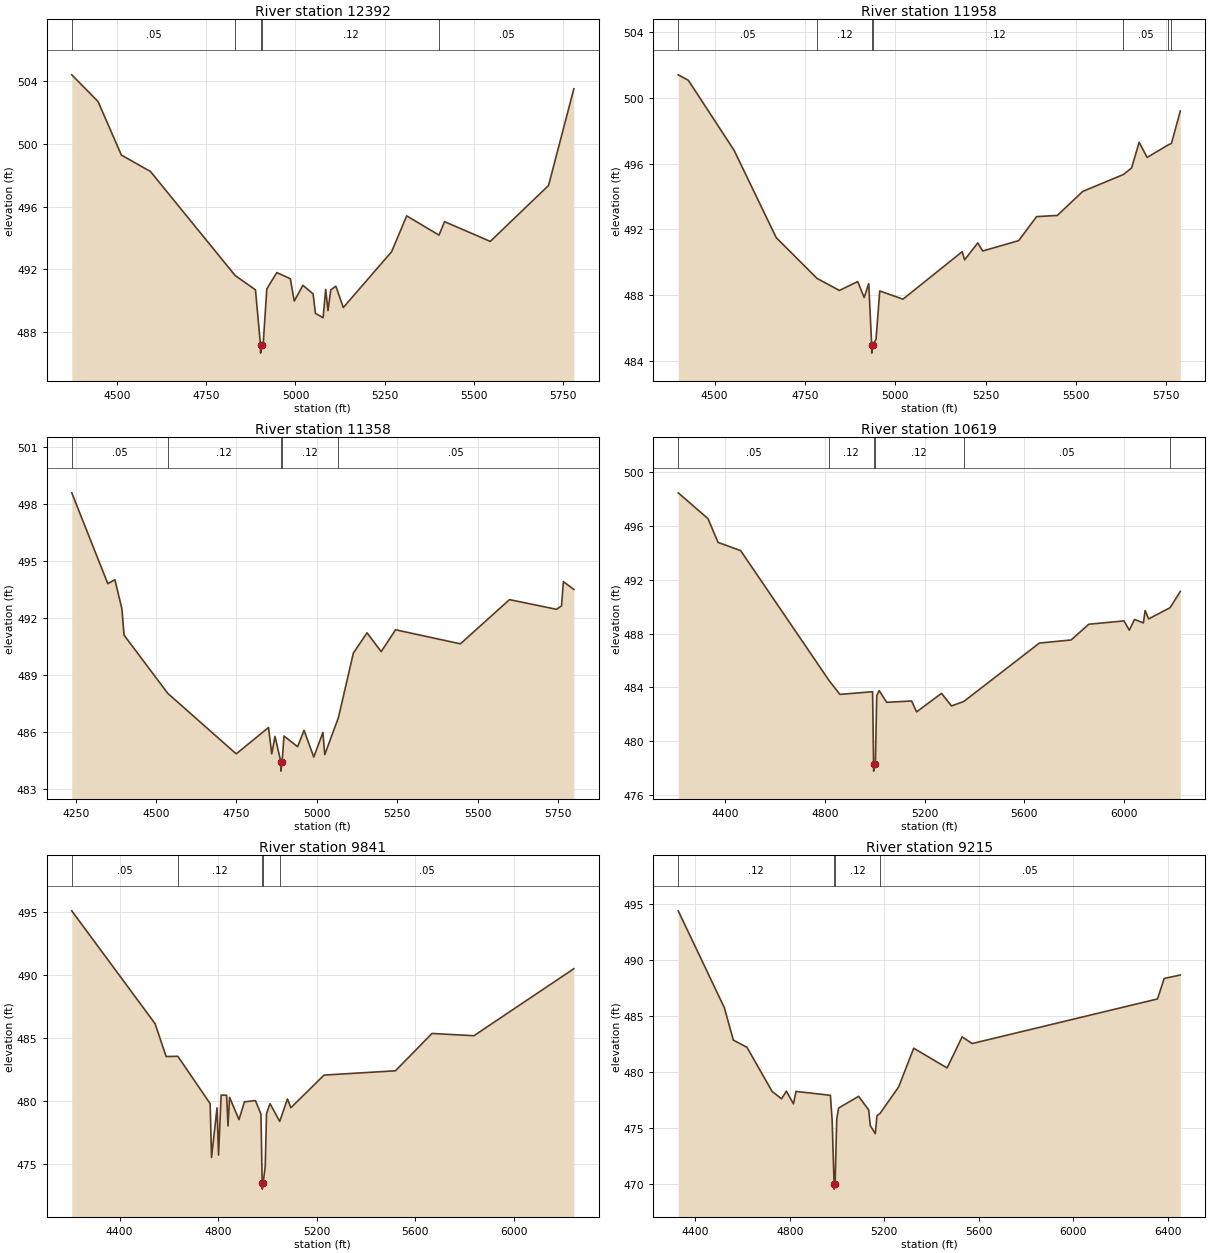
Type RM Length L Ch R = 1,12392,434,434,434
BEGIN DESCRIPTION:
Muddy T6 14.0
END DESCRIPTION:
XS GIS Cut Line= 3
      2690476.01      6946410.99      2689926.00      6946711.00
      2689426.02      6947310.97
#Sta/Elev= 30
  4372.9  504.41  4446.5  502.71  4512.0  499.29  4593.6  498.24  4831.0  491.60
  4887.9  490.69  4902.0  487.15  4902.3  486.65  4906.0  487.15  4909.7  487.29
  4919.7  490.75  4947.7  491.79  4985.6  491.40  4996.6  489.97  5020.9  490.98
  5049.5  490.43  5056.0  489.19  5077.5  488.91  5084.7  490.72  5091.2  489.36
  5099.0  490.69  5113.3  490.92  5134.1  489.56  5269.5  493.12  5311.8  495.41
  5402.5  494.18  5417.9  495.04  5546.1  493.78  5709.5  497.35  5780.4  503.52
#Mann=5,-1,0
  4372.9    0.05       0  4831.0    0.12       0  4902.0    0.07       0
  4906.0    0.12       0  5402.5    0.05       0
Bank Sta=4902,4906
Exp/Cntr=0.3,0.1

Type RM Length L Ch R = 1,11958,600,600,600
BEGIN DESCRIPTION:
Muddy T6 13.0
END DESCRIPTION:
XS GIS Cut Line= 3
      2690325.98      6946311.00      2689726.00      6946411.00
      2689225.99      6947011.02
#Sta/Elev= 30
  4399.6  501.40  4427.5  501.07  4554.2  496.81  4670.8  491.50  4783.9  489.02
  4845.6  488.29  4896.3  488.83  4914.1  487.86  4926.7  488.71  4934.9  484.98
  4935.1  484.48  4938.9  484.98  4947.0  485.34  4957.2  488.26  5021.5  487.76
  5185.5  490.65  5192.0  490.15  5228.5  491.18  5242.2  490.69  5341.7  491.32
  5391.2  492.78  5448.5  492.85  5518.8  494.31  5631.5  495.34  5654.2  495.74
  5675.0  497.30  5697.1  496.38  5756.2  497.15  5764.4  497.23  5788.9  499.20
#Mann=7,-1,0
  4399.6    0.05       0  4783.9    0.12       0  4934.9    0.07       0
  4938.9    0.12       0  5631.5    0.05       0  5756.2    0.12       0
  5764.4    0.05       0
Bank Sta=4934.9,4938.9
Exp/Cntr=0.3,0.1

Type RM Length L Ch R = 1,11358,739,739,739
BEGIN DESCRIPTION:
Muddy T6 12.0
END DESCRIPTION:
XS GIS Cut Line= 4
      2690299.12      6946059.50      2690024.21      6945911.35
      2689576.41      6945955.80      2688895.40      6946374.27
#Sta/Elev= 30
  4237.7  498.59  4349.8  493.80  4371.7  494.01  4393.6  492.48  4400.3  491.09
  4536.3  488.02  4749.2  484.83  4849.7  486.22  4859.7  484.83  4869.8  485.75
  4887.9  484.42  4888.1  483.92  4891.9  484.42  4897.8  485.77  4940.1  485.21
  4960.2  486.07  4990.4  484.66  5018.8  485.96  5024.6  484.79  5067.2  486.75
  5113.5  490.14  5156.1  491.21  5200.0  490.22  5244.9  491.37  5446.5  490.63
  5599.1  492.96  5745.5  492.45  5761.0  492.63  5766.8  493.91  5799.3  493.50
#Mann=5,-1,0
  4237.7    0.05       0  4536.3    0.12       0  4887.9    0.07       0
  4891.9    0.12       0  5067.2    0.05       0
Bank Sta=4887.9,4891.9
Exp/Cntr=0.3,0.1

Type RM Length L Ch R = 1,10619,778,778,778
BEGIN DESCRIPTION:
Mapping XS 2d0ec69e
END DESCRIPTION:
XS GIS Cut Line= 4
      2690554.08      6945760.07      2689821.46      6945461.46
      2689380.49      6945457.99      2688821.80      6946006.27
#Sta/Elev= 30
  4211.6  498.47  4331.0  496.55  4371.5  494.78  4462.1  494.17  4816.3  484.52
  4860.5  483.47  4991.6  483.67  4995.6  478.26  4995.8  477.76  4999.6  478.26
  5002.7  478.26  5008.2  483.39  5018.2  483.75  5048.2  482.88  5148.2  482.98
  5168.2  482.17  5268.2  483.55  5308.2  482.61  5357.3  482.94  5661.1  487.29
  5788.4  487.52  5859.1  488.69  6000.6  488.94  6021.8  488.25  6043.0  489.05
  6078.4  488.79  6085.4  489.71  6099.6  489.09  6185.4  489.92  6226.5  491.13
#Mann=6,-1,0
  4211.6    0.05       0  4816.3    0.12       0  4995.6    0.07       0
  4999.6    0.12       0  5357.3    0.05       0  6185.4    0.12       0
Bank Sta=4995.6,4999.6
Exp/Cntr=0.3,0.1

Type RM Length L Ch R = 1,9841,626,626,626
BEGIN DESCRIPTION:
Mapping XS 89bda13f
END DESCRIPTION:
XS GIS Cut Line= 3
      2690238.13      6944600.35      2689536.74      6944954.52
      2688689.50      6945878.15
#Sta/Elev= 30
  4205.4  495.08  4543.9  486.13  4588.7  483.53  4636.1  483.55  4767.4  479.80
  4773.0  475.53  4795.3  479.46  4801.5  475.72  4812.0  480.47  4834.3  480.46
  4839.9  478.03  4846.3  480.30  4884.5  478.53  4906.8  479.94  4951.4  480.04
  4973.7  478.97  4978.8  473.52  4979.0  473.02  4982.8  473.52  4991.1  474.84
  4996.4  479.01  5010.6  479.80  5049.9  478.39  5081.4  480.17  5095.1  479.47
  5230.1  482.06  5519.9  482.40  5668.5  485.36  5838.7  485.18  6244.5  490.49
#Mann=5,-1,0
  4205.4    0.05       0  4636.1    0.12       0  4978.8    0.07       0
  4982.8    0.12       0  5049.9    0.05       0
Bank Sta=4978.8,4982.8
Exp/Cntr=0.3,0.1

Type RM Length L Ch R = 1,9215,430,430,430
BEGIN DESCRIPTION:
Mapping XS ad8e4357
END DESCRIPTION:
XS GIS Cut Line= 3
      2689924.68      6944317.25      2689263.24      6944452.67
      2688252.81      6945494.35
#Sta/Elev= 30
  4327.8  494.40  4523.2  485.73  4561.2  482.84  4619.0  482.19  4725.0  478.26
  4765.3  477.59  4785.8  478.27  4815.7  477.14  4826.6  478.25  4972.2  477.90
  4979.7  475.67  4987.8  470.01  4988.1  469.51  4992.1  470.01  4999.0  475.76
  5006.9  476.76  5091.8  477.81  5134.2  476.60  5141.2  475.19  5162.5  474.47
  5169.5  476.08  5182.6  476.28  5261.5  478.66  5325.1  482.11  5466.6  480.35
  5530.1  483.13  5572.6  482.53  6357.6  486.52  6385.9  488.35  6454.2  488.66
#Mann=4,-1,0
  4327.8    0.12       0  4987.8    0.07       0  4992.1    0.12       0
  5182.6    0.05       0
Bank Sta=4987.8,4992.1
Exp/Cntr=0.3,0.1

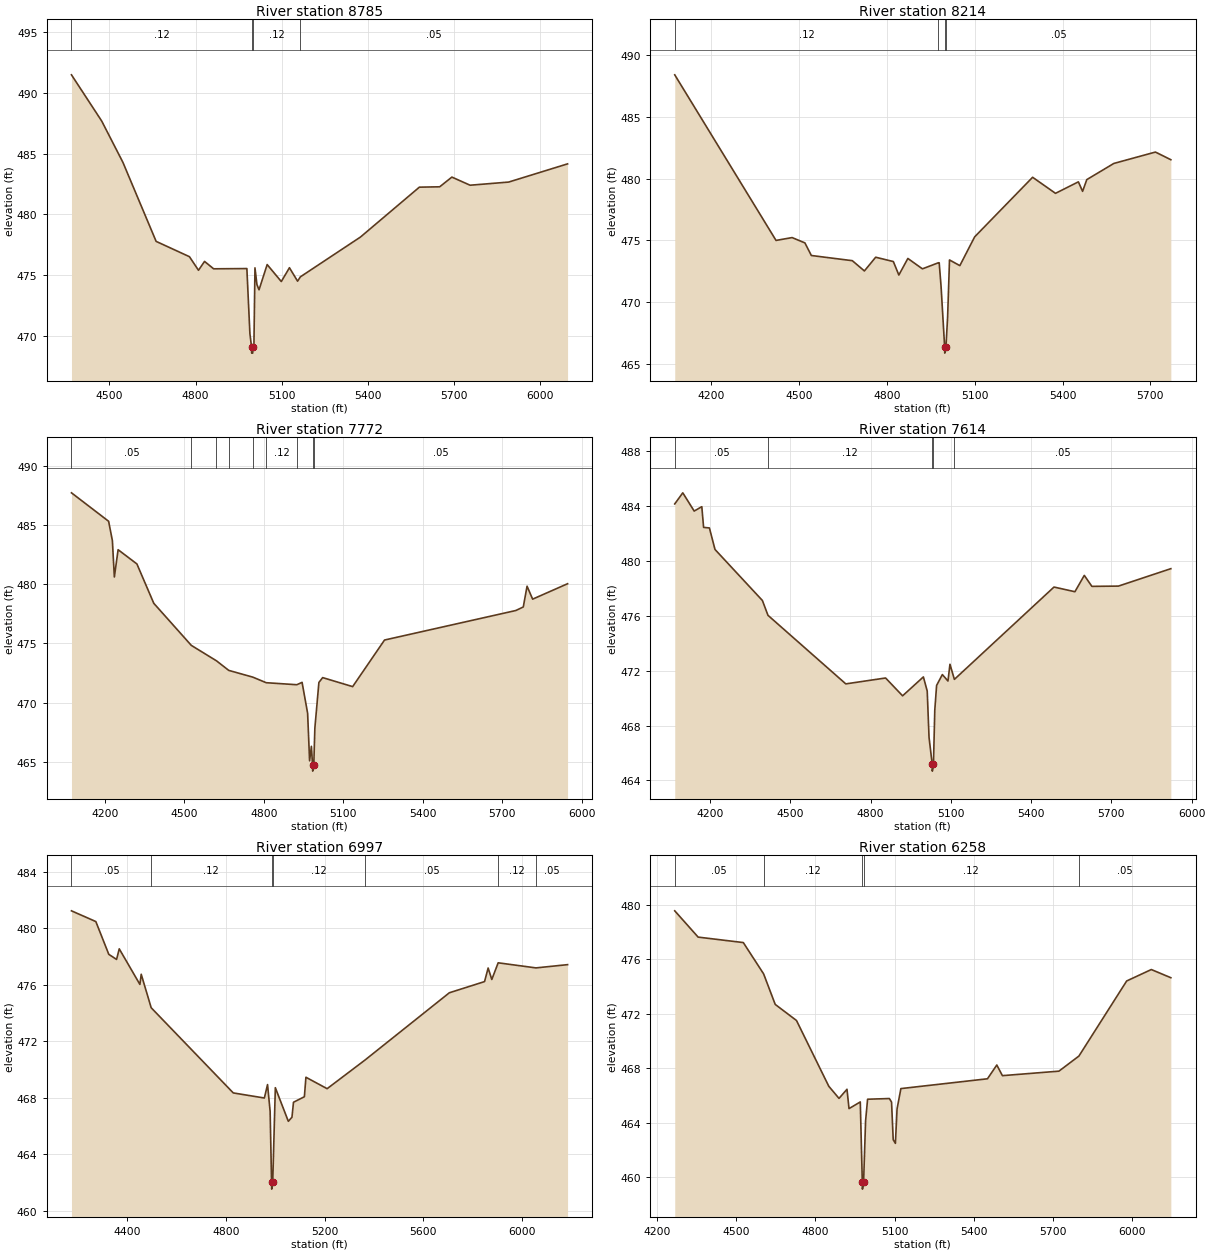
Type RM Length L Ch R = 1,8785,571,571,571
BEGIN DESCRIPTION:
Muddy T6 7.0
END DESCRIPTION:
XS GIS Cut Line= 3
      2689625.97      6943911.01      2689026.00      6944111.00
      2688276.01      6944910.99
#Sta/Elev= 30
  4367.6  491.51  4473.0  487.70  4546.8  484.30  4662.7  477.78  4778.7  476.52
  4810.3  475.40  4831.4  476.13  4863.0  475.52  4978.9  475.54  4989.5  470.18
  4995.2  469.07  4995.6  468.57  4999.2  468.57  4999.5  469.07  5003.4  469.07
  5007.1  475.60  5014.0  474.22  5021.3  473.79  5049.6  475.87  5098.9  474.47
  5127.3  475.61  5155.6  474.50  5165.5  474.86  5374.9  478.14  5580.1  482.25
  5650.9  482.28  5693.4  483.08  5756.9  482.41  5891.2  482.67  6096.6  484.17
#Mann=4,-1,0
  4367.6    0.12       0  4995.2    0.07       0  4999.5    0.12       0
  5165.5    0.05       0
Bank Sta=4995.2,4999.5
Exp/Cntr=0.3,0.1

Type RM Length L Ch R = 1,8214,442,442,442
BEGIN DESCRIPTION:
Mapping XS ba752101
END DESCRIPTION:
XS GIS Cut Line= 3
      2689471.75      6943502.31      2688703.84      6943793.42
      2688147.36      6944466.40
#Sta/Elev= 30
  4075.3  488.39  4421.3  474.99  4476.2  475.22  4519.9  474.79  4541.9  473.77
  4681.9  473.35  4723.1  472.52  4761.7  473.63  4822.0  473.28  4840.8  472.19
  4871.6  473.53  4921.3  472.69  4975.6  473.18  4978.6  473.18  4985.1  471.23
  4997.2  466.37  4997.6  465.87  5001.6  466.37  5007.3  468.76  5013.8  473.41
  5049.1  472.95  5099.8  475.28  5297.7  480.10  5375.9  478.80  5454.0  479.73
  5468.4  478.96  5482.7  479.91  5575.2  481.22  5717.2  482.14  5769.8  481.52
#Mann=4,-1,0
  4075.3    0.12       0  4975.6    0.05       0  4997.2    0.03       0
  5001.6    0.05       0
Bank Sta=4997.2,5001.6
Exp/Cntr=0.3,0.1

Type RM Length L Ch R = 1,7772,158,158,158
BEGIN DESCRIPTION:
Mapping XS 6917c696
END DESCRIPTION:
XS GIS Cut Line= 3
      2689258.59      6942825.23      2688581.53      6943445.00
      2687915.50      6944126.63
#Sta/Elev= 30
  4074.8  487.71  4214.9  485.31  4229.1  483.68  4236.5  480.61  4250.7  482.91
  4321.6  481.71  4385.2  478.39  4526.7  474.84  4621.4  473.54  4667.9  472.73
  4758.6  472.16  4809.2  471.69  4924.7  471.52  4944.5  471.72  4965.4  469.11
  4972.8  465.10  4979.6  466.32  4984.0  464.73  4984.5  464.23  4988.6  464.73
  4992.7  467.86  5007.9  471.71  5022.1  472.12  5135.2  471.36  5255.4  475.29
  5750.4  477.78  5778.7  478.08  5792.9  479.83  5814.0  478.74  5945.7  480.04
#Mann=9,-1,0
  4074.8    0.05       0  4526.7    0.12       0  4621.4    0.05       0
  4667.9    0.12       0  4758.6    0.05       0  4809.2    0.12       0
  4924.7    0.05       0  4984.0    0.03       0  4988.6    0.05       0
Bank Sta=4984,4988.6
Exp/Cntr=0.3,0.1

Type RM Length L Ch R = 1,7614,617,617,617
BEGIN DESCRIPTION:
Mapping XS e1a40106
END DESCRIPTION:
XS GIS Cut Line= 3
      2689214.27      6942686.65      2688516.37      6943311.63
      2687891.34      6943983.53
#Sta/Elev= 30
  4067.7  484.16  4097.8  484.97  4140.4  483.64  4168.9  483.96  4175.6  482.45
  4197.3  482.41  4218.2  480.84  4395.4  477.12  4416.2  476.04  4707.1  471.04
  4855.9  471.47  4919.5  470.17  4997.2  471.55  5011.5  470.52  5018.3  467.15
  5030.2  465.18  5030.6  464.68  5034.8  465.18  5039.8  469.13  5046.6  470.93
  5068.1  471.72  5089.1  471.25  5096.5  472.47  5113.1  471.37  5485.4  478.10
  5563.6  477.76  5598.7  478.95  5627.1  478.15  5726.3  478.17  5922.2  479.44
#Mann=5,-1,0
  4067.7    0.05       0  4416.2    0.12       0  5030.2    0.07       0
  5034.8    0.12       0  5113.1    0.05       0
Bank Sta=5030.2,5034.8
Exp/Cntr=0.3,0.1

Type RM Length L Ch R = 1,6997,739,739,739
BEGIN DESCRIPTION:
Mapping XS c1e5d1c9
END DESCRIPTION:
XS GIS Cut Line= 3
      2689159.66      6942476.25      2688367.99      6942741.87
      2687685.67      6943700.25
#Sta/Elev= 30
  4173.4  481.22  4272.2  480.46  4324.7  478.14  4356.3  477.78  4367.1  478.53
  4450.9  476.01  4456.2  476.73  4496.6  474.36  4829.4  468.33  4955.5  467.97
  4968.4  468.92  4978.9  467.02  4984.7  462.02  4985.2  461.52  4989.4  462.02
  5000.0  468.70  5052.7  466.32  5067.4  466.61  5073.6  467.67  5117.8  468.06
  5124.0  469.44  5210.0  468.63  5363.0  470.65  5705.6  475.42  5848.2  476.21
  5862.9  477.17  5877.7  476.36  5903.5  477.54  6056.8  477.18  6184.9  477.41
#Mann=7,-1,0
  4173.4    0.05       0  4496.6    0.12       0  4984.7    0.07       0
  4989.4    0.12       0  5363.0    0.05       0  5903.5    0.12       0
  6056.8    0.05       0
Bank Sta=4984.7,4989.4
Exp/Cntr=0.3,0.1

Type RM Length L Ch R = 1,6258,793,793,793
BEGIN DESCRIPTION:
Muddy T6 2.0
END DESCRIPTION:
XS GIS Cut Line= 3
      2688954.04      6942136.08      2688226.00      6942047.53
      2687528.09      6942957.51
#Sta/Elev= 30
  4266.6  479.55  4355.3  477.62  4526.5  477.22  4603.5  474.92  4647.4  472.68
  4728.0  471.50  4850.5  466.67  4889.2  465.78  4919.4  466.45  4927.1  465.03
  4969.8  465.52  4977.5  459.62  4978.0  459.12  4982.3  459.62  4989.9  464.13
  4997.5  465.72  5080.1  465.77  5088.3  465.51  5094.6  462.75  5102.9  462.48
  5109.2  465.01  5123.7  466.50  5451.8  467.22  5487.2  468.23  5508.5  467.45
  5722.7  467.78  5798.5  468.89  5979.4  474.40  6072.8  475.24  6146.8  474.64
#Mann=5,-1,0
  4266.6    0.05       0  4603.5    0.12       0  4977.5    0.07       0
  4982.3    0.12       0  5798.5    0.05       0
Bank Sta=4977.5,4982.3
Exp/Cntr=0.3,0.1

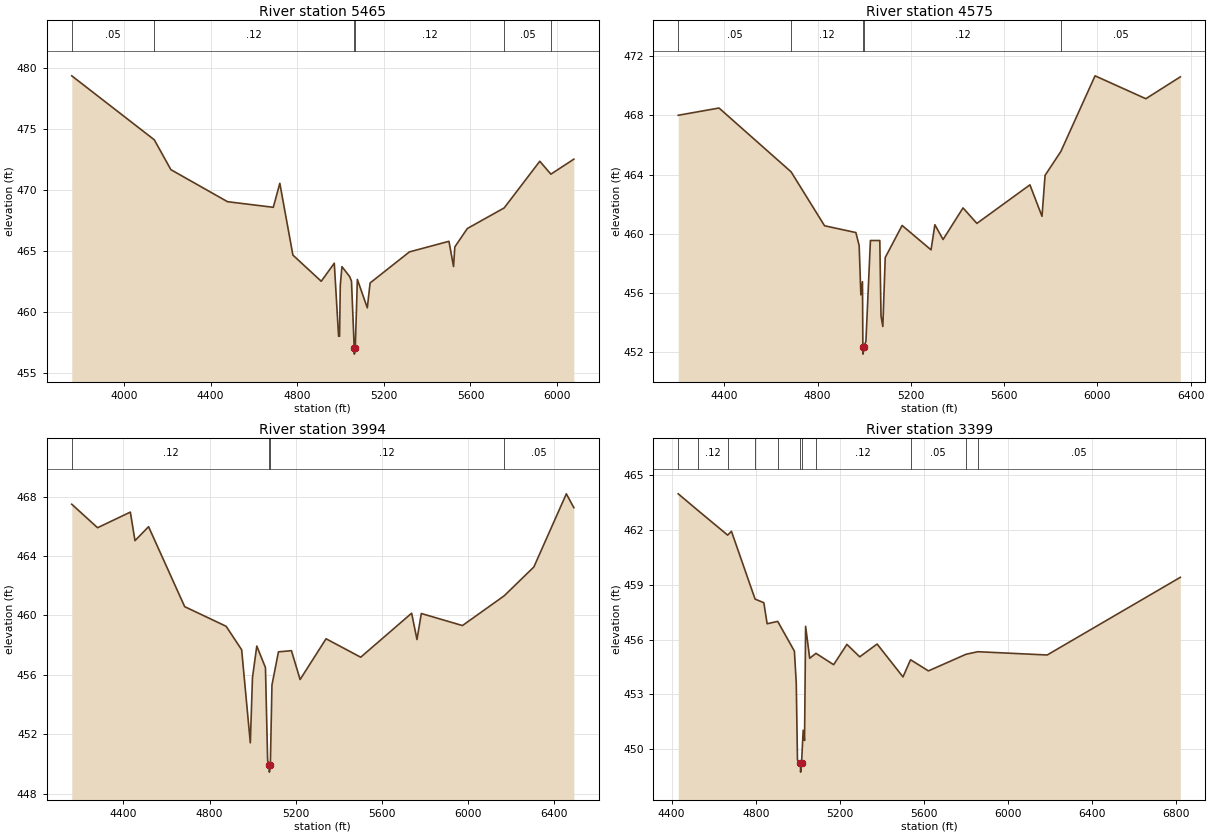
Type RM Length L Ch R = 1,5465,890,890,890
BEGIN DESCRIPTION:
Mapping XS 9267c813
END DESCRIPTION:
XS GIS Cut Line= 3
      2689180.90      6941249.80      2687951.75      6941381.74
      2687376.12      6942297.20
#Sta/Elev= 30
  3759.5  479.38  4140.5  474.13  4217.0  471.68  4478.5  469.05  4689.7  468.59
  4719.9  470.56  4780.2  464.67  4911.0  462.52  4971.3  464.00  4991.1  458.01
  4995.7  458.01  4998.9  462.15  5006.6  463.72  5042.1  462.91  5050.7  462.53
  5063.3  457.04  5063.9  456.54  5068.2  457.04  5077.8  462.67  5123.7  460.34
  5136.6  462.38  5318.1  464.93  5500.6  465.80  5521.8  463.73  5527.7  465.34
  5585.5  466.85  5755.6  468.54  5919.9  472.37  5971.1  471.31  6077.1  472.54
#Mann=6,-1,0
  3759.5    0.05       0  4140.5    0.12       0  5063.3    0.07       0
  5068.2    0.12       0  5755.6    0.05       0  5971.1    0.12       0
Bank Sta=5063.3,5068.2
Exp/Cntr=0.3,0.1

Type RM Length L Ch R = 1,4575,581,581,581
BEGIN DESCRIPTION:
Mapping XS a0bfbae3
END DESCRIPTION:
XS GIS Cut Line= 3
      2688215.65      6940173.40      2687639.25      6940722.02
      2687292.03      6942034.51
#Sta/Elev= 30
  4202.2  468.01  4377.2  468.50  4686.3  464.18  4829.8  460.53  4964.1  460.07
  4978.2  459.19  4985.5  455.85  4992.4  456.74  4994.1  452.34  4994.8  451.84
  4999.3  452.34  5007.2  452.72  5026.5  459.53  5066.7  459.53  5071.9  454.43
  5079.7  453.71  5090.0  458.38  5162.4  460.55  5286.5  458.90  5303.0  460.60
  5338.1  459.60  5423.7  461.74  5483.1  460.69  5710.6  463.30  5762.4  461.17
  5775.5  463.94  5843.3  465.56  5989.9  470.68  6207.8  469.13  6355.6  470.61
#Mann=5,-1,0
  4202.2    0.05       0  4686.3    0.12       0  4994.1    0.07       0
  4999.3    0.12       0  5843.3    0.05       0
Bank Sta=4994.1,4999.3
Exp/Cntr=0.3,0.1

Type RM Length L Ch R = 1,3994,595,595,595
BEGIN DESCRIPTION:
Mapping XS af3da471
END DESCRIPTION:
XS GIS Cut Line= 3
      2687882.31      6939930.35      2687208.70      6940381.74
      2687035.09      6941895.65
#Sta/Elev= 30
  4159.5  467.48  4279.4  465.90  4431.9  466.95  4453.5  465.03  4516.6  465.97
  4684.6  460.59  4877.3  459.27  4949.5  457.69  4989.8  451.43  4999.8  455.82
  5019.9  457.94  5060.2  456.49  5070.3  450.24  5077.7  449.96  5078.4  449.46
  5082.9  449.96  5090.4  455.32  5120.6  457.55  5181.0  457.63  5221.3  455.69
  5342.0  458.43  5503.1  457.19  5739.9  460.15  5764.8  458.38  5784.9  460.13
  5976.2  459.32  6170.3  461.32  6308.3  463.26  6459.3  468.18  6494.2  467.25
#Mann=4,-1,0
  4159.5    0.12       0  5077.7    0.07       0  5082.9    0.12       0
  6170.3    0.05       0
Bank Sta=5077.7,5082.9
Exp/Cntr=0.3,0.1

Type RM Length L Ch R = 1,3399,0,0,0
BEGIN DESCRIPTION:
Mapping XS 4a0dc27e
END DESCRIPTION:
XS GIS Cut Line= 4
      2687241.42      6939798.77      2686748.39      6940090.42
      2686477.56      6941118.20      2686824.80      6941784.90
#Sta/Elev= 30
  4431.5  463.98  4523.3  463.09  4666.6  461.72  4684.5  461.93  4796.9  458.22
  4838.6  458.02  4854.2  456.87  4904.5  457.00  4983.9  455.37  4992.7  453.64
  4998.5  449.41  5012.6  449.25  5013.4  448.75  5017.9  449.25  5025.6  451.04
  5032.1  450.48  5037.2  456.73  5056.6  454.98  5086.5  455.25  5170.4  454.63
  5233.6  455.74  5294.5  455.06  5377.2  455.76  5500.2  453.96  5536.2  454.90
  5621.1  454.29  5800.0  455.20  5856.1  455.34  6185.8  455.16  6818.9  459.41
#Mann=11,-1,0
  4431.5    0.05       0  4523.3    0.12       0  4666.6    0.05       0
  4796.9    0.12       0  4904.5    0.05       0  5012.6    0.03       0
  5017.9    0.05       0  5086.5    0.12       0  5536.2    0.05       0
  5800.0    0.12       0  5856.1    0.05       0
Bank Sta=5012.6,5017.9
Exp/Cntr=0.3,0.1

Chan Stop Cuts=-1