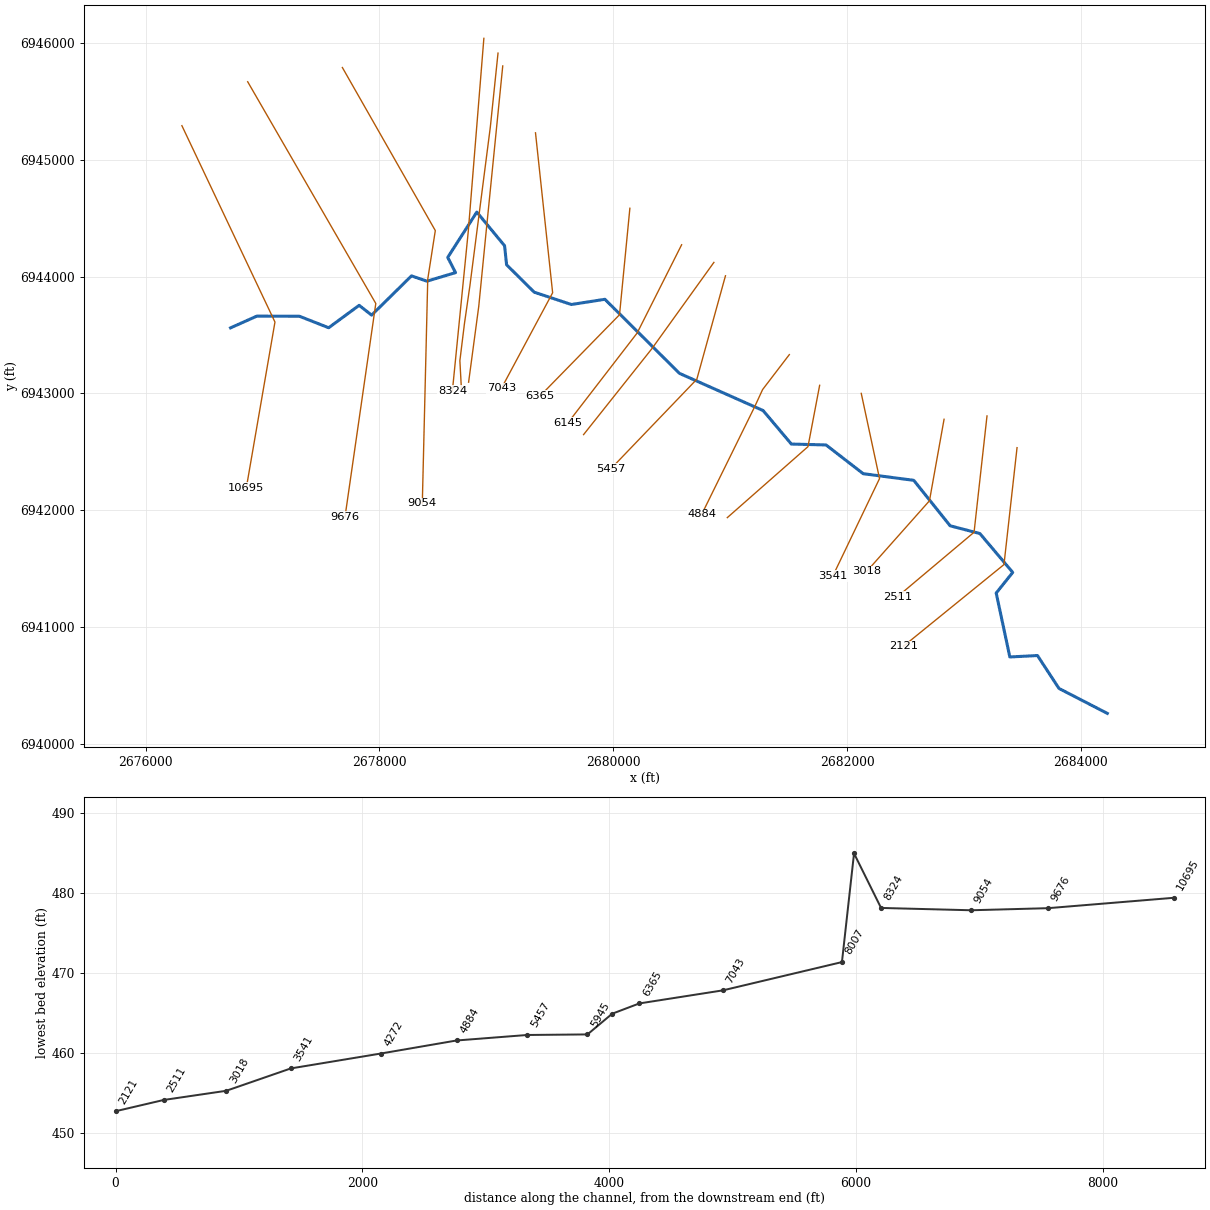
--- Muddy T7.prj (project) ---

Proj Title=Muddy T7 Base Level Engineering
Current Plan=p01
Default Exp/Contr=0.3,0.1
English Units
Geom File=g01
Flow File=f01
Plan File=p01
Y Axis Title=Elevation
X Axis Title(PF)=Main Channel Distance
X Axis Title(XS)=Station
BEGIN DESCRIPTION:
Muddy T7
END DESCRIPTION:
DSS Export Rating Curves= 0
DSS Export Rating Curve Sorted= 0
DSS Export Volume Flow Curves= 0
DXF OffsetX= 0
DXF OffsetY= 0
DXF ScaleX= 1
DXF ScaleY= 10

--- Muddy T7.p01 (plan) ---

Plan Title=Multiple Run
Short Identifier=Multiple
Geom File=g01
Flow File=f01
Subcritical Flow
K Sum by GR= 0
Std Step Tol= 0.01
Critical Tol= 0.01
Num of Std Step Trials= 20
Max Error Tol= 0.3
Flow Tol Ratio= 0.001
Split Flow NTrial= 30
Split Flow Tol= 0.02
Split Flow Ratio= 0.02
Log Output Level= 0
Friction Slope Method= 1
Unsteady Friction Slope Method= 2
Unsteady Bridges Friction Slope Method= 1
Parabolic Critical Depth
Global Vel Dist=  1 , 1 , 1
Global Log Level= 0
CheckData=True
Encroach Param= -1, 0, 0, 0
BEGIN DESCRIPTION:
Multiple Run
END DESCRIPTION:

--- Muddy T7.f01 (steady flow) ---

Flow Title=Multiple
Number of Profiles=7
Profile Names=10-year,25-year,50-year,1pct_min,100-year,1pct_plu,500-year
River Rch & RM= Muddy T7,Reach-1,10695
     621     831     999     596    1189    2372    1683
River Rch & RM= Muddy T7,Reach-1,8007
     929    1270    1550     937    1870    3731    2721
Boundary for River Rch & Prof#=Muddy T7,Reach-1,1
Up Type=0
Dn Type=3
Dn Slope=0.005
Boundary for River Rch & Prof#=Muddy T7,Reach-1,2
Up Type=0
Dn Type=3
Dn Slope=0.005
Boundary for River Rch & Prof#=Muddy T7,Reach-1,3
Up Type=0
Dn Type=3
Dn Slope=0.005
Boundary for River Rch & Prof#=Muddy T7,Reach-1,4
Up Type=0
Dn Type=3
Dn Slope=0.005
Boundary for River Rch & Prof#=Muddy T7,Reach-1,5
Up Type=0
Dn Type=3
Dn Slope=0.005
Boundary for River Rch & Prof#=Muddy T7,Reach-1,6
Up Type=0
Dn Type=3
Dn Slope=0.005
Boundary for River Rch & Prof#=Muddy T7,Reach-1,7
Up Type=0
Dn Type=3
Dn Slope=0.005

--- Muddy T7.g01 (geometry) ---

Geom Title=Existing Conditions
Program Version=4.10

River Reach=Muddy T7        ,Reach-1
Reach XY= 30
        2676726.        6943561.      2676950.96      6943661.49
      2677315.38       6943660.4      2677565.56      6943562.04
        2677826.      6943753.89      2677932.68      6943669.96
      2678273.71      6944005.89      2678405.82      6943960.72
      2678650.53      6944033.86      2678583.85      6944164.23
      2678832.51      6944552.13      2679070.29      6944263.54
      2679087.24        6944101.      2679323.55      6943866.46
      2679641.34      6943760.96      2679928.45      6943805.54
      2680566.21      6943171.52      2681282.06      6942852.86
       2681523.3      6942566.36      2681820.07      6942558.76
      2682137.88      6942312.76      2682570.56      6942255.82
      2682881.61      6941866.59      2683135.82      6941800.53
       2683416.9      6941467.71      2683275.57      6941290.97
       2683392.2      6940743.86      2683628.55      6940756.01
      2683812.44      6940474.49        2684226.        6940261.

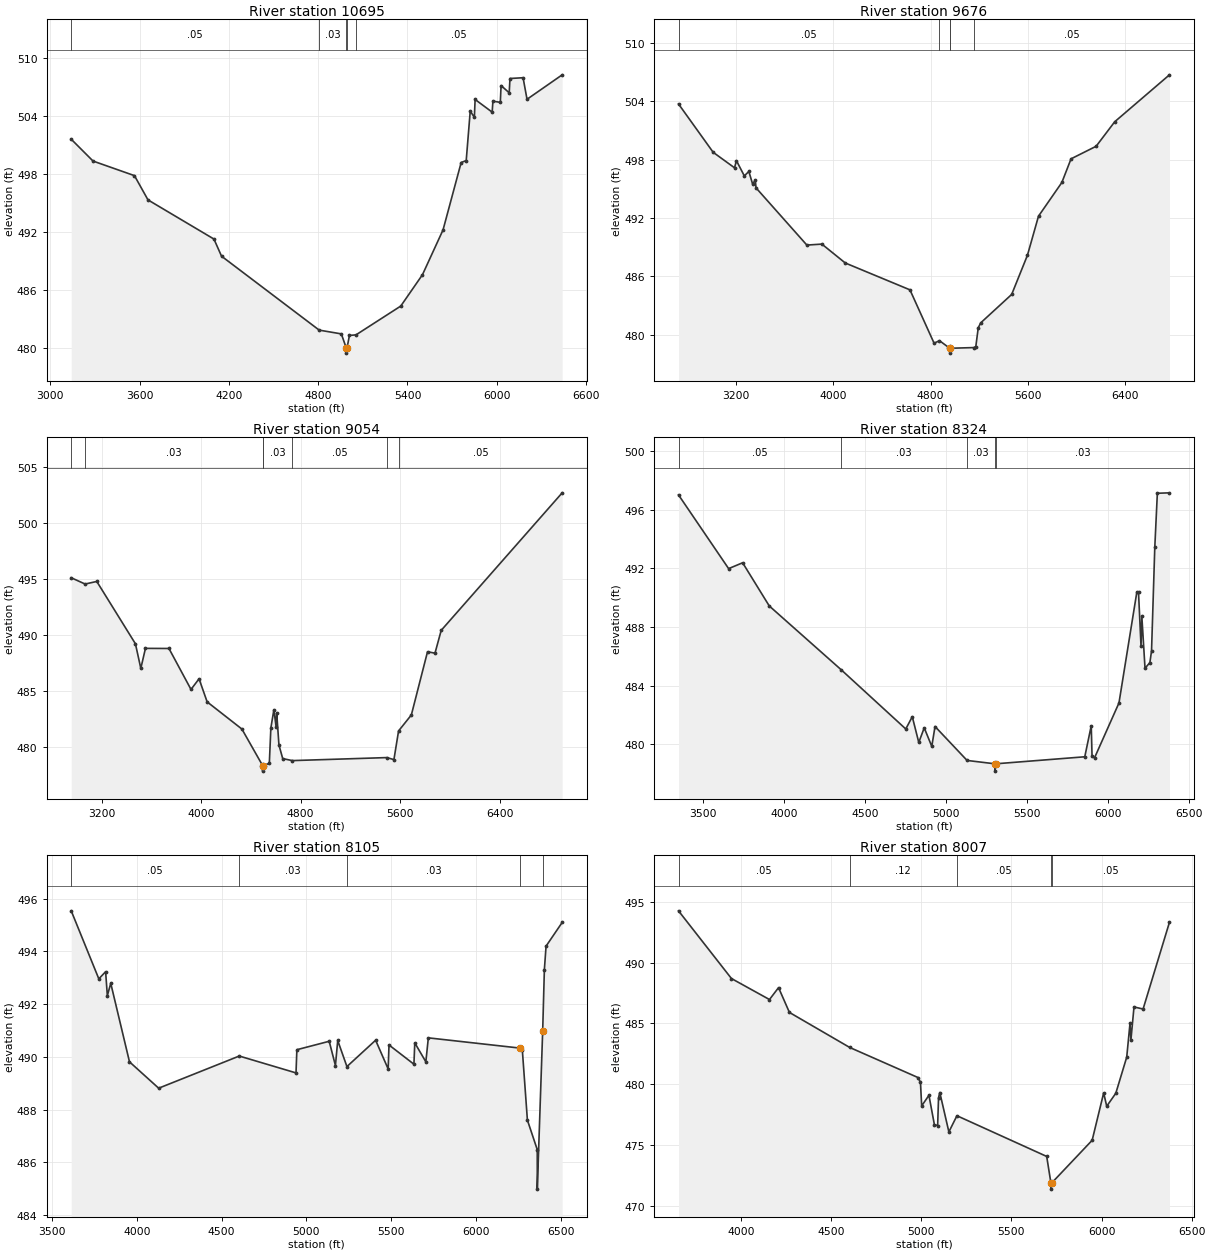
Type RM Length L Ch R = 1 ,10695   ,1019,1019,1019
BEGIN DESCRIPTION:
Muddy T7 10.0
END DESCRIPTION:
XS GIS Cut Line= 3
      2676309.86      6945291.83      2677105.94       6943610.8
        2676861.      6942191.99
#Sta/Elev= 30
    3140  501.55  3286.6  499.29  3565.1  497.78  3656.1  495.27  4099.3  491.22
  4150.3  489.45  4806.7   481.8  4955.5  481.41  4989.3  479.92  4989.6  479.42
  4993.3  479.92  5009.9  481.25  5054.1  481.31    5355  484.29  5500.7  487.53
  5639.1  492.17  5760.9  499.14  5794.8  499.34  5821.8  504.46  5849.6  503.81
  5854.6  505.66  5969.2  504.35  5974.3  505.49    6024  505.36  6029.1   507.1
  6083.8  506.35  6088.9  507.83    6177  507.91  6203.5  505.68  6439.8  508.21
#Mann= 5 ,-1 , 0
    3140     .05       0  4806.7     .03       0  4989.3     .03       0
  4993.3     .03       0  5054.1     .05       0
Bank Sta=4989.3,4993.3
XS Rating Curve= 0 ,0
Exp/Cntr=0.3,0.1

Type RM Length L Ch R = 1 ,9676    ,622,622,622
BEGIN DESCRIPTION:
Mapping XS de809bc5
END DESCRIPTION:
XS GIS Cut Line= 3
      2676872.66      6945667.82      2677968.49      6943769.66
      2677705.52      6941945.79
#Sta/Elev= 30
  2728.9  503.72  3013.9  498.75  3189.2  497.16    3205  497.89  3269.7  496.33
    3307  496.78  3337.2  495.52  3360.1  495.87  3365.8   495.1  3783.7  489.22
  3907.2  489.32  4099.3  487.38  4630.9  484.62  4829.1  479.14  4873.6   479.4
  4957.7  478.62    4958  478.12  4961.7  478.62  5155.7  478.69  5171.9  478.78
  5192.1  480.73  5212.3  481.23  5466.8  484.15  5596.2  488.17  5687.2  492.19
  5879.1  495.65  5954.6  498.08  6160.7  499.37  6313.6  501.89  6763.4  506.71
#Mann= 5 ,-1 , 0
  2728.9     .05       0  4873.6     .03       0  4957.7     .03       0
  4961.7     .03       0  5155.7     .05       0
Bank Sta=4957.7,4961.7
XS Rating Curve= 0 ,0
Exp/Cntr=0.3,0.1

Type RM Length L Ch R = 1 ,9054    ,730,730,730
BEGIN DESCRIPTION:
Mapping XS 8248b5f1
END DESCRIPTION:
XS GIS Cut Line= 4
       2677682.6      6945789.53       2678477.6      6944393.88
      2678412.93      6943977.99      2678366.37      6942058.83
#Sta/Elev= 30
  2956.3  495.14    3068  494.58  3161.8  494.81  3472.5  489.24  3515.8  487.04
  3553.1  488.83    3742  488.82  3919.2  485.16    3984  486.11  4048.9  484.05
  4328.4  481.62  4494.8  478.36    4495  477.86  4498.8  478.36  4548.9  478.55
  4561.3  481.72  4585.6  483.35  4603.1  481.84  4608.2  483.06  4626.1   480.2
  4656.5  478.98  4734.2   478.8    5493  479.07  5550.5  478.89  5587.8  481.45
  5690.6  482.88  5820.6  488.53  5880.6   488.4  5930.6  490.44  6903.1  502.73
#Mann= 7 ,-1 , 0
  2956.3     .05       0    3068     .03       0  4494.8     .03       0
  4498.8     .03       0  4734.2     .05       0    5493      .1       0
  5587.8     .05       0
Bank Sta=4494.8,4498.8
XS Rating Curve= 0 ,0
Exp/Cntr=0.3,0.1

Type RM Length L Ch R = 1 ,8324    ,219,219,219
BEGIN DESCRIPTION:
Mapping XS bdb8bf0b
END DESCRIPTION:
XS GIS Cut Line= 3
      2678892.97       6946039.4      2678759.41      6944385.63
      2678623.67      6943020.82
#Sta/Elev= 30
  3350.2  497.03  3659.6  491.99  3746.1  492.39  3910.4  489.44  4354.2  485.08
  4753.2  481.03  4793.3  481.87  4833.4  480.11    4867  481.11  4913.7  479.84
  4933.7   481.2  5131.6  478.88  5303.4  478.65  5303.7  478.15  5307.4  478.65
  5858.1  479.13    5898  481.25    5903  479.16  5918.4  479.06  6069.2  482.81
  6179.7   490.4  6189.8  490.38  6205.3  486.69  6210.3  488.73    6230  485.18
  6260.1  485.57  6270.2  486.37  6290.3  493.44  6306.1  497.14  6380.9  497.17
#Mann= 5 ,-1 , 0
  3350.2     .05       0  4354.2     .03       0  5131.6     .03       0
  5303.4     .03       0  5307.4     .03       0
Bank Sta=5303.4,5307.4
XS Rating Curve= 0 ,0
Exp/Cntr=0.3,0.1

Type RM Length L Ch R = 1 ,8105    ,98,98,98
BEGIN DESCRIPTION:
Mapping XS 8eb71cfe
END DESCRIPTION:
XS GIS Cut Line= 6
      2679013.98      6945913.05      2678948.18      6945279.76
       2678773.7      6943922.99      2678726.82      6943597.47
      2678687.76      6943279.76        2678701.      6943036.05
#Sta/Elev= 30
  3612.2  495.54  3775.1  492.96  3815.3  493.23  3825.4  492.32  3845.5  492.79
  3956.1  489.81  4128.4  488.81    4604  490.03    4939  489.39    4944  490.27
  5134.8  490.59  5171.6  489.67  5185.2  490.62  5239.4  489.63  5408.8  490.63
  5482.8  489.54  5487.8  490.45  5634.9  489.72  5639.9  490.53  5705.3  489.81
  5719.9  490.72  6262.7  490.33  6274.6  490.27  6304.6   487.6  6362.7  486.48
    6363  484.98  6394.8  490.98  6404.8  493.31  6414.8   494.2  6509.9   495.1
#Mann= 5 ,-1 , 0
  3612.2     .05       0    4604     .03       0  5239.4     .03       0
  6262.7     .03       0  6394.8     .03       0
Bank Sta=6262.7,6394.8
XS Rating Curve= 0 ,0
Exp/Cntr=0.3,0.1

Type RM Length L Ch R = 1 ,8007    ,964,964,964
BEGIN DESCRIPTION:
Mapping XS 681fb7ab
END DESCRIPTION:
XS GIS Cut Line= 4
      2679054.47      6945803.11      2678908.26      6944342.57
      2678849.24      6943745.34      2678762.42        6943096.
#Sta/Elev= 30
  3653.8  494.27  3947.4   488.7  4158.4  486.97  4208.7  487.95    4269  485.91
  4603.1  483.03  4982.5  480.55  4995.7  480.16  5002.6  478.22  5042.8  479.09
    5073  476.68  5091.1   476.6  5096.1   478.9  5103.1  479.32  5153.4  476.08
  5198.1  477.41    5696  474.06  5719.4  471.87  5719.7  471.37  5723.4  471.87
  5948.1  475.39    6012  479.29  6028.8  478.19  6079.3  479.26  6139.8  482.23
  6158.1  485.02  6163.1  483.65  6180.2  486.36  6230.6  486.19  6376.9  493.33
#Mann= 5 ,-1 , 0
  3653.8     .05       0  4603.1     .12       0  5198.1     .05       0
  5719.4     .07       0  5723.4     .05       0
Bank Sta=5719.4,5723.4
XS Rating Curve= 0 ,0
Exp/Cntr=0.3,0.1

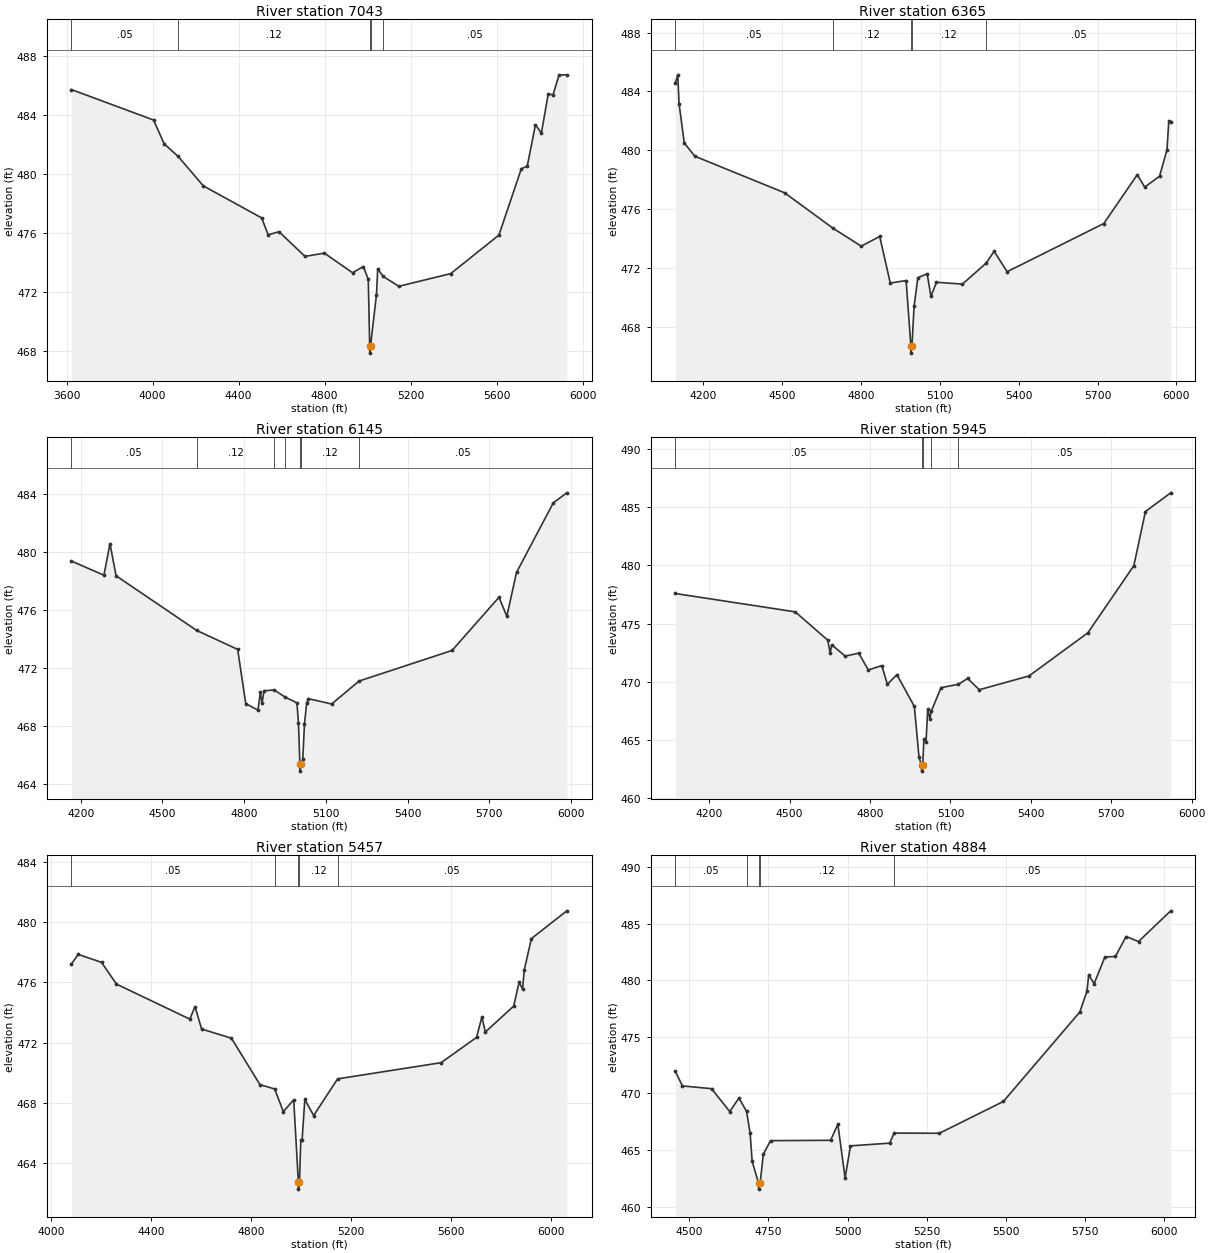
Type RM Length L Ch R = 1 ,7043    ,678,678,678
BEGIN DESCRIPTION:
Mapping XS d48d174b
END DESCRIPTION:
XS GIS Cut Line= 3
      2679334.64      6945230.75       2679481.2      6943861.47
       2679043.7      6943044.66
#Sta/Elev= 30
  3622.9  485.73  4004.8  483.66  4054.3  482.04  4118.6   481.2  4236.1  479.19
  4507.7  477.01  4537.8  475.86  4588.1  476.08  4708.8   474.4  4799.3  474.62
  4930.1  473.29  4980.4  473.71  5003.3  472.84  5009.9  468.33  5010.1  467.83
  5013.9  468.33  5041.5  471.81  5047.2  473.56  5072.1  473.04  5145.5  472.37
  5386.8  473.23    5611  475.85    5715  480.35  5742.6  480.53  5780.8  483.34
  5808.4  482.77    5840  485.42  5862.7  485.38  5890.5  486.72  5926.6  486.73
#Mann= 5 ,-1 , 0
  3622.9     .05       0  4118.6     .12       0  5009.9     .07       0
  5013.9     .12       0  5072.1     .05       0
Bank Sta=5009.9,5013.9
XS Rating Curve= 0 ,0
Exp/Cntr=0.3,0.1

Type RM Length L Ch R = 1 ,6365    ,220,220,220
BEGIN DESCRIPTION:
Mapping XS 8a27d723
END DESCRIPTION:
XS GIS Cut Line= 3
      2680141.92       6944584.9      2680053.39      6943673.49
      2679376.27      6942980.75
#Sta/Elev= 30
  4093.6  484.56  4102.8  485.13  4107.9  483.16  4127.7  480.49  4167.9  479.59
  4509.5   477.1  4692.7   474.7  4800.8  473.47  4871.1  474.13  4911.3  470.96
  4971.6  471.13  4989.6  466.69  4989.9  466.19  4993.8  466.69  5001.8  469.38
  5016.2  471.32  5051.7  471.59  5065.8  470.05    5087  471.01    5186  470.89
  5276.4  472.32  5306.3  473.12  5355.7  471.73  5723.5  475.01  5850.8  478.33
  5879.1  477.49  5935.7  478.23  5963.8  480.03  5970.9     482    5978  481.95
#Mann= 5 ,-1 , 0
  4093.6     .05       0  4692.7     .12       0  4989.6     .07       0
  4993.8     .12       0  5276.4     .05       0
Bank Sta=4989.6,4993.8
XS Rating Curve= 0 ,0
Exp/Cntr=0.3,0.1

Type RM Length L Ch R = 1 ,6145    ,200,200,200
BEGIN DESCRIPTION:
Mapping XS b5571ec9
END DESCRIPTION:
XS GIS Cut Line= 3
      2680584.64      6944272.45      2680204.43      6943517.24
      2679610.81      6942746.58
#Sta/Elev= 30
    4166  479.36  4285.2  478.39  4307.5  480.56  4329.9  478.35  4625.3  474.59
  4776.2  473.28  4805.8  469.55  4850.6   469.1  4859.8  470.36  4865.4  469.56
    4873  470.43  4910.3  470.49  4950.9  469.99  4993.7   469.6  4999.3  468.22
  5004.5   465.4  5004.8   464.9  5008.7   465.4  5015.1  465.71  5021.4  468.17
  5029.6   469.6  5035.9  469.89  5121.1  469.52  5221.6   471.1  5563.2  473.21
  5735.4  476.87  5764.1  475.56  5799.7  478.58  5934.7  483.37  5984.3  484.06
#Mann= 7 ,-1 , 0
    4166     .05       0  4625.3     .12       0  4910.3     .05       0
  4950.9     .12       0  5004.5     .07       0  5008.7     .12       0
  5221.6     .05       0
Bank Sta=5004.5,5008.7
XS Rating Curve= 0 ,0
Exp/Cntr=0.3,0.1

Type RM Length L Ch R = 1 ,5945    ,488,488,488
BEGIN DESCRIPTION:
Mapping XS 339b9dc0
END DESCRIPTION:
XS GIS Cut Line= 3
      2680860.67      6944121.41      2680329.43      6943381.83
      2679746.07      6942647.42
#Sta/Elev= 30
  4073.3  477.59  4520.8  476.01  4642.4  473.57  4650.9  472.47  4657.1  473.18
  4707.4   472.2  4757.8  472.46  4793.4  471.01  4843.7  471.39  4864.6  469.78
  4900.2  470.61  4965.3  467.87  4982.6   463.5  4992.2  462.81  4992.6  462.31
  4996.5  462.81  5000.8  465.09  5008.8  464.82  5015.2  467.66  5023.2  466.79
  5027.9  467.44  5064.9  469.49  5129.3  469.78  5164.2  470.28  5207.5  469.31
  5393.3   470.5  5612.8  474.21  5784.2  479.98  5827.5  484.64  5921.8  486.25
#Mann= 5 ,-1 , 0
  4073.3     .05       0  4992.2     .03       0  4996.5     .05       0
  5027.9     .12       0  5129.3     .05       0
Bank Sta=4992.2,4996.5
XS Rating Curve= 0 ,0
Exp/Cntr=0.3,0.1

Type RM Length L Ch R = 1 ,5457    ,573,573,573
BEGIN DESCRIPTION:
Mapping XS d575cb67
END DESCRIPTION:
XS GIS Cut Line= 3
      2680959.65      6944006.87      2680714.84      6943121.41
      2679980.86       6942356.2
#Sta/Elev= 30
  4082.8  477.23  4109.6  477.87    4203  477.34  4262.7  475.89  4555.8  473.56
  4576.5  474.39  4602.8   472.9  4721.8  472.29  4835.9   469.2  4894.7  468.91
  4929.3   467.4  4970.8  468.19  4989.2  462.74  4989.7  462.24  4993.8  462.74
  4999.1  465.53  5004.3  465.53  5015.2  468.21  5050.5  467.14    5146  469.58
  5559.6  470.66  5701.1  472.34  5722.5   473.7  5736.4   472.7  5849.6  474.43
  5870.9     476  5885.1  475.58    5892  476.85  5920.3  478.92  6061.8  480.77
#Mann= 5 ,-1 , 0
  4082.8     .05       0  4894.7     .12       0  4989.2     .07       0
  4993.8     .12       0    5146     .05       0
Bank Sta=4989.2,4993.8
XS Rating Curve= 0 ,0
Exp/Cntr=0.3,0.1

Type RM Length L Ch R = 1 ,4884    ,612,612,612
BEGIN DESCRIPTION:
Mapping XS a5da73ee
END DESCRIPTION:
XS GIS Cut Line= 4
      2681505.92      6943332.01      2681277.29      6943032.76
      2681209.16      6942885.14       2680756.3      6941964.36
#Sta/Elev= 30
  4455.6  471.95    4478  470.66  4570.1  470.42  4627.6   468.4  4656.7  469.59
  4680.8  468.41    4692  466.48  4698.3  464.03  4718.8  462.05  4719.2  461.55
  4723.4  462.05  4733.7  464.63  4756.4  465.83  4946.2  465.86  4969.2  467.28
  4992.1  462.54  5009.1  465.37  5133.1  465.61  5146.8   466.5  5289.9  466.48
  5492.2  469.29  5733.8  477.19  5756.3  479.02  5761.9  480.48  5778.8  479.68
  5812.9  482.04  5846.2  482.09  5879.8  483.85  5919.2  483.41  6020.9  486.12
#Mann= 5 ,-1 , 0
  4455.6     .05       0  4680.8     .12       0  4718.8     .07       0
  4723.4     .12       0  5146.8     .05       0
Bank Sta=4718.8,4723.4
XS Rating Curve= 0 ,0
Exp/Cntr=0.3,0.1

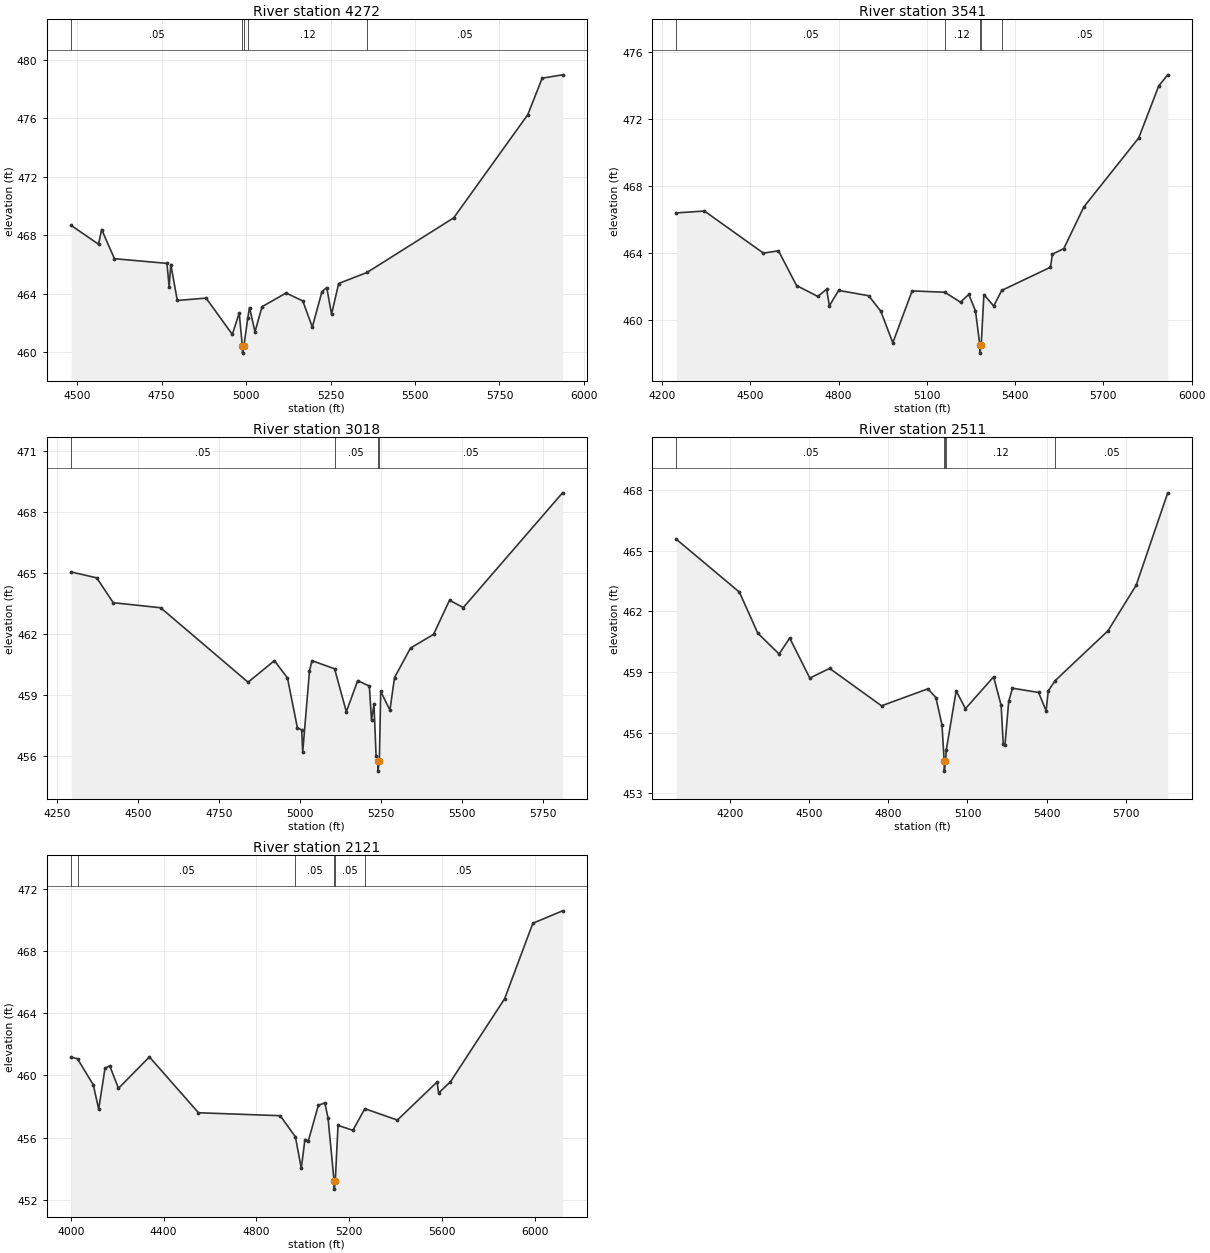
Type RM Length L Ch R = 1 ,4272    ,731,731,731
BEGIN DESCRIPTION:
Mapping XS ed368788
END DESCRIPTION:
XS GIS Cut Line= 3
      2681765.33      6943069.38      2681665.51      6942544.22
      2680975.44      6941936.62
#Sta/Elev= 30
  4482.5  468.67  4563.3  467.38  4572.5  468.39  4610.4  466.39  4765.9  466.07
  4772.2  464.47  4777.3  465.99  4796.4  463.53  4881.7  463.69  4959.3   461.2
  4979.6  462.67  4988.9  460.42  4989.4  459.92  4993.6  460.42  5005.1  462.34
  5010.2  463.04  5026.3  461.38  5047.2   463.1  5118.3  464.04  5167.7   463.5
  5196.1  461.71  5224.6  464.14  5238.8  464.41    5253  462.58  5273.9  464.69
  5358.2  465.45  5614.5  469.19  5833.7  476.26  5876.4  478.76  5936.5  478.99
#Mann= 5 ,-1 , 0
  4482.5     .05       0  4988.9     .03       0  4993.6     .05       0
  5005.1     .12       0  5358.2     .05       0
Bank Sta=4988.9,4993.6
XS Rating Curve= 0 ,0
Exp/Cntr=0.3,0.1

Type RM Length L Ch R = 1 ,3541    ,523,523,523
BEGIN DESCRIPTION:
Mapping XS d2523dde
END DESCRIPTION:
XS GIS Cut Line= 3
      2682121.23        6943000.      2682277.49      6942270.79
      2681878.19      6941437.48
#Sta/Elev= 30
  4248.9  466.41  4344.1  466.52  4544.5  464.01  4595.6  464.15    4657  462.08
  4729.4  461.43  4759.2  461.86  4768.6  460.87  4800.1  461.79  4902.4  461.47
  4943.3  460.55  4984.2  458.67  5049.9  461.76  5160.6  461.68  5214.3  461.09
  5242.5  461.55  5265.2  460.57  5279.9  458.55  5280.4  458.05  5284.7  458.55
  5293.8  461.54  5327.1  460.86  5354.6  461.79    5520  463.17  5526.7  463.95
  5565.3  464.28  5633.3  466.76  5820.1  470.88  5888.1  473.98  5918.7  474.64
#Mann= 5 ,-1 , 0
  4248.9     .05       0  5160.6     .12       0  5279.9     .03       0
  5284.7     .12       0  5354.6     .05       0
Bank Sta=5279.9,5284.7
XS Rating Curve= 0 ,0
Exp/Cntr=0.3,0.1

Type RM Length L Ch R = 1 ,3018    ,507,507,507
BEGIN DESCRIPTION:
Mapping XS 927055b0
END DESCRIPTION:
XS GIS Cut Line= 3
      2682829.57      6942778.58      2682704.57      6942080.68
      2682168.09      6941476.49
#Sta/Elev= 30
  4292.5  465.04  4371.3  464.75  4422.1  463.53  4568.7  463.28  4838.6  459.62
  4919.9  460.68  4960.2  459.83    4991  457.37  5004.2  457.28  5007.3  456.19
  5028.2  460.17  5035.8  460.68  5105.7  460.28    5142  458.17  5177.1   459.7
    5213  459.43  5219.7  457.76  5227.3  458.54  5233.9  455.98  5239.1  455.75
  5239.6  455.25  5243.9  455.75  5248.2  459.17  5276.6  458.25  5290.8  459.85
  5340.2   461.3  5411.2  461.97  5460.6  463.65  5503.2  463.29  5809.5  468.93
#Mann= 4 ,-1 , 0
  4292.5     .05       0  5105.7     .05       0  5239.1     .03       0
  5243.9     .05       0
Bank Sta=5239.1,5243.9
XS Rating Curve= 0 ,0
Exp/Cntr=0.3,0.1

Type RM Length L Ch R = 1 ,2511    ,390,390,390
BEGIN DESCRIPTION:
Mapping XS 06085e01
END DESCRIPTION:
XS GIS Cut Line= 3
      2683196.85      6942807.12      2683086.19      6941811.45
      2682429.75       6941258.8
#Sta/Elev= 30
  3998.2  465.56  4236.5  462.95  4306.2  460.92  4386.7  459.89  4426.9  460.68
  4503.1   458.7  4577.9  459.18  4774.7  457.33  4950.1  458.17  4980.3  457.74
  5003.4  456.39  5011.7   454.6  5012.3   454.1  5016.7   454.6  5019.4  455.12
  5057.1  458.07  5092.2  457.19  5198.8  458.76  5227.4  457.35  5235.2  455.45
  5241.7  455.37    5256  457.55  5270.3   458.2  5369.2  457.99  5397.8  457.08
  5405.5  458.06  5431.5  458.57  5631.9  461.04  5738.5  463.29  5858.1  467.86
#Mann= 5 ,-1 , 0
  3998.2     .05       0  5011.7     .03       0  5016.7     .05       0
  5019.4     .12       0  5431.5     .05       0
Bank Sta=5011.7,5016.7
XS Rating Curve= 0 ,0
Exp/Cntr=0.3,0.1

Type RM Length L Ch R = 1 ,2121    ,0,0,0
BEGIN DESCRIPTION:
Mapping XS eec1b6f0
END DESCRIPTION:
XS GIS Cut Line= 3
      2683453.88      6942535.63      2683342.08      6941534.84
      2682481.66       6940835.5
#Sta/Elev= 30
  4002.2  461.17  4029.3  461.07  4097.4  459.39  4120.4  457.83  4147.7  460.46
  4167.9  460.62  4205.7  459.17  4338.9  461.19  4550.2   457.6  4902.4  457.41
  4967.7  456.05    4993  454.03  5008.6  455.88  5023.4  455.79  5066.5  458.08
  5094.4  458.23  5108.1  457.28  5134.3  453.19  5134.9  452.69  5139.3  453.19
  5151.2  456.79  5215.1  456.47  5266.7  457.86  5406.9  457.13  5577.9  459.58
  5584.3  458.87  5635.4  459.59  5868.8  464.93  5990.2  469.78    6118  470.58
#Mann= 6 ,-1 , 0
  4002.2     .12       0  4029.3     .05       0  4967.7     .05       0
  5134.3     .03       0  5139.3     .05       0  5266.7     .05       0
Bank Sta=5134.3,5139.3
XS Rating Curve= 0 ,0
Exp/Cntr=0.3,0.1

Chan Stop Cuts=-1
Use User Specified Reach Order=0
Composite Channel Slope=5