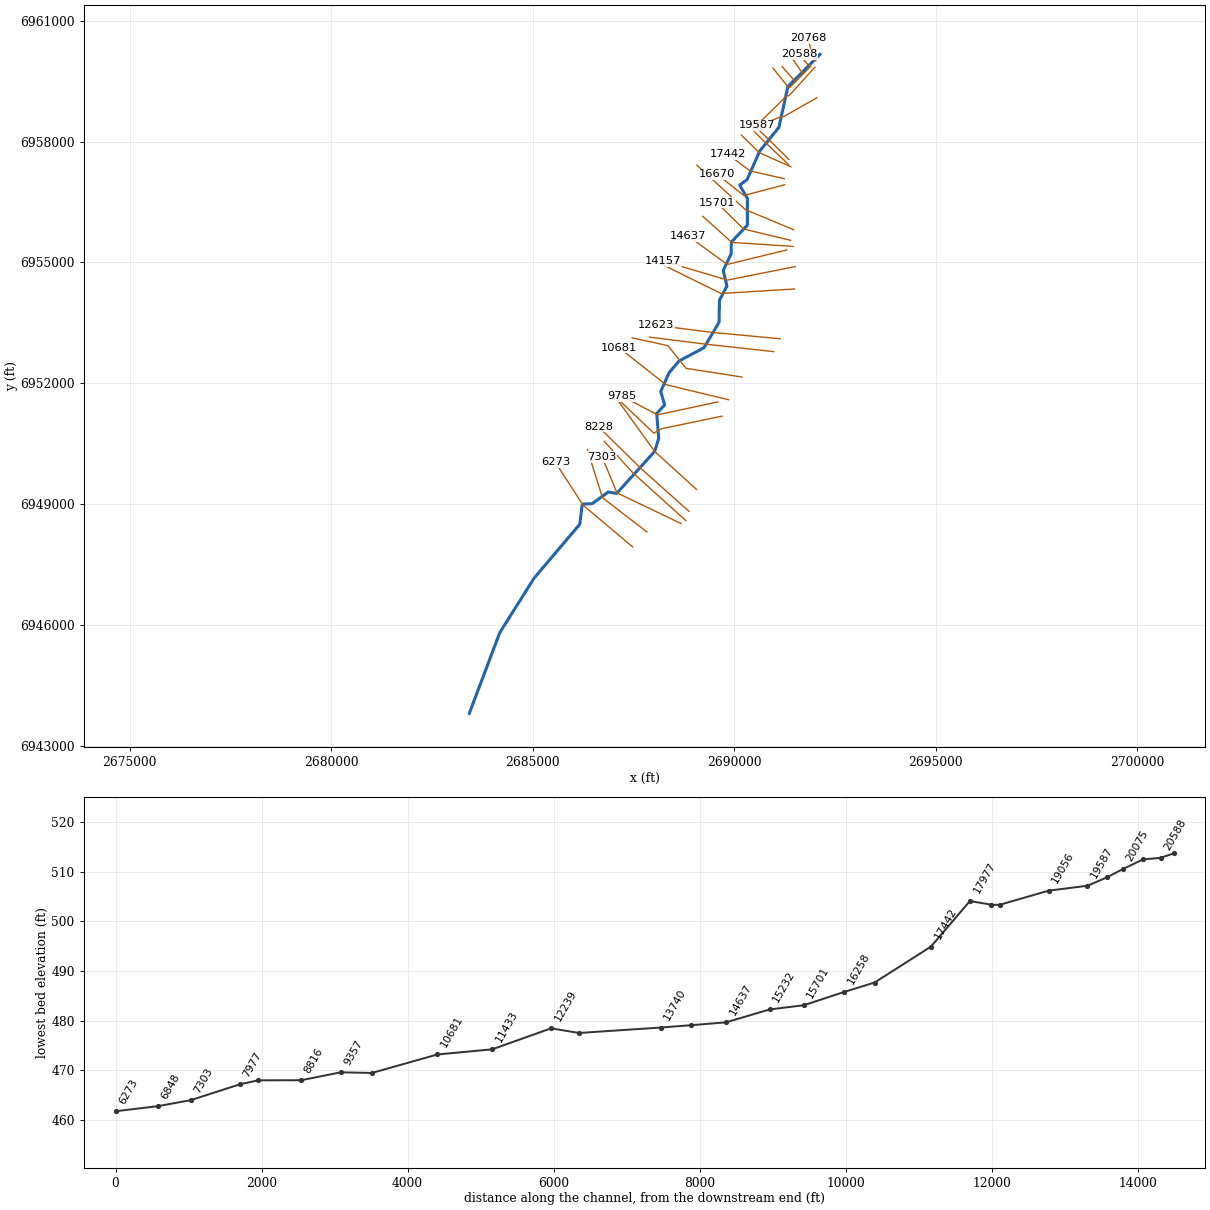
--- Muddy T8.prj (project) ---

Proj Title=Muddy T8 Base Level Engineering
Current Plan=p01
Default Exp/Contr=0.3,0.1
English Units
Geom File=g01
Flow File=f01
Plan File=p01
Y Axis Title=Elevation
X Axis Title(PF)=Main Channel Distance
X Axis Title(XS)=Station
BEGIN DESCRIPTION:
Muddy T8
END DESCRIPTION:
DSS Export Rating Curves= 0
DSS Export Rating Curve Sorted= 0
DSS Export Volume Flow Curves= 0
DXF OffsetX= 0
DXF OffsetY= 0
DXF ScaleX= 1
DXF ScaleY= 10

--- Muddy T8.p01 (plan) ---

Plan Title=Multiple Run
Short Identifier=Multiple
Geom File=g01
Flow File=f01
Subcritical Flow
K Sum by GR= 0
Std Step Tol= 0.01
Critical Tol= 0.01
Num of Std Step Trials= 20
Max Error Tol= 0.3
Flow Tol Ratio= 0.001
Split Flow NTrial= 30
Split Flow Tol= 0.02
Split Flow Ratio= 0.02
Log Output Level= 0
Friction Slope Method= 1
Unsteady Friction Slope Method= 2
Unsteady Bridges Friction Slope Method= 1
Parabolic Critical Depth
Global Vel Dist=  1 , 1 , 1
Global Log Level= 0
CheckData=True
Encroach Param= -1, 0, 0, 0
BEGIN DESCRIPTION:
Multiple Run
END DESCRIPTION:

--- Muddy T8.f01 (steady flow) ---

Flow Title=Multiple
Program Version=4.10
Number of Profiles= 7
Profile Names=10-year,25-year,50-year,1pct_min,100-year,1pct_plu,500-year
River Rch & RM=Muddy T8,Reach-1         ,20768
     651     878    1062     638    1273    2541    1828
River Rch & RM=Muddy T8,Reach-1         ,19056
     801    1095    1338     810    1617    3226    2362
River Rch & RM=Muddy T8,Reach-1         ,16258
    1388    1950    2425    1493    2978    5942    4494
River Rch & RM=Muddy T8,Reach-1         ,12623
    1950    2777    3484    2161    4311    8602    6605
River Rch & RM=Muddy T8,Reach-1         ,8816
    2208    3158    3973    2469    4926    9828    7579
River Rch & RM=Muddy T8,Reach-1         ,5674
    2157    3071    3853    2387    4762    9501    7281
Boundary for River Rch & Prof#=Muddy T8,Reach-1         , 1
Up Type= 0
Dn Type= 3
Dn Slope=0.003
Boundary for River Rch & Prof#=Muddy T8,Reach-1         , 2
Up Type= 0
Dn Type= 3
Dn Slope=0.003
Boundary for River Rch & Prof#=Muddy T8,Reach-1         , 3
Up Type= 0
Dn Type= 3
Dn Slope=0.003
Boundary for River Rch & Prof#=Muddy T8,Reach-1         , 4
Up Type= 0
Dn Type= 3
Dn Slope=0.003
Boundary for River Rch & Prof#=Muddy T8,Reach-1         , 5
Up Type= 0
Dn Type= 3
Dn Slope=0.003
Boundary for River Rch & Prof#=Muddy T8,Reach-1         , 6
Up Type= 0
Dn Type= 3
Dn Slope=0.003
Boundary for River Rch & Prof#=Muddy T8,Reach-1         , 7
Up Type= 0
Dn Type= 3
Dn Slope=0.003
DSS Import GetInterval= 0
DSS Import GetPeak= 0
DSS Import FillOption= 0

--- Muddy T8.g01 (geometry) ---

Geom Title=Existing Conditions
Program Version=4.10

River Reach=Muddy T8        ,Reach-1
Reach XY= 30
        2692126.        6960161.      2691331.11      6959363.29
      2691108.38      6958354.61      2690631.52      6957763.43
      2690318.26      6957054.55       2690135.1      6956917.75
      2690325.06      6956595.04      2690325.41      6955922.84
      2689927.98      6955505.33      2689923.93      6955216.86
       2689726.4      6954799.98      2689818.45        6954411.
      2689633.63      6954064.18      2689623.86      6953516.97
      2689249.84      6952883.86      2688634.62      6952557.16
      2688379.75      6952259.45      2688176.49      6951795.78
      2688274.39      6951467.03      2688077.05      6951250.57
       2688126.4        6950636.        2688026.        6950311.
      2687082.19      6949268.81      2686872.65      6949302.97
      2686474.74      6949014.48        2686229.      6949003.05
      2686168.19      6948504.81      2685036.78      6947170.68
      2684181.85      6945813.29        2683426.        6943811.

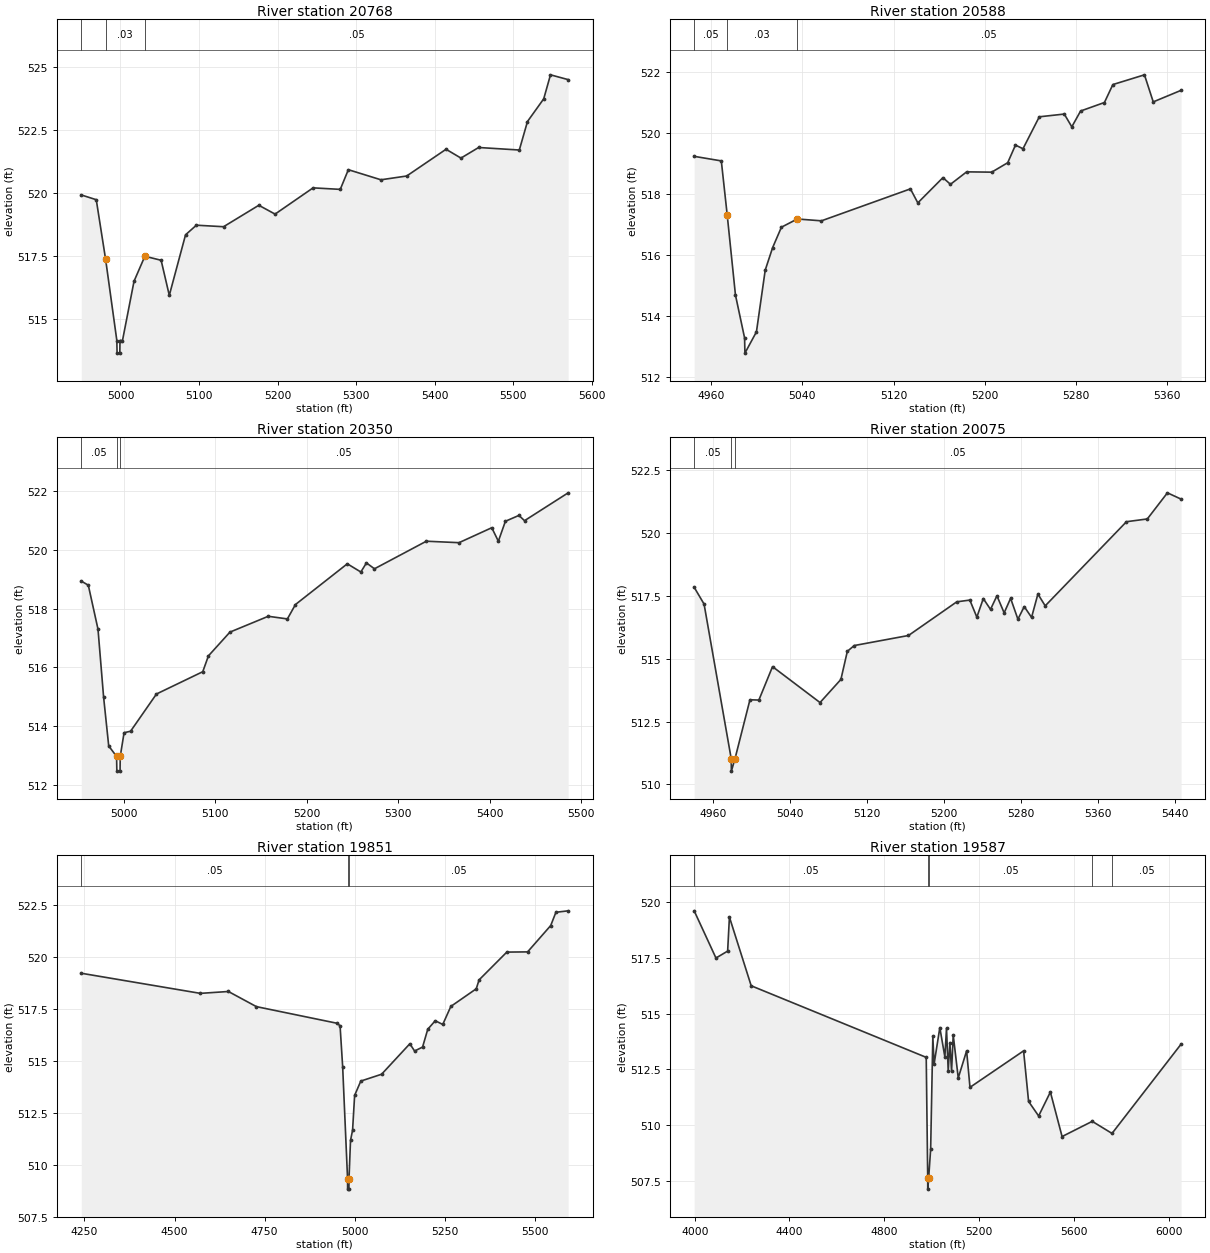
Type RM Length L Ch R = 1 ,20768   ,180,180,180
BEGIN DESCRIPTION:
Muddy T8 32.0
END DESCRIPTION:
XS GIS Cut Line= 3
      2692024.63      6959999.84        2691976.        6960011.
        2691826.      6960561.01
#Sta/Elev= 30
  4950.1  519.93  4969.2  519.74  4981.1  517.38  4995.4  514.16  4995.7  513.66
  4999.2  513.66  4999.4  514.16  5002.6  514.16  5017.3  516.51  5031.1   517.5
  5051.8  517.34  5062.2  515.95  5082.9  518.35  5096.7  518.73  5131.3  518.67
  5176.2  519.52  5196.9  519.17  5245.3  520.21  5279.9  520.15  5290.2  520.93
  5331.7  520.53  5364.5  520.68  5414.6  521.74  5433.6  521.39  5456.1  521.81
  5507.9  521.71  5518.3  522.84    5539  523.74  5547.6  524.69  5570.1   524.5
#Mann= 3 ,-1 , 0
  4950.1     .05       0  4981.1     .03       0  5031.1     .05       0
Bank Sta=4981.1,5031.1
XS Rating Curve= 0 ,0
Exp/Cntr=0.3,0.1

Type RM Length L Ch R = 1 ,20588   ,238,238,238
BEGIN DESCRIPTION:
Mapping XS 3c98cee7
END DESCRIPTION:
XS GIS Cut Line= 3
      2691901.31      6959870.23      2691851.32      6959881.22
      2691606.64      6960166.35
#Sta/Elev= 30
  4945.2  519.24    4969  519.09  4974.2   517.3  4981.4  514.68  4989.4  513.27
  4989.7  512.77  4999.8  513.47  5007.5   515.5    5014  516.24  5021.7  516.91
  5035.6  517.18  5056.8  517.12  5134.8  518.17  5141.3  517.71  5163.3  518.54
  5169.9  518.32  5184.1  518.73  5206.1  518.72  5220.1  519.03  5226.9  519.61
  5233.5  519.49  5247.8  520.54  5269.7  520.63  5276.3  520.21    5284  520.73
  5304.9  521.01  5312.3   521.6    5340  521.92  5347.7  521.03  5372.1  521.41
#Mann= 3 ,-1 , 0
  4945.2     .05       0  4974.2     .03       0  5035.6     .05       0
Bank Sta=4974.2,5035.6
XS Rating Curve= 0 ,0
Exp/Cntr=0.3,0.1

Type RM Length L Ch R = 1 ,20350   ,275,275,275
BEGIN DESCRIPTION:
Mapping XS d1cab3ea
END DESCRIPTION:
XS GIS Cut Line= 3
      2691722.31      6959694.77      2691679.38      6959716.32
      2691402.66      6960113.61
#Sta/Elev= 30
  4953.4  518.94  4961.1   518.8  4971.7   517.3  4977.8  514.99  4983.4  513.32
    4992  512.96  4992.3  512.46  4995.8  512.46    4996  512.96  5000.2  513.77
  5007.3  513.82  5035.6  515.09  5086.2  515.85  5092.4  516.39  5115.9   517.2
  5157.8  517.74  5178.7  517.65  5187.5  518.14  5244.2  519.53    5259  519.25
  5265.1  519.56  5273.9  519.36  5330.6   520.3  5366.3  520.25  5402.1  520.76
  5409.3   520.3    5417  520.98  5431.8  521.18  5437.9     521  5485.6  521.95
#Mann= 3 ,-1 , 0
  4953.4     .05       0    4992     .04       0    4996     .05       0
Bank Sta=4992,4996
XS Rating Curve= 0 ,0
Exp/Cntr=0.3,0.1

Type RM Length L Ch R = 1 ,20075   ,224,224,224
BEGIN DESCRIPTION:
Mapping XS 1eb76700
END DESCRIPTION:
XS GIS Cut Line= 3
       2691546.3      6959515.92      2691486.16       6959521.5
      2691190.72      6959855.61
#Sta/Elev= 30
  4939.9  517.85  4950.2  517.18  4978.4  511.03  4978.6  510.53  4982.4  511.03
  4997.9  513.37  5007.2  513.36  5021.4  514.69  5070.8  513.26  5092.5  514.18
  5099.2   515.3  5106.4  515.53  5162.8  515.93    5213  517.27  5226.6  517.34
  5233.9  516.66  5240.6   517.4  5248.1  516.97  5254.8  517.51  5262.3  516.83
    5269  517.41  5276.6  516.58  5283.2  517.08  5290.8  516.65  5297.4  517.58
    5305  517.11  5389.5  520.46  5411.2  520.57  5432.1  521.61  5446.3  521.36
#Mann= 3 ,-1 , 0
  4939.9     .05       0  4978.4     .04       0  4982.4     .05       0
Bank Sta=4978.4,4982.4
XS Rating Curve= 0 ,0
Exp/Cntr=0.3,0.1

Type RM Length L Ch R = 1 ,19851   ,264,264,264
BEGIN DESCRIPTION:
Mapping XS e7400149
END DESCRIPTION:
XS GIS Cut Line= 4
      2691871.87       6959842.3      2691373.82      6959337.58
      2691329.99      6959361.46      2690961.07      6959824.21
#Sta/Elev= 30
  4241.2  519.23  4571.5  518.26  4649.4  518.35  4727.1  517.62  4950.3  516.82
  4959.2   516.7  4966.4  514.72    4980  509.32  4980.2  508.82  4983.7  508.82
    4984  509.32  4988.2  511.17  4993.9  511.66  4999.6  513.34  5016.7  514.03
  5074.4  514.36  5152.8  515.83  5165.9  515.48  5188.1  515.67  5202.5  516.53
  5223.3  516.94  5244.1  516.76  5266.5  517.63    5337  518.48  5344.9  518.91
  5421.8  520.25  5479.5  520.26  5543.6  521.53    5558  522.17    5592  522.24
#Mann= 3 ,-1 , 0
  4241.2     .05       0    4980     .03       0    4984     .05       0
Bank Sta=4980,4984
XS Rating Curve= 0 ,0
Exp/Cntr=0.3,0.1

Type RM Length L Ch R = 1 ,19587   ,531,531,531
BEGIN DESCRIPTION:
Mapping XS 98cfce4e
END DESCRIPTION:
XS GIS Cut Line= 5
      2692001.93      6959845.14      2691366.49       6959144.9
      2691282.37      6959119.68       2691134.9      6958968.32
      2690554.79      6958402.04
#Sta/Elev= 30
  3997.6  519.59  4089.6  517.48  4138.9  517.79  4146.4  519.31  4238.3  516.24
  4977.2  513.04  4983.5  507.65  4983.7  507.15  4987.5  507.65  4995.9  508.94
  5005.1  513.98  5010.3  512.73  5034.6  514.37  5055.9  513.06  5062.8  514.34
    5070  512.44    5077   513.7  5084.2  512.43  5091.1  514.04  5112.4  512.12
  5147.7  513.33  5161.9   511.7  5388.2  513.33  5409.3  511.07  5451.7  510.42
  5501.3  511.49  5550.7   509.5    5678  510.18  5761.5  509.64    6053  513.63
#Mann= 5 ,-1 , 0
  3997.6     .05       0  4983.5     .03       0  4987.5     .05       0
    5678     .12       0  5761.5     .05       0
Bank Sta=4983.5,4987.5
XS Rating Curve= 0 ,0
Exp/Cntr=0.3,0.1

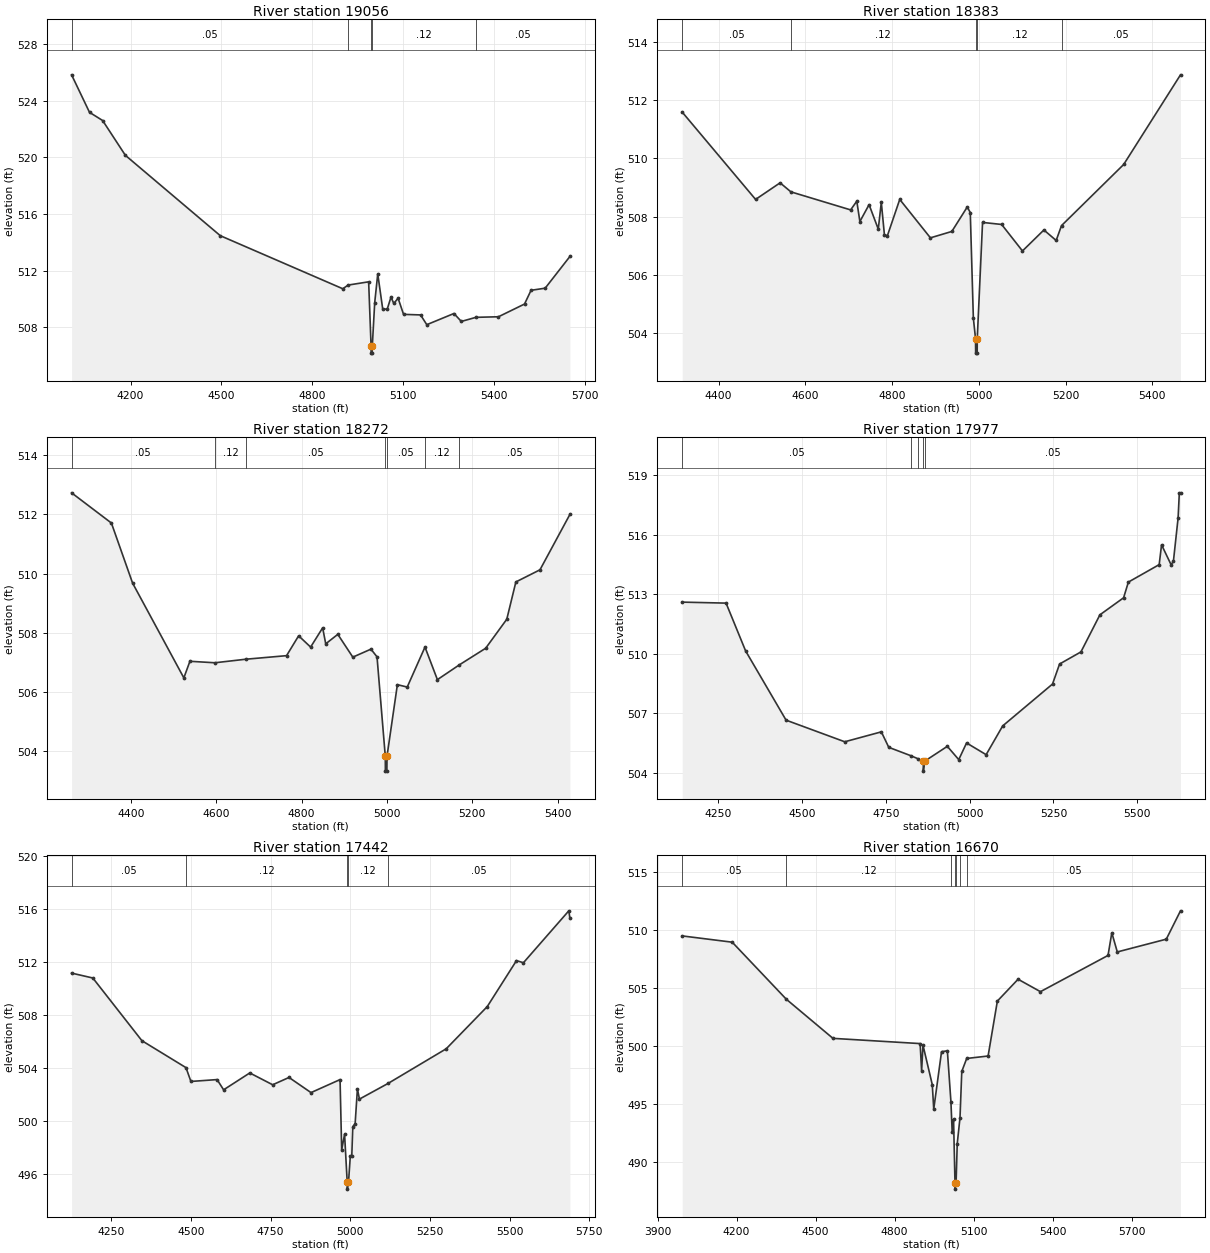
Type RM Length L Ch R = 1 ,19056   ,673,673,673
BEGIN DESCRIPTION:
Mapping XS 6475b2f5
END DESCRIPTION:
XS GIS Cut Line= 5
        2692051.        6959086.      2691218.68      6958613.88
      2691148.36      6958614.93      2691034.15      6958565.16
      2690576.73      6958385.62
#Sta/Elev= 30
  4005.7  525.84  4064.8  523.19  4108.1  522.61  4183.1  520.15  4496.1  514.47
    4900  510.72  4917.6  510.98  4985.3  511.21  4993.3  506.67  4993.5  506.17
    4997  506.17  4997.3  506.67  5005.3  509.74  5015.3  511.77  5031.6   509.3
  5046.4  509.27    5059  510.13  5068.2  509.68  5082.4  510.05  5100.4  508.91
  5156.5  508.87    5177  508.18  5266.5  508.97  5290.9  508.41  5339.2   508.7
  5413.3  508.74  5499.3  509.64  5520.8  510.61  5567.4  510.76  5648.9     513
#Mann= 5 ,-1 , 0
  4005.7     .05       0  4917.6     .12       0  4993.3     .07       0
  4997.3     .12       0  5339.2     .05       0
Bank Sta=4993.3,4997.3
XS Rating Curve= 0 ,0
Exp/Cntr=0.3,0.1

Type RM Length L Ch R = 1 ,18383   ,111,111,111
BEGIN DESCRIPTION:
Mapping XS 00246acc
END DESCRIPTION:
XS GIS Cut Line= 3
      2691359.42      6957555.24       2690836.4      6958068.24
      2690536.62      6958356.79
#Sta/Elev= 30
  4316.1  511.59  4485.3  508.59  4541.8  509.16  4566.7  508.85  4704.4  508.23
  4718.6  508.53  4725.7  507.83  4746.9  508.41  4768.1  507.57  4775.1  508.49
  4782.3  507.37  4789.3  507.35  4817.6  508.59  4888.3  507.27  4937.7  507.49
  4973.2  508.33  4980.2  508.14  4987.3  504.51  4992.3  503.81  4992.6  503.31
  4996.1  503.31  4996.3  503.81  5008.5   507.8  5052.5  507.73  5100.5  506.82
  5149.9  507.54  5178.2  507.18  5190.5  507.69  5333.8  509.79  5464.8  512.87
#Mann= 5 ,-1 , 0
  4316.1     .05       0  4566.7     .12       0  4992.3     .07       0
  4996.3     .12       0  5190.5     .05       0
Bank Sta=4992.3,4996.3
XS Rating Curve= 0 ,0
Exp/Cntr=0.3,0.1

Type RM Length L Ch R = 1 ,18272   ,295,295,295
BEGIN DESCRIPTION:
Mapping XS d675bde0
END DESCRIPTION:
XS GIS Cut Line= 3
      2691342.37      6957435.34      2690786.06      6957963.21
      2690499.88      6958243.98
#Sta/Elev= 30
  4260.9  512.73  4354.2  511.71  4403.9  509.68    4524  506.48  4538.2  507.04
  4596.8  506.99  4669.4  507.11  4764.7  507.23    4793   507.9  4821.1  507.52
  4849.3  508.17  4856.5  507.63  4884.8  507.95    4920  507.18  4962.5  507.45
  4976.7  507.19  4996.1  503.83  4996.3  503.33  4999.8  503.33  5000.1  503.83
  5024.4  506.25  5047.5  506.17  5089.1  507.52  5118.2  506.42  5169.7  506.92
  5231.3  507.48  5280.8  508.46  5302.1  509.72  5358.6  510.13  5428.7     512
#Mann= 7 ,-1 , 0
  4260.9     .05       0  4596.8     .12       0  4669.4     .05       0
  4996.1     .04       0  5000.1     .05       0  5089.1     .12       0
  5169.7     .05       0
Bank Sta=4996.1,5000.1
XS Rating Curve= 0 ,0
Exp/Cntr=0.3,0.1

Type RM Length L Ch R = 1 ,17977   ,535,535,535
BEGIN DESCRIPTION:
Muddy T8 26.0
END DESCRIPTION:
XS GIS Cut Line= 3
      2691408.81      6957371.89      2690625.84      6957721.07
      2690176.01        6958161.
#Sta/Elev= 30
  4142.7   512.6  4273.6  512.55  4331.9  510.14  4452.6  506.65  4627.6  505.56
  4736.8  506.06  4758.9  505.28  4824.3  504.86  4846.7   504.7  4861.9  504.58
  4862.1  504.08  4865.9  504.58  4933.6  505.33  4967.7  504.66    4991   505.5
  5049.4  504.91  5098.8  506.36  5247.4  508.47  5268.5  509.48  5332.2  510.09
  5388.8  511.96  5459.5  512.82  5473.7  513.61  5565.6  514.49  5572.7  515.49
    5601  514.49    5608  514.65  5622.1  516.85  5625.7  518.11  5629.2  518.11
#Mann= 5 ,-1 , 0
  4142.7     .05       0  4824.3     .12       0  4846.7     .05       0
  4861.9     .04       0  4865.9     .05       0
Bank Sta=4861.9,4865.9
XS Rating Curve= 0 ,0
Exp/Cntr=0.3,0.1

Type RM Length L Ch R = 1 ,17442   ,772,772,772
BEGIN DESCRIPTION:
Mapping XS 637eac18
END DESCRIPTION:
XS GIS Cut Line= 3
      2691241.04      6957078.18      2690385.98       6957273.5
      2689840.06      6957689.44
#Sta/Elev= 30
  4125.6  511.16  4192.3  510.79  4346.2  506.07  4484.5  504.04    4500     503
  4582.1  503.14  4602.6  502.37  4684.7  503.64  4756.5  502.75  4807.8   503.3
  4876.8  502.16  4967.9  503.14    4973  497.85  4982.1  499.02  4990.4  495.39
  4990.7  494.89  4994.4  495.39  5000.1  497.39  5004.7  497.39  5007.9   499.6
  5015.2  499.81  5022.4  502.44  5028.7  501.67  5118.5  502.85    5301  505.46
  5429.8  508.64  5521.4   512.1  5543.2  511.94  5685.6  515.85    5689  515.31
#Mann= 5 ,-1 , 0
  4125.6     .05       0  4484.5     .12       0  4990.4     .07       0
  4994.4     .12       0  5118.5     .05       0
Bank Sta=4990.4,4994.4
XS Rating Curve= 0 ,0
Exp/Cntr=0.3,0.1

Type RM Length L Ch R = 1 ,16670   ,412,412,412
BEGIN DESCRIPTION:
Mapping XS 1e5a81b3
END DESCRIPTION:
XS GIS Cut Line= 3
      2691249.67      6956926.27      2690238.41      6956661.52
       2689574.8      6957186.34
#Sta/Elev= 30
  3993.6  509.47  4183.5  508.93  4388.8  504.02  4565.9  500.65  4896.7   500.2
  4902.4  497.86  4907.5  500.07  4942.8  496.67  4948.4  494.56    4978   499.5
  5000.1  499.58  5013.6   495.2  5018.4  492.58  5023.6  493.68  5029.1  488.17
  5029.4  487.67  5033.1  488.17  5037.6  491.59  5048.1  493.82  5054.8   497.8
  5073.5  498.92  5154.7  499.13  5189.9  503.86  5268.5  505.74  5353.4  504.67
  5609.9  507.79  5624.3  509.74  5645.1  508.09  5831.1  509.19    5885  511.63
#Mann= 7 ,-1 , 0
  3993.6     .05       0  4388.8     .12       0  5013.6     .05       0
  5029.1     .07       0  5033.1     .05       0  5048.1     .12       0
  5073.5     .05       0
Bank Sta=5029.1,5033.1
XS Rating Curve= 0 ,0
Exp/Cntr=0.3,0.1

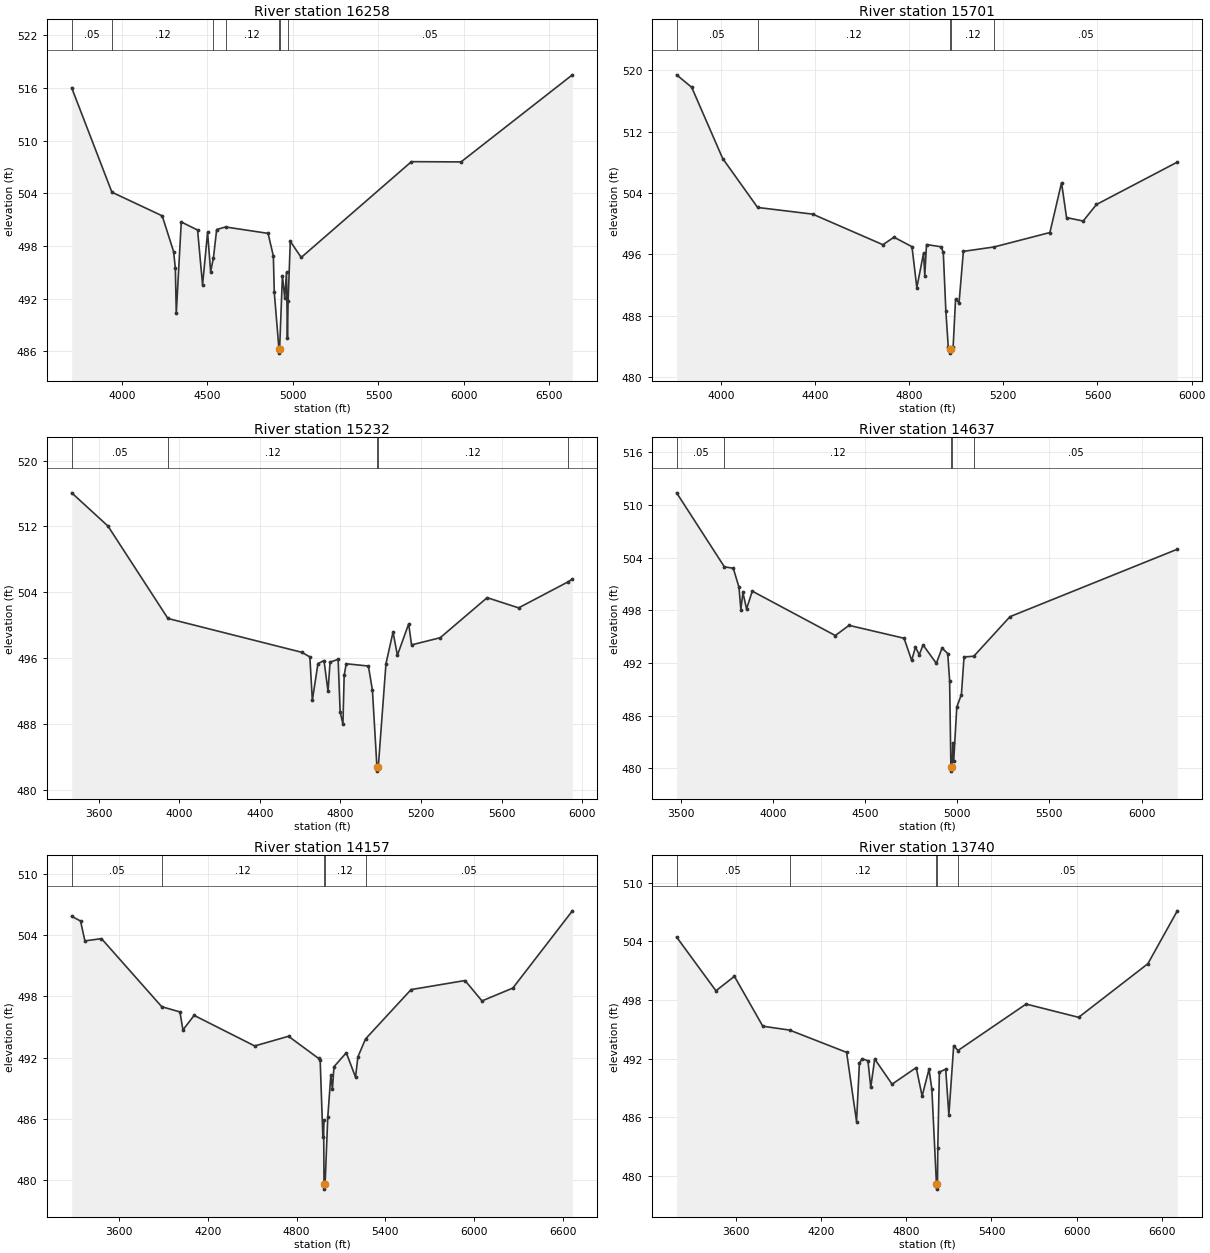
Type RM Length L Ch R = 1 ,16258   ,557,557,557
BEGIN DESCRIPTION:
Muddy T8 22.0
END DESCRIPTION:
XS GIS Cut Line= 3
      2691475.96      6955811.02        2690276.        6956311.
      2689076.03      6957410.97
#Sta/Elev= 30
  3706.3  516.02  3941.4  504.13  4235.5  501.44  4302.1  497.37  4312.4  495.48
  4317.8  490.32    4347  500.74  4442.4  499.82  4471.6  493.57  4500.9  499.56
  4518.8  495.07  4535.2  496.66    4554  499.88  4605.9  500.17  4854.6  499.44
  4885.5  496.86  4890.9  492.73  4918.1   486.3  4918.4   485.8  4922.2   486.3
  4938.5  494.62  4952.1  492.09  4962.4  495.02  4967.8  487.47  4971.8  491.74
  4984.6  498.53  5048.5   496.7  5692.9  507.61    5983  507.58  6634.1   517.5
#Mann= 7 ,-1 , 0
  3706.3     .05       0  3941.4     .12       0  4535.2     .05       0
  4605.9     .12       0  4918.1     .03       0  4922.2     .12       0
  4971.8     .05       0
Bank Sta=4918.1,4922.2
XS Rating Curve= 0 ,0
Exp/Cntr=0.3,0.1

Type RM Length L Ch R = 1 ,15701   ,469,469,469
BEGIN DESCRIPTION:
Mapping XS ae44be0b
END DESCRIPTION:
XS GIS Cut Line= 3
      2691398.26       6955549.4      2690231.61      6955830.65
      2689570.56      6956481.29
#Sta/Elev= 30
  3811.6  519.43  3875.6   517.8  4007.3  508.51  4155.8  502.12  4389.6  501.25
  4688.1  497.26  4735.2  498.24  4811.7     497  4832.3  491.65  4860.9  496.17
  4866.1  493.23  4873.4  497.28  4935.1  496.99  4944.7  496.28  4955.7  488.57
    4966  483.85  4973.1  483.61  4974.1  483.11  4979.5  483.61  4986.6  483.95
  4996.9  490.15  5011.7  489.69  5030.1  496.39  5161.2  496.97  5397.8  498.85
  5447.2  505.35  5468.5   500.8  5539.1  500.35  5595.7  502.51  5939.2  508.04
#Mann= 5 ,-1 , 0
  3811.6     .05       0  4155.8     .12       0  4973.1     .07       0
  4979.5     .12       0  5161.2     .05       0
Bank Sta=4973.1,4979.5
XS Rating Curve= 0 ,0
Exp/Cntr=0.3,0.1

Type RM Length L Ch R = 1 ,15232   ,595,595,595
BEGIN DESCRIPTION:
Mapping XS e7c30a15
END DESCRIPTION:
XS GIS Cut Line= 3
      2691455.57      6955398.36      2689939.94      6955497.32
      2689221.22      6956143.12
#Sta/Elev= 30
    3466  516.08    3646  512.04  3943.7  500.81    4608   496.7  4648.1  496.14
  4660.4  490.86  4688.2  495.32  4718.2   495.7  4738.3  491.96  4748.3  495.51
  4788.4  495.84  4798.4  489.43  4812.3  487.98  4818.4  493.89  4828.5  495.31
  4938.7  495.03  4958.7  492.08    4981  482.76  4982.1  482.26  4987.7  482.76
  5025.8  495.31  5060.9  499.16  5082.6  496.34  5138.6  500.16  5152.8   497.6
  5294.9  498.47  5528.1  503.34  5684.3   502.1    5928  505.24  5951.1   505.6
#Mann= 5 ,-1 , 0
    3466     .05       0  3943.7     .12       0    4981     .07       0
  4987.7     .12       0    5928     .05       0
Bank Sta=4981,4987.7
XS Rating Curve= 0 ,0
Exp/Cntr=0.3,0.1

Type RM Length L Ch R = 1 ,14637   ,480,480,480
BEGIN DESCRIPTION:
Mapping XS cb1ee261
END DESCRIPTION:
XS GIS Cut Line= 3
      2691304.48       6955309.8      2689825.36      6954950.44
      2688861.79      6955653.59
#Sta/Elev= 30
    3479   511.4    3738  502.96  3786.2   502.8    3817  500.64  3827.3  498.09
  3838.4  500.04  3858.2  498.16  3889.1  500.19  4339.5  495.13  4413.9  496.29
  4712.3  494.82  4753.5  492.29  4774.1  493.82  4794.7  492.94  4815.3  494.05
  4887.3  491.96  4918.2   493.7    4949  493.08  4959.3     490  4966.2  480.17
  4967.3  479.67    4973  480.17  4976.2  482.91  4981.3  480.78  4998.2  486.98
  5023.2   488.4  5037.5  492.69  5090.4  492.77  5286.6  497.28    6194  504.97
#Mann= 5 ,-1 , 0
    3479     .05       0    3738     .12       0  4966.2     .07       0
    4973     .12       0  5090.4     .05       0
Bank Sta=4966.2,4973
XS Rating Curve= 0 ,0
Exp/Cntr=0.3,0.1

Type RM Length L Ch R = 1 ,14157   ,417,417,417
BEGIN DESCRIPTION:
Mapping XS 9b0773c2
END DESCRIPTION:
XS GIS Cut Line= 3
      2691513.53      6954896.88      2689832.96      6954563.55
      2688229.88      6955035.45
#Sta/Elev= 30
  3279.8  505.86  3339.6   505.4    3369  503.45  3481.2  503.67  3888.5  496.99
  4011.3  496.48  4031.7  494.71  4107.4  496.14  4516.9  493.14  4745.3  494.09
  4949.2  491.91  4959.4  491.74  4977.6   484.2  4982.7  485.89  4985.4  479.59
  4986.6  479.09  4992.6  479.59  5010.8  486.16  5031.6  490.28  5042.2  488.89
  5052.5   491.1  5135.9  492.47  5198.4  490.08  5214.2  492.06    5266  493.83
  5573.7  498.67  5938.5  499.56  6053.2  497.56  6261.7  498.82  6664.2   506.4
#Mann= 5 ,-1 , 0
  3279.8     .05       0  3888.5     .12       0  4985.4     .07       0
  4992.6     .12       0    5266     .05       0
Bank Sta=4985.4,4992.6
XS Rating Curve= 0 ,0
Exp/Cntr=0.3,0.1

Type RM Length L Ch R = 1 ,13740   ,1117,1117,1117
BEGIN DESCRIPTION:
Mapping XS eb974955
END DESCRIPTION:
XS GIS Cut Line= 3
      2691492.71      6954341.33      2689673.23      6954230.21
      2688140.94      6954985.96
#Sta/Elev= 30
  3179.5  504.44  3456.7  498.94    3587  500.42  3787.3  495.31  3976.8  494.91
  4378.4  492.63  4448.6  485.54  4468.6  491.53  4488.6  491.98  4528.7  491.77
  4548.8  489.05  4576.6  491.95    4699  489.37  4869.4  491.07  4910.9  488.15
  4959.5   490.9  4979.6  488.87  5012.1  479.12  5013.3  478.62  5019.3  479.12
  5021.6  482.85  5032.6  490.61  5077.3  490.91  5099.6  486.21  5133.6  493.32
  5163.8  492.82  5644.4  497.58  6014.8  496.22  6503.2  501.71  6710.9  507.13
#Mann= 5 ,-1 , 0
  3179.5     .05       0  3976.8     .12       0  5012.1     .07       0
  5019.3     .12       0  5163.8     .05       0
Bank Sta=5012.1,5019.3
XS Rating Curve= 0 ,0
Exp/Cntr=0.3,0.1

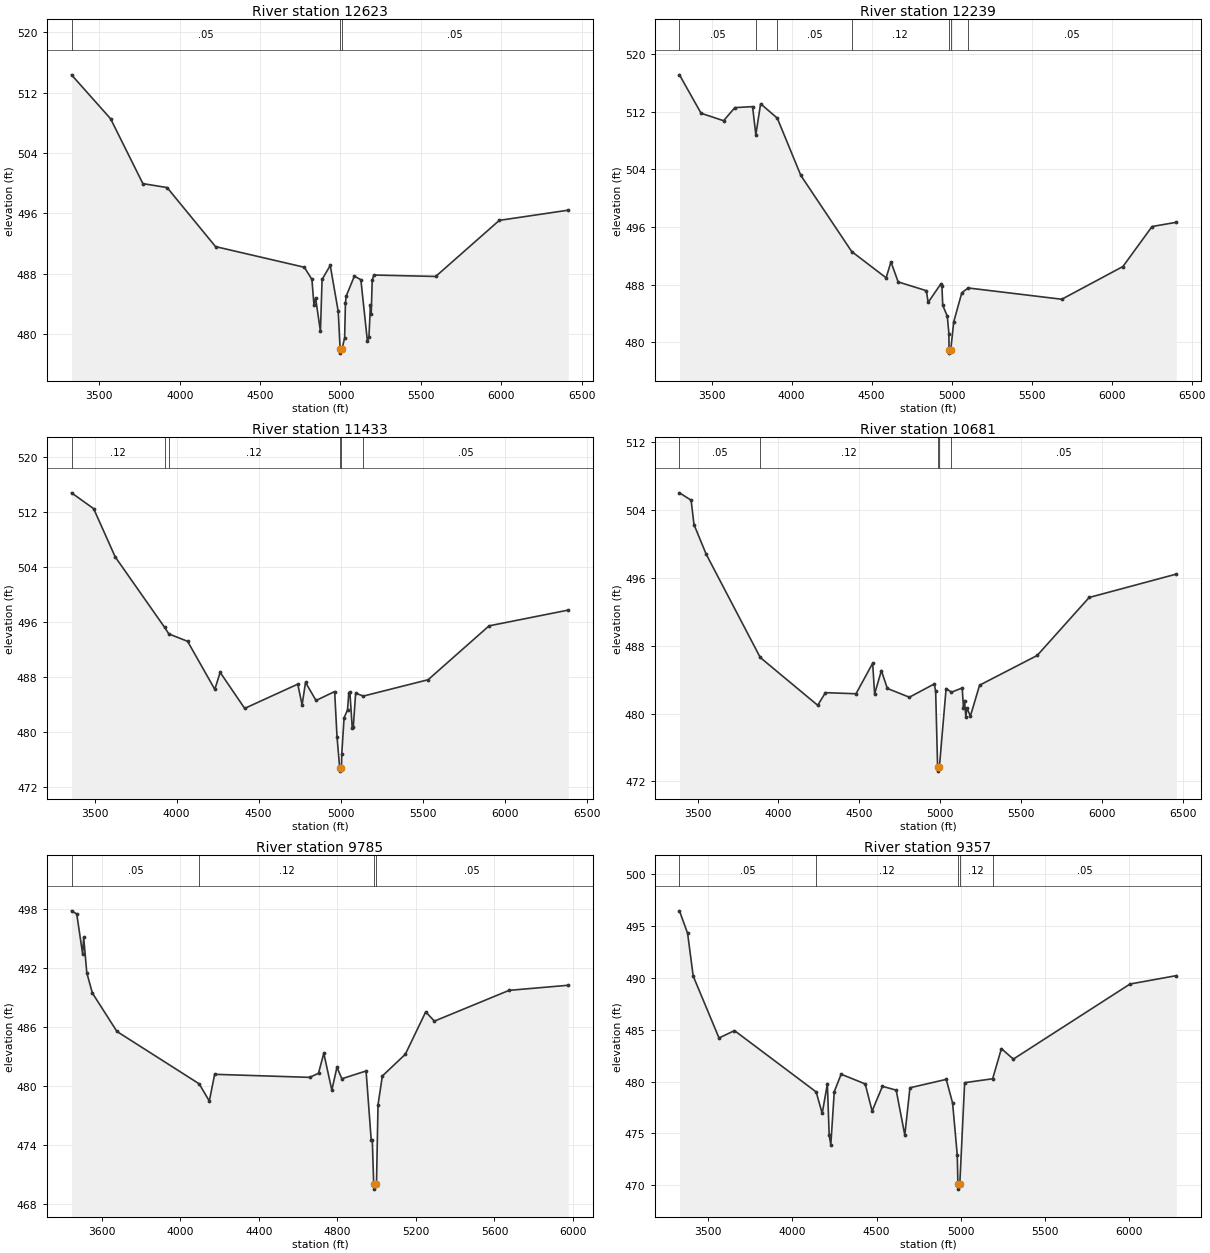
Type RM Length L Ch R = 1 ,12623   ,384,384,384
BEGIN DESCRIPTION:
Mapping XS f57c5c0e
END DESCRIPTION:
XS GIS Cut Line= 3
      2691138.11      6953106.63      2689466.25      6953262.88
      2688065.24      6953439.96
#Sta/Elev= 30
  3326.7  514.34  3569.9  508.53  3770.7  499.95  3921.4  499.43  4222.7  491.62
  4775.1  488.89  4822.4  487.28  4835.4  483.83  4845.4  484.84  4875.5   480.4
  4885.6  487.27  4936.4  489.13    4986  483.07  4998.1  478.03  4999.6  477.53
  5008.8  478.03    5026  479.54    5031  484.21  5036.3   485.1  5086.7  487.72
    5127  487.24  5167.4  479.17  5177.4  479.71  5186.4  483.86  5191.4  482.75
  5197.6  487.18  5207.7  487.86  5592.4  487.67  5988.3  495.09    6418  496.44
#Mann= 3 ,-1 , 0
  3326.7     .05       0  4998.1     .03       0  5008.8     .05       0
Bank Sta=4998.1,5008.8
XS Rating Curve= 0 ,0
Exp/Cntr=0.3,0.1

Type RM Length L Ch R = 1 ,12239   ,806,806,806
BEGIN DESCRIPTION:
Mapping XS c0f68cc7
END DESCRIPTION:
XS GIS Cut Line= 3
      2690980.15       6952787.3      2689298.39      6952971.39
      2687895.43      6953146.88
#Sta/Elev= 30
  3298.6  517.15  3433.6  511.81  3574.4  510.77  3644.8  512.59  3755.5  512.73
    3776  508.81  3805.8  513.13    3910  511.13  4057.3  503.16  4375.3  492.58
  4590.4  488.93  4620.6  491.14  4665.5  488.36  4841.9  487.14    4853  485.51
  4932.5  488.09  4939.2  487.81  4944.2  485.11  4972.7  483.59  4982.8  481.18
  4983.5  478.96    4985  478.46  4994.6  478.96    5013  482.82  5063.4  486.85
  5102.9  487.52  5688.2  485.95  6070.5   490.5  6252.6  496.06  6404.3  496.65
#Mann= 7 ,-1 , 0
  3298.6     .05       0    3776     .12       0    3910     .05       0
  4375.3     .12       0  4983.5     .07       0  4994.6     .12       0
  5102.9     .05       0
Bank Sta=4983.5,4994.6
XS Rating Curve= 0 ,0
Exp/Cntr=0.3,0.1

Type RM Length L Ch R = 1 ,11433   ,752,752,752
BEGIN DESCRIPTION:
Mapping XS b3789121
END DESCRIPTION:
XS GIS Cut Line= 4
      2690189.27      6952156.87      2688807.35      6952372.14
      2688355.96      6952934.64      2687467.09      6953129.08
#Sta/Elev= 30
  3358.7  514.74  3493.6  512.44  3625.1  505.42  3926.1  495.17  3952.2  494.21
  4066.6  493.13  4232.4  486.14  4265.2  488.61  4414.6  483.37  4738.4   486.9
  4764.8  483.86  4785.6  487.16  4849.7  484.52  4963.3  485.82  4977.7  479.24
  4993.9  474.74  4995.4  474.24    5005  474.74  5006.5   476.7  5020.9  482.01
  5041.7  483.15  5049.7  485.66  5056.1  485.77  5070.5  480.53  5076.9  480.64
  5091.3  485.59  5137.8  485.16  5533.2  487.54  5904.7  495.38  6388.4  497.68
#Mann= 6 ,-1 , 0
  3358.7     .12       0  3926.1     .05       0  3952.2     .12       0
  4993.9     .07       0    5005     .12       0  5137.8     .05       0
Bank Sta=4993.9,5005
XS Rating Curve= 0 ,0
Exp/Cntr=0.3,0.1

Type RM Length L Ch R = 1 ,10681   ,896,896,896
BEGIN DESCRIPTION:
Mapping XS cc5c99b5
END DESCRIPTION:
XS GIS Cut Line= 3
      2689855.94      6951594.37       2688300.4      6951969.36
      2687147.62      6952879.09
#Sta/Elev= 30
  3388.4  506.04  3460.3  505.17  3478.2  502.29  3552.9  498.82  3887.3  486.61
  4242.1  480.97  4289.9  482.46  4478.7  482.33  4581.6  485.93  4593.6  482.31
  4635.5  485.06  4672.2  482.96  4808.2  481.92  4962.2  483.49  4970.7   482.6
  4982.6   473.7  4984.1   473.2  4993.7   473.7  5035.1  482.94  5068.4  482.52
  5134.5  483.01  5142.5  480.69  5148.9  481.53    5157   479.6  5163.4  480.66
  5185.2  479.69  5241.9  483.34  5597.8  486.85  5918.5  493.69    6457  496.45
#Mann= 5 ,-1 , 0
  3388.4     .05       0  3887.3     .12       0  4982.6     .07       0
  4993.7     .12       0  5068.4     .05       0
Bank Sta=4982.6,4993.7
XS Rating Curve= 0 ,0
Exp/Cntr=0.3,0.1

Type RM Length L Ch R = 1 ,9785    ,428,428,428
BEGIN DESCRIPTION:
Mapping XS 0abf69c9
END DESCRIPTION:
XS GIS Cut Line= 3
      2689592.11      6951538.82      2688099.02      6951219.36
      2687210.56      6951684.42
#Sta/Elev= 30
  3446.7  497.79  3473.4  497.47  3503.5  493.39  3508.6  495.11  3524.5  491.49
  3552.9  489.43  3677.9  485.52  4096.8  480.19  4148.3  478.44  4175.5  481.16
  4659.9  480.85  4704.3  481.27  4731.2   483.3  4772.1  479.55  4798.1  481.87
  4823.3  480.71  4946.5   481.5  4972.6  474.48  4978.1  474.48  4985.3  469.98
  4986.9  469.48  4996.5  469.98  4999.6  470.15  5007.3  478.06  5029.4  480.99
  5146.3   483.2  5250.1  487.51  5294.2  486.57  5674.5   489.7  5976.4  490.22
#Mann= 4 ,-1 , 0
  3446.7     .05       0  4096.8     .12       0  4985.3     .04       0
  4996.5     .05       0
Bank Sta=4985.3,4996.5
XS Rating Curve= 0 ,0
Exp/Cntr=0.3,0.1

Type RM Length L Ch R = 1 ,9357    ,541,541,541
BEGIN DESCRIPTION:
Mapping XS 5fc5ea9f
END DESCRIPTION:
XS GIS Cut Line= 4
      2689695.82      6951186.36      2688206.54      6950876.06
      2688004.07      6950764.19      2687136.56      6951589.98
#Sta/Elev= 30
  3329.1  496.49  3377.4  494.32  3410.6  490.19  3563.9  484.21  3655.8  484.92
  4140.7     479  4176.7  476.92  4207.4  479.79    4218  474.84  4227.8  473.89
  4248.2  479.02  4289.1  480.71  4432.1  479.77    4473  477.15  4534.3  479.54
    4616  479.17  4667.1  474.83  4697.7   479.4  4913.2  480.21    4951  477.92
  4978.5  472.92  4982.5  470.11    4984  469.61  4993.7  470.11  5022.4  479.89
  5188.7  480.27  5240.8  483.18  5311.6  482.17  6004.5  489.42  6279.4  490.23
#Mann= 5 ,-1 , 0
  3329.1     .05       0  4140.7     .12       0  4982.5     .07       0
  4993.7     .12       0  5188.7     .05       0
Bank Sta=4982.5,4993.7
XS Rating Curve= 0 ,0
Exp/Cntr=0.3,0.1

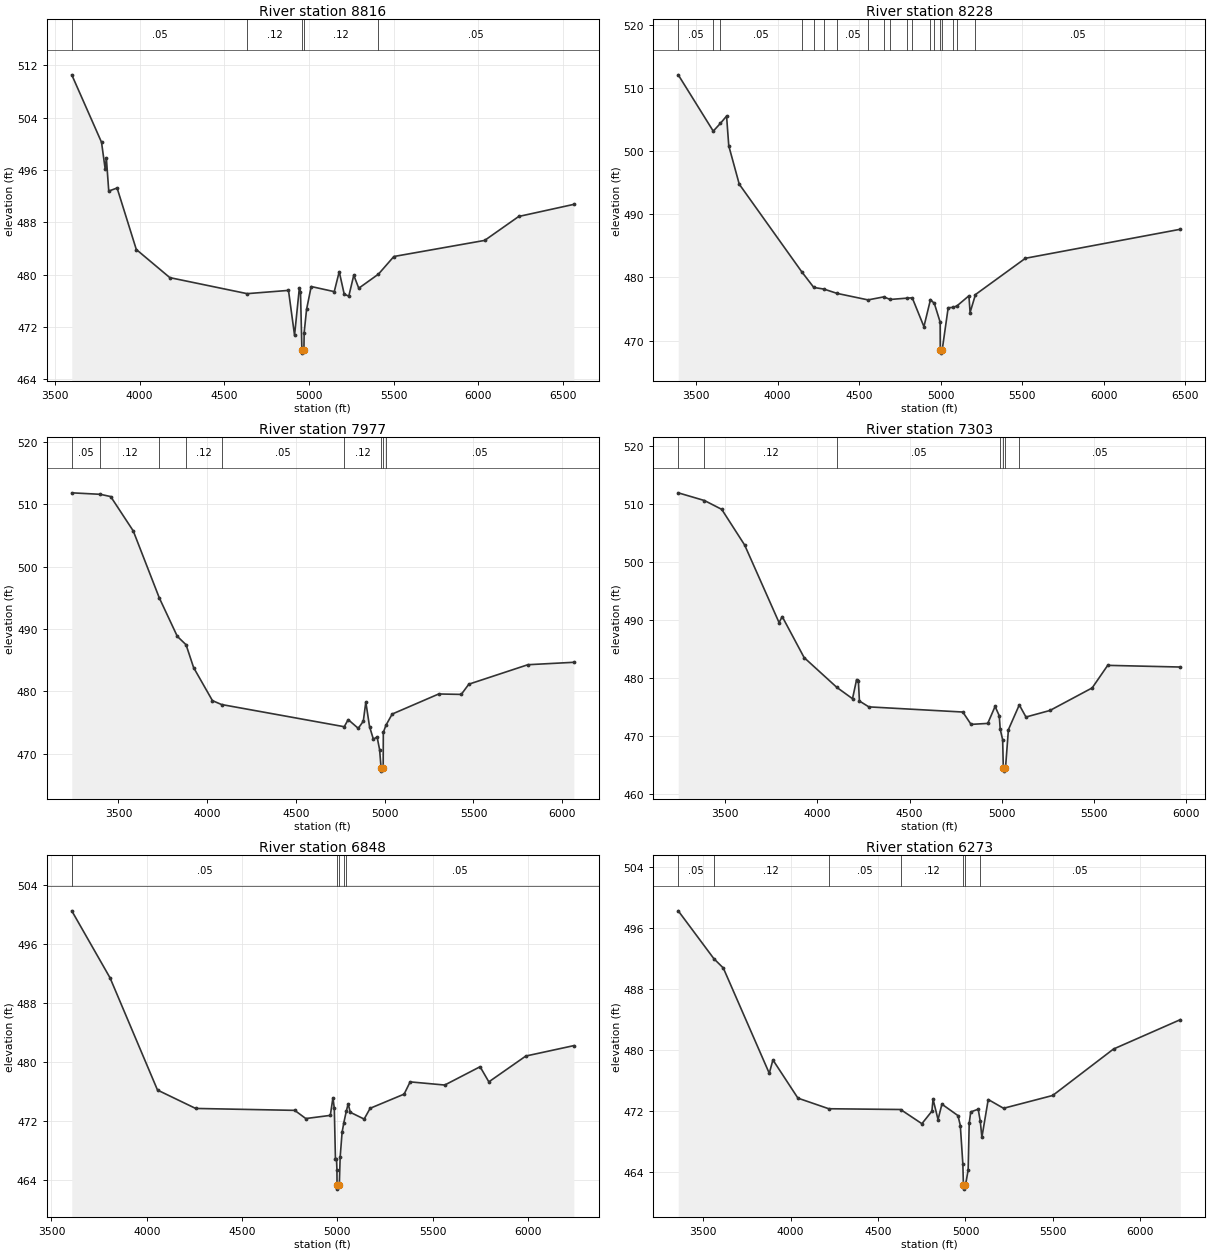
Type RM Length L Ch R = 1 ,8816    ,588,588,588
BEGIN DESCRIPTION:
Mapping XS 86219cc9
END DESCRIPTION:
XS GIS Cut Line= 3
      2689062.59      6949369.11        2688026.        6950311.
       2687110.7      6951580.18
#Sta/Elev= 30
  3599.4  510.56  3775.2  500.25  3796.8  496.14  3803.6  497.87  3817.8  492.79
  3867.1  493.26  3980.6  483.86  4178.6  479.56  4635.2  477.11  4879.4  477.61
  4915.2  470.75  4943.6  477.97  4950.3   477.4  4958.7  468.52  4960.3  468.02
  4970.4  468.52    4972  471.15  4986.1  474.69  5013.5   478.2  5149.7  477.42
  5179.1  480.47  5208.6  477.03  5235.6  476.73    5265  479.93  5294.5  477.94
    5411   480.1  5501.8  482.79  6038.1  485.25  6239.3  488.91  6564.8  490.76
#Mann= 5 ,-1 , 0
  3599.4     .05       0  4635.2     .12       0  4958.7     .07       0
  4970.4     .12       0    5411     .05       0
Bank Sta=4958.7,4970.4
XS Rating Curve= 0 ,0
Exp/Cntr=0.3,0.1

Type RM Length L Ch R = 1 ,8228    ,251,251,251
BEGIN DESCRIPTION:
Mapping XS 494ff4f7
END DESCRIPTION:
XS GIS Cut Line= 3
      2688877.19      6948824.02      2687663.69      6949907.33
      2686628.34      6950927.06
#Sta/Elev= 30
  3390.1  512.13  3604.9   503.2  3649.3  504.45  3686.6  505.59  3700.1  500.87
  3764.4  494.79  4147.4  480.91  4221.8  478.41  4283.1  478.16  4364.9  477.47
  4554.3  476.44  4651.1  476.92    4690  476.51  4794.2  476.72  4825.6  476.77
  4897.2   472.2  4937.4  476.49  4961.3  475.87  4996.7  472.92  4997.5   468.5
  4999.1     468  5009.3   468.5    5046   475.2  5077.4  475.25  5100.9  475.51
  5173.3  477.09  5180.4  474.44  5213.5  477.29  5519.8  483.04    6470  487.64
#Mann= 19 ,-1 , 0
  3390.1     .05       0  3604.9     .12       0  3649.3     .05       0
  4147.4     .12       0  4221.8     .05       0  4283.1     .12       0
  4364.9     .05       0  4554.3     .12       0  4651.1     .05       0
    4690     .12       0  4794.2     .05       0  4825.6     .12       0
  4937.4     .05       0  4961.3     .12       0  4997.5     .07       0
  5009.3     .12       0  5077.4     .05       0  5100.9     .12       0
  5213.5     .05       0
Bank Sta=4997.5,5009.3
XS Rating Curve= 0 ,0
Exp/Cntr=0.3,0.1

Type RM Length L Ch R = 1 ,7977    ,674,674,674
BEGIN DESCRIPTION:
Mapping XS 48e33fbd
END DESCRIPTION:
XS GIS Cut Line= 3
      2688799.08      6948594.85      2687481.39      6949782.33
      2686773.04       6950563.6
#Sta/Elev= 30
  3237.1  511.82  3398.5  511.58  3456.4  511.22  3583.5  505.71  3730.1  494.98
  3831.6  488.81    3881  487.46  3923.5   483.8  4029.6   478.5  4080.8  477.88
  4772.1  474.32  4794.2  475.46    4851  474.06  4879.4   475.2  4893.6  478.28
  4914.5  474.35  4936.2  472.32  4957.1  472.68  4971.3  470.64  4979.6   467.7
  4981.3   467.2  4991.4   467.7  4992.2  473.41  5006.8  474.54  5042.1  476.35
  5304.3  479.57  5431.3   479.5  5473.9  481.14  5806.4  484.26  6065.5  484.65
#Mann= 9 ,-1 , 0
  3237.1     .05       0  3398.5     .12       0  3730.1     .05       0
    3881     .12       0  4080.8     .05       0  4772.1     .12       0
  4979.6     .07       0  4991.4     .12       0  5006.8     .05       0
Bank Sta=4979.6,4991.4
XS Rating Curve= 0 ,0
Exp/Cntr=0.3,0.1

Type RM Length L Ch R = 1 ,7303    ,455,455,455
BEGIN DESCRIPTION:
Mapping XS ae826a1e
END DESCRIPTION:
XS GIS Cut Line= 3
      2688679.35      6948521.89      2687090.77      6949282.33
        2686721.       6950172.9
#Sta/Elev= 30
  3244.1     512  3386.6  510.67  3480.2  509.15  3604.6     503  3791.5  489.62
  3808.6  490.66  3927.5  483.59  4105.5  478.44  4190.2   476.5  4212.4   479.8
  4222.1   479.5  4227.7   476.1  4278.9  475.09  4788.9   474.2  4833.6  472.07
  4924.3  472.24  4964.1  475.17  4986.8  473.56  4991.9  471.25  5005.2  469.42
  5008.8  464.51  5010.4  464.01  5020.6  464.51  5036.4  471.16  5095.5  475.43
  5131.7  473.34  5261.9  474.47  5491.1  478.36  5575.4  482.25  5969.6  481.96
#Mann= 7 ,-1 , 0
  3244.1     .05       0  3386.6     .12       0  4105.5     .05       0
  4991.9     .12       0  5008.8     .07       0  5020.6     .12       0
  5095.5     .05       0
Bank Sta=5008.8,5020.6
XS Rating Curve= 0 ,0
Exp/Cntr=0.3,0.1

Type RM Length L Ch R = 1 ,6848    ,575,575,575
BEGIN DESCRIPTION:
Mapping XS 4772721a
END DESCRIPTION:
XS GIS Cut Line= 3
      2687830.35      6948313.58      2686731.39      6949162.54
      2686356.39      6950350.05
#Sta/Elev= 30
  3606.4  500.49  3807.2  491.41  4056.2  476.21  4256.3  473.72  4776.2  473.46
  4834.2  472.35  4962.8  472.78  4976.6  475.17  4983.7  473.73  4989.7  466.91
  4995.1  466.91  4997.5  465.44  4998.1  463.29  4999.7  462.79  5009.9  463.29
  5014.4  467.12  5024.6  470.49  5033.7  471.79  5046.5  473.33  5056.4  474.35
  5067.5   473.2  5140.3  472.28  5171.7  473.74    5350  475.66  5381.5  477.32
    5563  476.89  5748.5  479.37  5794.5  477.32  5988.5  480.82  6240.4  482.23
#Mann= 5 ,-1 , 0
  3606.4     .05       0  4998.1     .03       0  5009.9     .05       0
  5033.7     .12       0  5046.5     .05       0
Bank Sta=4998.1,5009.9
XS Rating Curve= 0 ,0
Exp/Cntr=0.3,0.1

Type RM Length L Ch R = 1 ,6273    ,599,599,599
BEGIN DESCRIPTION:
Mapping XS 27b0676a
END DESCRIPTION:
XS GIS Cut Line= 3
      2687479.62       6947941.1      2686250.49      6948975.79
      2685563.74      6950037.13
#Sta/Elev= 30
  3357.5  498.27  3561.1     492  3615.3  490.77    3878  476.97  3898.9  478.72
  4041.9  473.71  4218.2  472.32  4628.9  472.22  4750.7  470.36  4807.9     472
  4814.5  473.57    4843   470.9  4865.1  472.92    4957  471.42  4970.4  470.12
  4984.9  465.08  4988.2  462.28  4989.8  461.78    5000  462.28  5015.2   464.3
  5021.2  470.41  5029.9   471.9  5072.6  472.26  5084.7  470.66  5093.7  468.57
    5130  473.53  5217.7  472.38  5498.7  474.06  5846.3  480.15  6228.3     484
#Mann= 7 ,-1 , 0
  3357.5     .05       0  3561.1     .12       0  4218.2     .05       0
  4628.9     .12       0  4988.2     .07       0    5000     .12       0
  5084.7     .05       0
Bank Sta=4988.2,5000
XS Rating Curve= 0 ,0
Exp/Cntr=0.3,0.1