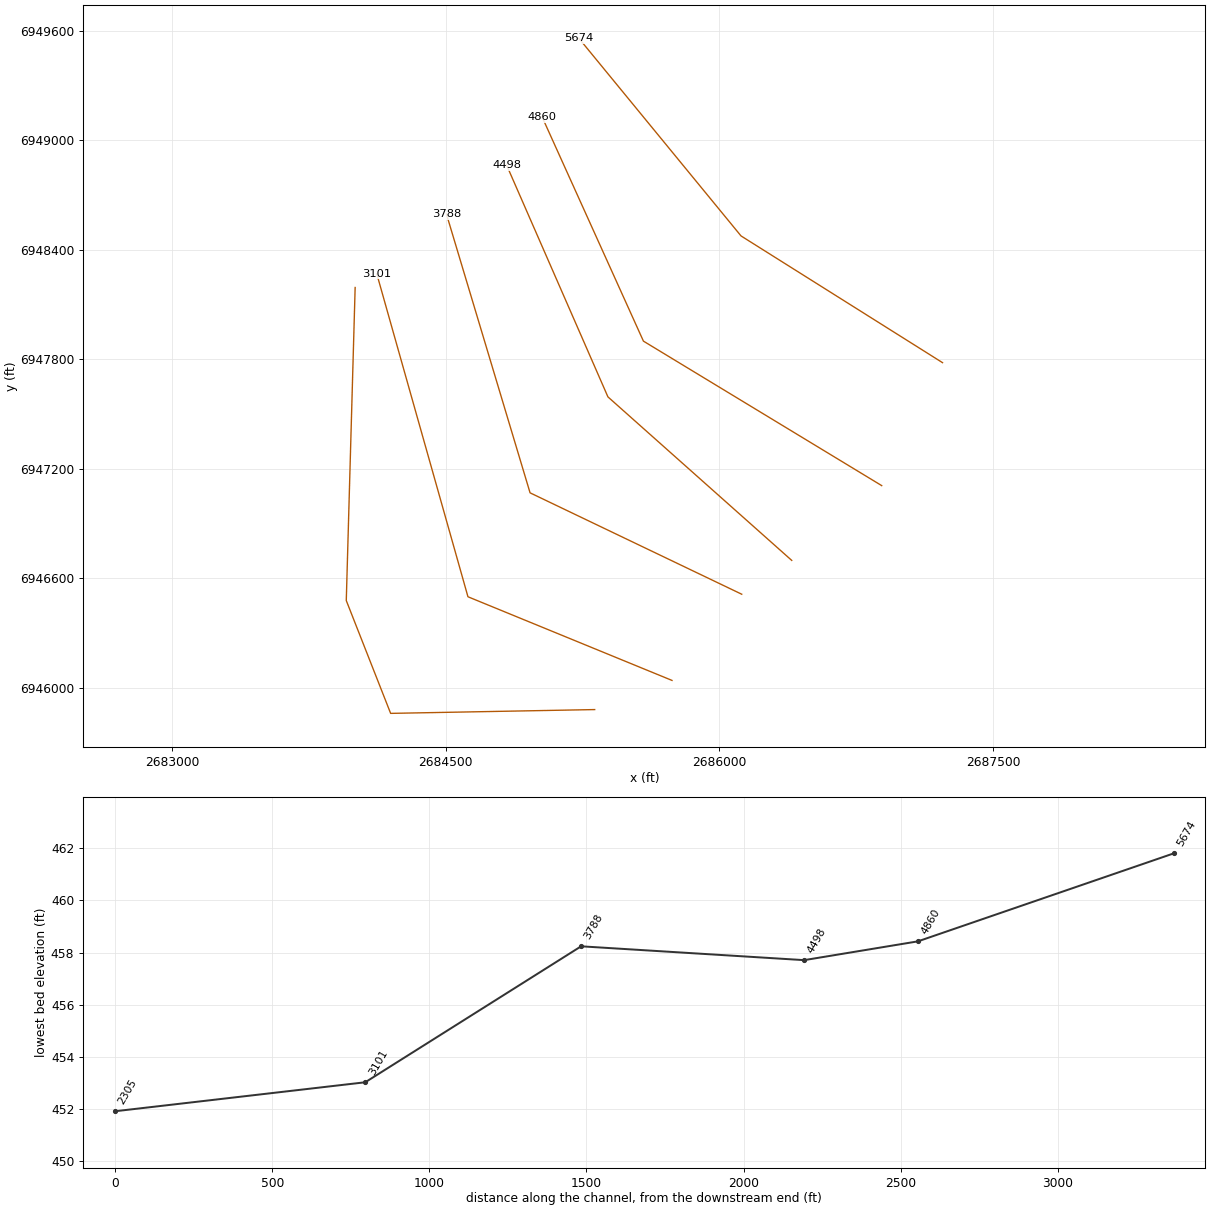
HEC-RAS study Muddy T8.prj: Muddy T8 Base Level Engineering

--- Muddy T8.g01 (geometry) --- (continued)

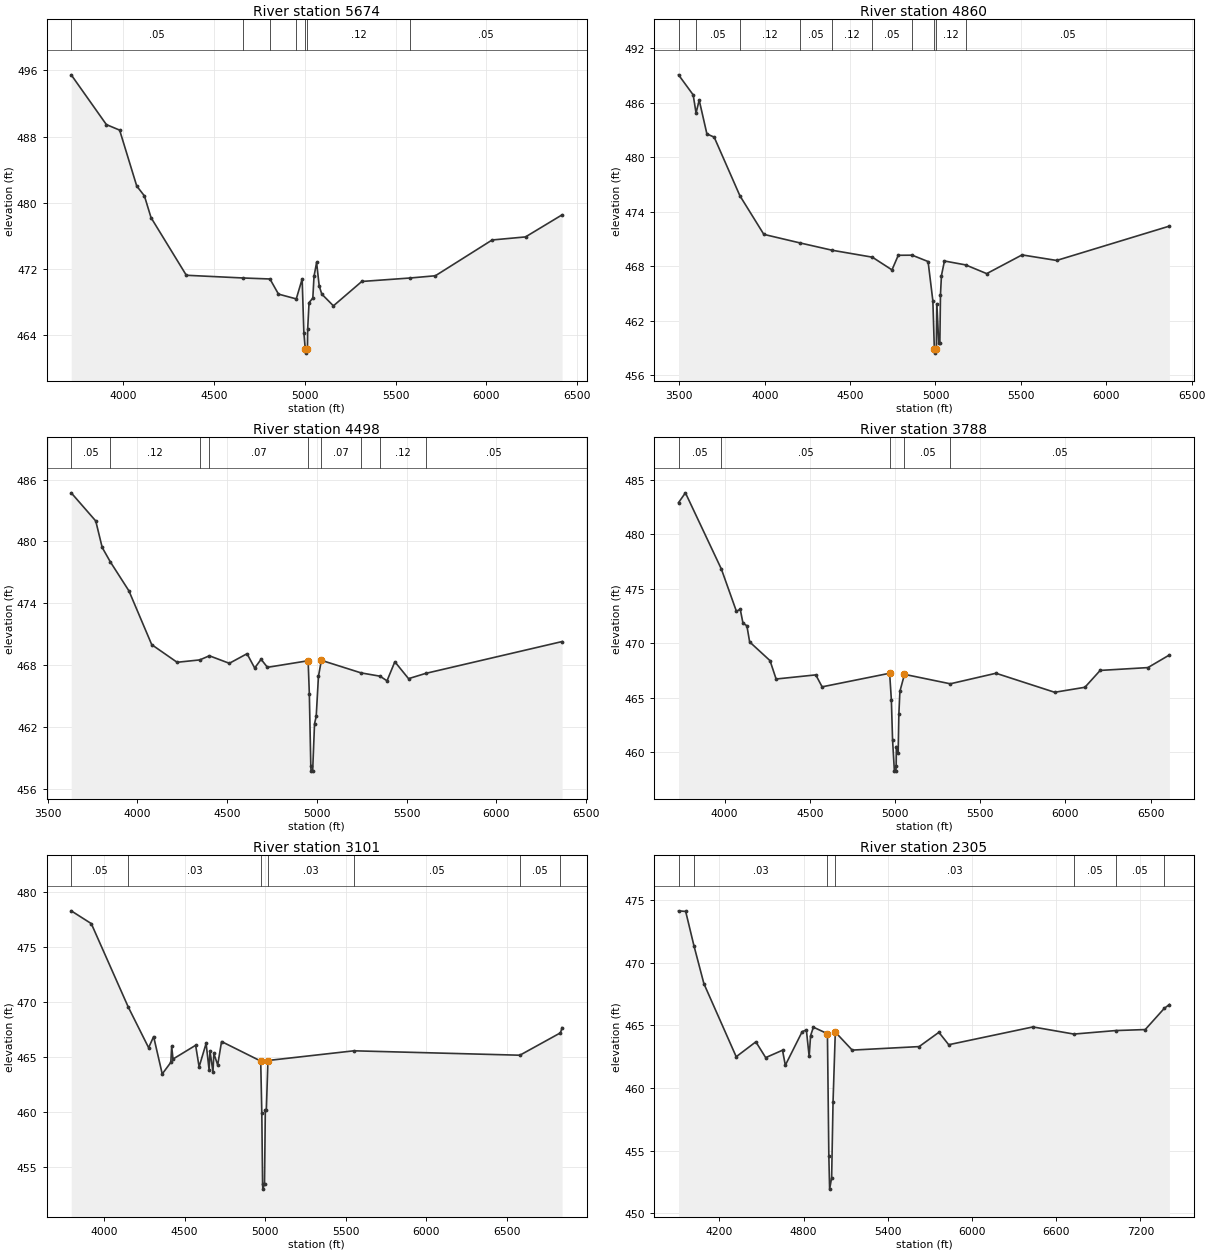
Type RM Length L Ch R = 1 ,5674    ,814,814,814
BEGIN DESCRIPTION:
Mapping XS 574ddb5d
END DESCRIPTION:
XS GIS Cut Line= 3
      2687222.71      6947781.35      2686118.55      6948475.79
      2685230.31      6949558.34
#Sta/Elev= 30
  3712.1  495.47  3905.9  489.45  3978.9  488.78  4073.1  482.02  4115.5  480.82
    4152  478.19  4346.4  471.22  4660.9  470.89  4807.2  470.77  4854.1  468.94
  4952.2  468.36  4984.6  470.77    4994  464.29  5001.7   462.3  5003.4   461.8
  5013.7   462.3    5015  464.71  5022.6  467.91  5043.4  468.46  5049.9  471.08
  5064.2  472.77  5078.6  469.92  5092.9  468.94  5156.8  467.52  5313.2  470.47
  5579.4  470.89  5718.7  471.16  6031.5  475.49  6215.3  475.86  6416.8  478.53
#Mann= 7 ,-1 , 0
  3712.1     .05       0  4660.9     .12       0  4807.2     .05       0
  4952.2     .12       0  5001.7     .07       0  5013.7     .12       0
  5579.4     .05       0
Bank Sta=5001.7,5013.7
XS Rating Curve= 0 ,0
Exp/Cntr=0.3,0.1

Type RM Length L Ch R = 1 ,4860    ,362,362,362
BEGIN DESCRIPTION:
Mapping XS 4d937a62
END DESCRIPTION:
XS GIS Cut Line= 3
      2686889.35      6947107.76      2685583.83      6947899.41
      2685028.84      6949127.31
#Sta/Elev= 30
  3495.4  489.06  3581.2  486.85  3597.9  484.85  3616.3  486.28  3661.4  482.56
  3704.1   482.2  3854.7  475.75  3994.9   471.5  4206.4  470.56  4395.8  469.75
  4630.3  468.99  4745.2  467.59  4782.1   469.2  4863.4  469.21  4956.6  468.51
  4984.6  464.18  4993.2  458.93  4994.9  458.43  5005.2  458.93    5008  463.88
  5018.9  459.56  5025.6  459.56  5029.2  464.88  5034.9  466.97  5052.4  468.57
  5176.6  468.14    5300  467.18  5506.8  469.24  5709.4  468.63  6369.7  472.41
#Mann= 10 ,-1 , 0
  3495.4     .12       0  3597.9     .05       0  3854.7     .12       0
  4206.4     .05       0  4395.8     .12       0  4630.3     .05       0
  4863.4     .12       0  4993.2     .05       0  5005.2     .12       0
  5176.6     .05       0
Bank Sta=4993.2,5005.2
XS Rating Curve= 0 ,0
Exp/Cntr=0.3,0.1

Type RM Length L Ch R = 1 ,4498    ,710,710,710
BEGIN DESCRIPTION:
Mapping XS 9ffc45a7
END DESCRIPTION:
XS GIS Cut Line= 3
      2686396.33      6946698.01      2685389.38      6947593.85
      2684833.84      6948864.66
#Sta/Elev= 30
  3631.7  484.71  3768.4  481.98  3804.3  479.41  3849.4  478.02  3953.2   475.2
  4080.3  469.98  4221.6  468.27  4347.7   468.5  4401.4   468.9  4512.6  468.17
  4611.2   469.1  4653.9  467.71  4689.5  468.56    4725  467.78  4951.6  468.42
  4958.3  465.23  4966.5  458.21  4968.1  457.71  4976.8  457.71  4987.3  462.31
  4996.6  463.02  5009.1   466.9  5025.4  468.46  5246.6  467.24  5352.3  466.92
  5391.1  466.47  5434.7  468.32  5511.1  466.68  5606.1  467.19  6366.4  470.28
#Mann= 9 ,-1 , 0
  3631.7     .05       0  3849.4     .12       0  4347.7     .05       0
  4401.4     .07       0  4951.6     .05       0  5025.4     .07       0
  5246.6     .05       0  5352.3     .12       0  5606.1     .05       0
Bank Sta=4951.6,5025.4
XS Rating Curve= 0 ,0
Exp/Cntr=0.3,0.1

Type RM Length L Ch R = 1 ,3788    ,687,687,687
BEGIN DESCRIPTION:
Mapping XS 2c83918e
END DESCRIPTION:
XS GIS Cut Line= 3
      2686122.43       6946512.7      2684962.73      6947068.24
      2684504.41      6948595.98
#Sta/Elev= 30
  3729.5  482.93  3769.9  483.83  3980.9  476.82  4069.3  472.93  4091.5  473.13
  4107.8  471.84  4130.5  471.61  4146.9  470.12  4266.4   468.4  4302.1  466.71
    4535  467.09  4572.1  465.99  4968.4  467.24  4978.5  464.81  4985.6  461.12
  4996.3  458.24    5005  458.24  5006.7  458.74  5008.2   460.5  5018.4  459.91
  5022.5  463.46  5028.7  465.58  5055.5  467.14  5324.3  466.27  5592.5  467.24
    5937  465.49  6114.5  465.95    6204   467.5  6484.1  467.76  6610.4  468.92
#Mann= 5 ,-1 , 0
  3729.5     .05       0  3980.9     .05       0  4968.4     .03       0
  5055.5     .05       0  5324.3     .05       0
Bank Sta=4968.4,5055.5
XS Rating Curve= 0 ,0
Exp/Cntr=0.3,0.1

Type RM Length L Ch R = 1 ,3101    ,796,796,796
BEGIN DESCRIPTION:
Mapping XS 5c511878
END DESCRIPTION:
XS GIS Cut Line= 3
      2685740.51      6946040.46      2684622.45       6946498.8
      2684122.98      6948267.78
#Sta/Elev= 30
  3796.7  478.28  3921.3  477.12  4151.1  469.54  4277.1  465.86  4308.2  466.87
  4361.6  463.48  4414.9  464.53  4420.3  465.98  4428.4  464.83  4568.9  466.08
  4590.5  464.12  4633.9  466.25  4652.5  463.85  4657.9  465.57  4676.5  463.66
  4681.9  465.34  4705.8  464.29  4729.8  466.42  4972.8  464.65  4979.6  459.95
  4984.4  453.53  4986.1  453.03  4996.4  453.53  5001.4  460.21  5007.7  460.21
  5017.7   464.7  5551.3  465.58  6581.3  465.18  6833.1  467.21  6843.2  467.68
#Mann= 7 ,-1 , 0
  3796.7     .05       0  4151.1     .03       0  4972.8     .03       0
  5017.7     .03       0  5551.3     .05       0  6581.3     .05       0
  6833.1     .05       0
Bank Sta=4972.8,5017.7
XS Rating Curve= 0 ,0
Exp/Cntr=0.3,0.1

Type RM Length L Ch R = 1 ,2305    ,0,0,0
BEGIN DESCRIPTION:
Mapping XS 28873f56
END DESCRIPTION:
XS GIS Cut Line= 4
      2685316.88      6945880.74      2684198.84      6945859.91
      2683955.79      6946477.96       2684004.4      6948193.21
#Sta/Elev= 30
  3908.3  474.14  3959.2  474.09  4017.7  471.37  4089.2  468.32  4319.3  462.49
  4459.3  463.68  4529.3  462.42  4649.3  463.01  4669.3  461.81  4789.3  464.49
  4819.3  464.63  4839.3  462.51  4849.3  464.17  4869.3  464.85  4969.4  464.33
  4979.4  454.59    4985  451.92  4999.4  452.82  5009.4  458.89  5025.5  464.46
  5145.9  463.02  5622.9   463.3  5763.7  464.44  5833.8  463.45    6434  464.87
  6725.8   464.3  7023.2  464.58  7234.3  464.66  7369.8  466.35  7406.6  466.66
#Mann= 7 ,-1 , 0
  3908.3     .05       0  4017.7     .03       0  4969.4     .03       0
  5025.5     .03       0  6725.8     .05       0  7023.2     .05       0
  7369.8     .05       0
Bank Sta=4969.4,5025.5
XS Rating Curve= 0 ,0
Exp/Cntr=0.3,0.1

Chan Stop Cuts=-1
Use User Specified Reach Order=0
Composite Channel Slope=5