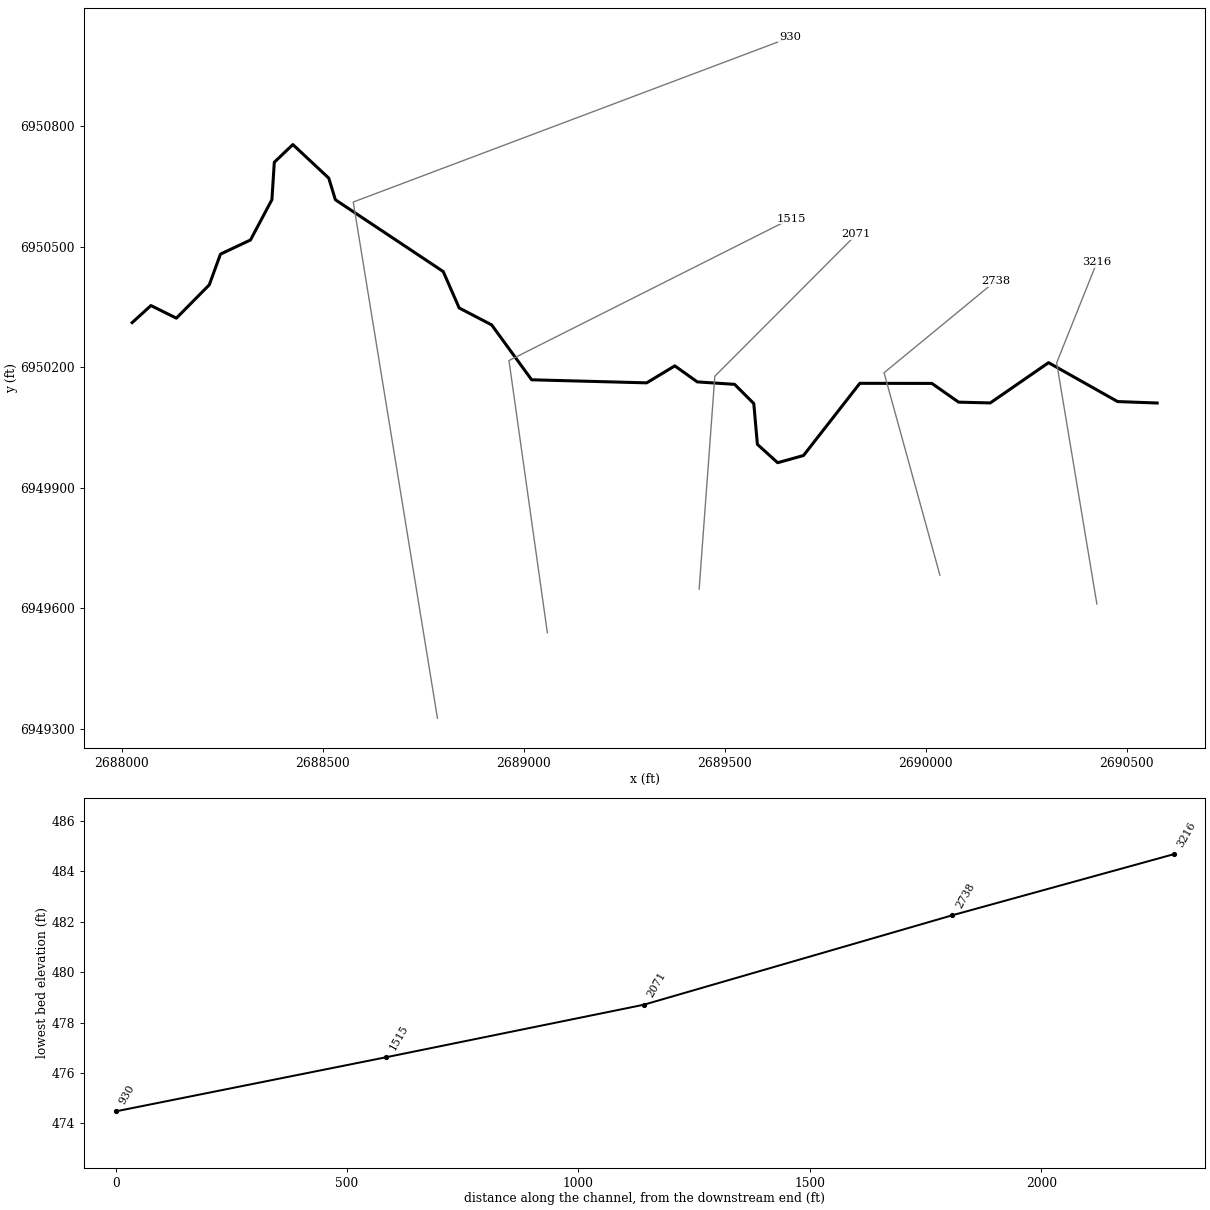
--- Muddy T8_1.prj (project) ---

Proj Title=Muddy T8_1 Base Level Engineering
Current Plan=p01
Default Exp/Contr=0.3,0.1
English Units
Geom File=g01
Flow File=f01
Plan File=p01
BEGIN DESCRIPTION:
Muddy T8_1
END DESCRIPTION:

--- Muddy T8_1.p01 (plan) ---

Plan Title=Multiple Run
Short Identifier=Multiple
Geom File=g01
Flow File=f01
Subcritical Flow
K Sum by GR= 0
Std Step Tol= 0.01
Critical Tol= 0.01
Num of Std Step Trials= 20
Max Error Tol= 0.3
Flow Tol Ratio= 0.001
Split Flow NTrial= 30
Split Flow Tol= 0.02
Split Flow Ratio= 0.02
Log Output Level= 0
Friction Slope Method= 1
Unsteady Friction Slope Method= 2
Unsteady Bridges Friction Slope Method= 1
Parabolic Critical Depth
Global Vel Dist=  1 , 1 , 1
Global Log Level= 0
CheckData=True
Encroach Param= -1, 0, 0, 0
BEGIN DESCRIPTION:
Multiple Run
END DESCRIPTION:

--- Muddy T8_1.f01 (steady flow) ---

Flow Title=Multiple
Number of Profiles=7
Profile Names=10-year,25-year,50-year,1pct_min,100-year,1pct_plu,500-year
River Rch & RM= Muddy T8_1,Reach-1,3216
     566     760     917     550    1096    2188    1566
Boundary for River Rch & Prof#=Muddy T8_1,Reach-1,1
Up Type=0
Dn Type=3
Dn Slope=0.005
Boundary for River Rch & Prof#=Muddy T8_1,Reach-1,2
Up Type=0
Dn Type=3
Dn Slope=0.005
Boundary for River Rch & Prof#=Muddy T8_1,Reach-1,3
Up Type=0
Dn Type=3
Dn Slope=0.005
Boundary for River Rch & Prof#=Muddy T8_1,Reach-1,4
Up Type=0
Dn Type=3
Dn Slope=0.005
Boundary for River Rch & Prof#=Muddy T8_1,Reach-1,5
Up Type=0
Dn Type=3
Dn Slope=0.005
Boundary for River Rch & Prof#=Muddy T8_1,Reach-1,6
Up Type=0
Dn Type=3
Dn Slope=0.005
Boundary for River Rch & Prof#=Muddy T8_1,Reach-1,7
Up Type=0
Dn Type=3
Dn Slope=0.005

--- Muddy T8_1.g01 (geometry) ---

Geom Title=Existing Conditions

River Reach=Muddy T8_1,Reach-1
Reach XY= 30
      2690576.00      6950111.00      2690477.50      6950114.63
      2690305.80      6950211.37      2690160.78      6950111.25
      2690081.98      6950113.16      2690015.50      6950159.78
      2689836.28      6950160.02      2689696.12      6949980.40
      2689631.85      6949962.49      2689581.42      6950008.25
      2689572.48      6950109.74      2689524.75      6950157.49
      2689431.90      6950163.56      2689376.00      6950203.44
      2689306.02      6950161.18      2689019.79      6950168.80
      2688920.35      6950305.36      2688839.56      6950347.48
      2688799.83      6950438.13      2688531.62      6950616.62
      2688515.11      6950670.46      2688425.77      6950754.03
      2688379.61      6950709.99      2688373.68      6950616.95
      2688320.38      6950516.62      2688245.73      6950481.43
      2688217.83      6950404.93      2688136.02      6950322.15
      2688072.67      6950353.48      2688026.00      6950311.00

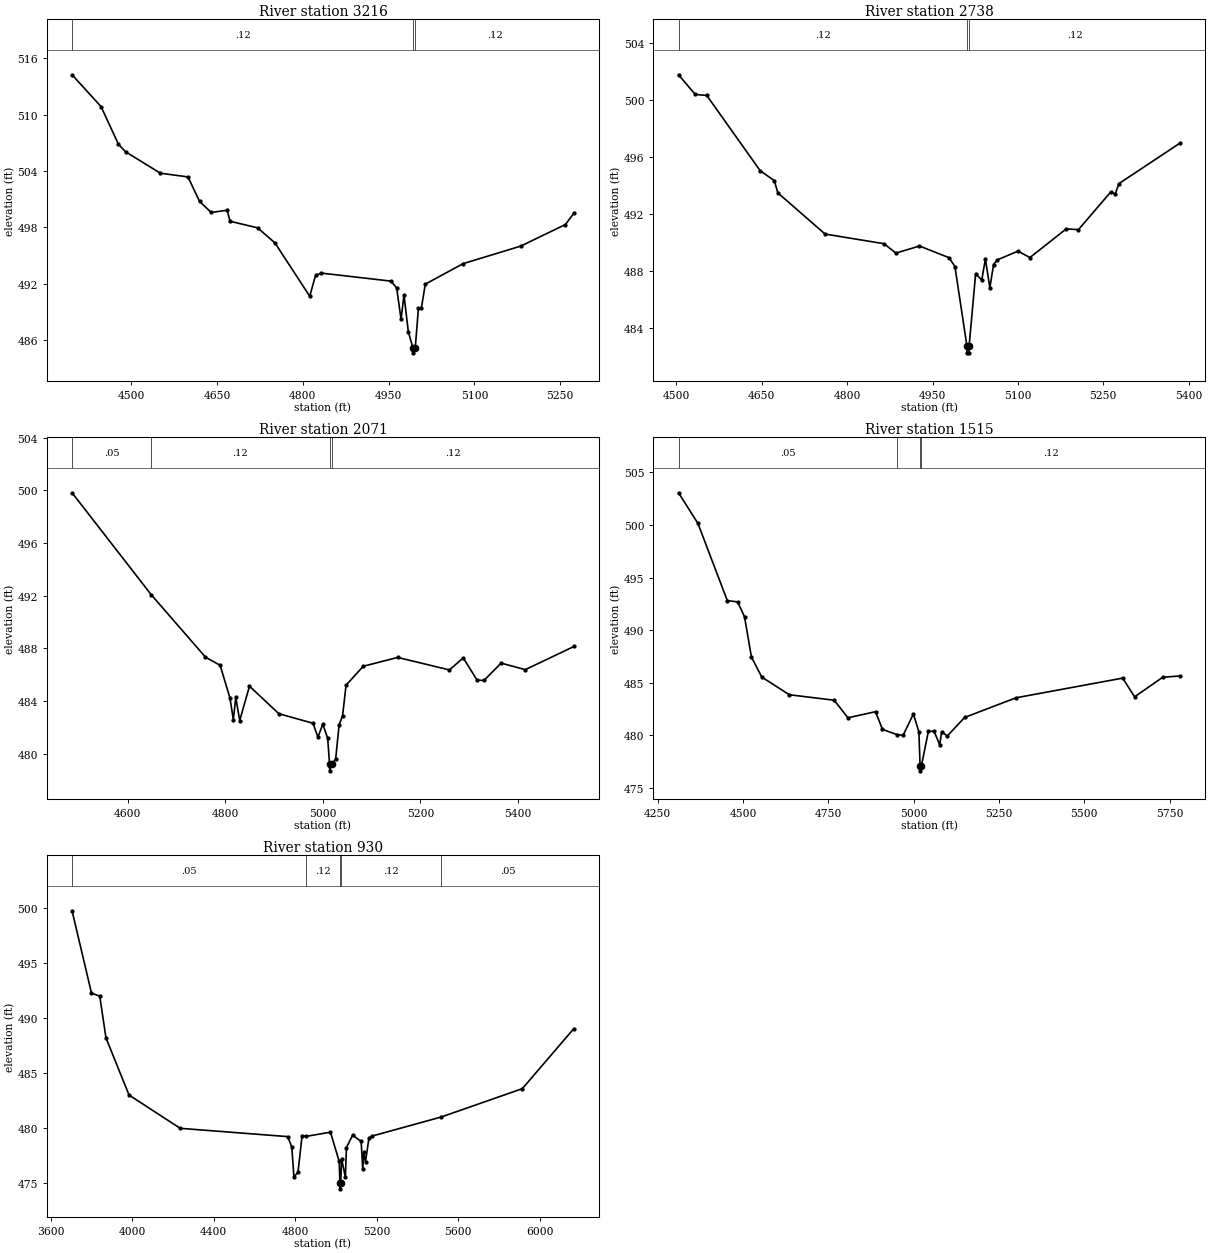
Type RM Length L Ch R = 1,3216,478,478,478
BEGIN DESCRIPTION:
Muddy T8_1 6.0
END DESCRIPTION:
XS GIS Cut Line= 3
      2690426.00      6949611.03      2690326.00      6950211.00
      2690426.00      6950460.99
#Sta/Elev= 30
  4396.4  514.22  4447.1  510.84  4477.5  506.84  4490.2  506.03  4551.0  503.76
  4599.1  503.37  4619.4  500.76  4639.7  499.59  4667.6  499.83  4672.6  498.66
  4720.8  497.96  4751.2  496.36  4812.0  490.69  4822.2  492.91  4832.3  493.15
  4954.0  492.30  4964.1  491.57  4971.7  488.23  4976.8  490.82  4984.4  486.94
  4992.5  485.18  4992.8  484.68  4996.5  485.18  5002.1  489.44  5007.3  489.44
  5014.1  491.98  5080.0  494.15  5181.0  496.02  5259.1  498.31  5273.9  499.51
#Mann=3,-1,0
  4396.4    0.12       0  4992.5    0.07       0  4996.5    0.12       0
Bank Sta=4992.5,4996.5
Exp/Cntr=0.3,0.1

Type RM Length L Ch R = 1,2738,667,667,667
BEGIN DESCRIPTION:
Mapping XS 55ae1e0c
END DESCRIPTION:
XS GIS Cut Line= 3
      2690035.48      6949682.80      2689896.58      6950186.28
      2690174.19      6950414.72
#Sta/Elev= 30
  4503.7  501.78  4533.0  500.40  4553.3  500.33  4647.1  495.05  4672.0  494.35
  4678.2  493.49  4761.2  490.60  4864.9  489.92  4885.7  489.26  4927.1  489.76
  4979.0  488.94  4989.4  488.32  5010.4  482.76  5010.6  482.26  5014.1  482.26
  5014.4  482.76  5025.8  487.82  5036.5  487.37  5043.0  488.84  5050.8  486.82
  5057.3  488.46  5064.1  488.79  5100.3  489.40  5121.2  488.95  5185.0  490.96
  5206.5  490.91  5263.2  493.55  5271.1  493.41  5277.6  494.14  5385.5  497.00
#Mann=3,-1,0
  4503.7    0.12       0  5010.4    0.07       0  5014.4    0.12       0
Bank Sta=5010.4,5014.4
Exp/Cntr=0.3,0.1

Type RM Length L Ch R = 1,2071,556,556,556
BEGIN DESCRIPTION:
Mapping XS c763d989
END DESCRIPTION:
XS GIS Cut Line= 3
      2689436.51      6949648.08      2689475.58      6950177.60
      2689827.57      6950530.37
#Sta/Elev= 30
  4485.6  499.82  4648.0  492.08  4759.3  487.34  4789.3  486.72  4809.4  484.25
  4816.4  482.60  4821.4  484.28  4829.5  482.53  4849.5  485.14  4909.7  483.05
  4979.9  482.32  4989.9  481.27  4999.9  482.25  5009.9  481.19  5013.8  479.21
  5014.0  478.71  5017.8  479.21  5026.3  479.61  5033.4  482.21  5040.5  482.90
  5047.6  485.21  5082.9  486.65  5153.6  487.32  5259.7  486.37  5288.0  487.29
  5316.3  485.60  5330.4  485.57  5365.7  486.89  5415.2  486.39  5514.9  488.15
#Mann=4,-1,0
  4485.6    0.05       0  4648.0    0.12       0  5013.8    0.07       0
  5017.8    0.12       0
Bank Sta=5013.8,5017.8
Exp/Cntr=0.3,0.1

Type RM Length L Ch R = 1,1515,585,585,585
BEGIN DESCRIPTION:
Mapping XS 96ef3122
END DESCRIPTION:
XS GIS Cut Line= 3
      2689058.91      6949539.59      2688963.42      6950216.66
      2689665.65      6950570.05
#Sta/Elev= 30
  4311.5  503.05  4368.3  500.14  4454.3  492.81  4484.6  492.68  4504.8  491.27
  4525.0  487.45  4555.3  485.54  4636.1  483.86  4767.4  483.34  4807.8  481.67
  4888.6  482.25  4908.8  480.57  4950.9  480.08  4969.4  480.01  4999.5  482.03
  5015.5  480.34  5019.1  477.13  5019.3  476.63  5023.1  477.13  5043.4  480.39
  5060.1  480.39  5076.5  479.11  5082.4  480.34  5098.9  479.94  5149.4  481.70
  5300.0  483.57  5612.5  485.44  5647.5  483.66  5729.7  485.52  5781.4  485.65
#Mann=4,-1,0
  4311.5    0.05       0  4950.9    0.12       0  5019.1    0.07       0
  5023.1    0.12       0
Bank Sta=5019.1,5023.1
Exp/Cntr=0.3,0.1

Type RM Length L Ch R = 1,930,0,0,0
BEGIN DESCRIPTION:
Muddy T8_1 1.0
END DESCRIPTION:
XS GIS Cut Line= 3
      2688785.47      6949326.91      2688576.00      6950611.00
      2689662.64      6951020.49
#Sta/Elev= 30
  3704.5  499.71  3799.8  492.24  3840.4  491.96  3870.8  488.18  3984.0  482.99
  4235.5  479.97  4762.4  479.22  4782.7  478.28  4793.0  475.56  4813.1  475.99
  4833.3  479.31  4853.1  479.24  4972.3  479.62  5015.3  476.97  5018.7  474.98
  5018.9  474.48  5022.7  474.98  5026.9  477.22  5045.5  475.52  5050.9  478.23
  5081.1  479.35  5123.1  478.78  5130.8  476.25  5136.2  477.83  5144.5  476.94
  5161.0  479.06  5176.6  479.27  5516.3  481.00  5913.9  483.57  6166.8  489.02
#Mann=5,-1,0
  3704.5    0.05       0  4853.1    0.12       0  5018.7    0.07       0
  5022.7    0.12       0  5516.3    0.05       0
Bank Sta=5018.7,5022.7
Exp/Cntr=0.3,0.1

Chan Stop Cuts=-1