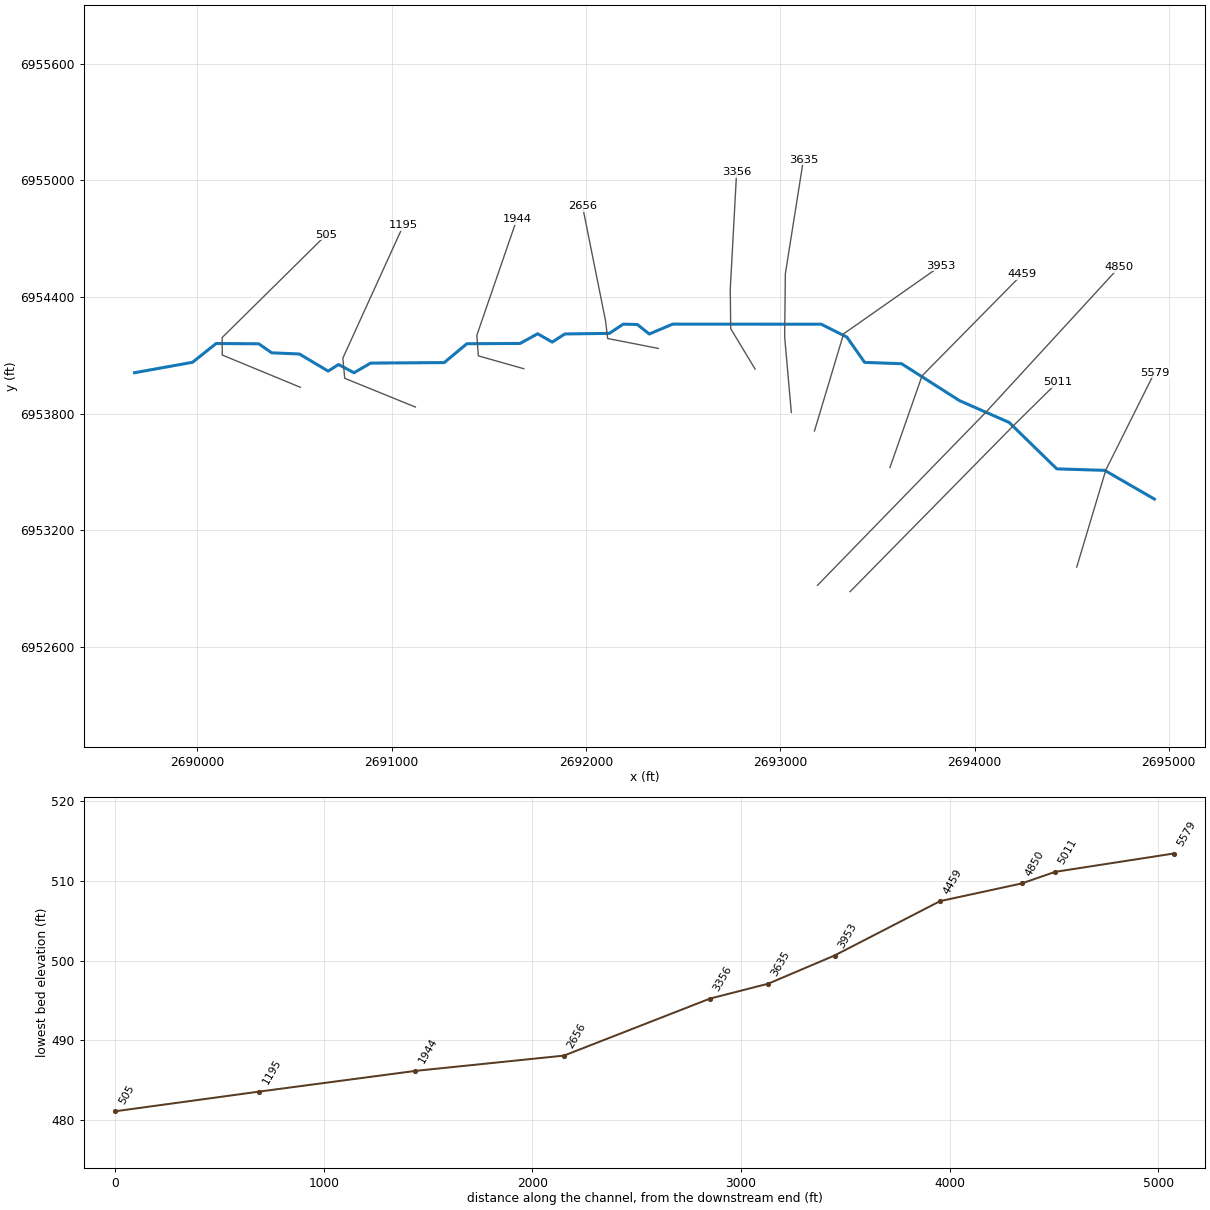
--- Muddy T8_2.prj (project) ---

Proj Title=Muddy T8_2 Base Level Engineering
Current Plan=p01
Default Exp/Contr=0.3,0.1
English Units
Geom File=g01
Flow File=f01
Plan File=p01
Y Axis Title=Elevation
X Axis Title(PF)=Main Channel Distance
X Axis Title(XS)=Station
BEGIN DESCRIPTION:
Muddy T8_2
END DESCRIPTION:
DSS Export Rating Curves= 0
DSS Export Rating Curve Sorted= 0
DSS Export Volume Flow Curves= 0
DXF OffsetX= 0
DXF OffsetY= 0
DXF ScaleX= 1
DXF ScaleY= 10

--- Muddy T8_2.p01 (plan) ---

Plan Title=Multiple Run
Short Identifier=Multiple
Geom File=g01
Flow File=f01
Subcritical Flow
K Sum by GR= 0
Std Step Tol= 0.01
Critical Tol= 0.01
Num of Std Step Trials= 20
Max Error Tol= 0.3
Flow Tol Ratio= 0.001
Split Flow NTrial= 30
Split Flow Tol= 0.02
Split Flow Ratio= 0.02
Log Output Level= 0
Friction Slope Method= 1
Unsteady Friction Slope Method= 2
Unsteady Bridges Friction Slope Method= 1
Parabolic Critical Depth
Global Vel Dist=  1 , 1 , 1
Global Log Level= 0
CheckData=True
Encroach Param= -1, 0, 0, 0
BEGIN DESCRIPTION:
Multiple Run
END DESCRIPTION:

--- Muddy T8_2.f01 (steady flow) ---

Flow Title=Multiple
Number of Profiles=7
Profile Names=10-year,25-year,50-year,1pct_min,100-year,1pct_plu,500-year
River Rch & RM= Muddy T8_2,Reach-1,5579
     503     664     792     469     936    1867    1306
River Rch & RM= Muddy T8_2,Reach-1,3953
     852    1161    1415     855    1706    3404    2477
Boundary for River Rch & Prof#=Muddy T8_2,Reach-1,1
Up Type=0
Dn Type=3
Dn Slope=0.005
Boundary for River Rch & Prof#=Muddy T8_2,Reach-1,2
Up Type=0
Dn Type=3
Dn Slope=0.005
Boundary for River Rch & Prof#=Muddy T8_2,Reach-1,3
Up Type=0
Dn Type=3
Dn Slope=0.005
Boundary for River Rch & Prof#=Muddy T8_2,Reach-1,4
Up Type=0
Dn Type=3
Dn Slope=0.005
Boundary for River Rch & Prof#=Muddy T8_2,Reach-1,5
Up Type=0
Dn Type=3
Dn Slope=0.005
Boundary for River Rch & Prof#=Muddy T8_2,Reach-1,6
Up Type=0
Dn Type=3
Dn Slope=0.005
Boundary for River Rch & Prof#=Muddy T8_2,Reach-1,7
Up Type=0
Dn Type=3
Dn Slope=0.005

--- Muddy T8_2.g01 (geometry) ---

Geom Title=Existing Conditions
Program Version=4.10

River Reach=Muddy T8_2      ,Reach-1
Reach XY= 30
        2694926.        6953361.      2694670.07      6953508.76
      2694423.55      6953516.46       2694178.3      6953755.17
      2693923.71      6953866.85      2693624.45      6954057.25
       2693434.3      6954064.07      2693342.71      6954194.37
      2693210.79      6954260.49      2692446.03      6954260.93
      2692325.66      6954210.08      2692263.99      6954259.14
       2692191.4      6954260.66      2692120.07      6954213.26
      2691891.16      6954210.34      2691825.99      6954168.59
      2691751.04      6954211.31      2691660.79      6954161.54
      2691386.44      6954159.94      2691270.14      6954063.07
      2690891.21      6954060.46      2690805.79      6954010.79
      2690725.92      6954053.17      2690672.77      6954019.24
      2690524.44      6954107.24      2690381.94      6954113.27
       2690315.5      6954159.78      2690095.98      6954161.04
       2689974.5      6954064.62        2689676.        6954011.

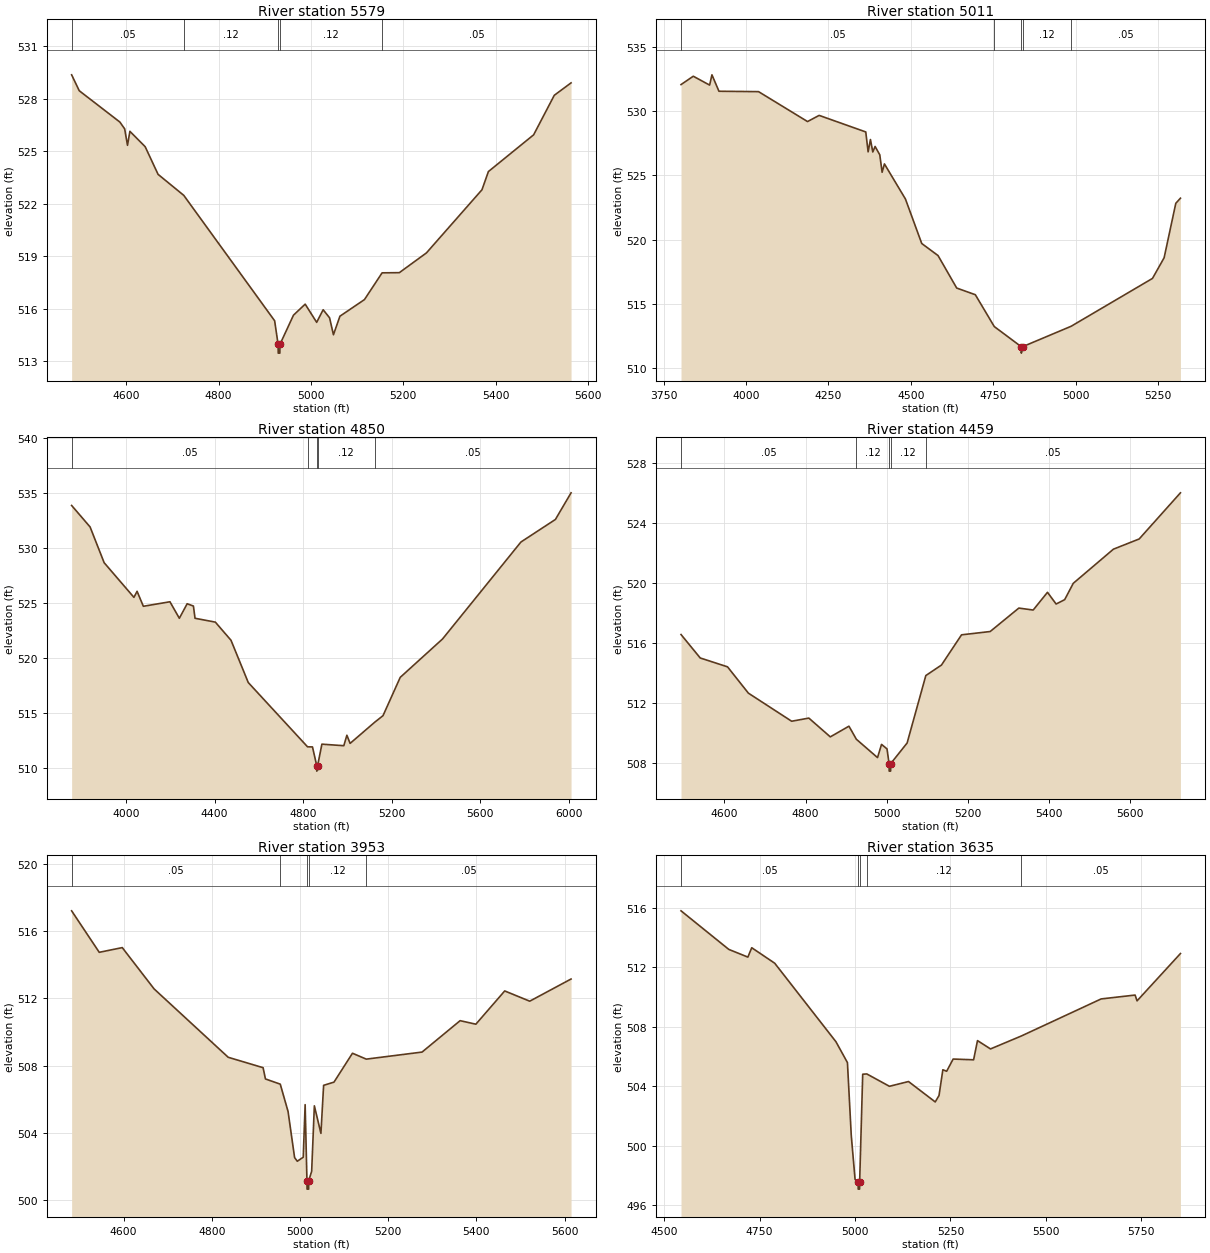
Type RM Length L Ch R = 1 ,5579    ,568,568,568
BEGIN DESCRIPTION:
Muddy T8_2 10.0
END DESCRIPTION:
XS GIS Cut Line= 3
        2694526.        6953011.        2694676.        6953511.
      2694925.99      6954010.98
#Sta/Elev= 30
  4482.1  529.36  4498.6  528.45  4586.5  526.66  4596.9  526.27    4603  525.33
  4608.2  526.13  4641.3  525.25  4669.2  523.67  4724.8  522.47  4921.5   515.3
    4929  513.95  4929.3  513.45  4932.8  513.45    4933  513.95  4962.3  515.62
  4987.6  516.25  5012.5  515.21  5026.5  515.93  5040.4  515.47  5048.8   514.5
  5062.8  515.56  5115.9  516.51  5154.1  518.04  5191.4  518.05  5250.1  519.18
  5370.3  522.79  5384.2  523.83  5482.1  525.93  5526.8  528.19  5563.1   528.9
#Mann= 5 ,-1 , 0
  4482.1     .05       0  4724.8     .12       0    4929     .07       0
    4933     .12       0  5154.1     .05       0
Bank Sta=4929,4933
XS Rating Curve= 0 ,0
Exp/Cntr=0.3,0.1

Type RM Length L Ch R = 1 ,5011    ,161,161,161
BEGIN DESCRIPTION:
Muddy T8_2 9.0
END DESCRIPTION:
XS GIS Cut Line= 3
      2693359.32      6952884.95      2694199.47      6953737.99
      2694426.01      6953961.01
#Sta/Elev= 30
  3802.7  532.07  3839.9  532.72  3889.5  532.03  3896.5  532.83  3917.8  531.55
  4037.9  531.52  4186.5  529.19  4221.8  529.67  4363.2  528.38  4370.4  526.83
  4377.4  527.79  4384.5  526.82  4391.5  527.25  4405.7   526.6  4412.8  525.24
  4419.8  525.89  4483.5  523.16    4533  519.69  4582.5  518.75  4639.1  516.22
  4695.6   515.7  4753.1  513.22    4835  511.65  4835.2  511.15    4839  511.65
  4986.1  513.24  5233.1  516.97  5268.4  518.58  5303.8  522.82  5317.9  523.22
#Mann= 5 ,-1 , 0
  3802.7     .05       0  4753.1     .12       0    4835     .03       0
    4839     .12       0  4986.1     .05       0
Bank Sta=4835,4839
XS Rating Curve= 0 ,0
Exp/Cntr=0.3,0.1

Type RM Length L Ch R = 1 ,4850    ,391,391,391
BEGIN DESCRIPTION:
Muddy T8_2 8.0
END DESCRIPTION:
XS GIS Cut Line= 3
      2693191.72      6952917.57      2694060.61      6953810.06
       2694743.8      6954552.98
#Sta/Elev= 30
  3754.4  533.83  3837.7  531.88  3901.2  528.63  4035.7  525.48  4049.9  526.03
  4078.2  524.67  4198.3  525.08  4240.7  523.58    4276   524.9  4304.3  524.69
  4311.5  523.58  4403.3  523.23    4474  521.58  4551.9  517.74  4819.5   511.9
  4841.8  511.89    4861  510.19  4861.2  509.69    4865  510.19  4884.3  512.14
  4983.3     512  4997.2  512.95  5011.7  512.21  5123.2  514.14  5160.3  514.73
    5238  518.21  5429.1   521.7    5783  530.51  5938.7  532.56  6009.3  534.98
#Mann= 5 ,-1 , 0
  3754.4     .05       0  4819.5     .12       0    4861     .07       0
    4865     .12       0  5123.2     .05       0
Bank Sta=4861,4865
XS Rating Curve= 0 ,0
Exp/Cntr=0.3,0.1

Type RM Length L Ch R = 1 ,4459    ,506,506,506
BEGIN DESCRIPTION:
Mapping XS 4af52dd5
END DESCRIPTION:
XS GIS Cut Line= 3
      2693564.57      6953523.34      2693729.67      6953994.66
      2694244.38      6954516.55
#Sta/Elev= 30
  4492.8  516.56  4540.2     515  4607.6  514.41    4659  512.66  4765.8  510.79
  4808.2     511  4861.2  509.75  4907.2  510.46  4925.5  509.59  4977.7  508.37
  4987.6  509.25  5001.1  508.95  5006.2  507.97  5006.5  507.47    5010  507.47
  5010.2  507.97  5050.7  509.34  5096.9  513.83  5135.5  514.53    5185  516.54
  5255.7  516.76  5326.4  518.32  5361.8  518.19  5397.1  519.37  5418.4  518.59
  5439.5  518.88  5460.8  519.97  5559.8  522.24  5623.4  522.92  5725.2  525.99
#Mann= 5 ,-1 , 0
  4492.8     .05       0  4925.5     .12       0  5006.2     .07       0
  5010.2     .12       0  5096.9     .05       0
Bank Sta=5006.2,5010.2
XS Rating Curve= 0 ,0
Exp/Cntr=0.3,0.1

Type RM Length L Ch R = 1 ,3953    ,318,318,318
BEGIN DESCRIPTION:
Muddy T8_2 7.0
END DESCRIPTION:
XS GIS Cut Line= 3
        2693176.      6953711.01        2693326.        6954211.
      2693825.97      6954560.98
#Sta/Elev= 30
  4482.3  517.21  4544.9  514.74  4597.1  515.02  4669.3  512.56  4837.3  508.49
  4916.4  507.87  4921.7   507.2  4955.3  506.89    4973  505.26  4987.8  502.52
  4993.9   502.3  5007.4  502.54  5011.7  505.67  5015.8  501.14  5016.1  500.64
  5019.6  500.64  5019.8  501.14  5026.5   501.7  5032.6   505.6  5047.5  503.96
  5053.6  506.82  5077.1  507.01    5119  508.73  5150.3  508.38  5276.8   508.8
  5363.1  510.67  5398.8  510.46  5464.2  512.44  5520.9  511.83  5614.6  513.15
#Mann= 5 ,-1 , 0
  4482.3     .05       0  4955.3     .12       0  5015.8     .07       0
  5019.8     .12       0  5150.3     .05       0
Bank Sta=5015.8,5019.8
XS Rating Curve= 0 ,0
Exp/Cntr=0.3,0.1

Type RM Length L Ch R = 1 ,3635    ,279,279,279
BEGIN DESCRIPTION:
Mapping XS 4e95dc7d
END DESCRIPTION:
XS GIS Cut Line= 4
      2693056.86      6953806.43      2693022.52      6954195.26
      2693026.21      6954520.05      2693119.13      6955106.28
#Sta/Elev= 30
  4543.9   515.8    4669  513.21  4719.1  512.69  4729.2  513.32  4789.4  512.28
    4950     507    4980   505.6    4990  500.71    5000  497.75    5008   497.6
  5008.2   497.1  5011.7   497.1    5012   497.6    5020  504.82  5030.7  504.84
    5090  504.01    5140  504.33    5210  502.96    5220  503.39    5230  505.12
    5240  505.02    5257  505.84  5310.6  505.79  5320.8  507.08  5354.9  506.52
  5435.7  507.39  5644.8  509.88  5733.8  510.14  5738.9  509.75  5852.6  512.93
#Mann= 5 ,-1 , 0
  4543.9     .05       0    5008     .03       0    5012     .05       0
  5030.7     .12       0  5435.7     .05       0
Bank Sta=5008,5012
XS Rating Curve= 0 ,0
Exp/Cntr=0.3,0.1

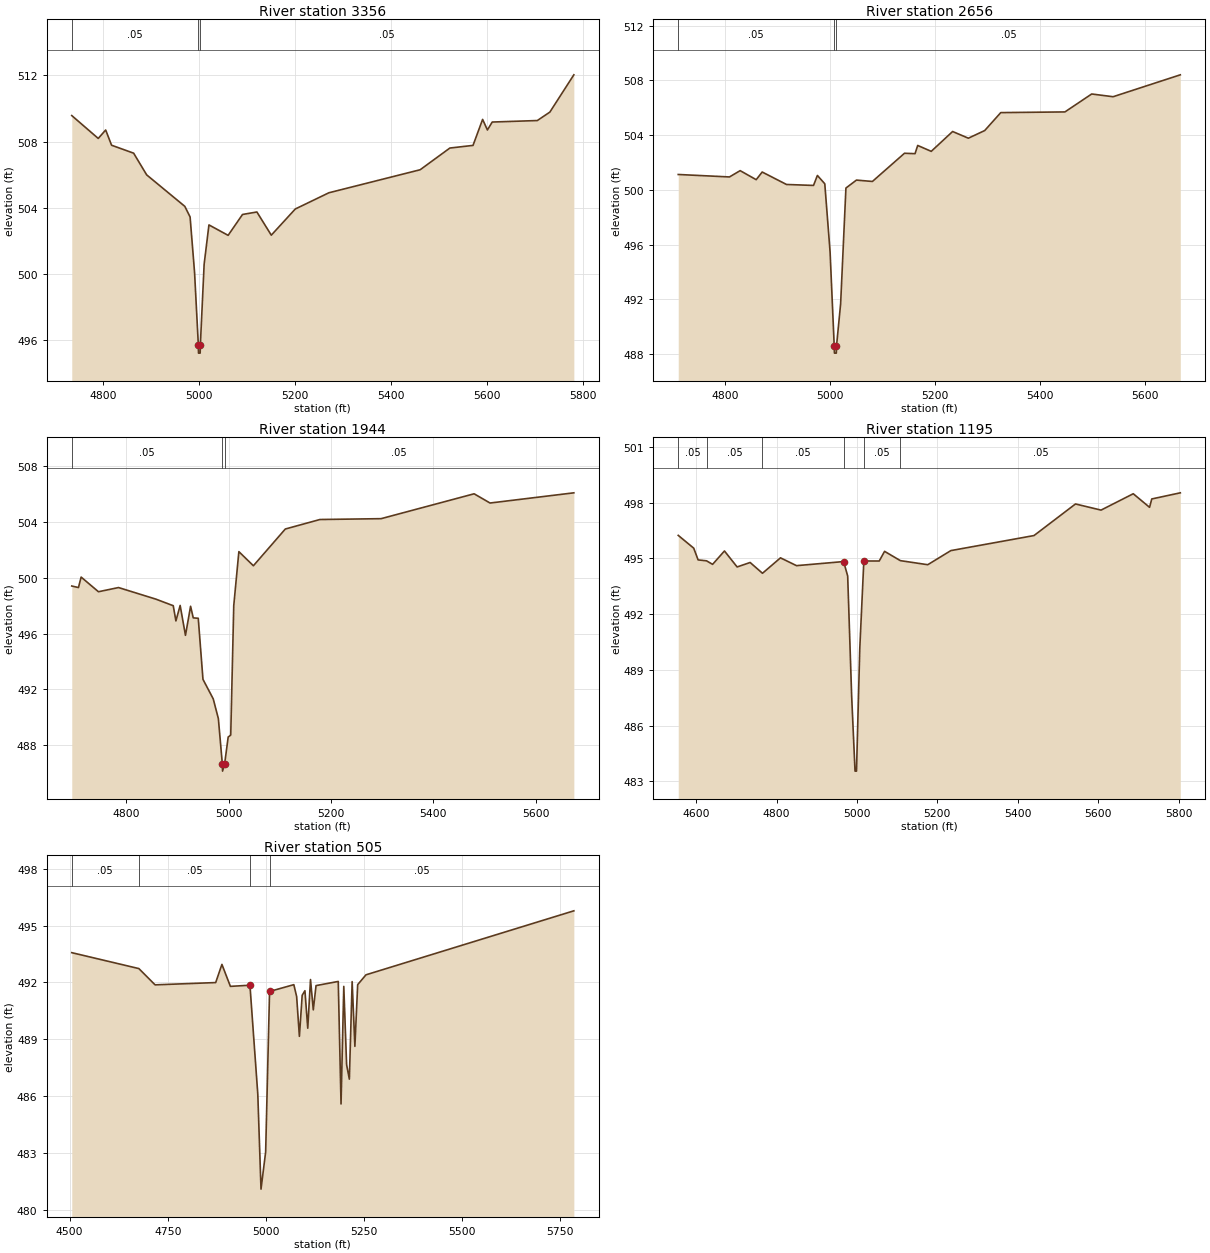
Type RM Length L Ch R = 1 ,3356    ,700,700,700
BEGIN DESCRIPTION:
Mapping XS 667d0f4c
END DESCRIPTION:
XS GIS Cut Line= 4
      2692870.31      6954029.96       2692744.9      6954237.52
      2692742.56      6954440.09       2692775.2      6955040.91
#Sta/Elev= 30
    4734  509.57  4789.2  508.19  4804.7   508.7    4817  507.78    4863   507.3
  4890.2  505.99  4969.7  504.09  4980.7  503.45    4990  500.11  4997.9  495.73
  4998.2  495.23  5001.7  495.23  5002.1  495.73    5010   500.6    5020  502.97
    5060  502.34    5090   503.6    5120  503.75    5150  502.35    5200  503.93
  5270.1  504.91  5460.4   506.3  5522.3  507.61  5570.6  507.77  5590.6  509.34
  5600.6   508.7  5610.6  509.18  5704.6  509.27  5730.8  509.78  5780.8  512.03
#Mann= 3 ,-1 , 0
    4734     .05       0  4997.9     .03       0  5002.1     .05       0
Bank Sta=4997.9,5002.1
XS Rating Curve= 0 ,0
Exp/Cntr=0.3,0.1

Type RM Length L Ch R = 1 ,2656    ,712,712,712
BEGIN DESCRIPTION:
Mapping XS 1d09f699
END DESCRIPTION:
XS GIS Cut Line= 4
      2692371.89        6954136.      2692111.46      6954186.96
      2692100.65      6954277.63      2691982.16      6954866.65
#Sta/Elev= 30
  4710.1  501.12  4807.8  500.94  4828.2   501.4  4858.8  500.74  4870.2   501.3
  4916.6  500.39  4968.1  500.32  4975.5  501.05  4989.6  500.44  4999.7  495.46
  5007.6  488.57    5008  488.07  5011.6  488.07  5011.9  488.57  5019.8  491.67
  5029.9  500.13    5050  500.71  5080.4  500.61  5141.6  502.67  5161.7  502.64
  5166.8  503.24  5192.6  502.81  5233.4  504.26  5263.4  503.77  5294.6  504.33
  5325.2  505.64  5447.6  505.69  5498.6     507  5539.4   506.8  5667.6   508.4
#Mann= 3 ,-1 , 0
  4710.1     .05       0  5007.6     .03       0  5011.9     .05       0
Bank Sta=5007.6,5011.9
XS Rating Curve= 0 ,0
Exp/Cntr=0.3,0.1

Type RM Length L Ch R = 1 ,1944    ,749,749,749
BEGIN DESCRIPTION:
Mapping XS e8e10d38
END DESCRIPTION:
XS GIS Cut Line= 4
      2691679.85      6954031.38      2691445.95      6954097.59
      2691438.09      6954203.48      2691644.29      6954801.24
#Sta/Elev= 30
    4693   499.4  4706.1  499.29  4711.3  500.04  4745.2  498.99  4784.4  499.29
  4857.5  498.46  4891.4  497.99  4896.6   496.9  4904.9  498.01  4915.3  495.87
  4925.3  497.95  4930.5  497.12  4940.3  497.09  4949.5  492.72  4969.6  491.32
  4979.6  489.91  4987.4  486.65  4987.8  486.15  4991.8  486.65  4998.8  488.59
  5003.8  488.73  5009.7     498  5019.7  501.86  5048.1  500.85  5110.5  503.48
  5178.2  504.16  5297.7  504.22  5479.6     506  5510.8  505.34  5674.6  506.07
#Mann= 3 ,-1 , 0
    4693     .05       0  4987.4     .03       0  4991.8     .05       0
Bank Sta=4987.4,4991.8
XS Rating Curve= 0 ,0
Exp/Cntr=0.3,0.1

Type RM Length L Ch R = 1 ,1195    ,690,690,690
BEGIN DESCRIPTION:
Mapping XS e89c3da0
END DESCRIPTION:
XS GIS Cut Line= 4
      2691121.75      6953834.46      2690757.95      6953982.19
      2690748.32      6954085.88      2691060.56      6954770.45
#Sta/Elev= 30
  4555.3  496.24  4593.9  495.55  4604.7  494.92  4625.7  494.87  4640.8  494.68
  4670.3   495.4  4701.8  494.54  4734.2  494.78  4764.9   494.2  4809.7  495.03
  4849.6  494.61  4966.8  494.83  4976.9  494.05  4986.9  487.53  4995.2  483.55
  4998.8  483.55    5007  490.15  5017.1  494.86  5055.4  494.86  5068.7  495.38
    5108  494.88  5176.1  494.66  5233.6  495.42  5440.5  496.23  5543.7  497.93
  5607.3   497.6  5687.4  498.48    5728  497.75  5733.5   498.2  5804.5  498.53
#Mann= 6 ,-1 , 0
  4555.3     .05       0  4625.7     .05       0  4764.9     .05       0
  4966.8     .03       0  5017.1     .05       0    5108     .05       0
Bank Sta=4966.8,5017.1
XS Rating Curve= 0 ,0
Exp/Cntr=0.3,0.1

Type RM Length L Ch R = 1 ,505     ,0,0,0
BEGIN DESCRIPTION:
Muddy T8_2 1.0
END DESCRIPTION:
XS GIS Cut Line= 4
      2690529.62        6953936.      2690127.65      6954101.88
       2690127.1      6954191.92      2690664.19       6954721.7
#Sta/Elev= 30
  4505.6  493.57  4676.5  492.73  4717.9  491.87  4872.3  491.99  4888.2  492.95
  4909.8  491.79  4959.6  491.85  4979.6   486.1  4987.8  481.08  4999.6  483.04
  5009.6  491.52  5071.4  491.88  5078.6  491.25  5085.6  489.15  5092.7  491.32
  5099.7  491.56  5106.9  489.58  5113.9  492.15    5121  490.55    5128  491.83
  5184.6  492.05  5191.7  485.58  5198.7  491.79  5205.9  487.65  5212.9  486.89
    5220  492.04    5227  488.62  5234.1  491.88  5255.3   492.4  5784.9  495.78
#Mann= 4 ,-1 , 0
  4505.6     .05       0  4676.5     .05       0  4959.6     .03       0
  5009.6     .05       0
Bank Sta=4959.6,5009.6
XS Rating Curve= 0 ,0
Exp/Cntr=0.3,0.1

Chan Stop Cuts=-1
Use User Specified Reach Order=0
Composite Channel Slope=5