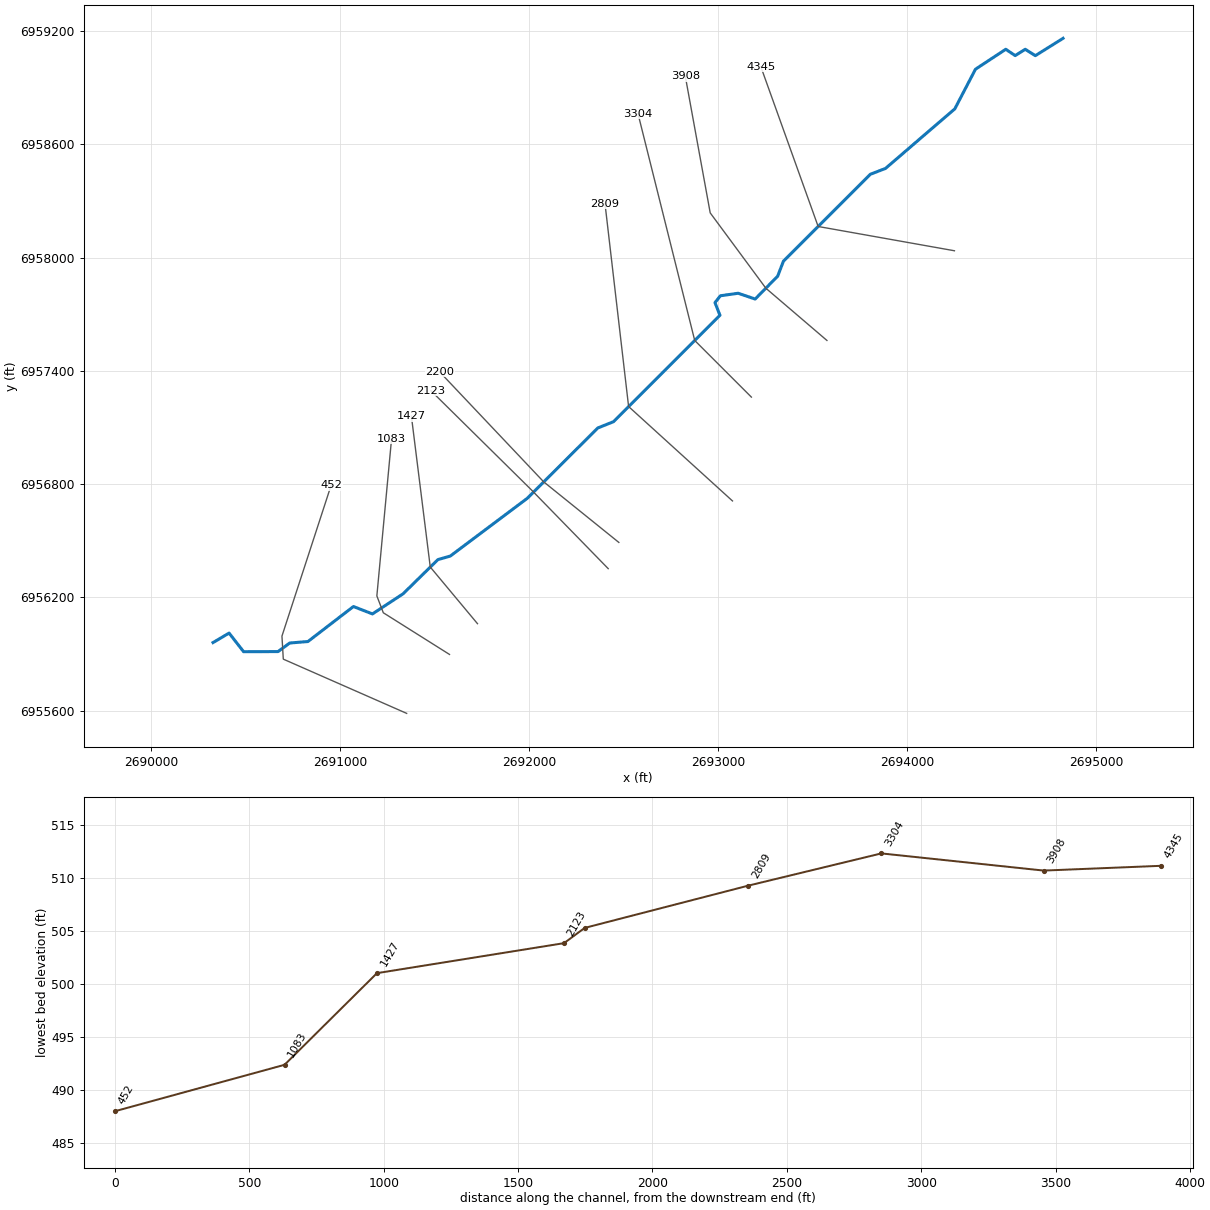
--- Muddy T8_3.prj (project) ---

Proj Title=Muddy T8_3 Base Level Engineering
Current Plan=p01
Default Exp/Contr=0.3,0.1
English Units
Geom File=g01
Flow File=f01
Plan File=p01
BEGIN DESCRIPTION:
Muddy T8_3
END DESCRIPTION:

--- Muddy T8_3.p01 (plan) ---

Plan Title=Multiple Run
Short Identifier=Multiple
Geom File=g01
Flow File=f01
Subcritical Flow
K Sum by GR= 0
Std Step Tol= 0.01
Critical Tol= 0.01
Num of Std Step Trials= 20
Max Error Tol= 0.3
Flow Tol Ratio= 0.001
Split Flow NTrial= 30
Split Flow Tol= 0.02
Split Flow Ratio= 0.02
Log Output Level= 0
Friction Slope Method= 1
Unsteady Friction Slope Method= 2
Unsteady Bridges Friction Slope Method= 1
Parabolic Critical Depth
Global Vel Dist=  1 , 1 , 1
Global Log Level= 0
CheckData=True
Encroach Param= -1, 0, 0, 0
BEGIN DESCRIPTION:
Multiple Run
END DESCRIPTION:

--- Muddy T8_3.f01 (steady flow) ---

Flow Title=Multiple
Number of Profiles=7
Profile Names=10-year,25-year,50-year,1pct_min,100-year,1pct_plu,500-year
River Rch & RM= Muddy T8_3,Reach-1,4345
     766    1039    1263     761    1519    3031    2196
Boundary for River Rch & Prof#=Muddy T8_3,Reach-1,1
Up Type=0
Dn Type=3
Dn Slope=0.005
Boundary for River Rch & Prof#=Muddy T8_3,Reach-1,2
Up Type=0
Dn Type=3
Dn Slope=0.005
Boundary for River Rch & Prof#=Muddy T8_3,Reach-1,3
Up Type=0
Dn Type=3
Dn Slope=0.005
Boundary for River Rch & Prof#=Muddy T8_3,Reach-1,4
Up Type=0
Dn Type=3
Dn Slope=0.005
Boundary for River Rch & Prof#=Muddy T8_3,Reach-1,5
Up Type=0
Dn Type=3
Dn Slope=0.005
Boundary for River Rch & Prof#=Muddy T8_3,Reach-1,6
Up Type=0
Dn Type=3
Dn Slope=0.005
Boundary for River Rch & Prof#=Muddy T8_3,Reach-1,7
Up Type=0
Dn Type=3
Dn Slope=0.005

--- Muddy T8_3.g01 (geometry) ---

Geom Title=Existing Conditions

River Reach=Muddy T8_3,Reach-1
Reach XY= 30
      2694826.00      6959161.00      2694679.23      6959069.21
      2694626.00      6959102.98      2694572.67      6959069.56
      2694522.67      6959103.00      2694362.44      6958997.52
      2694252.99      6958787.53      2693885.68      6958471.78
      2693805.91      6958441.21      2693345.79      6957981.09
      2693315.22      6957901.32      2693196.04      6957780.29
      2693105.93      6957810.99      2693011.91      6957797.66
      2692983.46      6957761.25      2693009.61      6957694.34
      2692446.09      6957130.79      2692362.79      6957097.37
      2691989.21      6956724.63      2691582.05      6956419.16
      2691516.32      6956400.22      2691332.05      6956219.16
      2691169.95      6956112.67      2691069.28      6956151.83
      2690828.42      6955966.54      2690731.98      6955958.64
      2690670.06      6955913.26      2690487.83      6955912.64
      2690410.87      6956011.23      2690326.00      6955961.00

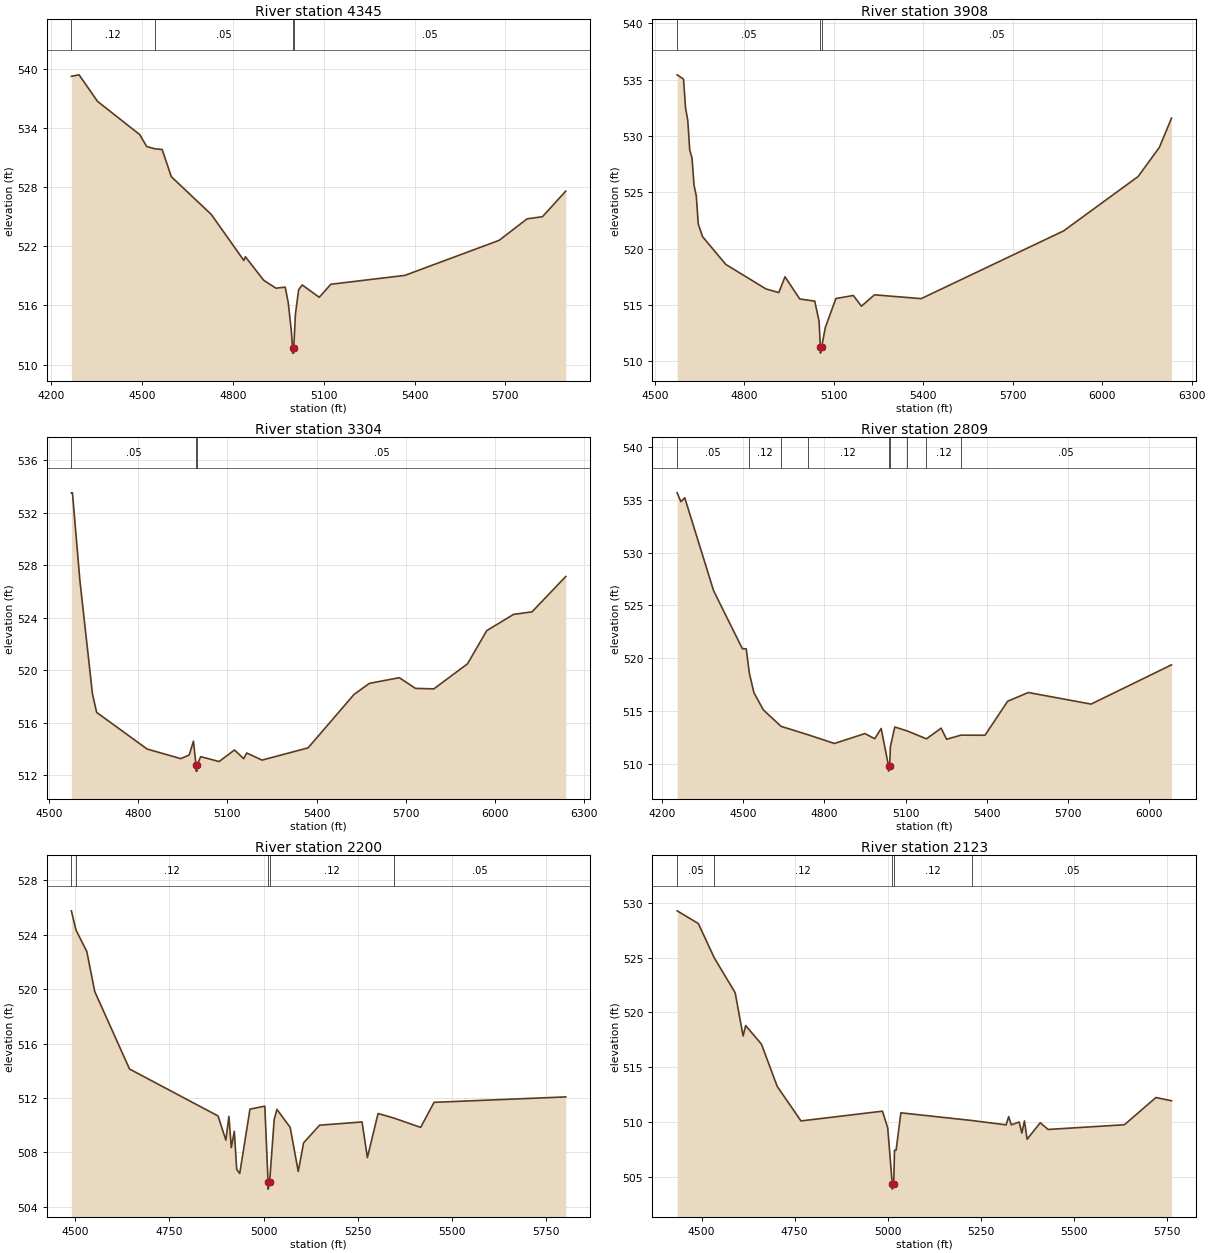
Type RM Length L Ch R = 1,4345,437,437,437
BEGIN DESCRIPTION:
Muddy T8_3 9.0
END DESCRIPTION:
XS GIS Cut Line= 3
      2694250.97      6958036.00      2693529.54      6958164.55
      2693226.01      6959010.97
#Sta/Elev= 30
  4267.2  539.22  4292.6  539.37  4353.5  536.68  4492.9  533.31  4516.0  532.10
  4543.3  531.87  4566.8  531.80  4597.3  529.04  4729.3  525.21  4836.6  520.55
  4841.7  520.93  4902.0  518.55  4942.6  517.74  4973.1  517.85  4983.3  516.25
  4993.4  513.39  4997.3  511.66  4997.5  511.16  5001.0  511.16  5001.3  511.66
  5006.9  515.12  5017.5  517.59  5029.3  518.07  5085.5  516.82  5123.7  518.14
  5368.1  519.04  5679.2  522.59  5771.7  524.77  5822.4  524.99  5899.2  527.58
#Mann=4,-1,0
  4267.2    0.12       0  4543.3    0.05       0  4997.3    0.03       0
  5001.3    0.05       0
Bank Sta=4997.3,5001.3
Exp/Cntr=0.3,0.1

Type RM Length L Ch R = 1,3908,604,604,604
BEGIN DESCRIPTION:
Muddy T8_3 8.0
END DESCRIPTION:
XS GIS Cut Line= 4
      2693575.99      6957561.01      2693252.73      6957837.53
      2692958.05      6958236.58      2692826.00      6958960.98
#Sta/Elev= 30
  4574.6  535.43  4596.0  535.05  4602.6  532.51  4610.3  531.36  4616.8  528.75
  4624.5  528.04  4631.1  525.64  4638.8  524.67  4645.4  522.18  4659.7  521.06
  4737.6  518.59  4872.6  516.41  4915.4  516.09  4936.3  517.49  4985.7  515.52
  5036.0  515.33  5050.6  513.53  5054.8  511.21  5055.1  510.71  5058.8  511.21
  5071.5  512.99  5106.9  515.56  5165.5  515.83  5192.5  514.88  5236.4  515.89
  5393.0  515.55  5870.8  521.57  6120.6  526.40  6191.8  528.99  6232.4  531.58
#Mann=3,-1,0
  4574.6    0.05       0  5054.8    0.04       0  5058.8    0.05       0
Bank Sta=5054.8,5058.8
Exp/Cntr=0.3,0.1

Type RM Length L Ch R = 1,3304,495,495,495
BEGIN DESCRIPTION:
Muddy T8_3 6.0
END DESCRIPTION:
XS GIS Cut Line= 3
      2693176.03      6957260.97      2692876.00      6957561.00
      2692576.01      6958760.96
#Sta/Elev= 30
  4575.7  533.51  4579.3  533.51  4604.0  526.91  4646.5  518.21  4660.6  516.80
  4830.3  514.01  4943.4  513.28  4971.7  513.56  4985.9  514.61  4994.5  512.83
  4994.7  512.33  4998.2  512.33  4998.5  512.83  5010.3  513.43  5072.2  513.06
  5123.7  513.94  5154.6  513.28  5164.9  513.71  5216.5  513.17  5371.1  514.10
  5525.7  518.17  5577.2  519.01  5677.7  519.44  5731.9  518.63  5793.7  518.59
  5907.1  520.50  5971.5  523.02  6061.7  524.26  6123.6  524.45  6236.9  527.14
#Mann=3,-1,0
  4575.7    0.05       0  4994.5    0.03       0  4998.5    0.05       0
Bank Sta=4994.5,4998.5
Exp/Cntr=0.3,0.1

Type RM Length L Ch R = 1,2809,609,609,609
BEGIN DESCRIPTION:
Muddy T8_3 5.0
END DESCRIPTION:
XS GIS Cut Line= 3
      2693076.01      6956710.99      2692526.00      6957211.00
      2692400.99      6958286.05
#Sta/Elev= 30
  4256.7  535.66  4270.6  534.82  4284.8  535.19  4391.5  526.37  4497.6  520.89
  4511.8  520.88  4523.3  518.58  4540.2  516.72  4575.3  515.08  4640.8  513.53
  4738.5  512.75  4837.5  511.91  4950.3  512.85  4986.2  512.36  5010.1  513.33
  5037.3  509.79  5037.5  509.29  5041.3  509.79  5044.3  511.62  5060.4  513.47
  5106.0  513.10  5177.5  512.35  5231.6  513.36  5251.7  512.31  5305.1  512.70
  5393.6  512.69  5477.2  515.91  5553.7  516.74  5785.3  515.64  6082.3  519.36
#Mann=9,-1,0
  4256.7    0.05       0  4523.3    0.12       0  4640.8    0.05       0
  4738.5    0.12       0  5037.3    0.07       0  5041.3    0.12       0
  5106.0    0.05       0  5177.5    0.12       0  5305.1    0.05       0
Bank Sta=5037.3,5041.3
Exp/Cntr=0.3,0.1

Type RM Length L Ch R = 1,2200,77,77,77
BEGIN DESCRIPTION:
Mapping XS a5be63e4
END DESCRIPTION:
XS GIS Cut Line= 3
      2692474.28      6956491.39      2692076.26      6956812.37
      2691525.31      6957394.87
#Sta/Elev= 30
  4489.5  525.76  4501.9  524.34  4530.5  522.77  4551.5  519.83  4644.0  514.13
  4879.1  510.68  4899.9  508.90  4907.9  510.65  4914.3  508.35  4922.3  509.55
  4928.7  506.75  4936.7  506.45  4963.9  511.18  5003.3  511.40  5012.0  505.80
  5012.3  505.30  5016.0  505.80  5028.2  510.41  5035.5  511.16  5070.7  509.84
  5092.1  506.60  5106.3  508.70  5148.7  510.00  5261.6  510.24  5275.8  507.62
  5304.1  510.86  5345.5  510.53  5417.3  509.84  5452.9  511.68  5802.6  512.08
#Mann=5,-1,0
  4489.5    0.05       0  4501.9    0.12       0  5012.0    0.07       0
  5016.0    0.12       0  5345.5    0.05       0
Bank Sta=5012,5016
Exp/Cntr=0.3,0.1

Type RM Length L Ch R = 1,2123,696,696,696
BEGIN DESCRIPTION:
Mapping XS 9f728b79
END DESCRIPTION:
XS GIS Cut Line= 3
      2692418.07      6956352.49      2692009.10      6956771.90
      2691480.14      6957294.24
#Sta/Elev= 30
  4434.1  529.28  4491.0  528.12  4534.3  524.96  4590.1  521.80  4611.4  517.85
  4618.3  518.80  4660.8  517.10  4703.2  513.24  4767.0  510.09  4986.1  510.98
  5000.3  509.45  5012.4  504.36  5012.7  503.86  5016.4  504.36  5018.5  507.41
  5022.8  507.41  5035.6  510.83  5225.9  510.13  5318.5  509.73  5325.5  510.48
  5332.6  509.73  5353.8  509.99  5360.9  508.98  5367.9  510.09  5375.1  508.42
  5410.4  509.92  5431.6  509.31  5636.7  509.74  5721.5  512.23  5763.3  511.93
#Mann=5,-1,0
  4434.1    0.05       0  4534.3    0.12       0  5012.4    0.07       0
  5016.4    0.12       0  5225.9    0.05       0
Bank Sta=5012.4,5016.4
Exp/Cntr=0.3,0.1

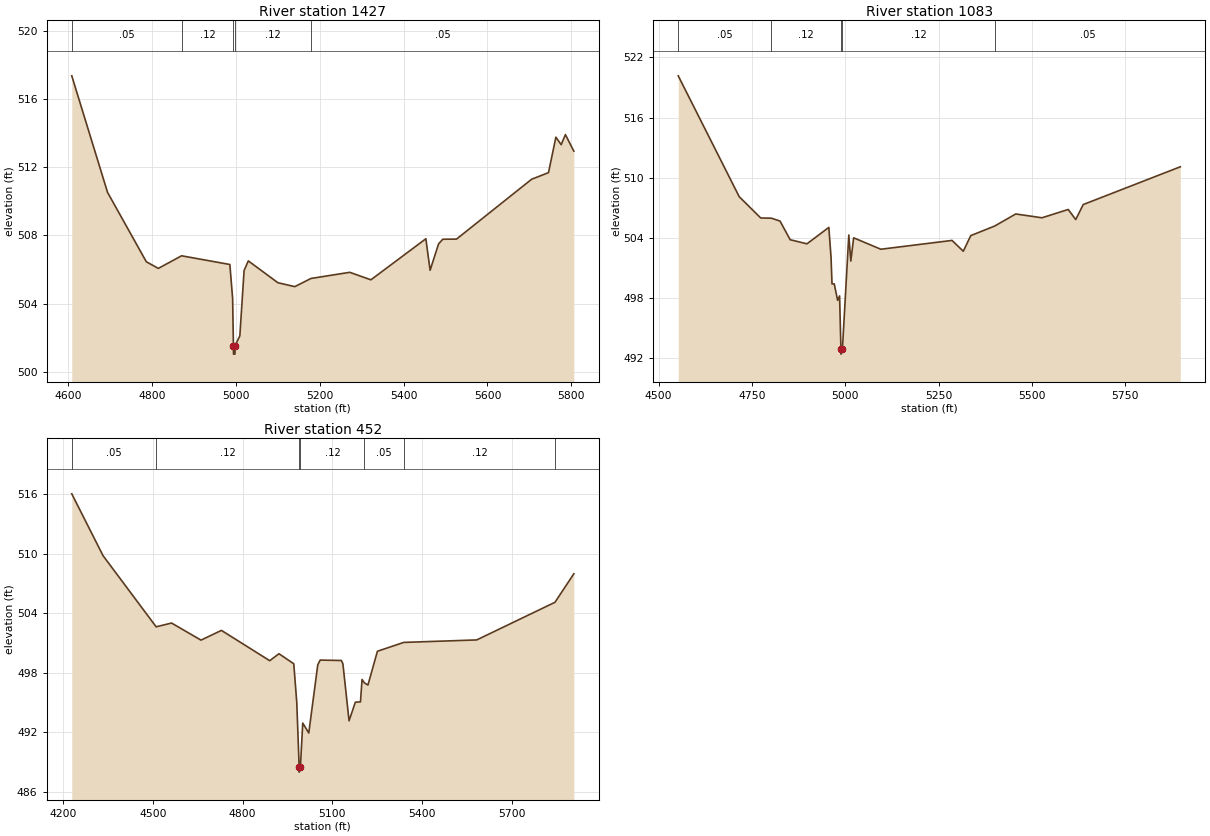
Type RM Length L Ch R = 1,1427,344,344,344
BEGIN DESCRIPTION:
Muddy T8_3 2.0
END DESCRIPTION:
XS GIS Cut Line= 3
      2691726.00      6956061.00      2691476.00      6956361.00
      2691376.01      6957160.96
#Sta/Elev= 30
  4609.2  517.36  4694.5  510.52  4786.9  506.45  4815.5  506.06  4870.9  506.80
  4986.0  506.29  4992.6  504.30  4994.5  501.53  4994.7  501.03  4998.2  501.03
  4998.5  501.53  5009.8  502.10  5019.9  505.93  5030.0  506.50  5100.5  505.22
  5140.8  504.99  5179.4  505.47  5271.8  505.83  5322.2  505.39  5453.2  507.80
  5463.3  505.95  5483.5  507.50  5493.5  507.77  5526.3  507.78  5705.2  511.29
  5745.5  511.68  5763.1  513.76  5775.7  513.32  5785.8  513.91  5805.9  512.94
#Mann=5,-1,0
  4609.2    0.05       0  4870.9    0.12       0  4994.5    0.07       0
  4998.5    0.12       0  5179.4    0.05       0
Bank Sta=4994.5,4998.5
Exp/Cntr=0.3,0.1

Type RM Length L Ch R = 1,1083,631,631,631
BEGIN DESCRIPTION:
Mapping XS adea26f3
END DESCRIPTION:
XS GIS Cut Line= 4
      2691577.84      6955898.10      2691227.45      6956118.85
      2691193.25      6956208.13      2691271.11      6957039.95
#Sta/Elev= 30
  4552.4  520.16  4715.7  508.10  4773.4  505.97  4802.0  505.95  4825.2  505.66
  4852.3  503.80  4897.3  503.39  4955.9  505.03  4961.8  502.05  4964.4  499.39
  4970.4  499.39  4979.4  497.75  4984.7  498.19  4988.3  492.88  4988.5  492.38
  4992.3  492.88  5009.4  504.27  5014.8  501.67  5022.4  503.99  5095.2  502.85
  5286.0  503.73  5316.1  502.65  5336.2  504.21  5400.5  505.17  5456.7  506.37
  5527.0  505.99  5597.3  506.82  5617.4  505.81  5637.5  507.31  5897.6  511.08
#Mann=5,-1,0
  4552.4    0.05       0  4802.0    0.12       0  4988.3    0.07       0
  4992.3    0.12       0  5400.5    0.05       0
Bank Sta=4988.3,4992.3
Exp/Cntr=0.3,0.1

Type RM Length L Ch R = 1,452,0,0,0
BEGIN DESCRIPTION:
Muddy T8_3 1.0
END DESCRIPTION:
XS GIS Cut Line= 4
      2691351.03      6955585.99      2690697.94      6955873.22
      2690690.82      6955995.15      2690951.37      6956794.66
#Sta/Elev= 30
  4229.8  516.02  4334.1  509.80  4511.6  502.63  4563.0  503.01  4661.3  501.29
  4729.5  502.27  4890.8  499.22  4921.7  499.92  4971.1  498.91  4981.1  495.02
  4989.1  488.50  4989.4  488.00  4993.2  488.50  5001.1  492.94  5021.2  491.94
  5051.2  498.80  5059.3  499.28  5130.0  499.24  5135.2  498.90  5155.7  493.17
  5176.7  495.04  5193.8  495.07  5199.1  497.33  5206.8  496.99  5218.8  496.77
  5250.4  500.17  5338.4  501.06  5582.0  501.31  5843.3  505.10  5906.3  507.97
#Mann=7,-1,0
  4229.8    0.05       0  4511.6    0.12       0  4989.1    0.07       0
  4993.2    0.12       0  5206.8    0.05       0  5338.4    0.12       0
  5843.3    0.05       0
Bank Sta=4989.1,4993.2
Exp/Cntr=0.3,0.1

Chan Stop Cuts=-1