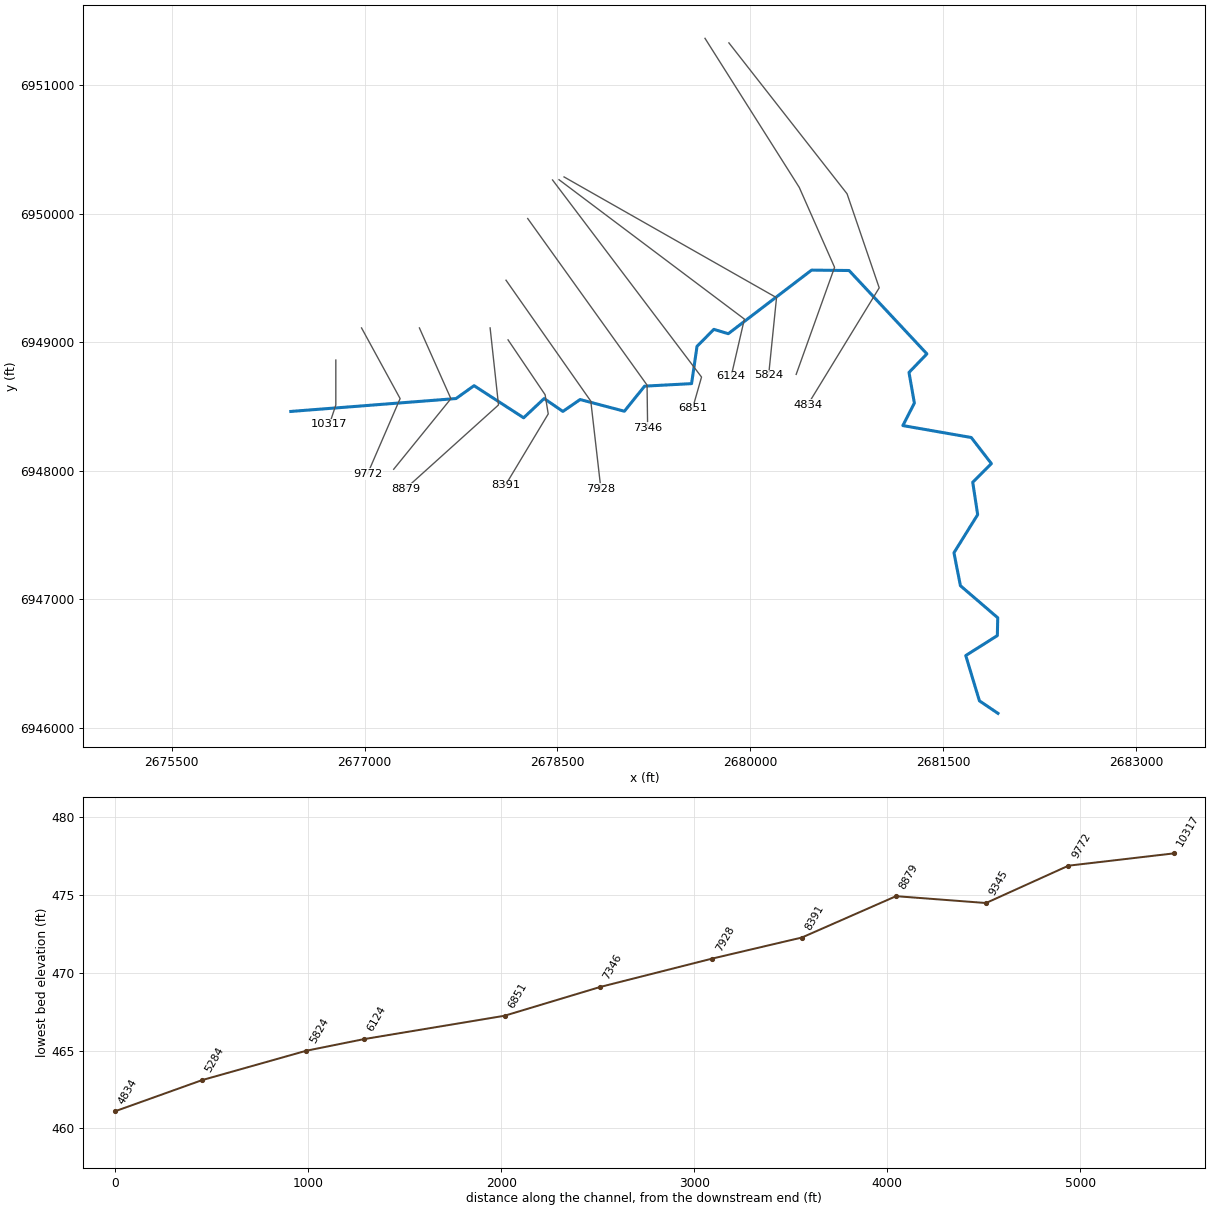
--- Muddy T9.prj (project) ---

Proj Title=Muddy T9 Base Level Engineering
Current Plan=p01
Default Exp/Contr=0.3,0.1
English Units
Geom File=g01
Flow File=f01
Plan File=p01
Y Axis Title=Elevation
X Axis Title(PF)=Main Channel Distance
X Axis Title(XS)=Station
BEGIN DESCRIPTION:
Muddy T9
END DESCRIPTION:
DSS Export Rating Curves= 0
DSS Export Rating Curve Sorted= 0
DSS Export Volume Flow Curves= 0
DXF OffsetX= 0
DXF OffsetY= 0
DXF ScaleX= 1
DXF ScaleY= 10

--- Muddy T9.p01 (plan) ---

Plan Title=Multiple Run
Short Identifier=Multiple
Geom File=g01
Flow File=f01
Subcritical Flow
K Sum by GR= 0
Std Step Tol= 0.01
Critical Tol= 0.01
Num of Std Step Trials= 20
Max Error Tol= 0.3
Flow Tol Ratio= 0.001
Split Flow NTrial= 30
Split Flow Tol= 0.02
Split Flow Ratio= 0.02
Log Output Level= 0
Friction Slope Method= 1
Unsteady Friction Slope Method= 2
Unsteady Bridges Friction Slope Method= 1
Parabolic Critical Depth
Global Vel Dist=  1 , 1 , 1
Global Log Level= 0
CheckData=True
Encroach Param= -1, 0, 0, 0
BEGIN DESCRIPTION:
Multiple Run
END DESCRIPTION:

--- Muddy T9.f01 (steady flow) ---

Flow Title=Multiple
Number of Profiles=7
Profile Names=10-year,25-year,50-year,1pct_min,100-year,1pct_plu,500-year
River Rch & RM= Muddy T9,Reach-1,10317
     611     818     984     588    1172    2339    1662
River Rch & RM= Muddy T9,Reach-1,5284
    1069    1473    1808    1098    2191    4372    3220
Boundary for River Rch & Prof#=Muddy T9,Reach-1,1
Up Type=0
Dn Type=3
Dn Slope=0.005
Boundary for River Rch & Prof#=Muddy T9,Reach-1,2
Up Type=0
Dn Type=3
Dn Slope=0.005
Boundary for River Rch & Prof#=Muddy T9,Reach-1,3
Up Type=0
Dn Type=3
Dn Slope=0.005
Boundary for River Rch & Prof#=Muddy T9,Reach-1,4
Up Type=0
Dn Type=3
Dn Slope=0.005
Boundary for River Rch & Prof#=Muddy T9,Reach-1,5
Up Type=0
Dn Type=3
Dn Slope=0.005
Boundary for River Rch & Prof#=Muddy T9,Reach-1,6
Up Type=0
Dn Type=3
Dn Slope=0.005
Boundary for River Rch & Prof#=Muddy T9,Reach-1,7
Up Type=0
Dn Type=3
Dn Slope=0.005

--- Muddy T9.g01 (geometry) ---

Geom Title=Existing Conditions
Program Version=4.10

River Reach=Muddy T9        ,Reach-1
Reach XY= 30
        2676426.        6948461.      2677710.78      6948561.25
        2677851.      6948661.59      2678236.69      6948411.54
      2678395.96      6948561.26      2678542.04      6948461.19
      2678675.92      6948553.64      2679019.97      6948462.61
      2679177.43      6948657.93      2679542.79      6948677.44
      2679585.13      6948967.74      2679715.94      6949099.89
      2679828.29      6949066.12        2680476.        6949561.
       2680767.7      6949557.88      2681373.06        6948909.
      2681233.79      6948764.43      2681275.61      6948526.16
      2681186.02      6948350.95      2681718.02      6948258.05
      2681874.51      6948055.09      2681729.45      6947909.75
      2681767.92       6947657.7      2681583.32       6947361.1
      2681633.74      6947104.54      2681923.95      6946855.13
      2681920.84      6946716.41      2681675.14      6946561.04
      2681781.45      6946208.53        2681926.        6946111.

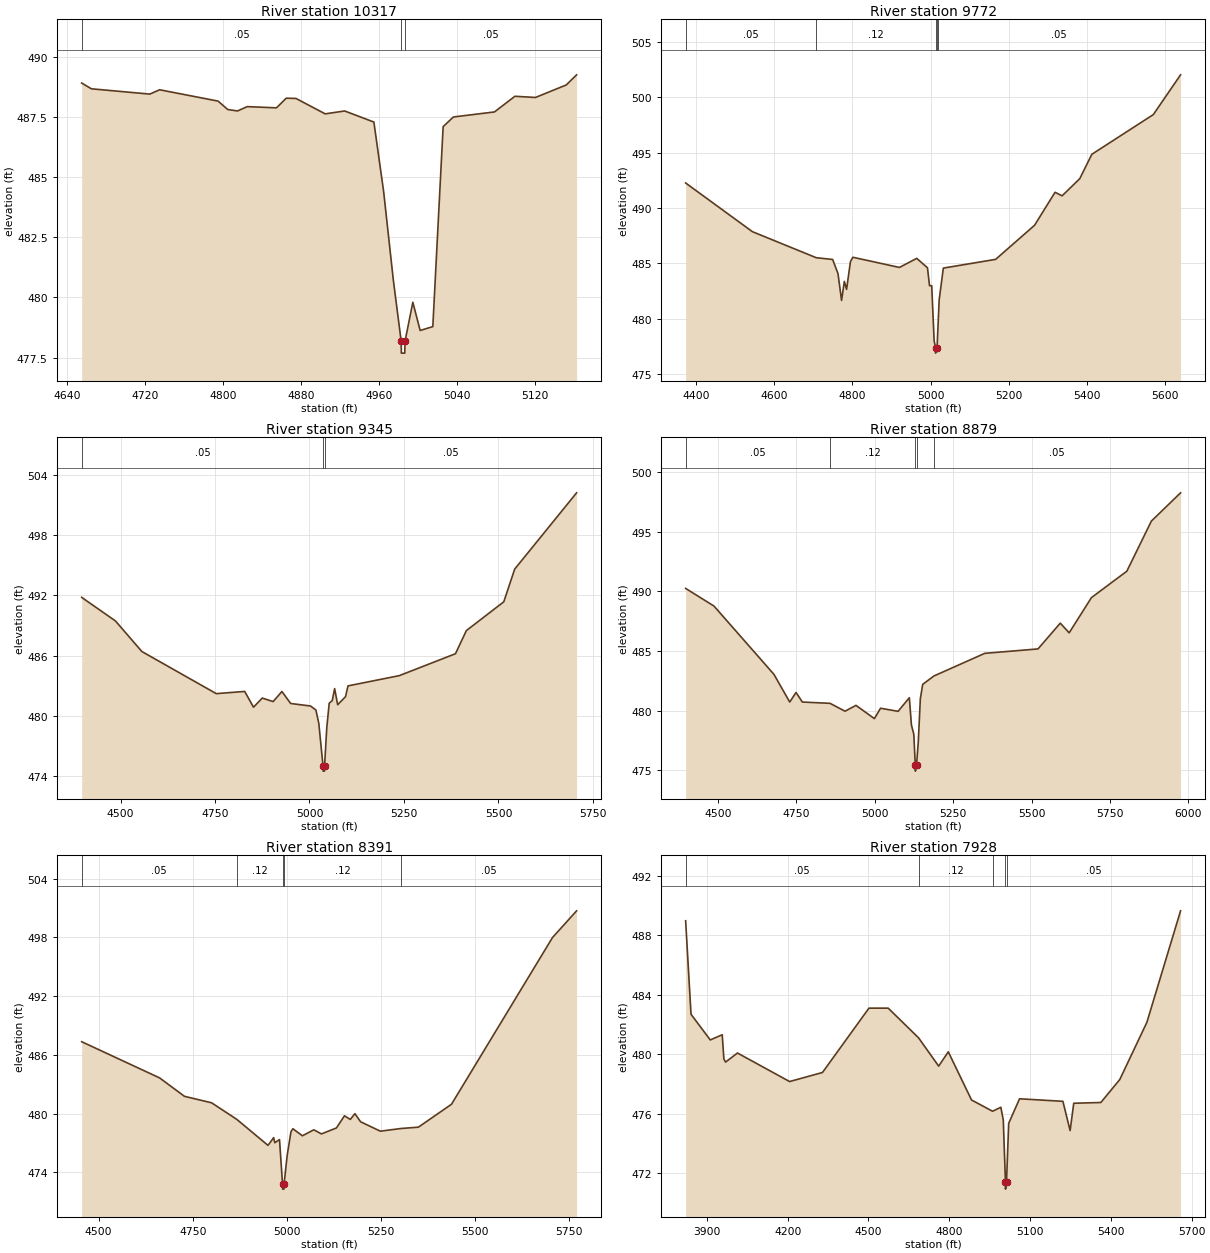
Type RM Length L Ch R = 1 ,10317   ,545,545,545
BEGIN DESCRIPTION:
Muddy T9 7.0
END DESCRIPTION:
XS GIS Cut Line= 3
        2676776.      6948860.97        2676776.        6948511.
        2676726.      6948360.99
#Sta/Elev= 30
  4654.8   488.9  4664.8  488.66  4724.8  488.44  4734.8  488.62  4794.8  488.15
  4804.8   487.8  4814.8  487.74  4824.8  487.92  4854.8  487.87  4864.8  488.27
  4874.8  488.26  4904.8  487.62  4924.8  487.74  4954.8  487.28  4964.8   484.4
  4974.8  480.71  4982.8  478.19    4983  477.69  4986.5  477.69  4986.8  478.19
  4994.8   479.8  5002.3  478.63  5015.3  478.79  5025.9  487.09  5036.4  487.49
  5078.6   487.7  5099.6  488.35  5120.7   488.3  5152.3  488.82  5162.9  489.24
#Mann= 3 ,-1 , 0
  4654.8     .05       0  4982.8     .03       0  4986.8     .05       0
Bank Sta=4982.8,4986.8
XS Rating Curve= 0 ,0
Exp/Cntr=0.3,0.1

Type RM Length L Ch R = 1 ,9772    ,427,427,427
BEGIN DESCRIPTION:
Muddy T9 6.0
END DESCRIPTION:
XS GIS Cut Line= 3
      2676976.01      6949110.98      2677275.97      6948561.08
      2677022.35      6947974.45
#Sta/Elev= 30
  4373.6  492.27  4544.4  487.87  4707.5  485.52  4749.5  485.36  4763.2  484.08
  4772.3  481.66  4779.4  483.38  4785.1  482.66    4795  485.16  4801.2  485.56
  4920.3  484.64  4964.5  485.46    4992  484.61  4997.2  482.99  5002.8  482.99
    5009  478.01  5012.5   477.4  5012.7   476.9  5016.5   477.4  5018.5     479
  5021.9  481.71  5032.5  484.58  5166.3  485.37  5265.8  488.45  5318.2  491.43
  5336.2  491.11  5381.4  492.66  5412.2  494.86  5569.5  498.45  5639.1  502.04
#Mann= 5 ,-1 , 0
  4373.6     .05       0  4707.5     .12       0  5012.5     .07       0
  5016.5     .12       0  5018.5     .05       0
Bank Sta=5012.5,5016.5
XS Rating Curve= 0 ,0
Exp/Cntr=0.3,0.1

Type RM Length L Ch R = 1 ,9345    ,466,466,466
BEGIN DESCRIPTION:
Muddy T9 5.0
END DESCRIPTION:
XS GIS Cut Line= 3
      2677426.02      6949110.96      2677670.98      6948560.17
      2677226.01      6948011.02
#Sta/Elev= 30
  4397.2  491.79  4486.7  489.44  4556.5   486.4  4753.4  482.21  4828.6  482.43
  4851.9  480.86  4875.1  481.77  4903.8  481.42  4927.1  482.42  4950.3  481.23
  5002.7  480.98    5017  480.58  5024.7  479.25  5035.9     475  5036.1   474.5
  5039.6   474.5  5039.9     475  5045.8  478.82  5052.2  481.26  5060.2  481.51
  5066.6  482.71  5074.6  481.11  5095.4  481.91  5101.9  482.98  5237.6     484
  5386.3  486.18  5415.1  488.48  5514.2  491.35    5543   494.6  5706.8  502.19
#Mann= 3 ,-1 , 0
  4397.2     .05       0  5035.9     .03       0  5039.9     .05       0
Bank Sta=5035.9,5039.9
XS Rating Curve= 0 ,0
Exp/Cntr=0.3,0.1

Type RM Length L Ch R = 1 ,8879    ,488,488,488
BEGIN DESCRIPTION:
Muddy T9 4.0
END DESCRIPTION:
XS GIS Cut Line= 3
        2677976.      6949110.99      2678041.22      6948511.53
      2677316.89      6947858.42
#Sta/Elev= 30
    4397  490.25  4487.5  488.77  4678.6  483.05  4728.9  480.73  4749.1  481.53
  4769.2  480.73  4857.6  480.62  4905.2  479.96  4940.2  480.45    4999  479.34
  5018.5  480.21  5074.5  479.95  5110.4  481.09  5117.1  478.79  5124.6  478.04
  5129.3  475.44  5129.6  474.94  5133.3  475.44  5138.8  477.34  5145.5  481.01
    5153  482.21  5188.6  482.91    5351  484.81  5520.7  485.18  5591.7  487.34
  5620.1  486.53  5691.1  489.48  5803.9  491.69  5882.2  495.89  5975.3  498.26
#Mann= 5 ,-1 , 0
    4397     .05       0  4857.6     .12       0  5129.3     .07       0
  5133.3     .12       0  5188.6     .05       0
Bank Sta=5129.3,5133.3
XS Rating Curve= 0 ,0
Exp/Cntr=0.3,0.1

Type RM Length L Ch R = 1 ,8391    ,463,463,463
BEGIN DESCRIPTION:
Mapping XS 030103d5
END DESCRIPTION:
XS GIS Cut Line= 4
      2678115.45      6949018.12      2678403.65      6948591.02
      2678427.96      6948441.72      2678094.63      6947886.16
#Sta/Elev= 30
  4455.1  487.34  4662.2  483.64  4728.1  481.76  4800.1   481.1    4867  479.41
    4950  476.75    4965  477.54    4968  477.02  4980.5  477.34  4988.6  472.78
  4988.9  472.28  4992.4  472.28  4992.6  472.78  5000.8   475.7  5010.9  478.13
    5016  478.45  5041.3  477.73  5071.7  478.34  5091.9  477.92  5131.7  478.53
  5153.1  479.77  5168.6   479.4  5180.8  479.99  5195.9  479.16  5248.3   478.2
  5302.5  478.47  5349.4  478.61  5437.3  480.95  5705.5  497.98  5769.5  500.71
#Mann= 5 ,-1 , 0
  4455.1     .05       0    4867     .12       0  4988.6     .07       0
  4992.6     .12       0  5302.5     .05       0
Bank Sta=4988.6,4992.6
XS Rating Curve= 0 ,0
Exp/Cntr=0.3,0.1

Type RM Length L Ch R = 1 ,7928    ,582,582,582
BEGIN DESCRIPTION:
Mapping XS bb5bd45b
END DESCRIPTION:
XS GIS Cut Line= 3
      2678099.61      6949482.47      2678759.04      6948541.11
      2678837.64      6947856.86
#Sta/Elev= 30
  3820.9  488.99  3840.9   482.7  3912.4  480.97  3956.8  481.32  3962.9  479.69
  3969.2  479.48  4013.5  480.09    4207  478.17  4329.1  478.78  4501.7  483.11
  4573.2  483.11  4686.1  481.11  4760.6  479.21  4796.4  480.17  4882.7  476.93
  4960.9  476.17  4991.5  476.44  5000.6  475.59  5008.6  471.43  5008.9  470.93
  5012.6  471.43  5020.7  475.36    5061  477.01    5222  476.84  5248.8  474.87
  5262.3  476.71  5362.9  476.76  5433.4  478.31    5534  482.16    5659  489.66
#Mann= 5 ,-1 , 0
  3820.9     .05       0  4686.1     .12       0  4960.9     .05       0
  5008.6     .05       0  5012.6     .05       0
Bank Sta=5008.6,5012.6
XS Rating Curve= 0 ,0
Exp/Cntr=0.3,0.1

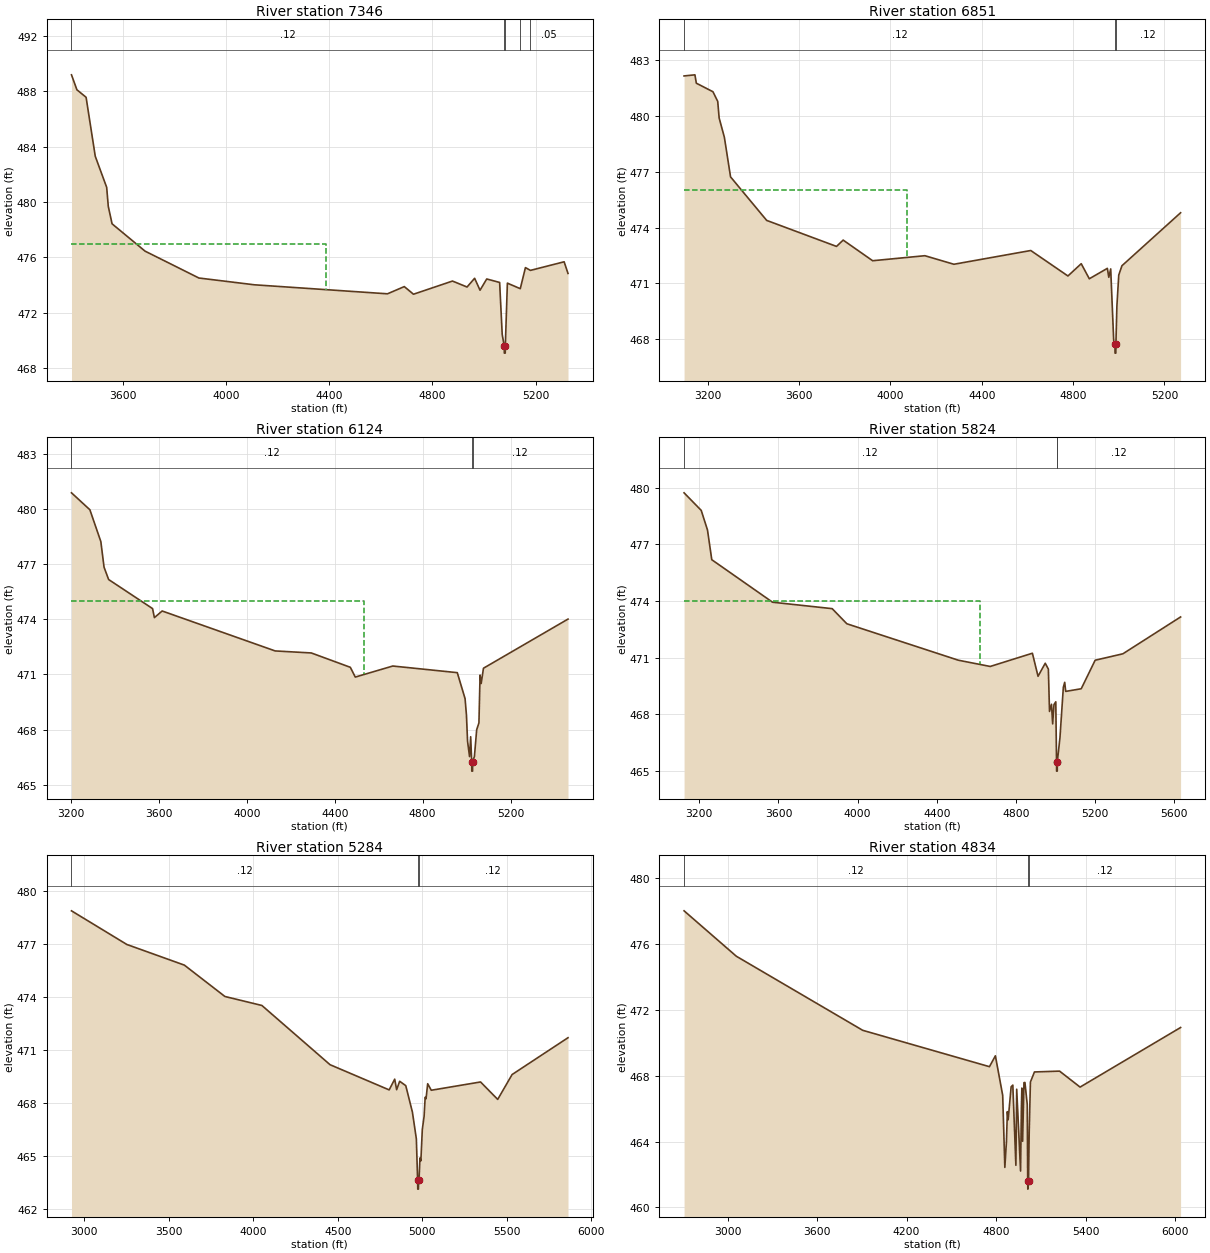
Type RM Length L Ch R = 1 ,7346    ,495,495,495
BEGIN DESCRIPTION:
Mapping XS ea17fc51
END DESCRIPTION:
XS GIS Cut Line= 3
      2678268.37      6949962.46      2679196.54      6948666.11
        2679201.      6948336.01
#Sta/Elev= 30
  3400.9  489.18  3421.9   488.1  3457.5  487.56  3493.1   483.3  3537.3  481.06
  3543.5  479.69  3558.2  478.43    3686  476.46  3894.6  474.52  4109.8  474.03
  4625.7  473.38  4690.8   473.9  4726.5  473.35  4877.6   474.3  4934.1  473.87
  4963.5   474.5  4984.4  473.64  5010.4  474.45  5060.4   474.2  5070.4  470.44
  5078.4   469.6  5078.6   469.1  5082.1   469.1  5082.4   469.6  5090.4  474.15
  5140.4  473.75  5160.4  475.27  5179.8  475.07  5310.4  475.69  5325.4  474.85
#Mann= 5 ,-1 , 0
  3400.9     .12       0  5078.4     .05       0  5082.4     .12       0
  5140.4     .12       0  5179.8     .05       0
#XS Ineff= 2 , 0
       0  4388.6     477               0
Permanent Ineff=
       F       F
Bank Sta=5078.4,5082.4
XS Rating Curve= 0 ,0
Exp/Cntr=0.3,0.1

Type RM Length L Ch R = 1 ,6851    ,727,727,727
BEGIN DESCRIPTION:
Mapping XS 8aba868e
END DESCRIPTION:
XS GIS Cut Line= 3
      2678461.43       6950262.6      2679620.15      6948728.61
        2679551.        6948486.
#Sta/Elev= 30
  3096.2  482.16  3143.7  482.22  3149.9  481.77  3222.7  481.31  3243.6  480.79
  3249.8   479.9  3272.7  478.86  3299.8  476.73  3457.9  474.39  3763.9  472.99
    3793  473.33  3922.1  472.22  4150.9  472.49    4278  472.03  4614.6  472.77
  4777.5   471.4  4835.7  472.06  4871.1  471.25  4950.2  471.81  4956.5  471.33
  4964.8  471.78    4978  467.91  4983.6  467.75  4983.8  467.25  4987.3  467.25
  4987.6  467.75  4991.9  469.78  5000.1  471.45    5014  471.95  5270.9   474.8
#Mann= 3 ,-1 , 0
  3096.2     .12       0  4983.6     .05       0  4987.6     .12       0
#XS Ineff= 2 , 0
       0  4071.9     476               0
Permanent Ineff=
       F       F
Bank Sta=4983.6,4987.6
XS Rating Curve= 0 ,0
Exp/Cntr=0.3,0.1

Type RM Length L Ch R = 1 ,6124    ,300,300,300
BEGIN DESCRIPTION:
Mapping XS 8015212a
END DESCRIPTION:
XS GIS Cut Line= 3
      2678511.87      6950264.59      2679953.48        6949180.
        2679851.      6948736.01
#Sta/Elev= 30
    3202  480.87  3285.7  479.95  3335.6  478.22  3350.2  476.83    3371  476.16
    3571  474.58  3579.3  474.09  3614.7  474.45    4129  472.28  4293.5  472.17
  4471.1  471.39  4493.5  470.86  4664.2  471.46  4957.8   471.1  4993.2  469.69
  4999.5   468.8  5004.5  467.38  5013.6  466.54  5018.7  467.62  5023.5  466.25
  5023.8  465.75  5027.3  465.75  5027.5  466.25  5035.8  466.55  5046.1     468
  5056.3  468.37  5061.5  470.97  5066.6  470.51  5076.9  471.34  5461.7  474.01
#Mann= 3 ,-1 , 0
    3202     .12       0  5023.5     .05       0  5027.5     .12       0
#XS Ineff= 2 , 0
       0  4535.1     475               0
Permanent Ineff=
       F       F
Bank Sta=5023.5,5027.5
XS Rating Curve= 0 ,0
Exp/Cntr=0.3,0.1

Type RM Length L Ch R = 1 ,5824    ,540,540,540
BEGIN DESCRIPTION:
Mapping XS 606f15de
END DESCRIPTION:
XS GIS Cut Line= 3
      2678550.98      6950286.19      2680203.48      6949346.66
      2680141.96      6948741.49
#Sta/Elev= 30
  3122.9  479.73  3209.6   478.8  3241.3  477.76  3262.9  476.19    3570  473.94
  3871.3   473.6  3945.4   472.8  4509.1  470.87  4670.1  470.54  4883.2  471.24
  4911.7  470.02  4948.1  470.71  4963.9   470.4  4969.7  468.16  4979.8  468.54
  4985.6   467.5  4992.2  468.52  5001.4  468.67  5005.2   465.5  5005.4     465
  5008.9     465  5009.2   465.5  5022.4  466.76  5039.6  469.44  5046.5   469.7
  5051.5  469.22    5130  469.36  5200.4  470.87  5340.5  471.21  5632.1  473.16
#Mann= 3 ,-1 , 0
  3122.9     .12       0  5005.2     .05       0  5009.2     .12       0
#XS Ineff= 2 , 0
       0  4619.4     474               0
Permanent Ineff=
       F       F
Bank Sta=5005.2,5009.2
XS Rating Curve= 0 ,0
Exp/Cntr=0.3,0.1

Type RM Length L Ch R = 1 ,5284    ,450,450,450
BEGIN DESCRIPTION:
Mapping XS 4bf90e61
END DESCRIPTION:
XS GIS Cut Line= 4
      2679647.15      6951364.96      2680380.35      6950204.64
      2680654.87      6949582.78      2680356.27      6948749.48
#Sta/Elev= 30
  2924.6   478.9  3252.3  476.99  3592.3  475.82  3832.3  474.04  4051.1  473.53
  4454.2  470.17    4804  468.74  4836.8  469.35  4848.3  468.75  4866.2  469.23
  4902.3  468.98  4941.6  467.48  4964.9  465.96  4972.4  463.61  4973.2  463.11
  4977.1  463.11  4977.9  463.61  4980.5  463.61  4986.3  464.88  4991.6  464.72
  5000.1  466.49  5010.7  467.24    5017  468.32  5022.3  468.24  5031.9  469.09
  5053.2  468.72  5344.7  469.19  5446.2   468.2  5531.2  469.61  5862.1   471.7
#Mann= 3 ,-1 , 0
  2924.6     .12       0  4972.4     .05       0  4977.9     .12       0
Bank Sta=4972.4,4977.9
XS Rating Curve= 0 ,0
Exp/Cntr=0.3,0.1

Type RM Length L Ch R = 1 ,4834    ,0,0,0
BEGIN DESCRIPTION:
Mapping XS a93a77d0
END DESCRIPTION:
XS GIS Cut Line= 4
      2679833.12      6951329.66      2680752.05        6950155.
      2681002.09      6949423.05      2680447.38      6948514.71
#Sta/Elev= 30
  2707.8  478.02  3058.3  475.26  3905.6  470.76  4755.5  468.55  4795.2  469.21
  4844.2  466.81  4858.6  462.43  4869.2  463.96  4875.5  465.82  4880.8  465.32
  4900.9  467.33  4912.1  467.43  4932.6  462.56  4938.1  467.18  4964.1  462.21
  4969.4  465.99  4972.7  467.25  4977.8  464.02  4986.8  467.58  4993.3  467.59
  5008.8  466.26  5011.9  461.61  5012.7  461.11  5017.4  461.61  5021.9  464.55
  5030.1  467.62  5057.2  468.23  5225.6  468.28  5363.1  467.31    6037  470.93
#Mann= 3 ,-1 , 0
  2707.8     .12       0  5011.9     .05       0  5017.4     .12       0
Bank Sta=5011.9,5017.4
XS Rating Curve= 0 ,0
Exp/Cntr=0.3,0.1

Chan Stop Cuts=-1
Use User Specified Reach Order=0
Composite Channel Slope=5