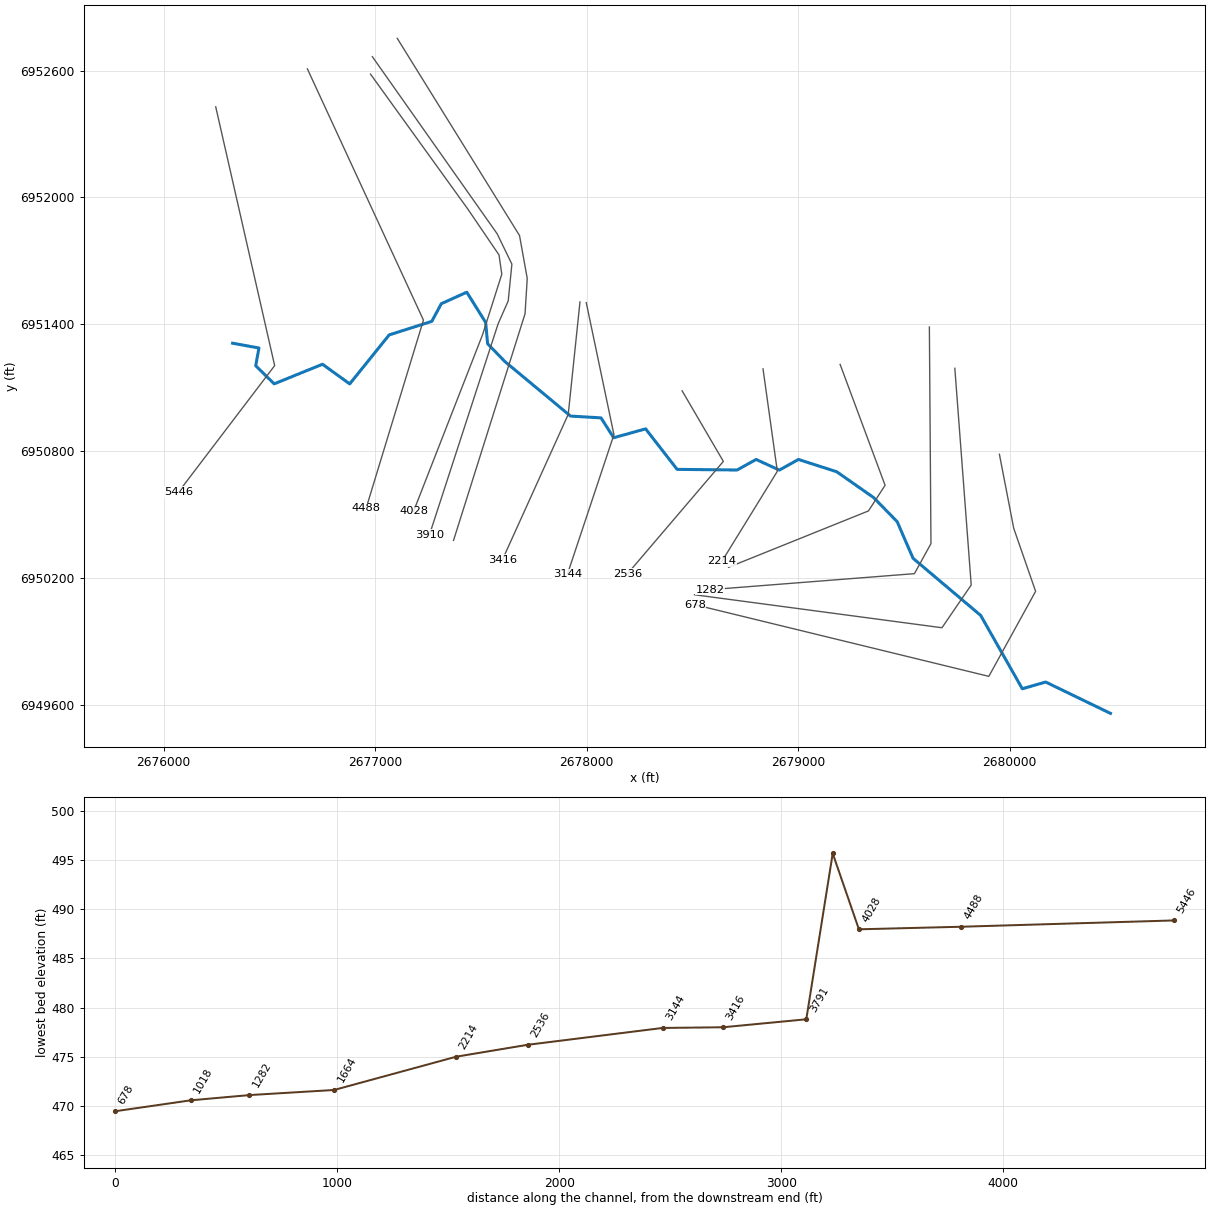
--- Muddy T9_1.prj (project) ---

Proj Title=Muddy T9_1 Base Level Engineering
Current Plan=p01
Default Exp/Contr=0.3,0.1
English Units
Geom File=g01
Flow File=f01
Plan File=p01
Y Axis Title=Elevation
X Axis Title(PF)=Main Channel Distance
X Axis Title(XS)=Station
BEGIN DESCRIPTION:
Muddy T9_1
END DESCRIPTION:
DSS Export Rating Curves= 0
DSS Export Rating Curve Sorted= 0
DSS Export Volume Flow Curves= 0
DXF OffsetX= 0
DXF OffsetY= 0
DXF ScaleX= 1
DXF ScaleY= 10

--- Muddy T9_1.p01 (plan) ---

Plan Title=Multiple Run
Short Identifier=Multiple
Geom File=g01
Flow File=f01
Subcritical Flow
K Sum by GR= 0
Std Step Tol= 0.01
Critical Tol= 0.01
Num of Std Step Trials= 20
Max Error Tol= 0.3
Flow Tol Ratio= 0.001
Split Flow NTrial= 30
Split Flow Tol= 0.02
Split Flow Ratio= 0.02
Log Output Level= 0
Friction Slope Method= 1
Unsteady Friction Slope Method= 2
Unsteady Bridges Friction Slope Method= 1
Parabolic Critical Depth
Global Vel Dist=  1 , 1 , 1
Global Log Level= 0
CheckData=True
Encroach Param= -1, 0, 0, 0
BEGIN DESCRIPTION:
Multiple Run
END DESCRIPTION:

--- Muddy T9_1.f01 (steady flow) ---

Flow Title=Multiple
Number of Profiles=7
Profile Names=10-year,25-year,50-year,1pct_min,100-year,1pct_plu,500-year
River Rch & RM= Muddy T9_1,Reach-1,5446
     532     707     847     504    1005    2006    1416
River Rch & RM= Muddy T9_1,Reach-1,3791
     561     746     895     533    1063    2120    1497
Boundary for River Rch & Prof#=Muddy T9_1,Reach-1,1
Up Type=0
Dn Type=3
Dn Slope=0.005
Boundary for River Rch & Prof#=Muddy T9_1,Reach-1,2
Up Type=0
Dn Type=3
Dn Slope=0.005
Boundary for River Rch & Prof#=Muddy T9_1,Reach-1,3
Up Type=0
Dn Type=3
Dn Slope=0.005
Boundary for River Rch & Prof#=Muddy T9_1,Reach-1,4
Up Type=0
Dn Type=3
Dn Slope=0.005
Boundary for River Rch & Prof#=Muddy T9_1,Reach-1,5
Up Type=0
Dn Type=3
Dn Slope=0.005
Boundary for River Rch & Prof#=Muddy T9_1,Reach-1,6
Up Type=0
Dn Type=3
Dn Slope=0.005
Boundary for River Rch & Prof#=Muddy T9_1,Reach-1,7
Up Type=0
Dn Type=3
Dn Slope=0.005

--- Muddy T9_1.g01 (geometry) ---

Geom Title=Existing Conditions
Program Version=4.10

River Reach=Muddy T9_1      ,Reach-1
Reach XY= 30
        2676326.        6951311.       2676450.5      6951288.12
       2676435.3       6951204.3      2676522.55      6951118.79
      2676751.04      6951211.49      2676879.58      6951118.49
      2677066.32      6951350.24      2677267.65      6951414.19
      2677312.47      6951497.47      2677433.01      6951552.01
      2677522.17      6951409.42      2677531.52      6951308.56
      2677612.76      6951224.62      2677923.56      6950966.47
      2678067.69      6950957.89      2678127.43      6950864.07
      2678278.55      6950906.01      2678427.45      6950714.53
      2678710.79      6950711.54        2678801.      6950761.39
      2678910.61      6950711.11        2679001.      6950761.39
      2679182.16      6950703.12      2679356.16      6950581.39
      2679467.86      6950467.06      2679542.63      6950294.29
      2679862.38      6950024.21      2680059.26      6949677.29
      2680169.87      6949709.16        2680476.        6949561.

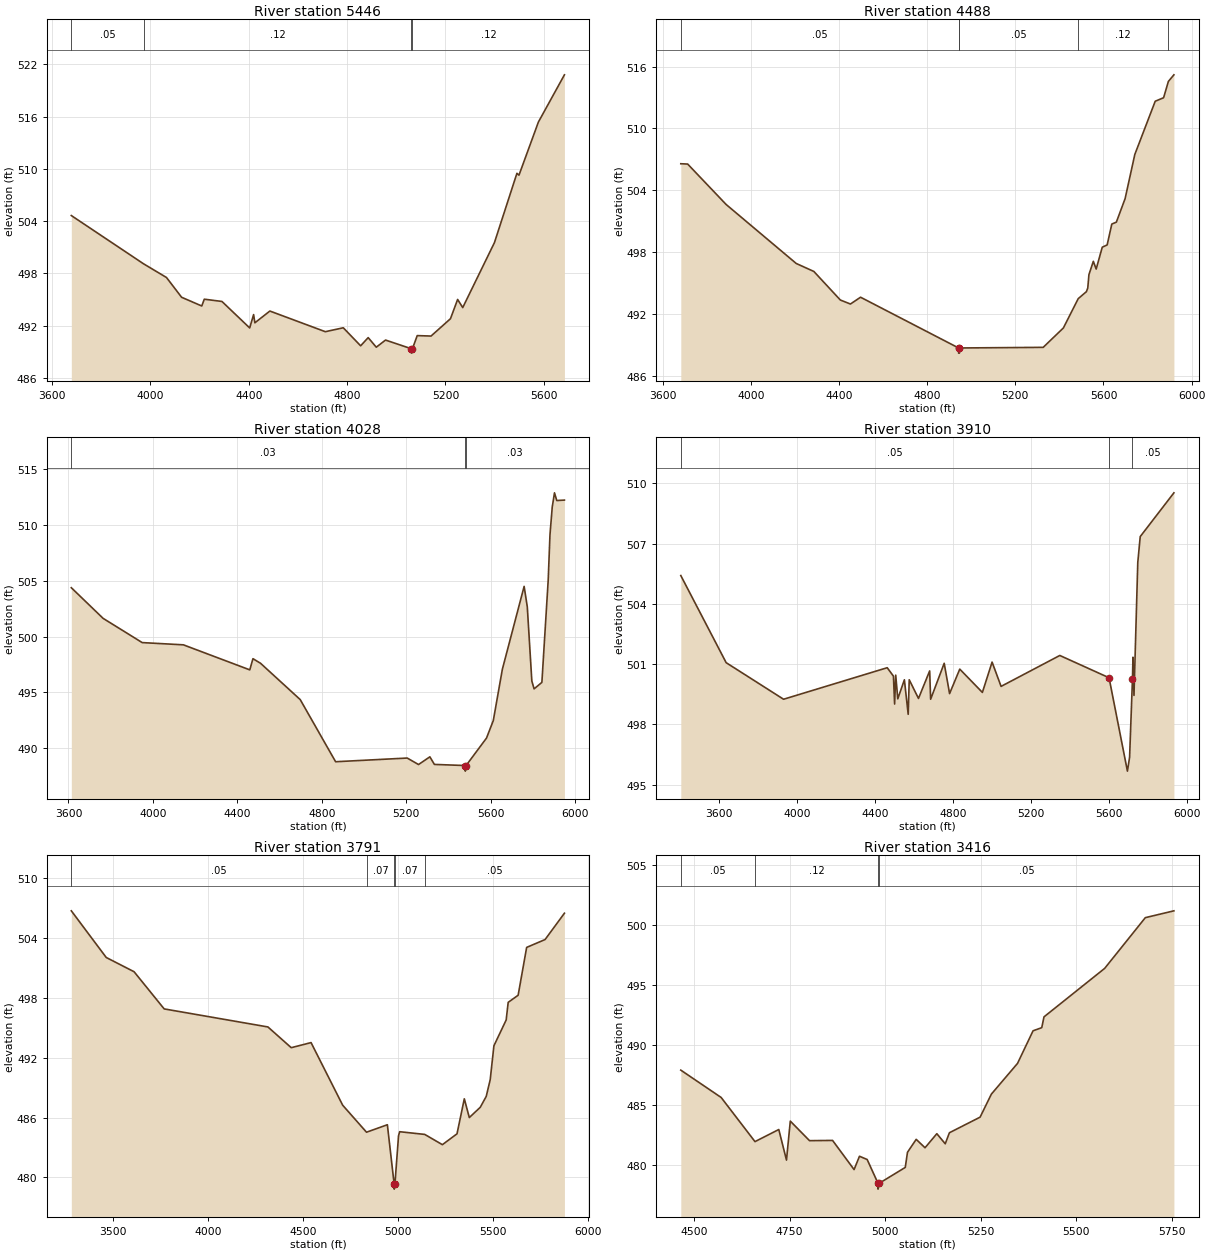
Type RM Length L Ch R = 1 ,5446    ,958,958,958
BEGIN DESCRIPTION:
Muddy T9_1 10.0
END DESCRIPTION:
XS GIS Cut Line= 3
      2676246.25       6952428.4      2676524.85        6951205.
      2676070.26      6950607.24
#Sta/Elev= 30
  3678.3  504.65  3972.2  499.11  4065.4  497.54  4126.9  495.27  4208.9  494.27
  4219.2  495.05    4291  494.79  4403.8  491.75  4419.7  493.28  4424.9  492.34
  4485.9  493.69  4711.5  491.32  4784.5  491.77  4855.1   489.7  4885.8  490.64
  4918.7  489.54  4956.4  490.36  5061.7  489.36  5061.9  488.86  5065.7  489.36
  5085.3  490.87  5141.5  490.82  5220.5  492.81  5249.6  495.02  5270.4  494.09
  5399.3  501.54  5490.8   509.5  5499.1  509.28  5578.1  515.38    5684   520.8
#Mann= 4 ,-1 , 0
  3678.3     .05       0  3972.2     .12       0  5061.7     .05       0
  5065.7     .12       0
Bank Sta=5061.7,5065.7
XS Rating Curve= 0 ,0
Exp/Cntr=0.3,0.1

Type RM Length L Ch R = 1 ,4488    ,460,460,460
BEGIN DESCRIPTION:
Mapping XS 98a902c3
END DESCRIPTION:
XS GIS Cut Line= 3
      2676679.58      6952607.73       2677228.2      6951420.19
      2676957.36      6950531.28
#Sta/Elev= 30
  3682.1  506.58  3713.2  506.55  3887.8  502.63  4205.9  496.91  4285.7  496.14
  4405.9  493.37  4451.8  492.98  4497.7  493.64  4942.5  488.72  4942.7  488.22
  4946.2  488.22  4946.5  488.72  5326.4  488.78    5418  490.66  5485.3   493.5
  5522.5  494.18  5528.7  494.54  5533.9  495.83  5553.9  497.12  5566.8  496.37
  5594.4  498.49  5616.6  498.71  5637.7  500.73  5658.4  500.92  5698.1   503.2
  5742.1  507.48  5834.7  512.64  5872.7  512.98  5894.4  514.56  5919.5   515.2
#Mann= 5 ,-1 , 0
  3682.1     .05       0  4942.5     .03       0  4946.5     .05       0
  5485.3     .12       0  5894.4     .05       0
Bank Sta=4942.5,4946.5
XS Rating Curve= 0 ,0
Exp/Cntr=0.3,0.1

Type RM Length L Ch R = 1 ,4028    ,118,118,118
BEGIN DESCRIPTION:
Mapping XS a5e6fa9d
END DESCRIPTION:
XS GIS Cut Line= 6
      2676977.93      6952583.07      2677437.98      6951945.08
      2677585.55      6951728.06      2677598.57      6951636.92
      2677507.43      6951350.46      2677181.92      6950517.16
#Sta/Elev= 30
  3613.4  504.37  3763.9  501.63  3949.2  499.46  4144.3  499.26    4459  497.02
  4473.9  498.02  4509.9  497.61  4697.9  494.36  4865.6   488.8  5204.8  489.13
  5258.5  488.55  5312.2  489.24  5333.6  488.56  5479.8  488.46    5480  487.96
  5483.8  488.46  5580.6  490.92  5612.8  492.49  5655.7  497.08  5758.8  504.49
  5773.8  502.65  5795.3  496.02    5806  495.32  5842.9   495.9  5872.8  505.04
  5881.2   509.1  5891.9  511.58  5902.6  512.86  5913.4  512.17  5949.7  512.21
#Mann= 3 ,-1 , 0
  3613.4     .03       0  5479.8     .03       0  5483.8     .03       0
Bank Sta=5479.8,5483.8
XS Rating Curve= 0 ,0
Exp/Cntr=0.3,0.1

Type RM Length L Ch R = 1 ,3910    ,119,119,119
BEGIN DESCRIPTION:
Mapping XS 5e2965b5
END DESCRIPTION:
XS GIS Cut Line= 6
      2676986.59      6952665.57      2677576.87      6951827.89
      2677646.32      6951684.66      2677628.96      6951511.05
      2677581.21      6951402.54      2677256.54      6950405.02
#Sta/Elev= 30
  3405.4  505.41  3637.9  501.07    3932  499.25  4463.1  500.82    4495   500.4
    4501  499.01  4506.7  500.45  4517.2  499.27  4551.1  500.22  4570.6   498.5
  4575.9  500.22  4623.4  499.29  4680.6  500.66  4685.6  499.25  4755.1  501.04
  4782.7  499.53  4834.9  500.75  4950.8  499.59  5000.5   501.1  5046.6  499.89
  5347.5  501.43  5599.9  500.32    5694  495.67  5705.1  496.36  5719.9 500.274
  5722.4  501.34  5727.6  499.44  5747.1  506.07  5759.6  507.35  5932.2  509.53
#Mann= 3 ,-1 , 0
  3405.4     .05       0  5599.9     .03       0  5719.9     .05       0
Bank Sta=5599.9,5719.9
XS Rating Curve= 0 ,0
Exp/Cntr=0.3,0.1

Type RM Length L Ch R = 1 ,3791    ,375,375,375
BEGIN DESCRIPTION:
Mapping XS 92320715
END DESCRIPTION:
XS GIS Cut Line= 5
      2677104.33      6952752.18      2677682.45       6951819.9
      2677718.91      6951616.77      2677708.49       6951450.1
      2677370.46      6950378.82
#Sta/Elev= 30
  3281.2  506.74  3464.8  502.06  3611.3  500.63  3769.6   496.9  4315.3  495.09
    4438  493.01  4542.2  493.52  4708.5  487.24  4833.9  484.53  4943.6  485.28
  4979.3  479.32  4979.6  478.82  4983.3  479.32  5002.3  484.17  5008.3  484.58
    5140  484.31    5233  483.28  5309.9  484.37  5348.3  487.88  5374.6     486
  5432.2  487.03  5463.7  488.13  5484.6  489.81    5504   493.2  5568.5  495.79
  5579.1  497.56  5631.4  498.27  5676.2  503.07  5773.2  503.86  5874.9   506.5
#Mann= 5 ,-1 , 0
  3281.2     .05       0  4833.9     .07       0  4979.3     .03       0
  4983.3     .07       0    5140     .05       0
Bank Sta=4979.3,4983.3
XS Rating Curve= 0 ,0
Exp/Cntr=0.3,0.1

Type RM Length L Ch R = 1 ,3416    ,272,272,272
BEGIN DESCRIPTION:
Mapping XS 2451747f
END DESCRIPTION:
XS GIS Cut Line= 3
       2677968.2      6951505.98      2677912.69      6950974.37
      2677600.98      6950285.96
#Sta/Elev= 30
  4465.5  487.93  4571.1  485.65  4659.6  481.97  4721.9  482.98    4742  480.43
    4752  483.68  4802.3  482.05  4862.6  482.07  4918.9  479.64    4933  480.75
  4953.1  480.48  4981.3  478.51  4981.5  478.01  4985.3  478.51  5052.8  479.82
  5058.6  481.08  5081.4  482.16  5104.5  481.46  5135.4  482.63  5157.4  481.79
  5168.3  482.71  5248.6  484.01  5278.1  485.93  5346.5  488.49  5387.2  491.21
  5409.9  491.47  5415.8  492.37  5574.5  496.41  5680.9  500.64  5755.7  501.21
#Mann= 4 ,-1 , 0
  4465.5     .05       0  4659.6     .12       0  4981.3     .03       0
  4985.3     .05       0
Bank Sta=4981.3,4985.3
XS Rating Curve= 0 ,0
Exp/Cntr=0.3,0.1

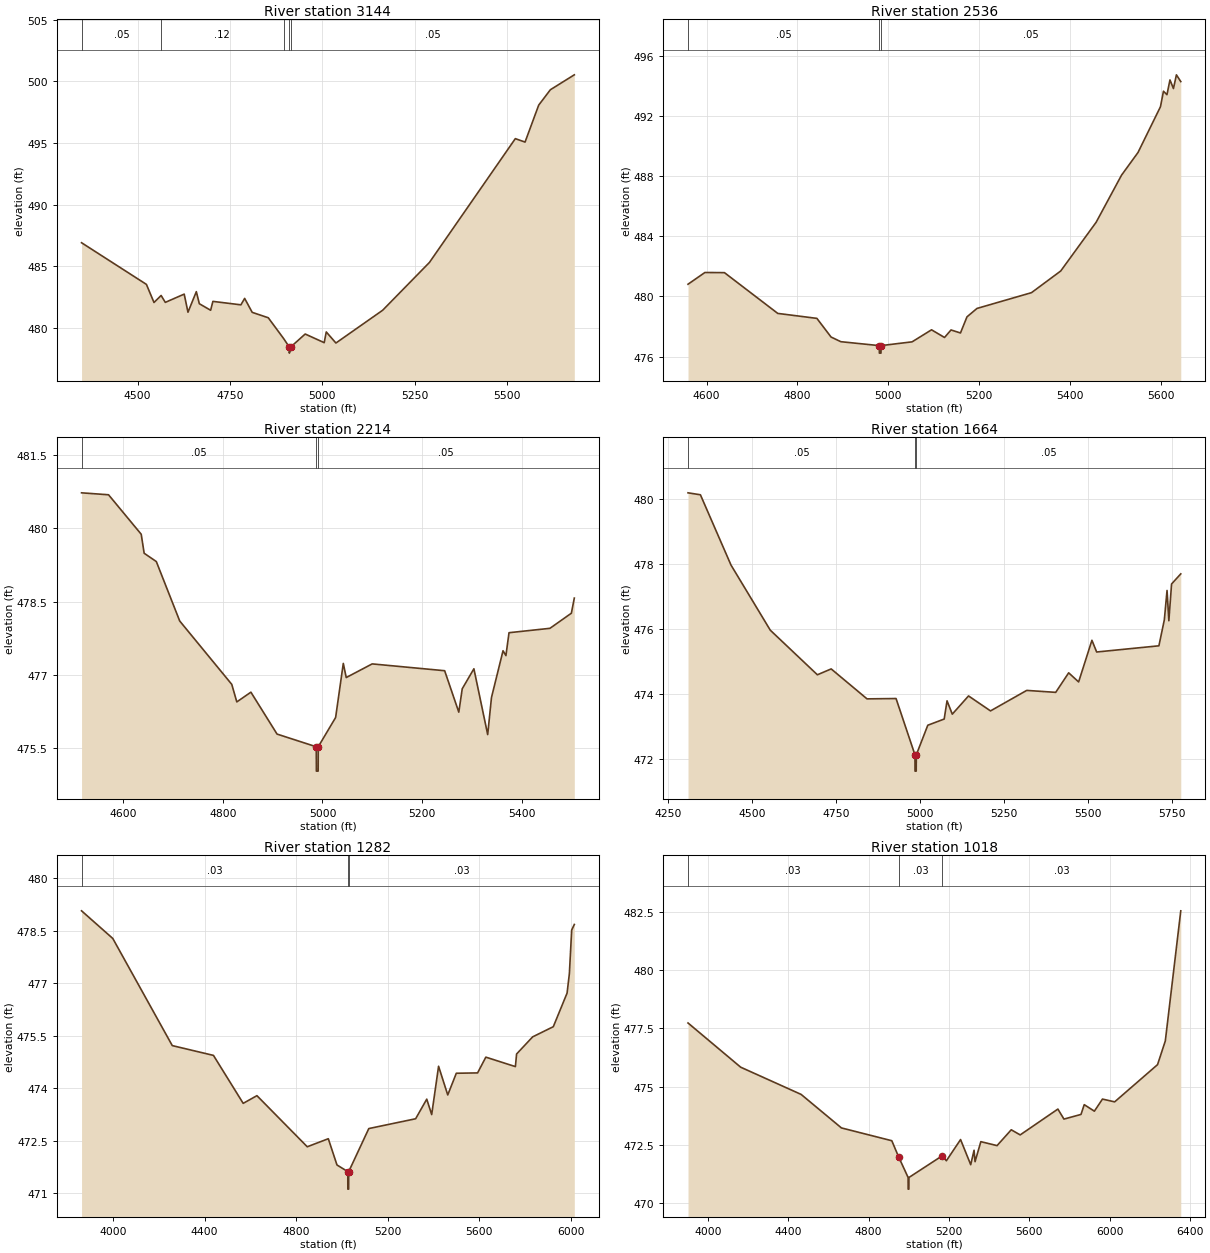
Type RM Length L Ch R = 1 ,3144    ,608,608,608
BEGIN DESCRIPTION:
Mapping XS 9cb55444
END DESCRIPTION:
XS GIS Cut Line= 3
      2677997.91      6951502.71      2678128.73       6950878.7
        2677909.      6950219.33
#Sta/Elev= 30
  4348.6   486.9    4524  483.52  4544.5  482.05  4563.8  482.62  4575.1  482.06
  4626.2  482.73  4636.4  481.26    4659  482.93  4667.1  481.95  4697.7  481.42
  4703.8  482.14  4779.5  481.86  4789.7  482.38  4810.1  481.25  4853.6  480.81
  4894.9  479.13  4910.3  478.44  4910.6  477.94  4914.3  478.44  4953.4  479.49
  5004.8  478.79  5010.4  479.66  5036.5  478.76  5162.9  481.42  5289.4   485.3
  5521.7  495.35    5548  495.07  5584.9  498.07  5616.5  499.32  5681.2  500.53
#Mann= 5 ,-1 , 0
  4348.6     .05       0  4563.8     .12       0  4894.9     .05       0
  4910.3     .05       0  4914.3     .05       0
Bank Sta=4910.3,4914.3
XS Rating Curve= 0 ,0
Exp/Cntr=0.3,0.1

Type RM Length L Ch R = 1 ,2536    ,322,322,322
BEGIN DESCRIPTION:
Mapping XS 3fdf9db0
END DESCRIPTION:
XS GIS Cut Line= 3
      2678451.01      6951085.99      2678645.99      6950752.19
      2678192.88      6950220.96
#Sta/Elev= 30
  4559.2  480.81  4596.4  481.59  4639.4  481.58  4756.8  478.87  4842.9  478.54
  4874.1   477.3  4895.6  476.99  4980.2  476.73  4980.5  476.23    4984  476.23
  4984.2  476.73  5052.5  476.98  5095.3  477.78  5123.9  477.27  5138.2  477.77
    5159  477.57  5173.3  478.64  5195.3   479.2  5315.4  480.25  5379.7  481.69
  5457.7  484.93  5513.6  488.06  5549.9  489.57  5599.3  492.61  5605.9  493.64
  5613.6  493.41  5620.2  494.39  5627.9  493.82  5634.4  494.73    5644  494.28
#Mann= 3 ,-1 , 0
  4559.2     .05       0  4980.2     .04       0  4984.2     .05       0
Bank Sta=4980.2,4984.2
XS Rating Curve= 0 ,0
Exp/Cntr=0.3,0.1

Type RM Length L Ch R = 1 ,2214    ,550,550,550
BEGIN DESCRIPTION:
Mapping XS e702e289
END DESCRIPTION:
XS GIS Cut Line= 3
      2678833.49      6951189.67       2678901.2      6950705.31
      2678638.87      6950279.38
#Sta/Elev= 30
  4516.3  480.73  4570.5  480.69  4636.1  479.88    4642  479.49  4666.4  479.32
  4713.4   478.1  4817.9   476.8    4828  476.44  4856.3  476.64  4908.8  475.78
  4987.5  475.52  4987.8  475.02  4991.3  475.02  4991.5  475.52  5026.4  476.12
  5041.8  477.23  5047.7  476.94  5099.8  477.22  5245.3  477.08  5273.7  476.23
  5280.6  476.71    5304  477.12  5331.7  475.77  5339.3  476.53  5362.5  477.49
  5368.3  477.39  5374.5  477.86  5456.7  477.95  5499.7  478.26  5505.6  478.57
#Mann= 3 ,-1 , 0
  4516.3     .05       0  4987.5     .04       0  4991.5     .05       0
Bank Sta=4987.5,4991.5
XS Rating Curve= 0 ,0
Exp/Cntr=0.3,0.1

Type RM Length L Ch R = 1 ,1664    ,382,382,382
BEGIN DESCRIPTION:
Mapping XS 50682325
END DESCRIPTION:
XS GIS Cut Line= 4
      2679198.08       6951210.5      2679410.55      6950639.26
      2679331.96      6950518.04      2678670.62      6950251.67
#Sta/Elev= 30
  4309.3  480.19  4346.2  480.13  4437.3  477.97  4554.2  475.97  4694.4   474.6
  4735.5  474.78  4842.2  473.86  4928.6  473.87  4984.9  472.14  4985.1  471.64
  4988.6  471.64  4988.9  472.14  5023.1  473.05  5071.9  473.24  5080.4   473.8
    5096  473.39  5144.4  473.95  5209.8  473.49  5317.6  474.12  5403.9  474.06
  5442.5  474.66  5472.1  474.38  5511.7  475.66  5525.8   475.3  5711.1  475.49
  5727.3  476.29  5735.3  477.19  5740.7  476.26  5748.8  477.39  5776.2   477.7
#Mann= 3 ,-1 , 0
  4309.3     .05       0  4984.9     .04       0  4988.9     .05       0
Bank Sta=4984.9,4988.9
XS Rating Curve= 0 ,0
Exp/Cntr=0.3,0.1

Type RM Length L Ch R = 1 ,1282    ,264,264,264
BEGIN DESCRIPTION:
Mapping XS 575e653d
END DESCRIPTION:
XS GIS Cut Line= 4
      2679619.95      6951387.56      2679627.43       6950363.5
       2679549.3      6950221.51      2678584.52      6950145.85
#Sta/Elev= 30
  3862.1  479.07  3998.7  478.28  4258.7  475.22  4438.7  474.94  4568.7  473.57
  4628.7  473.79  4848.7  472.33  4940.7  472.56  4978.6  471.81  5025.9  471.62
  5026.1  471.12  5029.6  471.12  5029.9  471.62  5117.7  472.85  5322.4  473.13
    5371  473.69  5392.6  473.25  5422.7  474.63  5462.8  473.81  5500.2  474.43
  5593.2  474.44  5629.3  474.89  5758.5  474.62  5763.7  474.98    5834  475.47
  5924.2  475.76  5984.4  476.72  5994.5  477.28  6004.5  478.52    6016  478.68
#Mann= 3 ,-1 , 0
  3862.1     .03       0  5025.9     .03       0  5029.9     .03       0
Bank Sta=5025.9,5029.9
XS Rating Curve= 0 ,0
Exp/Cntr=0.3,0.1

Type RM Length L Ch R = 1 ,1018    ,340,340,340
BEGIN DESCRIPTION:
Mapping XS f3c67800
END DESCRIPTION:
XS GIS Cut Line= 4
      2679740.29      6951192.36      2679817.75      6950168.01
      2679679.46      6949965.82      2678509.74      6950121.72
#Sta/Elev= 30
  3901.7  477.73  4163.8  475.83  4464.7  474.66  4665.2  473.22  4915.9  472.67
  4949.6  471.98  4997.1  471.09  4997.3  470.59  5000.8  470.59  5001.1  471.09
  5166.4  472.02  5187.5  471.81  5258.1  472.72  5308.6  471.64  5325.2  472.26
  5330.2  471.77    5359  472.63  5439.7  472.46  5510.3  473.14  5554.8  472.92
  5742.4  474.03  5772.6   473.6  5857.5   473.8  5873.5  474.22    5924  473.94
  5964.3  474.46  6024.9  474.34  6238.4  475.94  6277.1  476.96    6354  482.55
#Mann= 3 ,-1 , 0
  3901.7     .03       0  4949.6     .03       0  5166.4     .03       0
Bank Sta=4949.6,5166.4
XS Rating Curve= 0 ,0
Exp/Cntr=0.3,0.1

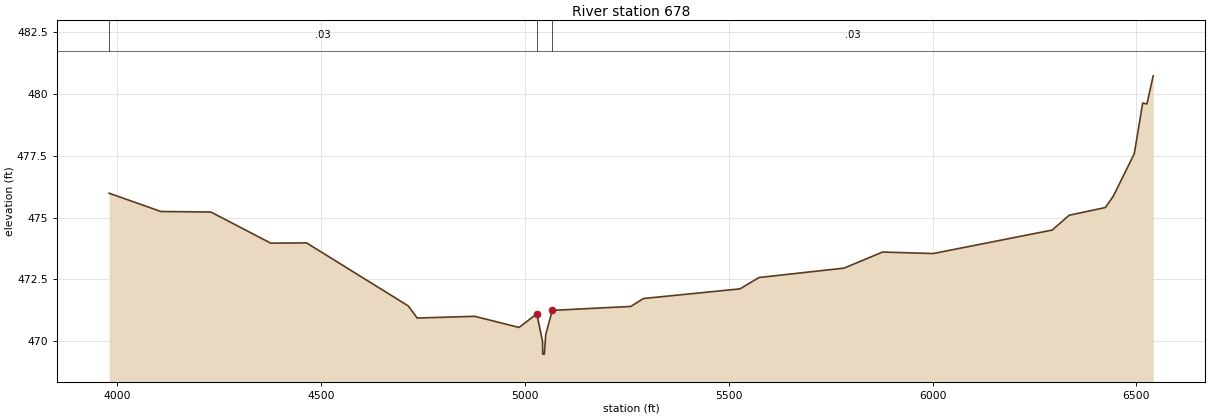
Type RM Length L Ch R = 1 ,678     ,0,0,0
BEGIN DESCRIPTION:
Mapping XS e0ba99c3
END DESCRIPTION:
XS GIS Cut Line= 5
        2679951.      6950786.02      2680018.69      6950435.92
      2680122.19      6950137.92        2679901.        6949736.
      2678510.91      6950074.84
#Sta/Elev= 30
  3979.5  475.99  4106.8  475.25  4229.1  475.23    4376  473.97    4464  473.98
  4713.5  471.43  4735.3  470.94  4876.3  471.01  4985.3  470.56  5028.9  471.11
    5043  469.98  5043.2  469.48  5047.3  469.48  5050.7  470.27  5066.7  471.25
  5259.6  471.41  5290.4  471.73  5527.2  472.12  5574.1  472.58  5782.6  472.96
  5877.1  473.61  6001.4  473.55  6293.3   474.5    6335   475.1  6423.6  475.41
  6443.2  475.87  6494.7  477.59  6515.3  479.64  6525.6   479.6  6541.1  480.74
#Mann= 3 ,-1 , 0
  3979.5     .03       0  5028.9     .03       0  5066.7     .03       0
Bank Sta=5028.9,5066.7
XS Rating Curve= 0 ,0
Exp/Cntr=0.3,0.1

Chan Stop Cuts=-1
Use User Specified Reach Order=0
Composite Channel Slope=5