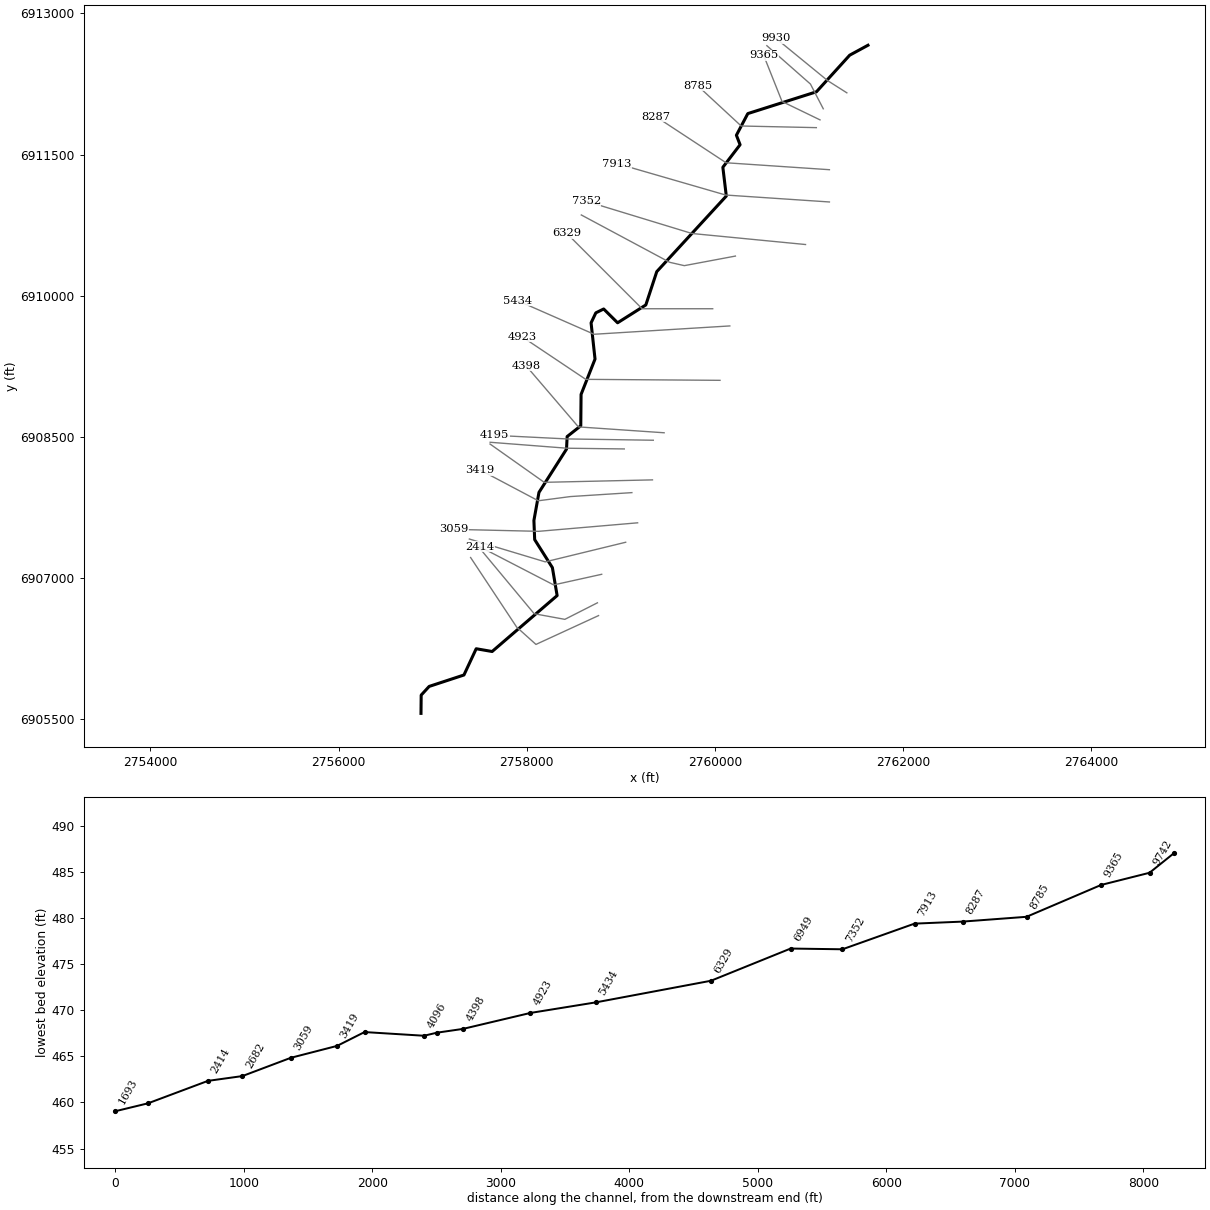
--- Rats Branch.prj (project) ---

Proj Title=Rats Branch Base Level Engineering
Current Plan=p01
Default Exp/Contr=0.3,0.1
English Units
Geom File=g01
Flow File=f01
Plan File=p01
Y Axis Title=Elevation
X Axis Title(PF)=Main Channel Distance
X Axis Title(XS)=Station
BEGIN DESCRIPTION:
Rats Branch
END DESCRIPTION:
DSS Export Rating Curves= 0
DSS Export Rating Curve Sorted= 0
DSS Export Volume Flow Curves= 0
DXF OffsetX= 0
DXF OffsetY= 0
DXF ScaleX= 1
DXF ScaleY= 10

--- Rats Branch.p01 (plan) ---

Plan Title=Multiple Run
Short Identifier=Multiple
Geom File=g01
Flow File=f01
Subcritical Flow
K Sum by GR= 0
Std Step Tol= 0.01
Critical Tol= 0.01
Num of Std Step Trials= 20
Max Error Tol= 0.3
Flow Tol Ratio= 0.001
Split Flow NTrial= 30
Split Flow Tol= 0.02
Split Flow Ratio= 0.02
Log Output Level= 0
Friction Slope Method= 1
Unsteady Friction Slope Method= 2
Unsteady Bridges Friction Slope Method= 1
Parabolic Critical Depth
Global Vel Dist=  1 , 1 , 1
Global Log Level= 0
CheckData=True
Encroach Param= -1, 0, 0, 0
BEGIN DESCRIPTION:
Multiple Run
END DESCRIPTION:

--- Rats Branch.f01 (steady flow) ---

Flow Title=Multiple
Program Version=4.10
Number of Profiles= 7
Profile Names=10-year,25-year,50-year,1pct_min,100-year,1pct_plu,500-year
River Rch & RM=Rats Branch,Reach-1         ,9930
     561     749     901     539    1075    2145    1533
River Rch & RM=Rats Branch,Reach-1         ,8785
     799    1084    1317     795    1586    3164    2302
River Rch & RM=Rats Branch,Reach-1         ,4195
     832    1131    1376     831    1657    3307    2410
River Rch & RM=Rats Branch,Reach-1         ,3059
     889    1210    1475     892    1780    3551    2596
Boundary for River Rch & Prof#=Rats Branch,Reach-1         , 1
Up Type= 0
Dn Type= 3
Dn Slope=0.005
Boundary for River Rch & Prof#=Rats Branch,Reach-1         , 2
Up Type= 0
Dn Type= 3
Dn Slope=0.005
Boundary for River Rch & Prof#=Rats Branch,Reach-1         , 3
Up Type= 0
Dn Type= 3
Dn Slope=0.005
Boundary for River Rch & Prof#=Rats Branch,Reach-1         , 4
Up Type= 0
Dn Type= 3
Dn Slope=0.005
Boundary for River Rch & Prof#=Rats Branch,Reach-1         , 5
Up Type= 0
Dn Type= 3
Dn Slope=0.005
Boundary for River Rch & Prof#=Rats Branch,Reach-1         , 6
Up Type= 0
Dn Type= 3
Dn Slope=0.005
Boundary for River Rch & Prof#=Rats Branch,Reach-1         , 7
Up Type= 0
Dn Type= 3
Dn Slope=0.005
DSS Import GetInterval= 0
DSS Import GetPeak= 0
DSS Import FillOption= 0

--- Rats Branch.g01 (geometry) ---

Geom Title=Existing Conditions

River Reach=Rats Branch,Reach-1
Reach XY= 30
      2761626.00      6912661.00      2761431.61      6912555.41
      2761078.45      6912166.47      2760349.08      6911934.84
      2760227.86      6911704.86      2760266.92      6911604.01
      2760083.81      6911364.41      2760120.54      6911058.55
      2759381.59      6910255.39      2759265.25      6909901.29
      2758965.29      6909711.70      2758817.46      6909858.42
      2758734.05      6909817.45      2758683.53      6909711.01
      2758725.48      6909326.22      2758577.22      6908950.50
      2758573.95      6908616.84      2758429.08      6908502.69
      2758422.61      6908369.42      2758129.75      6907909.45
      2758076.00      6907611.00      2758084.07      6907407.69
      2758272.45      6907109.53      2758322.67      6906812.69
      2757632.06      6906218.48      2757462.73      6906247.88
      2757332.41      6905968.77      2756962.76      6905847.40
      2756878.04      6905755.16      2756876.00      6905561.00

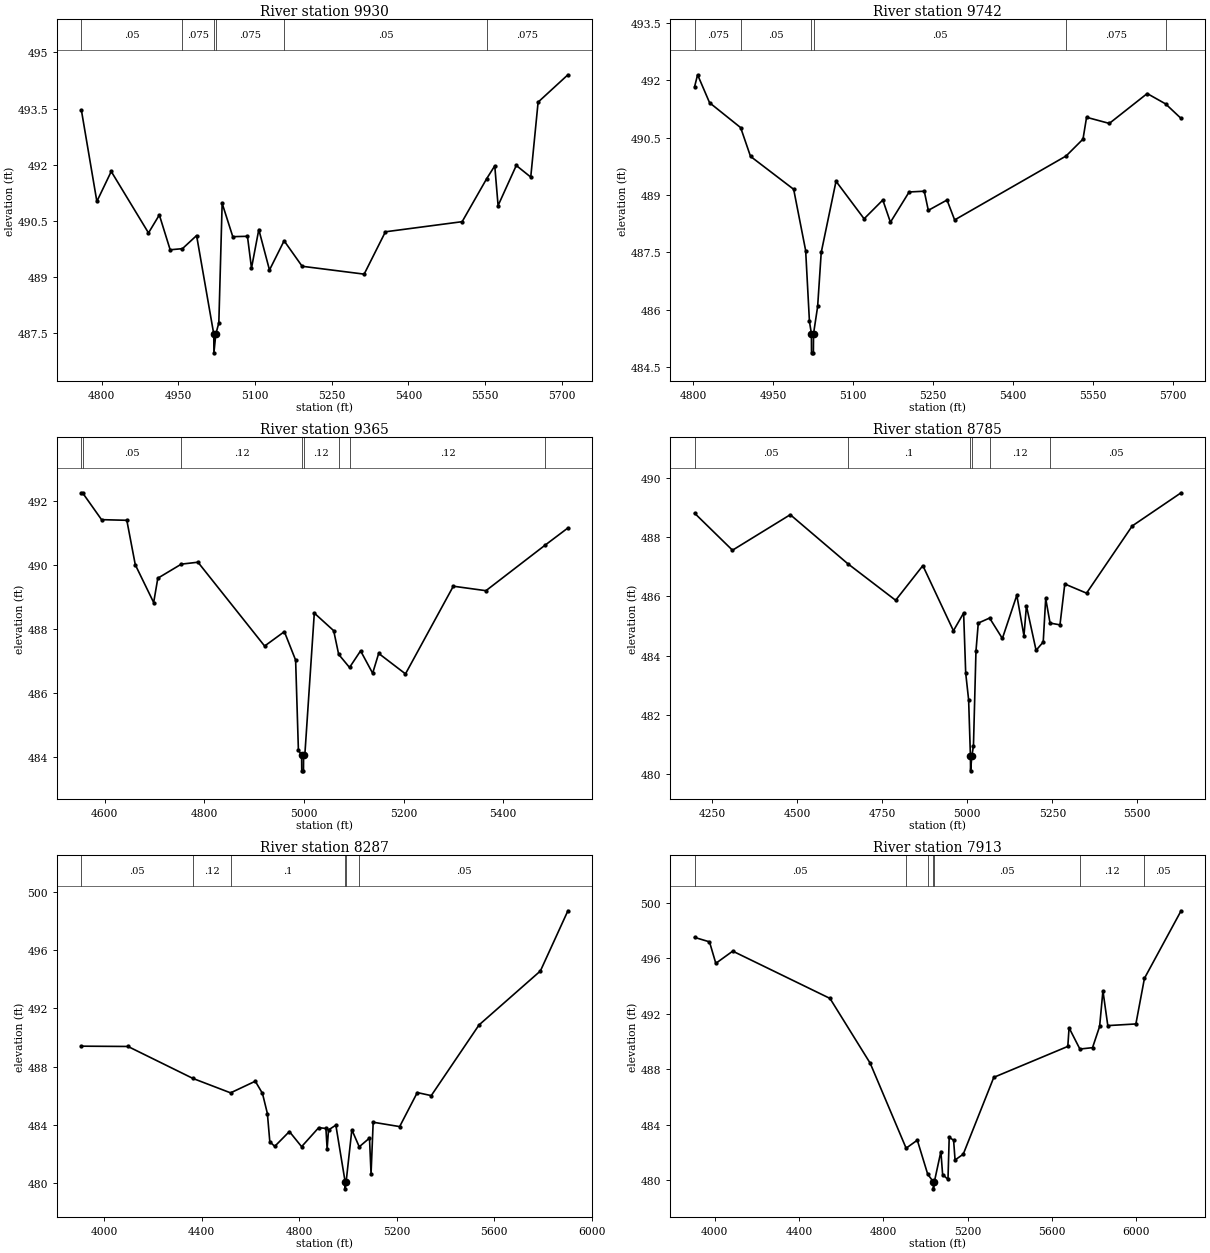
Type RM Length L Ch R = 1,9930,188,188,188
BEGIN DESCRIPTION:
Rats Branch 17.0
END DESCRIPTION:
XS GIS Cut Line= 3
      2761401.50      6912155.56      2761198.97      6912283.95
      2760647.85      6912734.58
#Sta/Elev= 30
  4760.2  493.45  4790.4  491.02  4818.5  491.82  4891.4  490.18  4912.6  490.66
  4933.8  489.73  4957.8  489.76  4985.5  490.11  5019.1  487.48  5019.4  486.98
  5023.1  487.48  5029.0  487.78  5035.5  490.97  5056.3  490.08  5085.0  490.09
  5092.9  489.24  5107.2  490.27  5128.1  489.19  5156.7  489.97  5192.0  489.29
  5313.3  489.08  5354.9  490.21  5505.0  490.48  5553.1  491.63  5568.8  491.97
  5575.3  490.91  5610.9  491.98  5639.2  491.67  5653.6  493.67  5711.9  494.40
#Mann=6,-1,0
  4760.2    0.05       0  4957.8   0.075       0  5019.1    0.07       0
  5023.1   0.075       0  5156.7    0.05       0  5553.1   0.075       0
Bank Sta=5019.1,5023.1
Exp/Cntr=0.3,0.1

Type RM Length L Ch R = 1,9742,377,377,377
BEGIN DESCRIPTION:
Mapping XS a2f88d2c
END DESCRIPTION:
XS GIS Cut Line= 3
      2761150.98      6911986.03      2761014.58      6912248.80
      2760551.52      6912656.46
#Sta/Elev= 30
  4802.5  491.83  4808.1  492.14  4830.6  491.41  4888.9  490.76  4907.4  490.01
  4988.4  489.15  5010.9  487.55  5018.0  485.70  5021.7  485.38  5021.9  484.88
  5025.4  484.88  5025.7  485.38  5033.4  486.09  5040.1  487.50  5067.9  489.36
  5120.6  488.38  5155.7  488.87  5170.0  488.29  5205.1  489.08  5233.5  489.10
  5241.1  488.60  5276.2  488.87  5290.5  488.35  5499.7  490.02  5531.4  490.46
  5538.1  491.03  5580.8  490.87  5651.9  491.65  5686.4  491.38  5715.5  491.00
#Mann=6,-1,0
  4802.5   0.075       0  4888.9    0.05       0  5021.7    0.05       0
  5025.7    0.05       0  5499.7   0.075       0  5686.4    0.05       0
Bank Sta=5021.7,5025.7
Exp/Cntr=0.3,0.1

Type RM Length L Ch R = 1,9365,580,580,580
BEGIN DESCRIPTION:
Mapping XS ba8b2c38
END DESCRIPTION:
XS GIS Cut Line= 3
      2761116.54      6911868.03      2760712.86      6912063.35
      2760517.53      6912553.84
#Sta/Elev= 30
  4553.4  492.25  4555.6  492.25  4593.8  491.41  4644.5  491.39  4661.5  490.00
  4698.4  488.82  4706.7  489.58  4753.9  490.02  4787.3  490.08  4921.1  487.46
  4960.7  487.91  4983.3  487.02  4988.9  484.20  4995.3  484.06  4995.6  483.56
  4999.1  483.56  4999.3  484.06  5001.8  484.06  5020.8  488.49  5059.7  487.94
  5069.7  487.20  5091.5  486.79  5113.7  487.31  5137.9  486.61  5150.0  487.23
  5203.8  486.59  5299.8  489.33  5365.3  489.19  5484.6  490.62  5529.8  491.15
#Mann=8,-1,0
  4553.4   0.075       0  4555.6    0.05       0  4753.9    0.12       0
  4995.3    0.07       0  4999.3    0.12       0  5069.7     0.1       0
  5091.5    0.12       0  5484.6   0.075       0
Bank Sta=4995.3,4999.3
Exp/Cntr=0.3,0.1

Type RM Length L Ch R = 1,8785,498,498,498
BEGIN DESCRIPTION:
Mapping XS d2cd28cb
END DESCRIPTION:
XS GIS Cut Line= 3
      2761077.40      6911785.58      2760278.83      6911802.94
      2759814.39      6912232.66
#Sta/Elev= 30
  4197.4  488.81  4308.8  487.56  4478.9  488.76  4647.6  487.11  4788.9  485.87
  4869.0  487.04  4959.0  484.84  4989.0  485.44  4995.1  483.41  5003.7  482.51
  5009.0  480.61  5009.4  480.11  5013.2  480.61  5017.9  480.95  5025.3  484.15
  5032.1  485.10  5065.4  485.27  5103.0  484.58  5145.5  486.04  5166.5  484.67
  5173.8  485.68  5202.2  484.18  5223.2  484.46  5230.5  485.93  5243.3  485.10
  5272.5  485.04  5286.7  486.42  5350.7  486.11  5485.1  488.38  5628.9  489.50
#Mann=6,-1,0
  4197.4    0.05       0  4647.6     0.1       0  5009.0    0.07       0
  5013.2     0.1       0  5065.4    0.12       0  5243.3    0.05       0
Bank Sta=5009,5013.2
Exp/Cntr=0.3,0.1

Type RM Length L Ch R = 1,8287,374,374,374
BEGIN DESCRIPTION:
Mapping XS 3d7e002b
END DESCRIPTION:
XS GIS Cut Line= 3
      2761216.37      6911338.52      2760118.24      6911412.31
      2759371.74      6911902.75
#Sta/Elev= 30
  3907.8  489.40  4098.6  489.38  4365.0  487.18  4519.1  486.19  4620.4  486.99
  4649.8  486.15  4669.9  484.77  4679.9  482.83  4700.0  482.51  4760.1  483.53
  4810.2  482.49  4880.4  483.80  4909.8  483.74  4914.8  482.34  4920.5  483.64
  4950.5  483.97  4988.4  480.09  4988.8  479.59  4992.8  480.09  5016.1  483.65
  5046.4  482.48  5088.4  483.08  5094.8  480.62  5103.5  484.17  5212.0  483.87
  5284.3  486.21  5341.5  486.00  5537.4  490.86  5788.8  494.57  5901.6  498.71
#Mann=6,-1,0
  3907.8    0.05       0  4365.0    0.12       0  4519.1     0.1       0
  4988.4    0.07       0  4992.8     0.1       0  5046.4    0.05       0
Bank Sta=4988.4,4992.8
Exp/Cntr=0.3,0.1

Type RM Length L Ch R = 1,7913,561,561,561
BEGIN DESCRIPTION:
Mapping XS 6f520fdf
END DESCRIPTION:
XS GIS Cut Line= 3
      2761216.31      6910995.65      2760113.90      6911069.43
      2758960.15      6911403.41
#Sta/Elev= 30
  3905.6  497.50  3976.1  497.18  4006.1  495.63  4086.3  496.51  4547.3  493.10
  4737.8  488.43  4908.2  482.30  4961.2  482.88  5010.2  480.44  5037.1  479.87
  5037.7  479.37  5041.9  479.87  5073.0  482.06  5081.2  480.40  5106.6  480.05
  5112.4  483.08  5133.2  482.88  5140.2  481.45  5179.0  481.87  5323.8  487.41
  5674.6  489.64  5680.6  490.98  5731.9  489.45  5791.8  489.55  5825.4  491.08
  5841.1  493.65  5864.2  491.14  5997.3  491.26  6037.9  494.55  6211.6  499.42
#Mann=7,-1,0
  3905.6    0.05       0  4908.2     0.1       0  5010.2    0.05       0
  5037.1    0.07       0  5041.9    0.05       0  5731.9    0.12       0
  6037.9    0.05       0
Bank Sta=5037.1,5041.9
Exp/Cntr=0.3,0.1

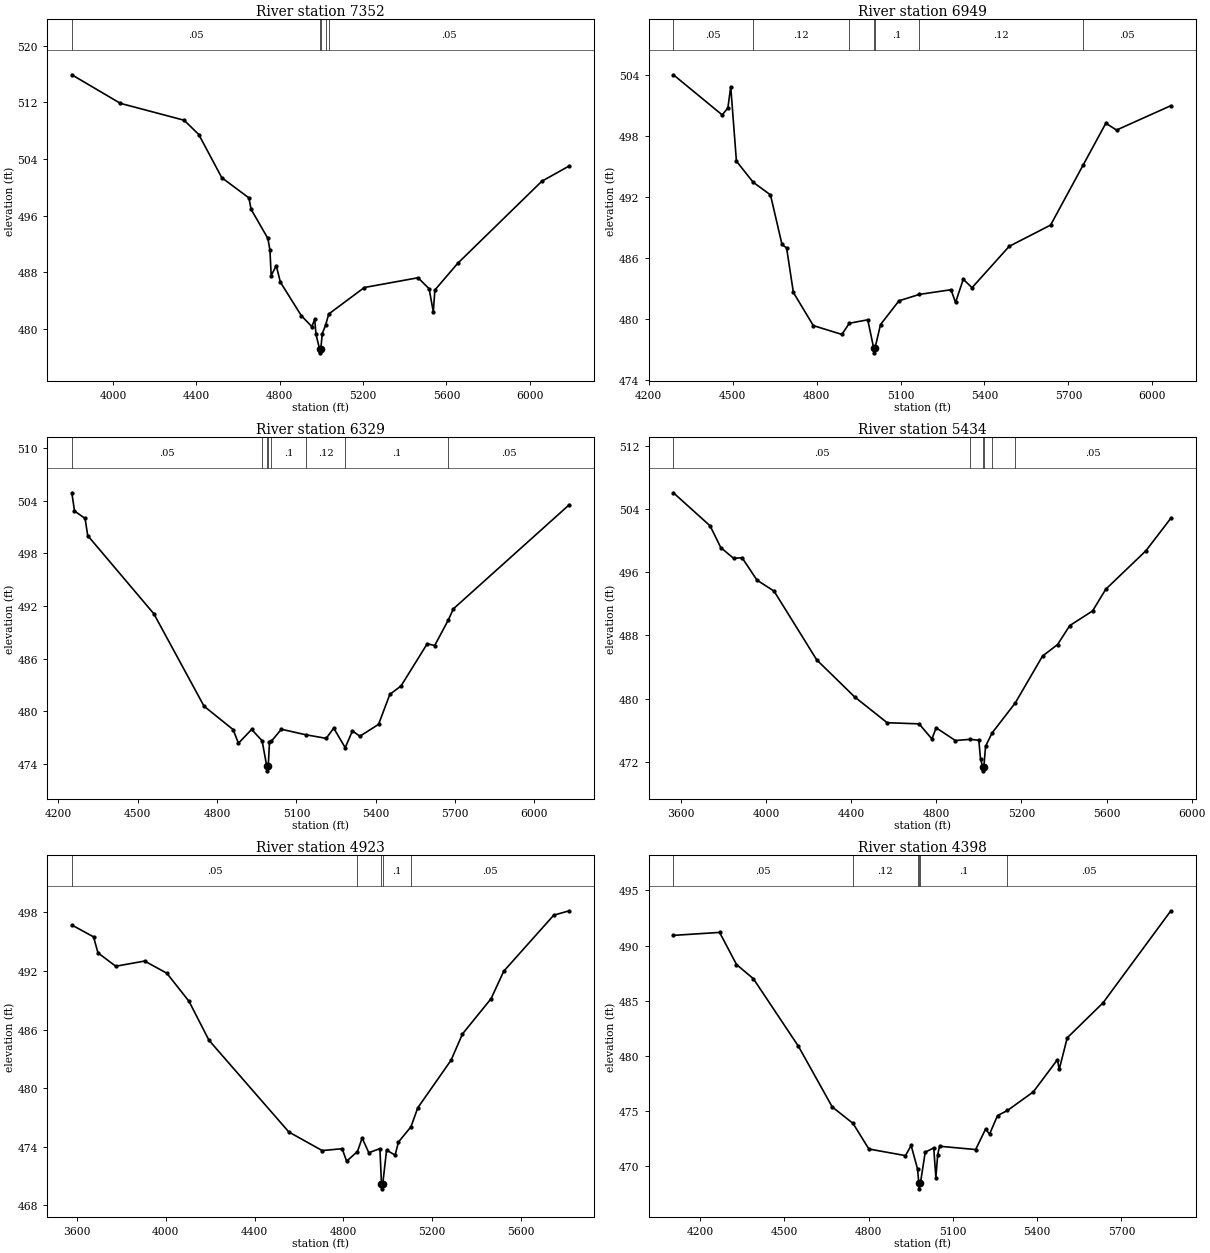
Type RM Length L Ch R = 1,7352,403,403,403
BEGIN DESCRIPTION:
Mapping XS 24718db1
END DESCRIPTION:
XS GIS Cut Line= 3
      2760962.36      6910543.45      2759755.77      6910660.63
      2758631.66      6911003.51
#Sta/Elev= 30
  3802.2  515.92  4035.1  511.88  4341.0  509.49  4411.4  507.47  4521.9  501.36
  4651.9  498.51  4662.6  496.89  4743.0  492.77  4753.0  491.12  4758.8  487.52
  4783.2  488.92  4803.2  486.58  4903.7  481.84  4954.0  480.30  4967.8  481.33
  4974.0  479.20  4991.5  477.09  4992.2  476.59  4996.8  477.09  5004.2  479.31
  5020.2  480.53  5035.1  482.08  5205.9  485.83  5463.8  487.21  5517.0  485.65
  5537.0  482.38  5544.6  485.48  5653.5  489.23  6057.8  500.86  6189.7  503.03
#Mann=5,-1,0
  3802.2    0.05       0  4991.5    0.05       0  4996.8    0.05       0
  5020.2    0.12       0  5035.1    0.05       0
Bank Sta=4991.5,4996.8
Exp/Cntr=0.3,0.1

Type RM Length L Ch R = 1,6949,620,620,620
BEGIN DESCRIPTION:
Mapping XS 7b328bab
END DESCRIPTION:
XS GIS Cut Line= 4
      2760217.29      6910420.76      2759674.20      6910318.93
      2759519.35      6910354.31      2758579.72      6910857.55
#Sta/Elev= 30
  4288.6  504.03  4462.9  500.08  4483.2  500.77  4493.4  502.86  4513.7  495.53
  4573.4  493.46  4635.4  492.21  4676.5  487.34  4693.0  486.99  4717.2  482.61
  4788.5  479.35  4890.6  478.48  4917.0  479.58  4982.9  479.92  5003.9  477.17
  5004.6  476.67  5009.2  477.17  5028.5  479.45  5094.5  481.79  5167.5  482.42
  5280.3  482.88  5296.6  481.63  5324.2  483.91  5355.5  483.08  5488.3  487.15
  5636.2  489.24  5752.3  495.14  5833.6  499.26  5871.8  498.59  6065.9  500.99
#Mann=7,-1,0
  4288.6    0.05       0  4573.4    0.12       0  4917.0     0.1       0
  5003.9    0.07       0  5009.2     0.1       0  5167.5    0.12       0
  5752.3    0.05       0
Bank Sta=5003.9,5009.2
Exp/Cntr=0.3,0.1

Type RM Length L Ch R = 1,6329,895,895,895
BEGIN DESCRIPTION:
Rats Branch 9.0
END DESCRIPTION:
XS GIS Cut Line= 3
      2759976.02      6909861.00      2759226.00      6909861.00
      2758425.99      6910661.01
#Sta/Elev= 30
  4250.6  504.93  4260.6  502.85  4300.6  502.00  4310.6  500.04  4560.6  491.12
  4750.6  480.56  4860.6  477.89  4880.6  476.33  4930.6  477.91  4970.2  476.61
  4987.9  473.68  4988.7  473.18  4993.3  473.68  4998.1  476.42  5005.5  476.57
  5043.0  477.93  5135.2  477.30  5212.7  476.89  5241.0  478.06  5284.5  475.82
  5311.7  477.74  5340.0  477.13  5410.7  478.49  5453.2  481.91  5495.6  482.87
  5594.6  487.69  5622.9  487.49  5673.7  490.36  5693.6  491.68  6132.0  503.57
#Mann=8,-1,0
  4250.6    0.05       0  4970.2    0.12       0  4987.9    0.07       0
  4993.3    0.12       0  5005.5     0.1       0  5135.2    0.12       0
  5284.5     0.1       0  5673.7    0.05       0
Bank Sta=4987.9,4993.3
Exp/Cntr=0.3,0.1

Type RM Length L Ch R = 1,5434,511,511,511
BEGIN DESCRIPTION:
Mapping XS 43a58ee4
END DESCRIPTION:
XS GIS Cut Line= 3
      2760157.95      6909678.36      2758715.23      6909589.81
      2757899.29      6909948.41
#Sta/Elev= 30
  3565.6  506.07  3737.9  501.88  3788.0  499.13  3848.1  497.77  3888.2  497.84
  3958.3  495.00  4038.4  493.61  4238.8  484.90  4417.2  480.20  4569.4  476.94
  4719.7  476.79  4779.8  474.88  4799.9  476.29  4890.0  474.68  4958.4  474.83
  5000.2  474.72  5008.1  472.38  5018.2  471.34  5019.1  470.84  5023.8  471.34
  5032.0  473.96  5062.3  475.63  5171.6  479.45  5299.7  485.39  5369.8  486.83
  5427.4  489.24  5534.5  491.10  5596.3  493.84  5785.7  498.74  5902.3  502.85
#Mann=6,-1,0
  3565.6    0.05       0  4958.4     0.1       0  5018.2    0.07       0
  5023.8     0.1       0  5062.3    0.12       0  5171.6    0.05       0
Bank Sta=5018.2,5023.8
Exp/Cntr=0.3,0.1

Type RM Length L Ch R = 1,4923,525,525,525
BEGIN DESCRIPTION:
Mapping XS f5d4f859
END DESCRIPTION:
XS GIS Cut Line= 3
      2760053.72      6909100.23      2758626.69      6909110.65
      2757950.26      6909563.33
#Sta/Elev= 30
  3576.7  496.71  3674.4  495.50  3694.4  493.86  3774.4  492.49  3904.4  493.02
  4004.4  491.78  4104.4  488.90  4194.4  484.91  4554.4  475.51  4704.5  473.61
  4794.5  473.80  4814.5  472.52  4863.3  473.51  4884.5  474.89  4914.5  473.39
  4964.5  473.81  4971.6  470.19  4972.5  469.69  4977.3  470.19  4994.5  473.66
  5033.0  473.14  5048.0  474.48  5104.3  476.04  5135.1  477.99  5285.2  482.87
  5336.3  485.55  5465.4  489.17  5522.4  491.98  5747.6  497.72  5817.7  498.17
#Mann=5,-1,0
  3576.7    0.05       0  4863.3     0.1       0  4971.6    0.07       0
  4977.3     0.1       0  5104.3    0.05       0
Bank Sta=4971.6,4977.3
Exp/Cntr=0.3,0.1

Type RM Length L Ch R = 1,4398,203,203,203
BEGIN DESCRIPTION:
Mapping XS 9ed5fced
END DESCRIPTION:
XS GIS Cut Line= 3
      2759460.01      6908542.94      2758548.56      6908605.44
      2757991.45      6909256.27
#Sta/Elev= 30
  4105.6  490.93  4270.0  491.20  4330.1  488.29  4390.3  487.00  4550.7  480.87
  4670.9  475.38  4744.8  473.89  4801.2  471.57  4931.5  470.97  4951.6  471.89
  4974.4  469.76  4978.8  468.46  4979.7  467.96  4984.5  468.46  5001.7  471.28
  5032.0  471.67  5039.6  468.98  5046.2  471.07  5052.8  471.82  5181.2  471.52
  5216.4  473.37  5230.6  472.92  5259.2  474.60  5294.4  475.06  5386.5  476.75
  5472.1  479.66  5478.7  478.80  5507.2  481.65  5634.6  484.82  5875.9  493.16
#Mann=6,-1,0
  4105.6    0.05       0  4744.8    0.12       0  4974.4     0.1       0
  4978.8    0.07       0  4984.5     0.1       0  5294.4    0.05       0
Bank Sta=4978.8,4984.5
Exp/Cntr=0.3,0.1

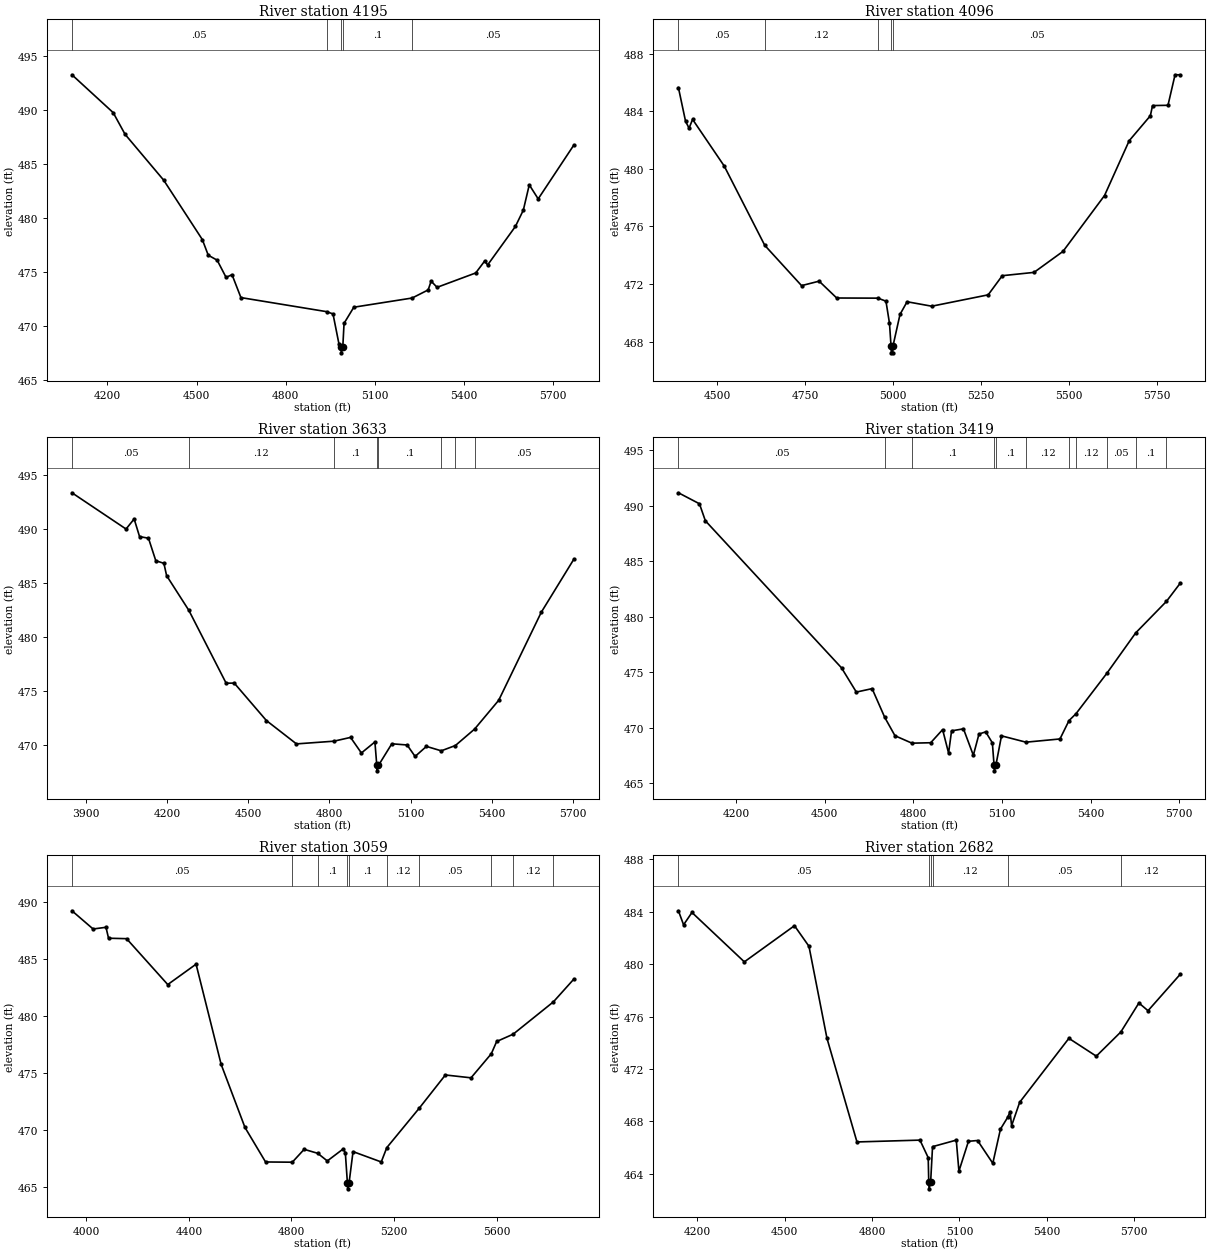
Type RM Length L Ch R = 1,4195,99,99,99
BEGIN DESCRIPTION:
Mapping XS 60355b22
END DESCRIPTION:
XS GIS Cut Line= 3
      2759344.83      6908463.58      2758426.74      6908477.52
      2757656.09      6908515.86
#Sta/Elev= 30
  4080.5  493.27  4219.3  489.77  4259.4  487.76  4389.4  483.52  4519.4  478.03
  4539.4  476.58  4569.4  476.12  4599.4  474.53  4619.4  474.78  4649.4  472.66
  4937.8  471.36  4959.4  471.15  4979.4  468.38  4986.5  468.05  4987.4  467.55
  4992.3  468.05  4996.6  470.28  5029.5  471.77  5225.8  472.62  5279.8  473.37
  5289.8  474.18  5309.8  473.61  5440.0  474.94  5470.0  476.04  5480.0  475.68
  5573.5  479.24  5600.2  480.75  5620.2  483.09  5650.2  481.79  5770.3  486.77
#Mann=5,-1,0
  4080.5    0.05       0  4937.8     0.1       0  4986.5    0.07       0
  4992.3     0.1       0  5225.8    0.05       0
Bank Sta=4986.5,4992.3
Exp/Cntr=0.3,0.1

Type RM Length L Ch R = 1,4096,463,463,463
BEGIN DESCRIPTION:
Mapping XS ebbcb0d0
END DESCRIPTION:
XS GIS Cut Line= 3
      2759036.31      6908371.18      2758426.21      6908378.79
      2757611.00      6908442.02
#Sta/Elev= 30
  4389.0  485.65  4409.3  483.31  4419.3  482.83  4429.3  483.44  4519.3  480.20
  4634.6  474.69  4739.3  471.89  4789.3  472.20  4839.3  471.03  4956.6  471.02
  4979.4  470.81  4989.4  469.28  4993.8  467.72  4994.7  467.22  4998.7  467.22
  4999.6  467.72  5019.4  469.89  5039.5  470.77  5109.7  470.46  5270.2  471.25
  5310.3  472.58  5400.6  472.81  5483.1  474.27  5601.2  478.15  5671.4  481.96
  5731.5  483.69  5737.8  484.40  5781.7  484.42  5801.8  486.54  5816.8  486.54
#Mann=5,-1,0
  4389.0    0.05       0  4634.6    0.12       0  4956.6    0.05       0
  4993.8    0.05       0  4999.6    0.05       0
Bank Sta=4993.8,4999.6
Exp/Cntr=0.3,0.1

Type RM Length L Ch R = 1,3633,214,214,214
BEGIN DESCRIPTION:
Mapping XS 92ac0b32
END DESCRIPTION:
XS GIS Cut Line= 3
      2759335.91      6908042.36      2758185.71      6908016.32
      2757609.74      6908423.40
#Sta/Elev= 30
  3848.1  493.32  4048.1  489.97  4078.1  490.90  4098.1  489.27  4131.1  489.12
  4158.1  487.04  4188.1  486.80  4198.1  485.66  4280.4  482.45  4418.2  475.72
  4448.2  475.73  4567.0  472.27  4678.2  470.11  4816.6  470.36  4878.3  470.71
  4918.3  469.27  4968.3  470.29  4975.3  468.12  4976.3  467.62  4981.4  468.12
  5030.8  470.12  5087.4  470.01  5116.9  468.95  5158.8  469.88  5213.6  469.47
  5265.9  469.96  5336.9  471.48  5426.0  474.14  5583.5  482.28  5703.9  487.18
#Mann=8,-1,0
  3848.1    0.05       0  4280.4    0.12       0  4816.6     0.1       0
  4975.3    0.07       0  4981.4     0.1       0  5213.6    0.12       0
  5265.9     0.1       0  5336.9    0.05       0
Bank Sta=4975.3,4981.4
Exp/Cntr=0.3,0.1

Type RM Length L Ch R = 1,3419,360,360,360
BEGIN DESCRIPTION:
Mapping XS d1ed524c
END DESCRIPTION:
XS GIS Cut Line= 4
      2759117.05      6907906.87      2758462.71      6907864.90
      2758122.94      6907820.23      2757503.60      6908148.01
#Sta/Elev= 30
  4004.6  491.15  4075.8  490.16  4095.8  488.63  4556.8  475.39  4606.9  473.21
  4660.3  473.52  4703.1  470.93  4737.7  469.28  4795.2  468.61  4858.7  468.65
  4899.0  469.83  4919.2  467.72  4929.3  469.72  4969.6  469.90  5003.0  467.52
  5022.1  469.43  5044.8  469.63  5067.4  468.64  5073.2  466.62  5074.2  466.12
  5079.3  466.62  5098.3  469.27  5181.1  468.70  5296.3  468.99  5326.8  470.64
  5350.4  471.26  5455.0  474.90  5552.7  478.54  5656.6  481.37  5703.7  483.02
#Mann=11,-1,0
  4004.6    0.05       0  4703.1    0.12       0  4795.2     0.1       0
  5073.2    0.07       0  5079.3     0.1       0  5181.1    0.12       0
  5326.8    0.05       0  5350.4    0.12       0  5455.0    0.05       0
  5552.7     0.1       0  5656.6    0.05       0
Bank Sta=5073.2,5079.3
Exp/Cntr=0.3,0.1

Type RM Length L Ch R = 1,3059,377,377,377
BEGIN DESCRIPTION:
Mapping XS cb995417
END DESCRIPTION:
XS GIS Cut Line= 3
      2759178.18      6907586.05      2758125.96      6907495.59
      2757225.10      6907516.61
#Sta/Elev= 30
  3943.9  489.25  4026.4  487.65  4076.6  487.80  4086.6  486.84  4156.9  486.80
  4317.5  482.77  4427.9  484.56  4525.7  475.76  4618.6  470.22  4698.9  467.19
  4803.2  467.17  4849.4  468.30  4902.3  467.95  4939.7  467.28  5002.5  468.35
  5010.0  467.98  5018.1  465.33  5019.1  464.83  5024.4  465.33  5040.0  468.10
  5150.0  467.19  5171.7  468.45  5298.8  471.93  5400.1  474.83  5500.1  474.58
  5579.1  476.69  5600.1  477.77  5664.3  478.41  5821.3  481.25  5901.1  483.25
#Mann=10,-1,0
  3943.9    0.05       0  4803.2    0.12       0  4902.3     0.1       0
  5018.1    0.07       0  5024.4     0.1       0  5171.7    0.12       0
  5298.8    0.05       0  5579.1     0.1       0  5664.3    0.12       0
  5821.3    0.05       0
Bank Sta=5018.1,5024.4
Exp/Cntr=0.3,0.1

Type RM Length L Ch R = 1,2682,268,268,268
BEGIN DESCRIPTION:
Mapping XS 593fbf52
END DESCRIPTION:
XS GIS Cut Line= 3
      2759051.18      6907379.46      2758196.13      6907171.12
      2757389.94      6907413.85
#Sta/Elev= 30
  4136.0  484.08  4153.7  483.01  4182.5  483.95  4362.2  480.18  4534.2  482.94
  4583.9  481.37  4645.7  474.34  4748.6  466.43  4964.7  466.57  4993.0  465.23
  4994.9  463.35  4996.0  462.85  5001.3  463.35  5007.9  466.07  5089.3  466.57
  5098.4  464.20  5131.1  466.48  5162.4  466.54  5214.6  464.80  5240.9  467.41
  5266.5  468.34  5273.9  468.75  5279.1  467.67  5306.9  469.46  5475.7  474.34
  5569.7  472.98  5654.0  474.83  5715.9  477.04  5747.2  476.45  5858.0  479.24
#Mann=6,-1,0
  4136.0    0.05       0  4994.9    0.04       0  5001.3    0.05       0
  5007.9    0.12       0  5266.5    0.05       0  5654.0    0.12       0
Bank Sta=4994.9,5001.3
Exp/Cntr=0.3,0.1

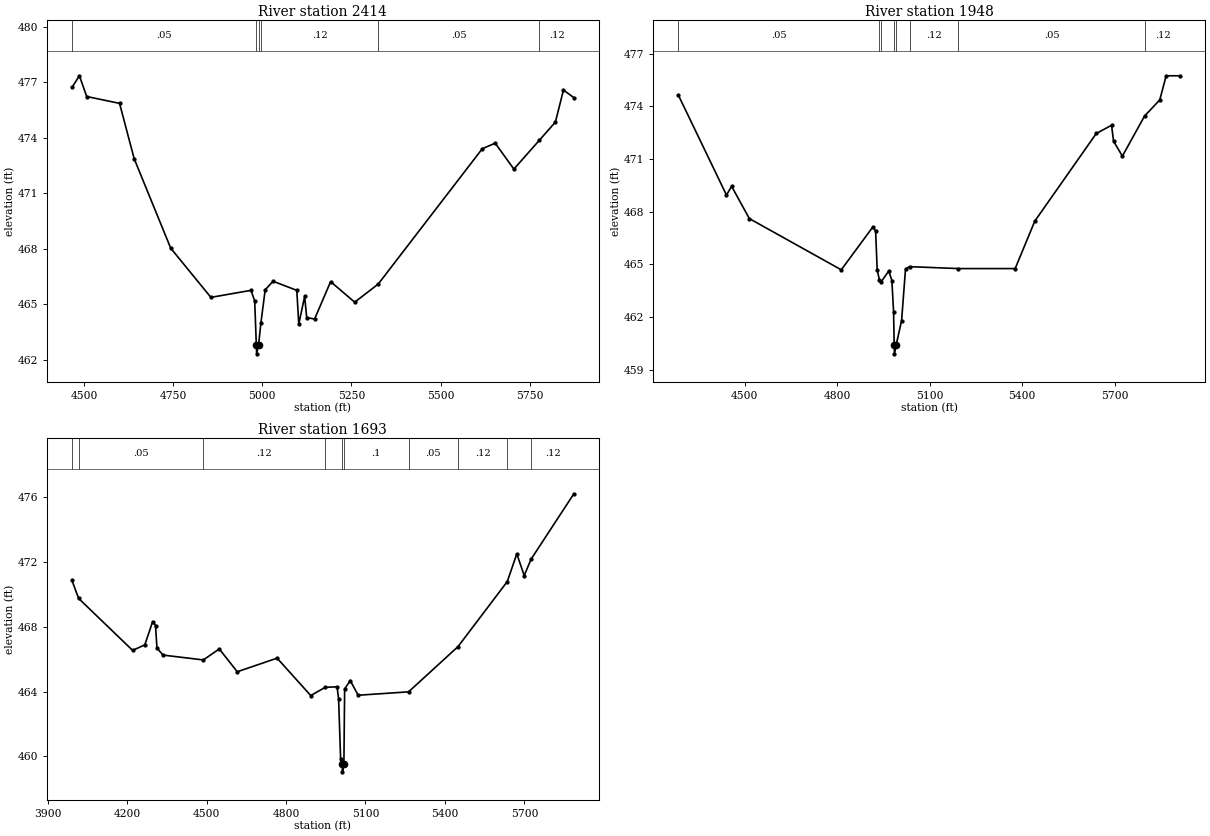
Type RM Length L Ch R = 1,2414,466,466,466
BEGIN DESCRIPTION:
Mapping XS 22140850
END DESCRIPTION:
XS GIS Cut Line= 3
      2758796.39      6907039.04      2758286.00      6906926.13
      2757500.03      6907332.43
#Sta/Elev= 30
  4466.1  476.72  4487.0  477.35  4507.5  476.23  4599.6  475.86  4640.6  472.87
  4743.0  468.04  4855.7  465.38  4968.3  465.76  4978.6  465.18  4983.1  462.83
  4984.1  462.33  4989.5  462.83  4996.0  464.00  5008.0  465.79  5030.2  466.25
  5096.6  465.76  5102.2  463.94  5118.7  465.43  5124.4  464.29  5146.5  464.21
  5191.5  466.23  5259.0  465.12  5325.0  466.10  5616.8  473.41  5653.0  473.71
  5705.4  472.31  5777.0  473.87  5821.9  474.85  5844.4  476.58  5873.6  476.17
#Mann=6,-1,0
  4466.1    0.05       0  4983.1    0.07       0  4989.5    0.05       0
  4996.0    0.12       0  5325.0    0.05       0  5777.0    0.12       0
Bank Sta=4983.1,4989.5
Exp/Cntr=0.3,0.1

Type RM Length L Ch R = 1,1948,255,255,255
BEGIN DESCRIPTION:
Mapping XS 36277302
END DESCRIPTION:
XS GIS Cut Line= 4
      2758750.99      6906735.99      2758404.73      6906560.18
      2758078.94      6906619.91      2757498.44      6907317.38
#Sta/Elev= 30
  4285.4  474.64  4441.2  468.95  4457.9  469.45  4515.3  467.61  4813.3  464.69
  4916.4  467.15  4924.7  466.88  4929.8  464.67  4937.1  464.11  4942.0  463.99
  4967.3  464.62  4977.4  464.08  4982.9  462.29  4984.8  460.40  4985.8  459.90
  4991.2  460.40  5008.9  461.80  5021.6  464.74  5034.7  464.87  5193.3  464.76
  5377.0  464.76  5440.8  467.47  5640.0  472.46  5689.5  472.93  5696.0  472.02
  5724.6  471.17  5796.6  473.46  5845.7  474.37  5866.5  475.75  5912.4  475.75
#Mann=8,-1,0
  4285.4    0.05       0  4937.1    0.12       0  4942.0     0.1       0
  4984.8    0.07       0  4991.2     0.1       0  5034.7    0.12       0
  5193.3    0.05       0  5796.6    0.12       0
Bank Sta=4984.8,4991.2
Exp/Cntr=0.3,0.1

Type RM Length L Ch R = 1,1693,0,0,0
BEGIN DESCRIPTION:
Rats Branch 1.0
END DESCRIPTION:
XS GIS Cut Line= 4
      2758762.80      6906600.08      2758097.65      6906293.74
      2757892.59      6906478.02      2757403.29      6907217.25
#Sta/Elev= 30
  3992.0  470.86  4017.1  469.75  4221.0  466.54  4267.0  466.88  4296.7  468.32
  4307.4  468.07  4312.9  466.68  4335.9  466.25  4488.0  465.95  4548.0  466.63
  4616.0  465.22  4766.4  466.06  4893.4  463.75  4948.1  464.26  4992.8  464.29
  4998.5  463.55  5006.2  459.82  5012.1  459.54  5013.1  459.04  5018.5  459.54
  5021.3  464.15  5042.3  464.68  5072.4  463.77  5262.7  463.98  5449.1  466.77
  5635.2  470.79  5671.2  472.50  5699.1  471.16  5725.0  472.17  5886.5  476.21
#Mann=10,-1,0
  3992.0    0.12       0  4017.1    0.05       0  4488.0    0.12       0
  4948.1     0.1       0  5012.1    0.07       0  5018.5     0.1       0
  5262.7    0.05       0  5449.1    0.12       0  5635.2    0.05       0
  5725.0    0.12       0
Bank Sta=5012.1,5018.5
Exp/Cntr=0.3,0.1

Chan Stop Cuts=-1