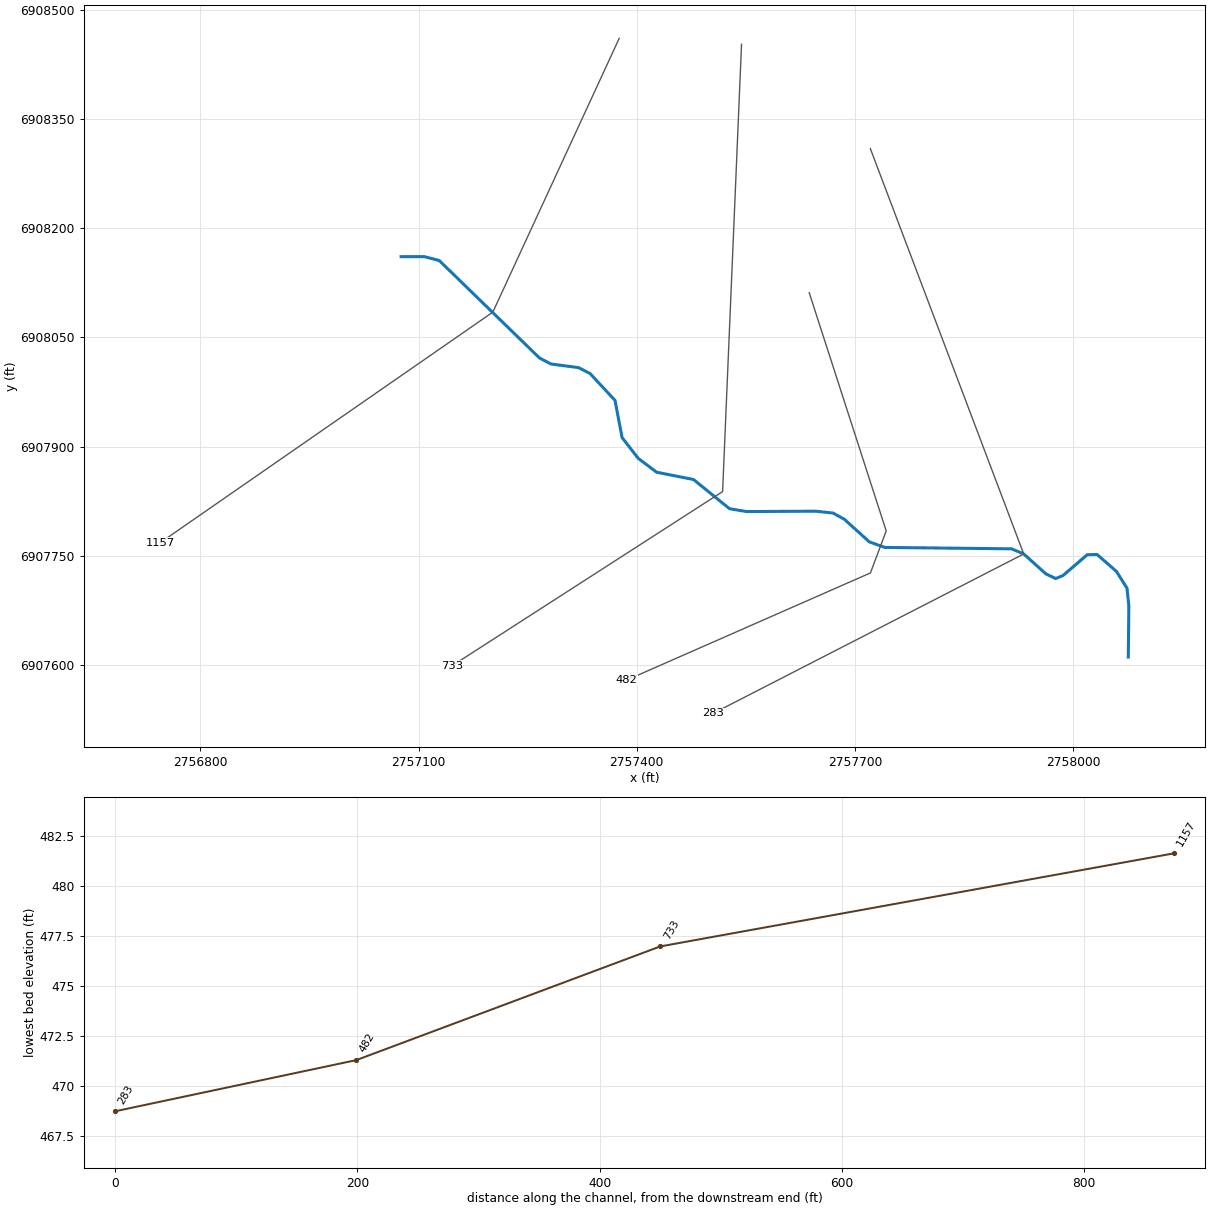
--- Rats T1.prj (project) ---

Proj Title=Rats T1 Base Level Engineering
Current Plan=p01
Default Exp/Contr=0.3,0.1
English Units
Geom File=g01
Flow File=f01
Plan File=p01
Y Axis Title=Elevation
X Axis Title(PF)=Main Channel Distance
X Axis Title(XS)=Station
BEGIN DESCRIPTION:
Rats T1
END DESCRIPTION:
DSS Export Rating Curves= 0
DSS Export Rating Curve Sorted= 0
DSS Export Volume Flow Curves= 0
DXF OffsetX= 0
DXF OffsetY= 0
DXF ScaleX= 1
DXF ScaleY= 10

--- Rats T1.p01 (plan) ---

Plan Title=Multiple Run
Short Identifier=Multiple
Geom File=g01
Flow File=f01
Subcritical Flow
K Sum by GR= 0
Std Step Tol= 0.01
Critical Tol= 0.01
Num of Std Step Trials= 20
Max Error Tol= 0.3
Flow Tol Ratio= 0.001
Split Flow NTrial= 30
Split Flow Tol= 0.02
Split Flow Ratio= 0.02
Log Output Level= 0
Friction Slope Method= 1
Unsteady Friction Slope Method= 2
Unsteady Bridges Friction Slope Method= 1
Parabolic Critical Depth
Global Vel Dist=  1 , 1 , 1
Global Log Level= 0
CheckData=True
Encroach Param= -1, 0, 0, 0
BEGIN DESCRIPTION:
Multiple Run
END DESCRIPTION:

--- Rats T1.f01 (steady flow) ---

Flow Title=Multiple
Program Version=4.10
Number of Profiles= 7
Profile Names=10-year,25-year,50-year,1pct_min,100-year,1pct_plu,500-year
River Rch & RM=Rats T1,Reach-1         ,1157
      96     114     127      71     141     282     175
Boundary for River Rch & Prof#=Rats T1,Reach-1         , 1
Up Type= 0
Dn Type= 3
Dn Slope=0.013
Boundary for River Rch & Prof#=Rats T1,Reach-1         , 2
Up Type= 0
Dn Type= 3
Dn Slope=0.013
Boundary for River Rch & Prof#=Rats T1,Reach-1         , 3
Up Type= 0
Dn Type= 3
Dn Slope=0.013
Boundary for River Rch & Prof#=Rats T1,Reach-1         , 4
Up Type= 0
Dn Type= 3
Dn Slope=0.013
Boundary for River Rch & Prof#=Rats T1,Reach-1         , 5
Up Type= 0
Dn Type= 3
Dn Slope=0.013
Boundary for River Rch & Prof#=Rats T1,Reach-1         , 6
Up Type= 0
Dn Type= 3
Dn Slope=0.013
Boundary for River Rch & Prof#=Rats T1,Reach-1         , 7
Up Type= 0
Dn Type= 3
Dn Slope=0.013
DSS Import GetInterval= 0
DSS Import GetPeak= 0
DSS Import FillOption= 0

--- Rats T1.g01 (geometry) ---

Geom Title=Existing Conditions

River Reach=Rats T1,Reach-1
Reach XY= 30
      2757076.00      6908161.00      2757107.88      6908161.07
      2757128.52      6908155.69      2757266.34      6908021.79
      2757282.09      6908013.55      2757320.13      6908008.54
      2757335.99      6908000.35      2757370.24      6907963.51
      2757379.90      6907912.46      2757402.16      6907883.86
      2757427.42      6907864.86      2757478.15      6907854.85
      2757527.56      6907814.76      2757550.92      6907810.81
      2757646.13      6907811.32      2757670.06      6907808.73
      2757685.64      6907800.14      2757719.94      6907769.14
      2757741.22      6907761.52      2757915.57      6907759.62
      2757932.19      6907752.56      2757962.85      6907725.07
      2757976.11      6907718.81      2757986.08      6907722.86
      2758019.51      6907751.48      2758032.98      6907751.88
      2758059.57      6907728.71      2758074.14      6907705.70
      2758076.74      6907681.50      2758076.00      6907611.00

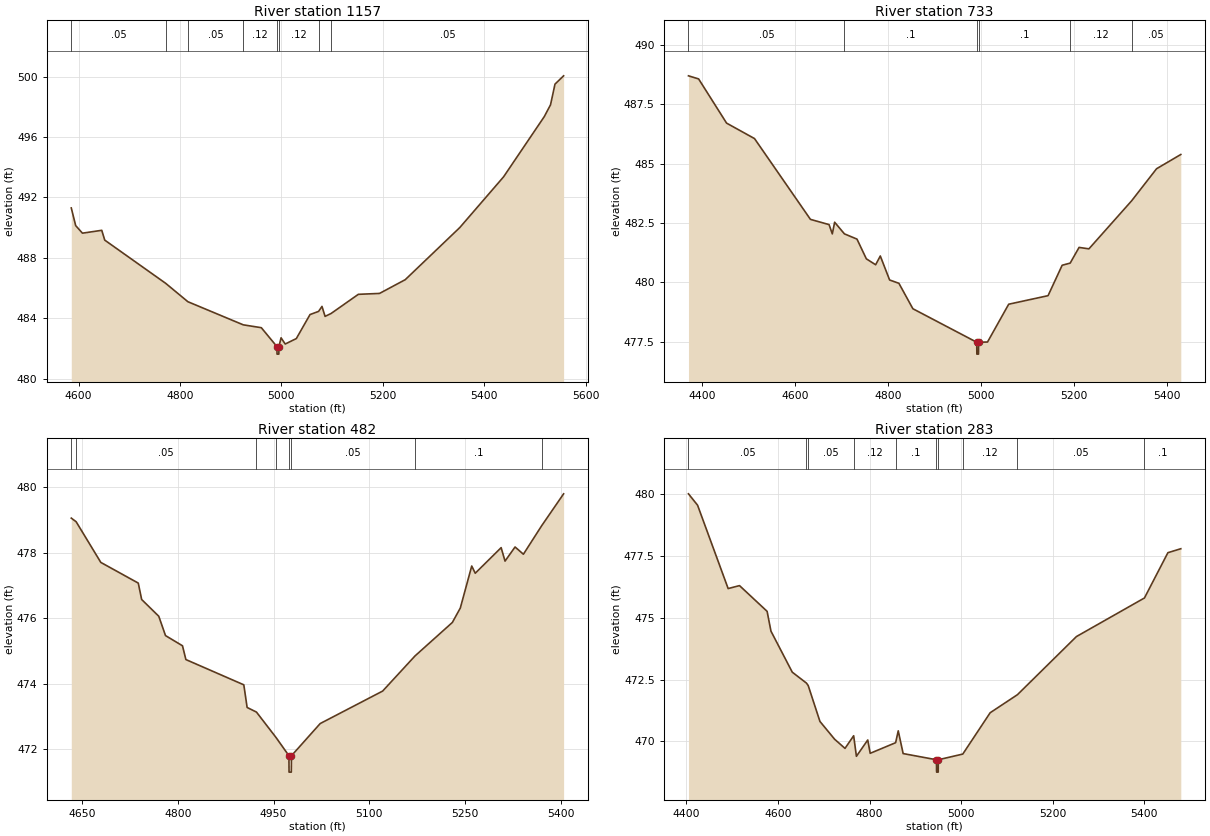
Type RM Length L Ch R = 1,1157,424,424,424
BEGIN DESCRIPTION:
Rats T1 1.0
END DESCRIPTION:
XS GIS Cut Line= 3
      2757375.98      6908460.96      2757202.18      6908084.77
      2756744.69      6907767.92
#Sta/Elev= 30
  4585.6  491.30  4594.3  490.13  4607.6  489.63  4645.7  489.82  4651.6  489.17
  4771.7  486.31  4815.6  485.09  4924.7  483.56  4960.4  483.37  4991.1  482.12
  4991.4  481.62  4994.9  481.62  4995.1  482.12  4999.3  482.70  5007.5  482.29
  5029.4  482.65  5056.4  484.24  5073.3  484.45  5080.0  484.78  5086.1  484.12
  5097.9  484.31  5151.7  485.58  5193.5  485.64  5244.2  486.55  5351.7  490.00
  5438.1  493.36  5518.4  497.35  5530.7  498.13  5539.5  499.50  5556.5  500.05
#Mann=8,-1,0
  4585.6    0.05       0  4771.7    0.12       0  4815.6    0.05       0
  4924.7    0.12       0  4991.1    0.07       0  4995.1    0.12       0
  5073.3     0.1       0  5097.9    0.05       0
Bank Sta=4991.1,4995.1
Exp/Cntr=0.3,0.1

Type RM Length L Ch R = 1,733,251,251,251
BEGIN DESCRIPTION:
Mapping XS a0843d17
END DESCRIPTION:
XS GIS Cut Line= 3
      2757544.17      6908452.82      2757518.13      6907838.24
      2757145.76      6907598.67
#Sta/Elev= 30
  4370.9  488.69  4392.7  488.56  4452.8  486.70  4512.8  486.05  4633.0  482.65
  4673.0  482.43  4680.0  482.04  4685.0  482.53  4706.0  482.04  4733.0  481.82
  4753.1  480.99  4773.1  480.74  4783.1  481.11  4803.1  480.10  4823.1  479.96
  4853.1  478.89  4990.3  477.48  4990.6  476.98  4994.1  476.98  4994.3  477.48
  5013.5  477.49  5059.0  479.08  5143.6  479.44  5173.9  480.72  5191.1  480.81
  5210.2  481.47  5231.4  481.41  5323.1  483.43  5376.7  484.78  5428.8  485.38
#Mann=6,-1,0
  4370.9    0.05       0  4706.0     0.1       0  4990.3    0.07       0
  4994.3     0.1       0  5191.1    0.12       0  5323.1    0.05       0
Bank Sta=4990.3,4994.3
Exp/Cntr=0.3,0.1

Type RM Length L Ch R = 1,482,199,199,199
BEGIN DESCRIPTION:
Mapping XS 23b27dfc
END DESCRIPTION:
XS GIS Cut Line= 4
      2757637.24      6908111.50      2757743.10      6907784.16
      2757721.41      6907726.48      2757386.36      6907579.33
#Sta/Elev= 30
  4632.9  479.05  4640.5  478.94  4679.2  477.70  4737.9  477.07  4743.2  476.57
  4770.0  476.06  4780.6  475.47  4807.2  475.16  4812.5  474.74  4903.3  473.97
  4908.5  473.28  4923.1  473.14  4954.0  472.36  4974.0  471.81  4974.2  471.31
  4977.7  471.31  4978.0  471.81  5023.0  472.79  5120.9  473.78  5171.6  474.85
  5230.1  475.87  5242.6  476.31  5260.5  477.59  5266.0  477.37  5306.6  478.15
  5312.7  477.74  5328.4  478.17  5341.5  477.95  5370.2  478.82  5404.5  479.79
#Mann=8,-1,0
  4632.9     0.1       0  4640.5    0.05       0  4923.1    0.12       0
  4954.0    0.05       0  4974.0    0.04       0  4978.0    0.05       0
  5171.6     0.1       0  5370.2    0.12       0
Bank Sta=4974,4978
Exp/Cntr=0.3,0.1

Type RM Length L Ch R = 1,283,0,0,0
BEGIN DESCRIPTION:
Rats T1 0.0
END DESCRIPTION:
XS GIS Cut Line= 3
      2757721.26      6908309.56      2757932.19      6907752.56
      2757505.08      6907533.54
#Sta/Elev= 30
  4404.4  480.01  4424.3  479.55  4491.1  476.18  4515.9  476.30  4576.2  475.26
  4584.6  474.46  4631.2  472.80  4662.1  472.36  4666.0  472.26  4691.6  470.81
  4723.7  470.09  4746.4  469.72  4765.3  470.23  4771.3  469.40  4796.1  470.06
  4801.4  469.52  4857.0  469.95  4862.7  470.43  4873.4  469.51  4946.2  469.26
  4946.5  468.76  4950.0  468.76  4950.2  469.26  5003.7  469.49  5063.5  471.16
  5123.1  471.89  5252.0  474.24  5400.6  475.80  5451.8  477.63  5480.0  477.79
#Mann=10,-1,0
  4404.4    0.05       0  4662.1    0.12       0  4666.0    0.05       0
  4765.3    0.12       0  4857.0     0.1       0  4946.2    0.07       0
  4950.2     0.1       0  5003.7    0.12       0  5123.1    0.05       0
  5400.6     0.1       0
Bank Sta=4946.2,4950.2
Exp/Cntr=0.3,0.1

Chan Stop Cuts=-1