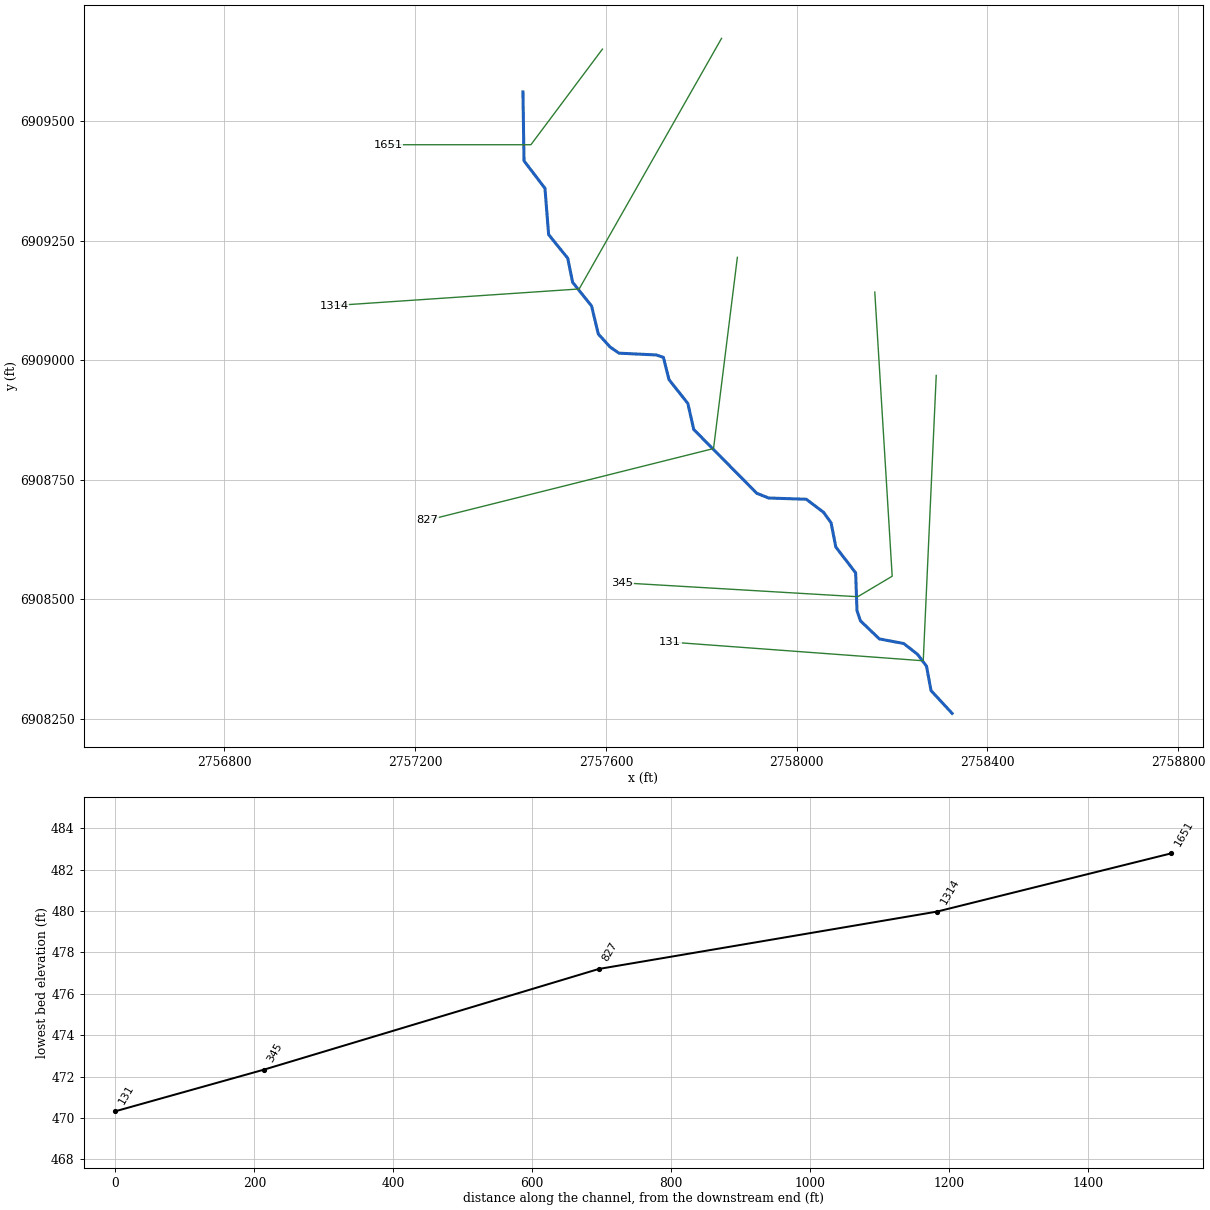
--- Rats T2.prj (project) ---

Proj Title=Rats T2 Base Level Engineering
Current Plan=p01
Default Exp/Contr=0.3,0.1
English Units
Geom File=g01
Flow File=f01
Plan File=p01
Y Axis Title=Elevation
X Axis Title(PF)=Main Channel Distance
X Axis Title(XS)=Station
BEGIN DESCRIPTION:
Rats T2
END DESCRIPTION:
DSS Export Rating Curves= 0
DSS Export Rating Curve Sorted= 0
DSS Export Volume Flow Curves= 0
DXF OffsetX= 0
DXF OffsetY= 0
DXF ScaleX= 1
DXF ScaleY= 10

--- Rats T2.p01 (plan) ---

Plan Title=Multiple Run
Short Identifier=Multiple
Geom File=g01
Flow File=f01
Subcritical Flow
K Sum by GR= 0
Std Step Tol= 0.01
Critical Tol= 0.01
Num of Std Step Trials= 20
Max Error Tol= 0.3
Flow Tol Ratio= 0.001
Split Flow NTrial= 30
Split Flow Tol= 0.02
Split Flow Ratio= 0.02
Log Output Level= 0
Friction Slope Method= 1
Unsteady Friction Slope Method= 2
Unsteady Bridges Friction Slope Method= 1
Parabolic Critical Depth
Global Vel Dist=  1 , 1 , 1
Global Log Level= 0
CheckData=True
Encroach Param= -1, 0, 0, 0
BEGIN DESCRIPTION:
Multiple Run
END DESCRIPTION:

--- Rats T2.f01 (steady flow) ---

Flow Title=Multiple
Program Version=4.10
Number of Profiles= 7
Profile Names=10-year,25-year,50-year,1pct_min,100-year,1pct_plu,500-year
River Rch & RM=Rats T2,Reach-1         ,1651
     125     152     171      97     194     386     246
Boundary for River Rch & Prof#=Rats T2,Reach-1         , 1
Up Type= 0
Dn Type= 3
Dn Slope=0.01
Boundary for River Rch & Prof#=Rats T2,Reach-1         , 2
Up Type= 0
Dn Type= 3
Dn Slope=0.01
Boundary for River Rch & Prof#=Rats T2,Reach-1         , 3
Up Type= 0
Dn Type= 3
Dn Slope=0.01
Boundary for River Rch & Prof#=Rats T2,Reach-1         , 4
Up Type= 0
Dn Type= 3
Dn Slope=0.01
Boundary for River Rch & Prof#=Rats T2,Reach-1         , 5
Up Type= 0
Dn Type= 3
Dn Slope=0.01
Boundary for River Rch & Prof#=Rats T2,Reach-1         , 6
Up Type= 0
Dn Type= 3
Dn Slope=0.01
Boundary for River Rch & Prof#=Rats T2,Reach-1         , 7
Up Type= 0
Dn Type= 3
Dn Slope=0.01
DSS Import GetInterval= 0
DSS Import GetPeak= 0
DSS Import FillOption= 0

--- Rats T2.g01 (geometry) ---

Geom Title=Existing Conditions

River Reach=Rats T2,Reach-1
Reach XY= 30
      2757426.00      6909561.00      2757428.22      6909416.92
      2757472.15      6909359.40      2757479.83      6909262.58
      2757519.88      6909213.18      2757530.16      6909162.72
      2757569.89      6909113.16      2757584.01      6909054.62
      2757608.89      6909027.31      2757627.35      6909014.55
      2757705.74      6909010.78      2757720.55      6909005.75
      2757732.26      6908959.20      2757771.82      6908909.30
      2757784.14      6908854.95      2757916.22      6908721.52
      2757941.22      6908711.53      2758020.29      6908708.92
      2758056.42      6908681.57      2758072.16      6908659.61
      2758082.15      6908608.85      2758123.67      6908555.03
      2758126.47      6908476.09      2758133.75      6908454.55
      2758173.45      6908416.75      2758224.54      6908407.10
      2758253.16      6908384.86      2758272.29      6908359.65
      2758281.72      6908308.68      2758326.00      6908261.00

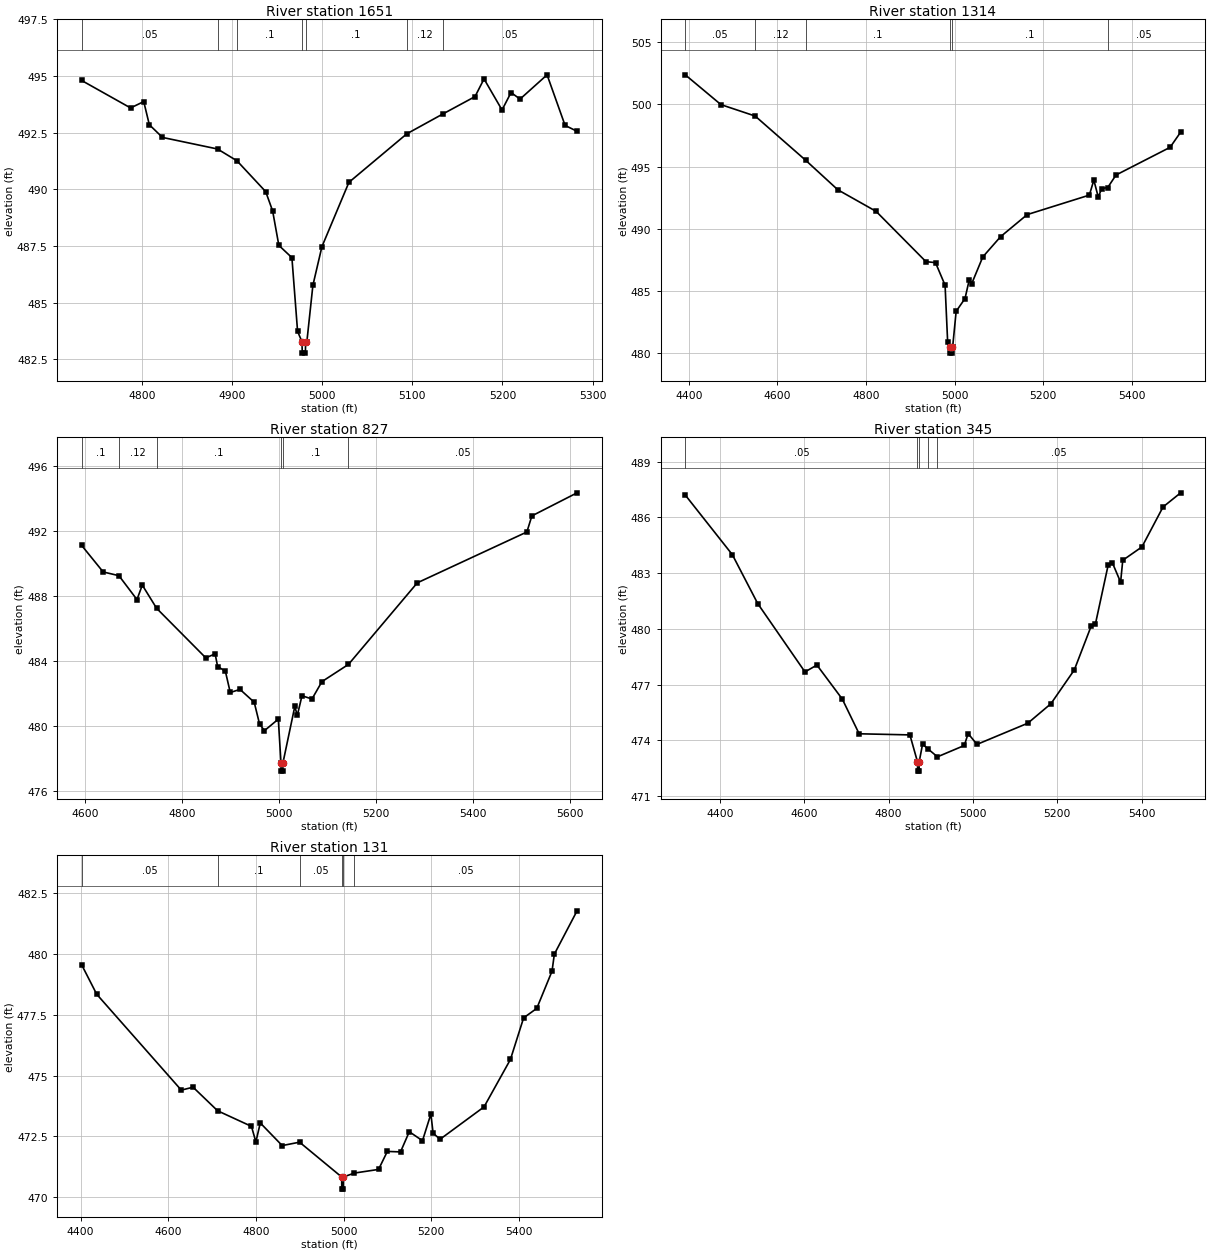
Type RM Length L Ch R = 1,1651,337,337,337
BEGIN DESCRIPTION:
Rats T2 3.0
END DESCRIPTION:
XS GIS Cut Line= 3
      2757592.68      6909650.60      2757442.67      6909450.58
      2757142.68      6909450.58
#Sta/Elev= 30
  4732.8  494.80  4787.1  493.59  4801.7  493.87  4807.9  492.85  4822.5  492.29
  4883.6  491.78  4905.2  491.26  4937.1  489.90  4944.8  489.05  4951.7  487.53
  4966.2  486.99  4972.5  483.74  4977.4  483.28  4977.7  482.78  4981.2  482.78
  4981.4  483.28  4982.8  483.28  4989.5  485.77  4999.5  487.47  5029.5  490.31
  5093.8  492.45  5133.6  493.32  5169.5  494.09  5179.5  494.87  5199.5  493.50
  5209.5  494.27  5219.5  493.98  5249.5  495.05  5269.5  492.82  5282.8  492.56
#Mann=7,-1,0
  4732.8    0.05       0  4883.6    0.12       0  4905.2     0.1       0
  4977.4    0.07       0  4981.4     0.1       0  5093.8    0.12       0
  5133.6    0.05       0
Bank Sta=4977.4,4981.4
Exp/Cntr=0.3,0.1

Type RM Length L Ch R = 1,1314,487,487,487
BEGIN DESCRIPTION:
Mapping XS 1fd51d16
END DESCRIPTION:
XS GIS Cut Line= 3
      2757842.48      6909673.15      2757543.88      6909148.86
      2757030.51      6909114.17
#Sta/Elev= 30
  4392.2  502.39  4472.7  499.99  4549.9  499.07  4664.1  495.50  4736.4  493.13
  4822.9  491.39  4935.3  487.34  4956.9  487.26  4978.5  485.44  4984.3  480.87
  4989.4  480.47  4989.7  479.97  4993.2  479.97  4993.4  480.47  4995.6  480.47
  5003.5  483.34  5023.5  484.37  5033.2  485.90  5038.2  485.53  5063.6  487.72
  5103.7  489.35  5163.8  491.13  5304.1  492.70  5314.2  493.91  5324.2  492.54
  5331.9  493.23  5345.5  493.31  5364.3  494.32  5486.3  496.55  5510.1  497.77
#Mann=6,-1,0
  4392.2    0.05       0  4549.9    0.12       0  4664.1     0.1       0
  4989.4    0.07       0  4993.4     0.1       0  5345.5    0.05       0
Bank Sta=4989.4,4993.4
Exp/Cntr=0.3,0.1

Type RM Length L Ch R = 1,827,482,482,482
BEGIN DESCRIPTION:
Rats T2 2.0
END DESCRIPTION:
XS GIS Cut Line= 3
      2757875.65      6909214.99      2757825.65      6908815.01
      2757225.61      6908665.00
#Sta/Elev= 30
  4593.6  491.09  4637.9  489.46  4670.4  489.23  4707.6  487.76  4718.6  488.65
  4748.2  487.22  4849.6  484.17  4868.8  484.42  4873.9  483.64  4889.9  483.35
  4900.0  482.04  4920.1  482.23  4949.4  481.44  4960.4  480.10  4970.5  479.69
  4999.1  480.40  5004.6  477.70  5004.9  477.20  5008.4  477.20  5008.6  477.70
  5033.1  481.18  5038.3  480.63  5047.9  481.84  5068.5  481.64  5089.1  482.71
  5143.8  483.77  5285.7  488.79  5511.7  491.92  5522.0  492.91  5615.2  494.33
#Mann=6,-1,0
  4593.6     0.1       0  4670.4    0.12       0  4748.2     0.1       0
  5004.6    0.07       0  5008.6     0.1       0  5143.8    0.05       0
Bank Sta=5004.6,5008.6
Exp/Cntr=0.3,0.1

Type RM Length L Ch R = 1,345,214,214,214
BEGIN DESCRIPTION:
Mapping XS 8e1baa2c
END DESCRIPTION:
XS GIS Cut Line= 4
      2758163.80      6909142.37      2758200.31      6908547.91
      2758128.05      6908505.02      2757634.41      6908534.10
#Sta/Elev= 30
  4318.2  487.20  4429.8  483.99  4489.9  481.36  4601.9  477.68  4630.2  478.05
  4690.3  476.22  4730.3  474.35  4850.6  474.29  4868.6  472.84  4868.9  472.34
  4872.4  472.34  4872.6  472.84  4880.6  473.79  4893.2  473.54  4915.9  473.11
  4979.5  473.72  4988.6  474.36  5009.7  473.78  5130.1  474.92  5184.9  475.97
  5240.3  477.79  5280.3  480.15  5290.4  480.27  5320.4  483.42  5330.4  483.56
  5350.0  482.51  5355.1  483.69  5400.6  484.41  5450.6  486.56  5492.3  487.32
#Mann=5,-1,0
  4318.2    0.05       0  4868.6    0.05       0  4872.6    0.05       0
  4893.2     0.1       0  4915.9    0.05       0
Bank Sta=4868.6,4872.6
Exp/Cntr=0.3,0.1

Type RM Length L Ch R = 1,131,0,0,0
BEGIN DESCRIPTION:
Rats T2 1.0
END DESCRIPTION:
XS GIS Cut Line= 3
      2758292.67      6908967.93      2758265.44      6908371.05
      2757734.38      6908410.22
#Sta/Elev= 30
  4402.5  479.55  4436.8  478.34  4629.7  474.40  4656.6  474.52  4712.6  473.55
  4789.8  472.91  4799.8  472.27  4809.9  473.05  4859.9  472.12  4899.5  472.26
  4995.5  470.83  4995.8  470.33  4999.3  470.33  4999.5  470.83  5024.5  470.99
  5079.7  471.14  5099.7  471.88  5129.8  471.86  5149.8  472.69  5179.9  472.32
  5199.1  473.42  5204.1  472.63  5220.0  472.38  5320.3  473.71  5380.5  475.66
  5410.6  477.37  5440.6  477.76  5475.4  479.29  5480.7  479.99  5532.5  481.77
#Mann=6,-1,0
  4402.5    0.05       0  4712.6     0.1       0  4899.5    0.05       0
  4995.5    0.07       0  4999.5    0.05       0  5024.5    0.05       0
Bank Sta=4995.5,4999.5
Exp/Cntr=0.3,0.1

Chan Stop Cuts=-1