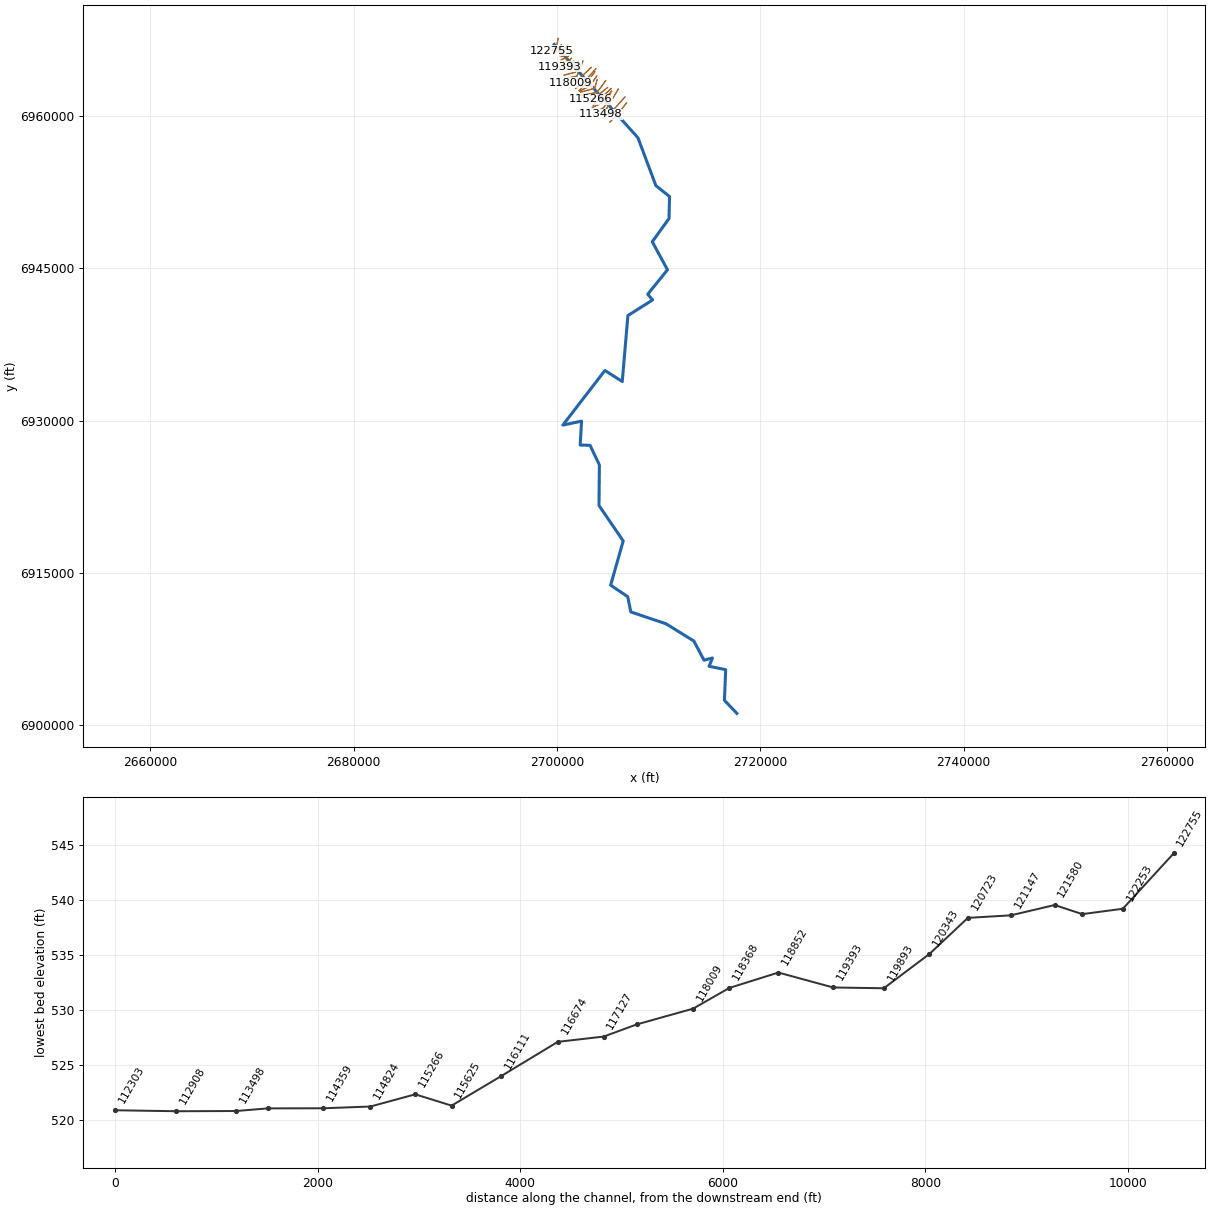
--- Rocky Cedar Creek.prj (project) ---

Proj Title=Rocky Cedar Creek Base Level Engineering
Current Plan=p01
Default Exp/Contr=0.3,0.1
English Units
Geom File=g01
Flow File=f01
Plan File=p01
Y Axis Title=Elevation
X Axis Title(PF)=Main Channel Distance
X Axis Title(XS)=Station
BEGIN DESCRIPTION:
Rocky Cedar Creek
END DESCRIPTION:
DSS File=dss
DSS Export Rating Curves= 0
DSS Export Rating Curve Sorted= 0
DSS Export Volume Flow Curves= 0
DXF OffsetX= 0
DXF OffsetY= 0
DXF ScaleX= 1
DXF ScaleY= 10

--- Rocky Cedar Creek.p01 (plan) ---

Plan Title=Multiple Run
Program Version=4.10
Short Identifier=Multiple Run
Geom File=g01
Flow File=f01
Subcritical Flow
K Sum by GR= 0
Std Step Tol= 0.01
Critical Tol= 0.01
Num of Std Step Trials= 20
Max Error Tol= 0.3
Flow Tol Ratio= 0.001
Split Flow NTrial= 30
Split Flow Tol= 0.02
Split Flow Ratio= 0.02
Log Output Level= 0
Friction Slope Method= 1
Unsteady Friction Slope Method= 2
Unsteady Bridges Friction Slope Method= 1
Parabolic Critical Depth
Global Vel Dist= 1 , 1 , 1
Global Log Level= 0
CheckData=True
Encroach Param=-1 ,0,0, 0
BEGIN DESCRIPTION:
Multiple Run
END DESCRIPTION:
Computation Interval=1HOUR
Output Interval=1HOUR
Run HTab= 0
Run UNet= 0
Run PostProcess= 0
Run WQNet= 0
UNET Theta= 1
UNET Theta Warmup= 1
UNET ZTol= 0.02
UNET ZSATol= 0.05
UNET MxIter= 20
UNET MaxInSteps= 0
UNET DtIC= 0
UNET DtMin= 0
UNET MaxCRTS= 20
UNET WFStab= 2
UNET SFStab= 1
UNET WFX= 1
UNET SFX= 1
UNET DSS MLevel= 4
UNET DZMax Abort= 100
UNET Convert EG Bridges= 0
UNET Use Existing IB Tables=-1
UNET Froude Reduction=False
UNET Froude Limit= 1
UNET Froude Power= 10
UNET Time Slicing=0,0, 5
UNET Junction Losses=0
Instantaneous Interval=1HOUR
DSS File=dss
Write IC File= 0
Write IC File at Sim End=0
Echo Input=False
Echo Parameters=False
Echo Output=False
Write Detailed= 0
WQ AD Non Conservative
WQ ULTIMATE=-1
WQ Max Comp Step=1HOUR
WQ Output Interval=15MIN
WQ Output Selected Increments= 0
WQ Output face flow=0
WQ Output face velocity=0
WQ Output face area=0
WQ Output face dispersion=0
WQ Output cell volume=0
WQ Output cell surface area=0
WQ Output cell continuity=0
WQ Output cumulative cell continuity=0
WQ Output face conc=0
WQ Output face dconc_dx=0
WQ Output face courant=0
WQ Output face peclet=0
WQ Output face adv mass=0
WQ Output face disp mass=0
WQ Output cell mass=0
WQ Output cell source sink temp=0
WQ Output cell source sink nsm=0
WQ Output MaxMinRange=-1
WQ Daily Max Min Mean=-1
WQ Daily Range=0
WQ Daily Time=0
WQ Create Restart=0
WQ Fixed Restart=0
WQ System Summary=0
WQ Use Fixed Temperature=0
Sorting and Armoring Iterations= 10
XS Update Threshold= 0.02
Hydraulics Update Threshold= 0.02
Energy Slope Method= 1
Volume Change Method= 0
XS Weighting Method= 0
Number of US Weighted Cross Sections= 1
Number of DS Weighted Cross Sections= 1
Upstream XS Weight=0.25
Main XS Weight=0.5
Downstream XS Weight=0.25
Number of DS XS's Weighted with US Boundary= 1
Upstream Boundary Weight= 1
Weight of XSs Associated with US Boundary= 0
Number of US XS's Weighted with DS Boundary= 1
Downstream Boundary Weight= 0.5
Weight of XSs Associated with DS Boundary= 0.5
Sediment Output Level= 4
Mass or Volume Output= 0
Output Increment Type= 1
Profile and TS Output Increment= 10
XS Output Flag= 0
XS Output Increment= 10
Disregard all LS=0
Disregard all Conn=0
Disregard all Breaches=0
Disregard all Pumps=0

--- Rocky Cedar Creek.f01 (steady flow) ---

Flow Title=Multiple
Program Version=4.10
Number of Profiles= 7
Profile Names=10-year,25-year,50-year,1pct_min,100-year,1pct_plu,500-year
River Rch & RM=Rocky Cedar Cree,Reach-1         ,122755
     588     783     939     559    1116    2227    1574
River Rch & RM=Rocky Cedar Cree,Reach-1         ,121852
     829    1125    1367     823    1643    3278    2370
River Rch & RM=Rocky Cedar Cree,Reach-1         ,118852
    1040    1426    1745    1057    2110    4210    3083
River Rch & RM=Rocky Cedar Cree,Reach-1         ,117451
    1265    1750    2154    1311    2616    5219    3859
River Rch & RM=Rocky Cedar Cree,Reach-1         ,114359
    1448    2014    2487    1518    3029    6043    4494
River Rch & RM=Rocky Cedar Cree,Reach-1         ,112908
    1609    2244    2775    1696    3383    6751    5031
River Rch & RM=Rocky Cedar Cree,Reach-1         ,111195
    1878    2638    3280    2014    4018    8017    6034
River Rch & RM=Rocky Cedar Cree,Reach-1         ,106407
    2014    2828    3515    2156    4302    8584    6449
River Rch & RM=Rocky Cedar Cree,Reach-1         ,99604
    2650    3759    4703    2902    5790   11552    8781
River Rch & RM=Rocky Cedar Cree,Reach-1         ,91029
    2676    3786    4728    2911    5809   11590    8772
River Rch & RM=Rocky Cedar Cree,Reach-1         ,81832
    2956    4206    5272    3259    6502   12973    9893
River Rch & RM=Rocky Cedar Cree,Reach-1         ,79002
    4096    5883    7422    4612    9202   18361   14152
River Rch & RM=Rocky Cedar Cree,Reach-1         ,68044
    4075    5847    7371    4577    9133   18222   14024
River Rch & RM=Rocky Cedar Cree,Reach-1         ,65202
    4558    6539    8244    5116   10209   20369   15659
River Rch & RM=Rocky Cedar Cree,Reach-1         ,52693
    4644    6661    8394    5208   10391   20732   15925
River Rch & RM=Rocky Cedar Cree,Reach-1         ,46949
    4616    6613    8328    5162   10300   20552   15761
River Rch & RM=Rocky Cedar Cree,Reach-1         ,45768
    4771    6839    8615    5342   10659   21267   16319
River Rch & RM=Rocky Cedar Cree,Reach-1         ,38593
    9160   13267   16839   10504   20959   41819   32450
River Rch & RM=Rocky Cedar Cree,Reach-1         ,37022
    9138   13216   16757   10442   20835   41572   32188
River Rch & RM=Rocky Cedar Cree,Reach-1         ,28087
    9492   13733   17418   10857   21662   43222   33481
River Rch & RM=Rocky Cedar Cree,Reach-1         ,12215
   12820   18647   23744   14853   29635   59129   46108
River Rch & RM=Rocky Cedar Cree,Reach-1         ,6118
   15500   22300   28300   21800   34900   48000   53000
Boundary for River Rch & Prof#=Rocky Cedar Cree,Reach-1         , 1
Up Type= 0
Dn Type= 1
Dn Known WS=390.43
Boundary for River Rch & Prof#=Rocky Cedar Cree,Reach-1         , 2
Up Type= 0
Dn Type= 1
Dn Known WS=391.04
Boundary for River Rch & Prof#=Rocky Cedar Cree,Reach-1         , 3
Up Type= 0
Dn Type= 1
Dn Known WS=391.47
Boundary for River Rch & Prof#=Rocky Cedar Cree,Reach-1         , 4
Up Type= 0
Dn Type= 1
Dn Known WS=391.01
Boundary for River Rch & Prof#=Rocky Cedar Cree,Reach-1         , 5
Up Type= 0
Dn Type= 1
Dn Known WS=391.9
Boundary for River Rch & Prof#=Rocky Cedar Cree,Reach-1         , 6
Up Type= 0
Dn Type= 1
Dn Known WS=392.71
Boundary for River Rch & Prof#=Rocky Cedar Cree,Reach-1         , 7
Up Type= 0
Dn Type= 1
Dn Known WS=393
DSS Import GetInterval= 0
DSS Import GetPeak= 0
DSS Import FillOption= 0

--- Rocky Cedar Creek.g01 (geometry) ---

Geom Title=Existing Conditions
Program Version=4.10

River Reach=Rocky Cedar Cree,Reach-1
Reach XY= 30
        2699726.        6967061.      2707965.67      6957871.17
      2709731.45      6953158.53      2711076.74      6952080.87
      2711022.45      6949912.47      2709375.65      6947631.15
      2710874.24      6944867.13      2708929.45      6942459.52
      2709412.89      6941897.79      2706979.52      6940359.54
      2706422.57      6933862.22      2704719.78      6934953.26
      2700577.37      6929572.52      2702420.54      6929963.47
      2702283.59      6927607.65      2703256.41      6927581.58
       2704174.8      6925650.49       2704133.6      6921657.68
      2706518.27      6918164.65      2705281.83       6913808.7
      2706965.82      6912670.71      2707266.32      6911171.76
      2710728.71      6910005.72      2713470.76      6908305.56
      2714466.15      6906421.47      2715299.52      6906638.31
       2714966.3      6905821.75      2716599.83      6905487.88
      2716478.24      6902466.93      2717701.85      6901183.69

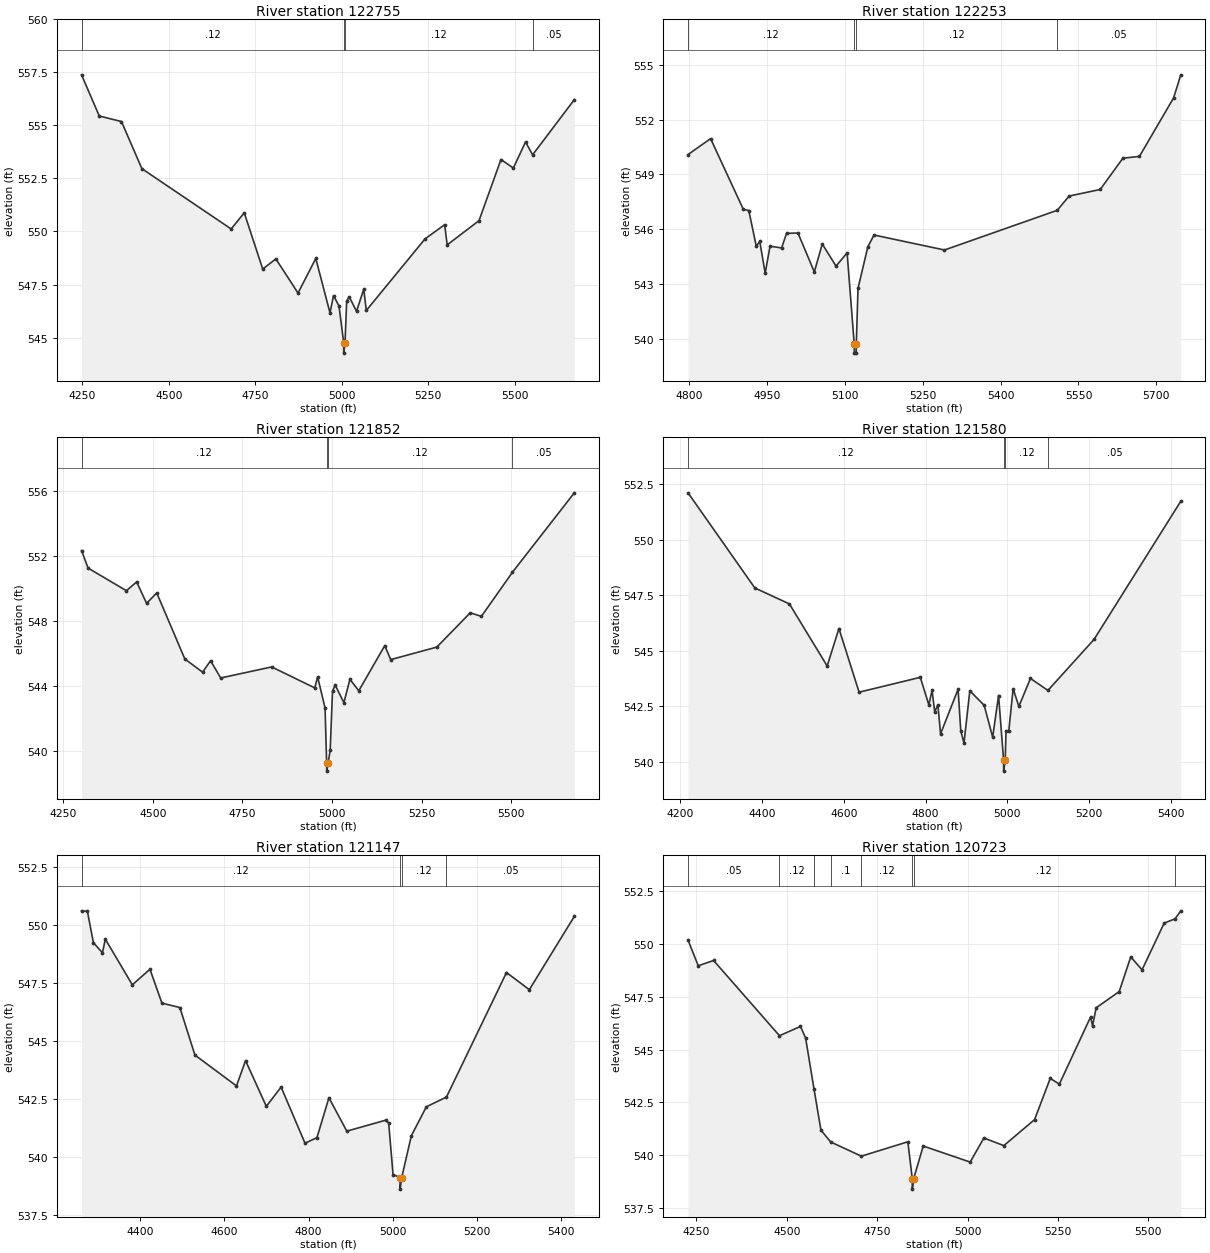
Type RM Length L Ch R = 1 ,122755  ,502,502,502
BEGIN DESCRIPTION:
Rocky Cedar Creek 135.0
END DESCRIPTION:
XS GIS Cut Line= 3
      2700125.99      6967660.96      2699959.29      6966927.57
      2699505.83      6966432.03
#Sta/Elev= 30
  4247.9  557.38  4299.1  555.44  4363.2  555.18  4422.2  552.96  4680.1  550.12
    4718  550.88  4771.4  548.23  4809.3  548.71  4873.4   547.1  4924.7  548.73
  4965.7  546.17    4976  546.98  4991.8  546.49  5005.2  544.77  5005.5  544.27
  5009.2  544.77    5014  546.74  5021.4  546.92  5042.4  546.24  5063.3  547.28
  5070.7  546.28  5240.3  549.65    5297  550.32  5304.4  549.37  5396.3  550.51
  5459.8  553.39  5495.6  552.99  5530.8  554.22  5551.1  553.61  5671.7  556.21
#Mann= 4 ,-1 , 0
  4247.9     .12       0  5005.2     .07       0  5009.2     .12       0
  5551.1     .05       0
Bank Sta=5005.2,5009.2
XS Rating Curve= 0 ,0
Exp/Cntr=0.3,0.1

Type RM Length L Ch R = 1 ,122253  ,401,401,401
BEGIN DESCRIPTION:
Rocky Cedar Creek 134.0
END DESCRIPTION:
XS GIS Cut Line= 3
      2700421.65      6967022.34      2700317.48      6966705.49
      2699776.01      6966411.01
#Sta/Elev= 30
  4797.3  550.09  4840.8  550.96    4904  547.09  4914.5  547.03  4928.9  545.07
  4935.6  545.34  4946.1   543.6  4955.4  545.08  4977.7  544.98  4987.2  545.78
  5009.2   545.8  5040.8  543.67  5056.1   545.2  5082.6  543.99    5104  544.71
  5117.7  539.73  5117.9  539.23  5121.4  539.23  5121.7  539.73    5125  542.77
  5143.9  545.04  5155.8  545.69  5291.7  544.87    5509  547.04    5532  547.82
  5591.9  548.18  5635.6  549.89  5667.5  549.99  5733.4  553.19  5747.2  554.45
#Mann= 4 ,-1 , 0
  4797.3     .12       0  5117.7     .07       0  5121.7     .12       0
    5509     .05       0
Bank Sta=5117.7,5121.7
XS Rating Curve= 0 ,0
Exp/Cntr=0.3,0.1

Type RM Length L Ch R = 1 ,121852  ,272,272,272
BEGIN DESCRIPTION:
Rocky Cedar Creek 133.0
END DESCRIPTION:
XS GIS Cut Line= 3
      2701016.39      6966936.42      2700466.37       6966486.4
      2699826.02      6966311.01
#Sta/Elev= 30
  4301.3  552.31  4319.5  551.23  4426.4  549.84  4455.1  550.38  4482.7  549.06
  4511.1   549.7  4589.4  545.64  4638.9  544.83  4661.2  545.53  4689.4  544.47
  4831.6  545.15  4951.9  543.86  4959.8  544.54  4980.6  542.63    4985  539.24
  4985.3  538.74    4989  539.24  4994.9  540.02  5001.4  543.67    5009  544.03
  5033.1  542.95    5050  544.39  5074.6  543.68  5147.1  546.46  5163.8   545.6
  5292.3  546.37  5385.6  548.48  5416.7  548.26  5503.2  550.97  5675.9  555.86
#Mann= 4 ,-1 , 0
  4301.3     .12       0    4985     .07       0    4989     .12       0
  5503.2     .05       0
Bank Sta=4985,4989
XS Rating Curve= 0 ,0
Exp/Cntr=0.3,0.1

Type RM Length L Ch R = 1 ,121580  ,433,433,433
BEGIN DESCRIPTION:
Rocky Cedar Creek 132.0
END DESCRIPTION:
XS GIS Cut Line= 3
      2701076.01      6966861.01        2700576.        6966261.
        2700276.        6965961.
#Sta/Elev= 30
  4218.7  552.12  4382.1  547.83  4466.7  547.11  4559.1  544.31  4587.8     546
  4637.2  543.13  4786.9   543.8  4807.7  542.56  4815.6  543.21  4822.1  542.25
  4829.9  542.56  4836.4  541.25  4879.3  543.26  4885.8   541.4  4893.7  540.83
    4908  543.19  4943.1  542.54  4963.9   541.1  4978.3  542.98  4990.6  540.07
  4990.8  539.57  4994.6  540.07  4996.5  541.38  5003.3  541.38  5013.9  543.28
    5028  542.49  5056.3  543.75    5099  543.21  5211.9  545.51    5424  551.74
#Mann= 4 ,-1 , 0
  4218.7     .12       0  4990.6     .07       0  4994.6     .12       0
    5099     .05       0
Bank Sta=4990.6,4994.6
XS Rating Curve= 0 ,0
Exp/Cntr=0.3,0.1

Type RM Length L Ch R = 1 ,121147  ,424,424,424
BEGIN DESCRIPTION:
Rocky Cedar Creek 131.0
END DESCRIPTION:
XS GIS Cut Line= 3
      2701326.01      6966561.02        2700826.        6966011.
      2700426.02      6965861.01
#Sta/Elev= 30
  4260.7  550.63  4274.6  550.61  4288.8  549.26  4310.4  548.82  4317.1  549.41
  4381.3  547.44  4423.2  548.11  4451.6  546.65  4494.2  546.46    4530  544.41
  4628.7  543.08  4650.3  544.17  4699.6   542.2  4734.7  543.03  4791.5  540.61
  4819.9  540.85  4848.3  542.57  4890.8  541.13  4982.7   541.6  4990.2  541.49
  5000.6  539.26  5017.2  539.13  5017.4  538.63  5021.2  539.13  5044.1  540.93
  5079.7  542.18  5127.5   542.6  5270.1  547.97  5324.4  547.23  5431.2  550.39
#Mann= 4 ,-1 , 0
  4260.7     .12       0  5017.2     .07       0  5021.2     .12       0
  5127.5     .05       0
Bank Sta=5017.2,5021.2
XS Rating Curve= 0 ,0
Exp/Cntr=0.3,0.1

Type RM Length L Ch R = 1 ,120723  ,380,380,380
BEGIN DESCRIPTION:
Rocky Cedar Creek 130.0
END DESCRIPTION:
XS GIS Cut Line= 3
      2701526.01      6966311.01        2700976.        6965761.
      2700425.97      6965560.99
#Sta/Elev= 30
  4226.7  550.19    4255  548.97  4297.4  549.22  4479.7  545.66  4537.8   546.1
    4552  545.55  4575.2  543.14  4594.4  541.19  4621.5  540.63  4706.2  539.96
  4834.8  540.64    4847   538.9  4847.2   538.4    4851   538.9  4877.3  540.44
  5007.2  539.68  5045.1  540.82  5100.3  540.46  5185.4  541.69  5228.7  543.64
  5253.9  543.37  5340.4  546.55  5345.7  546.12  5355.7  546.98  5419.5  547.75
  5451.4  549.39  5482.7  548.78  5543.9  550.99  5573.8  551.19  5589.8  551.57
#Mann= 8 ,-1 , 0
  4226.7     .05       0  4479.7     .12       0  4575.2     .05       0
  4621.5      .1       0  4706.2     .12       0    4847     .07       0
    4851     .12       0  5573.8     .05       0
Bank Sta=4847,4851
XS Rating Curve= 0 ,0
Exp/Cntr=0.3,0.1

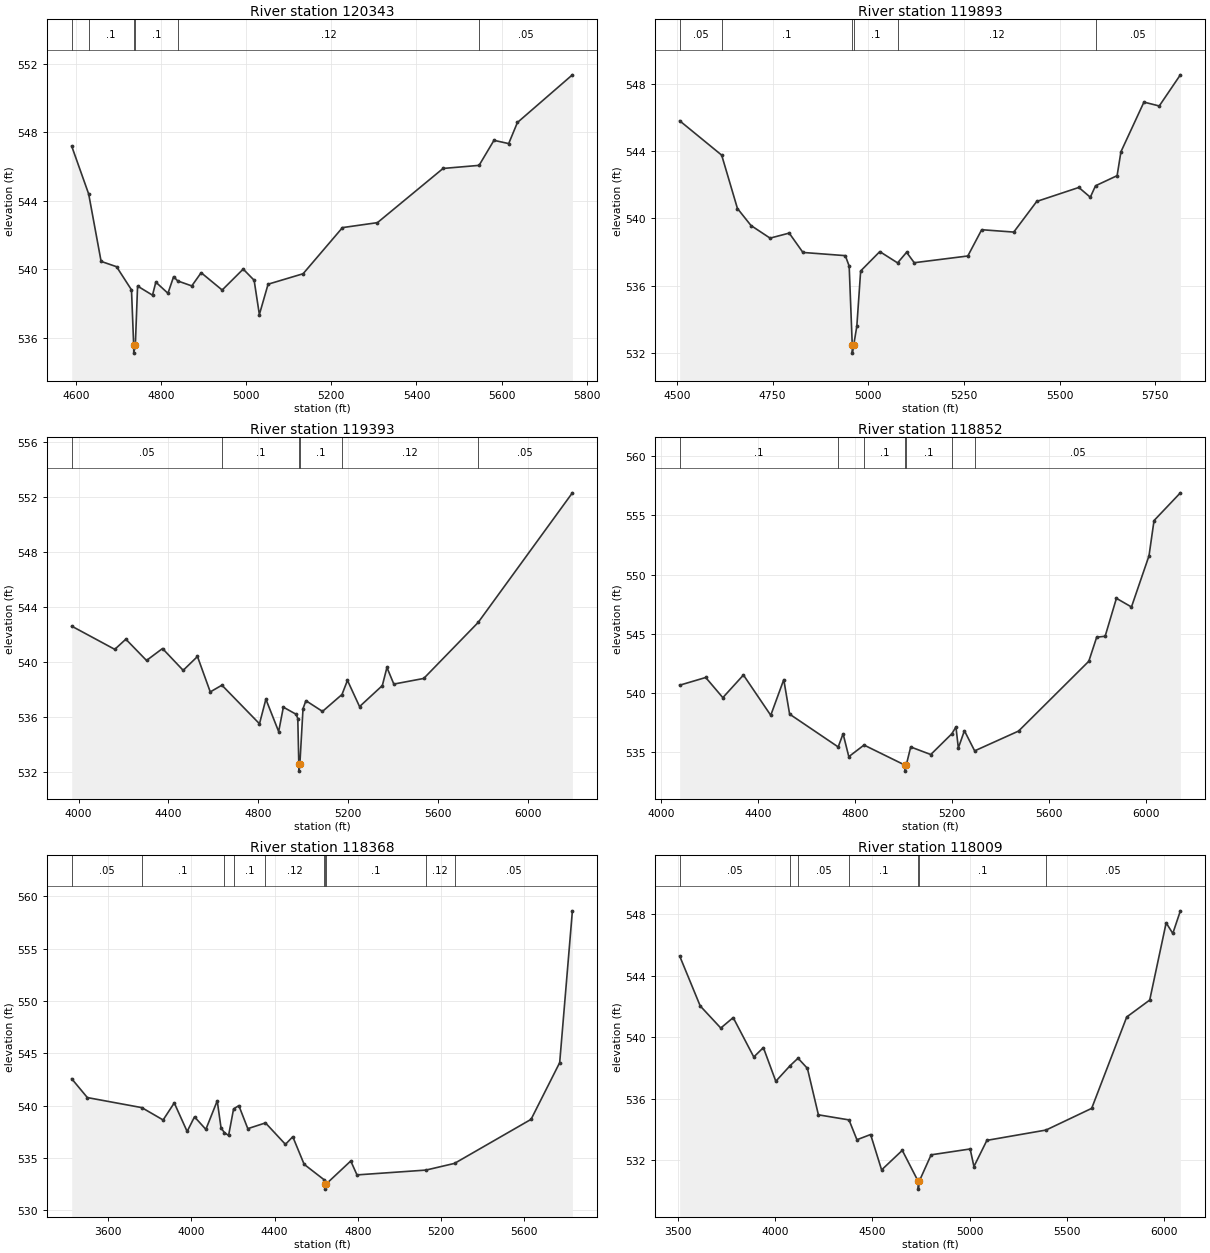
Type RM Length L Ch R = 1 ,120343  ,450,450,450
BEGIN DESCRIPTION:
Rocky Cedar Creek 129.0
END DESCRIPTION:
XS GIS Cut Line= 3
      2701418.46       6965696.7      2701105.96      6965430.98
      2700360.35      6965253.67
#Sta/Elev= 30
  4589.8  547.18  4629.7  544.39  4658.9  540.46  4695.2  540.15  4730.3   538.8
  4735.4  535.61  4735.7  535.11  4739.4  535.61  4744.6  539.02  4779.7  538.49
  4787.5  539.25    4816   538.6  4829.3  539.57  4838.9  539.32    4872  539.03
    4894   539.8  4943.4  538.79  4992.8  540.01  5018.5  539.36  5030.8  537.36
  5051.3  539.13  5133.6  539.74  5226.1  542.43  5308.3  542.72  5462.5  545.88
  5547.1  546.06  5582.1  547.52  5616.7  547.33  5637.2  548.56  5766.4  551.34
#Mann= 6 ,-1 , 0
  4589.8     .05       0  4629.7      .1       0  4735.4     .07       0
  4739.4      .1       0  4838.9     .12       0  5547.1     .05       0
Bank Sta=4735.4,4739.4
XS Rating Curve= 0 ,0
Exp/Cntr=0.3,0.1

Type RM Length L Ch R = 1 ,119893  ,500,500,500
BEGIN DESCRIPTION:
Rocky Cedar Creek 128.0
END DESCRIPTION:
XS GIS Cut Line= 3
      2701651.27      6965417.46      2701394.97      6965079.97
      2700510.77      6965094.52
#Sta/Elev= 30
  4507.5  545.79  4617.2  543.75  4658.4  540.58  4693.8  539.57  4743.7  538.82
  4793.6  539.12  4829.5  537.97  4940.2  537.78  4950.3  537.16  4958.3  532.49
  4958.5  531.99  4962.3  532.49  4970.3  533.59  4980.3  536.87  5030.3  538.02
  5076.8  537.35  5100.3  537.98  5120.3  537.36  5260.3  537.76  5296.5  539.32
  5380.3  539.18  5440.3     541  5550.3  541.83  5580.3  541.25  5593.9  541.93
  5650.3  542.53  5660.3  543.95  5720.4   546.9  5760.4  546.67  5815.6  548.52
#Mann= 6 ,-1 , 0
  4507.5     .05       0  4617.2      .1       0  4958.3     .07       0
  4962.3      .1       0  5076.8     .12       0  5593.9     .05       0
Bank Sta=4958.3,4962.3
XS Rating Curve= 0 ,0
Exp/Cntr=0.3,0.1

Type RM Length L Ch R = 1 ,119393  ,541,541,541
BEGIN DESCRIPTION:
Rocky Cedar Creek 127.0
END DESCRIPTION:
XS GIS Cut Line= 3
      2702101.03      6965386.03       2701419.7      6964612.78
       2700249.9       6964871.2
#Sta/Elev= 30
  3969.4  542.62  4161.1  540.93  4210.4  541.67  4302.4  540.12  4373.6  540.99
  4465.6   539.4  4529.2  540.41  4586.1  537.83    4638  538.32  4805.2  535.51
  4833.7   537.3  4890.6  534.94  4911.5  536.72  4968.4   536.2  4975.7  535.89
  4980.3  532.56  4980.8  532.06  4984.9  532.56    4999  536.61  5011.9  537.19
  5085.7  536.41  5172.4  537.64  5196.8  538.67  5250.7  536.76    5352  538.29
  5372.5  539.61  5403.2   538.4  5536.3  538.81  5778.6  542.89    6198  552.33
#Mann= 6 ,-1 , 0
  3969.4     .05       0    4638      .1       0  4980.3     .07       0
  4984.9      .1       0  5172.4     .12       0  5778.6     .05       0
Bank Sta=4980.3,4984.9
XS Rating Curve= 0 ,0
Exp/Cntr=0.3,0.1

Type RM Length L Ch R = 1 ,118852  ,484,484,484
BEGIN DESCRIPTION:
Rocky Cedar Creek 126.0
END DESCRIPTION:
XS GIS Cut Line= 3
      2702151.01      6965186.03      2701805.62      6964330.84
      2700700.99        6964036.
#Sta/Elev= 30
  4077.7  540.67  4185.1  541.32  4255.7  539.62  4340.7  541.53  4453.4  538.13
  4507.1  541.14  4531.2  538.23  4731.6  535.46  4751.8  536.57  4775.4  534.64
  4838.2  535.62  5007.6  533.92  5008.1  533.42  5012.3  533.92  5030.7  535.46
  5113.5  534.82  5200.8  536.58  5217.4  537.15  5227.3  535.37  5252.3  536.83
  5294.6  535.13  5475.7   536.8  5765.5  542.69    5798  544.72  5832.9   544.8
  5879.4     548  5941.5  547.27  6013.9  551.59  6034.6  554.56  6143.3   556.9
#Mann= 7 ,-1 , 0
  4077.7      .1       0  4731.6     .12       0  4838.2      .1       0
  5007.6     .07       0  5012.3      .1       0  5200.8     .12       0
  5294.6     .05       0
Bank Sta=5007.6,5012.3
XS Rating Curve= 0 ,0
Exp/Cntr=0.3,0.1

Type RM Length L Ch R = 1 ,118368  ,359,359,359
BEGIN DESCRIPTION:
Rocky Cedar Creek 125.0
END DESCRIPTION:
XS GIS Cut Line= 3
      2702551.21      6965421.27      2701985.98      6963950.98
      2701175.97      6963760.99
#Sta/Elev= 30
  3424.8  542.57  3500.1  540.77  3761.9  539.81  3864.3  538.63  3917.9  540.26
  3979.8  537.53  4015.2  538.93  4069.8  537.73  4124.5  540.46  4142.9  537.86
  4159.2  537.42  4179.1  537.15  4203.1  539.69  4228.4     540  4271.5   537.8
  4356.5  538.35  4452.4   536.3  4487.7  537.03  4542.4  534.39  4636.7  532.94
    4644  532.52  4644.5  532.02  4648.7  532.52  4766.4  534.71  4796.4  533.38
  5127.8  533.84  5265.3  534.48  5633.3  538.69  5770.9  544.11    5832  558.62
#Mann= 10 ,-1 , 0
  3424.8     .05       0  3761.9      .1       0  4159.2     .12       0
  4203.1      .1       0  4356.5     .12       0  4636.7      .1       0
    4644     .07       0  4648.7      .1       0  5127.8     .12       0
  5265.3     .05       0
Bank Sta=4644,4648.7
XS Rating Curve= 0 ,0
Exp/Cntr=0.3,0.1

Type RM Length L Ch R = 1 ,118009  ,558,558,558
BEGIN DESCRIPTION:
Rocky Cedar Creek 124.0
END DESCRIPTION:
XS GIS Cut Line= 3
      2703356.77      6964789.32        2702276.        6963761.
      2701300.97      6963285.98
#Sta/Elev= 30
  3508.4  545.28  3613.9  542.04  3719.9   540.6  3783.7  541.28  3889.7  538.72
  3939.1  539.33    4003  537.14  4076.9  538.16  4117.4  538.64  4165.6  537.98
  4222.2  534.96  4379.6  534.63  4420.4  533.34  4490.8  533.68  4547.4  531.38
  4653.8  532.65  4735.9  530.63  4736.5  530.13  4740.7  530.63  4802.2  532.36
    5003  532.74  5022.5   531.6  5089.2   533.3  5393.4  533.97  5628.4  535.38
  5808.7  541.32    5927  542.42  6011.6  547.44  6045.8  546.75  6084.8  548.22
#Mann= 7 ,-1 , 0
  3508.4     .05       0  4076.9     .12       0  4117.4     .05       0
  4379.6      .1       0  4735.9     .07       0  4740.7      .1       0
  5393.4     .05       0
Bank Sta=4735.9,4740.7
XS Rating Curve= 0 ,0
Exp/Cntr=0.3,0.1

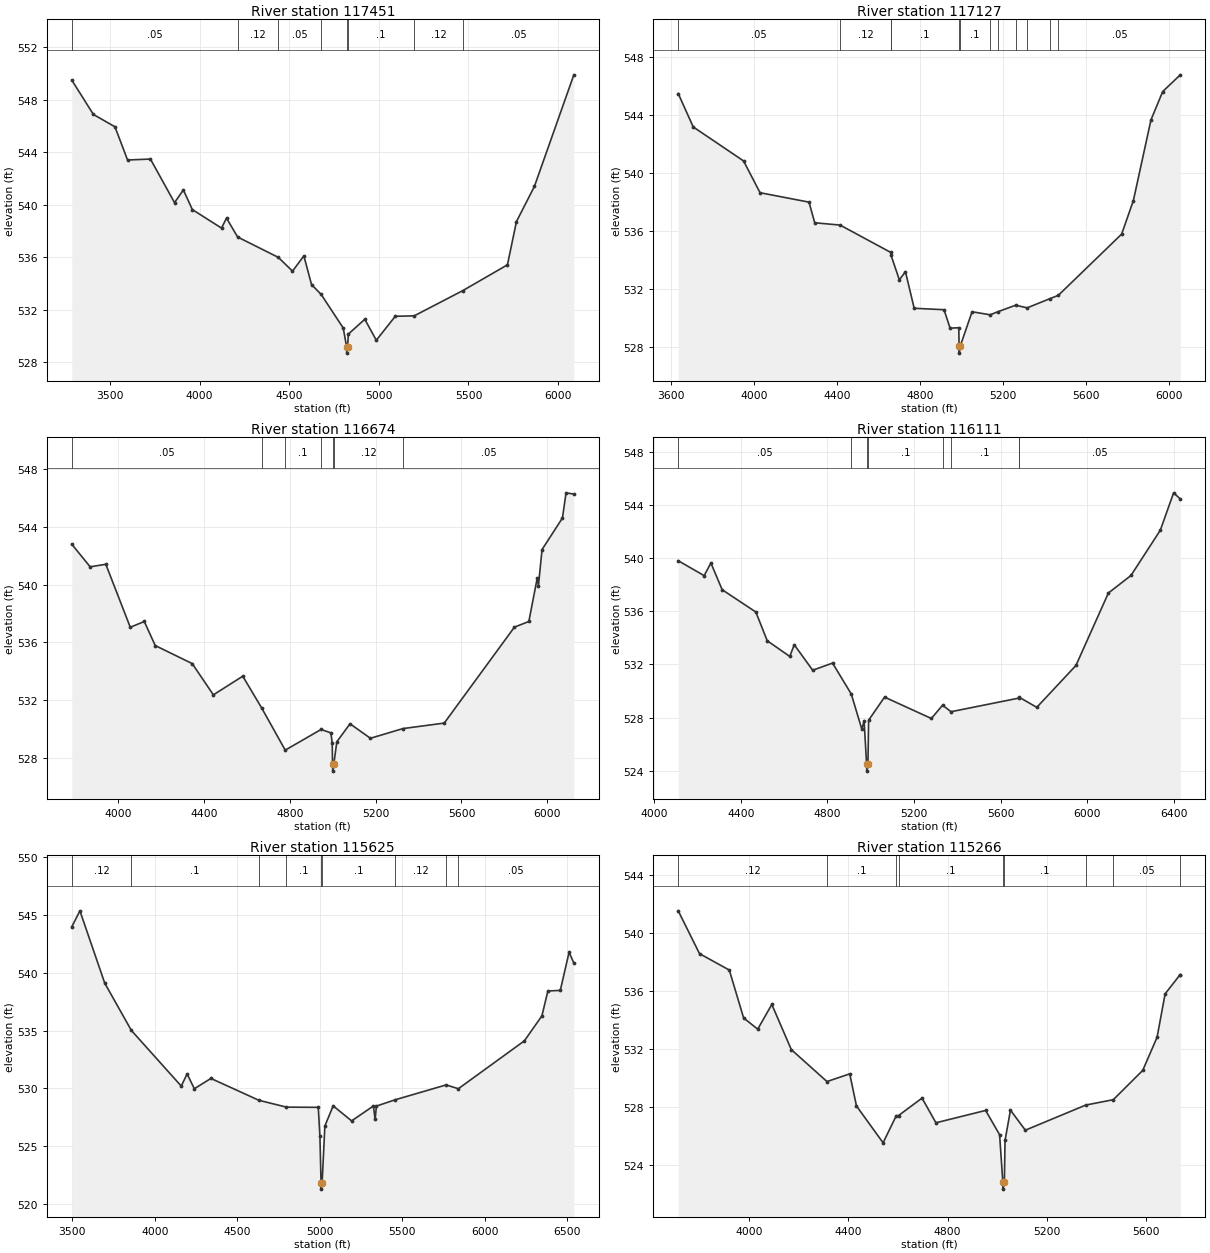
Type RM Length L Ch R = 1 ,117451  ,324,324,324
BEGIN DESCRIPTION:
Rocky Cedar Creek 123.0
END DESCRIPTION:
XS GIS Cut Line= 3
      2703826.03      6964661.03      2702675.58      6963390.76
      2701825.96      6962710.97
#Sta/Elev= 30
  3286.2   549.5  3406.9  546.88  3527.2  545.94  3597.5  543.41  3725.2  543.48
  3859.7  540.16    3909  541.13  3959.1  539.63  4121.9  538.22  4149.7  538.98
  4211.8  537.54  4438.6  535.99    4518  534.94  4581.5   536.1  4624.1  533.92
  4678.1  533.16  4801.2   530.6  4819.8  529.19  4820.8  528.69  4825.8  529.19
  4829.5  530.14  4921.5  531.27  4985.7  529.67  5091.6   531.5  5197.1  531.53
  5469.1  533.46  5717.5  535.42  5767.9  538.72  5867.9  541.39  6088.1   549.9
#Mann= 8 ,-1 , 0
  3286.2     .05       0  4211.8     .12       0  4438.6     .05       0
  4678.1      .1       0  4819.8     .07       0  4825.8      .1       0
  5197.1     .12       0  5469.1     .05       0
Bank Sta=4819.8,4825.8
XS Rating Curve= 0 ,0
Exp/Cntr=0.3,0.1

Type RM Length L Ch R = 1 ,117127  ,453,453,453
BEGIN DESCRIPTION:
Rocky Cedar Creek 122.0
END DESCRIPTION:
XS GIS Cut Line= 3
      2703726.01      6964361.01        2702926.        6963261.
      2702176.01      6962511.01
#Sta/Elev= 30
  3634.6  545.47  3706.9  543.17  3949.5  540.83  4029.1  538.64  4265.2  537.99
  4292.7  536.57  4415.2  536.41    4659  534.53  4660.4  534.34  4700.7  532.64
  4730.1   533.2  4772.2  530.68  4916.3  530.58  4945.3  529.31  4987.4  529.34
  4988.7  528.09  4989.7  527.59  4994.7  528.09  5051.3  530.44  5138.5  530.23
  5175.7  530.44  5261.3  530.89  5317.4  530.71    5428  531.35  5467.2  531.57
  5772.6  535.79  5829.1   538.1    5914  543.66  5970.6  545.61  6055.4  546.76
#Mann= 12 ,-1 , 0
  3634.6     .05       0  4415.2     .12       0    4659     .05       0
  4660.4      .1       0  4988.7     .07       0  4994.7      .1       0
  5138.5     .12       0  5175.7     .05       0  5261.3     .12       0
  5317.4     .05       0    5428     .12       0  5467.2     .05       0
Bank Sta=4988.7,4994.7
XS Rating Curve= 0 ,0
Exp/Cntr=0.3,0.1

Type RM Length L Ch R = 1 ,116674  ,563,563,563
BEGIN DESCRIPTION:
Rocky Cedar Creek 121.0
END DESCRIPTION:
XS GIS Cut Line= 3
      2703926.01      6963961.02        2703226.        6962961.
      2702226.01        6962461.
#Sta/Elev= 30
  3784.9  542.79  3870.4  541.23  3943.6   541.4  4057.4  537.05  4122.8  537.45
  4173.4  535.79    4346  534.54  4444.5  532.38  4581.4  533.67  4670.4  531.45
  4779.2  528.56  4946.4  529.99  4992.1  529.75  4998.2  529.02  4999.5  527.61
  5000.5  527.11  5005.6  527.61  5019.6  529.14    5081  530.38  5176.1  529.38
  5327.5  530.05  5519.9  530.43  5846.9  537.06    5914  537.45  5953.1  540.45
  5958.7  539.93  5975.5  542.42  6070.5   544.6  6087.3  546.34  6123.6  546.25
#Mann= 7 ,-1 , 0
  3784.9     .05       0  4670.4     .12       0  4779.2      .1       0
  4946.4     .12       0  4999.5     .07       0  5005.6     .12       0
  5327.5     .05       0
Bank Sta=4999.5,5005.6
XS Rating Curve= 0 ,0
Exp/Cntr=0.3,0.1

Type RM Length L Ch R = 1 ,116111  ,486,486,486
BEGIN DESCRIPTION:
Rocky Cedar Creek 120.0
END DESCRIPTION:
XS GIS Cut Line= 3
      2703950.99      6963585.96      2703706.27      6962731.51
      2702326.04      6962361.01
#Sta/Elev= 30
  4111.2   539.8  4230.8  538.68    4262  539.63    4314  537.62  4469.6  535.94
    4522  533.78  4626.1   532.6  4646.9  533.48  4731.9  531.56  4823.7   532.1
  4910.1  529.77  4958.9  527.12  4969.3  527.77  4980.8  524.47  4981.8  523.97
    4987  524.47  4990.1   527.8  5063.7  529.54  5279.8  527.93  5331.5  528.93
  5370.7  528.44  5682.1  529.46  5686.3  529.52  5766.5  528.77  5947.3  531.92
    6097  537.37  6201.3  538.69  6336.9   542.1  6398.1  544.91  6429.1  544.45
#Mann= 8 ,-1 , 0
  4111.2     .05       0  4910.1      .1       0  4980.8     .07       0
    4987      .1       0  5331.5     .12       0  5370.7      .1       0
  5682.1     .12       0  5686.3     .05       0
Bank Sta=4980.8,4987
XS Rating Curve= 0 ,0
Exp/Cntr=0.3,0.1

Type RM Length L Ch R = 1 ,115625  ,359,359,359
BEGIN DESCRIPTION:
Rocky Cedar Creek 119.0
END DESCRIPTION:
XS GIS Cut Line= 4
      2704782.96      6963481.99      2703915.68      6962302.16
       2703806.3      6962305.64      2702361.15      6962041.06
#Sta/Elev= 30
  3496.4  543.98  3545.7  545.36  3696.2  539.11  3857.6  535.02  4159.9  530.21
  4195.4  531.26  4239.3  529.98  4339.6  530.87  4630.7  528.98    4797  528.39
  4990.4  528.37  5000.4  525.85  5007.3   521.8  5008.3   521.3  5013.5   521.8
  5030.4  526.76  5080.6   528.5  5192.4   527.2  5324.6  528.49  5334.8  527.32
  5342.8  528.48  5455.4  529.02  5765.2  530.31  5839.3  529.98  6239.6  534.12
  6345.8  536.28  6381.9  538.43  6457.2  538.48  6510.4  541.78  6539.3  540.85
#Mann= 9 ,-1 , 0
  3496.4     .12       0  3857.6      .1       0  4630.7     .12       0
    4797      .1       0  5007.3     .07       0  5013.5      .1       0
  5455.4     .12       0  5765.2      .1       0  5839.3     .05       0
Bank Sta=5007.3,5013.5
XS Rating Curve= 0 ,0
Exp/Cntr=0.3,0.1

Type RM Length L Ch R = 1 ,115266  ,442,442,442
BEGIN DESCRIPTION:
Rocky Cedar Creek 118.0
END DESCRIPTION:
XS GIS Cut Line= 3
      2704976.03      6962811.02        2703976.        6962011.
      2703322.82      6961659.32
#Sta/Elev= 30
    3715   541.5  3800.7  538.55  3920.7  537.42  3978.4  534.12  4035.2  533.35
    4092  535.05  4170.5  531.94  4314.2  529.74  4405.8  530.27    4433  528.06
  4540.2  525.52    4593  527.38  4602.5   527.4  4697.1   528.6  4753.1   526.9
  4953.2  527.75  5009.5  526.08  5022.5  522.83  5023.5  522.33  5028.8  522.83
  5031.4  525.68  5053.3  527.77  5113.3  526.39  5356.5  528.12  5467.5  528.49
  5586.2  530.51  5643.9  532.79  5676.3  535.78  5735.6  537.08  5737.5  537.08
#Mann= 9 ,-1 , 0
    3715     .12       0  4314.2      .1       0    4593     .12       0
  4602.5      .1       0  5022.5     .07       0  5028.8      .1       0
  5356.5     .12       0  5467.5     .05       0  5735.6     .12       0
Bank Sta=5022.5,5028.8
XS Rating Curve= 0 ,0
Exp/Cntr=0.3,0.1

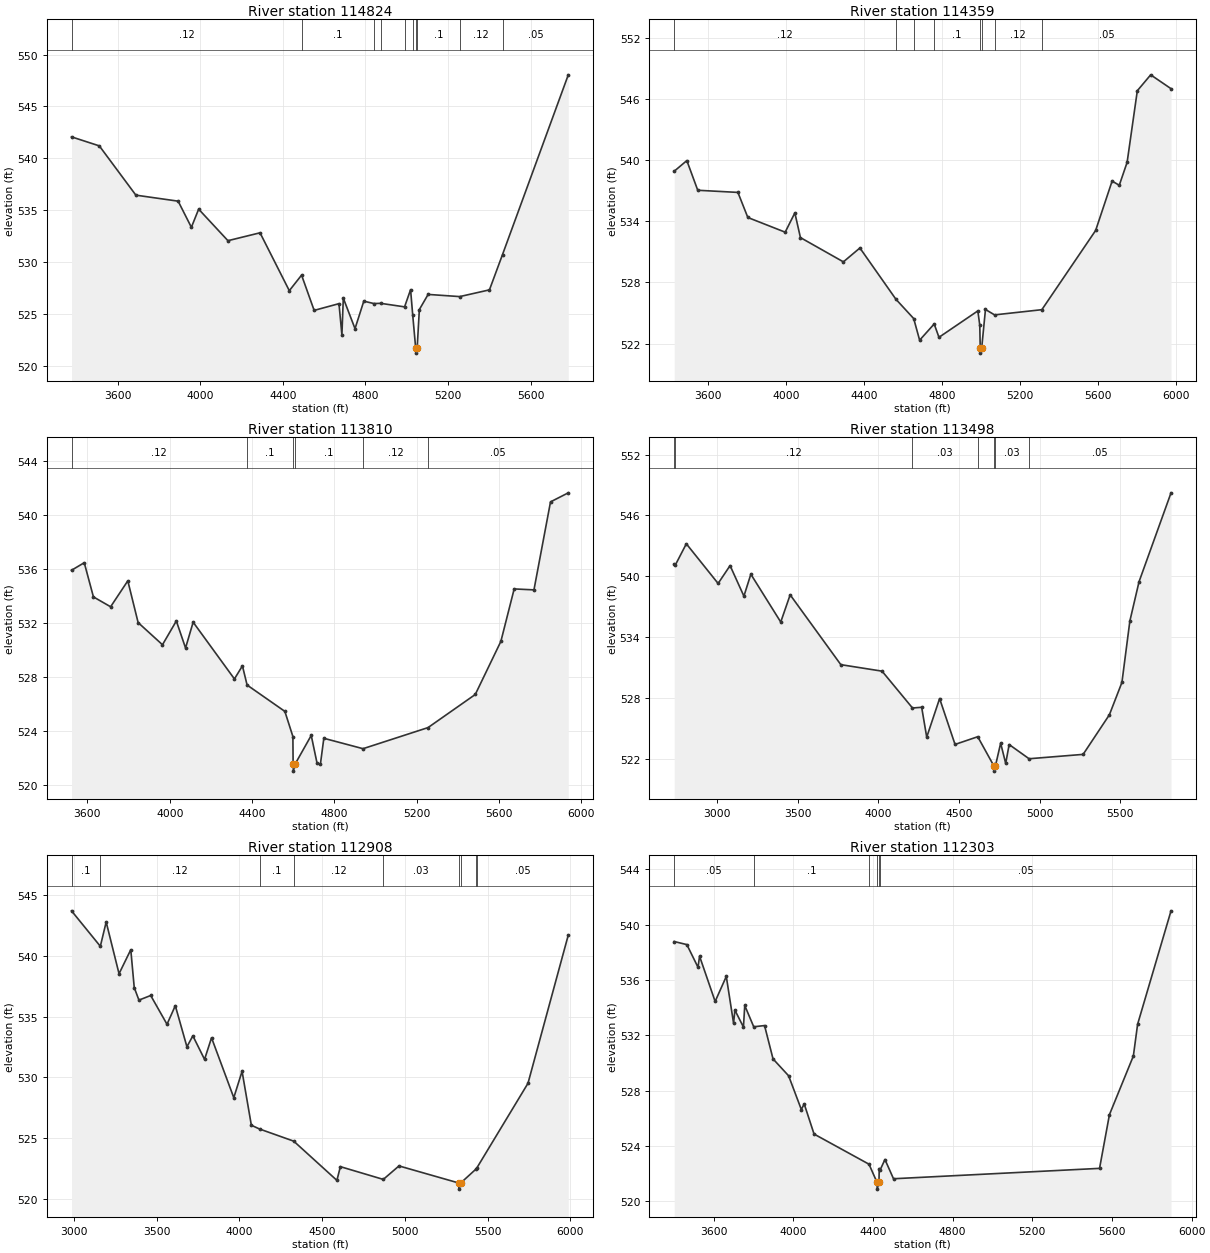
Type RM Length L Ch R = 1 ,114824  ,465,465,465
BEGIN DESCRIPTION:
Rocky Cedar Creek 117.0
END DESCRIPTION:
XS GIS Cut Line= 3
      2705325.99      6962710.99        2704126.        6961611.
      2703575.99      6961060.99
#Sta/Elev= 30
  3376.8  542.07  3511.5   541.2  3688.5  536.45  3893.2  535.87  3957.3  533.35
  3992.5   535.1  4134.3  532.06  4289.7  532.82  4431.5  527.24  4490.9  528.74
  4551.8  525.34    4672  525.99  4686.2  522.97    4693  526.52  4749.7  523.58
  4792.2  526.23    4841     526  4874.1  526.02  4989.7  525.68  5018.8  527.34
  5029.2  524.87  5043.4  521.72  5044.5  521.22  5050.7  521.72  5061.2  525.42
  5103.7  526.88  5256.7  526.67  5400.7  527.32  5463.9  530.72  5782.5  548.05
#Mann= 10 ,-1 , 0
  3376.8     .12       0  4490.9      .1       0    4841     .12       0
  4874.1      .1       0  4989.7     .12       0  5029.2      .1       0
  5043.4     .07       0  5050.7      .1       0  5256.7     .12       0
  5463.9     .05       0
Bank Sta=5043.4,5050.7
XS Rating Curve= 0 ,0
Exp/Cntr=0.3,0.1

Type RM Length L Ch R = 1 ,114359  ,549,549,549
BEGIN DESCRIPTION:
Rocky Cedar Creek 116.0
END DESCRIPTION:
XS GIS Cut Line= 3
      2705376.02      6962461.02        2704376.        6961261.
      2703481.09      6960855.93
#Sta/Elev= 30
  3428.5   538.9    3493  539.94  3548.9  537.03  3754.6  536.82  3805.4  534.36
  3996.7  532.92  4046.2  534.81  4074.8  532.39  4294.8  530.01  4379.4  531.37
    4564  526.34  4654.9  524.45  4685.3  522.33  4759.9  523.92  4784.3  522.61
  4983.4   525.2  4993.3   523.8  4995.7  521.56  4996.8  521.06  5003.1  521.56
  5022.5  525.34  5069.1  524.81  5311.3  525.32  5586.8  533.09  5671.1  537.93
  5707.8  537.52    5748  539.77  5800.2  546.79  5868.7  548.35  5972.9  546.99
#Mann= 8 ,-1 , 0
  3428.5     .12       0    4564      .1       0  4654.9     .12       0
  4759.9      .1       0  4995.7     .07       0  5003.1      .1       0
  5069.1     .12       0  5311.3     .05       0
Bank Sta=4995.7,5003.1
XS Rating Curve= 0 ,0
Exp/Cntr=0.3,0.1

Type RM Length L Ch R = 1 ,113810  ,312,312,312
BEGIN DESCRIPTION:
Rocky Cedar Creek 115.0
END DESCRIPTION:
XS GIS Cut Line= 3
      2705286.96      6962185.22      2704613.36      6960855.38
      2703814.78      6960393.59
#Sta/Elev= 30
    3523  535.91  3584.9  536.47  3629.5  533.94    3713  533.21  3796.5  535.13
  3846.6  532.04  3964.9   530.4  4032.2  532.16    4077  530.16  4113.9  532.07
  4314.4  527.87  4353.3  528.84  4375.9  527.42  4559.4  525.47  4598.4  523.61
  4599.5  521.55  4600.8  521.05  4608.4  521.55  4687.5  523.69    4716  521.62
    4732  521.56  4748.7  523.48  4939.1  522.71  5254.8  524.27  5484.3  526.72
  5608.7  530.65  5673.3  534.53  5769.4  534.46  5849.8  540.97  5936.2  541.64
#Mann= 6 ,-1 , 0
    3523     .12       0  4375.9      .1       0  4599.5     .05       0
  4608.4      .1       0  4939.1     .12       0  5254.8     .05       0
Bank Sta=4599.5,4608.4
XS Rating Curve= 0 ,0
Exp/Cntr=0.3,0.1

Type RM Length L Ch R = 1 ,113498  ,590,590,590
BEGIN DESCRIPTION:
Rocky Cedar Creek 114.0
END DESCRIPTION:
XS GIS Cut Line= 3
       2706029.8      6962659.42        2704876.        6960711.
      2704275.97      6960160.97
#Sta/Elev= 30
  2735.6  541.21  2741.2  541.08  2810.5  543.21  3007.4   539.3  3081.6  541.06
  3167.3  538.05  3210.3  540.21  3395.5   535.5  3453.9  538.18  3767.8   531.3
  4023.3  530.66  4211.9  527.03  4268.8   527.1  4300.1  524.16    4380  527.96
  4475.6  523.44  4616.2   524.2  4716.7  521.31    4718  520.81  4725.6  521.31
  4758.2  523.56  4789.5  521.57  4810.9  523.43  4934.3  522.03  5269.2  522.46
    5432  526.36  5509.7  529.55    5559  535.61  5615.7  539.47    5814  548.23
#Mann= 7 ,-1 , 0
  2735.6      .1       0  2741.2     .12       0  4211.9     .03       0
  4616.2     .03       0  4716.7     .03       0  4725.6     .03       0
  4934.3     .05       0
Bank Sta=4716.7,4725.6
XS Rating Curve= 0 ,0
Exp/Cntr=0.3,0.1

Type RM Length L Ch R = 1 ,112908  ,605,605,605
BEGIN DESCRIPTION:
Mapping XS 0f116183
END DESCRIPTION:
XS GIS Cut Line= 3
      2706692.76      6961890.04      2705346.87      6960388.36
      2704522.35      6959845.92
#Sta/Elev= 30
  2984.4   543.7  3158.7  540.78    3194  542.78  3271.8  538.52  3342.8   540.5
  3363.7  537.38  3392.1  536.35  3463.2  536.73  3561.8  534.36  3611.9  535.89
  3682.2  532.51  3718.1  533.41  3788.8  531.47    3831  533.25  3965.5  528.32
  4015.6  530.49  4071.7  526.05  4121.1  525.74  4327.8  524.74    4589  521.51
  4609.9  522.64  4869.4  521.59  4964.3   522.7  5326.9  521.29  5328.3  520.79
    5337  521.29  5432.2  522.47    5433  522.49  5744.1   529.5  5987.9  541.71
#Mann= 9 ,-1 , 0
  2984.4      .1       0  3158.7     .12       0  4121.1      .1       0
  4327.8     .12       0  4869.4     .03       0  5326.9     .03       0
    5337     .03       0  5432.2     .12       0    5433     .05       0
Bank Sta=5326.9,5337
XS Rating Curve= 0 ,0
Exp/Cntr=0.3,0.1

Type RM Length L Ch R = 1 ,112303  ,547,547,547
BEGIN DESCRIPTION:
Mapping XS e014ce85
END DESCRIPTION:
XS GIS Cut Line= 3
      2706844.26      6961291.13      2705819.96      6960045.48
      2705207.95      6959411.77
#Sta/Elev= 30
  3402.8  538.77  3466.1  538.55  3522.1  536.91  3529.9  537.71  3608.1  534.44
  3664.1  536.25  3700.7  532.86  3707.1  533.82  3750.2  532.59  3756.7  534.15
  3801.8  532.61  3856.1   532.7  3898.7  530.29  3976.9  529.07  4040.8  526.63
  4055.1  527.04  4104.6  524.86  4380.5  522.68  4420.3  521.38  4421.7  520.88
  4430.4  521.38  4431.8  522.37  4436.4  522.27  4460.5  523.02  4503.4  521.63
  5537.7  522.38  5587.3  526.26  5707.4   530.5  5728.8   532.8  5896.5  540.99
#Mann= 6 ,-1 , 0
  3402.8     .05       0  3801.8      .1       0  4380.5     .03       0
  4420.3     .03       0  4430.4     .03       0  4436.4     .05       0
Bank Sta=4420.3,4430.4
XS Rating Curve= 0 ,0
Exp/Cntr=0.3,0.1