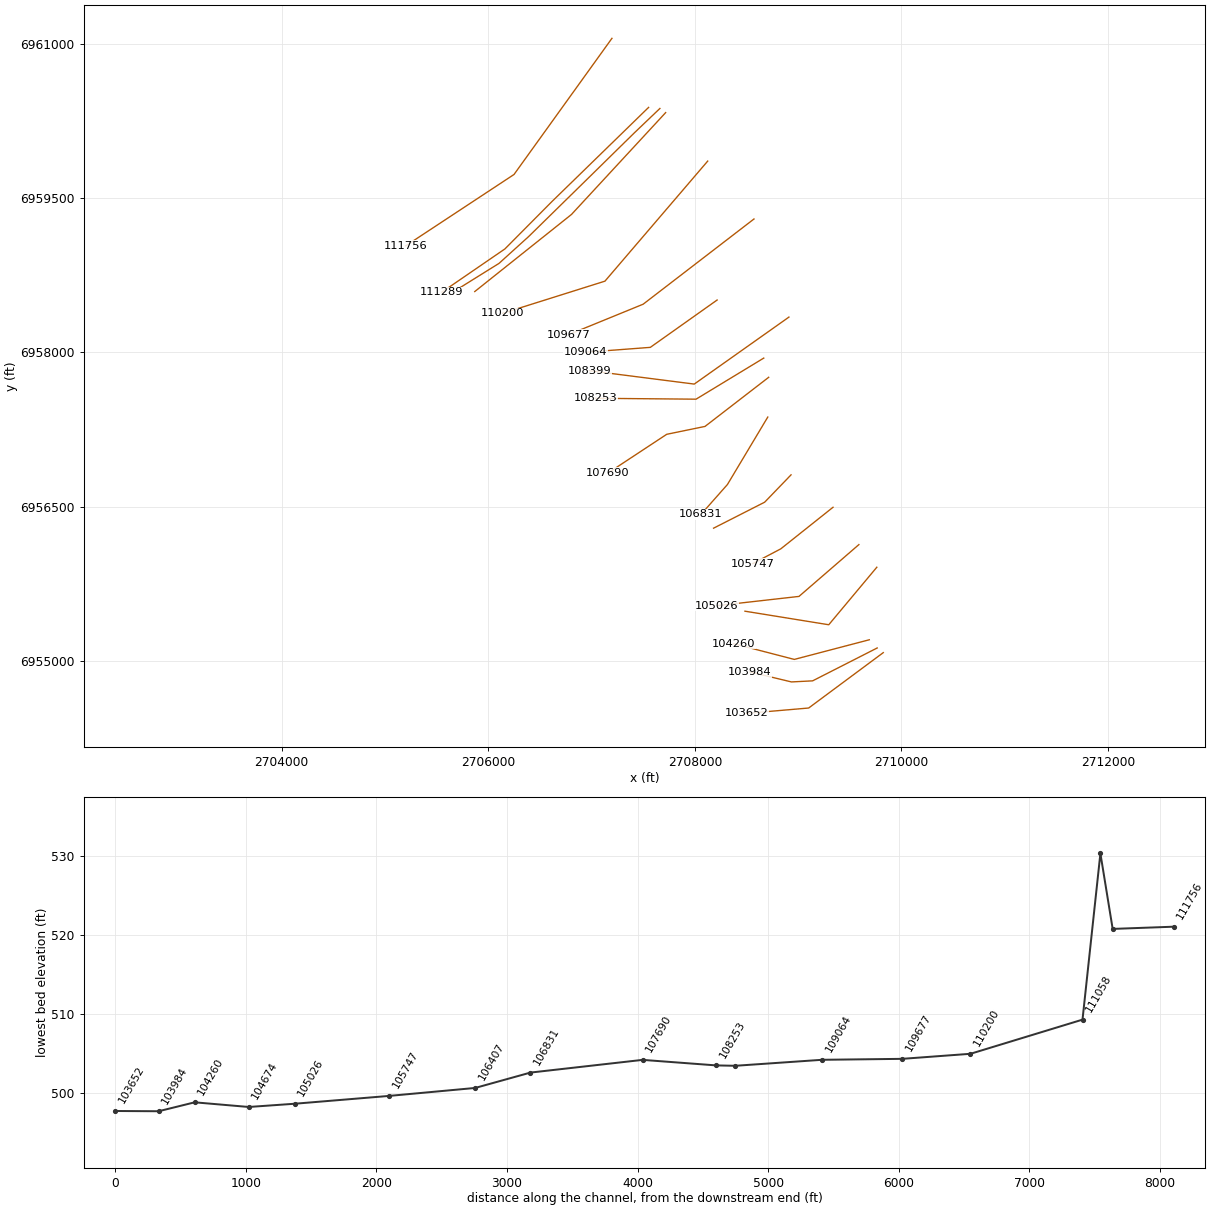
HEC-RAS study Rocky Cedar Creek.prj: Rocky Cedar Creek Base Level Engineering

--- Rocky Cedar Creek.g01 (geometry) --- (continued)

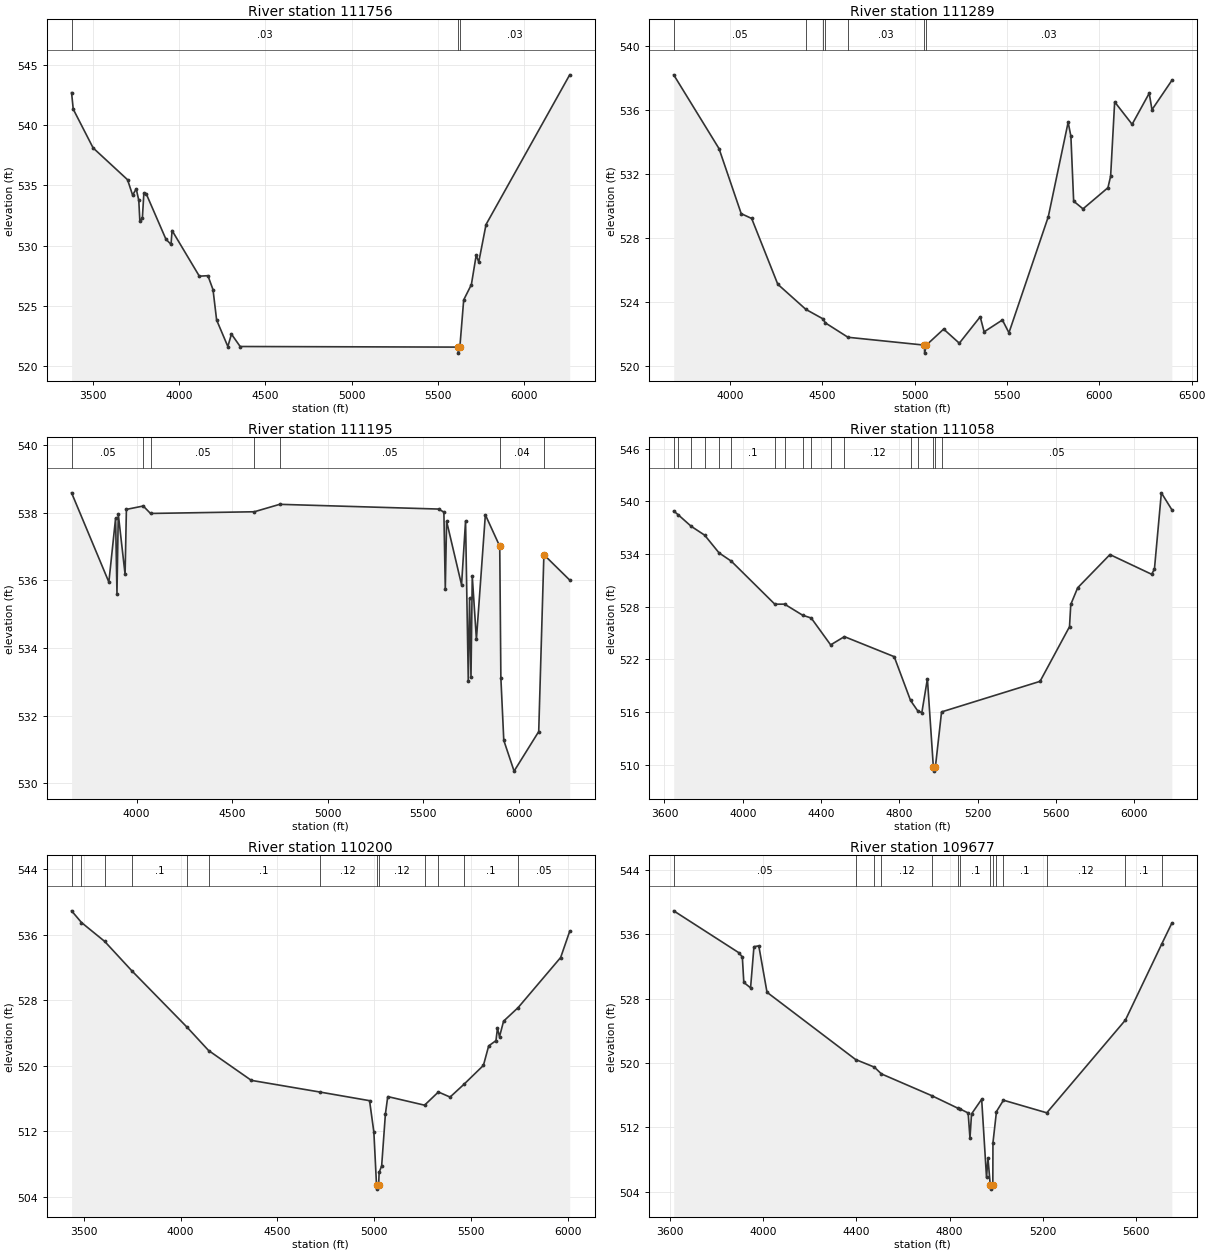
Type RM Length L Ch R = 1 ,111756  ,467,467,467
BEGIN DESCRIPTION:
Mapping XS d9230bea
END DESCRIPTION:
XS GIS Cut Line= 3
      2707197.59      6961052.46      2706249.65      6959729.51
      2705201.03      6959036.02
#Sta/Elev= 30
  3377.8   542.7  3387.4  541.33  3502.6  538.11  3701.9  535.47  3731.3  534.19
  3752.2  534.71    3767  533.76  3773.3  532.03  3787.9   532.3  3796.4  534.34
  3810.2   534.3  3924.2  530.53  3953.7   530.1  3959.8  531.25  4117.7  527.46
  4167.4   527.5  4196.9  526.34  4217.8  523.82  4282.8  521.62  4303.7  522.65
  4354.1  521.62  5615.9  521.57  5617.3  521.07  5626.4  521.57  5648.6  525.49
  5693.1  526.76  5720.9  529.19  5735.9  528.64    5778  531.75  6262.5  544.18
#Mann= 3 ,-1 , 0
  3377.8     .03       0  5615.9     .03       0  5626.4     .03       0
Bank Sta=5615.9,5626.4
XS Rating Curve= 0 ,0
Exp/Cntr=0.3,0.1

Type RM Length L Ch R = 1 ,111289  ,94,94,94
BEGIN DESCRIPTION:
Mapping XS 9729893c
END DESCRIPTION:
XS GIS Cut Line= 4
      2707552.56      6960381.49      2706615.05      6959464.82
      2706161.93      6959006.48      2705551.03      6958586.02
#Sta/Elev= 30
  3695.3  538.17  3940.8  533.56  4060.9   529.5  4117.5   529.2    4259  525.09
  4411.2  523.52  4503.7  522.93  4516.3  522.68  4639.1  521.78  5052.7  521.29
  5054.1  520.79  5063.3  521.29    5157  522.29  5241.9  521.41    5355  523.06
  5376.2  522.12  5475.2  522.86  5510.6  522.06  5723.7  529.31  5831.2  535.21
  5846.1  534.33    5861  530.28  5911.7   529.8  6046.7  531.12  6061.2  531.84
  6083.1  536.48  6177.6  535.08  6270.2  537.02  6285.1  535.99  6392.6  537.82
#Mann= 7 ,-1 , 0
  3695.3     .05       0  4411.2     .12       0  4503.7     .05       0
  4516.3     .03       0  4639.1     .03       0  5052.7     .03       0
  5063.3     .03       0
Bank Sta=5052.7,5063.3
XS Rating Curve= 0 ,0
Exp/Cntr=0.3,0.1

Type RM Length L Ch R = 1 ,111195  ,137,137,137
BEGIN DESCRIPTION:
Mapping XS 5e7a3c91
END DESCRIPTION:
XS GIS Cut Line= 6
       2707661.9      6960371.04      2707417.14      6960136.69
      2707047.35      6959772.11       2706391.1      6959126.27
      2706104.64      6958865.86      2705730.36      6958631.93
#Sta/Elev= 30
  3659.6  538.59  3854.8  535.95    3890  537.84  3897.2  535.61  3904.1  537.96
  3939.7  536.18  3946.6   538.1  4034.7   538.2  4072.8  537.98  4616.1  538.03
  4749.2  538.25  5580.5  538.11  5608.4  538.02  5615.8  535.74  5622.6  537.75
  5700.9  535.87  5721.9  537.76  5736.1  533.03  5742.8  535.47  5750.3  533.14
    5757  536.12  5778.7  534.26  5825.5  537.94  5900.8  537.01  5906.7  533.12
    5922  531.27  5975.9  530.36  6104.8  531.53  6131.9  536.76    6267  536.01
#Mann= 7 ,-1 , 0
  3659.6     .05       0  4034.7      .1       0  4072.8     .05       0
  4616.1     .12       0  4749.2     .05       0  5900.8     .04       0
  6131.9     .05       0
Bank Sta=5900.8,6131.9
XS Rating Curve= 0 ,0
Exp/Cntr=0.3,0.1

Type RM Length L Ch R = 1 ,111058  ,858,858,858
BEGIN DESCRIPTION:
Mapping XS 9d3a723d
END DESCRIPTION:
XS GIS Cut Line= 3
      2707717.49      6960330.71      2706806.03      6959341.12
      2705869.75       6958592.1
#Sta/Elev= 30
  3647.2   538.9  3669.3  538.49  3736.5  537.16  3805.4  536.15    3879  534.13
  3941.4  533.19  4163.9  528.29  4213.5   528.3  4306.4  527.03  4349.6  526.72
  4448.9  523.66  4519.1   524.6  4773.5  522.32  4857.1  517.33  4893.7  516.15
  4914.7  515.95  4943.1   519.8  4973.4  509.79  4974.9  509.29  4984.1  509.79
  5015.4  516.03  5518.5  519.51    5669  525.73  5675.4  528.26  5710.6  530.16
  5875.5  533.94  6088.4   531.7  6102.8  532.29  6138.1  540.97  6191.6  539.05
#Mann= 17 ,-1 , 0
  3647.2     .05       0  3669.3     .12       0  3736.5     .05       0
  3805.4     .12       0    3879     .05       0  3941.4      .1       0
  4163.9     .05       0  4213.5     .12       0  4306.4     .05       0
  4349.6      .1       0  4448.9     .05       0  4519.1     .12       0
  4857.1     .05       0  4893.7      .1       0  4973.4     .07       0
  4984.1      .1       0  5015.4     .05       0
Bank Sta=4973.4,4984.1
XS Rating Curve= 0 ,0
Exp/Cntr=0.3,0.1

Type RM Length L Ch R = 1 ,110200  ,523,523,523
BEGIN DESCRIPTION:
Mapping XS 8836f8a1
END DESCRIPTION:
XS GIS Cut Line= 3
      2708124.64      6959859.71      2707129.85      6958693.05
       2706140.6      6958380.65
#Sta/Elev= 30
  3437.4  538.94  3488.6  537.51  3608.1  535.21  3747.9  531.63  4034.2  524.71
  4144.7  521.88    4365  518.24  4717.6  516.82  4975.2  515.76  4997.4  511.92
  5011.1  505.46  5012.6  504.96  5022.1  505.46  5024.5     507  5037.6  507.79
  5056.9  514.12    5069  516.26    5259  515.21  5330.3  516.82  5390.7   516.2
  5461.4  517.74  5562.8  520.07  5589.9  522.45  5627.5  523.09  5635.3  524.62
  5645.8  523.57  5666.8  525.47  5742.1  527.13  5961.3  533.24    6008  536.44
#Mann= 13 ,-1 , 0
  3437.4     .12       0  3488.6      .1       0  3608.1     .12       0
  3747.9      .1       0  4034.2     .12       0  4144.7      .1       0
  4717.6     .12       0  5011.1     .07       0  5022.1     .12       0
    5259      .1       0  5330.3     .12       0  5461.4      .1       0
  5742.1     .05       0
Bank Sta=5011.1,5022.1
XS Rating Curve= 0 ,0
Exp/Cntr=0.3,0.1

Type RM Length L Ch R = 1 ,109677  ,613,613,613
BEGIN DESCRIPTION:
Mapping XS 9cdc526f
END DESCRIPTION:
XS GIS Cut Line= 3
      2708572.57      6959297.22      2707499.65      6958469.09
       2706775.7      6958172.22
#Sta/Elev= 30
  3616.3  538.93  3896.4  533.71  3910.9  533.18  3917.2  530.03  3946.2  529.35
  3960.7  534.46  3981.5  534.58  4016.8   528.8  4396.9  520.44  4477.6  519.49
  4507.7  518.65  4723.3  515.95  4838.3  514.35  4846.1  514.28    4880  513.79
  4887.8  510.65  4894.5  513.67    4938   515.5  4958.8  505.78  4965.1  508.17
  4974.9  504.82  4976.4  504.32  4985.9  504.82  4986.4  510.07  5001.5  513.97
  5031.5  515.38  5217.5  513.81    5555  525.35  5711.2  534.83  5754.1   537.4
#Mann= 14 ,-1 , 0
  3616.3     .05       0  4396.9     .12       0  4477.6      .1       0
  4507.7     .12       0  4723.3      .1       0  4838.3     .12       0
  4846.1      .1       0  4974.9     .07       0  4985.9      .1       0
  5001.5     .12       0  5031.5      .1       0  5217.5     .12       0
    5555      .1       0  5711.2     .12       0
Bank Sta=4974.9,4985.9
XS Rating Curve= 0 ,0
Exp/Cntr=0.3,0.1

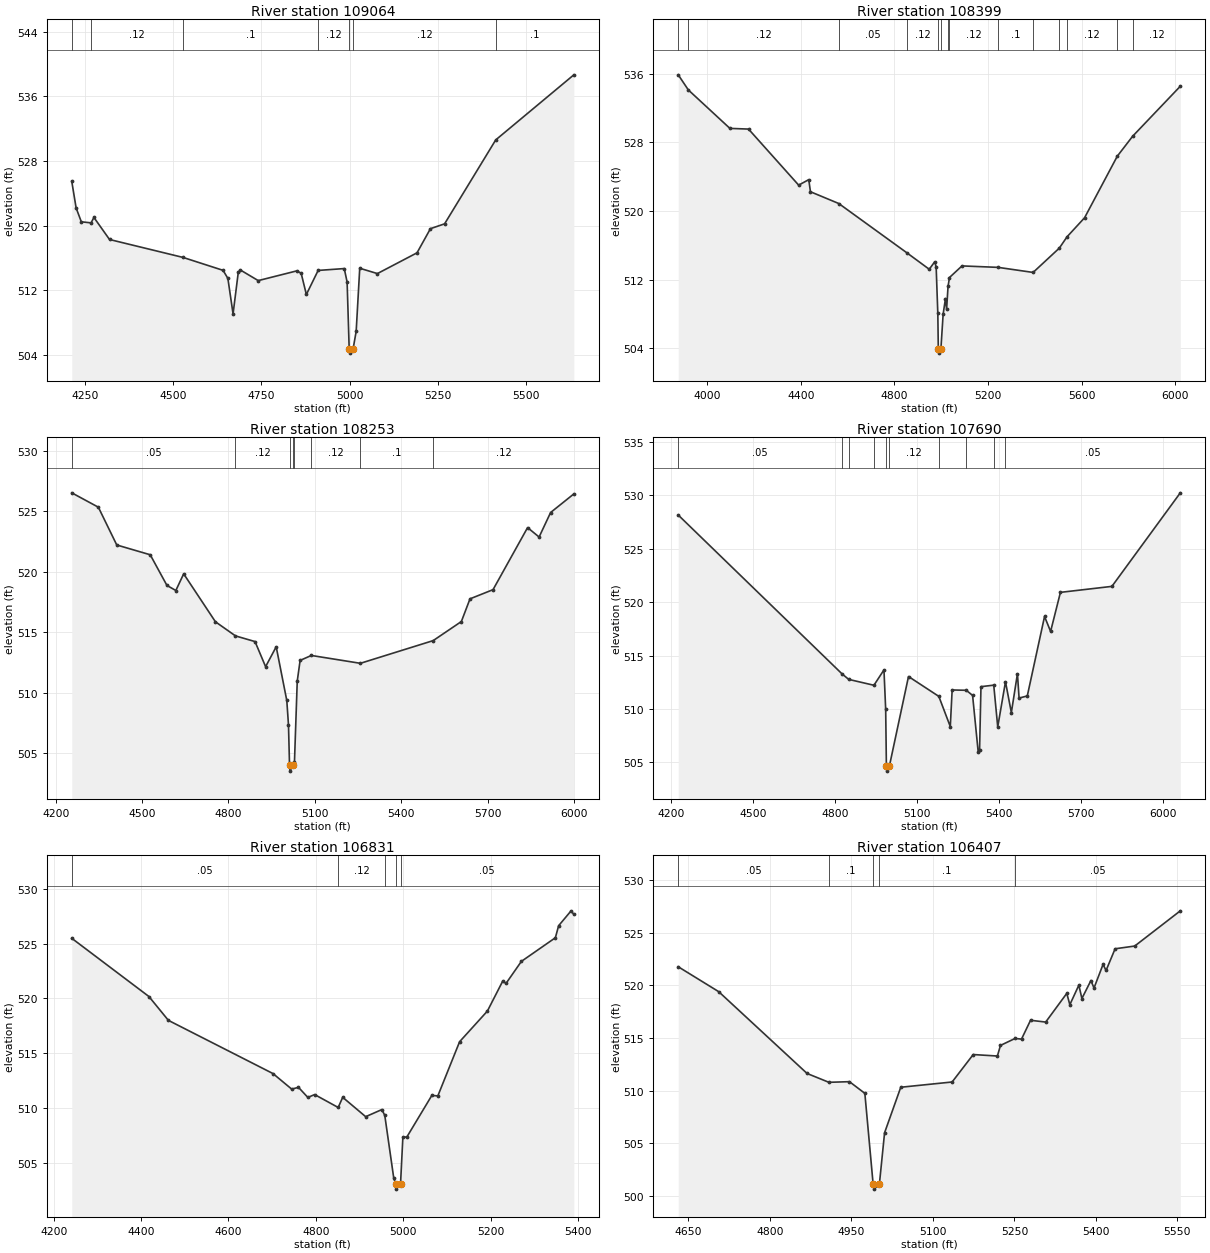
Type RM Length L Ch R = 1 ,109064  ,665,665,665
BEGIN DESCRIPTION:
Mapping XS 2894b873
END DESCRIPTION:
XS GIS Cut Line= 3
      2708215.75      6958509.86      2707569.09      6958049.82
       2706940.4      6958002.13
#Sta/Elev= 30
  4212.2  525.46  4224.6  522.17  4239.3  520.46    4267  520.33    4275     521
  4319.3  518.27  4527.8  516.05  4641.4  514.45    4655  513.45  4669.7  509.06
  4684.5  514.21  4690.6  514.49  4741.1  513.18  4850.1  514.38  4862.8   514.1
  4877.6  511.46    4911  514.44  4985.1  514.67  4993.2     513  4999.1   504.7
  5000.6   504.2  5010.1   504.7  5018.9   506.9    5029  514.71  5079.1  514.05
  5191.5  516.62  5229.5  519.61  5269.7  520.21  5414.7   530.6  5636.3  538.66
#Mann= 7 ,-1 , 0
  4212.2     .05       0    4267     .12       0  4527.8      .1       0
    4911     .12       0  4999.1     .07       0  5010.1     .12       0
  5414.7      .1       0
Bank Sta=4999.1,5010.1
XS Rating Curve= 0 ,0
Exp/Cntr=0.3,0.1

Type RM Length L Ch R = 1 ,108399  ,146,146,146
BEGIN DESCRIPTION:
Mapping XS 4c7bd7d5
END DESCRIPTION:
XS GIS Cut Line= 3
      2708911.08      6958344.08      2707994.44      6957693.05
      2706979.95      6957823.11
#Sta/Elev= 30
  3875.4  535.86  3918.6   534.1  4096.4  529.62    4176  529.54  4390.4  523.01
  4433.6  523.65  4440.8  522.24  4561.8  520.87  4853.5  515.12  4948.8  513.21
  4972.2  514.08  4978.4  513.47  4985.5  508.06  4987.6  503.94  4989.1  503.44
  4998.7  503.94  5008.2  507.96  5018.1  509.79  5023.1  508.55  5029.2  511.21
  5035.4  512.25  5088.9   513.6  5243.4  513.43    5393  512.84    5505  515.67
  5538.1  516.99  5613.1  519.21    5753  526.38  5818.8  528.71  6022.5  534.53
#Mann= 14 ,-1 , 0
  3875.4      .1       0  3918.6     .12       0  4561.8     .05       0
  4853.5     .12       0  4987.6     .07       0  4998.7     .12       0
  5029.2      .1       0  5035.4     .12       0  5243.4      .1       0
    5393     .12       0    5505      .1       0  5538.1     .12       0
    5753      .1       0  5818.8     .12       0
Bank Sta=4987.6,4998.7
XS Rating Curve= 0 ,0
Exp/Cntr=0.3,0.1

Type RM Length L Ch R = 1 ,108253  ,563,563,563
BEGIN DESCRIPTION:
Mapping XS 4ce398d8
END DESCRIPTION:
XS GIS Cut Line= 3
      2708667.17      6957945.65       2708011.8      6957546.35
      2707035.27      6957555.03
#Sta/Elev= 30
  4255.8  526.54  4348.1  525.35  4412.1  522.22  4528.3  521.41  4586.4  518.87
  4617.3  518.45  4644.5  519.83  4754.8  515.86  4824.5  514.69  4892.4  514.22
  4929.1  512.14  4965.9  513.79  5002.7  509.34  5008.6  507.31  5012.2  503.99
  5013.8  503.49  5023.4  503.99  5029.3  504.21    5039  510.94    5049  512.66
    5088  513.07  5258.3  512.42  5511.2   514.3  5609.1  515.88  5639.1  517.76
  5719.1  518.52  5839.1  523.66  5879.1  522.88  5919.1  524.91  5999.8  526.45
#Mann= 8 ,-1 , 0
  4255.8     .05       0  4824.5     .12       0  5012.2     .07       0
  5023.4     .12       0  5029.3      .1       0    5088     .12       0
  5258.3      .1       0  5511.2     .12       0
Bank Sta=5012.2,5023.4
XS Rating Curve= 0 ,0
Exp/Cntr=0.3,0.1

Type RM Length L Ch R = 1 ,107690  ,859,859,859
BEGIN DESCRIPTION:
Mapping XS 1e9ee2f2
END DESCRIPTION:
XS GIS Cut Line= 4
      2708714.94      6957759.04       2708098.6      6957281.59
      2707727.88      6957205.06      2707159.69      6956829.26
#Sta/Elev= 30
  4225.6  528.17    4826  513.29  4850.2  512.78  4942.5  512.23  4979.3  513.67
  4985.6  509.97  4988.2  504.69  4989.7  504.19  4999.4  504.69  5069.2  513.05
  5180.3  511.19  5222.3  508.36  5229.1  511.79  5280.9  511.76    5304  511.28
  5324.4  506.02  5329.6   506.2  5334.7   512.1  5381.5  512.24  5396.1  508.33
  5424.5  512.56    5446  509.67  5468.3  513.31  5474.3  511.03  5504.4  511.23
  5567.6  518.67  5589.8  517.27  5625.8  520.93  5814.4  521.49    6065  530.25
#Mann= 10 ,-1 , 0
  4225.6     .05       0    4826     .12       0  4850.2      .1       0
  4942.5     .12       0  4988.2     .07       0  4999.4     .12       0
  5180.3      .1       0  5280.9     .12       0  5381.5      .1       0
  5424.5     .05       0
Bank Sta=4988.2,4999.4
XS Rating Curve= 0 ,0
Exp/Cntr=0.3,0.1

Type RM Length L Ch R = 1 ,106831  ,424,424,424
BEGIN DESCRIPTION:
Mapping XS 91ed82e5
END DESCRIPTION:
XS GIS Cut Line= 3
      2708706.22       6957372.7      2708315.62      6956717.35
      2708060.27      6956427.38
#Sta/Elev= 30
  4241.4   525.5    4418  520.18  4462.6     518    4702  513.14  4744.8  511.72
  4760.4  511.88  4781.8  510.96  4797.4  511.22  4851.3  510.04  4861.6  510.97
  4914.2   509.2  4951.2  509.85  4957.9  509.32  4978.4   503.6  4982.5  503.08
    4984  502.58    4994  503.08  4999.3   507.3  5008.7  507.36  5065.6  511.14
  5079.4   511.1  5129.2  516.05  5192.8  518.85  5227.9  521.59  5235.5  521.38
  5270.6  523.39  5348.4  525.55  5355.9  526.65  5384.4  528.01  5390.7  527.68
#Mann= 5 ,-1 , 0
  4241.4     .05       0  4851.3     .12       0  4957.9     .05       0
  4982.5     .04       0    4994     .05       0
Bank Sta=4982.5,4994
XS Rating Curve= 0 ,0
Exp/Cntr=0.3,0.1

Type RM Length L Ch R = 1 ,106407  ,660,660,660
BEGIN DESCRIPTION:
Mapping XS ba9696f6
END DESCRIPTION:
XS GIS Cut Line= 3
      2708931.28       6956811.1      2708676.08      6956545.48
      2708181.28      6956292.87
#Sta/Elev= 30
  4631.4  521.78  4705.9  519.41  4868.5  511.63  4908.6  510.79  4946.5  510.85
  4974.8  509.74    4990  501.13  4991.6  500.63  5001.6  501.13  5011.1  505.99
  5040.9  510.32  5135.4  510.82  5174.2  513.43  5218.7  513.29  5224.4   514.3
  5251.2  514.96  5263.1   514.9  5279.7  516.69  5307.6  516.52  5346.4  519.25
    5352  518.17  5368.6  520.03  5374.2  518.76  5390.8  520.47  5396.5  519.76
  5413.1     522  5418.7  521.43  5435.3  523.49  5471.4  523.75  5555.3   527.1
#Mann= 5 ,-1 , 0
  4631.4     .05       0  4908.6      .1       0    4990     .07       0
  5001.6      .1       0  5251.2     .05       0
Bank Sta=4990,5001.6
XS Rating Curve= 0 ,0
Exp/Cntr=0.3,0.1

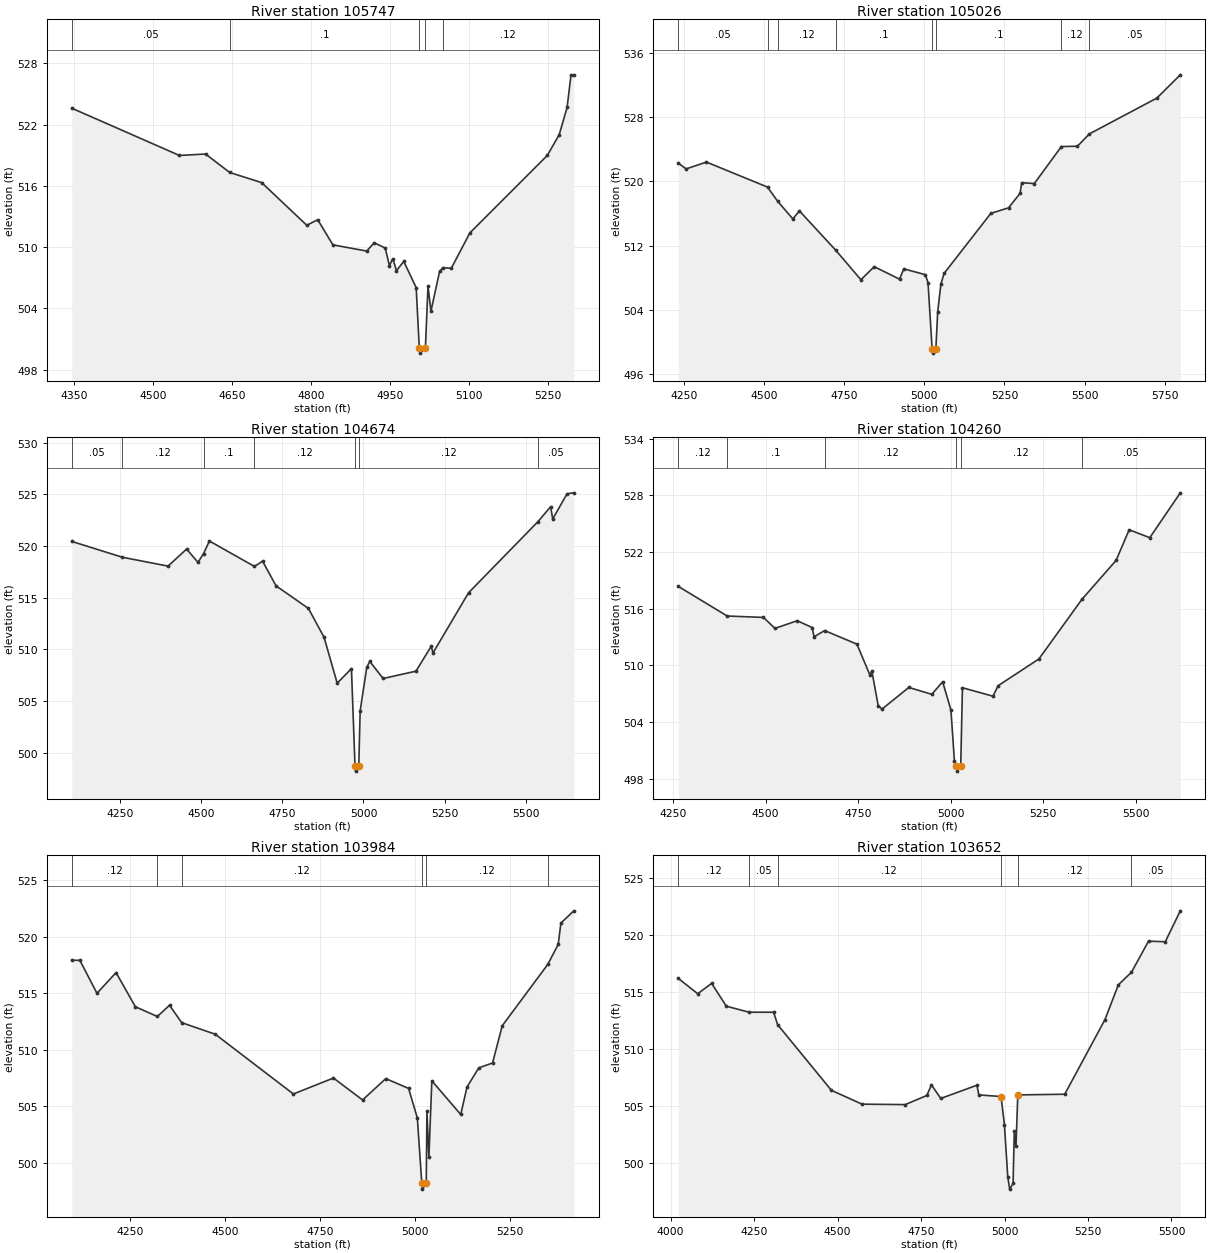
Type RM Length L Ch R = 1 ,105747  ,721,721,721
BEGIN DESCRIPTION:
Mapping XS f780adec
END DESCRIPTION:
XS GIS Cut Line= 3
      2709337.56      6956496.02      2708832.33      6956092.35
      2708561.46      6955949.11
#Sta/Elev= 30
  4345.9  523.62  4550.2  518.99  4599.9  519.13  4645.7  517.32  4706.3  516.33
    4792  512.15  4812.8  512.69  4841.6  510.23  4905.7  509.62  4920.1  510.43
  4940.9  509.92  4948.9  508.19  4955.3  508.87  4962.3   507.7  4976.1  508.61
  4999.7  506.04  5005.6  500.12  5007.2  499.62  5017.2  500.12  5022.1  506.17
  5027.8  503.74  5044.1  507.62  5050.4     508  5066.2  507.92  5101.6   511.4
  5248.6  518.99  5271.2  521.02  5286.2  523.69  5293.6  526.89    5299  526.89
#Mann= 5 ,-1 , 0
  4345.9     .05       0  4645.7      .1       0  5005.6     .07       0
  5017.2      .1       0  5050.4     .12       0
Bank Sta=5005.6,5017.2
XS Rating Curve= 0 ,0
Exp/Cntr=0.3,0.1

Type RM Length L Ch R = 1 ,105026  ,352,352,352
BEGIN DESCRIPTION:
Mapping XS 12310974
END DESCRIPTION:
XS GIS Cut Line= 3
      2709587.94      6956133.34      2709008.11       6955629.9
      2708213.01      6955539.62
#Sta/Elev= 30
  4231.1  522.27  4255.5  521.54  4319.2  522.39  4509.9  519.28  4542.1  517.49
  4588.9  515.33  4609.7  516.31  4722.3  511.46  4801.6  507.76  4843.3  509.38
  4922.2  507.83  4935.6  509.11  5002.6  508.39  5011.2  507.41  5024.1  499.13
  5025.7  498.63  5035.7  499.13  5041.4  503.74  5051.4  507.21  5061.5  508.55
  5207.4  516.01  5262.8   516.7  5298.7   518.5  5303.8  519.82  5343.3  519.72
  5427.7  524.32    5478  524.36    5515  525.89  5725.7  530.34  5799.2  533.24
#Mann= 8 ,-1 , 0
  4231.1     .05       0  4509.9      .1       0  4542.1     .12       0
  4722.3      .1       0  5024.1     .07       0  5035.7      .1       0
  5427.7     .12       0    5515     .05       0
Bank Sta=5024.1,5035.7
XS Rating Curve= 0 ,0
Exp/Cntr=0.3,0.1

Type RM Length L Ch R = 1 ,104674  ,414,414,414
BEGIN DESCRIPTION:
Mapping XS 782ccfca
END DESCRIPTION:
XS GIS Cut Line= 3
      2709761.58      6955913.58       2709296.3      6955354.55
      2708485.35      6955486.24
#Sta/Elev= 30
  4100.1  520.44  4256.1  518.91  4397.1  518.05  4454.4   519.7  4489.5  518.41
  4506.8  519.27  4524.7  520.48  4663.7  518.02  4688.7  518.53  4730.4  516.14
  4830.1  513.96  4878.4  511.17  4918.9  506.73  4962.9  508.13  4973.9  498.72
  4975.5  498.22  4985.5  498.72  4989.8  504.05  5010.1  508.25  5019.4  508.83
  5060.7  507.18    5162  507.89  5209.2  510.31  5214.3  509.64  5324.1  515.47
  5538.5  522.36  5577.4   523.8  5583.8  522.61  5628.1  525.05    5649  525.14
#Mann= 7 ,-1 , 0
  4100.1     .05       0  4256.1     .12       0  4506.8      .1       0
  4663.7     .12       0  4973.9     .07       0  4985.5     .12       0
  5538.5     .05       0
Bank Sta=4973.9,4985.5
XS Rating Curve= 0 ,0
Exp/Cntr=0.3,0.1

Type RM Length L Ch R = 1 ,104260  ,276,276,276
BEGIN DESCRIPTION:
Mapping XS ec5f540b
END DESCRIPTION:
XS GIS Cut Line= 3
      2709688.68      6955208.72      2708962.97      6955017.75
      2708376.15      6955170.53
#Sta/Elev= 30
  4263.9  518.37  4396.2  515.23  4494.2  515.08  4525.2  513.92  4585.5  514.73
  4625.8  514.01    4631  513.03  4659.5  513.69  4746.8  512.25    4782  508.97
  4787.1  509.41  4804.4  505.73  4814.7  505.38  4887.1  507.67  4949.1  506.94
  4978.4  508.27  5000.8  505.29  5010.2  499.91  5015.7  499.31  5017.3  498.81
  5027.3  499.31  5031.9  507.64  5114.5  506.74  5128.2  507.85  5238.5  510.68
  5354.5  516.98  5447.2  521.12  5482.5  524.36  5538.2  523.52  5620.7  528.27
#Mann= 6 ,-1 , 0
  4263.9     .12       0  4396.2      .1       0  4659.5     .12       0
  5015.7     .07       0  5027.3     .12       0  5354.5     .05       0
Bank Sta=5015.7,5027.3
XS Rating Curve= 0 ,0
Exp/Cntr=0.3,0.1

Type RM Length L Ch R = 1 ,103984  ,332,332,332
BEGIN DESCRIPTION:
Mapping XS d5e04f30
END DESCRIPTION:
XS GIS Cut Line= 4
      2709765.05      6955128.86      2709140.05      6954809.41
      2708935.19        6954799.      2708532.88      6954896.11
#Sta/Elev= 30
  4096.1  517.92  4117.5   517.9  4162.4  514.99  4212.6  516.82  4263.5   513.8
  4321.2  512.94  4353.3  513.93  4385.2   512.4  4473.6  511.37  4679.1  506.09
  4784.6   507.5  4861.2  505.56  4922.2  507.45  4982.3  506.58  5005.3  503.96
    5017  498.18  5018.7  497.68  5028.7  498.18  5030.5  504.56  5035.6  500.48
  5043.4  507.25  5119.4  504.28    5136  506.71  5166.9   508.4  5203.2  508.83
  5228.6  512.12  5348.3  517.54  5375.9  519.31  5382.9   521.2    5417  522.28
#Mann= 6 ,-1 , 0
  4096.1     .12       0  4321.2      .1       0  4385.2     .12       0
    5017     .07       0  5028.7     .12       0  5348.3     .05       0
Bank Sta=5017,5028.7
XS Rating Curve= 0 ,0
Exp/Cntr=0.3,0.1

Type RM Length L Ch R = 1 ,103652  ,665,665,665
BEGIN DESCRIPTION:
Mapping XS a38d3d43
END DESCRIPTION:
XS GIS Cut Line= 3
       2709824.1      6955083.73      2709101.86      6954545.52
      2708501.13      6954493.44
#Sta/Elev= 30
  4022.7  516.19  4081.1  514.84  4122.8  515.75  4166.6  513.75    4235  513.22
  4308.4  513.22  4320.3  512.13  4481.5  506.37  4573.2  505.16  4702.5  505.12
  4767.2  505.92  4781.1  506.85  4808.9  505.66  4917.3  506.82    4923  505.97
  4989.5  505.83  4999.6  503.36  5009.6   498.8  5015.4  497.71  5025.5  498.21
  5029.2  502.82  5034.2  501.45  5039.7  505.97  5180.2  506.03  5300.7  512.57
  5340.8  515.62  5380.2  516.73  5431.2  519.45  5481.4   519.4  5526.4  522.11
#Mann= 6 ,-1 , 0
  4022.7     .12       0    4235     .05       0  4320.3     .12       0
  4989.5     .07       0  5039.7     .12       0  5380.2     .05       0
Bank Sta=4989.5,5039.7
XS Rating Curve= 0 ,0
Exp/Cntr=0.3,0.1