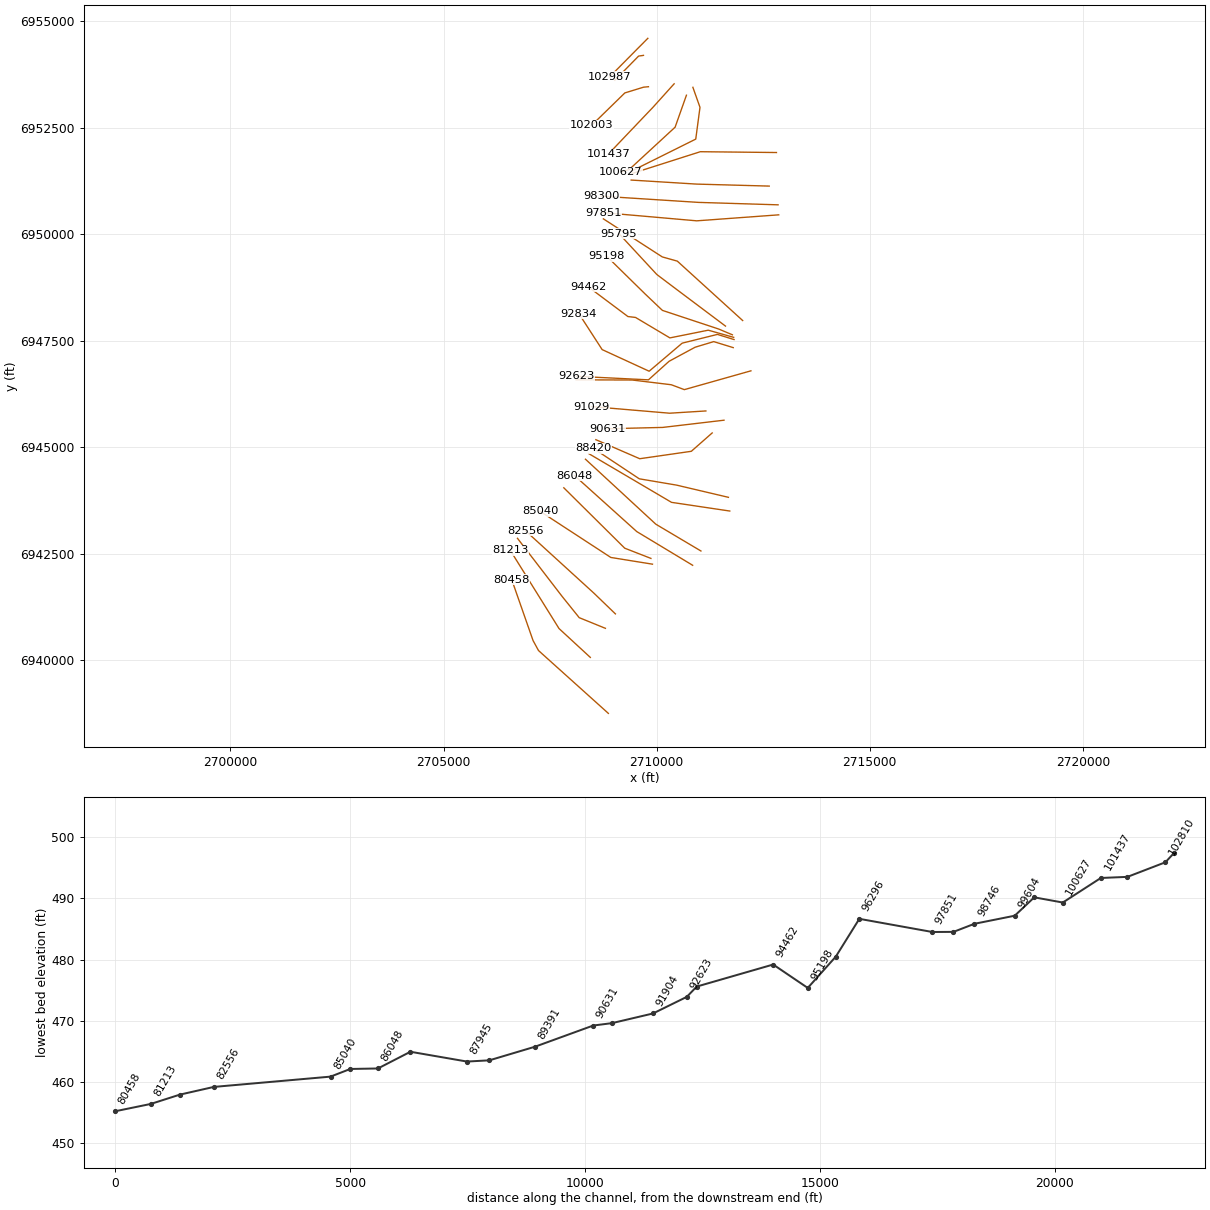
HEC-RAS study Rocky Cedar Creek.prj: Rocky Cedar Creek Base Level Engineering

--- Rocky Cedar Creek.g01 (geometry) --- (continued)

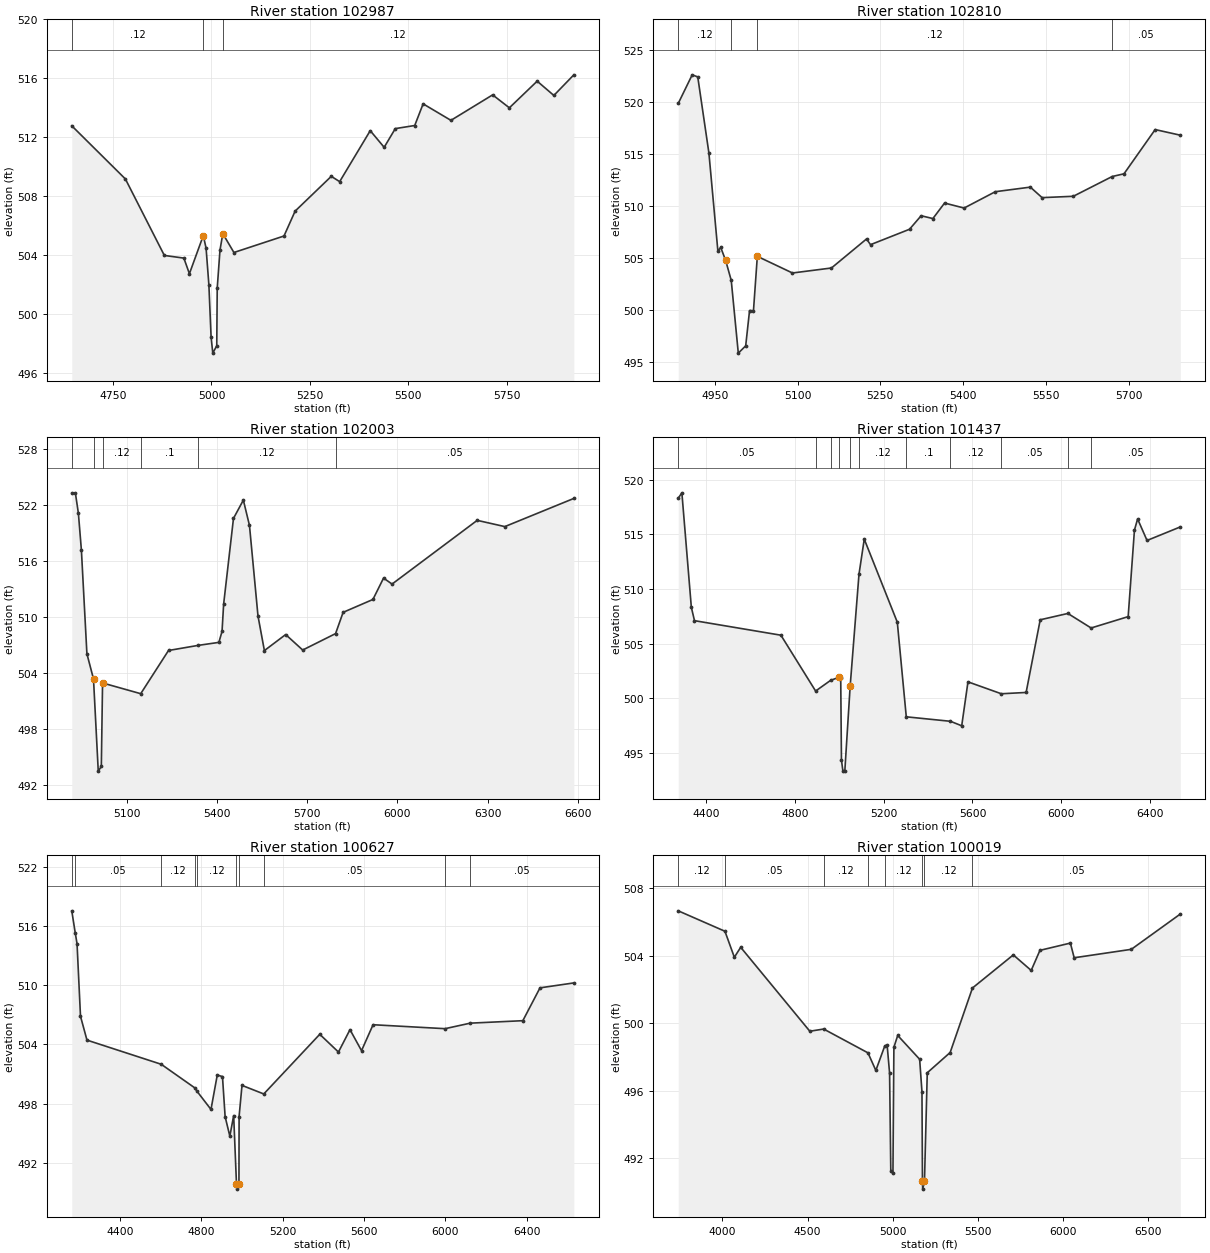
Type RM Length L Ch R = 1 ,102987  ,177,177,177
BEGIN DESCRIPTION:
Mapping XS 13cc8a9f
END DESCRIPTION:
XS GIS Cut Line= 3
      2709793.56      6954596.28      2709543.12      6954344.53
       2708895.4      6953689.78
#Sta/Elev= 30
  4644.9  512.77  4781.2  509.16  4880.2  503.97  4929.8  503.79  4943.9  502.73
  4979.2  505.32  4986.3  504.46  4993.4  501.97    4999  498.44  5003.3  497.34
  5013.4  497.84  5014.6  501.75  5021.6  504.33  5028.8  505.45    5057  504.17
  5184.3  505.29  5212.6  506.98  5304.5  509.34  5325.8  508.98  5403.5  512.44
  5438.9  511.31  5467.2  512.58  5516.6  512.79  5537.9  514.26  5608.6  513.14
  5714.6  514.87  5757.1  513.99  5827.8   515.8  5870.2  514.83    5921  516.23
#Mann= 3 ,-1 , 0
  4644.9     .12       0  4979.2     .07       0  5028.8     .12       0
Bank Sta=4979.2,5028.8
XS Rating Curve= 0 ,0
Exp/Cntr=0.3,0.1

Type RM Length L Ch R = 1 ,102810  ,807,807,807
BEGIN DESCRIPTION:
Rocky Cedar Creek 94.0
END DESCRIPTION:
XS GIS Cut Line= 3
      2709691.07      6954196.46      2709577.28      6954179.99
      2709019.79      6953612.78
#Sta/Elev= 30
  4883.6  519.88  4908.9  522.63    4919  522.43  4939.2  515.12  4955.5  505.69
  4960.6  506.05  4969.6  504.79  4979.7  502.88  4992.5  495.89  5005.9  496.59
  5012.9  499.98    5020  499.96    5027  505.19  5090.7  503.59  5161.4  504.07
    5225  506.86  5232.2  506.31  5302.9  507.79    5324  509.09  5345.3  508.82
  5366.5  510.31  5401.9  509.83  5458.5   511.4    5522  511.84  5543.3  510.83
  5599.9  510.96  5670.4  512.86  5691.8  513.12  5748.3  517.37  5793.9  516.83
#Mann= 4 ,-1 , 0
  4883.6     .12       0  4979.7     .07       0    5027     .12       0
  5670.4     .05       0
Bank Sta=4969.6,5027
XS Rating Curve= 0 ,0
Exp/Cntr=0.3,0.1

Type RM Length L Ch R = 1 ,102003  ,566,566,566
BEGIN DESCRIPTION:
Mapping XS 53374b5d
END DESCRIPTION:
XS GIS Cut Line= 4
      2709807.88      6953460.97      2709693.05      6953450.25
      2709254.68      6953315.71      2708471.39      6952551.51
#Sta/Elev= 30
  4917.8  523.28  4929.7  523.34  4939.8  521.15  4949.8  517.19  4968.1  506.09
    4990  503.39  5005.8  493.51    5016  494.01  5020.1  502.96  5146.9  501.81
  5239.2  506.44  5338.1  506.99  5406.6  507.31  5417.1  508.49  5422.4  511.41
  5455.1   520.6  5487.9  522.56  5508.2  519.85  5536.5  510.15  5557.8  506.43
  5628.5  508.15  5685.1  506.49  5794.3  508.25  5819.4  510.53  5918.4  511.91
  5953.7   514.2    5982  513.56  6264.9  520.39  6356.7  519.72    6586  522.74
#Mann= 6 ,-1 , 0
  4917.8     .12       0    4990     .07       0  5020.1     .12       0
  5146.9      .1       0  5338.1     .12       0  5794.3     .05       0
#XS Ineff= 2 , 0
       0                  5487.9       0  522.56
Permanent Ineff=
       F       F
Bank Sta=4990,5020.1
XS Rating Curve= 0 ,0
Exp/Cntr=0.3,0.1

Type RM Length L Ch R = 1 ,101437  ,810,810,810
BEGIN DESCRIPTION:
Mapping XS a31d36c1
END DESCRIPTION:
XS GIS Cut Line= 3
      2710410.92      6953529.39      2709916.72      6952981.21
       2708866.4      6951878.82
#Sta/Elev= 30
  4275.2  518.31  4291.6   518.8  4334.2  508.32  4348.4   507.1  4737.5  505.77
  4893.8  500.66  4960.8  501.63  5000.1  501.93  5006.8  501.86  5010.1  494.35
  5016.7  493.33  5025.3  493.33  5049.3   501.1  5089.1  511.35  5112.8  514.56
  5261.6  506.96    5302   498.3  5501.1  497.89  5551.6  497.48  5579.8   501.5
    5730  500.41  5841.6  500.53  5905.1  507.18  6029.6  507.76  6134.3  506.43
  6301.1  507.47  6329.4  515.39  6343.6  516.41  6386.1  514.44  6535.9  515.68
#Mann= 11 ,-1 , 0
  4275.2     .05       0  4893.8     .12       0  4960.8      .1       0
  5000.1     .07       0  5049.3      .1       0  5089.1     .12       0
    5302      .1       0  5501.1     .12       0    5730     .05       0
  6029.6     .12       0  6134.3     .05       0
#XS Ineff= 2 , 0
       0                  5112.8       0  514.56
Permanent Ineff=
       F       F
Bank Sta=5000.1,5049.3
XS Rating Curve= 0 ,0
Exp/Cntr=0.3,0.1

Type RM Length L Ch R = 1 ,100627  ,608,608,608
BEGIN DESCRIPTION:
Mapping XS b809cca7
END DESCRIPTION:
XS GIS Cut Line= 4
      2710699.26      6953261.46      2710433.63      6952511.43
      2709360.71      6951521.85      2709159.28       6951454.7
#Sta/Elev= 30
  4163.4  517.54  4180.7  515.27  4189.3  514.21  4206.3  506.85  4238.1  504.43
  4603.1  501.98  4768.5  499.58  4777.9  499.27  4847.6   497.4  4878.5  500.89
  4904.1  500.73  4917.1  496.67  4940.3  494.69  4959.1  496.78    4973  489.82
  4974.7  489.32    4985  489.82  4985.8  496.68    5000  499.84  5107.1  498.97
  5382.2  505.02  5474.1  503.22  5530.8  505.49  5587.5  503.36  5644.2  505.99
    5998  505.59  6121.7  506.15  6380.3   506.4  6464.7  509.73    6631  510.23
#Mann= 10 ,-1 , 0
  4163.4     .12       0  4180.7     .05       0  4603.1     .12       0
  4768.5      .1       0  4777.9     .12       0    4973     .07       0
    4985     .12       0  5107.1     .05       0    5998     .12       0
  6121.7     .05       0
Bank Sta=4973,4985
XS Rating Curve= 0 ,0
Exp/Cntr=0.3,0.1

Type RM Length L Ch R = 1 ,100019  ,415,415,415
BEGIN DESCRIPTION:
Mapping XS e43d659e
END DESCRIPTION:
XS GIS Cut Line= 4
      2710850.95      6953446.65      2711017.39      6952977.29
      2710918.01      6952231.92      2709398.21      6951475.49
#Sta/Elev= 30
  3740.8  506.65    4015  505.44  4070.2   503.9  4107.5  504.49  4513.3  499.52
  4594.7  499.65  4854.7  498.24  4900.9   497.2  4953.7  498.66  4967.3  498.69
  4981.6  497.04  4988.7  491.23  5001.3  491.13  5006.9  498.57  5029.3  499.27
  5158.1  497.86  5171.7  495.93  5174.5  490.67  5176.1  490.17  5186.5  490.67
  5202.8  497.06  5337.2  498.26  5468.2  502.08  5707.9  504.04    5813  503.12
  5864.3  504.31    6043  504.74  6065.3  503.87  6400.8  504.37  6688.4  506.46
#Mann= 8 ,-1 , 0
  3740.8     .12       0    4015     .05       0  4594.7     .12       0
  4854.7      .1       0  4953.7     .12       0  5174.5     .07       0
  5186.5     .12       0  5468.2     .05       0
Bank Sta=5174.5,5186.5
XS Rating Curve= 0 ,0
Exp/Cntr=0.3,0.1

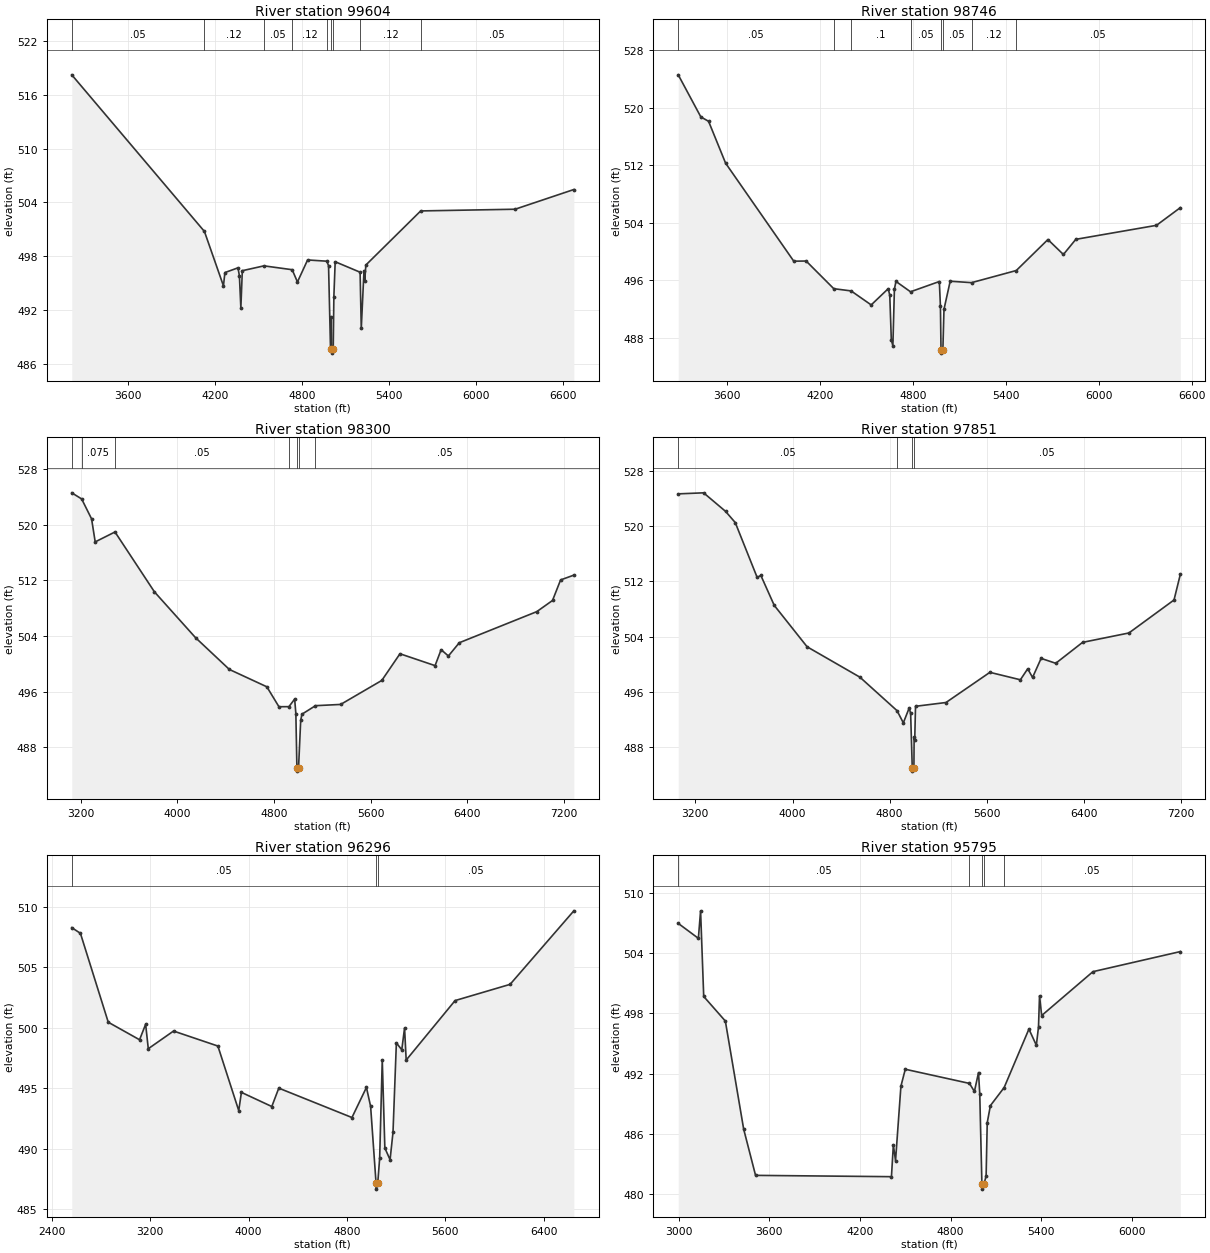
Type RM Length L Ch R = 1 ,99604   ,858,858,858
BEGIN DESCRIPTION:
Mapping XS 871c8ec0
END DESCRIPTION:
XS GIS Cut Line= 3
      2712811.34      6951917.08      2711025.54      6951936.18
      2709430.17      6951427.51
#Sta/Elev= 30
  3214.1  518.23  4128.4  500.75  4259.5  494.68  4269.5  496.16  4359.5  496.69
  4369.5  495.81  4379.5  492.21  4389.5  496.37  4538.7  496.91  4733.2  496.48
  4769.5  495.11  4839.5  497.57  4972.2  497.43  4983.9  496.92  4997.3  487.75
    5000  487.75  5002.7  491.21    5004  487.67  5005.7  487.17  5016.1  487.67
  5020.5  493.46  5029.6  497.37  5201.3   496.2  5209.4  489.92  5228.1  496.37
  5233.3  495.23  5240.9     497  5618.9  503.04  6269.5  503.23  6674.5  505.43
#Mann= 9 ,-1 , 0
  3214.1     .05       0  4128.4     .12       0  4538.7     .05       0
  4733.2     .12       0  4972.2      .1       0    5004     .07       0
  5016.1      .1       0  5201.3     .12       0  5618.9     .05       0
Bank Sta=5004,5016.1
XS Rating Curve= 0 ,0
Exp/Cntr=0.3,0.1

Type RM Length L Ch R = 1 ,98746   ,446,446,446
BEGIN DESCRIPTION:
Mapping XS 416a88b8
END DESCRIPTION:
XS GIS Cut Line= 3
      2712641.92      6951129.49      2710937.24      6951176.26
      2709402.28       6951270.9
#Sta/Elev= 30
  3283.8  524.59  3429.8  518.73  3479.8  518.12  3589.8  512.29    4030  498.65
    4110  498.67  4288.5  494.82  4400.5  494.51  4530.2  492.56  4640.2  494.82
  4650.2  493.92  4660.2  487.72  4670.2  486.86  4680.2  494.77  4690.3  495.83
  4784.2  494.39  4970.4  495.82  4977.4   492.4  4981.2  486.35  4982.9  485.85
  4993.3  486.35  5000.4  491.95  5040.5  495.86  5178.5  495.66  5467.5  497.35
  5671.7  501.66  5771.8  499.58    5852  501.69    6373  503.64    6527   506.1
#Mann= 8 ,-1 , 0
  3283.8     .05       0  4288.5     .12       0  4400.5      .1       0
  4784.2     .05       0  4981.2     .05       0  4993.3     .05       0
  5178.5     .12       0  5467.5     .05       0
Bank Sta=4981.2,4993.3
XS Rating Curve= 0 ,0
Exp/Cntr=0.3,0.1

Type RM Length L Ch R = 1 ,98300   ,449,449,449
BEGIN DESCRIPTION:
Mapping XS f37f2054
END DESCRIPTION:
XS GIS Cut Line= 3
      2712849.83      6950689.82      2710980.07      6950747.11
      2708699.86      6950892.87
#Sta/Elev= 30
  3125.7  524.63  3207.4  523.75  3289.6  520.88  3319.6  517.56  3483.4  518.99
  3809.9  510.36    4150  503.76  4430.1  499.18  4740.3  496.68  4840.3  493.81
  4923.1  493.82  4970.4  494.91  4980.4  492.83  4989.1  485.03    4991  484.53
  5002.7  485.03  5020.5  491.84  5030.5  492.73  5142.9  493.96  5351.1  494.14
  5691.8   497.6  5842.1  501.44  6132.7  499.73  6182.8  502.03  6242.9  501.12
  6333.1  503.03  6974.4  507.51  7104.7  509.12  7171.6  512.08  7281.2  512.77
#Mann= 7 ,-1 , 0
  3125.7     .05       0  3207.4    .075       0  3483.4     .05       0
  4923.1     .12       0  4989.1     .07       0  5002.7     .12       0
  5142.9     .05       0
Bank Sta=4989.1,5002.7
XS Rating Curve= 0 ,0
Exp/Cntr=0.3,0.1

Type RM Length L Ch R = 1 ,97851   ,1555,1555,1555
BEGIN DESCRIPTION:
Mapping XS fff23a15
END DESCRIPTION:
XS GIS Cut Line= 3
      2712864.21      6950455.01      2710942.31      6950314.38
      2708744.38      6950507.09
#Sta/Elev= 30
  3059.3  524.67  3268.1  524.82  3448.6  522.14  3528.8  520.51  3709.2  512.56
  3739.3  512.86  3849.6  508.52  4120.3  502.52  4554.8  498.12  4860.5  493.27
  4912.5   491.5  4960.9  493.67  4972.6  492.86  4985.9  485.01  4987.8  484.51
  4999.5  485.01  5001.3  489.39  5006.3  489.05  5012.8   493.9  5263.7  494.45
  5625.1  498.82  5876.1  497.74  5936.3  499.33  5976.4  498.08  6046.7  500.84
  6167.2  500.13    6388  503.16  6769.5  504.52  7140.9   509.3  7192.7     513
#Mann= 4 ,-1 , 0
  3059.3     .05       0  4860.5     .12       0  4985.9     .04       0
  4999.5     .05       0
Bank Sta=4985.9,4999.5
XS Rating Curve= 0 ,0
Exp/Cntr=0.3,0.1

Type RM Length L Ch R = 1 ,96296   ,501,501,501
BEGIN DESCRIPTION:
Mapping XS 38ad929a
END DESCRIPTION:
XS GIS Cut Line= 4
      2712018.93      6947974.84      2710486.13      6949368.33
      2710132.48      6949467.76      2708750.29      6950360.81
#Sta/Elev= 30
  2561.1  508.28  2631.5  507.81  2857.9  500.46  3112.6  499.01    3162  500.29
  3183.6  498.27    3389  499.73  3749.8  498.49  3919.5  493.15  3941.1  494.66
  4188.4  493.49  4245.2  495.01  4840.5  492.58  4958.3  495.07  4992.3   493.5
  5036.5  487.16  5038.5  486.66  5050.3  487.16  5065.9  489.22    5087  497.35
  5108.1  490.06  5150.6  489.09  5174.4  491.36  5201.8  498.75  5245.8  498.18
  5268.4  499.98  5281.6  497.33  5679.5  502.25  6126.9  503.59  6645.6  509.67
#Mann= 3 ,-1 , 0
  2561.1     .05       0  5036.5     .04       0  5050.3     .05       0
Bank Sta=5036.5,5050.3
XS Rating Curve= 0 ,0
Exp/Cntr=0.3,0.1

Type RM Length L Ch R = 1 ,95795   ,597,597,597
BEGIN DESCRIPTION:
Mapping XS 5ac23f34
END DESCRIPTION:
XS GIS Cut Line= 4
      2711615.63      6947844.35      2710468.41      6948705.52
      2710005.55      6949054.42      2709113.56      6950016.27
#Sta/Elev= 30
  2996.1  506.96  3129.5  505.47  3144.1  508.21  3164.9  499.68  3308.2  497.23
  3429.5  486.47  3508.3  481.86  4408.5  481.73  4421.1  484.89  4435.6  483.33
  4471.2  490.74  4500.1  492.43  4925.2  491.02  4958.1  490.22  4985.2   492.1
  4993.5  489.96  5007.7  480.99  5009.7  480.49  5021.5  480.99  5035.6  481.81
    5043  487.11    5064  488.81  5155.1  490.61  5319.1  496.43  5368.4  494.82
  5382.6  496.65  5389.4  499.75  5403.6  497.78  5743.2  502.15    6322  504.15
#Mann= 5 ,-1 , 0
  2996.1     .05       0  4925.2     .12       0  5007.7     .07       0
  5021.5     .12       0  5155.1     .05       0
Bank Sta=5007.7,5021.5
XS Rating Curve= 0 ,0
Exp/Cntr=0.3,0.1

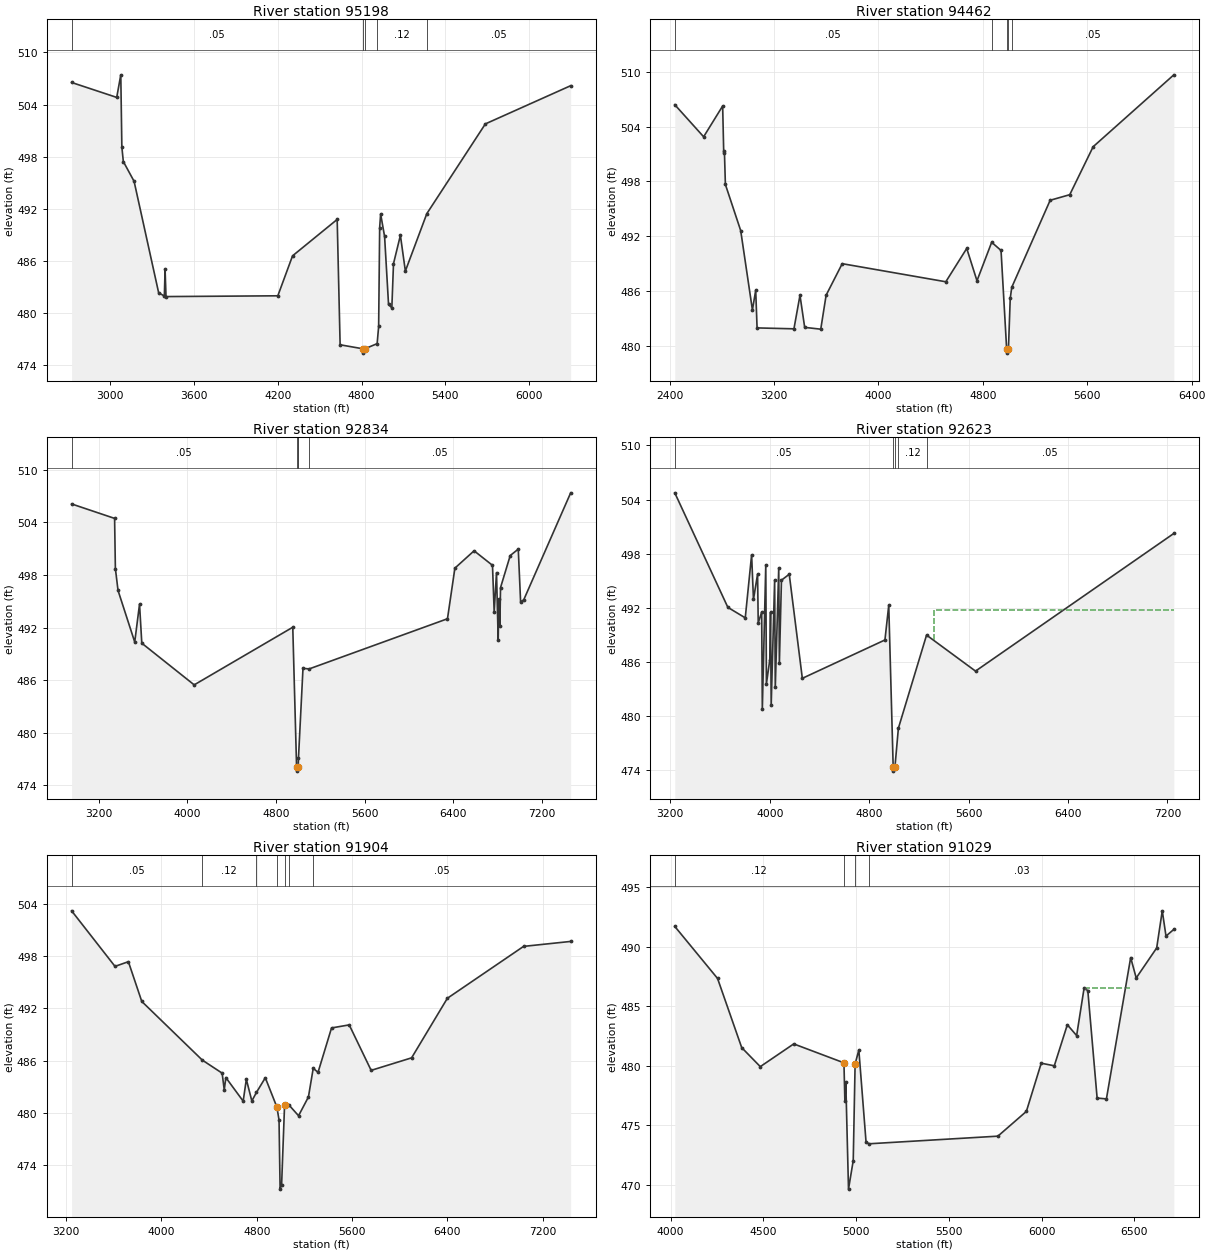
Type RM Length L Ch R = 1 ,95198   ,736,736,736
BEGIN DESCRIPTION:
Mapping XS aef6df52
END DESCRIPTION:
XS GIS Cut Line= 5
       2711777.7      6947640.28      2711456.12      6947775.75
      2710135.65      6948212.99      2709735.25      6948593.44
      2708821.55      6949490.35
#Sta/Elev= 30
  2724.6  506.54  3047.5  504.82  3076.6  507.42  3084.2  499.12  3094.7  497.44
  3171.8  495.16  3347.6  482.33  3388.4  481.95  3393.7  485.01  3400.2  481.89
  4200.8  481.98  4306.1  486.58  4625.6  490.77  4646.7  476.34  4809.6  475.88
  4811.6  475.38  4823.5  475.88  4911.7  476.47  4922.5  478.45  4929.8  489.84
  4936.7   491.4    4965  488.82  4993.3  480.99  5016.9  480.59  5028.8  485.68
  5078.2  488.94  5113.7  484.83  5267.4  491.44  5686.4  501.77  6297.2  506.17
#Mann= 5 ,-1 , 0
  2724.6     .05       0  4809.6     .07       0  4823.5     .05       0
  4911.7     .12       0  5267.4     .05       0
Bank Sta=4809.6,4823.5
XS Rating Curve= 0 ,0
Exp/Cntr=0.3,0.1

Type RM Length L Ch R = 1 ,94462   ,1628,1628,1628
BEGIN DESCRIPTION:
Mapping XS b19c8165
END DESCRIPTION:
XS GIS Cut Line= 6
      2711808.33      6947580.38       2711211.5      6947748.48
      2710311.52      6947567.61      2709506.21      6948047.01
      2709326.34      6948068.87      2708395.37      6948766.13
#Sta/Elev= 30
  2439.7  506.39  2660.8  502.88  2806.6  506.25  2814.8  501.11    2820   501.3
  2827.5  497.66  2944.8  492.61  3034.6  483.93  3059.8  486.07  3070.3  481.96
  3352.8  481.86    3399  485.53    3435  482.02  3558.2  481.82  3599.3  485.54
  3722.6  488.99  4516.4  487.01  4676.7  490.66  4755.2  487.12  4867.7  491.33
  4939.5  490.44  4982.3   479.7  4984.3   479.2  4996.3   479.7    5010   485.2
  5021.8  486.41  5315.9  495.93    5466  496.54  5645.2  501.79  6263.5  509.66
#Mann= 5 ,-1 , 0
  2439.7     .05       0  4867.7     .12       0  4982.3     .07       0
  4996.3     .12       0  5021.8     .05       0
Bank Sta=4982.3,4996.3
XS Rating Curve= 0 ,0
Exp/Cntr=0.3,0.1

Type RM Length L Ch R = 1 ,92834   ,211,211,211
BEGIN DESCRIPTION:
Mapping XS 5d77df8e
END DESCRIPTION:
XS GIS Cut Line= 6
      2711816.84      6947528.63      2711426.08      6947649.51
      2710599.87      6947444.36      2709824.32       6946785.8
      2708721.85      6947293.03      2708175.98      6948136.85
#Sta/Elev= 30
  2953.5  506.11  3341.7  504.46  3348.8  498.73  3372.8  496.23  3523.6  490.34
  3566.9  494.67  3587.4  490.21  4060.7  485.45  4951.1  492.03  4985.5   476.1
  4987.5   475.6    5000   476.1  5002.6  477.08  5043.4  487.34  5098.6  487.27
  6348.5     493  6415.5  498.78  6588.9  500.76  6755.1   499.1  6770.3  493.81
  6791.4  498.27  6806.6  490.56  6812.5  495.23  6821.7  492.16  6827.7  496.56
  6915.4  500.22  6987.9  500.95  7009.1  494.92  7037.6  495.17  7461.4  507.38
#Mann= 5 ,-1 , 0
  2953.5     .05       0  4985.5     .05       0    5000     .05       0
  5002.6     .12       0  5098.6     .05       0
Bank Sta=4985.5,5000
XS Rating Curve= 0 ,0
Exp/Cntr=0.3,0.1

Type RM Length L Ch R = 1 ,92623   ,719,719,719
BEGIN DESCRIPTION:
Mapping XS adbd2e30
END DESCRIPTION:
XS GIS Cut Line= 6
      2711797.07       6947339.4      2711339.92      6947480.41
      2710903.68      6947349.16      2710292.64      6947019.08
      2709808.46      6946583.68       2708122.7      6946666.27
#Sta/Elev= 30
    3236  504.75  3663.2  492.06  3803.2   490.9  3854.3  497.88  3869.2  492.94
  3902.3  495.75  3907.5  490.34  3935.3  491.54  3940.5  480.76  3968.3  496.78
  3973.5   483.6  4000.5  486.24  4006.5  491.51  4011.8  481.22  4039.6  495.08
  4044.8   483.2  4072.6  496.44  4077.8   485.9  4094.4  495.07  4157.1  495.73
  4262.4   484.2  4927.2  488.45  4957.8  492.29  4993.4  474.42  4995.4  473.92
  5007.9  474.42  5035.3  478.67  5262.1  488.99    5656     485  7251.9  500.25
#Mann= 5 ,-1 , 0
    3236     .05       0  4993.4     .05       0  5007.9     .05       0
  5035.3     .12       0  5262.1     .05       0
#XS Ineff= 2 , 0
       0                  5318.8       0  491.73
Permanent Ineff=
       F       F
Bank Sta=4993.4,5007.9
XS Rating Curve= 0 ,0
Exp/Cntr=0.3,0.1

Type RM Length L Ch R = 1 ,91904   ,875,875,875
BEGIN DESCRIPTION:
Mapping XS 6f1c4f5b
END DESCRIPTION:
XS GIS Cut Line= 5
       2712212.3       6946794.8      2710650.34      6946353.73
      2710344.79      6946468.31      2709427.86      6946579.28
      2708110.45      6946583.72
#Sta/Elev= 30
  3245.5  503.22  3609.8  496.83  3722.1  497.37  3834.5   492.8  4342.8  486.05
  4509.4  484.55    4527  482.62  4540.5  484.04    4686  481.33  4712.5  483.84
  4758.7  481.35  4797.3  482.33  4871.8  484.02  4969.3  480.64  4987.1  479.15
    4996  471.21  5008.7  471.71  5033.4  480.84  5068.2  480.92  5150.9  479.65
  5233.9  481.81  5274.2  485.11  5314.5  484.64  5427.9  489.75  5576.4   490.1
  5760.5  484.87  6100.2  486.31  6400.3  493.16  7040.4  499.13  7435.9   499.7
#Mann= 7 ,-1 , 0
  3245.5     .05       0  4342.8     .12       0  4797.3      .1       0
  4969.3     .07       0  5033.4      .1       0  5068.2     .12       0
  5274.2     .05       0
#XS Ineff= 2 , 0
       0                  5576.4       0   490.1
Permanent Ineff=
       F       F
Bank Sta=4969.3,5033.4
XS Rating Curve= 0 ,0
Exp/Cntr=0.3,0.1

Type RM Length L Ch R = 1 ,91029   ,398,398,398
BEGIN DESCRIPTION:
Mapping XS d80cc4c3
END DESCRIPTION:
XS GIS Cut Line= 3
      2711156.11      6945853.55      2710304.51       6945800.6
      2708473.85      6945956.09
#Sta/Elev= 30
  4022.6   491.7  4253.2  487.33  4383.4  481.52  4483.6  479.92  4663.9  481.83
  4934.6  480.24  4939.6  477.07  4944.6  478.61  4959.2  469.63  4984.7  472.03
  4994.8  480.14  5014.9  481.32  5053.9  473.56  5070.8  473.44  5764.6  474.08
  5918.1  476.16  5998.2  480.21  6068.6  479.99  6138.9  483.44  6189.1  482.53
  6229.2  486.51  6249.3  486.31  6299.5  477.28  6349.6  477.21  6480.4  489.08
  6510.2  487.37  6620.6  489.89  6650.7  493.01  6670.8  490.89  6713.1  491.45
#Mann= 4 ,-1 , 0
  4022.6     .12       0  4934.6     .07       0  4994.8     .12       0
  5070.8     .03       0
#XS Ineff= 2 ,-1
  5014.9    6100  481.32  6241.8    6475  486.49
Permanent Ineff=
       T       F
Bank Sta=4934.6,4994.8
XS Rating Curve= 0 ,0
Exp/Cntr=0.3,0.1

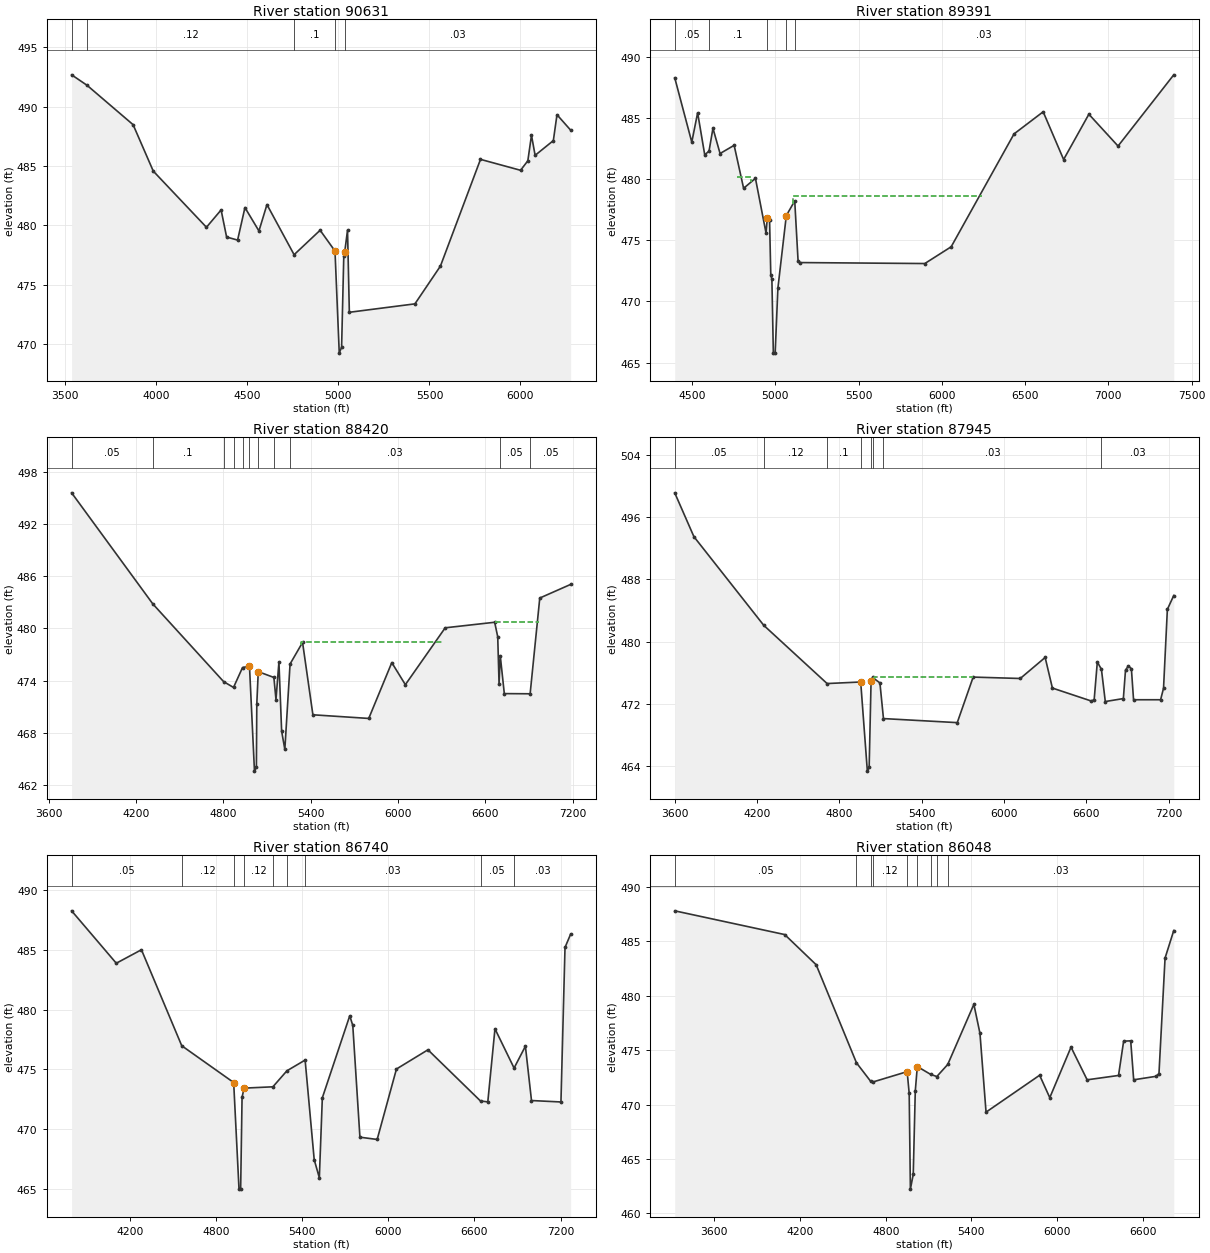
Type RM Length L Ch R = 1 ,90631   ,1240,1240,1240
BEGIN DESCRIPTION:
Mapping XS c21ed2fb
END DESCRIPTION:
XS GIS Cut Line= 3
      2711581.39      6945636.53      2710144.79      6945467.27
        2708851.        6945436.
#Sta/Elev= 30
  3534.7  492.68  3619.3   491.8  3872.4  488.48  3983.2  484.57  4275.2  479.84
  4355.7   481.3  4385.9  479.02  4446.3  478.76  4486.6   481.5  4563.5  479.53
  4607.5  481.75  4756.6  477.53  4899.5  479.59  4981.2  477.84  5004.6  469.24
  5017.5  469.74  5029.4  477.38  5034.4  477.73    5050   479.6    5060  472.68
  5420.2  473.39  5560.2  476.57  5780.3  485.56  6000.3  484.64  6040.3  485.44
  6060.3  487.59  6080.3   485.9  6180.4  487.14  6200.4  489.32  6275.4  488.02
#Mann= 5 ,-1 , 0
  3534.7     .05       0  3619.3     .12       0  4756.6      .1       0
  4981.2     .07       0  5034.4     .03       0
#XS Ineff= 1 ,-1
    5050    5700   479.6
Permanent Ineff=
       T
Bank Sta=4981.2,5034.4
XS Rating Curve= 0 ,0
Exp/Cntr=0.3,0.1

Type RM Length L Ch R = 1 ,89391   ,971,971,971
BEGIN DESCRIPTION:
Mapping XS 3b9dbffb
END DESCRIPTION:
XS GIS Cut Line= 4
      2711303.62      6945337.44      2710814.06      6944906.91
      2709603.69      6944732.59      2708574.08      6945179.21
#Sta/Elev= 30
  4395.4  488.28  4497.8  483.02    4533  485.42  4575.6  481.98  4601.4  482.29
    4625  484.15  4667.7  482.09  4752.2  482.76  4809.1  479.25  4880.2  480.06
  4943.8  475.59  4951.4  476.86  4964.9  476.69  4972.3  472.16  4978.9  471.83
  4987.7  465.78  4998.6  465.78  5014.9  471.08  5065.6  477.02  5116.1  478.22
  5136.3   473.3  5146.4  473.18  5897.3   473.1  6055.7  474.47  6433.1  483.69
  6608.2   485.5    6731   481.6  6882.7   485.3  7057.9   482.7  7392.5  488.52
#Mann= 5 ,-1 , 0
  4395.4     .05       0  4601.4      .1       0  4951.4     .07       0
  5065.6      .1       0  5116.1     .03       0
#XS Ineff= 2 ,-1
    5106    6243  478.58    4770  4851.8  480.16
Permanent Ineff=
       T       F
Bank Sta=4951.4,5065.6
XS Rating Curve= 0 ,0
Exp/Cntr=0.3,0.1

Type RM Length L Ch R = 1 ,88420   ,475,475,475
BEGIN DESCRIPTION:
Mapping XS 3fd3d28c
END DESCRIPTION:
XS GIS Cut Line= 4
      2711684.57      6943827.11      2710471.17      6944112.64
      2709593.62      6944261.37      2708517.26      6944975.28
#Sta/Elev= 30
    3758  495.62    4316  482.82  4802.3  473.87  4870.2   473.2  4932.1  475.49
  4979.9  475.65  5014.2  463.56  5027.4  464.06  5030.1  471.28  5040.2  475.02
  5147.5  474.35  5161.9  471.81  5182.2  476.12  5200.8  468.16  5222.8  466.06
  5258.7   475.9  5344.5  478.39  5415.5  470.05  5799.2  469.63  5957.5  476.06
  6050.7  473.52  6324.4  480.07  6664.3  480.71  6685.3  479.03  6694.4  473.64
  6702.8  476.84  6730.5  472.49  6907.9  472.47  6974.1   483.5  7186.2  485.07
#Mann= 11 ,-1 , 0
    3758     .05       0    4316      .1       0  4802.3      .1       0
  4870.2      .1       0  4932.1     .12       0  4979.9     .07       0
  5040.2     .12       0  5147.5     .12       0  5258.7     .03       0
  6702.8     .05       0  6907.9     .05       0
#XS Ineff= 2 ,-1
  5334.4    6300  478.49    6664    6970  480.71
Permanent Ineff=
       T       F
Bank Sta=4979.9,5040.2
XS Rating Curve= 0 ,0
Exp/Cntr=0.3,0.1

Type RM Length L Ch R = 1 ,87945   ,1205,1205,1205
BEGIN DESCRIPTION:
Mapping XS 3c536834
END DESCRIPTION:
XS GIS Cut Line= 3
      2711716.85        6943505.      2710349.65      6943708.99
      2708405.86      6944853.23
#Sta/Elev= 30
  3599.5  499.11  3739.3  493.48  4248.5  482.09  4710.3  474.61  4955.2  474.81
  5003.7  463.36  5016.9  463.86  5030.9  474.96  5041.5   475.4  5095.3  474.69
  5121.2  470.11  5659.1  469.59  5775.1  475.44  6118.4  475.26  6299.9  477.96
  6352.7  474.03  6635.7  472.37  6657.2  472.53  6680.2  477.38  6710.1  476.44
  6738.3   472.3    6870  472.68  6885.7  476.34  6907.1  476.88  6928.6   476.5
  6944.3  472.53  7141.5  472.53  7162.9  474.01  7190.8  484.14  7237.4  485.92
#Mann= 8 ,-1 , 0
  3599.5     .05       0  4248.5     .12       0  4710.3      .1       0
  4955.2     .07       0  5030.9     .12       0  5041.5      .1       0
  5121.2     .03       0  6710.1     .03       0
#XS Ineff= 2 ,-1
  5052.3  5775.1  475.44  6299.9    7200  477.96
Permanent Ineff=
       T       T
Bank Sta=4955.2,5030.9
XS Rating Curve= 0 ,0
Exp/Cntr=0.3,0.1

Type RM Length L Ch R = 1 ,86740   ,692,692,692
BEGIN DESCRIPTION:
Mapping XS e0bae30e
END DESCRIPTION:
XS GIS Cut Line= 3
      2711039.73      6942567.51      2709980.72      6943196.84
      2708330.39      6944721.05
#Sta/Elev= 30
  3791.8  488.27  4103.2  483.88  4278.5  485.01  4559.4  476.97  4921.4  473.89
  4958.6  464.96    4970  464.96  4979.9  472.66  4994.3  473.42  5194.7  473.53
  5292.4  474.87  5419.4  475.77  5482.7  467.43  5518.5  465.91  5539.4  472.61
  5730.5  479.48  5751.6  478.67  5801.4  469.31  5921.6  469.12    6056  475.02
  6275.5  476.63    6642  472.34  6692.8  472.27  6742.7  478.39  6875.9   475.1
  6954.8  476.93  6997.3  472.38  7202.6  472.26  7230.9   485.2  7270.2  486.32
#Mann= 9 ,-1 , 0
  3791.8     .05       0  4559.4     .12       0  4921.4     .07       0
  4994.3     .12       0  5194.7     .03       0  5292.4     .12       0
  5419.4     .03       0    6642     .05       0  6875.9     .03       0
#XS Ineff= 2 , 0
       0                  5730.5       0  479.48
Permanent Ineff=
       F       F
Bank Sta=4921.4,4994.3
XS Rating Curve= 0 ,0
Exp/Cntr=0.3,0.1

Type RM Length L Ch R = 1 ,86048   ,588,588,588
BEGIN DESCRIPTION:
Mapping XS b101a127
END DESCRIPTION:
XS GIS Cut Line= 3
      2710845.34      6942232.41      2709532.81       6943024.1
      2708075.28      6944336.29
#Sta/Elev= 30
  3322.8  487.79  4092.8  485.61    4313  482.84  4595.3  473.83  4695.3  472.12
  4710.5  472.07  4950.2  473.02  4964.4  471.02  4972.8  462.23  4992.8  463.58
    5007  471.22  5021.2  473.49  5114.3  472.77  5157.8  472.57  5234.3  473.68
  5417.3   479.2  5459.9  476.54  5502.5   469.3  5877.7  472.69  5948.7  470.63
  6097.5  475.27  6210.3  472.27  6430.1  472.67  6465.9  475.82  6515.3  475.85
  6536.2  472.27  6692.4  472.59  6713.3  472.84  6755.9  483.45  6816.8  485.98
#Mann= 9 ,-1 , 0
  3322.8     .05       0  4595.3     .12       0  4695.3     .03       0
  4710.5     .12       0  4950.2     .07       0  5021.2     .12       0
  5114.3     .03       0  5157.8     .12       0  5234.3     .03       0
#XS Ineff= 2 , 0
       0                  5417.3       0   479.2
Permanent Ineff=
       F       F
Bank Sta=4950.2,5021.2
XS Rating Curve= 0 ,0
Exp/Cntr=0.3,0.1

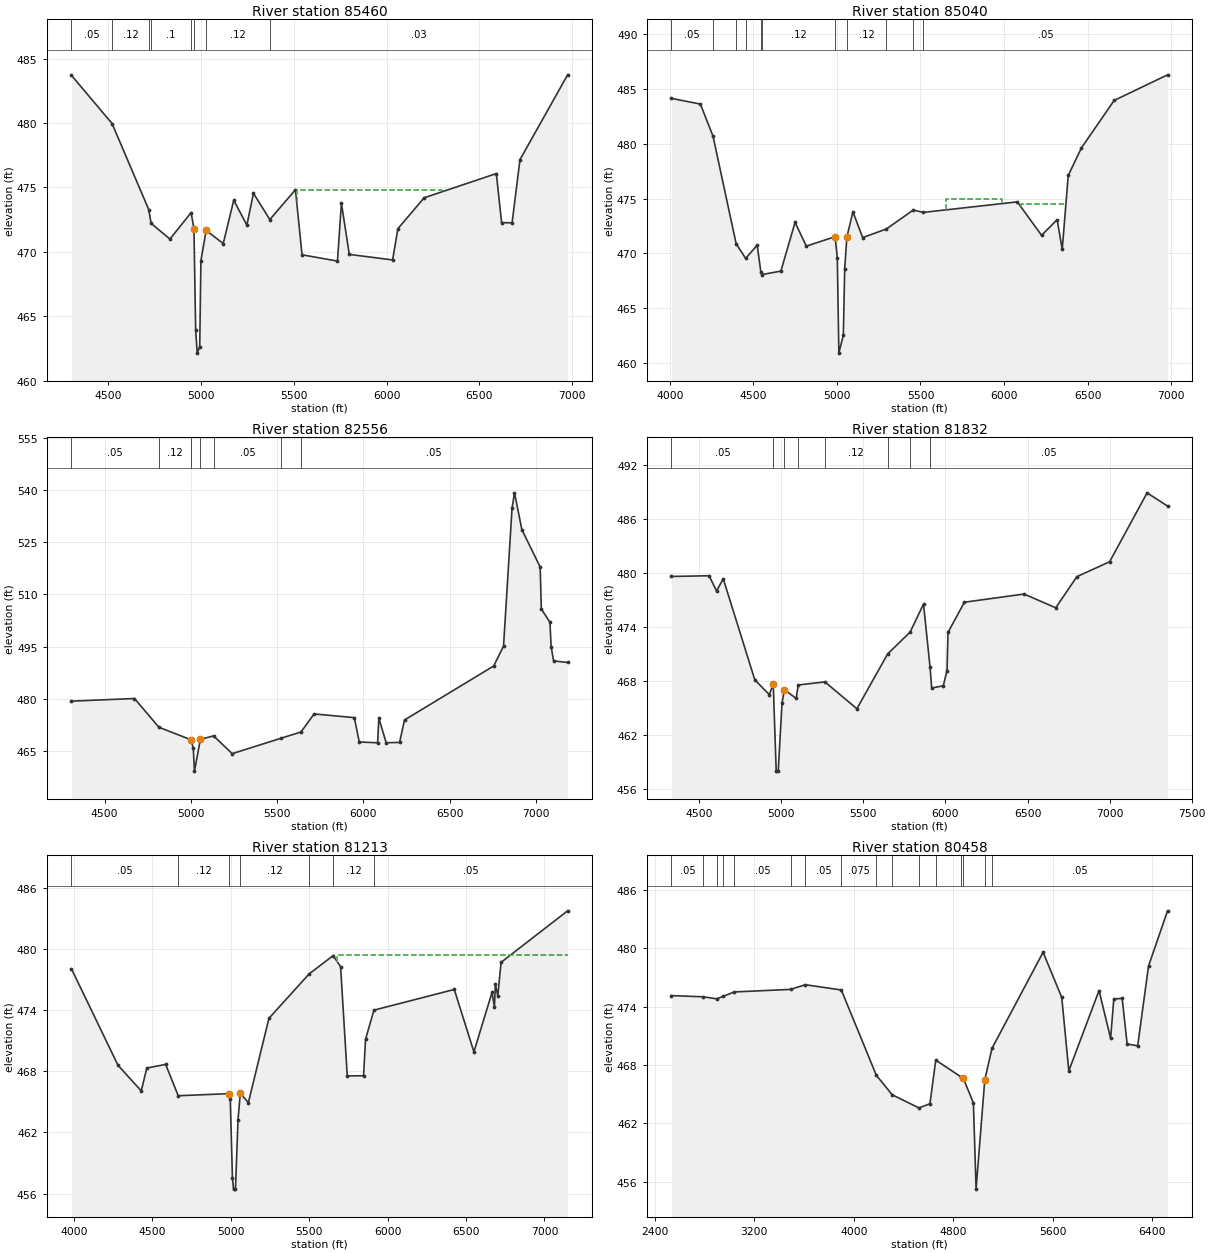
Type RM Length L Ch R = 1 ,85460   ,420,420,420
BEGIN DESCRIPTION:
Mapping XS 945372b3
END DESCRIPTION:
XS GIS Cut Line= 3
      2709866.12       6942393.9      2709251.56      6942633.47
      2707822.37      6944050.21
#Sta/Elev= 30
  4303.1   483.7  4521.7  479.96  4719.7  473.27  4731.7  472.22  4833.3     471
  4947.5  473.05  4962.7   471.8  4971.9  463.96  4980.3  462.15  4993.8  462.65
  5000.2  469.33  5028.5  471.67  5120.5  470.65    5177  474.01  5247.7  472.08
  5283.1  474.55  5371.5  472.51  5509.4  474.83  5544.7  469.78  5735.6  469.29
  5756.9  473.78  5799.3  469.81  6032.6  469.38  6060.9   471.8  6202.3   474.2
  6591.2  476.08  6619.5  472.27  6676.1  472.26  6718.5  477.16  6975.1  483.74
#Mann= 8 ,-1 , 0
  4303.1     .05       0  4521.7     .12       0  4719.7     .05       0
  4731.7      .1       0  4947.5     .12       0  4962.7     .07       0
  5028.5     .12       0  5371.5     .03       0
#XS Ineff= 2 ,-1
  6591.2    6710  476.08  5516.5    6300  474.83
Permanent Ineff=
       F       T
Bank Sta=4962.7,5028.5
XS Rating Curve= 0 ,0
Exp/Cntr=0.3,0.1

Type RM Length L Ch R = 1 ,85040   ,2484,2484,2484
BEGIN DESCRIPTION:
Mapping XS c1430199
END DESCRIPTION:
XS GIS Cut Line= 3
      2709902.63      6942258.47      2708925.15      6942416.05
      2707268.31      6943497.23
#Sta/Elev= 30
  4009.9  484.16  4183.3  483.64  4258.8  480.71  4397.2  470.89    4454  469.55
  4523.1  470.76  4545.3  468.29  4550.5  468.07  4664.9  468.39  4749.7  472.84
  4816.8  470.67    4989  471.53  5002.5  469.63  5011.8   460.9  5038.6  462.56
  5046.7  468.59  5059.7   471.5  5095.9   473.8  5154.2  471.45  5295.4  472.23
  5456.6  473.96  5517.6  473.75  6079.6  474.71  6224.4  471.66  6317.9  473.08
  6348.2  470.37  6384.1  477.12  6462.8  479.63  6658.8  483.97  6978.4  486.31
#Mann= 11 ,-1 , 0
  4009.9     .05       0  4258.8     .12       0  4397.2      .1       0
    4454     .12       0  4545.3      .1       0  4550.5     .12       0
    4989     .07       0  5059.7     .12       0  5295.4     .05       0
  5456.6     .12       0  5517.6     .05       0
#XS Ineff= 2 ,-1
  5654.2  5986.1  474.93  6100.7    6370  474.55
Permanent Ineff=
       T       T
Bank Sta=4989,5059.7
XS Rating Curve= 0 ,0
Exp/Cntr=0.3,0.1

Type RM Length L Ch R = 1 ,82556   ,724,724,724
BEGIN DESCRIPTION:
Mapping XS 9f243e29
END DESCRIPTION:
XS GIS Cut Line= 3
      2709032.81       6941091.8      2708529.16      6941577.85
      2706922.83      6943042.57
#Sta/Elev= 30
  4308.6  479.32  4673.6  480.08  4815.1  471.82    4999  468.27  5014.1  465.92
    5021  459.22  5055.2  468.34  5131.7  469.35  5239.7  464.24  5523.7  468.69
  5637.9  470.46    5714  475.65  5947.1  474.59  5975.5  467.59  6081.9  467.36
    6089  474.41  6131.5  467.38  6209.2  467.47  6237.6  473.91  6754.5  489.43
  6811.2  495.13  6860.5   534.7  6874.7  539.17  6917.3  528.61  7023.4  517.85
  7030.1   505.8  7080.1  501.99  7086.9  494.99  7101.1  490.89  7182.4  490.44
#Mann= 7 ,-1 , 0
  4308.6     .05       0  4815.1     .12       0    4999     .07       0
  5055.2     .12       0  5131.7     .05       0  5523.7     .12       0
  5637.9     .05       0
#XS Ineff= 2 , 0
       0                    5714       0  475.65
Permanent Ineff=
       F       F
Bank Sta=4999,5055.2
XS Rating Curve= 0 ,0
Exp/Cntr=0.3,0.1

Type RM Length L Ch R = 1 ,81832   ,619,619,619
BEGIN DESCRIPTION:
Mapping XS efc866d8
END DESCRIPTION:
XS GIS Cut Line= 4
      2708798.41      6940753.27      2708183.85      6941003.26
       2707777.6      6941508.47      2706735.12      6942865.03
#Sta/Elev= 30
  4330.5  479.58  4559.8  479.66  4605.8  477.97  4646.2  479.33  4838.5   468.1
  4926.9  466.46    4951  467.62  4968.9  457.96  4981.2  457.96  5004.4  465.52
  5018.8  467.01  5090.8  466.03  5103.1  467.53  5265.9  467.87  5460.4  464.89
  5647.8  470.97    5785  473.41  5866.3  476.51  5906.2  469.51  5916.1  467.19
  5986.8  467.44  6009.5  469.12  6015.8  473.38  6115.5  476.72  6478.9  477.63
  6671.9   476.1  6800.6  479.56    7000  481.21  7228.4  488.87  7353.1   487.4
#Mann= 8 ,-1 , 0
  4330.5     .05       0    4951     .05       0  5018.8     .12       0
  5103.1      .1       0  5265.9     .12       0  5647.8     .05       0
    5785     .12       0  5906.2     .05       0
#XS Ineff= 2 , 0
       0                  5866.3       0  476.51
Permanent Ineff=
       F       F
Bank Sta=4951,5018.8
XS Rating Curve= 0 ,0
Exp/Cntr=0.3,0.1

Type RM Length L Ch R = 1 ,81213   ,755,755,755
BEGIN DESCRIPTION:
Mapping XS ba8d5458
END DESCRIPTION:
XS GIS Cut Line= 3
      2708444.27      6940070.97      2707709.89      6940748.05
       2706565.8      6942584.09
#Sta/Elev= 30
  3985.6  478.04  4281.9  468.59  4430.5  466.07  4465.6  468.31  4585.8  468.67
    4666   465.6  4989.2   465.8  4997.6  465.32  5011.5  457.58  5018.5  456.44
  5030.8  456.44  5046.9  463.17  5061.3  465.82  5113.2  464.93  5244.2  473.19
  5499.4  477.53  5653.5  479.34  5700.9  478.26  5743.3  467.54  5847.2  467.56
  5859.9  471.13  5913.3  473.99  6425.4  476.02  6550.5   469.9  6666.1  475.73
  6681.5  474.29  6687.3  476.53  6702.7   475.4  6723.9  478.68  7147.8  483.73
#Mann= 7 ,-1 , 0
  3985.6     .05       0    4666     .12       0  4989.2     .07       0
  5061.3     .12       0  5499.4     .05       0  5653.5     .12       0
  5913.3     .05       0
#XS Ineff= 2 , 0
       0                  5679.6       0  479.44
Permanent Ineff=
       F       F
Bank Sta=4989.2,5061.3
XS Rating Curve= 0 ,0
Exp/Cntr=0.3,0.1

Type RM Length L Ch R = 1 ,80458   ,142,142,142
BEGIN DESCRIPTION:
Mapping XS bd03606e
END DESCRIPTION:
XS GIS Cut Line= 4
      2708867.62      6938757.66      2707228.99      6940231.56
      2707100.51       6940466.8      2706599.56      6941897.52
#Sta/Elev= 30
  2534.2  475.15  2790.2  475.03  2897.8  474.82    2947  475.06  3040.4  475.53
  3491.5  475.79  3610.7  476.27  3899.8  475.73  4180.9  466.97  4308.1  464.96
  4524.1   463.6  4612.3  464.03  4658.9  468.52  4858.3  466.82    4880  466.66
  4961.6  464.11    4983  455.25    5053  466.49    5111  469.73  5521.8  479.61
  5671.7  474.96  5728.4  467.41  5971.3  475.67  6064.4  470.76  6090.1   474.8
  6157.4  474.87  6197.3  470.17  6282.1  469.99  6369.3   478.2  6522.1  483.87
#Mann= 16 ,-1 , 0
  2534.2     .05       0  2790.2    .075       0  2897.8     .05       0
    2947    .075       0  3040.4     .05       0  3491.5    .075       0
  3610.7     .05       0  3899.8    .075       0  4180.9     .05       0
  4308.1    .075       0  4524.1     .05       0  4658.9    .075       0
  4858.3     .05       0    4880     .07       0    5053    .075       0
    5111     .05       0
#XS Ineff= 2 , 0
       0                  5521.8       0  479.61
Permanent Ineff=
       F       F
Bank Sta=4880,5053
XS Rating Curve= 0 ,0
Exp/Cntr=0.3,0.1