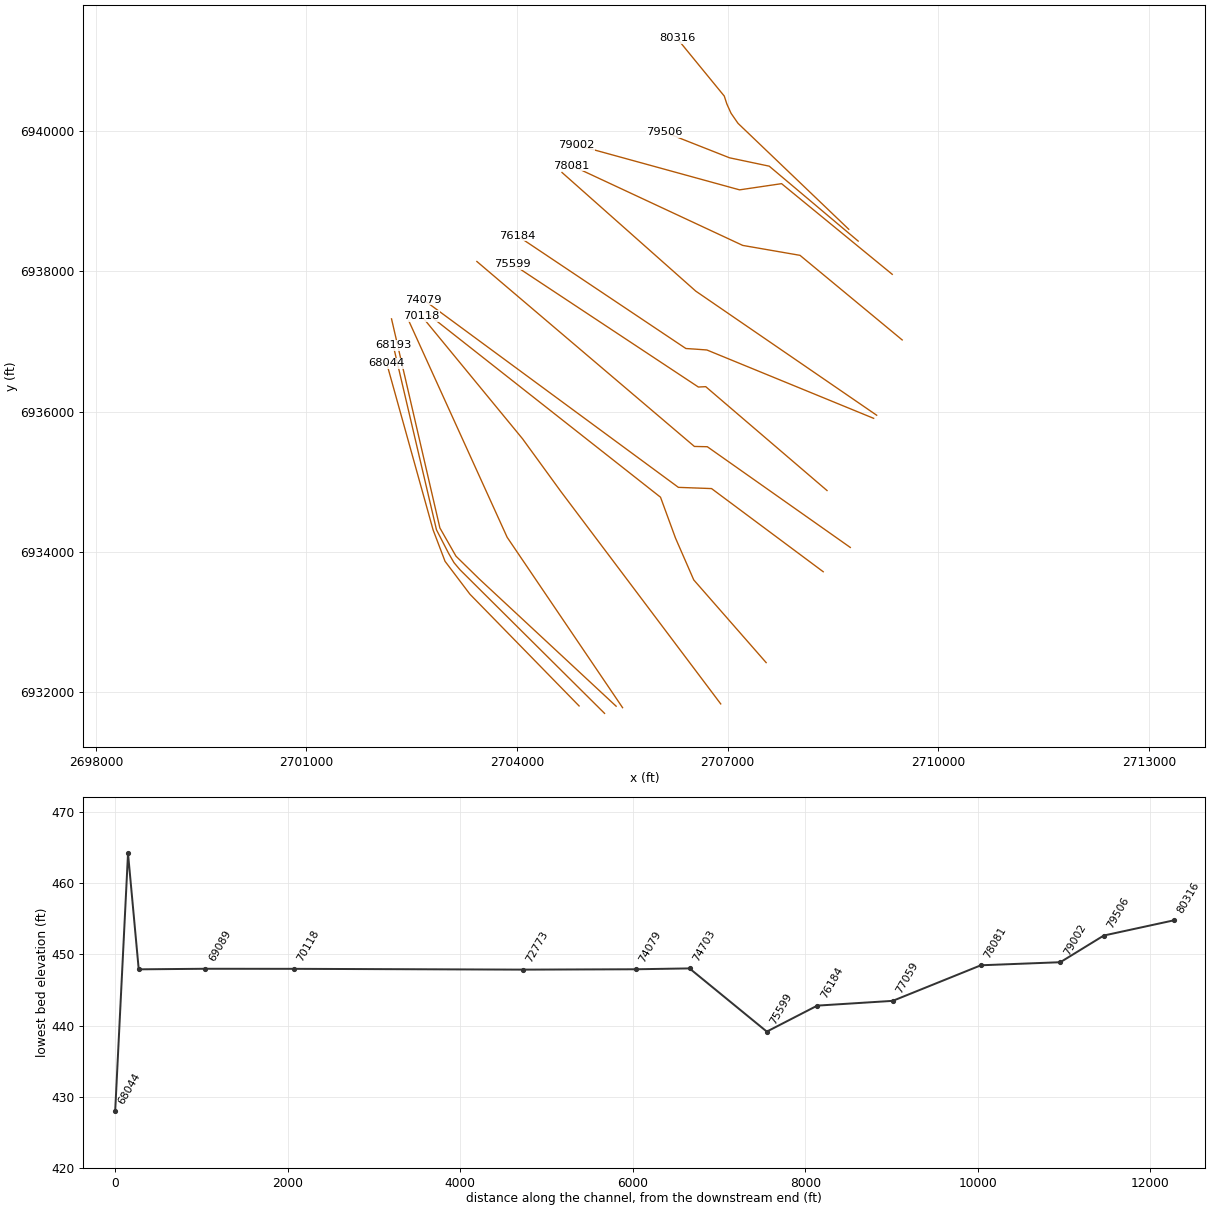
HEC-RAS study Rocky Cedar Creek.prj: Rocky Cedar Creek Base Level Engineering

--- Rocky Cedar Creek.g01 (geometry) --- (continued)

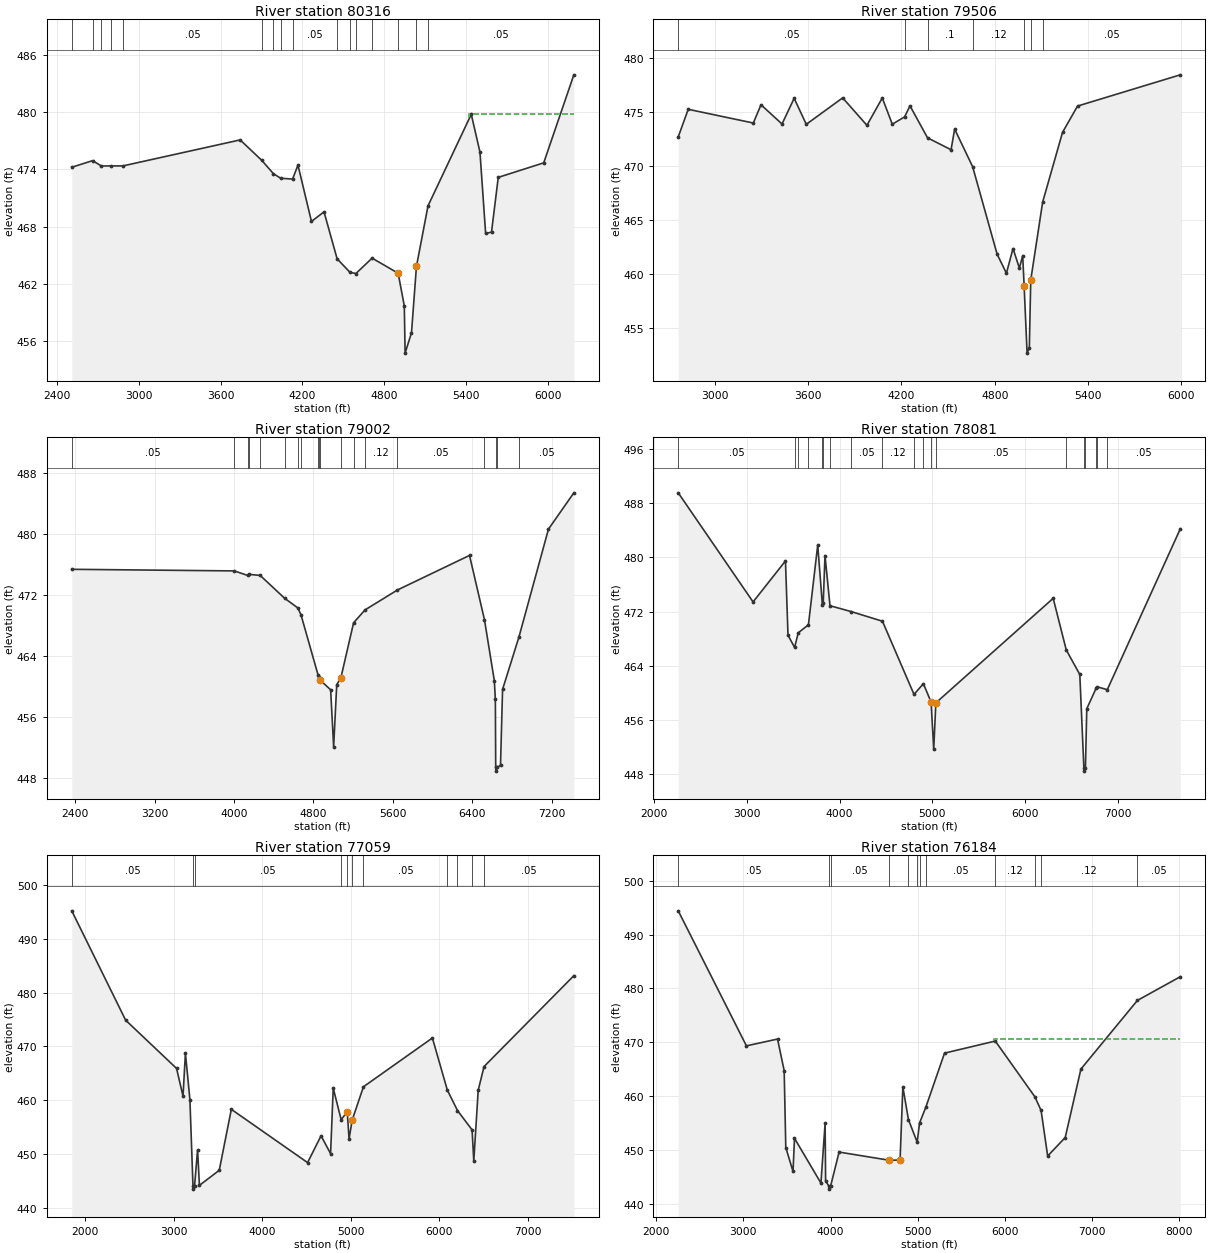
Type RM Length L Ch R = 1 ,80316   ,810,810,810
BEGIN DESCRIPTION:
Mapping XS 701b3059
END DESCRIPTION:
XS GIS Cut Line= 6
      2708724.74      6938601.98      2707146.96      6940112.64
        2707048.      6940255.87       2706988.1      6940388.68
      2706951.64      6940500.66      2706278.24      6941323.77
#Sta/Elev= 30
  2507.3  474.23  2660.1  474.92  2725.1  474.36  2798.2  474.37  2882.8  474.37
  3743.4  477.09  3902.8  474.94  3987.8  473.55  4040.8  473.08  4128.1  472.99
  4167.7  474.45  4266.7  468.56  4358.9  469.56  4455.1  464.65    4549  463.24
  4593.1  463.11  4711.9  464.72    4903  463.14  4948.2  459.72  4954.1  454.78
    5001  456.91  5037.3  463.85  5122.3  470.19  5439.7  479.77  5503.6  475.81
  5545.2   467.3  5588.3  467.44  5637.8  473.17  5971.6  474.69  6192.7   483.9
#Mann= 16 ,-1 , 0
  2507.3     .05       0  2660.1    .075       0  2725.1     .05       0
  2798.2    .075       0  2882.8     .05       0  3902.8    .075       0
  3987.8     .05       0  4040.8    .075       0  4128.1     .05       0
  4455.1    .075       0    4549     .05       0  4593.1    .075       0
  4711.9     .05       0    4903     .07       0  5037.3    .075       0
  5122.3     .05       0
#XS Ineff= 2 , 0
       0                  5425.3       0  479.85
Permanent Ineff=
       F       F
Bank Sta=4903,5037.3
XS Rating Curve= 0 ,0
Exp/Cntr=0.3,0.1

Type RM Length L Ch R = 1 ,79506   ,504,504,504
BEGIN DESCRIPTION:
Rocky Cedar Creek 65.0
END DESCRIPTION:
XS GIS Cut Line= 4
      2708858.96       6938433.6      2707591.79      6939501.54
      2707026.52      6939620.78      2706101.05      6939985.98
#Sta/Elev= 30
  2764.2  472.66  2828.5  475.21  3247.2  473.94  3296.6  475.63  3431.8  473.85
  3509.9  476.23  3587.9  473.82    3822  476.27    3978  473.73  4076.9  476.26
  4141.2  473.83  4220.3  474.51    4255  475.53    4368  472.57  4519.3  471.47
  4542.3  473.38  4658.1   469.9  4815.6   461.8  4875.4  460.04  4917.8  462.33
  4958.7  460.52  4980.1  461.67  4989.4  458.83  5008.3  452.65  5022.8  453.15
  5031.9  459.41  5108.4  466.62  5236.4  473.08  5332.9  475.51    5994   478.4
#Mann= 7 ,-1 , 0
  2764.2     .05       0  4220.3     .12       0    4368      .1       0
  4658.1     .12       0  4989.4     .07       0  5031.9     .12       0
  5108.4     .05       0
Bank Sta=4989.4,5031.9
XS Rating Curve= 0 ,0
Exp/Cntr=0.3,0.1

Type RM Length L Ch R = 1 ,79002   ,921,921,921
BEGIN DESCRIPTION:
Mapping XS bf747fbf
END DESCRIPTION:
XS GIS Cut Line= 4
      2709344.36      6937959.82      2707767.66      6939252.15
      2707169.52      6939163.85      2704844.05      6939803.47
#Sta/Elev= 30
  2366.4  475.34  4002.6  475.13  4139.5  474.53  4149.6  474.68  4263.2  474.54
  4509.2  471.55  4642.5  470.28  4674.3  469.38  4847.4  461.44  4851.5  461.29
  4862.3  460.88  4972.8  459.56  5003.1  452.08  5034.1  460.23  5075.6  461.11
    5204  468.34  5318.9  470.02  5645.2  472.63    6371  477.16  6521.3  468.76
  6620.9  460.75  6631.3  458.32  6634.8   449.4  6636.8   448.9  6651.3   449.4
  6683.1  449.67  6703.9  459.61  6868.5  466.46  7166.2  480.61  7421.5  485.36
#Mann= 19 ,-1 , 0
  2366.4     .05       0  4002.6     .12       0  4139.5     .05       0
  4149.6     .12       0  4263.2     .05       0  4509.2     .12       0
  4642.5      .1       0  4674.3     .12       0  4847.4      .1       0
  4851.5     .12       0  4862.3     .07       0  5075.6     .12       0
    5204      .1       0  5318.9     .12       0  5645.2     .05       0
  6521.3     .12       0  6634.8     .07       0  6651.3     .12       0
  6868.5     .05       0
#XS Ineff= 2 , 0
       0                    6371       0  477.16
Permanent Ineff=
       F       F
Bank Sta=4862.3,5075.6
XS Rating Curve= 0 ,0
Exp/Cntr=0.3,0.1

Type RM Length L Ch R = 1 ,78081   ,1022,1022,1022
BEGIN DESCRIPTION:
Mapping XS 2ae6e8e6
END DESCRIPTION:
XS GIS Cut Line= 4
      2709485.88      6937024.48      2708030.38      6938230.34
       2707214.4      6938371.84      2704774.51      6939510.97
#Sta/Elev= 30
    2261  489.54  3067.6  473.44  3416.6  479.49    3444  468.53  3515.1  466.72
  3554.3  468.88  3664.2  470.07  3764.4  481.85  3814.5  472.98  3823.8  473.35
  3842.6  480.28  3896.5  472.88  4123.7  472.02    4462  470.59  4802.1  459.79
    4903  461.38  4986.1  458.66  5014.5  451.67  5037.3  458.54  6301.9  473.97
  6442.9  466.35  6588.8  462.73  6632.6  448.97  6634.6  448.47  6649.6  448.97
    6664  457.68    6767  460.77  6774.4  460.92  6884.9  460.49    7672  484.23
#Mann= 19 ,-1 , 0
    2261     .05       0  3515.1      .1       0  3554.3     .12       0
  3664.2     .05       0  3814.5     .12       0  3823.8     .05       0
  3896.5     .12       0  4123.7     .05       0    4462     .12       0
  4802.1     .05       0    4903     .12       0  4986.1     .07       0
  5037.3     .05       0  6442.9     .12       0  6632.6     .07       0
  6649.6     .12       0    6767      .1       0  6774.4     .12       0
  6884.9     .05       0
#XS Ineff= 2 , 0
       0                  6301.9       0  473.97
Permanent Ineff=
       F       F
Bank Sta=4986.1,5037.3
XS Rating Curve= 0 ,0
Exp/Cntr=0.3,0.1

Type RM Length L Ch R = 1 ,77059   ,875,875,875
BEGIN DESCRIPTION:
Mapping XS c56414d2
END DESCRIPTION:
XS GIS Cut Line= 3
      2709122.33      6935951.12        2706546.      6937719.76
      2704640.43      6939411.26
#Sta/Elev= 30
  1848.2  495.19  2456.9  474.87  3032.4   465.9  3105.2  460.73  3132.3  468.73
    3183  460.11    3218  443.97    3220  443.47    3235  443.97  3269.7  450.74
  3290.6  444.17  3514.6  446.97  3651.1   458.3  4512.7   448.4    4665  453.38
  4772.6  450.06  4802.4  462.24  4892.1  456.37  4960.8  457.87  4981.2  452.77
  5016.4  456.29  5143.8  462.49  5922.9  471.56  6091.9  461.87  6206.3  458.08
  6371.4  454.48  6390.6  448.69  6440.6  461.85  6506.6  466.25  7521.2  483.14
#Mann= 11 ,-1 , 0
  1848.2     .05       0    3218     .07       0    3235     .05       0
  4892.1      .1       0  4960.8     .03       0  5016.4     .03       0
  5143.8     .05       0  6091.9     .12       0  6206.3      .1       0
  6371.4     .12       0  6506.6     .05       0
#XS Ineff= 2 , 0
       0                  5922.9       0  471.56
Permanent Ineff=
       F       F
Bank Sta=4960.8,5016.4
XS Rating Curve= 0 ,0
Exp/Cntr=0.3,0.1

Type RM Length L Ch R = 1 ,76184   ,585,585,585
BEGIN DESCRIPTION:
Mapping XS 525de4a3
END DESCRIPTION:
XS GIS Cut Line= 5
      2709079.39      6935906.84      2706703.96      6936881.23
      2706539.06      6936893.37      2706404.69       6936902.1
       2704003.6      6938509.73
#Sta/Elev= 30
  2253.4  494.39  3035.3  469.36    3392  470.62  3468.2  464.76  3486.7  450.51
  3569.5  446.08  3586.5  452.22  3889.7  443.92  3937.7  455.03  3943.2  444.36
  3982.5   443.3  3984.5   442.8  3999.6   443.3  4097.8  449.67  4674.1  448.15
  4797.1  448.18  4828.9  461.75  4893.4  455.67  4993.5   451.5  5020.2  455.04
  5092.2  457.97  5306.8  468.01  5888.8  470.25  6343.2  459.91  6414.2  457.38
  6489.6  448.94  6690.8  452.37  6870.9  465.06  7518.4  477.78  8010.5  482.18
#Mann= 12 ,-1 , 0
  2253.4     .05       0  3982.5     .04       0  3999.6     .05       0
  4674.1     .03       0  4893.4     .12       0  4993.5     .05       0
  5020.2     .12       0  5092.2     .05       0  5888.8     .12       0
  6343.2      .1       0  6414.2     .12       0  7518.4     .05       0
#XS Ineff= 2 , 0
       0                  5877.2       0  470.61
Permanent Ineff=
       F       F
Bank Sta=4674.1,4797.1
XS Rating Curve= 0 ,0
Exp/Cntr=0.3,0.1

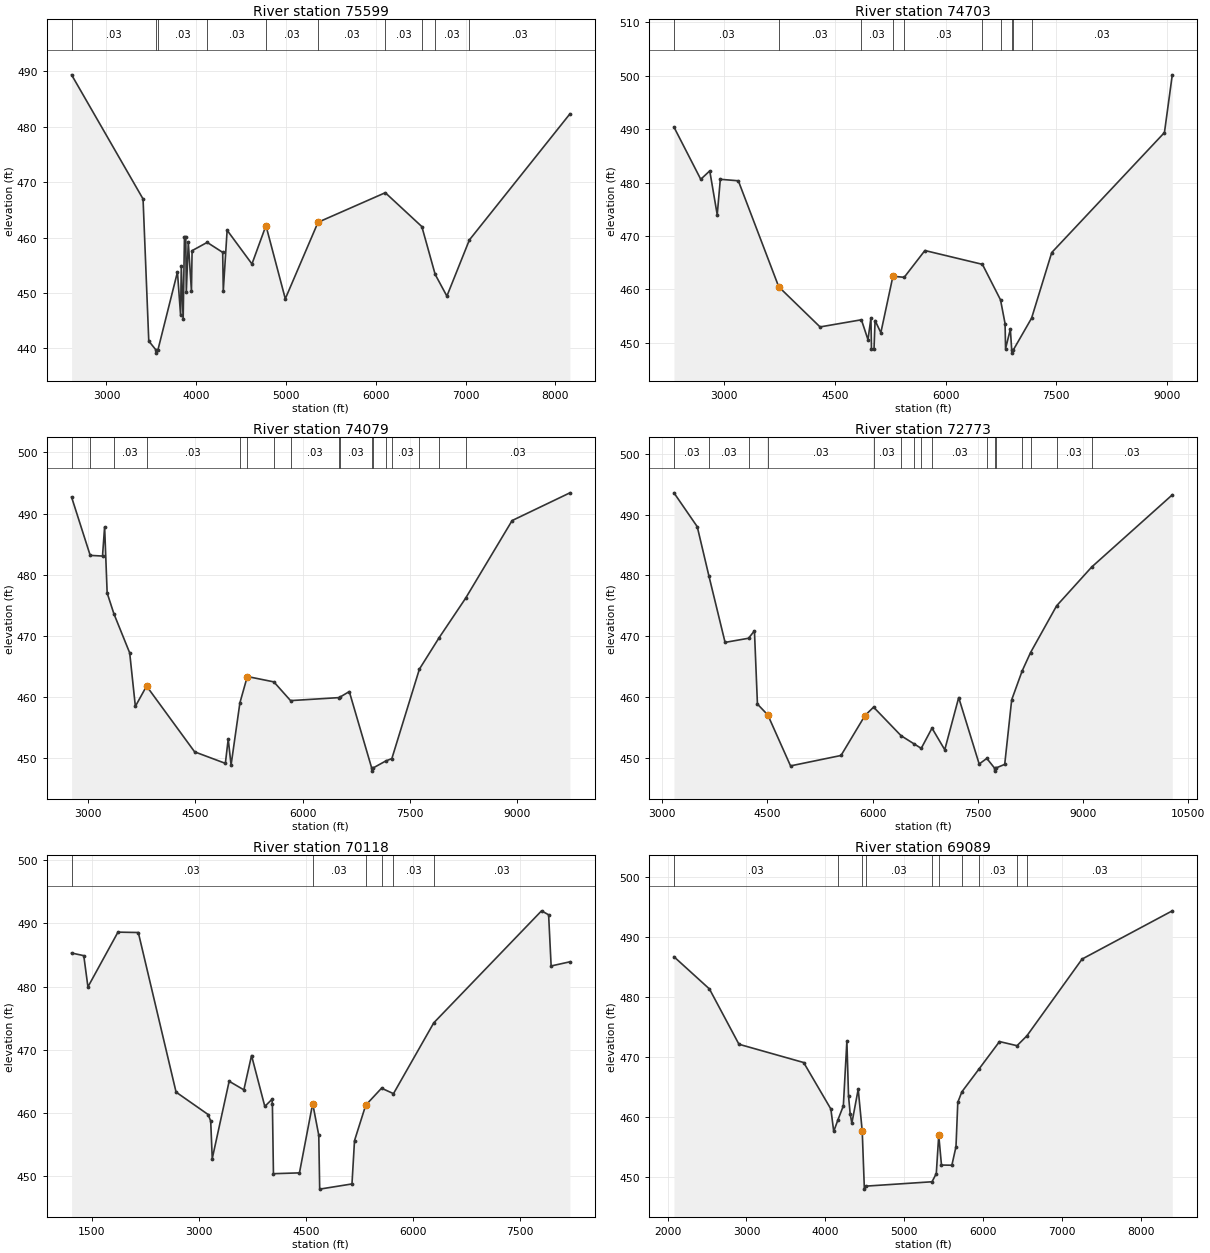
Type RM Length L Ch R = 1 ,75599   ,896,896,896
BEGIN DESCRIPTION:
Mapping XS 8de68344
END DESCRIPTION:
XS GIS Cut Line= 4
      2708415.14      6934877.76      2706687.32       6936358.3
       2706582.6      6936353.15       2703939.5      6938103.22
#Sta/Elev= 30
  2611.9  489.34  3407.9  466.95  3471.6  441.33  3555.2  439.65  3557.2  439.15
  3572.3  439.65    3791  453.77  3826.1  445.95  3833.8   454.9  3854.6  445.22
  3868.9  460.14  3883.2  460.18  3889.8  450.25  3911.7  459.17  3946.8  450.35
    3954  457.63    4122  459.12  4294.8  457.32  4301.4  450.38  4344.2  461.31
  4620.8  455.23  4776.6  462.15  4992.1  448.95  5356.7  462.75  6105.7  468.08
  6512.9  461.97  6661.2  453.35  6791.8  449.43  7042.2  459.56  8162.1   482.3
#Mann= 10 ,-1 , 0
  2611.9     .03       0  3555.2     .03       0  3572.3     .03       0
    4122     .03       0  4776.6     .03       0  5356.7     .03       0
  6105.7     .03       0  6512.9     .03       0  6661.2     .03       0
  7042.2     .03       0
Bank Sta=4776.6,5356.7
XS Rating Curve= 0 ,0
Exp/Cntr=0.3,0.1

Type RM Length L Ch R = 1 ,74703   ,624,624,624
BEGIN DESCRIPTION:
Mapping XS 516bc10f
END DESCRIPTION:
XS GIS Cut Line= 4
      2708746.62      6934066.32        2706710.      6935502.11
      2706526.09      6935505.96      2703427.53      6938142.71
#Sta/Elev= 30
  2324.2   490.4    2687  480.61  2808.9  482.19  2909.9  473.96  2951.8  480.61
  3195.6  480.33  3742.5  460.46  4301.5  452.94  4861.3  454.28  4950.1  450.55
  4990.1  454.62  4997.5  448.81  5031.9  448.84  5046.2  454.14  5124.2  451.86
  5287.8  462.44  5440.6  462.24  5720.5  467.26  6498.8  464.67    6744  458.01
  6805.5  453.56  6812.1  448.87  6876.9  452.52  6895.7  448.53  6897.7  448.03
    6913  448.53  7164.2  454.58    7437  466.88  8962.3  489.37  9068.6  500.19
#Mann= 10 ,-1 , 0
  2324.2     .03       0  3742.5     .03       0  4861.3     .03       0
  5287.8     .03       0  5440.6     .03       0  6498.8     .03       0
    6744     .03       0  6895.7     .03       0    6913     .03       0
  7164.2     .03       0
Bank Sta=3742.5,5287.8
XS Rating Curve= 0 ,0
Exp/Cntr=0.3,0.1

Type RM Length L Ch R = 1 ,74079   ,1306,1306,1306
BEGIN DESCRIPTION:
Mapping XS 11627658
END DESCRIPTION:
XS GIS Cut Line= 4
      2708360.89      6933720.22      2706770.39      6934905.49
      2706298.17      6934922.85      2702670.45      6937594.77
#Sta/Elev= 30
  2771.5  492.68  3031.5  483.16  3203.7  483.05  3232.9  487.83  3268.4  477.02
  3362.3  473.63  3583.2  467.23  3662.5  458.49  3818.9  461.81  4490.3  451.06
  4919.6  449.18  4959.6  453.15  4999.6  448.91  5122.9  459.07  5226.2  463.37
  5597.3  462.49  5830.4  459.43  6505.2  459.92  6518.8  459.99  6650.9  460.91
  6963.9  448.41  6965.9  447.91  6981.2  448.41    7161  449.57  7245.5  449.96
  7630.4  464.58  7901.9  469.64  8275.2  476.15  8925.5  488.85  9733.1  493.38
#Mann= 17 ,-1 , 0
  2771.5     .03       0  3031.5     .03       0  3362.3     .03       0
  3818.9     .03       0  5122.9     .03       0  5226.2     .03       0
  5597.3     .03       0  5830.4     .03       0  6505.2     .03       0
  6518.8     .03       0  6963.9     .03       0  6981.2     .03       0
    7161     .03       0  7245.5     .03       0  7630.4     .03       0
  7901.9     .03       0  8275.2     .03       0
Bank Sta=3818.9,5226.2
XS Rating Curve= 0 ,0
Exp/Cntr=0.3,0.1

Type RM Length L Ch R = 1 ,72773   ,2655,2655,2655
BEGIN DESCRIPTION:
Mapping XS 82989271
END DESCRIPTION:
XS GIS Cut Line= 5
      2707548.28      6932424.43      2706516.92      6933603.41
       2706256.5      6934200.63      2706043.55      6934782.25
      2702692.23      6937422.43
#Sta/Elev= 30
  3169.4  493.56  3501.5     488  3667.4  479.93  3898.3     469  4232.5  469.68
  4316.8   470.9  4359.5  458.87  4507.6  457.08  4831.4  448.72  5550.8  450.43
  5892.1  456.98  6014.9  458.37  6406.7  453.68  6591.5  452.34  6694.4   451.6
  6847.9  454.92  7029.6  451.37  7228.4  459.94  7520.3  449.03  7629.4  449.95
  7739.2  448.36  7741.2  447.86  7756.6  448.36  7884.3  448.97  7983.7  459.57
  8133.2  464.32  8252.2  467.32  8624.4  475.01  9124.4  481.38 10273.1  493.23
#Mann= 16 ,-1 , 0
  3169.4     .03       0  3667.4     .03       0  4232.5     .03       0
  4507.6     .03       0  6014.9     .03       0  6406.7     .03       0
  6591.5     .03       0  6694.4     .03       0  6847.9     .03       0
  7629.4     .03       0  7739.2     .03       0  7756.6     .03       0
  8133.2     .03       0  8252.2     .03       0  8624.4     .03       0
  9124.4     .03       0
Bank Sta=4507.6,5892.1
XS Rating Curve= 0 ,0
Exp/Cntr=0.3,0.1

Type RM Length L Ch R = 1 ,70118   ,1029,1029,1029
BEGIN DESCRIPTION:
Mapping XS 74163ecd
END DESCRIPTION:
XS GIS Cut Line= 4
      2706900.99      6931836.01        2704626.      6934861.01
      2704079.01        6935614.      2702640.25      6937365.04
#Sta/Elev= 30
    1215  485.31  1385.8  484.89  1444.1  479.95  1864.7  488.61    2150  488.55
    2679  463.31  3128.8  459.76  3164.2  458.72  3185.7   452.8  3422.5  465.03
  3628.6  463.67  3736.2   469.1  3922.3  461.05  4022.2  462.17  4028.5  461.37
  4043.1  450.41  4407.5  450.54  4592.9  461.51  4678.2  456.49  4691.1  447.97
  5143.4  448.79  5178.9  455.64  5335.8  461.24  5557.6  463.93  5724.9  463.07
  6289.5  474.27  7799.5  491.98  7898.5  491.35  7933.7  483.26    8197  483.92
#Mann= 6 ,-1 , 0
    1215     .03       0  4592.9     .03       0  5335.8     .03       0
  5557.6     .03       0  5724.9     .03       0  6289.5     .03       0
Bank Sta=4592.9,5335.8
XS Rating Curve= 0 ,0
Exp/Cntr=0.3,0.1

Type RM Length L Ch R = 1 ,69089   ,772,772,772
BEGIN DESCRIPTION:
Mapping XS db12988b
END DESCRIPTION:
XS GIS Cut Line= 3
      2705502.91      6931782.49      2703858.93      6934211.05
      2702457.48      6937297.06
#Sta/Elev= 30
  2080.5  486.77  2530.7  481.39  2905.2  472.16  3726.1  469.11  4071.2  461.35
  4107.4  457.61  4161.9  459.58  4229.4  461.87  4274.3  472.69  4295.3  463.51
  4316.3  460.54  4337.3  458.97  4418.1  464.66    4469  457.66  4496.3  447.98
  4515.7  448.48  5354.6  449.21  5408.5  450.57  5439.7  456.97  5474.4     452
  5606.2  451.97  5658.4  455.06  5681.5  462.47  5733.1  464.22    5955  468.11
  6210.3  472.61  6432.8  471.92  6558.2  473.57  7258.2  486.38  8402.5  494.43
#Mann= 10 ,-1 , 0
  2080.5     .03       0  4161.9     .03       0    4469     .03       0
  4515.7     .03       0  5354.6     .03       0  5439.7     .03       0
  5733.1     .03       0    5955     .03       0  6432.8     .03       0
  6558.2     .03       0
Bank Sta=4469,5439.7
XS Rating Curve= 0 ,0
Exp/Cntr=0.3,0.1

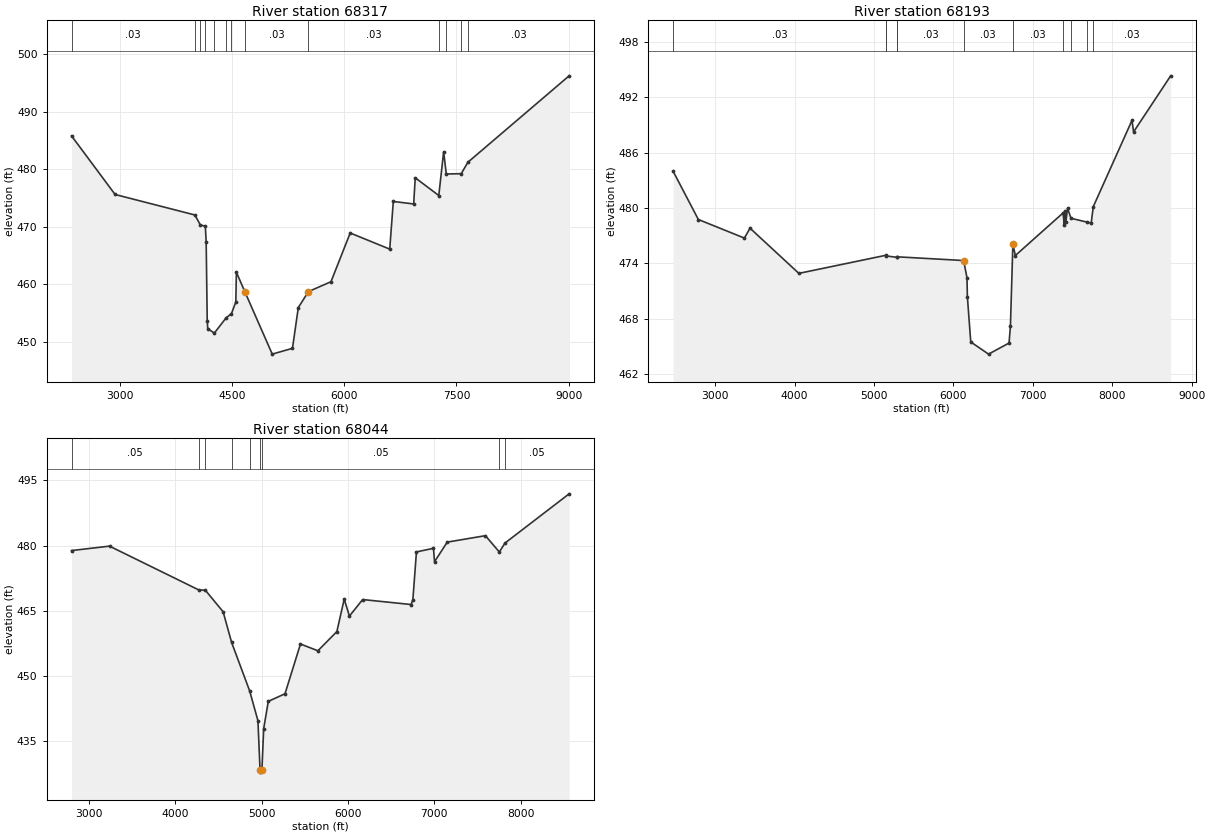
Type RM Length L Ch R = 1 ,68317   ,124,124,124
BEGIN DESCRIPTION:
Mapping XS dcf389df
END DESCRIPTION:
XS GIS Cut Line= 5
      2705410.91       6931803.4       2703463.1      6933615.56
      2703129.77      6933941.95       2702900.6      6934344.73
      2702211.84       6937324.6
#Sta/Elev= 30
  2356.9  485.81  2938.7  475.63  4004.5  472.07    4078  470.34  4144.6  470.12
  4155.8  467.44  4169.9  453.72  4177.3  452.31  4265.3  451.56  4424.8  454.24
    4493  454.91    4552  456.96  4559.3  462.13  4672.2  458.75  5038.7   447.9
    5309  448.91  5386.9  455.99  5522.4  458.76  5823.6  460.48  6080.3  468.94
  6608.5  466.14  6656.4  474.42  6928.7  473.98  6949.3  478.53  7264.2  475.45
    7329  483.06  7364.1  479.19  7563.9  479.24  7653.1  481.23  9005.7  496.24
#Mann= 13 ,-1 , 0
  2356.9     .03       0  4004.5     .03       0    4078     .03       0
  4144.6     .03       0  4265.3     .03       0  4424.8     .03       0
    4493     .03       0  4672.2     .03       0  5522.4     .03       0
  7264.2     .03       0  7364.1     .03       0  7563.9     .03       0
  7653.1     .03       0
Bank Sta=4672.2,5522.4
XS Rating Curve= 0 ,0
Exp/Cntr=0.3,0.1

Type RM Length L Ch R = 1 ,68193   ,149,149,149
BEGIN DESCRIPTION:
Mapping XS 2e6a8f2e
END DESCRIPTION:
XS GIS Cut Line= 6
      2705246.24      6931700.95      2703186.72       6933748.6
      2703100.91      6933850.55      2703023.13      6933985.59
      2702851.98      6934318.08       2702236.2      6936945.47
#Sta/Elev= 30
  2468.7  483.99  2787.1  478.76  3366.9  476.75  3437.7  477.82  4052.8  472.93
  5149.4  474.89  5150.3  474.82  5284.6  474.67  5293.8  474.72  6127.2  474.32
  6169.7  472.47  6174.8  470.42  6217.3  465.51  6441.3  464.19  6699.7  465.39
    6717  467.24  6747.8  476.12  6778.6  474.86    7380  479.47  7394.3  478.21
  7399.5  479.65  7415.4  478.53    7436  479.98  7479.9  478.89  7679.9  478.48
  7733.8  478.37  7760.8  480.16  8247.4  489.48  8267.9  488.24  8734.7  494.31
#Mann= 11 ,-1 , 0
  2468.7     .03       0  5149.4     .03       0  5150.3     .03       0
  5284.6     .03       0  5293.8     .03       0  6127.2     .03       0
  6747.8     .03       0    7380     .03       0  7479.9     .03       0
  7679.9     .03       0  7760.8     .03       0
Bank Sta=6127.2,6747.8
XS Rating Curve= 0 ,0
Exp/Cntr=0.3,0.1

Type RM Length L Ch R = 1 ,68044   ,447,447,447
BEGIN DESCRIPTION:
Mapping XS d5ab572c
END DESCRIPTION:
XS GIS Cut Line= 5
      2704883.46      6931806.98      2703328.12      6933400.28
      2702973.95      6933869.03      2702803.81      6934316.95
       2702142.3      6936693.99
#Sta/Elev= 30
  2799.7  478.84  3239.1  479.86  4269.8  469.83  4349.6  469.71  4554.4  464.79
  4652.9  457.74  4861.4  446.63  4957.5  439.78    4982  428.46  4984.2  427.96
  5003.8  428.46  5024.2  437.95  5077.4  444.21    5271  445.96  5449.9  457.38
  5651.8  455.83  5871.4  460.24  5956.4   467.7  6016.7  463.79  6169.8  467.59
  6730.3  466.45  6751.1  467.52  6792.6  478.53  6989.8  479.36    7002  476.28
  7149.3  480.78    7591  482.26  7752.4  478.51  7817.4  480.56  8560.3  491.87
#Mann= 9 ,-1 , 0
  2799.7     .05       0  4269.8    .075       0  4349.6     .05       0
  4652.9     .12       0  4861.4     .05       0    4982     .03       0
  5003.8     .05       0  7752.4     .12       0  7817.4     .05       0
Bank Sta=4982,5003.8
XS Rating Curve= 0 ,0
Exp/Cntr=0.3,0.1