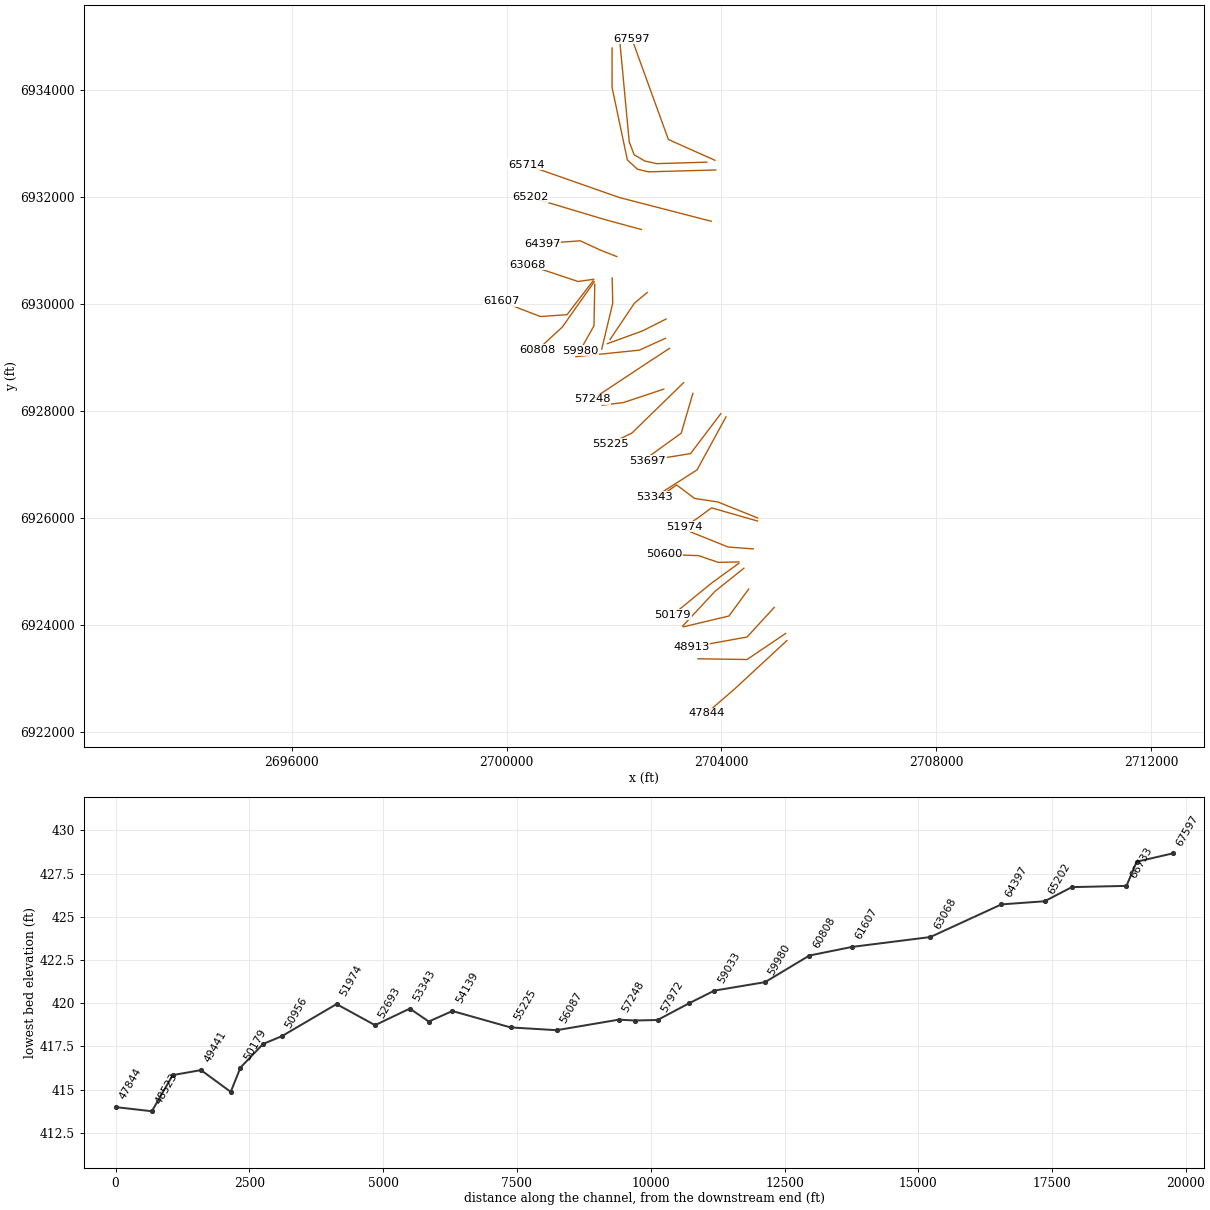
HEC-RAS study Rocky Cedar Creek.prj: Rocky Cedar Creek Base Level Engineering

--- Rocky Cedar Creek.g01 (geometry) --- (continued)

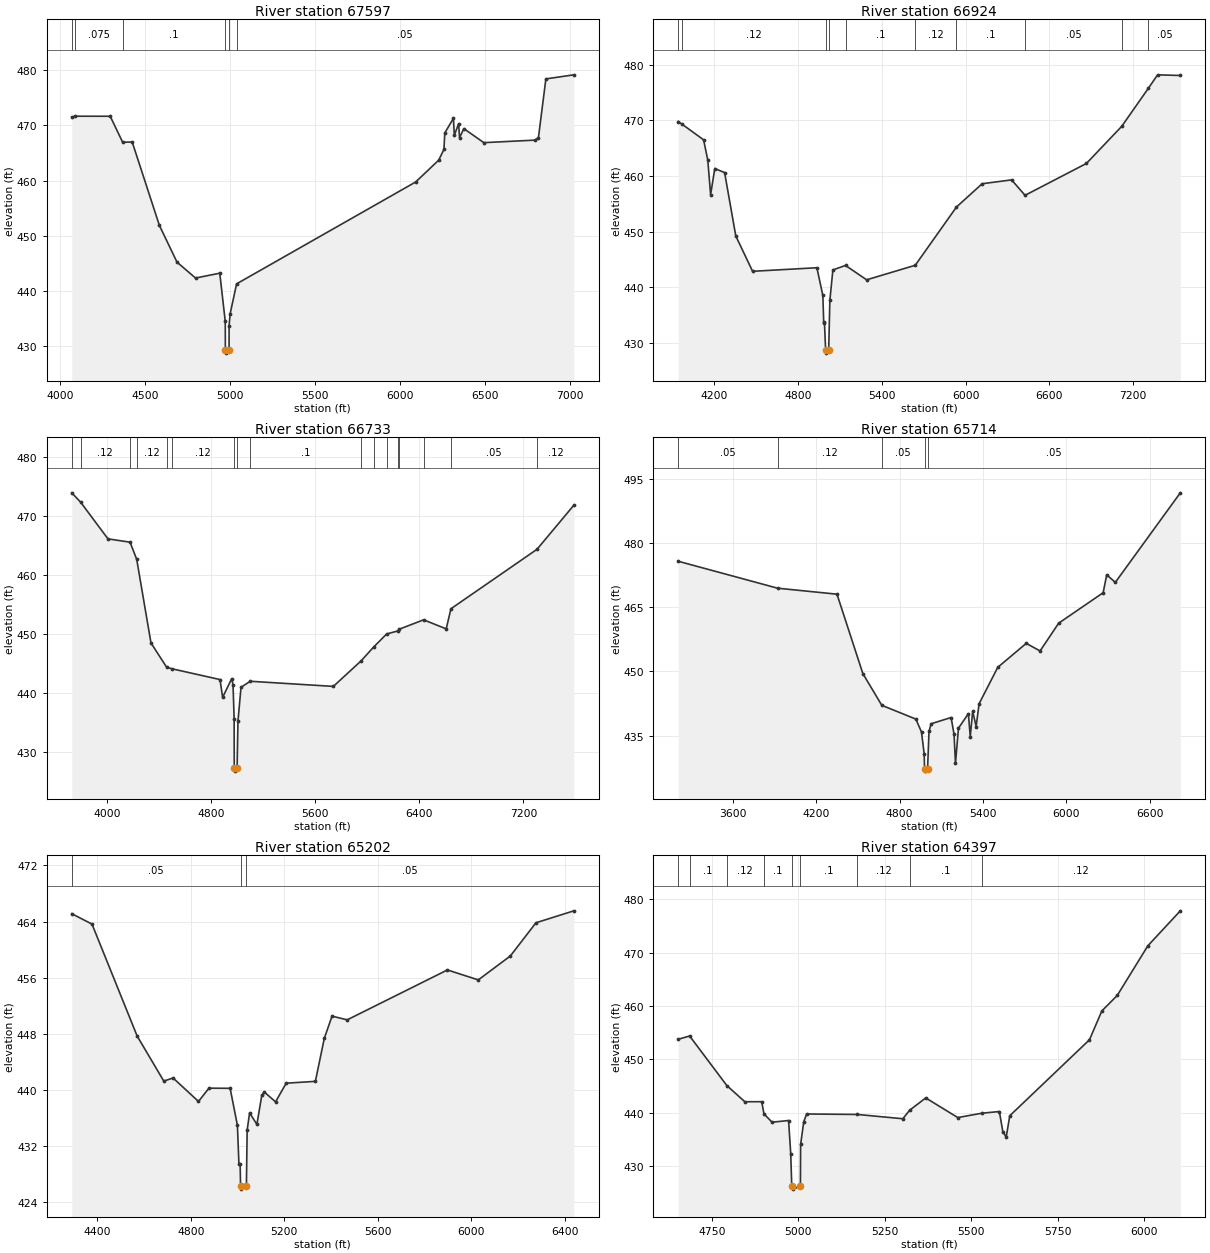
Type RM Length L Ch R = 1 ,67597   ,673,673,673
BEGIN DESCRIPTION:
Mapping XS dd240950
END DESCRIPTION:
XS GIS Cut Line= 3
       2703880.2      6932684.92      2703012.11      6933073.82
      2702331.57      6934955.72
#Sta/Elev= 30
    4069   471.5  4090.6  471.67    4295  471.66  4368.3  466.94  4424.3  466.99
  4584.2  451.85  4687.9  445.18  4796.8   442.3  4939.3  443.18  4971.6  434.42
  4972.2  429.17  4974.3  428.67    4994  429.17  4994.1  433.65  5000.3   435.8
  5038.1  441.24  6091.2  459.73  6226.6  463.69  6257.3  465.63  6262.6  468.64
  6313.3  471.28  6318.6  468.21  6343.9  470.31  6349.3  467.77  6374.6  469.42
  6491.9  466.87  6793.1  467.33  6813.1  467.76  6856.9  478.44  7021.4  479.18
#Mann= 6 ,-1 , 0
    4069     .05       0  4090.6    .075       0  4368.3      .1       0
  4972.2     .07       0    4994      .1       0  5038.1     .05       0
Bank Sta=4972.2,4994
XS Rating Curve= 0 ,0
Exp/Cntr=0.3,0.1

Type RM Length L Ch R = 1 ,66924   ,191,191,191
BEGIN DESCRIPTION:
Mapping XS 6e690be1
END DESCRIPTION:
XS GIS Cut Line= 6
      2703727.41      6932650.21      2702796.83      6932622.43
      2702574.61      6932671.04      2702373.22       6932789.1
      2702282.94      6933032.15      2702102.39      6934962.67
#Sta/Elev= 30
  3945.8  469.77  3970.2  469.34  4127.3  466.48  4157.3   462.8  4177.3  456.64
  4207.3  461.33  4277.4   460.6  4357.4  449.22  4477.5  442.88  4937.1  443.52
    4980  438.54  4986.1  433.63  4991.2  433.79  4999.8  428.69    5002  428.19
  5021.7  428.69    5030  437.65  5051.7  443.13  5142.1  443.93    5293  441.35
  5640.5  443.96  5935.5  454.42  6119.1   458.6  6329.9  459.29  6425.7  456.52
  6864.7  462.24  7117.4  468.91  7308.1  475.75  7373.8  478.15  7536.1  478.03
#Mann= 10 ,-1 , 0
  3945.8    .075       0  3970.2     .12       0  4999.8     .07       0
  5021.7     .12       0  5142.1      .1       0  5640.5     .12       0
  5935.5      .1       0  6425.7     .05       0  7117.4     .12       0
  7308.1     .05       0
Bank Sta=4999.8,5021.7
XS Rating Curve= 0 ,0
Exp/Cntr=0.3,0.1

Type RM Length L Ch R = 1 ,66733   ,1019,1019,1019
BEGIN DESCRIPTION:
Mapping XS a6b4fc00
END DESCRIPTION:
XS GIS Cut Line= 6
      2703894.05      6932504.38      2702644.05      6932469.65
      2702435.72      6932518.27      2702248.22      6932691.88
       2701963.5      6934046.04      2701963.51       6934782.2
#Sta/Elev= 30
  3730.9  473.99  3798.3  472.42  4009.1  466.18  4178.4  465.62  4229.6  462.71
  4339.2  448.53  4459.4  444.41    4500  444.15  4869.4  442.32  4889.4   439.3
  4959.4  442.48  4969.4   441.4  4977.9  435.62  4978.7  427.29  4980.9  426.79
  5000.6  427.29  5007.2  435.25  5030.7  441.01  5101.8  442.03  5739.7  441.16
  5951.5  445.46  6050.3  447.86  6149.1  450.05    6237  450.58  6246.9  450.87
  6432.9  452.45  6606.4  450.92  6642.9  454.33  7303.7  464.41  7586.7  471.89
#Mann= 17 ,-1 , 0
  3730.9     .05       0  3798.3     .12       0  4178.4      .1       0
  4229.6     .12       0  4459.4      .1       0    4500     .12       0
  4978.7     .07       0  5000.6     .12       0  5101.8      .1       0
  5951.5     .12       0  6050.3      .1       0  6149.1     .12       0
    6237      .1       0  6246.9     .12       0  6432.9      .1       0
  6642.9     .05       0  7303.7     .12       0
Bank Sta=4978.7,5000.6
XS Rating Curve= 0 ,0
Exp/Cntr=0.3,0.1

Type RM Length L Ch R = 1 ,65714   ,512,512,512
BEGIN DESCRIPTION:
Mapping XS a97baafe
END DESCRIPTION:
XS GIS Cut Line= 3
      2703811.61      6931546.04      2702096.31      6931990.49
      2700360.55      6932601.47
#Sta/Elev= 30
  3207.6  475.73  3922.2  469.44  4349.7  468.04  4535.7  449.51  4672.1  442.09
  4917.3  438.87  4957.8  435.84  4977.1  430.75  4979.5  427.22  4981.7  426.72
  5001.4  427.22  5011.7  435.98  5026.9  437.78  5170.7  439.24  5191.9  435.33
  5202.1  428.53  5223.7  436.75    5295  440.15  5308.5  434.76  5325.9   440.7
  5350.9  437.14  5372.1  442.46  5506.4  450.96  5711.4  456.56  5810.7  454.78
  5944.6  461.27  6264.5  468.38  6290.2  472.56  6352.1   470.8  6819.7  491.71
#Mann= 5 ,-1 , 0
  3207.6     .05       0  3922.2     .12       0  4672.1     .05       0
  4979.5     .03       0  5001.4     .05       0
Bank Sta=4979.5,5001.4
XS Rating Curve= 0 ,0
Exp/Cntr=0.3,0.1

Type RM Length L Ch R = 1 ,65202   ,805,805,805
BEGIN DESCRIPTION:
Mapping XS 85c53aaa
END DESCRIPTION:
XS GIS Cut Line= 3
      2702509.88      6931391.95      2701818.53      6931580.77
      2700447.04      6931993.08
#Sta/Elev= 30
  4290.5  465.13    4377  463.65  4570.4   447.7  4684.3  441.29  4724.1  441.73
  4832.8  438.39  4877.7  440.28  4968.3  440.26  4999.4  434.98  5005.9   429.5
  5011.1   429.5  5012.9   426.4  5015.4   425.9  5037.9   426.4  5041.1   434.3
  5051.6  436.75  5082.9  435.12  5103.8  439.27  5114.2  439.74  5162.8  438.33
  5208.2  440.99  5333.1  441.25  5371.4  447.39  5404.4  450.54  5469.3  450.01
  5898.2  457.12  6030.3   455.7  6167.6  459.11  6277.2  463.84  6439.3  465.54
#Mann= 3 ,-1 , 0
  4290.5     .05       0  5012.9     .03       0  5037.9     .05       0
Bank Sta=5012.9,5037.9
XS Rating Curve= 0 ,0
Exp/Cntr=0.3,0.1

Type RM Length L Ch R = 1 ,64397   ,1329,1329,1329
BEGIN DESCRIPTION:
Mapping XS 9124e280
END DESCRIPTION:
XS GIS Cut Line= 4
      2702052.91      6930886.32      2701744.75      6931007.85
      2701371.49      6931181.46      2700664.03      6931129.38
#Sta/Elev= 30
  4652.9  453.78  4685.9  454.39  4793.4  445.12  4845.6  442.08  4894.4  442.09
  4900.8  439.82  4924.2  438.25  4972.1  438.57  4978.3  432.35  4981.3  426.22
  4983.8  425.72  5006.3  426.22  5006.9  434.08  5015.9  438.32  5024.3  439.79
  5170.9   439.7  5302.6   438.9  5322.1  440.48  5368.8   442.8  5461.5  439.12
  5530.6  439.93  5581.8  440.25  5591.8  436.49  5601.6  435.46  5611.9  439.46
  5842.5  453.69  5878.2  459.08  5922.7  461.98  6011.5   471.3  6105.2  477.83
#Mann= 9 ,-1 , 0
  4652.9     .05       0  4685.9      .1       0  4793.4     .12       0
  4900.8      .1       0  4981.3     .07       0  5006.3      .1       0
  5170.9     .12       0  5322.1      .1       0  5530.6     .12       0
Bank Sta=4981.3,5006.3
XS Rating Curve= 0 ,0
Exp/Cntr=0.3,0.1

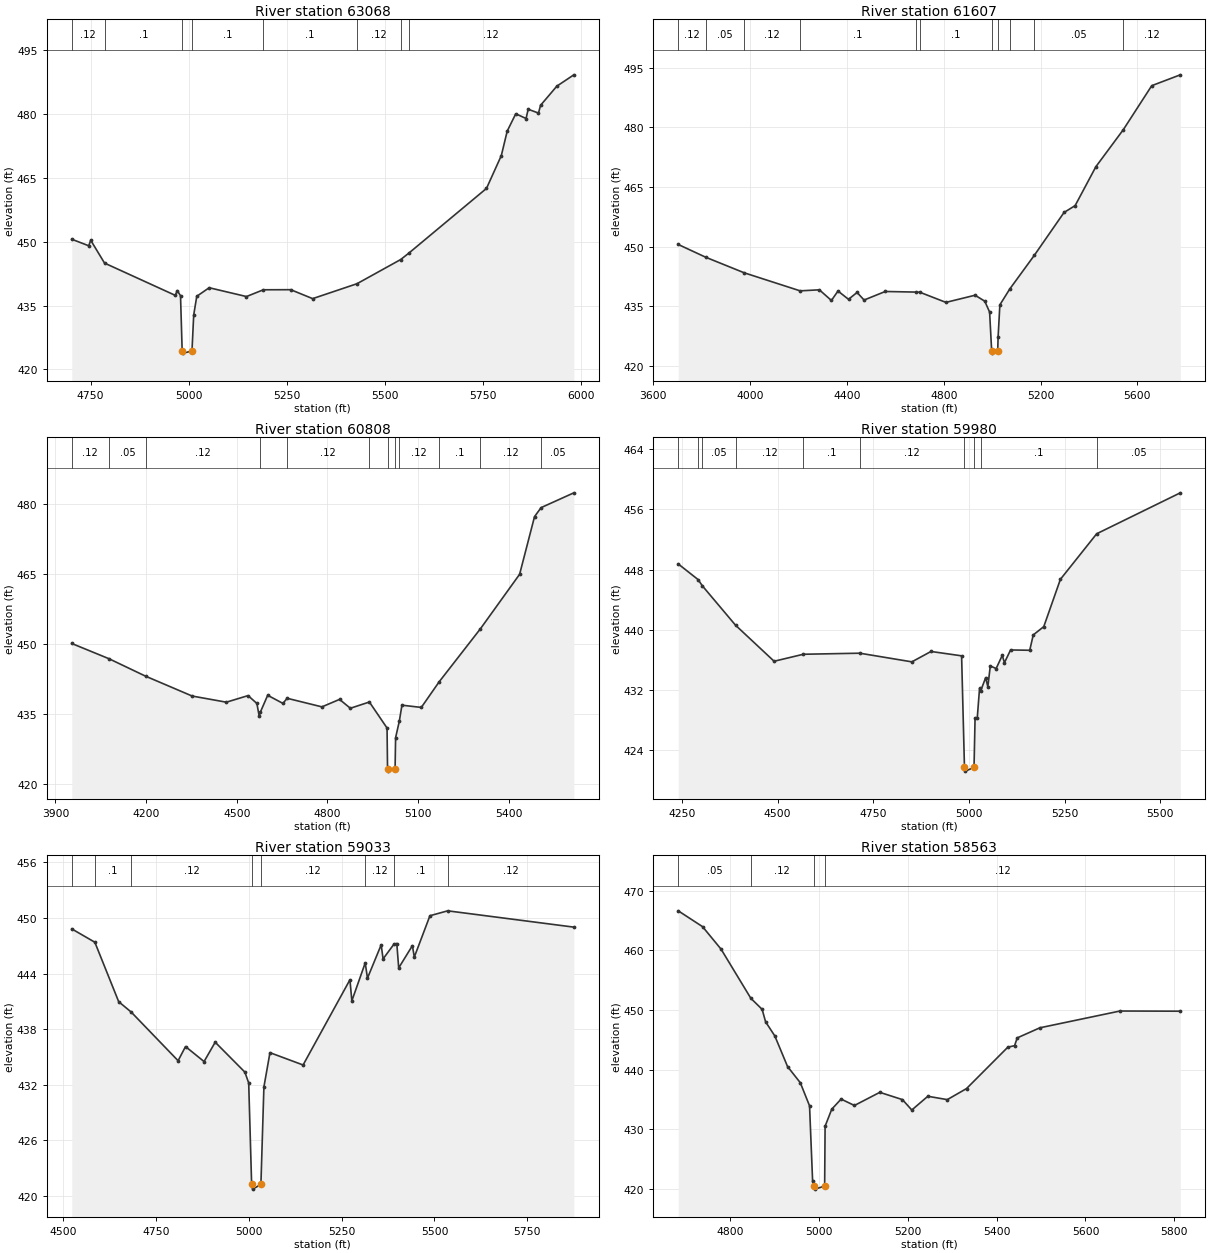
Type RM Length L Ch R = 1 ,63068   ,1461,1461,1461
BEGIN DESCRIPTION:
Mapping XS 2fa1b0df
END DESCRIPTION:
XS GIS Cut Line= 3
      2701620.53      6930462.39      2701328.08      6930421.91
      2700394.95       6930734.4
#Sta/Elev= 30
  4701.8  450.58    4745  449.05  4750.1  450.34  4785.3  444.98  4965.5   437.4
  4970.6  438.52  4978.9  437.31  4983.1  424.33  4985.6  423.83  5008.1  424.33
  5012.5  432.79  5020.3  437.18    5052  439.19  5146.9  437.12    5190  438.71
  5259.7  438.73  5315.6  436.63  5428.5  440.13    5540  445.82  5560.8  447.33
  5758.5  462.52  5796.3  470.23  5811.3  475.98  5833.1  480.05  5859.4  478.94
  5864.7  481.11    5891  480.22  5896.3  482.04  5937.8  486.54  5981.1   489.2
#Mann= 8 ,-1 , 0
  4701.8     .12       0  4785.3      .1       0  4983.1     .07       0
  5008.1      .1       0    5190      .1       0  5428.5     .12       0
    5540      .1       0  5560.8     .12       0
Bank Sta=4983.1,5008.1
XS Rating Curve= 0 ,0
Exp/Cntr=0.3,0.1

Type RM Length L Ch R = 1 ,61607   ,799,799,799
BEGIN DESCRIPTION:
Mapping XS 7c383df0
END DESCRIPTION:
XS GIS Cut Line= 5
      2701610.15      6930433.54      2701124.09      6929801.25
       2700985.2      6929792.57       2700629.3      6929766.53
      2699900.58      6930048.47
#Sta/Elev= 30
  3702.8  450.58  3817.2  447.35  3975.8  443.45  4206.5  438.92    4286  439.18
  4335.8   436.5    4363  438.88  4406.5  436.79  4441.8  438.52  4470.8  436.61
  4558.5  438.76  4684.5  438.61  4701.3  438.57  4809.1  436.02  4929.5  437.82
  4969.6  436.32  4989.6  433.58  4998.1  423.76  5000.6  423.26  5023.1  423.76
  5024.6  427.19    5032   435.4  5072.7  439.37  5174.1  447.83  5297.2  458.63
    5343  460.35  5428.8  470.14  5542.4  479.47  5659.6  490.51  5777.7  493.24
#Mann= 11 ,-1 , 0
  3702.8     .12       0  3817.2     .05       0  3975.8     .12       0
  4206.5      .1       0  4684.5     .12       0  4701.3      .1       0
  4998.1     .07       0  5023.1      .1       0  5072.7     .12       0
  5174.1     .05       0  5542.4     .12       0
Bank Sta=4998.1,5023.1
XS Rating Curve= 0 ,0
Exp/Cntr=0.3,0.1

Type RM Length L Ch R = 1 ,60808   ,828,828,828
BEGIN DESCRIPTION:
Mapping XS 92dc4179
END DESCRIPTION:
XS GIS Cut Line= 3
      2701632.49      6930418.49      2701037.28      6929571.22
      2700577.29      6929145.94
#Sta/Elev= 30
    3954  450.09  4077.1  446.83  4198.7  443.08  4352.4  438.84  4465.7  437.52
  4537.5  438.93  4566.8  437.25  4574.2  434.58  4578.6  435.45  4602.5     439
    4653  437.26  4666.8  438.36    4782  436.52  4840.4  438.12  4876.1  436.22
  4939.1  437.56  4997.6  431.99  4999.2  423.26  5001.7  422.76  5024.2  423.26
  5025.9  429.92  5038.1  433.42  5046.9  436.88    5111   436.4    5170  441.88
  5306.9  453.26  5436.4  464.91  5485.8  477.26  5507.5  479.18  5615.9  482.35
#Mann= 12 ,-1 , 0
    3954     .12       0  4077.1     .05       0  4198.7     .12       0
  4578.6      .1       0  4666.8     .12       0  4939.1      .1       0
  4999.2     .07       0  5024.2      .1       0  5038.1     .12       0
    5170      .1       0  5306.9     .12       0  5507.5     .05       0
Bank Sta=4999.2,5024.2
XS Rating Curve= 0 ,0
Exp/Cntr=0.3,0.1

Type RM Length L Ch R = 1 ,59980   ,947,947,947
BEGIN DESCRIPTION:
Mapping XS ad8e53b1
END DESCRIPTION:
XS GIS Cut Line= 3
      2701641.45      6930371.56      2701626.86       6929595.6
      2701365.12      6929127.49
#Sta/Elev= 30
  4240.1  448.75  4291.8  446.68  4303.5  445.82  4389.9  440.61  4490.7  435.82
  4567.2  436.75  4714.7  436.89  4850.8  435.74  4900.8  437.12  4980.8  436.54
  4988.3  421.72  4990.8  421.22  5013.3  421.72    5016  428.26  5021.7  428.26
  5027.7  432.21    5031  431.93  5043.7  433.64  5049.4  432.43  5055.8   435.2
  5071.1  434.85  5087.1   436.6  5092.8  435.63  5108.8  437.32  5158.9  437.28
  5168.1  439.32  5195.6  440.42  5239.1  446.71  5333.9  452.76  5552.5   458.2
#Mann= 10 ,-1 , 0
  4240.1     .05       0  4291.8     .12       0  4303.5     .05       0
  4389.9     .12       0  4567.2      .1       0  4714.7     .12       0
  4988.3     .07       0  5013.3     .12       0    5031      .1       0
  5333.9     .05       0
Bank Sta=4988.3,5013.3
XS Rating Curve= 0 ,0
Exp/Cntr=0.3,0.1

Type RM Length L Ch R = 1 ,59033   ,470,470,470
BEGIN DESCRIPTION:
Mapping XS 59322cc1
END DESCRIPTION:
XS GIS Cut Line= 3
       2701965.3      6930487.51      2701975.65      6930015.66
      2701770.97      6929158.42
#Sta/Elev= 30
  4522.4  448.82  4584.6  447.38  4648.9  440.96  4682.4  439.85    4809  434.59
    4829  436.12    4879   434.5    4909  436.59    4989  433.36  4999.3  432.19
  5007.2  421.23  5009.7  420.73  5032.2  421.23  5040.3  431.76  5056.6  435.46
  5145.9  434.13  5272.2  443.33  5277.3  441.05  5313.4  445.15  5319.4   443.5
  5356.4   447.1  5361.5  445.58  5391.3   447.2  5398.5  447.24  5403.6  444.61
  5440.5  447.01  5445.7  445.78  5487.8  450.24  5535.6  450.77  5875.7  449.01
#Mann= 8 ,-1 , 0
  4522.4     .05       0  4584.6      .1       0  4682.4     .12       0
  5007.2     .07       0  5032.2     .12       0  5313.4     .12       0
  5391.3      .1       0  5535.6     .12       0
Bank Sta=5007.2,5032.2
XS Rating Curve= 0 ,0
Exp/Cntr=0.3,0.1

Type RM Length L Ch R = 1 ,58563   ,591,591,591
BEGIN DESCRIPTION:
Mapping XS 2f50efd0
END DESCRIPTION:
XS GIS Cut Line= 3
      2702617.99       6930215.3       2702379.3      6930015.66
      2701924.15      6929335.11
#Sta/Elev= 30
  4683.6  466.61  4738.3  463.96    4780  460.19    4847  451.96  4872.4  450.11
  4880.2  448.02    4901  445.65  4929.6  440.53  4958.3  437.82  4979.1  433.95
    4986  421.36  4988.1   420.5  4990.6     420  5013.1   420.5  5014.1  430.53
  5029.1  433.39  5050.1  435.08  5080.1  434.01  5137.2  436.21  5188.2  434.99
  5209.2  433.25  5245.3  435.55  5289.1  434.99  5332.4  436.84  5425.4  443.78
  5440.5  444.02  5446.5  445.33  5497.5  447.02  5677.7  449.83  5813.5   449.8
#Mann= 4 ,-1 , 0
  4683.6     .05       0    4847     .12       0  4988.1     .07       0
  5013.1     .12       0
Bank Sta=4988.1,5013.1
XS Rating Curve= 0 ,0
Exp/Cntr=0.3,0.1

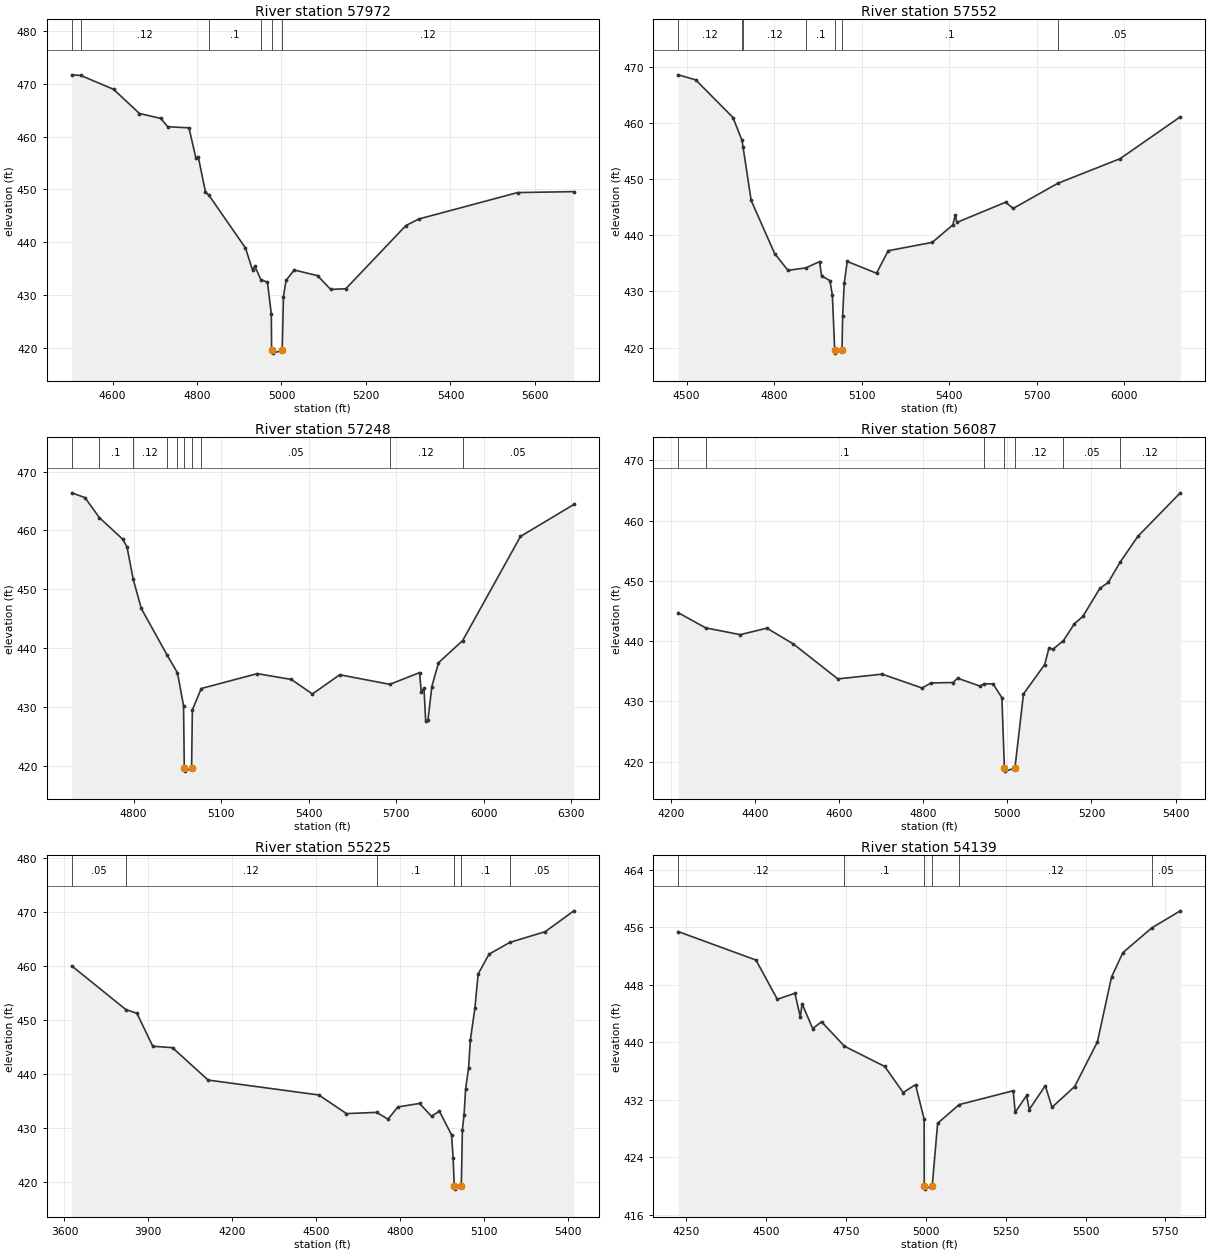
Type RM Length L Ch R = 1 ,57972   ,420,420,420
BEGIN DESCRIPTION:
Mapping XS f405b42a
END DESCRIPTION:
XS GIS Cut Line= 3
       2702969.6      6929720.53      2702531.21      6929499.17
      2701875.84      6929260.46
#Sta/Elev= 30
  4503.5  471.69  4524.8  471.57  4602.5  468.95  4663.8  464.37    4714  463.45
  4730.7  461.87  4780.9  461.66  4797.6  455.88  4803.2  456.08  4819.9  449.55
  4828.5  448.87  4914.7  438.93  4931.4  434.77    4937  435.46    4951  432.96
  4966.8  432.43  4975.9  426.42  4976.6  419.53  4979.1  419.03  5001.6  419.53
  5004.7  429.73  5010.8  432.78  5029.9  434.76  5085.3  433.69  5116.3  431.09
  5152.2  431.21  5294.4  443.16    5325  444.41    5559  449.41  5692.1  449.59
#Mann= 6 ,-1 , 0
  4503.5     .05       0  4524.8     .12       0  4828.5      .1       0
    4951     .12       0  4976.6     .07       0  5001.6     .12       0
Bank Sta=4976.6,5001.6
XS Rating Curve= 0 ,0
Exp/Cntr=0.3,0.1

Type RM Length L Ch R = 1 ,57552   ,304,304,304
BEGIN DESCRIPTION:
Mapping XS d8adc7be
END DESCRIPTION:
XS GIS Cut Line= 3
       2702956.6       6929360.3      2702470.44      6929138.93
      2701290.46      6929017.46
#Sta/Elev= 30
  4471.3  468.56  4531.2  467.66  4658.8  460.96  4689.8  456.89  4693.6  455.64
  4721.1   446.2  4801.6  436.74  4847.3  433.74  4908.8  434.18  4955.4   435.3
  4962.6  432.77  4991.1   431.9  4999.4  429.34  5007.5   419.5    5010     419
  5032.5   419.5  5034.6  425.59  5040.1  431.42  5050.2  435.33  5150.7  433.23
  5190.9  437.24  5341.7  438.72  5412.1  441.83  5420.9  443.58  5425.9  442.27
    5593  445.87  5619.1  444.77  5771.9  449.24  5985.1  453.62  6191.7  461.08
#Mann= 7 ,-1 , 0
  4471.3     .12       0  4689.8      .1       0  4693.6     .12       0
  4908.8      .1       0  5007.5     .07       0  5032.5      .1       0
  5771.9     .05       0
Bank Sta=5007.5,5032.5
XS Rating Curve= 0 ,0
Exp/Cntr=0.3,0.1

Type RM Length L Ch R = 1 ,57248   ,1161,1161,1161
BEGIN DESCRIPTION:
Mapping XS 46221056
END DESCRIPTION:
XS GIS Cut Line= 3
      2703034.67      6929173.64      2702709.16      6928960.97
      2701599.56      6928224.13
#Sta/Elev= 30
  4587.8  466.38  4633.2  465.56    4682  462.18  4762.9  458.47  4777.3  457.15
  4798.4  451.68  4826.1  446.71  4914.9  438.76  4950.1  435.77  4970.9  430.18
  4973.5  419.55    4976  419.05  4998.5  419.55  5001.1  429.46  5031.6   433.1
  5223.6  435.63  5340.5  434.64  5412.6  432.17  5506.2  435.44  5677.9  433.81
  5779.8   435.8  5785.8  432.45  5794.9  433.13  5800.9  427.54  5808.7  427.77
  5821.9  433.43  5844.7  437.48  5927.6  441.26  6125.6  458.96  6308.6   464.4
#Mann= 10 ,-1 , 0
  4587.8     .12       0    4682      .1       0  4798.4     .12       0
  4914.9      .1       0  4950.1     .12       0  4973.5     .07       0
  4998.5     .12       0  5031.6     .05       0  5677.9     .12       0
  5927.6     .05       0
Bank Sta=4973.5,4998.5
XS Rating Curve= 0 ,0
Exp/Cntr=0.3,0.1

Type RM Length L Ch R = 1 ,56087   ,862,862,862
BEGIN DESCRIPTION:
Rocky Cedar Creek 40.0
END DESCRIPTION:
XS GIS Cut Line= 3
      2702925.96      6928410.99        2702176.        6928161.
      2701776.04      6928111.01
#Sta/Elev= 30
  4217.6  444.72  4282.8  442.21  4365.1  441.08  4428.4  442.16  4491.6  439.52
    4597  433.74  4702.4  434.53  4797.3  432.23  4818.4  433.07  4871.1  433.14
  4881.6  433.86  4934.3  432.56  4945.1  432.93    4966  432.91    4987  430.63
    4993  418.94  4995.5  418.44    5018  418.94  5038.4  431.25  5088.8  436.12
  5098.8  438.84  5108.9  438.68  5133.4   440.1  5159.3  442.88  5179.5   444.1
  5219.8  448.75  5239.9  449.74  5268.3  453.13  5310.5  457.41  5411.2  464.61
#Mann= 7 ,-1 , 0
  4217.6     .12       0  4282.8      .1       0  4945.1     .12       0
    4993     .07       0    5018     .12       0  5133.4     .05       0
  5268.3     .12       0
Bank Sta=4993,5018
XS Rating Curve= 0 ,0
Exp/Cntr=0.3,0.1

Type RM Length L Ch R = 1 ,55225   ,1086,1086,1086
BEGIN DESCRIPTION:
Mapping XS d6f1e352
END DESCRIPTION:
XS GIS Cut Line= 3
      2703295.12      6928531.31      2702335.89      6927593.79
      2701929.46      6927390.57
#Sta/Elev= 30
  3626.1  460.04  3819.7  451.93  3859.1  451.25  3915.7  445.13  3986.4  444.86
  4113.7  438.85  4509.6  436.08  4608.6  432.62  4716.5  432.85  4757.2  431.59
  4792.5  433.86  4870.2  434.51  4912.7  432.12  4940.9  433.08  4984.4  428.67
    4990  424.43  4994.3   419.1  4996.8   418.6  5019.3   419.1  5023.2  429.64
  5029.1  432.37  5034.7   437.2  5045.5  441.18  5051.5   446.2  5067.9   452.2
  5079.5  458.55  5118.6  462.23  5192.6   464.4  5319.8  466.41  5421.8  470.27
#Mann= 6 ,-1 , 0
  3626.1     .05       0  3819.7     .12       0  4716.5      .1       0
  4994.3     .07       0  5019.3      .1       0  5192.6     .05       0
Bank Sta=4994.3,5019.3
XS Rating Curve= 0 ,0
Exp/Cntr=0.3,0.1

Type RM Length L Ch R = 1 ,54139   ,442,442,442
BEGIN DESCRIPTION:
Mapping XS ae3cefad
END DESCRIPTION:
XS GIS Cut Line= 3
      2703468.71      6928331.66      2703251.69      6927589.45
        2702605.       6927120.7
#Sta/Elev= 30
  4224.6  455.39    4468  451.43  4534.9  445.97  4589.9  446.81    4607  443.48
  4612.2  445.36  4645.6  441.89  4673.3  442.84    4745  439.44  4871.2  436.62
  4928.8  432.99  4967.5  434.09  4994.5   429.3  4994.9  420.05  4997.4  419.55
  5019.9  420.05  5036.8  428.72  5104.2  431.31  5273.4  433.24  5279.6  430.23
  5315.2  432.58  5323.7  430.63  5373.9  433.95  5394.8  430.94  5465.9  433.83
  5537.1  440.05  5581.2  449.06  5616.7  452.46  5707.1   455.9  5796.6  458.28
#Mann= 6 ,-1 , 0
  4224.6     .12       0    4745      .1       0  4994.9     .07       0
  5019.9      .1       0  5104.2     .12       0  5707.1     .05       0
Bank Sta=4994.9,5019.9
XS Rating Curve= 0 ,0
Exp/Cntr=0.3,0.1

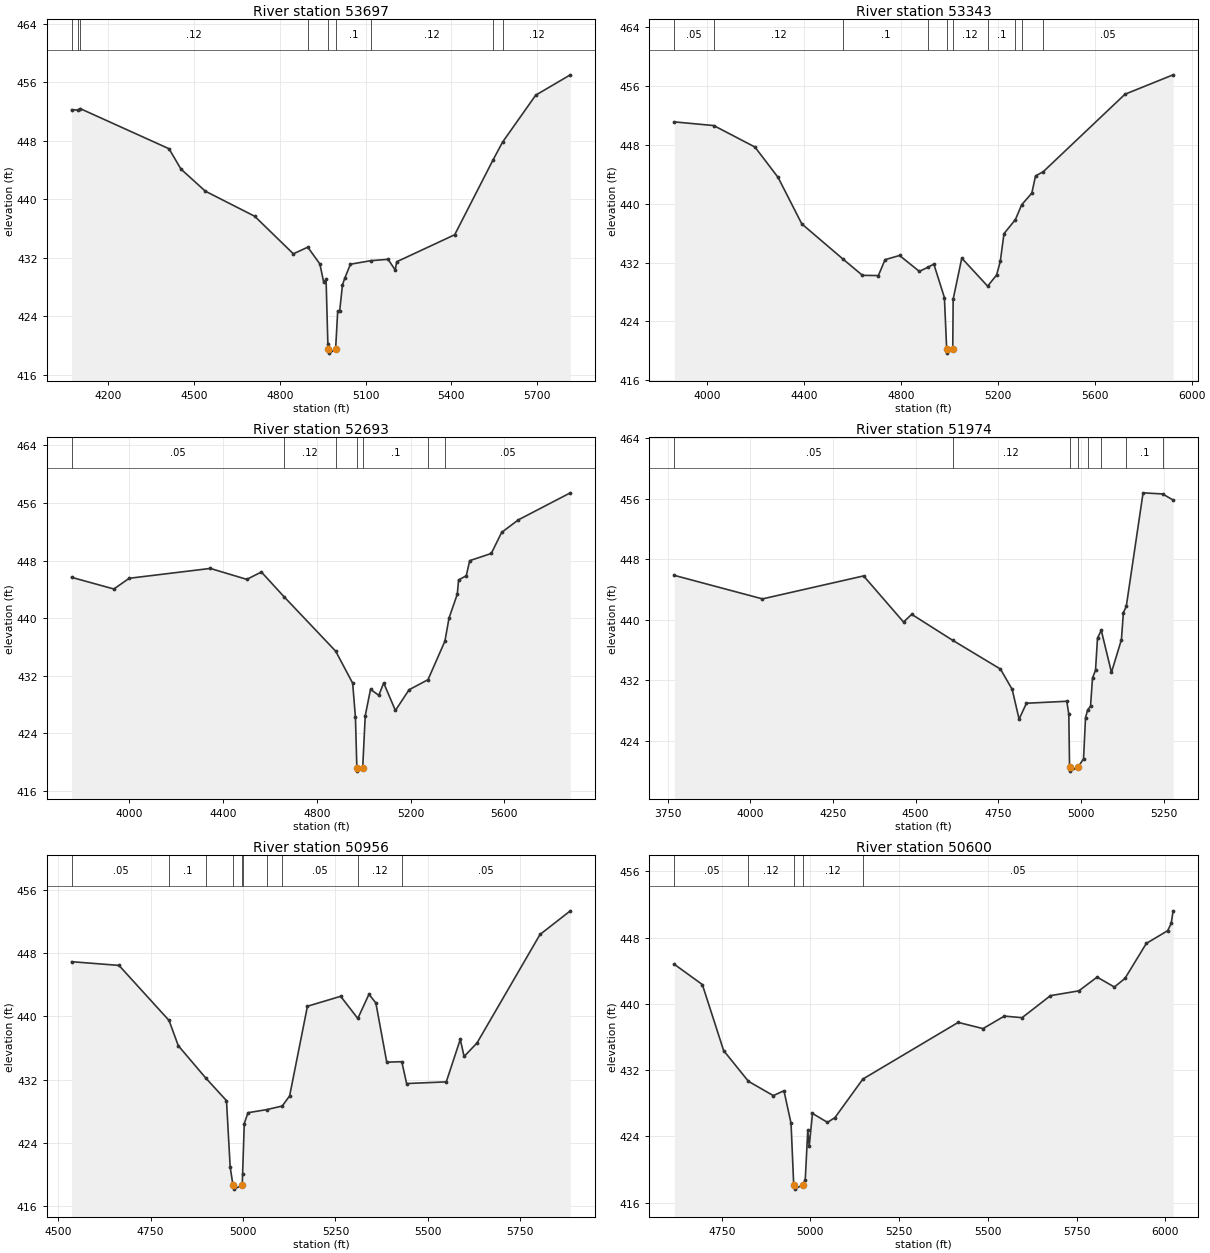
Type RM Length L Ch R = 1 ,53697   ,354,354,354
BEGIN DESCRIPTION:
Mapping XS 803e1980
END DESCRIPTION:
XS GIS Cut Line= 3
      2703989.56      6927954.05       2703425.3       6927207.5
      2702626.65      6927077.29
#Sta/Elev= 30
    4071  452.23  4093.5  452.18  4100.6  452.39  4411.9  446.89  4453.6  444.11
  4538.9  441.09  4711.6  437.66  4846.9  432.52  4897.4  433.43  4939.7  431.13
  4953.1  428.63  4961.4  429.01  4967.6  420.25  4969.7  419.44  4972.2  418.94
  4994.7  419.44  5002.1  424.71    5009  424.71  5018.7  428.25  5026.4  429.15
  5046.6   431.1    5119  431.59  5178.3  431.77  5203.1  430.32  5208.7  431.44
  5411.4  435.13  5544.6  445.29  5579.1  447.81  5694.9  454.22    5816     457
#Mann= 9 ,-1 , 0
    4071     .12       0  4093.5     .05       0  4100.6     .12       0
  4897.4      .1       0  4969.7     .07       0  4994.7      .1       0
    5119     .12       0  5544.6      .1       0  5579.1     .12       0
Bank Sta=4969.7,4994.7
XS Rating Curve= 0 ,0
Exp/Cntr=0.3,0.1

Type RM Length L Ch R = 1 ,53343   ,650,650,650
BEGIN DESCRIPTION:
Mapping XS ec550d37
END DESCRIPTION:
XS GIS Cut Line= 3
      2704085.02      6927893.26      2703546.83      6926903.68
      2702761.27      6926400.23
#Sta/Elev= 30
  3863.9  451.14  4026.5  450.64  4196.6  447.72  4292.1  443.59    4390  437.27
  4560.6  432.47  4640.5  430.27  4706.3  430.24  4733.9   432.4  4793.7  432.97
  4875.4  430.81  4912.1  431.39  4935.3   431.8    4979  427.25  4988.4  420.19
  4990.9  419.69  5013.4  420.19  5015.1  427.02  5050.7  432.61  5157.5   428.8
  5194.6  430.32  5209.8  432.18    5225  435.94  5272.1  437.85  5298.1  439.87
    5340  441.45  5355.2  443.78    5388  444.39  5724.6   454.9  5923.4  457.54
#Mann= 10 ,-1 , 0
  3863.9     .05       0  4026.5     .12       0  4560.6      .1       0
  4912.1     .12       0  4988.4     .07       0  5013.4     .12       0
  5157.5      .1       0  5272.1     .12       0  5298.1      .1       0
    5388     .05       0
Bank Sta=4988.4,5013.4
XS Rating Curve= 0 ,0
Exp/Cntr=0.3,0.1

Type RM Length L Ch R = 1 ,52693   ,719,719,719
BEGIN DESCRIPTION:
Mapping XS 5f5de22d
END DESCRIPTION:
XS GIS Cut Line= 5
      2704673.41      6926005.72      2703934.04      6926304.08
      2703498.85      6926370.38      2703164.93      6926622.55
      2702780.22      6926346.93
#Sta/Elev= 30
  3752.9  445.67  3933.4  444.05  3998.8  445.54  4345.1  446.91  4500.7  445.39
  4563.2  446.41  4660.9  442.94  4880.3  435.41  4952.8  430.96  4964.7   426.2
  4970.7  419.23  4973.2  418.73  4995.7  419.23  5006.5  426.43  5029.1   430.1
  5064.5  429.27  5085.3  430.99  5135.3  427.16  5193.5  430.04  5274.4  431.44
  5346.7   436.8  5364.2  440.01  5399.6  443.34    5405  445.31  5437.8  445.89
  5452.5  447.99  5544.6  448.99  5588.9  451.92  5660.1  453.66  5882.1  457.42
#Mann= 7 ,-1 , 0
  3752.9     .05       0  4660.9     .12       0  4880.3      .1       0
  4970.7     .07       0  4995.7      .1       0  5274.4      .1       0
  5346.7     .05       0
Bank Sta=4970.7,4995.7
XS Rating Curve= 0 ,0
Exp/Cntr=0.3,0.1

Type RM Length L Ch R = 1 ,51974   ,1018,1018,1018
BEGIN DESCRIPTION:
Mapping XS 77a2e69e
END DESCRIPTION:
XS GIS Cut Line= 4
      2704671.99      6925948.46       2703816.4      6926194.03
      2703547.82      6925996.22      2703310.03      6925840.58
#Sta/Elev= 30
  3770.8  445.84  4037.1  442.73  4342.9  445.77  4463.7  439.67  4488.3  440.69
  4611.7  437.27  4756.7  433.45  4792.2  430.76    4813  426.83  4835.3  428.93
  4957.2  429.19  4963.4  427.47  4965.6  420.45  4968.1  419.95  4990.6  420.45
  5007.9  421.57  5013.9  427.02  5020.5  428.07    5029  428.53    5035  432.27
  5044.1  433.29  5050.1  437.56  5061.5  438.57  5092.3  433.01  5122.4  437.34
  5128.4  440.92  5137.1  441.74  5187.9  456.76    5247  456.61  5278.7  455.81
#Mann= 8 ,-1 , 0
  3770.8     .05       0  4611.7     .12       0  4965.6     .07       0
  4990.6     .12       0  5020.5      .1       0  5061.5     .12       0
  5137.1      .1       0    5247     .05       0
Bank Sta=4965.6,4990.6
XS Rating Curve= 0 ,0
Exp/Cntr=0.3,0.1

Type RM Length L Ch R = 1 ,50956   ,356,356,356
BEGIN DESCRIPTION:
Mapping XS 8d4bf8ca
END DESCRIPTION:
XS GIS Cut Line= 3
      2704593.85      6925427.64      2704125.07      6925462.36
      2703310.01      6925791.86
#Sta/Elev= 30
  4536.4  446.94  4664.6  446.47    4800  439.49    4825  436.29  4899.5  432.18
  4955.4  429.32  4965.4  420.89    4973   418.6  4975.5   418.1    4998   418.6
    4999  420.02  5003.5  426.41  5013.5  427.79  5064.1  428.18  5106.2  428.64
  5126.2  429.92  5174.4  441.29  5264.3  442.55  5310.7  439.74  5340.8  442.81
  5359.5  441.71    5389   434.2  5429.7  434.26  5442.7  431.49    5550   431.7
  5587.9  437.09  5598.2  434.92  5633.1  436.63  5803.6  450.39  5885.6  453.39
#Mann= 10 ,-1 , 0
  4536.4     .05       0    4800      .1       0  4899.5     .12       0
    4973     .07       0    4998     .12       0    4999      .1       0
  5064.1     .12       0  5106.2     .05       0  5310.7     .12       0
  5429.7     .05       0
Bank Sta=4973,4998
XS Rating Curve= 0 ,0
Exp/Cntr=0.3,0.1

Type RM Length L Ch R = 1 ,50600   ,421,421,421
BEGIN DESCRIPTION:
Mapping XS b01593e7
END DESCRIPTION:
XS GIS Cut Line= 4
      2704324.75      6925184.59      2703942.78       6925175.9
      2703573.86      6925301.77      2702940.61      6925323.46
#Sta/Elev= 30
  4616.6  444.78  4695.4  442.34  4755.4  434.37  4825.2  430.66  4895.4  428.93
  4925.4  429.52  4945.4  425.58  4952.9  418.14  4955.4  417.64  4977.9  418.14
  4985.4  418.77  4992.5  424.72  4996.6  422.84  5005.8  426.78  5048.1   425.7
  5069.2  426.28  5147.8  430.93  5416.4  437.77  5486.4  437.02  5546.4  438.53
  5596.5  438.34  5676.5     441  5756.5  441.58  5807.9  443.24  5856.6  442.04
  5886.6  443.09  5946.7  447.31  6006.7  448.84  6016.7  449.71  6022.1  451.24
#Mann= 5 ,-1 , 0
  4616.6     .05       0  4825.2     .12       0  4952.9     .07       0
  4977.9     .12       0  5147.8     .05       0
Bank Sta=4952.9,4977.9
XS Rating Curve= 0 ,0
Exp/Cntr=0.3,0.1

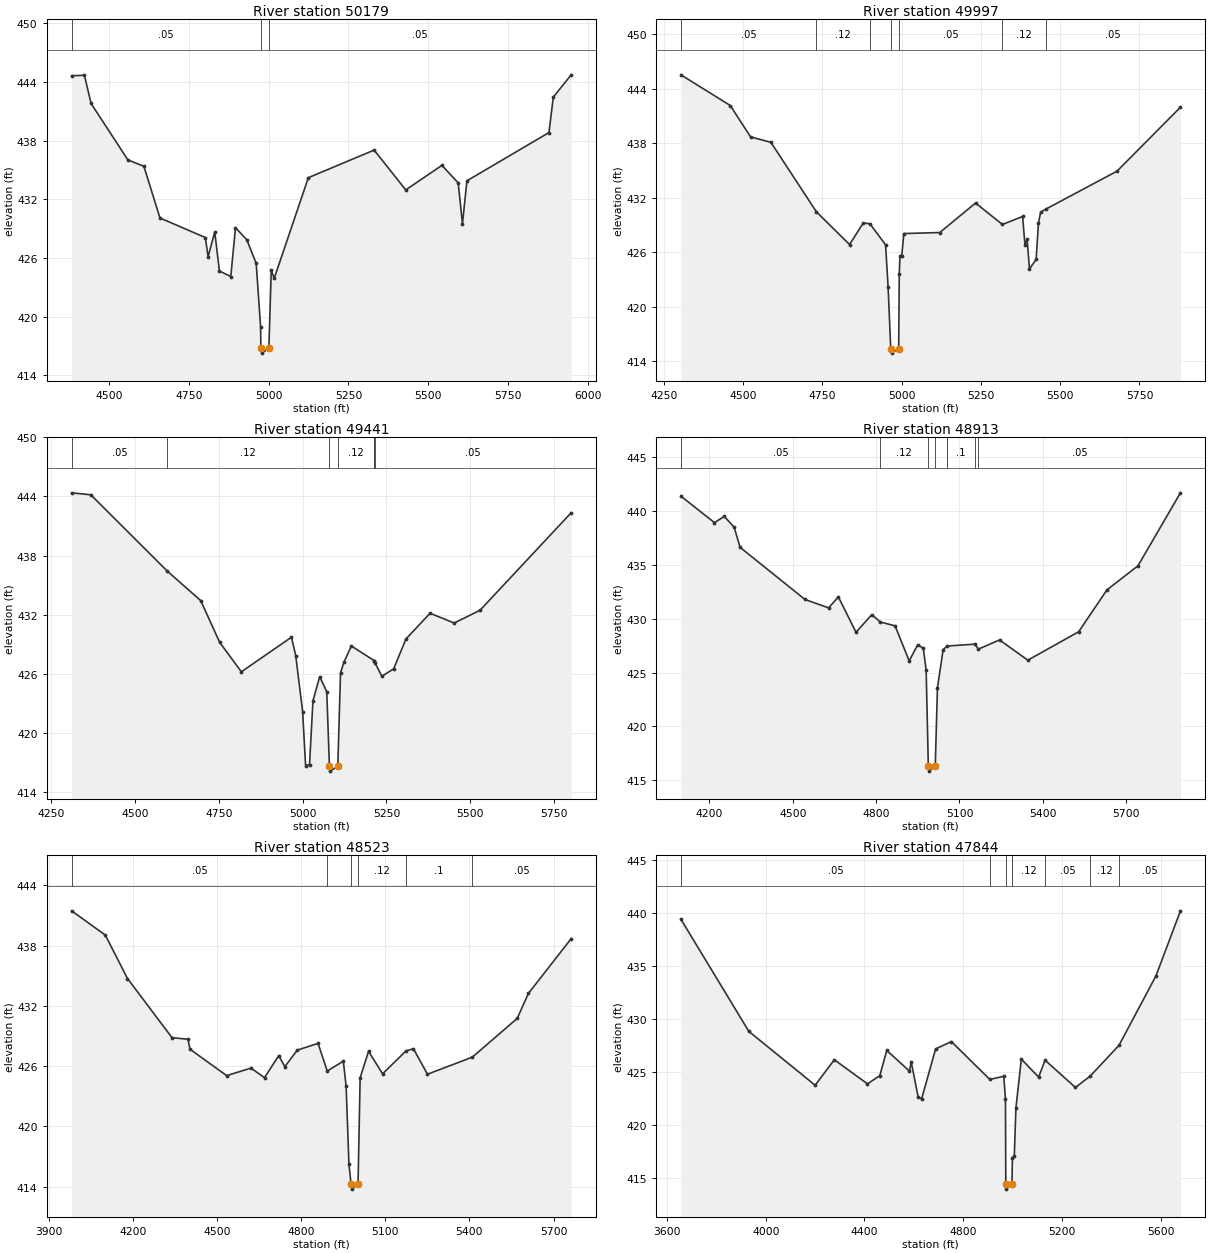
Type RM Length L Ch R = 1 ,50179   ,182,182,182
BEGIN DESCRIPTION:
Mapping XS 4e9b4aee
END DESCRIPTION:
XS GIS Cut Line= 3
      2704324.74      6925158.56      2703816.91      6924789.62
      2703092.72      6924195.52
#Sta/Elev= 30
    4383  444.63    4423  444.67  4443.9  441.79  4559.1  436.03  4609.3  435.37
  4659.6  430.09  4801.8  428.09  4810.3  426.13  4831.2  428.66  4845.8  424.67
  4881.4  424.11  4896.1   429.1  4931.6  427.86    4961  425.44  4974.7  418.98
  4975.6  416.78  4978.1  416.28  5000.6  416.78  5008.2  424.76  5017.4  423.92
  5124.3  434.21  5330.3  437.03  5429.3  432.96  5542.7  435.47  5593.6  433.67
  5606.9   429.5  5620.9  433.89  5877.8  438.82  5891.4  442.44  5947.4  444.72
#Mann= 3 ,-1 , 0
    4383     .05       0  4975.6     .05       0  5000.6     .05       0
Bank Sta=4975.6,5000.6
XS Rating Curve= 0 ,0
Exp/Cntr=0.3,0.1

Type RM Length L Ch R = 1 ,49997   ,556,556,556
BEGIN DESCRIPTION:
Mapping XS d20cb77b
END DESCRIPTION:
XS GIS Cut Line= 3
      2704418.72      6925066.55      2703879.63      6924634.24
      2703278.15      6923985.89
#Sta/Elev= 30
  4303.9  445.52  4459.7  442.14  4523.7  438.68  4587.7  438.09  4731.3  430.43
  4835.8  426.83    4879   429.2    4900  429.12  4949.4   426.8  4957.4  422.15
  4965.7  415.37  4968.2  414.87  4990.7  415.37  4992.6  423.58  4994.9   425.6
  5000.5   425.6  5006.9  428.04  5120.3  428.15  5233.1   431.4  5317.8  429.04
  5381.6  429.92    5389  426.78  5395.8  427.43  5403.2  424.13  5424.2   425.2
  5431.5  429.17  5438.3  430.38  5454.8  430.73  5679.3  434.91  5879.3  441.95
#Mann= 7 ,-1 , 0
  4303.9     .05       0  4731.3     .12       0    4900     .05       0
  4965.7    .035       0  4990.7     .05       0  5317.8     .12       0
  5454.8     .05       0
Bank Sta=4965.7,4990.7
XS Rating Curve= 0 ,0
Exp/Cntr=0.3,0.1

Type RM Length L Ch R = 1 ,49441   ,528,528,528
BEGIN DESCRIPTION:
Mapping XS 7e657637
END DESCRIPTION:
XS GIS Cut Line= 3
       2704508.1      6924677.64      2704140.05      6924174.17
      2703296.31      6923972.78
#Sta/Elev= 30
  4310.5  444.37  4367.7  444.17  4595.6  436.44  4695.9  433.43  4752.3   429.2
  4817.2  426.21  4966.7  429.72  4979.4  427.85    5000  422.17  5008.8   416.7
  5020.6  416.79  5030.8  423.27  5050.9  425.71    5072  424.19    5080  416.63
  5082.5  416.13    5105  416.63  5113.1   426.1  5123.4  427.19  5145.4  428.83
  5213.3  427.35    5214  427.29  5215.8  427.13  5236.5  425.76  5271.7  426.51
  5308.4  429.54  5380.4  432.15  5452.4  431.16  5529.4  432.45  5801.6  442.35
#Mann= 7 ,-1 , 0
  4310.5     .05       0  4595.6     .12       0    5080     .07       0
    5105     .12       0  5213.3     .05       0    5214     .12       0
  5215.8     .05       0
Bank Sta=5080,5105
XS Rating Curve= 0 ,0
Exp/Cntr=0.3,0.1

Type RM Length L Ch R = 1 ,48913   ,390,390,390
BEGIN DESCRIPTION:
Mapping XS ce89ba6e
END DESCRIPTION:
XS GIS Cut Line= 3
      2704983.83      6924333.93      2704476.85      6923781.81
      2703445.63      6923594.31
#Sta/Elev= 30
  4097.5  441.39  4218.4  438.93  4253.6  439.51  4289.3   438.5  4310.3  436.64
    4544  431.79  4629.1  431.01  4664.2  432.03  4727.7  428.74  4784.4  430.38
  4814.9   429.7  4868.3  429.34  4919.1  426.08  4949.6  427.58  4969.9  427.26
  4980.1  425.23  4987.9  416.34  4990.4  415.84  5012.9  416.34  5020.7  423.56
  5041.1  427.11  5054.6  427.46  5154.8  427.64  5168.4  427.18  5244.3  428.03
    5346  426.15  5528.9  428.79  5630.6  432.68  5742.4  434.92  5895.2   441.7
#Mann= 7 ,-1 , 0
  4097.5     .05       0  4814.9     .12       0  4987.9     .07       0
  5012.9     .12       0  5054.6      .1       0  5154.8     .12       0
  5168.4     .05       0
Bank Sta=4987.9,5012.9
XS Rating Curve= 0 ,0
Exp/Cntr=0.3,0.1

Type RM Length L Ch R = 1 ,48523   ,679,679,679
BEGIN DESCRIPTION:
Mapping XS c7850f50
END DESCRIPTION:
XS GIS Cut Line= 3
       2705195.6      6923847.78      2704476.85      6923361.67
      2703563.65      6923375.56
#Sta/Elev= 30
  3981.8  441.46    4102  439.04  4180.9  434.72  4339.7  428.83  4396.7  428.67
  4403.8  427.68  4534.5  425.05  4621.1   425.8  4669.4  424.85  4720.3  427.05
  4741.9  425.94  4786.2  427.59  4860.3  428.26    4893  425.51  4950.4  426.49
  4960.4  424.01  4970.4  416.28  4977.9  414.25  4980.4  413.75  5002.9  414.25
  5010.4  424.84  5040.4  427.47  5090.4  425.23    5174  427.51  5200.4  427.73
  5250.4  425.19  5410.4  426.89  5570.4  430.75  5610.4  433.24  5762.8  438.69
#Mann= 6 ,-1 , 0
  3981.8     .05       0    4893     .12       0  4977.9     .07       0
  5002.9     .12       0    5174      .1       0  5410.4     .05       0
Bank Sta=4977.9,5002.9
XS Rating Curve= 0 ,0
Exp/Cntr=0.3,0.1

Type RM Length L Ch R = 1 ,47844   ,555,555,555
BEGIN DESCRIPTION:
Mapping XS 98b1c8e6
END DESCRIPTION:
XS GIS Cut Line= 3
      2705219.94      6923715.86      2704251.16      6922816.53
      2703721.17      6922355.82
#Sta/Elev= 30
  3656.4   439.4  3931.7  428.84  4200.4  423.77  4278.1  426.17  4412.4   423.9
  4462.3  424.67  4490.6  427.05  4582.5   425.1  4589.6  425.97  4617.7  422.67
  4631.8  422.49  4688.5  427.19  4752.5  427.88    4908  424.32  4964.6  424.61
  4971.5  422.52  4972.9  414.49  4975.4  413.99  4997.9  414.49  4999.6  416.94
  5007.3   417.1  5013.9  421.62  5035.8  426.23    5106  424.53  5131.9  426.13
  5255.1  423.56  5314.9  424.63  5431.6  427.53  5581.4  434.07  5680.5  440.19
#Mann= 7 ,-1 , 0
  3656.4     .05       0    4908     .12       0  4972.9     .07       0
  4997.9     .12       0  5131.9     .05       0  5314.9     .12       0
  5431.6     .05       0
Bank Sta=4972.9,4997.9
XS Rating Curve= 0 ,0
Exp/Cntr=0.3,0.1