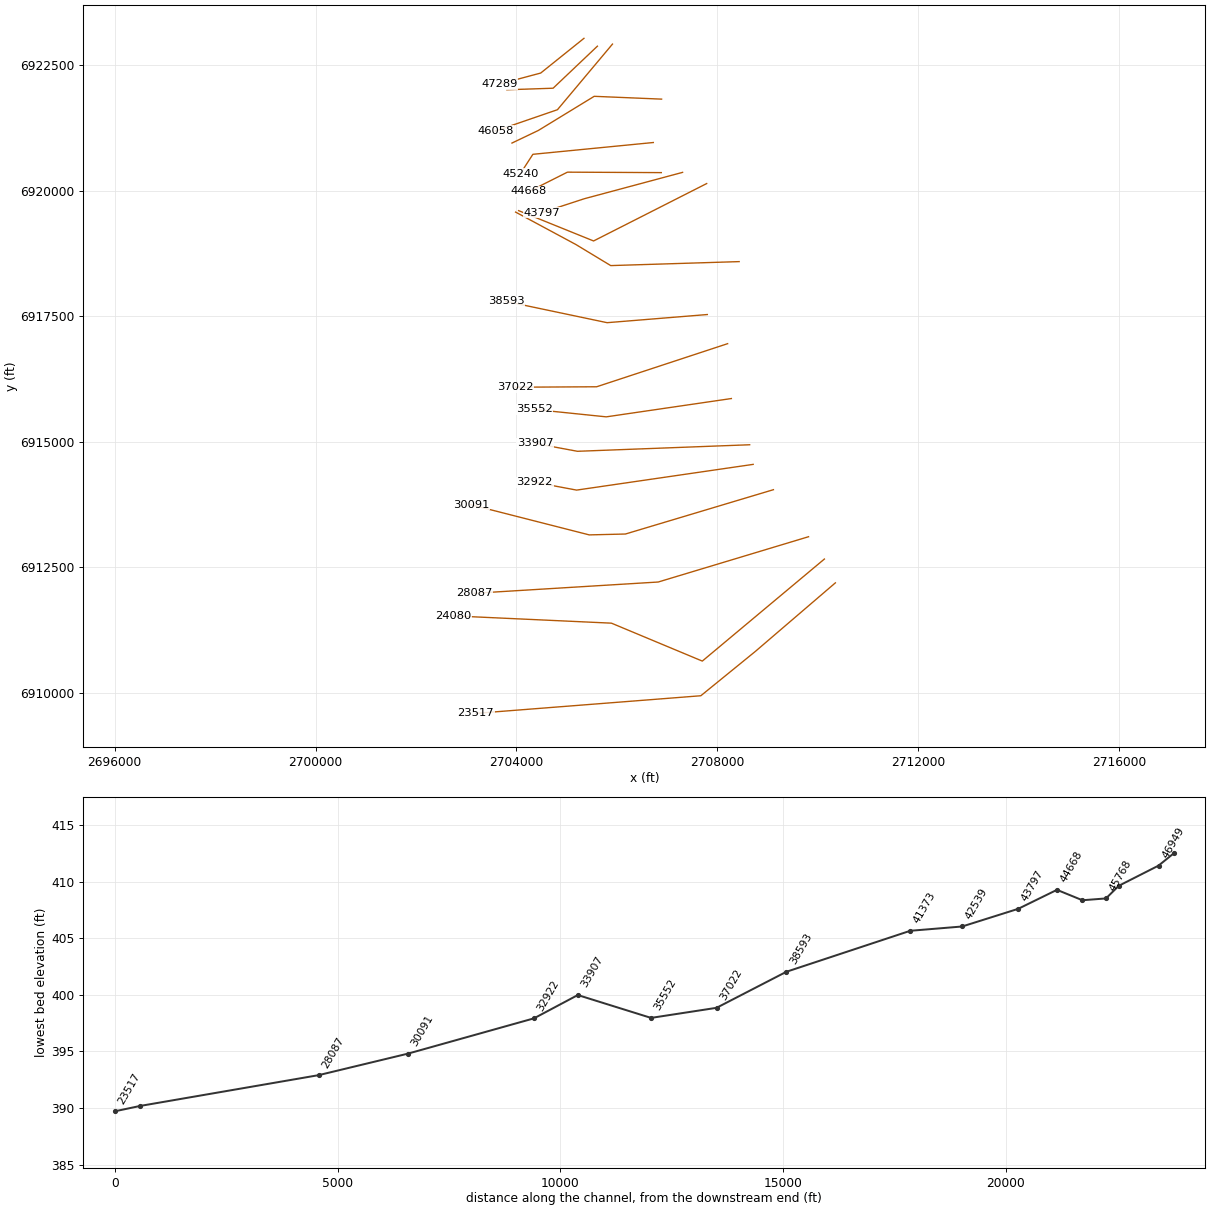
HEC-RAS study Rocky Cedar Creek.prj: Rocky Cedar Creek Base Level Engineering

--- Rocky Cedar Creek.g01 (geometry) --- (continued)

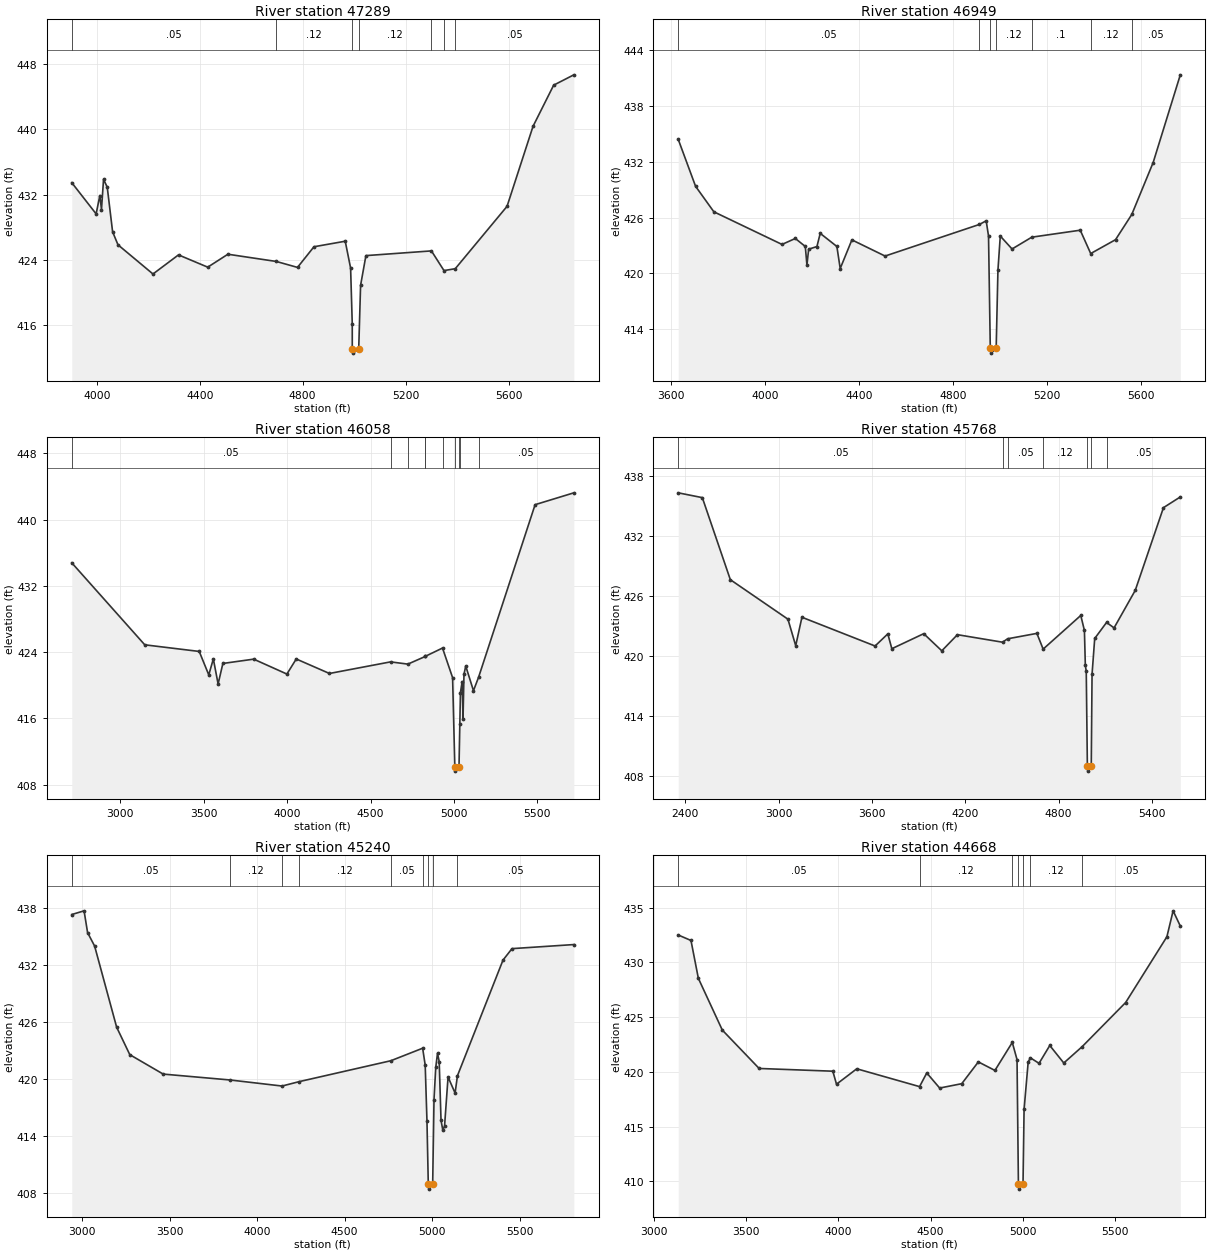
Type RM Length L Ch R = 1 ,47289   ,340,340,340
BEGIN DESCRIPTION:
Mapping XS 082a362f
END DESCRIPTION:
XS GIS Cut Line= 3
      2705344.91      6923035.28       2704483.8      6922344.31
      2703665.22      6922125.79
#Sta/Elev= 30
  3902.6  433.46  3997.3  429.62  4011.7  431.88  4018.1  430.16  4026.1  433.88
  4040.5   432.9  4061.3  427.42  4082.2  425.82  4218.2  422.23  4317.4  424.58
    4431  423.07  4509.4  424.66  4697.8  423.77  4779.9  423.04  4843.9  425.58
  4965.4  426.26  4986.3  422.96  4992.7  416.09  4992.8     413  4995.3   412.5
  5017.8     413  5025.1  420.84  5045.8  424.49  5300.4  425.07  5349.2  422.65
    5393  422.88  5594.3  430.55  5695.3  440.39  5775.5  445.45  5853.9  446.72
#Mann= 7 ,-1 , 0
  3902.6     .05       0  4697.8     .12       0  4992.8     .07       0
  5017.8     .12       0  5300.4     .05       0  5349.2      .1       0
    5393     .05       0
Bank Sta=4992.8,5017.8
XS Rating Curve= 0 ,0
Exp/Cntr=0.3,0.1

Type RM Length L Ch R = 1 ,46949   ,891,891,891
BEGIN DESCRIPTION:
Mapping XS efeb500e
END DESCRIPTION:
XS GIS Cut Line= 3
      2705612.24        6922879.      2704730.32      6922042.22
      2703810.57      6922010.99
#Sta/Elev= 30
  3630.2  434.41    3704  429.36  3781.7  426.62  4071.7  423.11  4128.3  423.75
  4170.8  422.89  4177.7  420.89    4185   422.6  4220.2  422.88  4234.3   424.3
  4305.1  422.89  4319.3  420.52    4369   423.6  4510.2  421.86  4911.5  425.26
  4940.3  425.65  4950.3  424.01  4957.8  411.92  4960.3  411.42  4982.8  411.92
  4990.3  420.33  5000.3  424.01  5050.4  422.62  5134.3  423.89  5340.5  424.64
    5385  422.13  5490.6  423.62  5559.7  426.33  5650.7  431.92  5766.2  441.35
#Mann= 7 ,-1 , 0
  3630.2     .05       0  4911.5     .12       0  4957.8     .07       0
  4982.8     .12       0  5134.3      .1       0    5385     .12       0
  5559.7     .05       0
Bank Sta=4957.8,4982.8
XS Rating Curve= 0 ,0
Exp/Cntr=0.3,0.1

Type RM Length L Ch R = 1 ,46058   ,290,290,290
BEGIN DESCRIPTION:
Mapping XS 927b1e70
END DESCRIPTION:
XS GIS Cut Line= 3
      2705912.61      6922920.73      2704817.01      6921614.25
      2703583.13       6921189.8
#Sta/Elev= 30
  2708.9  434.79  3146.5  424.89    3473  424.09  3530.2  421.26  3557.6  423.19
  3586.2  420.16  3614.8  422.64  3799.5  423.16  3998.6  421.36  4054.6  423.18
  4253.6  421.43  4619.9  422.83  4723.8  422.56  4827.6  423.48  4828.4   423.5
  4931.5   424.5    4992  420.92  5005.3  410.14  5007.8  409.64  5030.3  410.14
  5035.3  415.31    5039  419.13  5049.2  420.46  5054.5  415.99  5060.1  421.33
  5070.7  422.33    5117  419.35  5147.8  420.98  5486.5  441.81  5718.8  443.24
#Mann= 10 ,-1 , 0
  2708.9     .05       0  4619.9      .1       0  4723.8     .12       0
  4827.6      .1       0  4828.4     .12       0  4931.5      .1       0
  5005.3     .07       0  5030.3      .1       0  5035.3     .12       0
  5147.8     .05       0
Bank Sta=5005.3,5030.3
XS Rating Curve= 0 ,0
Exp/Cntr=0.3,0.1

Type RM Length L Ch R = 1 ,45768   ,528,528,528
BEGIN DESCRIPTION:
Mapping XS 785fc031
END DESCRIPTION:
XS GIS Cut Line= 4
       2706890.8      6921824.91      2705548.73      6921880.87
      2704437.15      6921201.48       2703911.2      6920950.19
#Sta/Elev= 30
    2354   436.3  2508.9  435.82  2689.1  427.63  3059.4  423.69  3109.5  421.04
  3149.5  423.88  3619.9  421.01  3701.8  422.22  3727.7  420.74  3932.8  422.24
    4049  420.53  4149.6  422.14  4439.5  421.39  4472.4  421.73  4660.5  422.27
  4700.8   420.7  4942.8  424.06  4966.2  422.56  4972.1  419.08    4978  418.47
  4985.2  409.02  4987.7  408.52  5010.2  409.02  5015.3   418.2  5032.4  421.76
  5108.5  423.36  5156.9  422.82    5293  426.56  5474.5  434.82  5582.9  435.89
#Mann= 7 ,-1 , 0
    2354     .05       0  4439.5     .12       0  4472.4     .05       0
  4700.8     .12       0  4985.2     .07       0  5010.2     .12       0
  5108.5     .05       0
Bank Sta=4985.2,5010.2
XS Rating Curve= 0 ,0
Exp/Cntr=0.3,0.1

Type RM Length L Ch R = 1 ,45240   ,572,572,572
BEGIN DESCRIPTION:
Rocky Cedar Creek 24.0
END DESCRIPTION:
XS GIS Cut Line= 3
      2706726.01        6920961.      2704327.89      6920726.25
      2704077.88      6920340.82
#Sta/Elev= 30
  2940.5  437.34  3010.8  437.73  3030.9  435.43  3071.1  434.01  3196.9  425.45
  3272.1  422.55    3463   420.5  3844.3  419.88    4142  419.24  4241.3  419.71
  4763.8  421.91  4945.5  423.23  4960.1  421.45  4970.2  415.54  4977.8  408.86
  4980.3  408.36  5002.8  408.86  5010.4  417.81  5020.4  421.21  5030.5   422.7
  5040.1  421.82  5050.5  415.62  5060.6   414.6  5070.6  414.98  5090.7  420.19
  5130.9   418.5  5144.4  420.33  5404.7  432.53  5456.1  433.74  5809.5  434.17
#Mann= 9 ,-1 , 0
  2940.5     .05       0  3844.3     .12       0    4142      .1       0
  4241.3     .12       0  4763.8     .05       0  4945.5     .12       0
  4977.8     .07       0  5002.8     .12       0  5144.4     .05       0
Bank Sta=4977.8,5002.8
XS Rating Curve= 0 ,0
Exp/Cntr=0.3,0.1

Type RM Length L Ch R = 1 ,44668   ,871,871,871
BEGIN DESCRIPTION:
Rocky Cedar Creek 22.0
END DESCRIPTION:
XS GIS Cut Line= 3
      2706885.15      6920361.67      2705015.57      6920370.81
      2704250.96      6919985.98
#Sta/Elev= 30
  3130.4  432.51  3199.6  432.01  3239.6  428.55  3369.6  423.82  3569.6  420.31
  3969.6  420.06  3989.6  418.87  4099.6  420.28  4440.5  418.65  4479.6   419.9
  4549.6  418.52  4669.6  418.92  4759.6  420.91  4849.6  420.13  4943.9  422.69
  4969.6  421.12  4977.1  409.78  4979.6  409.28  5002.1  409.78  5007.9  416.57
  5030.2  420.91  5042.4  421.28  5089.1  420.78  5147.4  422.41  5223.4  420.81
  5322.9   422.3  5559.3  426.34  5783.2  432.35  5816.9  434.72    5856  433.33
#Mann= 7 ,-1 , 0
  3130.4     .05       0  4440.5     .12       0  4943.9      .1       0
  4977.1     .07       0  5002.1      .1       0  5042.4     .12       0
  5322.9     .05       0
Bank Sta=4977.1,5002.1
XS Rating Curve= 0 ,0
Exp/Cntr=0.3,0.1

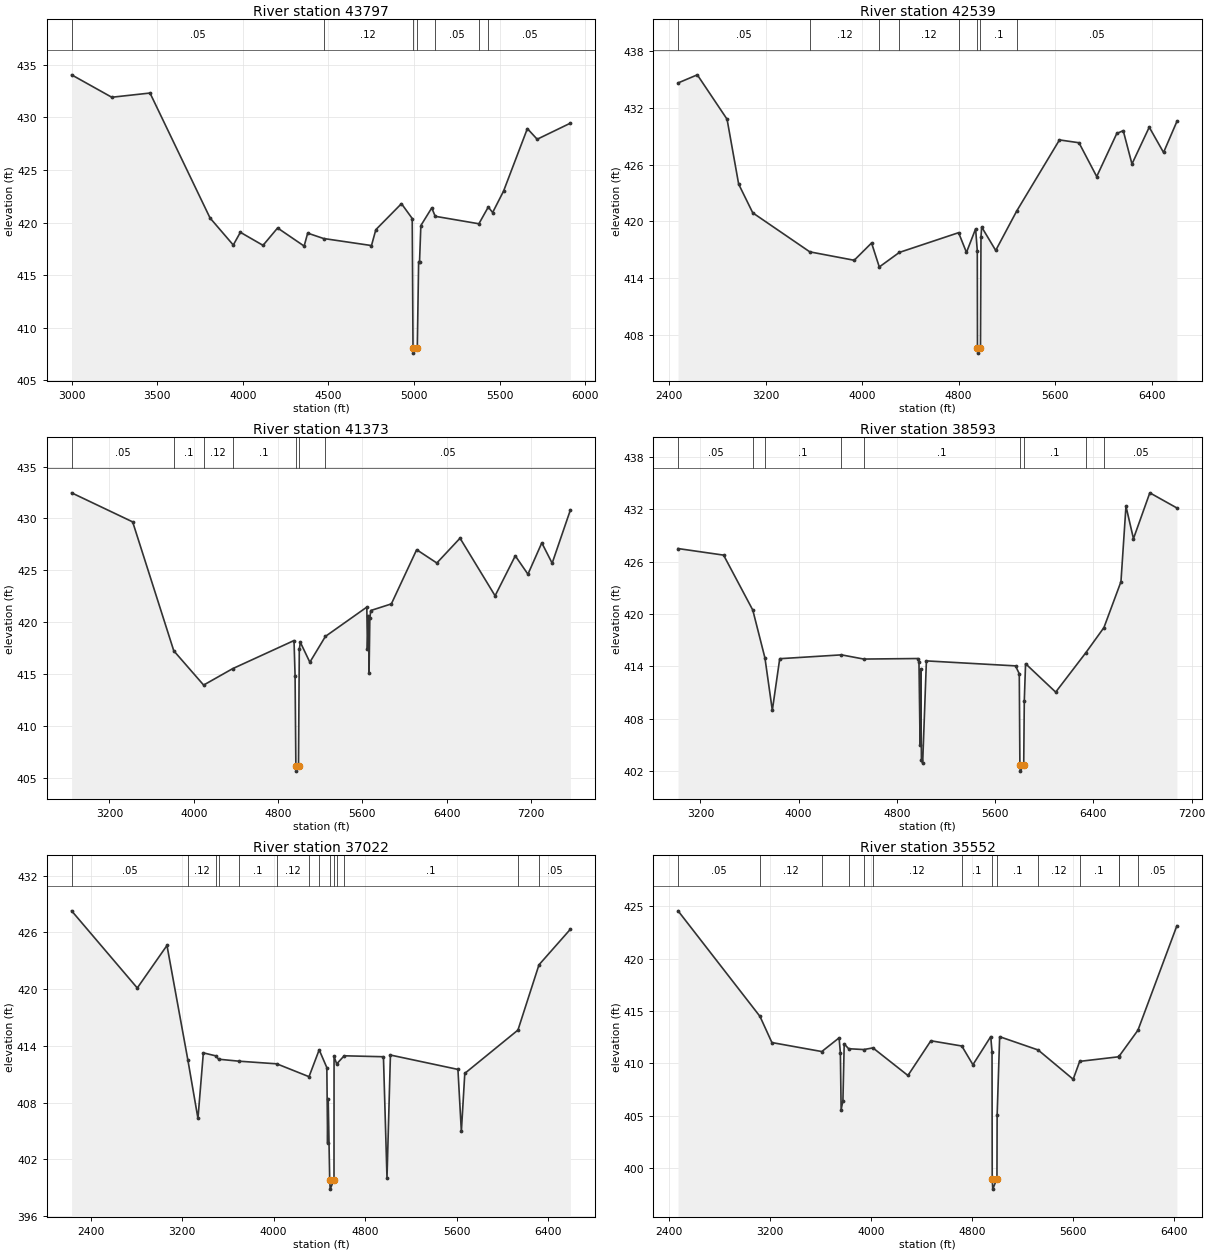
Type RM Length L Ch R = 1 ,43797   ,1258,1258,1258
BEGIN DESCRIPTION:
Mapping XS 855040b6
END DESCRIPTION:
XS GIS Cut Line= 3
      2707308.41      6920366.64      2705348.73      6919840.84
      2704506.83       6919565.4
#Sta/Elev= 30
  2999.2  434.04  3233.9  431.91  3457.3  432.31  3808.1  420.44  3943.9  417.87
  3985.3  419.08  4117.7  417.84  4202.9  419.49    4358  417.77  4378.7     419
  4471.5  418.49  4751.5  417.82    4777  419.33  4926.7   421.8  4989.6  420.39
  4994.2   408.1  4996.7   407.6  5019.2   408.1    5027  416.29  5032.3  416.29
    5040  419.72  5103.8   421.4  5123.8   420.6  5379.1  419.89  5433.9  421.48
  5459.5  420.96  5523.2  422.99  5662.4  428.93  5719.7  427.92    5914  429.45
#Mann= 7 ,-1 , 0
  2999.2     .05       0  4471.5     .12       0  4994.2     .07       0
  5019.2     .12       0  5123.8     .05       0  5379.1     .12       0
  5433.9     .05       0
Bank Sta=4994.2,5019.2
XS Rating Curve= 0 ,0
Exp/Cntr=0.3,0.1

Type RM Length L Ch R = 1 ,42539   ,1166,1166,1166
BEGIN DESCRIPTION:
Mapping XS 273cd06e
END DESCRIPTION:
XS GIS Cut Line= 3
      2707788.28      6920143.82       2705536.3       6919000.9
      2704043.61      6919604.72
#Sta/Elev= 30
  2474.6  434.64  2634.2   435.5  2880.9   430.8  2977.1  423.93    3094  420.89
    3567  416.76    3935  415.87    4079   417.7    4143  415.16  4309.1   416.7
  4800.4  418.79  4865.8   416.7  4941.6   419.2  4955.5  416.86    4957  406.54
  4959.5  406.04    4982  406.54  4986.1  418.35  4991.7  419.39  5108.2  416.91
  5282.2  421.08  5636.8  428.61  5798.6  428.31  5945.6  424.73  6111.9  429.29
  6165.5  429.59  6237.9  426.06  6381.1  429.96  6499.7  427.28  6610.2  430.56
#Mann= 8 ,-1 , 0
  2474.6     .05       0    3567     .12       0    4143      .1       0
  4309.1     .12       0  4800.4      .1       0    4957     .07       0
    4982      .1       0  5282.2     .05       0
Bank Sta=4957,4982
XS Rating Curve= 0 ,0
Exp/Cntr=0.3,0.1

Type RM Length L Ch R = 1 ,41373   ,2780,2780,2780
BEGIN DESCRIPTION:
Mapping XS c7627d94
END DESCRIPTION:
XS GIS Cut Line= 4
      2708434.89      6918589.65        2705878.      6918510.46
      2705182.57      6918931.01      2703983.82      6919575.62
#Sta/Elev= 30
  2841.4  432.47  3420.6  429.67  3810.7  417.25  4093.8  413.95  4368.8  415.53
  4951.3  418.24  4961.3  414.84  4968.8  406.16  4971.3  405.66  4993.8  406.16
  5001.3  417.39  5011.3  418.07  5101.4  416.15  5249.2  418.64  5641.8  421.46
  5647.6  417.44  5657.3  420.59  5663.1  415.09  5670.6  420.37  5678.6  421.13
  5874.6  421.77  6114.7  426.99    6306  425.71  6526.2   428.1  6858.7  422.55
  7050.2   426.4  7170.3  424.63  7301.8  427.65    7400  425.69  7573.3  430.83
#Mann= 7 ,-1 , 0
  2841.4     .05       0  3810.7      .1       0  4093.8     .12       0
  4368.8      .1       0  4968.8     .07       0  4993.8      .1       0
  5249.2     .05       0
Bank Sta=4968.8,4993.8
XS Rating Curve= 0 ,0
Exp/Cntr=0.3,0.1

Type RM Length L Ch R = 1 ,38593   ,1571,1571,1571
BEGIN DESCRIPTION:
Mapping XS dddff31b
END DESCRIPTION:
XS GIS Cut Line= 3
      2707801.02        6917536.      2705805.76      6917373.82
      2703790.41      6917797.77
#Sta/Elev= 30
  3018.1  427.48  3388.9  426.73  3626.5  420.45  3725.6  414.97  3785.6  408.99
  3845.8  414.89  4348.5  415.33  4529.9  414.85  4969.5  414.91  4979.6  414.48
  4988.8  404.98  4993.8   413.7  4999.6  403.35  5009.7  402.95  5040.1  414.64
  5765.7  414.07  5796.3  413.17  5801.3  402.74  5804.3  402.04  5832.3  402.74
  5837.2  410.11  5847.4  414.32  6092.7  411.07  6336.3  415.54  6485.6  418.45
  6624.1  423.69  6664.9  432.32  6725.9  428.61  6859.1  433.85  7079.4  432.12
#Mann= 9 ,-1 , 0
  3018.1     .05       0  3626.5     .12       0  3725.6      .1       0
  4348.5     .12       0  4529.9      .1       0  5801.3     .07       0
  5832.3      .1       0  6336.3     .12       0  6485.6     .05       0
Bank Sta=5801.3,5832.3
XS Rating Curve= 0 ,0
Exp/Cntr=0.3,0.1

Type RM Length L Ch R = 1 ,37022   ,1470,1470,1470
BEGIN DESCRIPTION:
Mapping XS fbabbdd3
END DESCRIPTION:
XS GIS Cut Line= 3
      2708204.97      6916955.82      2705597.43      6916097.78
      2703982.84       6916089.1
#Sta/Elev= 30
    2234  428.28    2808  420.12  3067.5  424.62  3250.8  412.46  3338.3  406.33
  3385.4  413.26  3495.2  412.94    3518  412.59  3696.8  412.38  4027.4   412.1
    4309  410.74  4397.8  413.58  4464.7   411.7  4471.5  403.71  4476.7  408.35
  4489.8  399.85  4494.2  398.85  4527.3  399.85  4527.9  412.89  4550.7  412.09
  4616.4  412.95  4959.5  412.85  4990.5  400.04  5020.5  413.03  5610.5  411.51
  5640.5  404.95  5670.5  411.09    6135  415.67  6318.8  422.57  6593.7  426.34
#Mann= 14 ,-1 , 0
    2234     .05       0  3250.8     .12       0  3495.2      .1       0
    3518     .12       0  3696.8      .1       0  4027.4     .12       0
    4309      .1       0  4397.8     .12       0  4489.8     .07       0
  4527.3     .12       0  4550.7     .12       0  4616.4      .1       0
    6135     .12       0  6318.8     .05       0
Bank Sta=4489.8,4527.3
XS Rating Curve= 0 ,0
Exp/Cntr=0.3,0.1

Type RM Length L Ch R = 1 ,35552   ,1645,1645,1645
BEGIN DESCRIPTION:
Mapping XS 9de1910c
END DESCRIPTION:
XS GIS Cut Line= 3
      2708279.76      6915863.41       2705788.4      6915498.82
      2704357.97       6915646.2
#Sta/Elev= 30
  2470.5  424.58  3120.3  414.48  3214.7  411.98  3610.5  411.12  3747.7  412.43
  3757.8  410.98  3763.8  405.56    3778  406.42  3788.1  411.85  3823.4  411.39
  3943.2  411.31    4016  411.47  4293.5  408.83  4475.4  412.15  4720.8  411.65
  4808.9  409.86  4950.4  412.55  4960.5  411.06    4962  398.96  4966.4  397.96
  4999.5  398.96  5000.9  405.01    5021  412.54  5326.1  411.27    5604  408.47
  5655.7  410.18  5964.9  410.62    5970   410.7  6117.6  413.16  6426.4  423.15
#Mann= 14 ,-1 , 0
  2470.5     .05       0  3120.3     .12       0  3610.5      .1       0
  3823.4     .12       0  3943.2      .1       0    4016     .12       0
  4720.8      .1       0    4962     .07       0  4999.5      .1       0
  5326.1     .12       0  5655.7      .1       0  5964.9     .05       0
    5970      .1       0  6117.6     .05       0
Bank Sta=4962,4999.5
XS Rating Curve= 0 ,0
Exp/Cntr=0.3,0.1

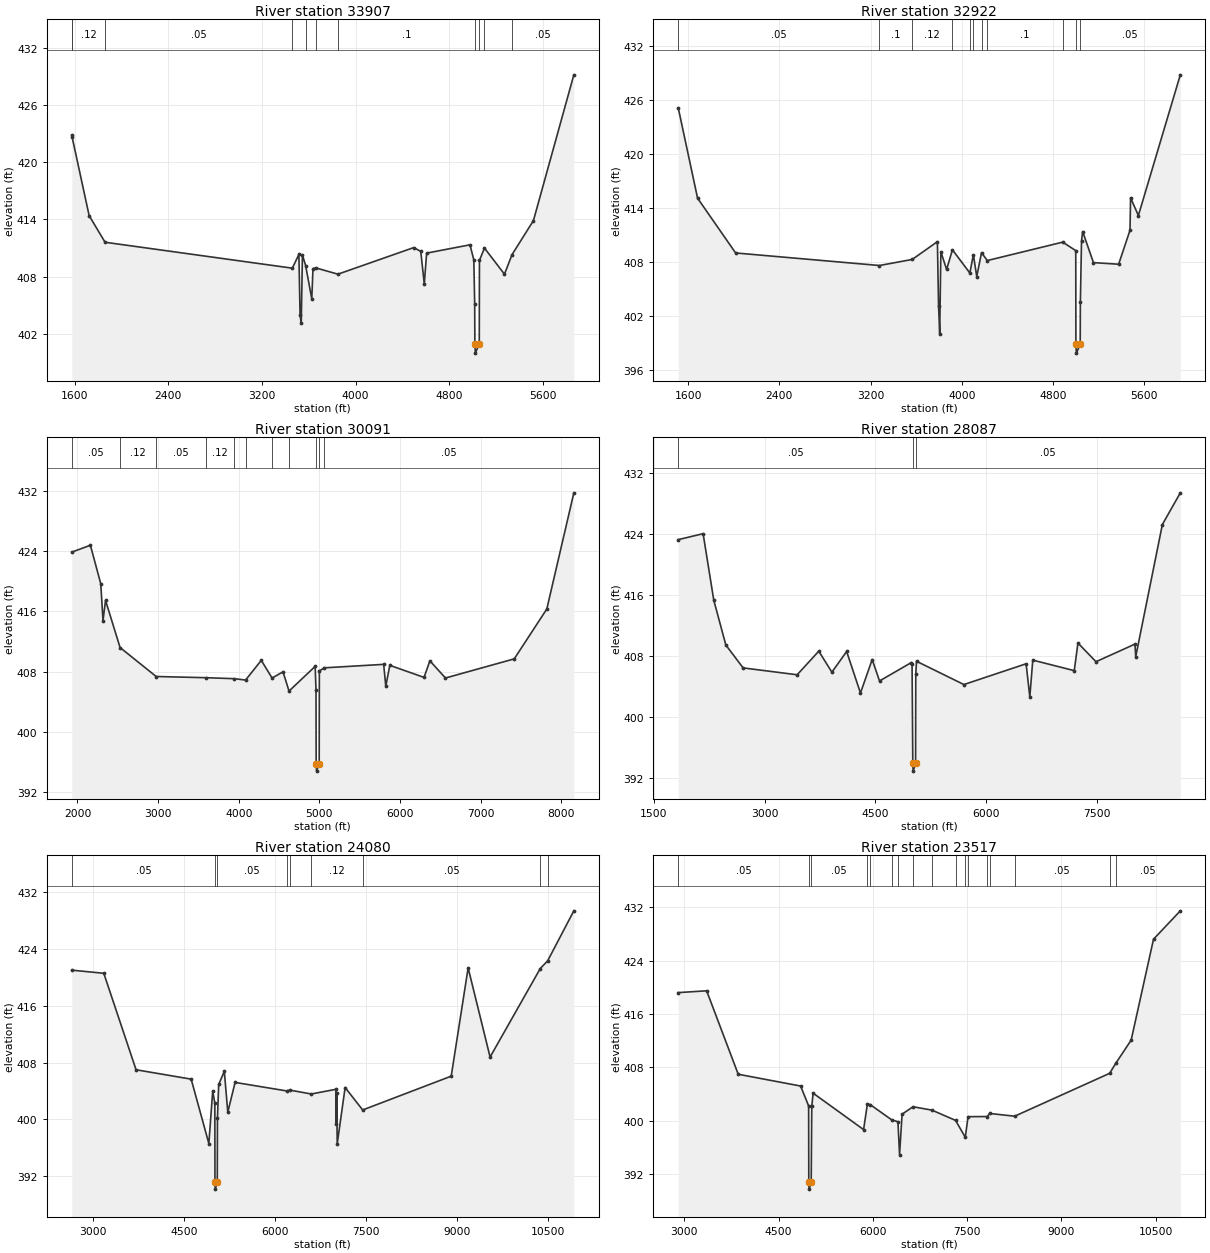
Type RM Length L Ch R = 1 ,33907   ,985,985,985
BEGIN DESCRIPTION:
Mapping XS 39c6e178
END DESCRIPTION:
XS GIS Cut Line= 3
      2708644.28      6914943.26      2705215.48      6914813.06
      2704373.42      6914969.32
#Sta/Elev= 30
  1575.9  422.83  1578.6  422.66  1724.3   414.4  1860.2  411.61  3459.4  408.89
  3515.6  410.33  3525.6  403.94  3535.6  403.12  3545.6  410.27  3573.1  409.17
  3625.7  405.66  3635.7  408.83  3657.4  408.93  3848.8  408.26  4496.3  411.05
  4556.3  410.65  4586.3  407.24  4606.4  410.47  4976.6  411.34  5009.4  409.76
  5016.8  405.14  5018.3  400.98  5022.8  399.98    5056  400.98  5057.5   409.7
  5100.2     411  5271.1  408.26  5335.7  410.31  5518.4  413.88  5863.6  429.17
#Mann= 11 ,-1 , 0
  1575.9     .05       0  1578.6     .12       0  1860.2     .05       0
  3459.4     .12       0  3573.1      .1       0  3657.4     .12       0
  3848.8      .1       0  5018.3     .07       0    5056      .1       0
  5100.2     .12       0  5335.7     .05       0
Bank Sta=5018.3,5056
XS Rating Curve= 0 ,0
Exp/Cntr=0.3,0.1

Type RM Length L Ch R = 1 ,32922   ,2831,2831,2831
BEGIN DESCRIPTION:
Mapping XS 4ea770cf
END DESCRIPTION:
XS GIS Cut Line= 3
      2708713.77      6914552.64      2705198.12      6914040.49
       2704364.8      6914196.74
#Sta/Elev= 30
  1513.9   425.1  1683.4  415.09  2016.9  409.02  3277.3  407.63  3564.5   408.3
  3785.4  410.27  3795.5  403.18  3805.6  400.09  3815.7  409.15  3866.2  407.19
  3917.2  409.37  4069.8   406.8  4100.6  408.82  4130.3  406.41    4172  409.05
  4223.1  408.18  4883.9  410.22  4998.1  409.28  4999.4  398.92  5003.9  397.92
  5037.1  398.92  5038.5  403.56  5048.6  410.35  5058.7  411.39  5153.1  407.95
    5374  407.77  5473.6  411.54  5478.6  415.13    5547  413.17  5914.5  428.76
#Mann= 11 ,-1 , 0
  1513.9     .05       0  3277.3      .1       0  3564.5     .12       0
  3917.2      .1       0  4069.8     .12       0  4100.6      .1       0
    4172     .12       0  4223.1      .1       0  4883.9     .12       0
  4999.4     .07       0  5037.1     .05       0
Bank Sta=4999.4,5037.1
XS Rating Curve= 0 ,0
Exp/Cntr=0.3,0.1

Type RM Length L Ch R = 1 ,30091   ,2004,2004,2004
BEGIN DESCRIPTION:
Mapping XS 5c6e9d9f
END DESCRIPTION:
XS GIS Cut Line= 4
      2709117.11       6914048.6      2706170.34      6913165.92
      2705449.86      6913148.56      2703096.23       6913748.9
#Sta/Elev= 30
  1929.6  423.84  2160.4  424.76    2289  419.66  2316.9  414.76  2348.3  417.44
  2528.6  411.19  2976.2  407.35  3597.3  407.19  3943.5  407.06  4084.8  406.88
  4279.5  409.49  4413.5  407.15  4549.1  407.97  4623.6  405.42  4947.6  408.69
  4958.1  405.59  4960.1   395.8  4964.6   394.8  4997.8   395.8  4999.8  408.08
  5059.8   408.5  5797.2  408.96  5823.3  406.08  5873.8  408.83    6298  407.23
  6370.3  409.43  6563.4  407.15  7416.6  409.69  7820.1   416.3  8155.4  431.71
#Mann= 11 ,-1 , 0
  1929.6     .05       0  2528.6     .12       0  2976.2     .05       0
  3597.3     .12       0  3943.5     .05       0  4084.8      .1       0
  4413.5     .12       0  4623.6      .1       0  4960.1     .07       0
  4997.8      .1       0  5059.8     .05       0
Bank Sta=4960.1,4997.8
XS Rating Curve= 0 ,0
Exp/Cntr=0.3,0.1

Type RM Length L Ch R = 1 ,28087   ,4007,4007,4007
BEGIN DESCRIPTION:
Mapping XS 50e77b77
END DESCRIPTION:
XS GIS Cut Line= 3
       2709816.4      6913112.14      2706823.09      6912210.27
      2703163.76      6911986.23
#Sta/Elev= 30
  1832.3  423.22  2168.8     424  2313.1  415.29  2476.3  409.42    2710  406.42
  3441.1  405.52  3733.5  408.61  3911.1  405.86  4110.7  408.57  4297.5  403.13
  4456.4  407.51  4555.4  404.71  4985.7  407.12  4995.7  406.92  5005.7   393.9
  5010.2   392.9  5043.4   393.9  5045.8  405.56  5055.8  407.29    5697  404.24
  6538.6  406.96  6588.7  402.62  6628.7  407.44  7189.8  406.06  7239.9  409.68
  7484.1  407.23  8011.3  409.54  8021.3  407.88    8382   425.2  8624.7  429.35
#Mann= 3 ,-1 , 0
  1832.3     .05       0  5005.7    .035       0  5043.4     .05       0
Bank Sta=5005.7,5043.4
XS Rating Curve= 0 ,0
Exp/Cntr=0.3,0.1

Type RM Length L Ch R = 1 ,24080   ,563,563,563
BEGIN DESCRIPTION:
Mapping XS edc15824
END DESCRIPTION:
XS GIS Cut Line= 4
      2710131.88      6912667.84        2707701.        6910636.
      2705891.94      6911391.12      2702746.52      6911536.01
#Sta/Elev= 30
    2648     421  3175.7  420.56    3708  406.98  4616.4  405.66  4907.9   396.6
  4971.6  403.98  5006.8  402.26  5008.7  391.18  5013.3  390.18  5046.8  391.18
  5049.7   400.2  5070.5  404.91  5162.9  406.76  5220.2  401.01  5340.5   405.2
  6191.1     404  6240.6  404.12  6596.6  403.57  7002.8  404.23  7009.3  399.33
  7014.7  403.76  7024.4  396.57  7154.5  404.48  7444.1  401.32  8903.7  406.08
  9182.7  421.32  9544.4  408.77 10371.9  421.23 10493.9  422.32 10925.3  429.35
#Mann= 9 ,-1 , 0
    2648     .05       0  5008.7     .05       0  5046.8     .05       0
  6191.1     .12       0  6240.6      .1       0  6596.6     .12       0
  7444.1     .05       0 10371.9    .075       0 10493.9     .05       0
Bank Sta=5008.7,5046.8
XS Rating Curve= 0 ,0
Exp/Cntr=0.3,0.1

Type RM Length L Ch R = 1 ,23517   ,1063,1063,1063
BEGIN DESCRIPTION:
Mapping XS 5ed8a4f3
END DESCRIPTION:
XS GIS Cut Line= 4
      2710350.52      6912193.59      2708754.54       6910826.3
      2707671.86      6909945.91      2703190.82      6909594.88
#Sta/Elev= 30
  2902.8  419.22    3355  419.49  3857.7  406.96  4851.1  405.19  4978.4   402.2
    4981  390.71  4985.6  389.71  5019.2  390.71  5028.3  402.12    5050  404.12
  5853.2  398.65  5913.6   402.5  5958.8   402.4    6300  400.12  6399.7  399.83
  6425.8   394.9  6465.9  400.96  6640.3  402.08    6942  401.57  7317.5  400.03
    7472  397.49  7515.9  400.59  7821.5  400.61  7860.8  401.07  8257.7  400.66
  9769.9   407.1    9869  408.63   10112  412.08 10468.1  427.24 10894.6   431.5
#Mann= 17 ,-1 , 0
  2902.8     .05       0    4981    .035       0  5019.2     .05       0
  5913.6     .12       0  5958.8     .05       0    6300     .12       0
  6399.7      .1       0  6640.3     .12       0    6942      .1       0
  7317.5     .12       0    7472      .1       0  7515.9     .12       0
  7821.5      .1       0  7860.8     .12       0  8257.7     .05       0
  9769.9      .1       0    9869     .05       0
Bank Sta=4981,5019.2
XS Rating Curve= 0 ,0
Exp/Cntr=0.3,0.1