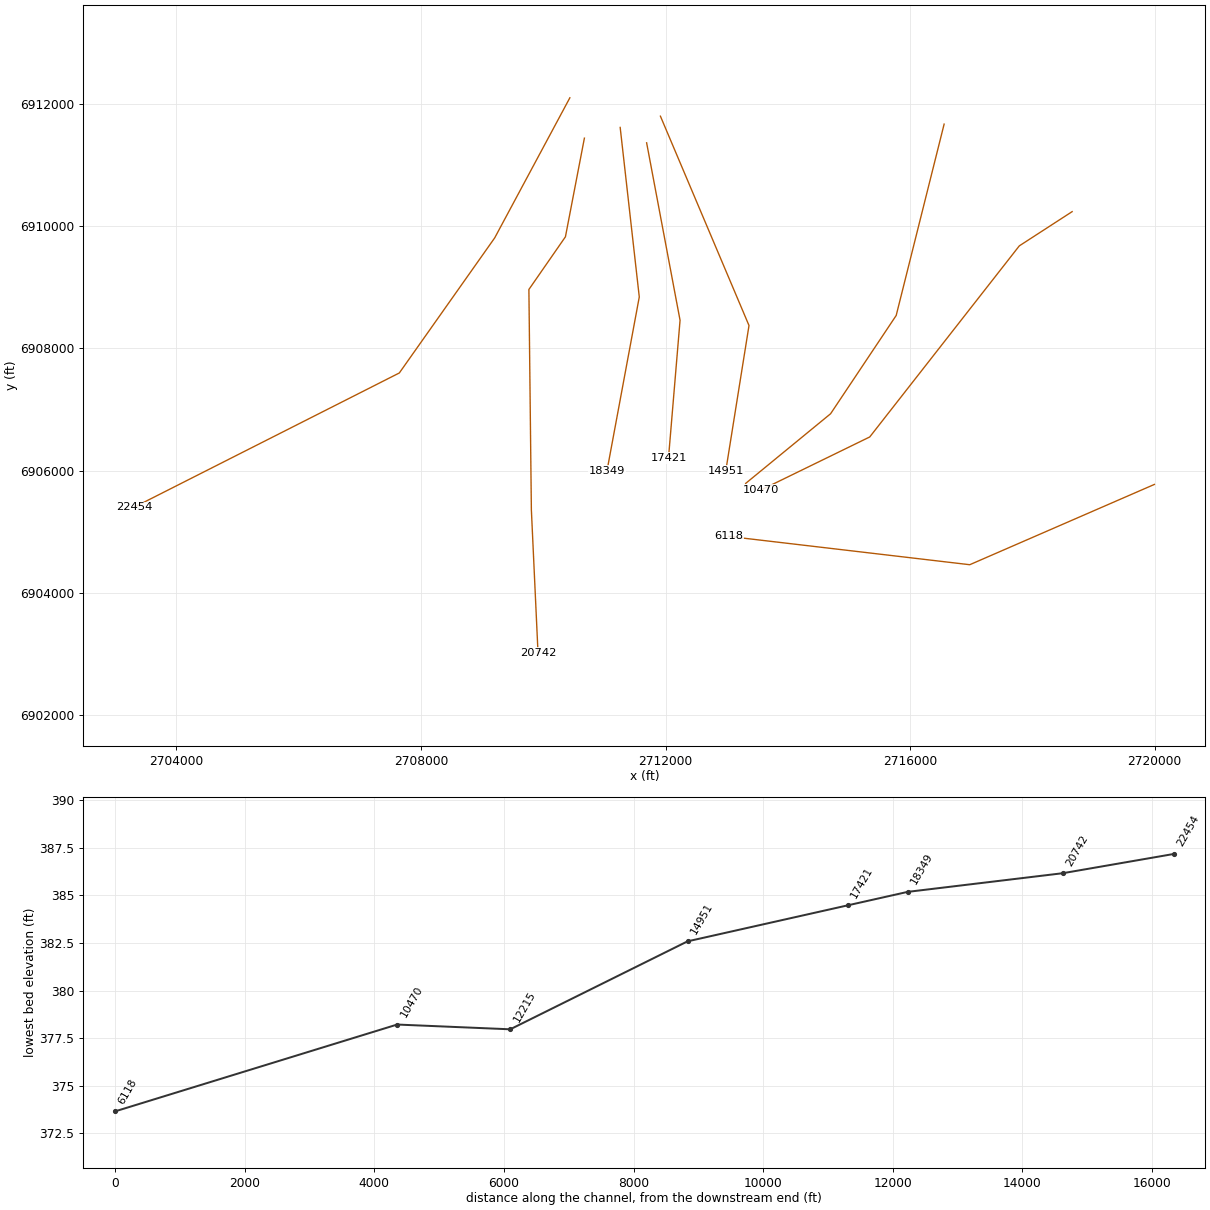
HEC-RAS study Rocky Cedar Creek.prj: Rocky Cedar Creek Base Level Engineering

--- Rocky Cedar Creek.g01 (geometry) --- (continued)

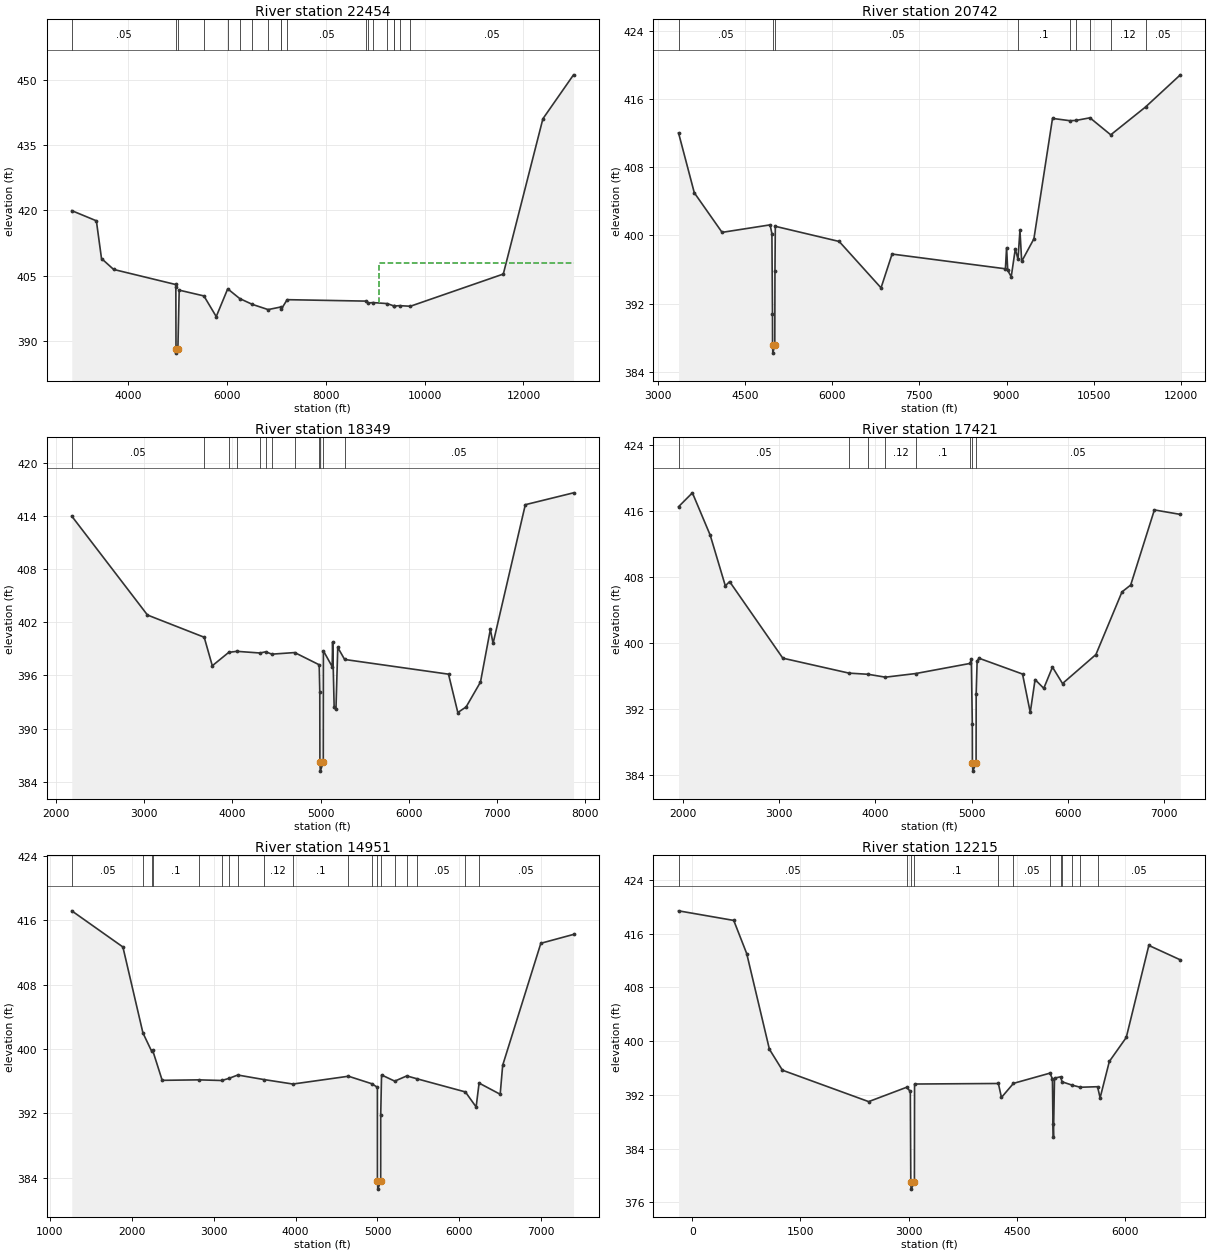
Type RM Length L Ch R = 1 ,22454   ,1712,1712,1712
BEGIN DESCRIPTION:
Mapping XS b864a1f5
END DESCRIPTION:
XS GIS Cut Line= 4
      2710435.17      6912098.14       2709205.5      6909806.39
       2707645.6      6907597.13      2703312.57      6905403.36
#Sta/Elev= 30
  2852.9  419.94  3351.4   417.6  3455.4  408.93  3700.8  406.42  4955.2  402.96
  4960.9  402.31  4964.1  388.18  4968.7  387.18  5002.3  388.18  5028.6  401.66
  5529.3  400.33  5779.1  395.58  6011.4  401.96  6255.1  399.72  6509.6  398.39
  6829.4  397.19  7084.3  397.78  7099.6  397.35  7215.5  399.47  8809.6  399.14
  8861.8  398.72  8953.7   398.8  9240.2  398.57  9382.5  398.01  9383.2  398.01
  9492.1  398.09  9711.4  397.96 11592.7  405.36 12394.7  441.06 13014.9  451.16
#Mann= 19 ,-1 , 0
  2852.9     .05       0  4964.1     .04       0  5002.3     .05       0
  5529.3      .1       0  6011.4     .12       0  6255.1      .1       0
  6509.6     .12       0  6829.4      .1       0  7084.3     .12       0
  7099.6      .1       0  7215.5     .05       0  8809.6     .12       0
  8861.8     .05       0  8953.7     .12       0  9240.2     .05       0
  9382.5     .12       0  9383.2     .05       0  9492.1     .12       0
  9711.4     .05       0
#XS Ineff= 2 , 0
       0                  9076.8       0     408
Permanent Ineff=
       F       F
Bank Sta=4964.1,5002.3
XS Rating Curve= 0 ,0
Exp/Cntr=0.3,0.1

Type RM Length L Ch R = 1 ,20742   ,2393,2393,2393
BEGIN DESCRIPTION:
Mapping XS 8a8a9dfa
END DESCRIPTION:
XS GIS Cut Line= 5
      2710672.95      6911438.27      2710362.67      6909824.32
      2709765.07      6908963.13      2709805.55      6905357.68
      2709913.97       6903024.1
#Sta/Elev= 30
  3356.5  412.04  3627.6  405.01  4105.3  400.36  4932.1  401.24  4962.7  400.21
  4972.8  390.77  4974.1  387.17  4978.7  386.17  5012.3  387.17  5015.3  395.81
  5021.4  401.07  6120.4  399.29  6840.4  393.84  7030.4  397.81  8980.5  396.08
  9000.5  398.56  9020.5  395.88  9080.6  395.15  9150.6  398.41  9196.5  397.21
  9230.6  400.59  9260.6  396.95  9470.6   399.6  9790.7  413.75 10089.1  413.48
 10193.2  413.51 10435.1  413.82 10792.6  411.82 11391.1  415.09   11990  418.87
#Mann= 9 ,-1 , 0
  3356.5     .05       0  4974.1     .04       0  5012.3     .05       0
  9196.5      .1       0 10089.1     .12       0 10193.2      .1       0
 10435.1     .05       0 10792.6     .12       0 11391.1     .05       0
Bank Sta=4974.1,5012.3
XS Rating Curve= 0 ,0
Exp/Cntr=0.3,0.1

Type RM Length L Ch R = 1 ,18349   ,928,928,928
BEGIN DESCRIPTION:
Mapping XS 41cf6339
END DESCRIPTION:
XS GIS Cut Line= 3
      2711258.16      6911613.37      2711570.66      6908839.89
      2711042.02      6905994.62
#Sta/Elev= 30
  2179.4  413.99  3037.2  402.82    3680  400.31  3771.8  397.09  3957.8   398.6
  4048.5  398.72  4313.2  398.53  4377.2  398.67  4445.8   398.4  4705.3  398.58
  4982.9   397.2  4989.6  394.14  4990.9  386.19  4995.5  385.19  5029.1  386.19
  5030.3  398.78  5129.9  396.99    5135  399.76  5152.4   392.4  5172.7  392.16
  5193.1  399.16  5271.2   397.8  6447.9  396.14  6553.5  391.81  6647.5  392.44
  6810.3  395.25  6922.2  401.21  6952.7  399.61  7318.2  415.28  7864.4  416.62
#Mann= 12 ,-1 , 0
  2179.4     .05       0    3680      .1       0  3957.8     .12       0
  4048.5      .1       0  4313.2     .12       0  4377.2      .1       0
  4445.8     .12       0  4705.3      .1       0  4982.9     .05       0
  4990.9    .035       0  5029.1     .05       0  5271.2     .05       0
Bank Sta=4990.9,5029.1
XS Rating Curve= 0 ,0
Exp/Cntr=0.3,0.1

Type RM Length L Ch R = 1 ,17421   ,2470,2470,2470
BEGIN DESCRIPTION:
Mapping XS a5ce12a7
END DESCRIPTION:
XS GIS Cut Line= 3
      2711690.74      6911362.34      2712237.62      6908458.67
      2712048.46      6906206.92
#Sta/Elev= 30
  1955.2  416.48    2099  418.16    2284  413.04  2441.4   406.9  2485.7  407.42
  3038.7  398.15  3726.7  396.34    3925   396.2  4104.8  395.85  4419.8  396.29
  4983.2  397.51  4997.9     398  5007.9   390.2  5008.9  385.48  5013.5  384.48
  5047.1  385.48  5048.1  393.84  5058.1  397.82  5078.2  398.14  5529.8  396.23
  5610.1  391.58  5660.2  395.56  5750.5   394.5  5840.9  397.07  5945.4  395.08
  6292.4  398.59  6563.4  406.17  6653.7     407  6899.9  416.09  7169.6  415.55
#Mann= 8 ,-1 , 0
  1955.2     .05       0  3726.7     .12       0    3925      .1       0
  4104.8     .12       0  4419.8      .1       0  4983.2     .05       0
  5008.9     .04       0  5047.1     .05       0
Bank Sta=5008.9,5047.1
XS Rating Curve= 0 ,0
Exp/Cntr=0.3,0.1

Type RM Length L Ch R = 1 ,14951   ,2736,2736,2736
BEGIN DESCRIPTION:
Mapping XS 242760a5
END DESCRIPTION:
XS GIS Cut Line= 3
      2711916.27      6911797.49      2713365.37      6908373.32
       2712985.6      6905997.05
#Sta/Elev= 30
  1268.6  417.15  1892.9  412.66  2137.3  401.99  2242.5  399.74  2254.9  399.87
  2372.4   396.1  2817.9  396.16    3100  396.08  3189.6  396.35  3294.8  396.76
  3611.8   396.2  3968.1  395.64  4646.2  396.61  4933.2  395.67  4999.3  395.23
  4999.6  383.59  5004.6  382.59  5039.4  383.59  5039.8  391.81  5049.9  396.77
  5210.7     396  5357.9  396.65  5486.9  396.28  6073.4  394.66  6204.4  392.79
  6240.4  395.76    6498  394.37  6528.4  397.97  6994.3  413.12  7393.2  414.22
#Mann= 19 ,-1 , 0
  1268.6     .05       0  2137.3      .1       0  2242.5     .12       0
  2254.9      .1       0  2817.9     .12       0    3100      .1       0
  3189.6     .12       0  3294.8     .05       0  3611.8     .12       0
  3968.1      .1       0  4646.2     .12       0  4933.2      .1       0
  4999.6     .07       0  5039.4      .1       0  5210.7     .12       0
  5357.9      .1       0  5486.9     .05       0  6073.4     .12       0
  6240.4     .05       0
Bank Sta=4999.6,5039.4
XS Rating Curve= 0 ,0
Exp/Cntr=0.3,0.1

Type RM Length L Ch R = 1 ,12215   ,1745,1745,1745
BEGIN DESCRIPTION:
Mapping XS e8635d56
END DESCRIPTION:
XS GIS Cut Line= 4
      2716557.05      6911667.55      2715772.96      6908537.44
        2714700.      6906930.17      2713311.13      6905790.87
#Sta/Elev= 30
  -189.7  419.41   575.4  417.98   755.2  413.04  1069.7   398.8    1250  395.68
  2445.8     391  2970.3  393.13  3023.1  392.53  3029.8  378.97  3033.8  377.97
  3079.8  378.97  3081.8  393.62  4243.8   393.7  4286.4  391.62  4453.1  393.72
  4958.7  395.24  4993.1  394.39  5000.7  387.62  5007.4  385.66  5021.8   394.5
    5105  394.69  5127.5  393.95  5263.9  393.46  5378.7  393.14  5618.5  393.22
    5654  391.56  5781.8  396.98  6016.4  400.55  6329.3  414.26    6766  412.11
#Mann= 12 ,-1 , 0
  -189.7     .05       0  2970.3      .1       0  3029.8     .07       0
  3079.8      .1       0  4243.8     .12       0  4453.1     .05       0
  4958.7      .1       0    5105     .12       0  5127.5     .05       0
  5263.9      .1       0  5378.7     .12       0  5618.5     .05       0
Bank Sta=3029.8,3079.8
XS Rating Curve= 0 ,0
Exp/Cntr=0.3,0.1

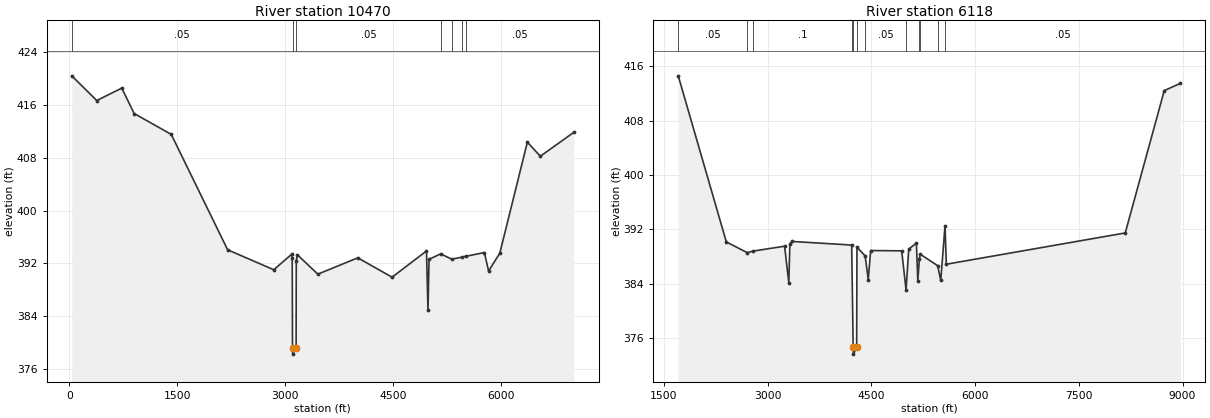
Type RM Length L Ch R = 1 ,10470   ,4352,4352,4352
BEGIN DESCRIPTION:
Mapping XS 87acf1a0
END DESCRIPTION:
XS GIS Cut Line= 4
      2718650.96      6910235.98      2717786.55      6909675.87
      2715340.19       6906550.4      2713560.85      6905682.43
#Sta/Elev= 30
    34.2  420.44   381.6  416.69   729.1  418.58   901.2  414.72  1416.8  411.56
  2200.6  394.05  2841.8  391.02  3090.5  393.37  3098.6  392.79  3102.5  379.22
  3106.5  378.22  3152.5  379.22  3154.7  392.31  3169.1   393.3  3454.8  390.35
    4010  392.83  4486.5  389.89  4964.8  393.87  4985.7  384.84  5000.1   392.6
  5160.7  393.43  5316.4  392.63  5459.3  392.93  5516.2  393.07  5769.9  393.63
  5827.9  390.83  5983.8  393.53  6366.9  410.38  6547.1  408.24    7013  411.87
#Mann= 7 ,-1 , 0
    34.2     .05       0  3102.5     .04       0  3152.5     .05       0
  5160.7     .12       0  5316.4     .05       0  5459.3     .12       0
  5516.2     .05       0
Bank Sta=3102.5,3152.5
XS Rating Curve= 0 ,0
Exp/Cntr=0.3,0.1

Type RM Length L Ch R = 1 ,6118    ,0,0,0
BEGIN DESCRIPTION:
Rocky Cedar Creek 3.0
END DESCRIPTION:
XS GIS Cut Line= 3
      2719996.72      6905774.25      2716976.01      6904460.65
      2713034.88      6904923.57
#Sta/Elev= 30
    1706  414.61  2401.5  390.17  2704.6  388.59  2788.6  388.82  3244.3  389.54
  3305.4  384.19  3320.7  389.91  3352.3  390.24  4214.7  389.71  4236.6  374.66
  4240.6  373.66  4286.6  374.66  4291.2   389.4  4409.6  388.11  4454.6  384.63
    4489   388.9  4938.2  388.86  5001.3  383.11  5040.3  389.13    5151  389.98
  5171.2  384.49  5194.3  387.65  5205.1  388.37  5458.1  386.68  5503.4   384.5
  5564.8  392.53    5584  386.89  8171.6  391.49  8736.2  412.44  8968.2  413.49
#Mann= 12 ,-1 , 0
    1706     .05       0  2704.6     .12       0  2788.6      .1       0
  4214.7     .12       0  4236.6     .04       0  4286.6     .12       0
  4409.6     .05       0  5001.3     .12       0  5194.3     .05       0
  5205.1     .12       0  5458.1      .1       0  5564.8     .05       0
Bank Sta=4236.6,4286.6
XS Rating Curve= 0 ,0
Exp/Cntr=0.3,0.1

Chan Stop Cuts=-1
Use User Specified Reach Order=0
Composite Channel Slope=5