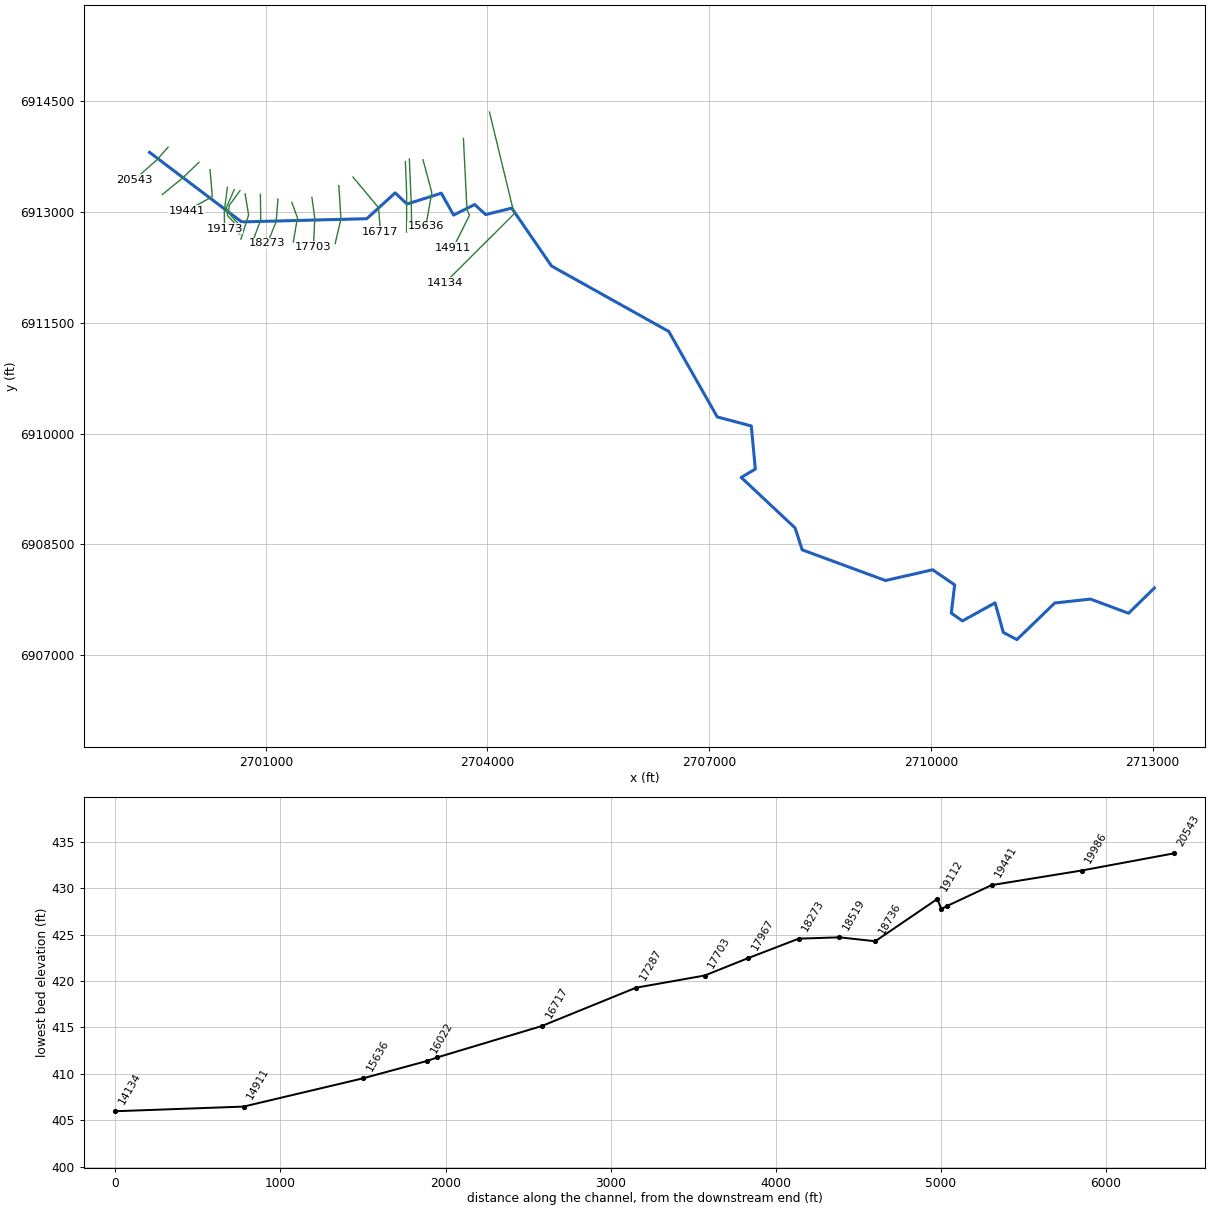
--- Rocky Cedar T1.prj (project) ---

Proj Title=Rocky Cedar T1 Base Level Engineering
Current Plan=p01
Default Exp/Contr=0.3,0.1
English Units
Geom File=g01
Flow File=f01
Plan File=p01
BEGIN DESCRIPTION:
Rocky Cedar T1
END DESCRIPTION:

--- Rocky Cedar T1.p01 (plan) ---

Plan Title=Multiple Run
Short Identifier=Multiple
Geom File=g01
Flow File=f01
Subcritical Flow
K Sum by GR= 0
Std Step Tol= 0.01
Critical Tol= 0.01
Num of Std Step Trials= 20
Max Error Tol= 0.3
Flow Tol Ratio= 0.001
Split Flow NTrial= 30
Split Flow Tol= 0.02
Split Flow Ratio= 0.02
Log Output Level= 0
Friction Slope Method= 1
Unsteady Friction Slope Method= 2
Unsteady Bridges Friction Slope Method= 1
Parabolic Critical Depth
Global Vel Dist=  1 , 1 , 1
Global Log Level= 0
CheckData=True
Encroach Param= -1, 0, 0, 0
BEGIN DESCRIPTION:
Multiple Run
END DESCRIPTION:

--- Rocky Cedar T1.f01 (steady flow) ---

Flow Title=Multiple
Number of Profiles=7
Profile Names=10-year,25-year,50-year,1pct_min,100-year,1pct_plu,500-year
River Rch & RM= Rocky Cedar T1,Reach-1,20543
     477     633     758     451     900    1795    1266
River Rch & RM= Rocky Cedar T1,Reach-1,19986
     855    1173    1437     873    1742    3475    2557
River Rch & RM= Rocky Cedar T1,Reach-1,16085
     908    1237    1507     909    1814    3619    2626
Boundary for River Rch & Prof#=Rocky Cedar T1,Reach-1,1
Up Type=0
Dn Type=3
Dn Slope=0.005
Boundary for River Rch & Prof#=Rocky Cedar T1,Reach-1,2
Up Type=0
Dn Type=3
Dn Slope=0.005
Boundary for River Rch & Prof#=Rocky Cedar T1,Reach-1,3
Up Type=0
Dn Type=3
Dn Slope=0.005
Boundary for River Rch & Prof#=Rocky Cedar T1,Reach-1,4
Up Type=0
Dn Type=3
Dn Slope=0.005
Boundary for River Rch & Prof#=Rocky Cedar T1,Reach-1,5
Up Type=0
Dn Type=3
Dn Slope=0.005
Boundary for River Rch & Prof#=Rocky Cedar T1,Reach-1,6
Up Type=0
Dn Type=3
Dn Slope=0.005
Boundary for River Rch & Prof#=Rocky Cedar T1,Reach-1,7
Up Type=0
Dn Type=3
Dn Slope=0.005

--- Rocky Cedar T1.g01 (geometry) ---

Geom Title=Existing Conditions

River Reach=Rocky Cedar T1,Reach-1
Reach XY= 30
      2699426.00      6913811.00      2700672.42      6912868.50
      2702365.57      6912912.05      2702750.92      6913261.33
      2702910.69      6913110.47      2703374.75      6913257.55
      2703541.02      6912961.32      2703825.99      6913103.93
      2703976.00      6912968.08      2704328.29      6913055.16
      2704866.21      6912271.52      2706453.34      6911385.02
      2707109.24      6910227.43      2707570.38      6910105.44
      2707624.95      6909521.11      2707433.84      6909407.79
      2708162.63      6908724.32      2708259.20      6908427.42
      2709386.44      6908012.04      2710024.50      6908157.39
      2710322.67      6907952.83      2710276.98      6907571.28
      2710427.55      6907464.75      2710869.92      6907709.44
      2710981.45      6907308.53      2711165.48      6907211.99
      2711677.25      6907707.55      2712160.78      6907760.48
      2712675.99      6907568.53      2713026.00      6907911.00

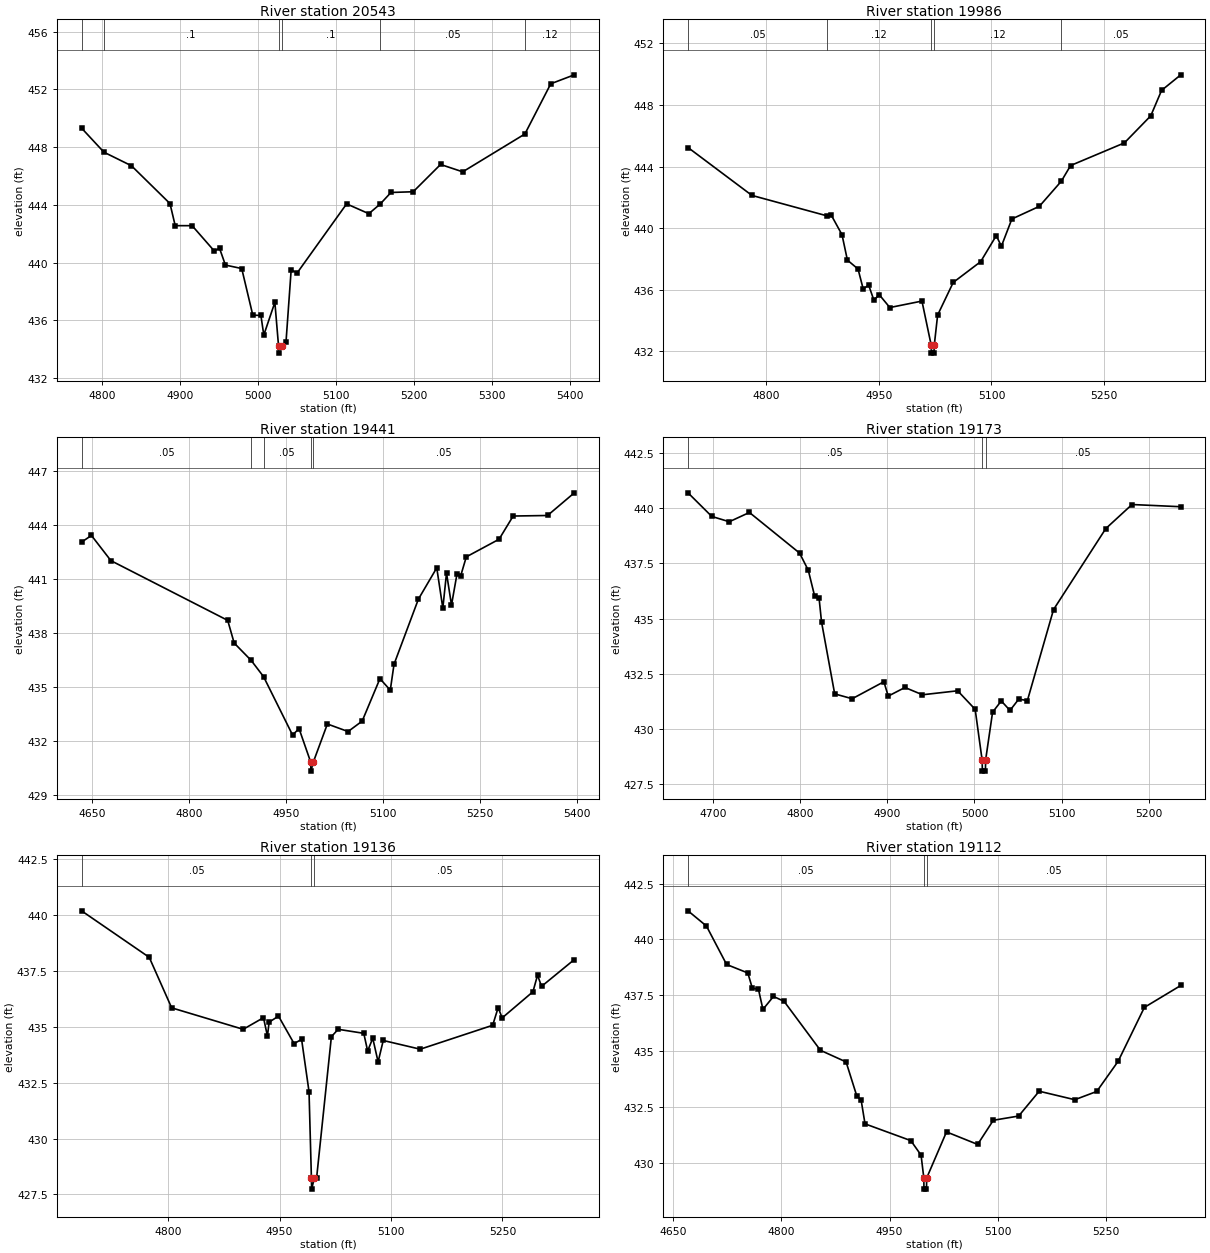
Type RM Length L Ch R = 1,20543,557,557,557
BEGIN DESCRIPTION:
Rocky Cedar T1 15.0
END DESCRIPTION:
XS GIS Cut Line= 3
      2699676.79      6913880.16      2699526.56      6913710.39
      2699223.20      6913441.76
#Sta/Elev= 30
  4773.3  449.32  4802.0  447.65  4837.3  446.71  4886.7  444.09  4893.4  442.56
  4915.1  442.56  4943.6  440.80  4950.2  441.00  4957.8  439.83  4978.7  439.59
  4992.9  436.36  5003.3  436.34  5007.0  434.98  5021.2  437.25  5025.9  434.23
  5026.2  433.73  5029.9  434.23  5035.5  434.51  5042.1  439.50  5049.7  439.28
  5113.2  444.07  5141.7  443.39  5156.3  444.06  5170.1  444.86  5198.6  444.91
  5233.7  446.80  5262.1  446.29  5341.8  448.91  5375.0  452.39  5405.2  453.01
#Mann=6,-1,0
  4773.3    0.12       0  4802.0     0.1       0  5025.9    0.07       0
  5029.9     0.1       0  5156.3    0.05       0  5341.8    0.12       0
Bank Sta=5025.9,5029.9
Exp/Cntr=0.3,0.1

Type RM Length L Ch R = 1,19986,545,545,545
BEGIN DESCRIPTION:
Rocky Cedar T1 14.0
END DESCRIPTION:
XS GIS Cut Line= 3
      2700093.46      6913673.99      2699873.65      6913463.12
      2699600.88      6913240.00
#Sta/Elev= 30
  4695.4  445.24  4780.6  442.13  4880.2  440.81  4886.5  440.84  4900.7  439.58
  4907.9  437.93  4922.1  437.35  4929.0  436.05  4936.2  436.31  4943.2  435.33
  4950.4  435.68  4964.5  434.85  5007.3  435.27  5019.7  432.39  5019.9  431.89
  5023.4  431.89  5023.7  432.39  5028.2  434.36  5049.0  436.48  5085.6  437.83
  5106.4  439.52  5113.2  438.83  5127.2  440.60  5163.8  441.42  5193.1  443.05
  5205.5  444.07  5277.2  445.54  5312.4  447.30  5326.8  448.95  5352.4  449.96
#Mann=5,-1,0
  4695.4    0.05       0  4880.2    0.12       0  5019.7    0.07       0
  5023.7    0.12       0  5193.1    0.05       0
Bank Sta=5019.7,5023.7
Exp/Cntr=0.3,0.1

Type RM Length L Ch R = 1,19441,268,268,268
BEGIN DESCRIPTION:
Rocky Cedar T1 13.0
END DESCRIPTION:
XS GIS Cut Line= 3
      2700245.37      6913576.29      2700276.00      6913211.00
      2699929.80      6913019.31
#Sta/Elev= 30
  4634.1  443.05  4649.4  443.42  4679.5  442.02  4860.2  438.70  4870.2  437.44
  4896.6  436.47  4915.7  435.57  4960.5  432.33  4970.6  432.68  4988.6  430.82
  4988.9  430.32  4992.6  430.82  5014.4  432.94  5046.4  432.52  5068.2  433.10
  5095.7  435.46  5111.7  434.82  5117.5  436.26  5155.2  439.88  5183.6  441.62
  5193.0  439.38  5198.7  441.33  5206.4  439.55  5214.8  441.26  5220.5  441.16
  5229.3  442.23  5280.0  443.21  5301.8  444.50  5355.0  444.53  5396.4  445.79
#Mann=5,-1,0
  4634.1    0.05       0  4896.6    0.12       0  4915.7    0.05       0
  4988.6    0.04       0  4992.6    0.05       0
Bank Sta=4988.6,4992.6
Exp/Cntr=0.3,0.1

Type RM Length L Ch R = 1,19173,37,37,37
BEGIN DESCRIPTION:
Mapping XS 2509c25f
END DESCRIPTION:
XS GIS Cut Line= 4
      2700479.62      6913338.04      2700453.58      6913133.22
      2700437.96      6913016.90      2700441.41      6912774.96
#Sta/Elev= 30
  4671.1  440.70  4698.4  439.63  4718.5  439.39  4741.6  439.81  4799.2  437.97
  4809.2  437.19  4816.5  436.02  4821.6  435.92  4824.4  434.85  4839.5  431.59
  4859.6  431.37  4896.0  432.14  4901.0  431.49  4920.2  431.88  4940.3  431.55
  4980.7  431.73  5000.8  430.89  5008.8  428.59  5009.1  428.09  5012.6  428.09
  5012.8  428.59  5020.8  430.76  5030.8  431.27  5040.8  430.84  5050.8  431.35
  5060.8  431.29  5090.8  435.41  5150.8  439.08  5180.9  440.17  5236.9  440.07
#Mann=3,-1,0
  4671.1    0.05       0  5008.8    0.04       0  5012.8    0.05       0
Bank Sta=5008.8,5012.8
Exp/Cntr=0.3,0.1

Type RM Length L Ch R = 1,19136,24,24,24
BEGIN DESCRIPTION:
Mapping XS 7840d2d6
END DESCRIPTION:
XS GIS Cut Line= 6
      2700572.51      6913304.67      2700469.64      6913072.89
      2700477.45      6912977.83      2700483.96      6912953.09
      2700563.39      6912868.46      2700629.79      6912709.61
#Sta/Elev= 30
  4683.4  440.19  4774.5  438.11  4804.7  435.85  4901.0  434.89  4928.3  435.41
  4933.6  434.59  4935.9  435.21  4948.5  435.48  4969.5  434.25  4979.6  434.44
  4989.6  432.10  4992.8  428.24  4993.1  427.74  4996.8  428.24  4999.8  428.24
  5019.7  434.56  5028.8  434.89  5063.3  434.71  5068.5  433.92  5075.4  434.49
  5082.6  433.43  5089.5  434.39  5139.3  434.00  5236.8  435.07  5244.2  435.86
  5249.6  435.40  5291.0  436.57  5297.2  437.31  5302.6  436.81  5346.7  438.01
#Mann=3,-1,0
  4683.4    0.05       0  4992.8    0.04       0  4996.8    0.05       0
Bank Sta=4992.8,4996.8
Exp/Cntr=0.3,0.1

Type RM Length L Ch R = 1,19112,376,376,376
BEGIN DESCRIPTION:
Mapping XS 586e1e79
END DESCRIPTION:
XS GIS Cut Line= 6
      2700650.65      6913291.66      2700504.80      6913091.12
      2700496.98      6913016.90      2700517.82      6912966.12
      2700628.49      6912842.42      2700647.92      6912705.16
#Sta/Elev= 30
  4671.0  441.28  4696.5  440.60  4724.4  438.88  4753.8  438.50  4760.0  437.82
  4768.5  437.77  4774.7  436.87  4789.3  437.45  4804.0  437.23  4854.3  435.04
  4889.8  434.52  4904.5  433.01  4910.7  432.80  4916.0  431.75  4979.4  431.00
  4993.6  430.35  4997.4  429.33  4997.6  428.83  5001.1  428.83  5001.4  429.33
  5028.8  431.39  5071.9  430.83  5093.6  431.91  5128.7  432.10  5157.1  433.21
  5206.4  432.83  5236.8  433.20  5266.4  434.55  5302.7  436.96  5353.1  437.94
#Mann=3,-1,0
  4671.0    0.05       0  4997.4    0.04       0  5001.4    0.05       0
Bank Sta=4997.4,5001.4
Exp/Cntr=0.3,0.1

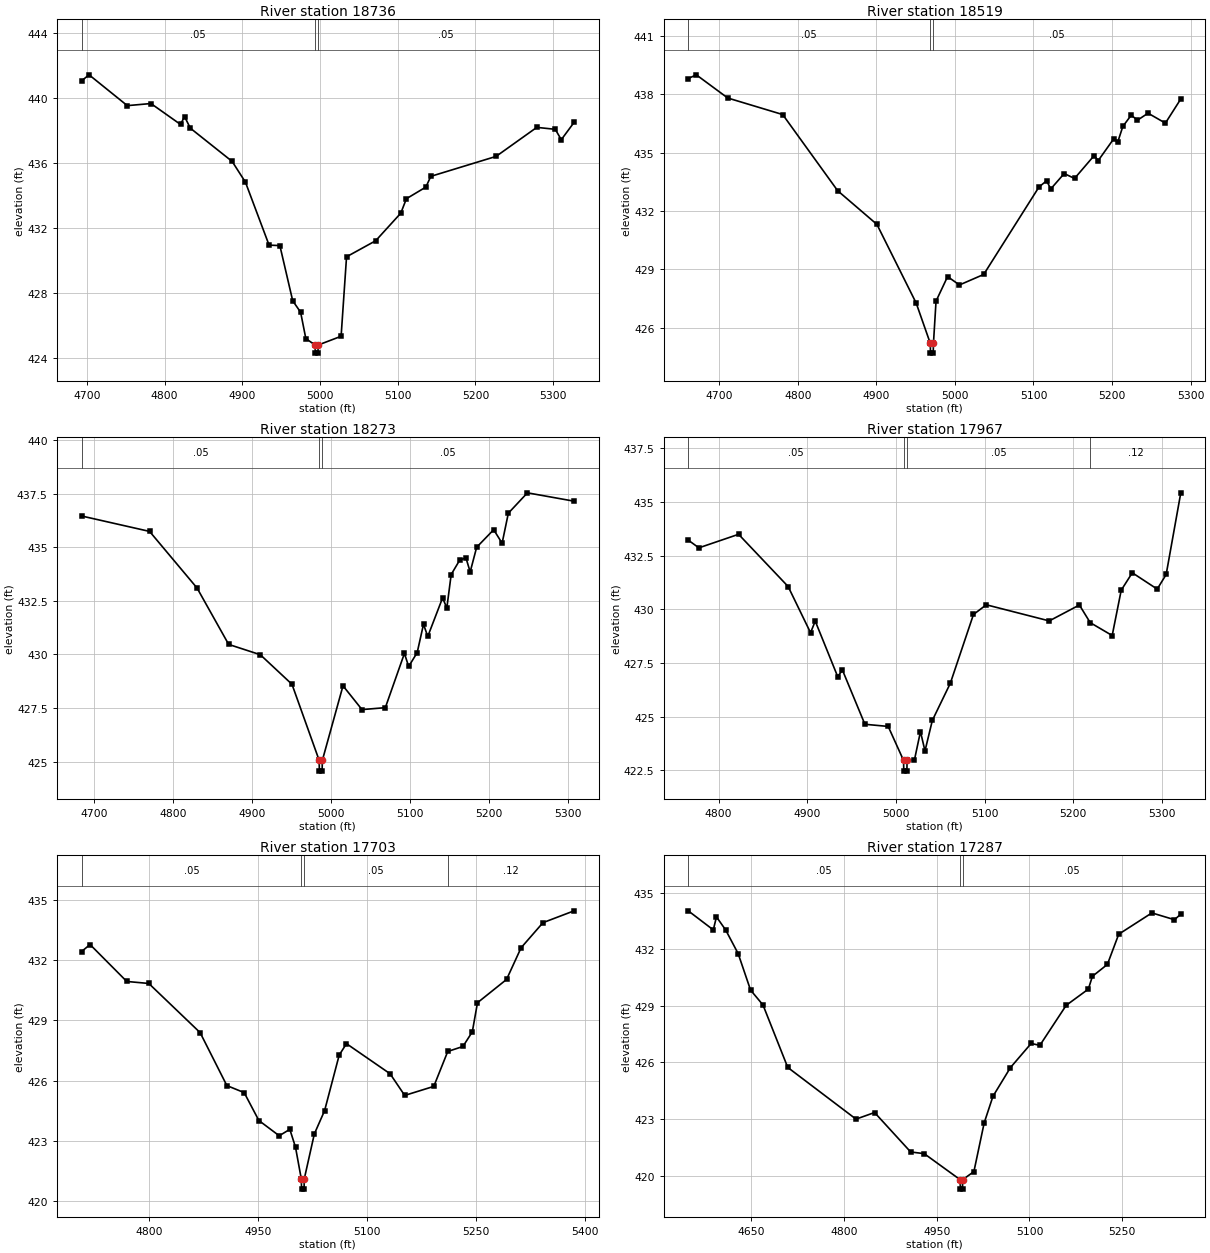
Type RM Length L Ch R = 1,18736,217,217,217
BEGIN DESCRIPTION:
Mapping XS b9ee1965
END DESCRIPTION:
XS GIS Cut Line= 3
      2700720.01      6913249.16      2700766.88      6912962.69
      2700662.94      6912635.27
#Sta/Elev= 30
  4693.1  441.07  4702.8  441.44  4752.0  439.54  4782.4  439.67  4820.5  438.38
  4825.6  438.87  4833.1  438.15  4886.9  436.10  4904.0  434.82  4934.4  430.94
  4948.3  430.91  4964.8  427.51  4975.0  426.80  4981.7  425.18  4993.6  424.78
  4993.9  424.28  4997.4  424.28  4997.6  424.78  5027.1  425.32  5034.1  430.22
  5071.6  431.21  5103.9  432.91  5111.1  433.80  5136.2  434.52  5142.5  435.18
  5226.5  436.41  5278.9  438.20  5302.7  438.08  5310.4  437.44  5326.9  438.51
#Mann=3,-1,0
  4693.1    0.05       0  4993.6    0.04       0  4997.6    0.05       0
Bank Sta=4993.6,4997.6
Exp/Cntr=0.3,0.1

Type RM Length L Ch R = 1,18519,246,246,246
BEGIN DESCRIPTION:
Mapping XS bbe9ac59
END DESCRIPTION:
XS GIS Cut Line= 3
      2700926.24      6913241.26      2700931.45      6912895.80
      2700832.50      6912631.94
#Sta/Elev= 30
  4660.3  438.80  4670.6  438.99  4710.6  437.80  4780.6  436.95  4850.6  433.04
  4900.6  431.31  4950.6  427.27  4968.6  425.20  4968.8  424.70  4972.3  424.70
  4972.6  425.20  4975.9  427.37  4990.6  428.63  5005.7  428.20  5036.6  428.74
  5107.0  433.23  5116.7  433.55  5122.0  433.13  5139.1  433.92  5152.3  433.67
  5177.2  434.84  5182.5  434.59  5202.1  435.70  5207.5  435.56  5213.8  436.34
  5224.5  436.92  5232.4  436.66  5245.9  437.02  5268.0  436.51  5287.6  437.75
#Mann=3,-1,0
  4660.3    0.05       0  4968.6    0.04       0  4972.6    0.05       0
Bank Sta=4968.6,4972.6
Exp/Cntr=0.3,0.1

Type RM Length L Ch R = 1,18273,306,306,306
BEGIN DESCRIPTION:
Mapping XS bb0a5142
END DESCRIPTION:
XS GIS Cut Line= 3
      2701163.91      6913177.04      2701140.04      6912873.23
      2701020.84      6912576.31
#Sta/Elev= 30
  4683.6  436.46  4769.9  435.74  4830.1  433.10  4870.2  430.47  4910.3  429.99
  4950.5  428.61  4985.0  425.06  4985.2  424.56  4988.7  424.56  4989.0  425.06
  5015.2  428.54  5039.3  427.43  5068.9  427.52  5093.1  430.05  5098.5  429.44
  5109.3  430.09  5117.3  431.41  5122.7  430.84  5141.5  432.64  5146.9  432.17
  5152.4  433.73  5163.2  434.40  5171.1  434.51  5176.5  433.85  5184.7  435.00
  5206.3  435.82  5217.0  435.19  5224.9  436.59  5249.1  437.54  5308.3  437.15
#Mann=3,-1,0
  4683.6    0.05       0  4985.0    0.04       0  4989.0    0.05       0
Bank Sta=4985,4989
Exp/Cntr=0.3,0.1

Type RM Length L Ch R = 1,17967,264,264,264
BEGIN DESCRIPTION:
Mapping XS 77c09c22
END DESCRIPTION:
XS GIS Cut Line= 3
      2701352.72      6913132.32      2701428.23      6912924.01
      2701371.20      6912594.78
#Sta/Elev= 30
  4765.7  433.22  4777.7  432.86  4822.5  433.49  4878.4  431.06  4903.7  428.91
  4909.0  429.45  4934.3  426.87  4939.7  427.17  4965.0  424.65  4991.3  424.55
  5008.6  422.97  5008.9  422.47  5012.4  422.47  5012.6  422.97  5020.8  422.97
  5027.7  424.31  5032.8  423.41  5041.1  424.83  5061.4  426.56  5087.5  429.76
  5102.0  430.21  5173.0  429.46  5207.0  430.20  5219.2  429.38  5244.0  428.78
  5254.2  430.89  5266.7  431.70  5294.8  430.94  5304.9  431.62  5321.4  435.42
#Mann=4,-1,0
  4765.7    0.05       0  5008.6    0.04       0  5012.6    0.05       0
  5219.2    0.12       0
Bank Sta=5008.6,5012.6
Exp/Cntr=0.3,0.1

Type RM Length L Ch R = 1,17703,416,416,416
BEGIN DESCRIPTION:
Mapping XS 8376504c
END DESCRIPTION:
XS GIS Cut Line= 3
      2701623.55      6913202.62      2701662.61      6912918.81
      2701644.38      6912528.22
#Sta/Elev= 30
  4707.0  432.43  4718.7  432.78  4769.2  430.94  4799.5  430.84  4870.1  428.39
  4906.9  425.75  4930.7  425.40  4950.9  424.01  4978.9  423.25  4993.5  423.57
  5001.3  422.68  5009.3  421.09  5009.6  420.59  5013.1  420.59  5013.3  421.09
  5027.2  423.34  5041.3  424.50  5061.4  427.27  5071.4  427.84  5131.4  426.34
  5151.5  425.26  5191.5  425.71  5210.7  427.45  5231.6  427.70  5244.5  428.43
  5251.6  429.88  5291.6  431.04  5311.6  432.62  5341.7  433.87  5384.5  434.46
#Mann=4,-1,0
  4707.0    0.05       0  5009.3    0.04       0  5013.3    0.05       0
  5210.7    0.12       0
Bank Sta=5009.3,5013.3
Exp/Cntr=0.3,0.1

Type RM Length L Ch R = 1,17287,570,570,570
BEGIN DESCRIPTION:
Mapping XS 87cbfa09
END DESCRIPTION:
XS GIS Cut Line= 3
      2701988.13      6913361.53      2702016.78      6912908.39
      2701938.77      6912575.55
#Sta/Elev= 30
  4548.6  434.03  4589.1  433.02  4594.2  433.71  4609.2  433.01  4629.3  431.76
  4649.3  429.83  4669.4  429.04  4709.4  425.73  4819.7  422.99  4849.7  423.34
  4908.0  421.25  4929.9  421.16  4988.0  419.78  4988.3  419.28  4991.8  419.28
  4992.0  419.78  5010.2  420.21  5026.8  422.79  5041.0  424.20  5069.2  425.72
  5102.7  427.00  5116.8  426.90  5159.3  429.02  5195.1  429.88  5201.7  430.56
  5225.9  431.19  5244.2  432.79  5297.8  433.92  5334.2  433.56  5344.5  433.85
#Mann=3,-1,0
  4548.6    0.05       0  4988.0    0.04       0  4992.0    0.05       0
Bank Sta=4988,4992
Exp/Cntr=0.3,0.1

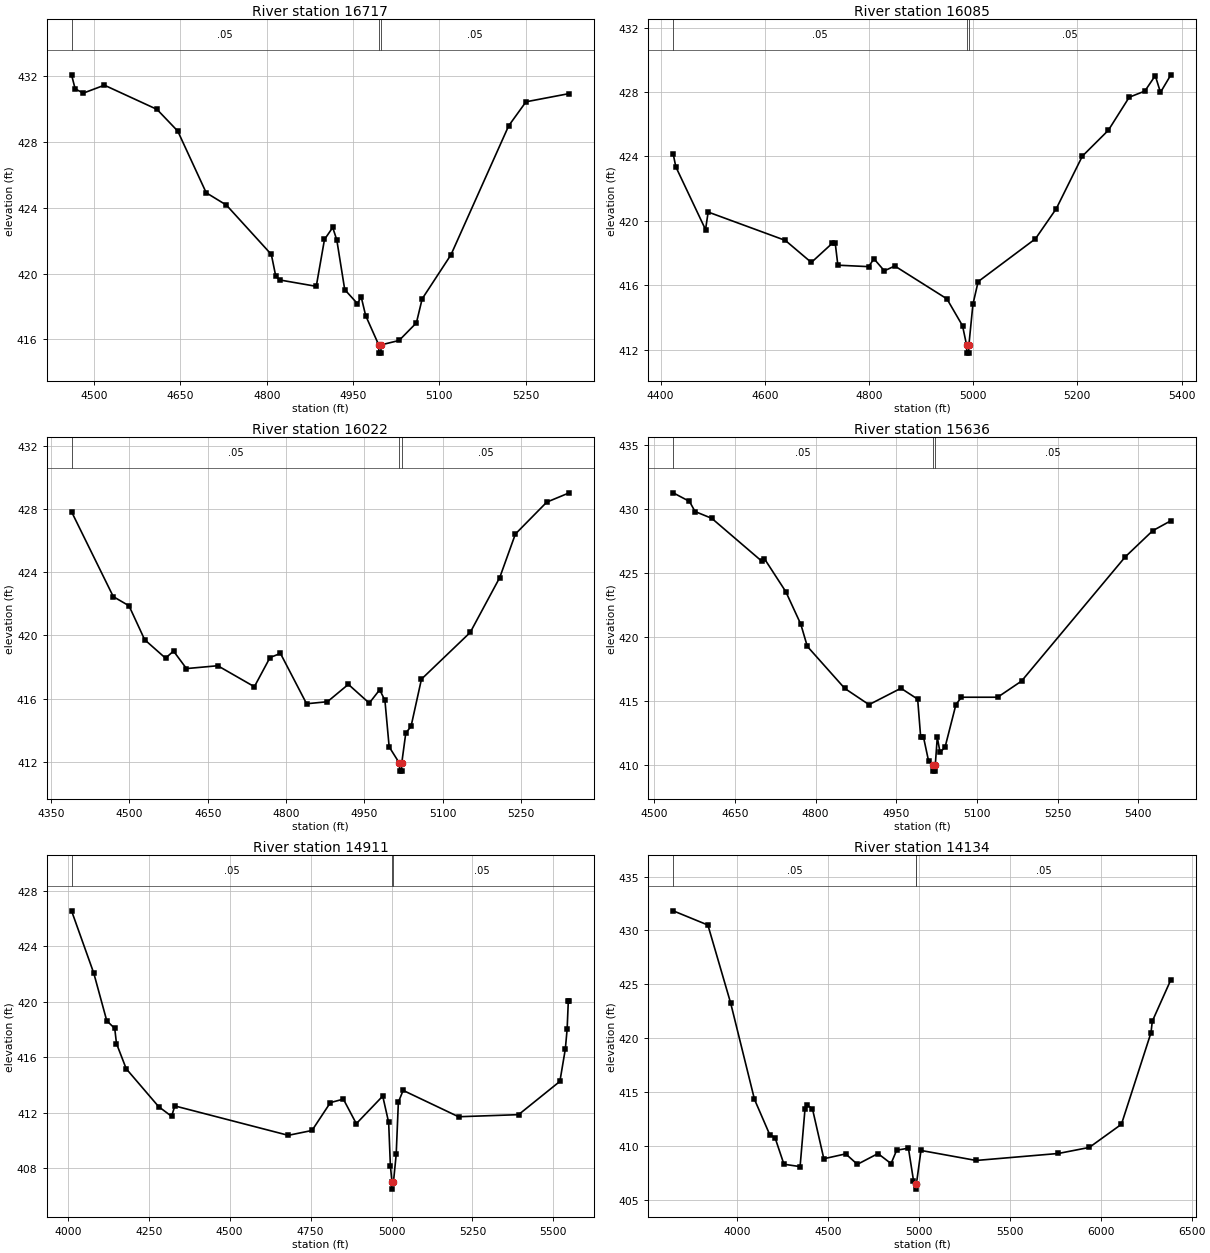
Type RM Length L Ch R = 1,16717,632,632,632
BEGIN DESCRIPTION:
Rocky Cedar T1 7.0
END DESCRIPTION:
XS GIS Cut Line= 3
      2702180.40      6913474.99      2702526.00      6913061.00
      2702551.00      6912736.05
#Sta/Elev= 30
  4460.7  432.08  4467.0  431.22  4481.3  430.97  4517.8  431.45  4609.2  429.98
  4645.3  428.66  4694.8  424.91  4729.9  424.16  4808.0  421.16  4815.8  419.82
  4822.3  419.61  4886.1  419.22  4900.4  422.07  4914.7  422.80  4921.8  422.04
  4935.6  419.02  4957.7  418.17  4964.2  418.58  4972.0  417.44  4994.7  415.66
  4995.0  415.16  4998.5  415.16  4998.7  415.66  5030.1  415.93  5060.2  417.00
  5070.2  418.46  5120.3  421.14  5220.6  428.98  5250.7  430.44  5325.9  430.94
#Mann=3,-1,0
  4460.7    0.05       0  4994.7    0.04       0  4998.7    0.05       0
Bank Sta=4994.7,4998.7
Exp/Cntr=0.3,0.1

Type RM Length L Ch R = 1,16085,63,63,63
BEGIN DESCRIPTION:
Rocky Cedar T1 6.0
END DESCRIPTION:
XS GIS Cut Line= 3
      2702888.41      6913686.01      2702906.03      6913249.86
      2702905.01      6912730.97
#Sta/Elev= 30
  4424.2  424.16  4429.2  423.36  4486.3  419.46  4491.3  420.55  4639.4  418.79
  4689.4  417.42  4729.5  418.61  4735.3  418.60  4740.3  417.25  4799.5  417.16
  4809.5  417.65  4829.5  416.90  4849.6  417.20  4949.6  415.16  4979.6  413.49
  4987.4  412.29  4987.8  411.79  4991.4  411.79  4991.8  412.29  4999.6  414.83
  5009.6  416.23  5119.6  418.89  5159.6  420.76  5209.6  424.02  5259.6  425.63
  5299.6  427.68  5329.6  428.06  5349.6  429.02  5359.6  427.98  5379.6  429.07
#Mann=3,-1,0
  4424.2    0.05       0  4987.4    0.04       0  4991.8    0.05       0
Bank Sta=4987.4,4991.8
Exp/Cntr=0.3,0.1

Type RM Length L Ch R = 1,16022,386,386,386
BEGIN DESCRIPTION:
Mapping XS 09eb841d
END DESCRIPTION:
XS GIS Cut Line= 3
      2702942.67      6913720.96      2702968.71      6913109.87
      2702973.92      6912767.86
#Sta/Elev= 30
  4389.0  427.84  4469.0  422.46  4499.1  421.88  4529.1  419.73  4569.1  418.56
  4584.4  419.01  4609.2  417.90  4669.2  418.08  4739.3  416.75  4769.3  418.60
  4789.3  418.86  4839.4  415.67  4879.4  415.80  4919.4  416.90  4959.5  415.71
  4979.5  416.56  4989.5  415.88  4997.6  412.94  5017.3  411.90  5017.7  411.40
  5021.3  411.40  5021.7  411.90  5029.5  413.82  5039.5  414.23  5059.5  417.23
  5152.9  420.19  5209.5  423.67  5239.5  426.43  5299.6  428.45  5342.7  429.04
#Mann=3,-1,0
  4389.0    0.05       0  5017.3    0.03       0  5021.7    0.05       0
Bank Sta=5017.3,5021.7
Exp/Cntr=0.3,0.1

Type RM Length L Ch R = 1,15636,725,725,725
BEGIN DESCRIPTION:
Mapping XS 37d74b12
END DESCRIPTION:
XS GIS Cut Line= 3
      2703127.23      6913710.26      2703246.59      6913265.36
      2703164.13      6912807.46
#Sta/Elev= 30
  4535.0  431.27  4565.3  430.60  4575.6  429.81  4606.7  429.28  4699.3  425.95
  4704.5  426.14  4744.5  423.55  4772.4  421.01  4784.5  419.28  4854.1  416.00
  4899.3  414.73  4958.7  416.01  4989.8  415.16  4995.3  412.24  5000.4  412.24
  5010.2  410.31  5018.2  410.04  5018.6  409.54  5022.2  409.54  5022.6  410.04
  5026.3  412.18  5031.4  411.02  5040.7  411.40  5061.0  414.74  5071.2  415.31
  5138.6  415.31  5183.0  416.57  5376.0  426.27  5427.0  428.31  5460.9  429.09
#Mann=3,-1,0
  4535.0    0.05       0  5018.2    0.04       0  5022.6    0.05       0
Bank Sta=5018.2,5022.6
Exp/Cntr=0.3,0.1

Type RM Length L Ch R = 1,14911,777,777,777
BEGIN DESCRIPTION:
Rocky Cedar T1 4.0
END DESCRIPTION:
XS GIS Cut Line= 4
      2703674.43      6913999.66      2703721.66      6913043.64
      2703755.27      6912956.33      2703537.72      6912520.89
#Sta/Elev= 30
  4011.5  426.56  4080.2  422.06  4120.3  418.63  4144.9  418.08  4150.3  416.99
  4180.4  415.17  4280.5  412.44  4320.5  411.74  4330.5  412.49  4681.0  410.37
  4754.3  410.72  4811.1  412.73  4851.2  412.98  4891.2  411.21  4972.8  413.20
  4991.1  411.30  4996.5  408.17  5001.4  406.99  5001.9  406.49  5005.9  406.99
  5014.4  408.99  5021.1  412.76  5035.8  413.61  5207.0  411.71  5392.4  411.86
  5520.1  414.26  5536.9  416.59  5542.5  418.04  5546.1  420.05  5549.0  420.05
#Mann=3,-1,0
  4011.5    0.05       0  5001.4    0.04       0  5005.9    0.05       0
Bank Sta=5001.4,5005.9
Exp/Cntr=0.3,0.1

Type RM Length L Ch R = 1,14134,0,0,0
BEGIN DESCRIPTION:
Mapping XS 7f147d69
END DESCRIPTION:
XS GIS Cut Line= 3
      2704027.06      6914355.42      2704360.71      6912977.59
      2703426.58      6912045.75
#Sta/Elev= 30
  3648.7  431.82  3839.5  430.50  3965.0  423.24  4095.7  414.32  4179.2  411.06
  4208.9  410.76  4257.7  408.30  4346.5  408.08  4373.5  413.42  4383.2  413.82
  4414.6  413.44  4477.1  408.81  4597.4  409.26  4661.6  408.29  4775.0  409.29
  4846.8  408.36  4877.6  409.60  4942.3  409.79  4970.2  406.79  4981.9  406.49
  4982.3  405.99  4986.4  406.49  5011.4  409.58  5314.8  408.65  5767.3  409.30
  5937.0  409.86  6113.8  412.01  6276.4  420.51  6283.5  421.57  6385.8  425.43
#Mann=3,-1,0
  3648.7    0.05       0  4981.9    0.04       0  4986.4    0.05       0
Bank Sta=4981.9,4986.4
Exp/Cntr=0.3,0.1

Chan Stop Cuts=-1