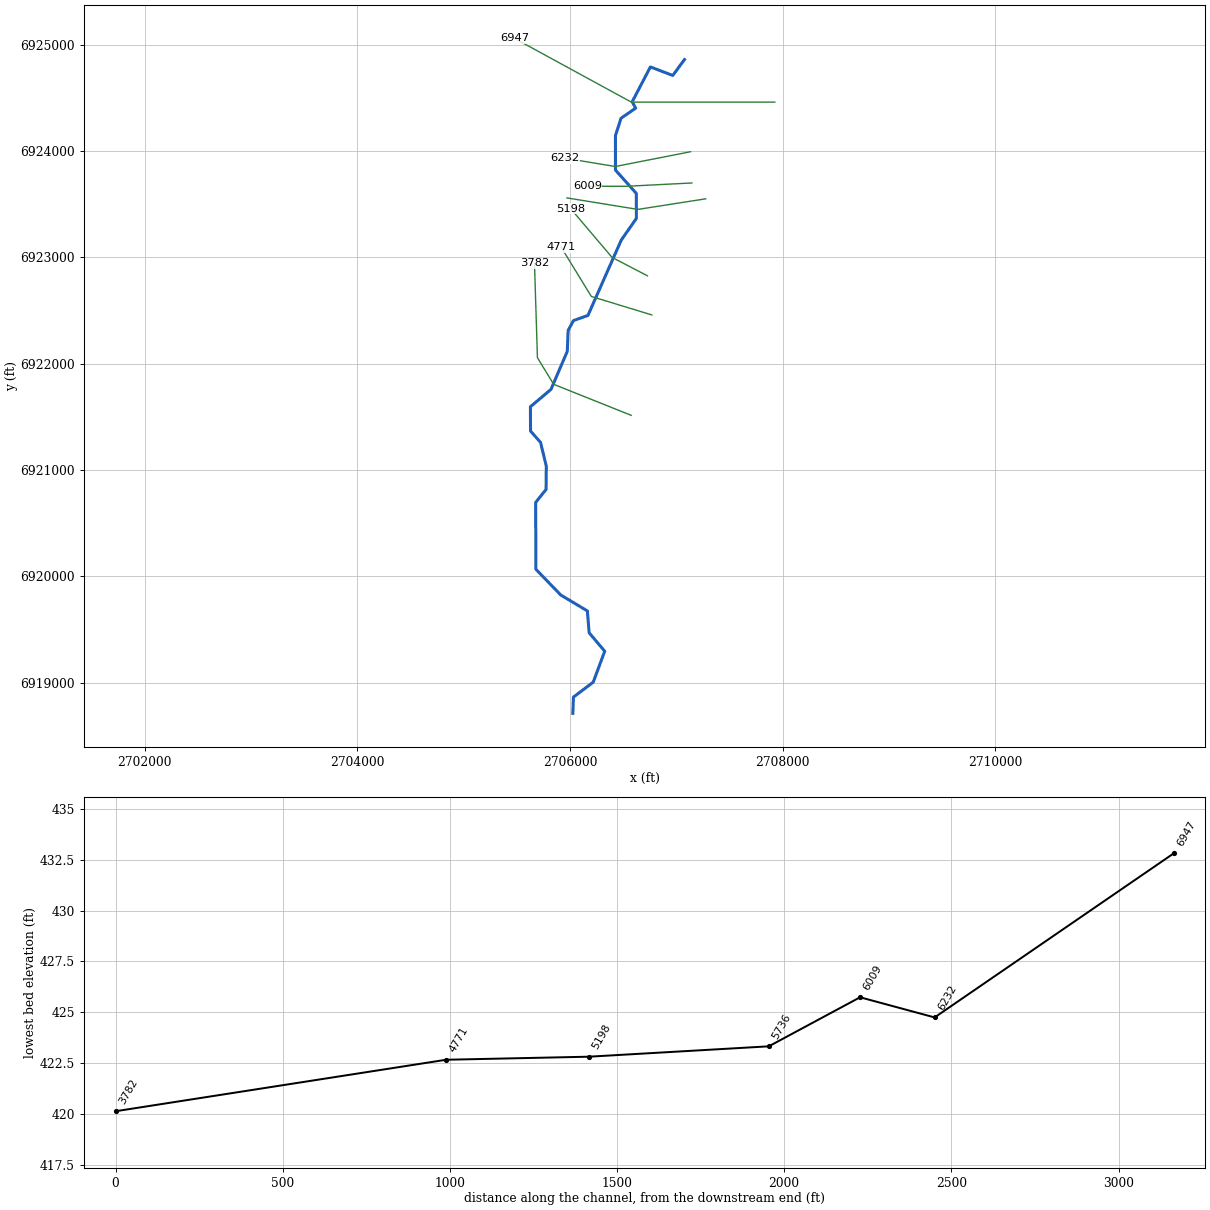
--- Rocky Cedar T3.prj (project) ---

Proj Title=Rocky Cedar T3 Base Level Engineering
Current Plan=p01
Default Exp/Contr=0.3,0.1
English Units
Geom File=g01
Flow File=f01
Plan File=p01
BEGIN DESCRIPTION:
Rocky Cedar T3
END DESCRIPTION:

--- Rocky Cedar T3.p01 (plan) ---

Plan Title=Multiple Run
Short Identifier=Multiple
Geom File=g01
Flow File=f01
Subcritical Flow
K Sum by GR= 0
Std Step Tol= 0.01
Critical Tol= 0.01
Num of Std Step Trials= 20
Max Error Tol= 0.3
Flow Tol Ratio= 0.001
Split Flow NTrial= 30
Split Flow Tol= 0.02
Split Flow Ratio= 0.02
Log Output Level= 0
Friction Slope Method= 1
Unsteady Friction Slope Method= 2
Unsteady Bridges Friction Slope Method= 1
Parabolic Critical Depth
Global Vel Dist=  1 , 1 , 1
Global Log Level= 0
CheckData=True
Encroach Param= -1, 0, 0, 0
BEGIN DESCRIPTION:
Multiple Run
END DESCRIPTION:

--- Rocky Cedar T3.f01 (steady flow) ---

Flow Title=Multiple
Number of Profiles=7
Profile Names=10-year,25-year,50-year,1pct_min,100-year,1pct_plu,500-year
River Rch & RM= Rocky Cedar T3,Reach-1,6947
     489     642     763     450     899    1793    1244
River Rch & RM= Rocky Cedar T3,Reach-1,6232
     638     849    1019     606    1209    2413    1701
Boundary for River Rch & Prof#=Rocky Cedar T3,Reach-1,1
Up Type=0
Dn Type=3
Dn Slope=0.005
Boundary for River Rch & Prof#=Rocky Cedar T3,Reach-1,2
Up Type=0
Dn Type=3
Dn Slope=0.005
Boundary for River Rch & Prof#=Rocky Cedar T3,Reach-1,3
Up Type=0
Dn Type=3
Dn Slope=0.005
Boundary for River Rch & Prof#=Rocky Cedar T3,Reach-1,4
Up Type=0
Dn Type=3
Dn Slope=0.005
Boundary for River Rch & Prof#=Rocky Cedar T3,Reach-1,5
Up Type=0
Dn Type=3
Dn Slope=0.005
Boundary for River Rch & Prof#=Rocky Cedar T3,Reach-1,6
Up Type=0
Dn Type=3
Dn Slope=0.005
Boundary for River Rch & Prof#=Rocky Cedar T3,Reach-1,7
Up Type=0
Dn Type=3
Dn Slope=0.005

--- Rocky Cedar T3.g01 (geometry) ---

Geom Title=Existing Conditions

River Reach=Rocky Cedar T3,Reach-1
Reach XY= 30
      2707076.00      6924861.00      2706965.67      6924711.86
      2706755.52      6924791.99      2706584.25      6924464.22
      2706616.82      6924404.05      2706479.53      6924309.72
      2706426.52      6924145.78      2706427.05      6923821.44
      2706622.91      6923602.69      2706623.76      6923366.93
      2706481.54      6923163.42      2706167.99      6922454.62
      2706031.44      6922405.75      2705981.69      6922313.39
      2705973.76      6922116.93      2705820.17      6921758.70
      2705626.66      6921595.17      2705628.07      6921366.86
      2705722.44      6921259.53      2705776.20      6921036.08
      2705773.93      6920816.86      2705676.39      6920695.84
      2705678.05      6920066.84      2705912.44      6919824.49
      2706162.77      6919674.67      2706179.09      6919469.31
      2706325.63      6919295.73      2706217.87      6919004.93
      2706031.33      6918863.72      2706026.00      6918711.00

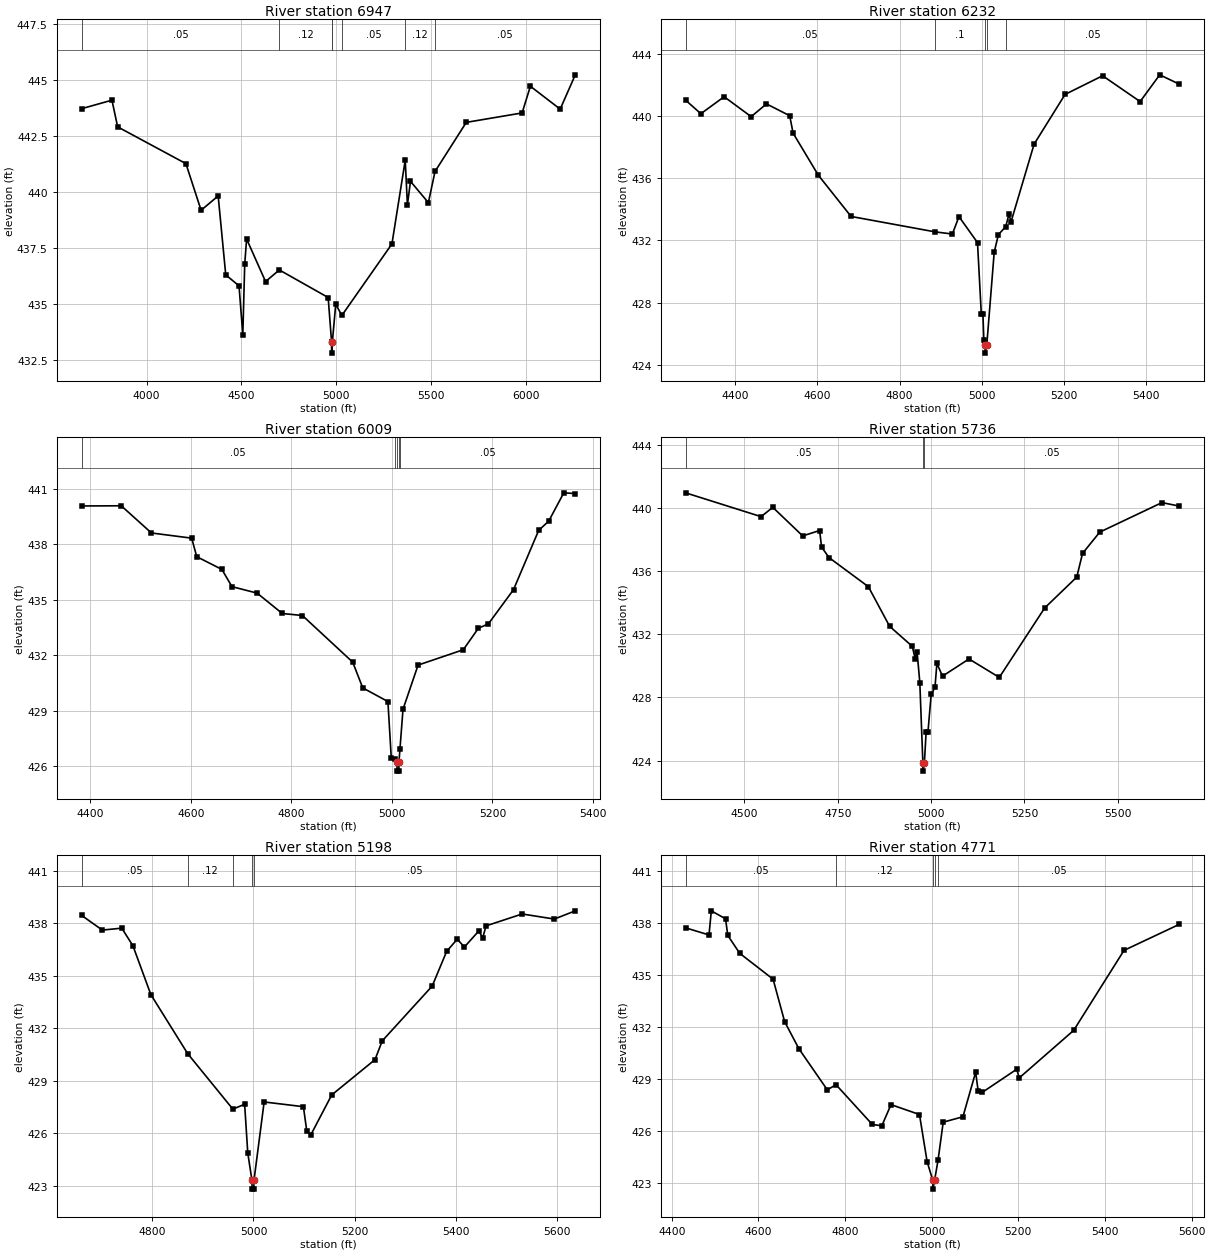
Type RM Length L Ch R = 1,6947,715,715,715
BEGIN DESCRIPTION:
Rocky Cedar T3 7.0
END DESCRIPTION:
XS GIS Cut Line= 3
      2707925.99      6924461.00      2706576.00      6924461.00
      2705475.99      6925061.00
#Sta/Elev= 30
  3657.8  443.71  3817.8  444.09  3847.8  442.90  4207.8  441.26  4287.8  439.18
  4377.8  439.82  4417.8  436.30  4487.8  435.81  4507.8  433.63  4517.8  436.77
  4527.8  437.90  4627.8  436.00  4700.2  436.52  4957.8  435.29  4975.8  433.31
  4976.0  432.81  4979.8  433.31  4997.8  434.99  5029.9  434.49  5294.0  437.68
  5364.1  441.41  5375.6  439.42  5391.8  440.47  5486.2  439.52  5521.1  440.91
  5686.0  443.10  5980.3  443.52  6024.0  444.71  6181.1  443.69  6260.8  445.22
#Mann=7,-1,0
  3657.8    0.05       0  4700.2    0.12       0  4975.8    0.07       0
  4979.8    0.12       0  5029.9    0.05       0  5364.1    0.12       0
  5521.1    0.05       0
Bank Sta=4975.8,4979.8
Exp/Cntr=0.3,0.1

Type RM Length L Ch R = 1,6232,223,223,223
BEGIN DESCRIPTION:
Mapping XS d479bcb9
END DESCRIPTION:
XS GIS Cut Line= 3
      2707132.54      6923994.17      2706425.10      6923855.29
      2705952.05      6923933.41
#Sta/Elev= 30
  4279.5  441.02  4316.7  440.15  4373.3  441.24  4439.0  439.96  4476.2  440.78
  4532.7  440.02  4540.9  438.90  4602.1  436.20  4681.9  433.54  4886.0  432.55
  4928.2  432.41  4944.2  433.53  4989.3  431.86  4998.6  427.24  5002.5  427.24
  5004.7  425.59  5007.8  425.25  5008.0  424.75  5011.8  425.25  5029.9  431.24
  5040.1  432.37  5058.0  432.89  5065.8  433.69  5070.9  433.20  5126.9  438.19
  5202.2  441.39  5293.5  442.59  5384.7  440.93  5432.4  442.65  5479.9  442.05
#Mann=5,-1,0
  4279.5    0.05       0  4886.0     0.1       0  5007.8    0.07       0
  5011.8     0.1       0  5058.0    0.05       0
Bank Sta=5007.8,5011.8
Exp/Cntr=0.3,0.1

Type RM Length L Ch R = 1,6009,273,273,273
BEGIN DESCRIPTION:
Mapping XS 56271278
END DESCRIPTION:
XS GIS Cut Line= 3
      2707144.81      6923700.37      2706527.67      6923669.13
      2706163.10      6923669.13
#Sta/Elev= 30
  4382.4  440.07  4461.3  440.08  4521.4  438.61  4601.5  438.33  4611.5  437.33
  4661.6  436.64  4681.6  435.71  4731.7  435.36  4781.7  434.26  4821.8  434.15
  4921.9  431.63  4941.9  430.24  4992.0  429.50  4998.7  426.44  5005.1  426.40
  5010.0  426.24  5010.3  425.74  5013.8  425.74  5014.0  426.24  5016.0  426.95
  5022.0  429.08  5052.0  431.47  5142.0  432.30  5172.0  433.46  5192.0  433.70
  5242.0  435.55  5292.0  438.75  5312.0  439.25  5342.0  440.78  5364.9  440.74
#Mann=5,-1,0
  4382.4    0.05       0  5005.1     0.1       0  5010.0    0.04       0
  5014.0     0.1       0  5016.0    0.05       0
Bank Sta=5010,5014
Exp/Cntr=0.3,0.1

Type RM Length L Ch R = 1,5736,538,538,538
BEGIN DESCRIPTION:
Mapping XS 17fe73ad
END DESCRIPTION:
XS GIS Cut Line= 3
      2707275.80      6923551.47      2706637.77      6923451.64
      2705970.20      6923560.01
#Sta/Elev= 30
  4342.4  440.97  4544.6  439.46  4576.0  440.05  4656.0  438.24  4701.4  438.58
  4706.6  437.53  4726.8  436.86  4831.9  435.02  4888.8  432.51  4949.5  431.24
  4957.3  430.45  4962.3  430.91  4969.7  428.94  4977.9  423.83  4978.1  423.33
  4981.9  423.83  4986.6  425.84  4991.6  425.84  5000.1  428.20  5010.3  428.64
  5015.4  430.16  5030.5  429.35  5101.4  430.44  5182.5  429.27  5304.0  433.67
  5390.0  435.63  5405.4  437.13  5451.6  438.48  5618.1  440.35  5664.5  440.13
#Mann=3,-1,0
  4342.4    0.05       0  4977.9    0.04       0  4981.9    0.05       0
Bank Sta=4977.9,4981.9
Exp/Cntr=0.3,0.1

Type RM Length L Ch R = 1,5198,427,427,427
BEGIN DESCRIPTION:
Mapping XS c947041b
END DESCRIPTION:
XS GIS Cut Line= 3
      2706727.59      6922827.20      2706394.28      6923000.80
      2706005.39      6923459.13
#Sta/Elev= 30
  4659.9  438.46  4700.9  437.62  4739.4  437.73  4761.5  436.72  4797.0  433.93
  4869.8  430.56  4959.2  427.39  4982.5  427.67  4988.7  424.89  4997.0  423.32
  4997.2  422.82  5000.7  422.82  5001.0  423.32  5021.1  427.80  5098.8  427.53
  5105.4  426.15  5113.1  425.90  5154.8  428.20  5240.5  430.22  5254.8  431.29
  5353.6  434.42  5382.2  436.40  5403.2  437.10  5417.3  436.65  5445.9  437.57
  5453.6  437.17  5460.2  437.86  5531.6  438.54  5595.3  438.25  5636.8  438.72
#Mann=5,-1,0
  4659.9    0.05       0  4869.8    0.12       0  4959.2    0.05       0
  4997.0    0.04       0  5001.0    0.05       0
Bank Sta=4997,5001
Exp/Cntr=0.3,0.1

Type RM Length L Ch R = 1,4771,989,989,989
BEGIN DESCRIPTION:
Mapping XS fc6922b4
END DESCRIPTION:
XS GIS Cut Line= 3
      2706769.26      6922459.13      2706199.84      6922632.74
      2705915.73      6923097.01
#Sta/Elev= 30
  4431.9  437.73  4486.0  437.32  4491.3  438.71  4524.1  438.25  4529.4  437.29
  4556.9  436.26  4633.9  434.77  4660.6  432.32  4693.5  430.76  4759.1  428.39
  4779.1  428.69  4862.8  426.40  4884.9  426.32  4906.1  427.54  4971.8  426.97
  4989.4  424.26  5002.6  423.17  5002.8  422.67  5006.6  423.17  5014.7  424.34
  5026.6  426.53  5072.1  426.84  5101.5  429.41  5107.4  428.30  5116.9  428.25
  5196.3  429.58  5202.1  429.08  5327.8  431.82  5443.9  436.43  5571.5  437.93
#Mann=5,-1,0
  4431.9    0.05       0  4779.1    0.12       0  5002.6    0.07       0
  5006.6    0.12       0  5014.7    0.05       0
Bank Sta=5002.6,5006.6
Exp/Cntr=0.3,0.1

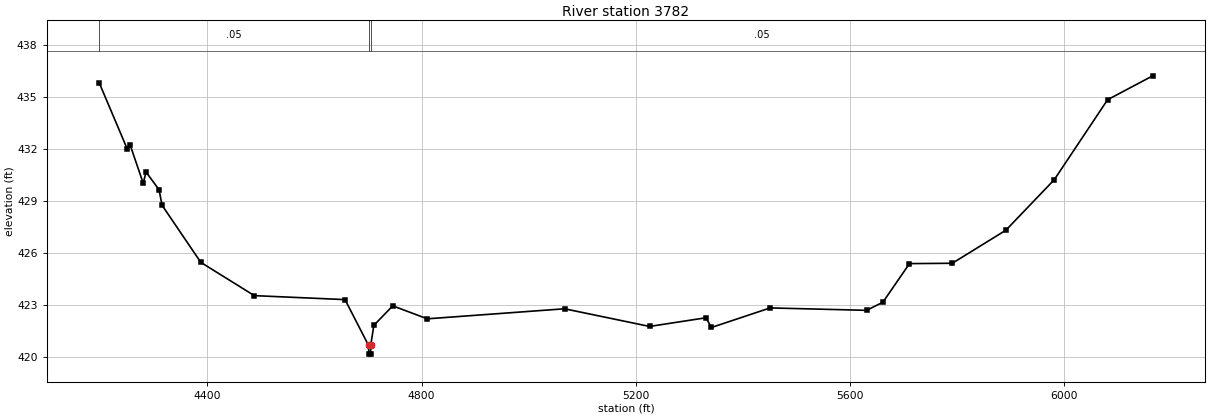
Type RM Length L Ch R = 1,3782,0,0,0
BEGIN DESCRIPTION:
Mapping XS 4411f933
END DESCRIPTION:
XS GIS Cut Line= 4
      2706574.82      6921514.69      2705845.67      6921806.35
      2705692.89      6922056.35      2705665.11      6922945.22
#Sta/Elev= 30
  4198.2  435.80  4250.5  431.98  4255.9  432.21  4280.1  430.02  4285.5  430.66
  4309.7  429.64  4315.4  428.74  4387.8  425.44  4487.7  423.52  4657.1  423.29
  4701.1  420.64  4701.4  420.14  4704.9  420.14  4705.1  420.64  4710.9  421.80
  4746.2  422.93  4810.8  422.18  5067.2  422.76  5225.9  421.74  5331.2  422.24
  5341.6  421.68  5451.2  422.81  5631.3  422.67  5661.8  423.14  5711.4  425.37
  5791.4  425.39  5891.5  427.30  5981.9  430.22  6081.5  434.84  6165.8  436.22
#Mann=3,-1,0
  4198.2    0.05       0  4701.1    0.05       0  4705.1    0.05       0
Bank Sta=4701.1,4705.1
Exp/Cntr=0.3,0.1

Chan Stop Cuts=-1