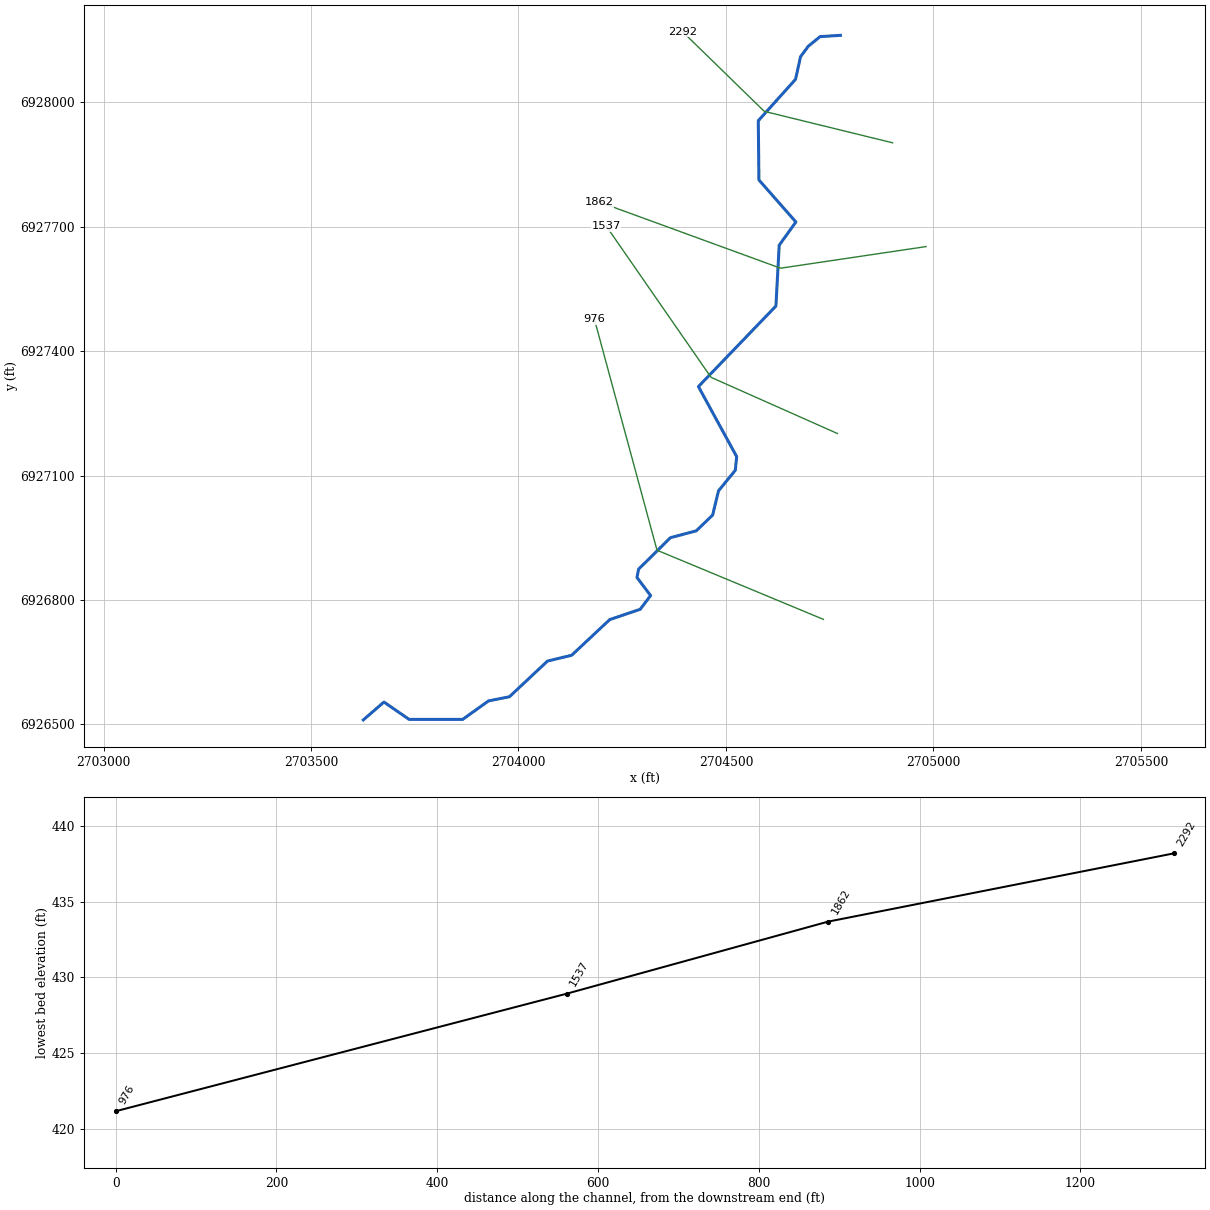
--- Rocky Cedar T4.prj (project) ---

Proj Title=Rocky Cedar T4 Base Level Engineering
Current Plan=p01
Default Exp/Contr=0.3,0.1
English Units
Geom File=g01
Flow File=f01
Plan File=p01
BEGIN DESCRIPTION:
Rocky Cedar T4
END DESCRIPTION:

--- Rocky Cedar T4.p01 (plan) ---

Plan Title=Multiple Run
Short Identifier=Multiple
Geom File=g01
Flow File=f01
Subcritical Flow
K Sum by GR= 0
Std Step Tol= 0.01
Critical Tol= 0.01
Num of Std Step Trials= 20
Max Error Tol= 0.3
Flow Tol Ratio= 0.001
Split Flow NTrial= 30
Split Flow Tol= 0.02
Split Flow Ratio= 0.02
Log Output Level= 0
Friction Slope Method= 1
Unsteady Friction Slope Method= 2
Unsteady Bridges Friction Slope Method= 1
Parabolic Critical Depth
Global Vel Dist=  1 , 1 , 1
Global Log Level= 0
CheckData=True
Encroach Param= -1, 0, 0, 0
BEGIN DESCRIPTION:
Multiple Run
END DESCRIPTION:

--- Rocky Cedar T4.f01 (steady flow) ---

Flow Title=Multiple
Number of Profiles=7
Profile Names=10-year,25-year,50-year,1pct_min,100-year,1pct_plu,500-year
River Rch & RM= Rocky Cedar T4,Reach-1,2292
     423     555     659     389     777    1550    1077
Boundary for River Rch & Prof#=Rocky Cedar T4,Reach-1,1
Up Type=0
Dn Type=3
Dn Slope=0.005
Boundary for River Rch & Prof#=Rocky Cedar T4,Reach-1,2
Up Type=0
Dn Type=3
Dn Slope=0.005
Boundary for River Rch & Prof#=Rocky Cedar T4,Reach-1,3
Up Type=0
Dn Type=3
Dn Slope=0.005
Boundary for River Rch & Prof#=Rocky Cedar T4,Reach-1,4
Up Type=0
Dn Type=3
Dn Slope=0.005
Boundary for River Rch & Prof#=Rocky Cedar T4,Reach-1,5
Up Type=0
Dn Type=3
Dn Slope=0.005
Boundary for River Rch & Prof#=Rocky Cedar T4,Reach-1,6
Up Type=0
Dn Type=3
Dn Slope=0.005
Boundary for River Rch & Prof#=Rocky Cedar T4,Reach-1,7
Up Type=0
Dn Type=3
Dn Slope=0.005

--- Rocky Cedar T4.g01 (geometry) ---

Geom Title=Existing Conditions

River Reach=Rocky Cedar T4,Reach-1
Reach XY= 30
      2704776.00      6928161.00      2704727.03      6928157.86
      2704698.73      6928134.85      2704679.86      6928109.54
      2704667.83      6928054.97      2704578.05      6927955.14
      2704579.55      6927812.47      2704668.67      6927711.10
      2704628.48      6927655.14      2704620.53      6927508.55
      2704433.77      6927314.41      2704525.93      6927145.61
      2704522.66      6927112.72      2704482.19      6927063.16
      2704467.98      6927004.66      2704428.54      6926966.75
      2704366.29      6926950.21      2704289.64      6926874.36
      2704285.62      6926854.32      2704318.53      6926810.79
      2704293.53      6926777.65      2704220.00      6926752.82
      2704128.28      6926666.87      2704069.96      6926652.82
      2703978.29      6926566.84      2703927.75      6926556.78
      2703865.50      6926512.19      2703736.43      6926512.30
      2703675.86      6926554.09      2703626.00      6926511.00

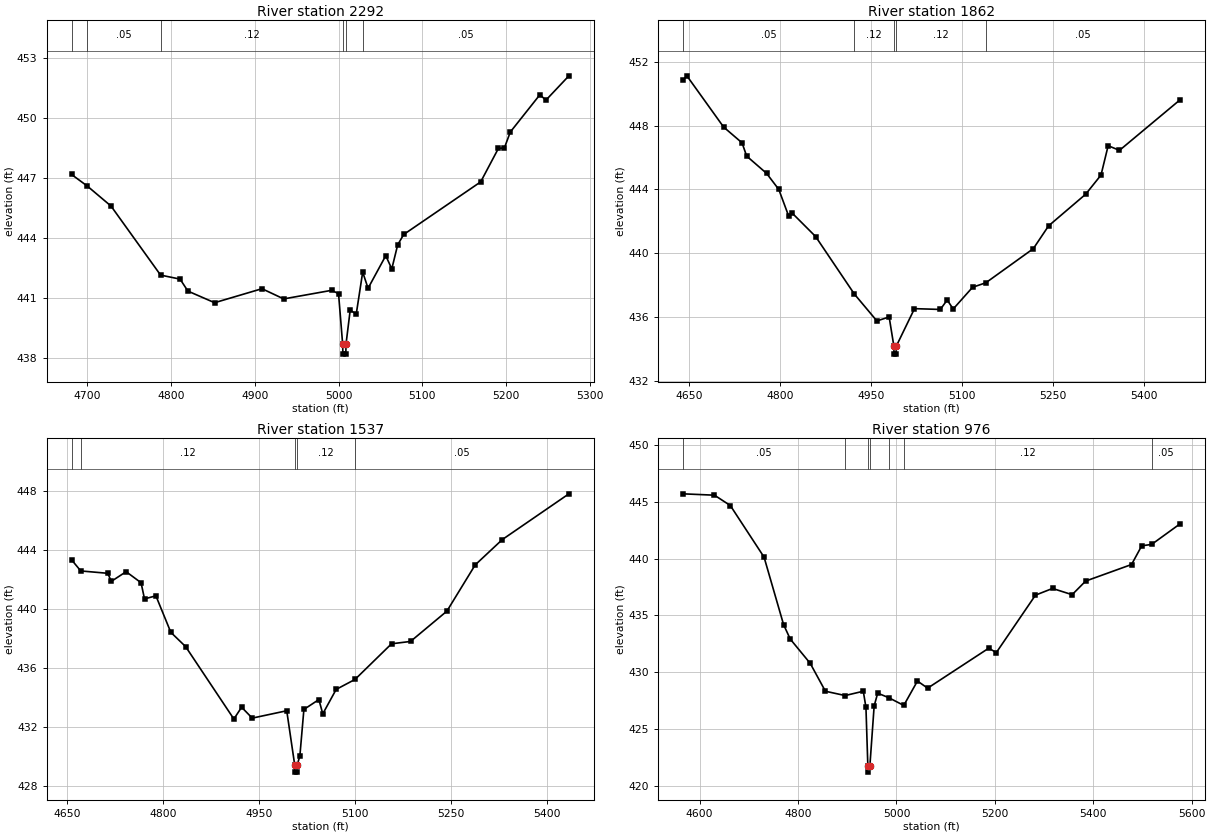
Type RM Length L Ch R = 1,2292,430,430,430
BEGIN DESCRIPTION:
Rocky Cedar T4 3.0
END DESCRIPTION:
XS GIS Cut Line= 3
      2704901.71      6927901.97      2704592.46      6927977.75
      2704395.78      6928169.52
#Sta/Elev= 30
  4681.6  447.16  4700.4  446.58  4728.7  445.58  4787.8  442.13  4811.0  441.93
  4820.4  441.33  4852.2  440.75  4908.7  441.45  4934.6  440.94  4991.9  441.37
  5000.0  441.20  5004.9  438.68  5005.2  438.18  5008.7  438.18  5008.9  438.68
  5013.9  440.38  5021.1  440.18  5028.8  442.28  5035.2  441.47  5056.3  443.10
  5063.5  442.44  5070.5  443.64  5077.7  444.16  5169.5  446.79  5190.6  448.46
  5197.8  448.49  5204.8  449.28  5240.2  451.15  5247.2  450.87  5274.7  452.09
#Mann=6,-1,0
  4681.6    0.12       0  4700.4    0.05       0  4787.8    0.12       0
  5004.9    0.07       0  5008.9    0.12       0  5028.8    0.05       0
Bank Sta=5004.9,5008.9
Exp/Cntr=0.3,0.1

Type RM Length L Ch R = 1,1862,325,325,325
BEGIN DESCRIPTION:
Mapping XS 0f1bc4ce
END DESCRIPTION:
XS GIS Cut Line= 3
      2704982.39      6927651.82      2704631.66      6927599.73
      2704194.18      6927759.44
#Sta/Elev= 30
  4639.2  450.85  4645.7  451.12  4706.3  447.91  4736.7  446.92  4744.3  446.09
  4777.1  445.01  4797.3  444.00  4813.7  442.32  4818.8  442.54  4858.0  441.05
  4922.0  437.44  4959.1  435.76  4979.3  436.01  4987.1  434.18  4987.3  433.68
  4990.8  433.68  4991.1  434.18  5021.1  436.53  5063.7  436.48  5075.0  437.07
  5085.0  436.51  5116.9  437.87  5138.7  438.15  5217.1  440.29  5242.3  441.72
  5303.4  443.70  5328.7  444.90  5340.5  446.74  5359.2  446.45  5459.5  449.63
#Mann=5,-1,0
  4639.2    0.05       0  4922.0    0.12       0  4987.1    0.07       0
  4991.1    0.12       0  5138.7    0.05       0
Bank Sta=4987.1,4991.1
Exp/Cntr=0.3,0.1

Type RM Length L Ch R = 1,1537,561,561,561
BEGIN DESCRIPTION:
Mapping XS a353d783
END DESCRIPTION:
XS GIS Cut Line= 3
      2704768.82      6927201.29      2704464.13      6927336.71
      2704211.50      6927701.32
#Sta/Elev= 30
  4657.0  443.36  4671.4  442.60  4713.6  442.44  4719.1  441.89  4742.3  442.55
  4765.6  441.80  4771.0  440.70  4788.8  440.91  4812.1  438.43  4835.2  437.46
  4910.6  432.54  4922.7  433.34  4939.3  432.60  4993.2  433.10  5005.6  429.43
  5005.9  428.93  5009.4  428.93  5009.6  429.43  5013.7  430.03  5020.0  433.19
  5043.4  433.86  5049.5  432.89  5070.4  434.55  5099.9  435.23  5156.9  437.65
  5186.6  437.81  5243.4  439.87  5287.6  443.01  5329.9  444.73  5434.0  447.84
#Mann=5,-1,0
  4657.0     0.1       0  4671.4    0.12       0  5005.6    0.07       0
  5009.6    0.12       0  5099.9    0.05       0
Bank Sta=5005.6,5009.6
Exp/Cntr=0.3,0.1

Type RM Length L Ch R = 1,976,0,0,0
BEGIN DESCRIPTION:
Mapping XS 49bbcd72
END DESCRIPTION:
XS GIS Cut Line= 3
      2704734.94      6926753.38      2704333.92      6926920.04
      2704183.05      6927476.69
#Sta/Elev= 30
  4566.0  445.71  4630.1  445.59  4662.3  444.68  4730.9  440.13  4770.6  434.18
  4784.1  432.91  4824.7  430.77  4855.6  428.31  4895.7  427.93  4932.6  428.31
  4938.0  426.89  4941.9  421.68  4942.1  421.18  4945.9  421.68  4954.7  427.02
  4961.9  428.14  4984.4  427.74  5014.9  427.06  5042.7  429.21  5063.4  428.58
  5187.8  432.11  5202.9  431.71  5282.6  436.78  5317.3  437.37  5357.1  436.82
  5384.6  438.02  5477.9  439.48  5498.6  441.13  5518.7  441.25  5577.0  443.08
#Mann=7,-1,0
  4566.0    0.05       0  4895.7    0.12       0  4941.9    0.07       0
  4945.9    0.12       0  4984.4     0.1       0  5014.9    0.12       0
  5518.7    0.05       0
Bank Sta=4941.9,4945.9
Exp/Cntr=0.3,0.1

Chan Stop Cuts=-1