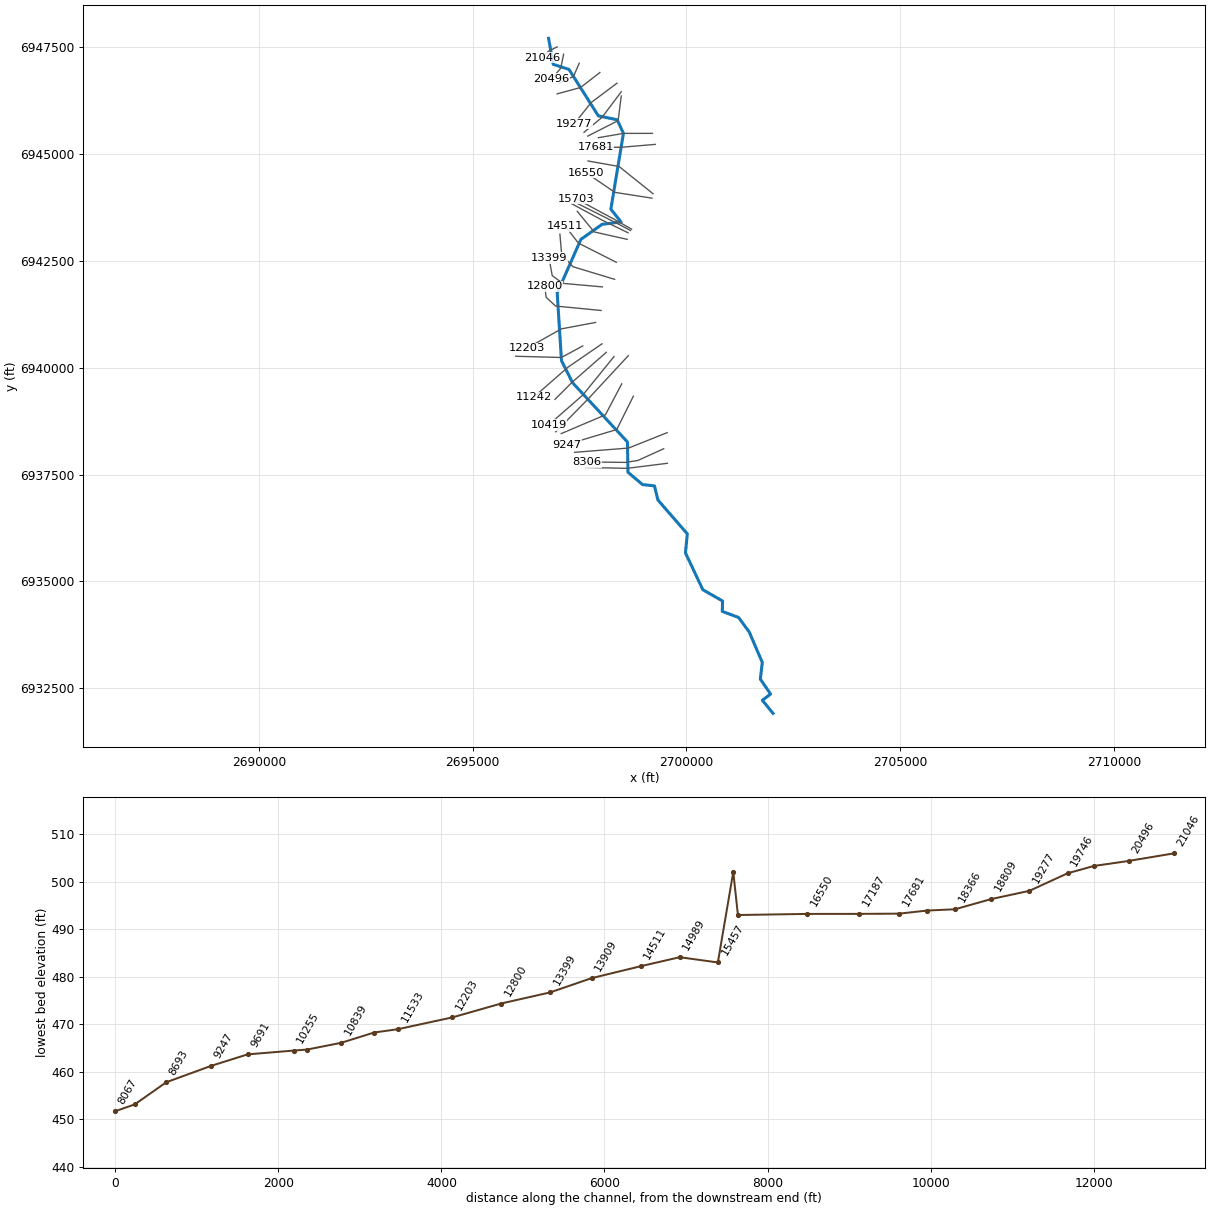
--- Rocky Cedar T5.prj (project) ---

Proj Title=Rocky Cedar T5 Base Level Engineering
Current Plan=p01
Default Exp/Contr=0.3,0.1
English Units
Geom File=g01
Flow File=f01
Plan File=p01
Y Axis Title=Elevation
X Axis Title(PF)=Main Channel Distance
X Axis Title(XS)=Station
BEGIN DESCRIPTION:
Rocky Cedar T5
END DESCRIPTION:
DSS Export Rating Curves= 0
DSS Export Rating Curve Sorted= 0
DSS Export Volume Flow Curves= 0
DXF OffsetX= 0
DXF OffsetY= 0
DXF ScaleX= 1
DXF ScaleY= 10

--- Rocky Cedar T5.p01 (plan) ---

Plan Title=Multiple Run
Short Identifier=Multiple
Geom File=g01
Flow File=f01
Subcritical Flow
K Sum by GR= 0
Std Step Tol= 0.01
Critical Tol= 0.01
Num of Std Step Trials= 20
Max Error Tol= 0.3
Flow Tol Ratio= 0.001
Split Flow NTrial= 30
Split Flow Tol= 0.02
Split Flow Ratio= 0.02
Log Output Level= 0
Friction Slope Method= 1
Unsteady Friction Slope Method= 2
Unsteady Bridges Friction Slope Method= 1
Parabolic Critical Depth
Global Vel Dist=  1 , 1 , 1
Global Log Level= 0
CheckData=True
Encroach Param= -1, 0, 0, 0
BEGIN DESCRIPTION:
Multiple Run
END DESCRIPTION:

--- Rocky Cedar T5.f01 (steady flow) ---

Flow Title=Multiple
Program Version=4.10
Number of Profiles= 7
Profile Names=10-year,25-year,50-year,1pct_min,100-year,1pct_plu,500-year
River Rch & RM=Rocky Cedar T5,Reach-1         ,21046
     640     855    1028     613    1223    2439    1729
River Rch & RM=Rocky Cedar T5,Reach-1         ,15457
     770    1040    1260     756    1509    3011    2163
River Rch & RM=Rocky Cedar T5,Reach-1         ,12203
    1201    1662    2047    1247    2488    4964    3677
River Rch & RM=Rocky Cedar T5,Reach-1         ,9691
    1539    2154    2672    1638    3269    6522    4894
River Rch & RM=Rocky Cedar T5,Reach-1         ,3320
    1579    2209    2739    1679    3350    6684    5012
Boundary for River Rch & Prof#=Rocky Cedar T5,Reach-1         , 1
Up Type= 0
Dn Type= 3
Dn Slope=0.005
Boundary for River Rch & Prof#=Rocky Cedar T5,Reach-1         , 2
Up Type= 0
Dn Type= 3
Dn Slope=0.005
Boundary for River Rch & Prof#=Rocky Cedar T5,Reach-1         , 3
Up Type= 0
Dn Type= 3
Dn Slope=0.005
Boundary for River Rch & Prof#=Rocky Cedar T5,Reach-1         , 4
Up Type= 0
Dn Type= 3
Dn Slope=0.005
Boundary for River Rch & Prof#=Rocky Cedar T5,Reach-1         , 5
Up Type= 0
Dn Type= 3
Dn Slope=0.005
Boundary for River Rch & Prof#=Rocky Cedar T5,Reach-1         , 6
Up Type= 0
Dn Type= 3
Dn Slope=0.005
Boundary for River Rch & Prof#=Rocky Cedar T5,Reach-1         , 7
Up Type= 0
Dn Type= 3
Dn Slope=0.005
DSS Import GetInterval= 0
DSS Import GetPeak= 0
DSS Import FillOption= 0

--- Rocky Cedar T5.g01 (geometry) ---

Geom Title=Existing Conditions
Program Version=4.10

River Reach=Rocky Cedar T5  ,Reach-1
Reach XY= 30
        2696776.        6947711.      2696886.35      6947100.88
      2697252.88      6946984.74      2697939.26      6945897.35
      2698382.39      6945803.66      2698526.29      6945486.12
      2698233.32       6943710.9      2698473.01       6943412.4
      2698027.45      6943357.47      2697531.58      6943005.42
      2696977.92      6941749.05      2697078.06      6940166.85
      2697339.46       6939647.3      2698620.54      6938263.45
      2698633.62       6937554.5      2698973.53      6937266.45
       2699253.2      6937234.97      2699333.81      6936904.81
      2700020.63      6936113.38      2699978.24      6935666.93
      2700383.86      6934804.83      2700846.09      6934541.63
      2700838.96      6934297.44      2701220.56      6934155.75
      2701470.54      6933813.45      2701774.35      6933104.96
      2701729.61       6932712.5       2701968.2      6932364.03
      2701777.43      6932217.44        2702026.        6931911.

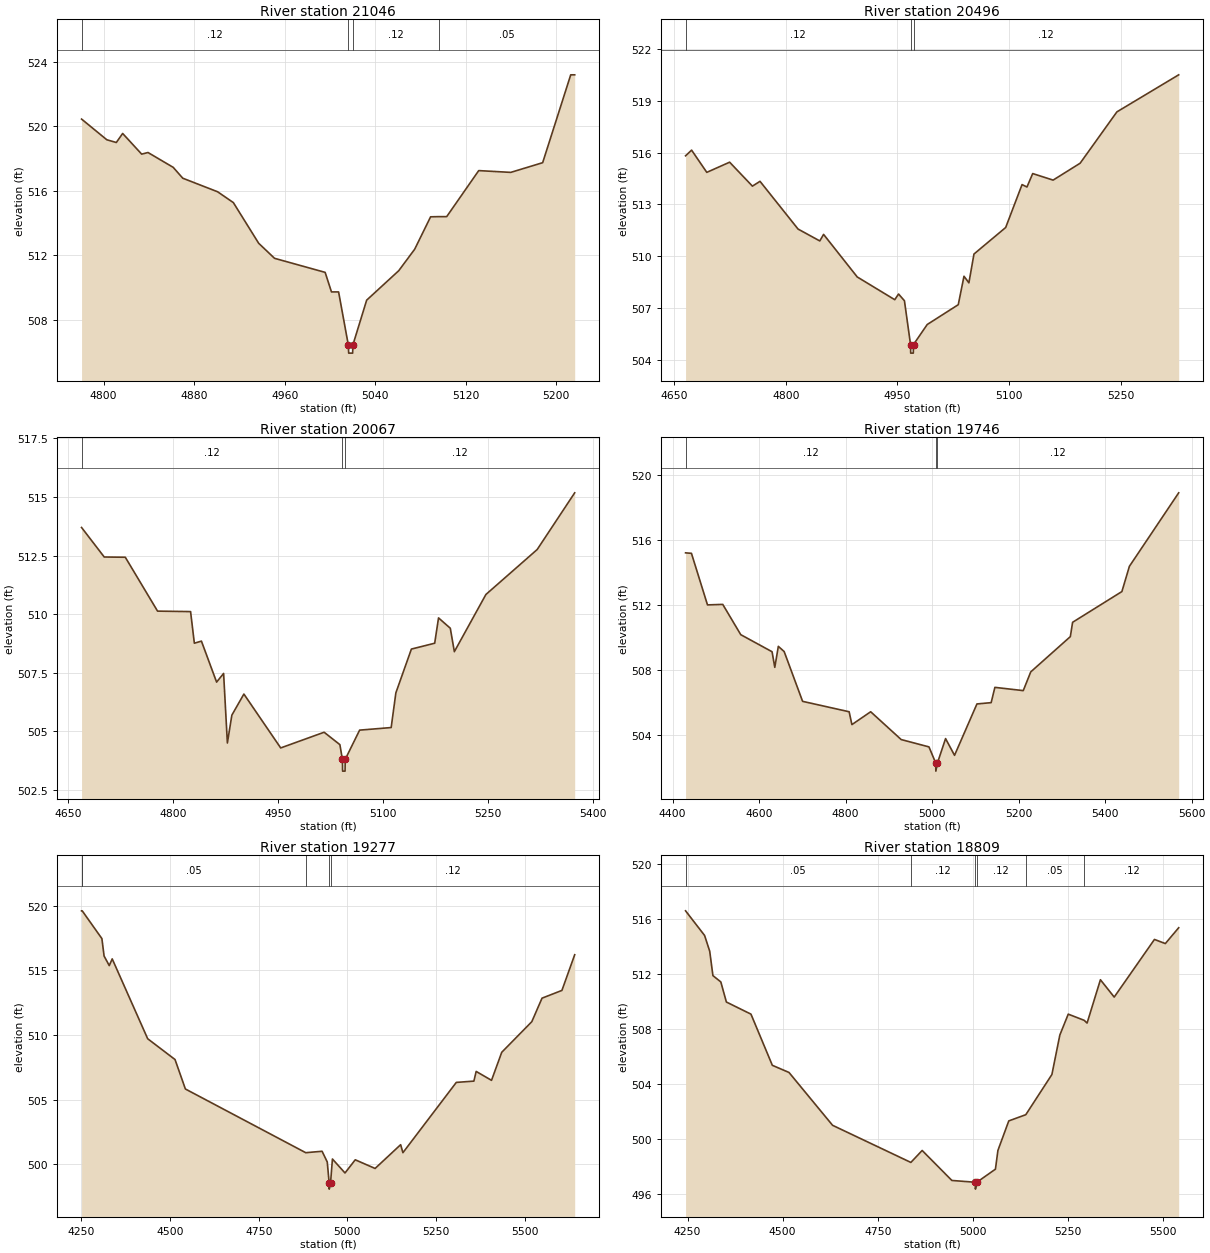
Type RM Length L Ch R = 1 ,21046   ,550,550,550
BEGIN DESCRIPTION:
Rocky Cedar T5 42.0
END DESCRIPTION:
XS GIS Cut Line= 3
      2696975.98      6947510.99        2696776.        6947411.
      2696626.01      6947261.01
#Sta/Elev= 30
  4780.5  520.44  4802.8  519.16  4811.2  518.99  4816.8  519.55  4833.6  518.27
  4839.2  518.37  4861.5  517.45  4869.9  516.78  4900.7  515.94  4914.6  515.27
    4937  512.75    4951  511.82  4995.7  510.95  5001.3  509.74  5007.6  509.74
  5016.2  506.45  5016.5  505.95    5020  505.95  5020.2  506.45  5032.4  509.23
  5060.7  511.05  5074.8  512.38  5088.9  514.39  5096.5   514.4  5103.1   514.4
  5131.4  517.25  5159.7  517.14  5187.9  517.74  5212.7  523.18  5216.2  523.18
#Mann= 4 ,-1 , 0
  4780.5     .12       0  5016.2     .07       0  5020.2     .12       0
  5096.5     .05       0
Bank Sta=5016.2,5020.2
XS Rating Curve= 0 ,0
Exp/Cntr=0.3,0.1

Type RM Length L Ch R = 1 ,20496   ,429,429,429
BEGIN DESCRIPTION:
Rocky Cedar T5 41.0
END DESCRIPTION:
XS GIS Cut Line= 3
      2697128.05      6947338.96      2697060.66      6947011.22
       2696848.1      6946761.68
#Sta/Elev= 30
  4665.4  515.82  4673.5  516.15  4693.9  514.86  4724.6  515.45  4755.2  514.06
  4765.4  514.34  4816.5  511.57  4845.7  510.88  4850.8  511.26    4896  508.79
  4946.4  507.47  4951.5   507.8  4959.4  507.41  4967.6  504.87  4967.8  504.37
  4971.3  504.37  4971.6  504.87    4990  506.03  5031.7  507.18  5039.4  508.83
    5046  508.45  5052.8  510.12  5095.4  511.66  5117.4  514.15    5124  514.01
  5131.7  514.79  5159.1  514.41  5195.4  515.39  5244.8  518.37  5327.8  520.52
#Mann= 3 ,-1 , 0
  4665.4     .12       0  4967.6     .07       0  4971.6     .12       0
Bank Sta=4967.6,4971.6
XS Rating Curve= 0 ,0
Exp/Cntr=0.3,0.1

Type RM Length L Ch R = 1 ,20067   ,321,321,321
BEGIN DESCRIPTION:
Rocky Cedar T5 40.0
END DESCRIPTION:
XS GIS Cut Line= 3
      2697492.63      6947128.44      2697362.42      6946824.23
      2697026.03      6946661.01
#Sta/Elev= 30
  4669.1   513.7  4701.5  512.44  4731.6  512.43  4777.7  510.13  4824.9  510.11
  4830.3  508.76  4840.4  508.85  4862.1   507.1  4872.1  507.47  4877.5   504.5
  4883.9  505.69  4901.1  506.59  4953.7  504.29  5015.8  504.96  5038.3  504.43
  5041.9   503.8  5042.2   503.3  5045.7   503.3  5045.9   503.8  5066.5  505.05
  5111.6  505.16  5118.3  506.64  5140.5  508.51  5173.8  508.76  5179.3  509.84
  5196.1   509.4  5201.9   508.4    5247  510.84  5320.3  512.76  5373.9  515.18
#Mann= 3 ,-1 , 0
  4669.1     .12       0  5041.9     .07       0  5045.9     .12       0
Bank Sta=5041.9,5045.9
XS Rating Curve= 0 ,0
Exp/Cntr=0.3,0.1

Type RM Length L Ch R = 1 ,19746   ,469,469,469
BEGIN DESCRIPTION:
Rocky Cedar T5 39.0
END DESCRIPTION:
XS GIS Cut Line= 3
        2697976.        6946911.        2697526.        6946561.
      2696975.97      6946410.99
#Sta/Elev= 30
  4429.9  515.19  4443.5  515.16  4480.6  511.99  4515.9  512.02  4557.5  510.16
  4629.9  509.11  4636.2  508.15  4644.4  509.44  4657.9  509.12  4700.5  506.06
  4808.1  505.42  4814.5  504.63  4857.9  505.42  4928.5  503.71  4992.7  503.26
  5008.3  502.27  5008.6  501.77  5012.3  502.27  5031.1  503.77  5051.8  502.74
  5103.6   505.9  5136.5  505.98  5145.1  506.92  5210.7  506.72    5228  507.87
  5319.6  510.04  5324.8  510.92  5438.8  512.81  5456.1  514.36  5570.1  518.88
#Mann= 3 ,-1 , 0
  4429.9     .12       0  5008.3     .07       0  5012.3     .12       0
Bank Sta=5008.3,5012.3
XS Rating Curve= 0 ,0
Exp/Cntr=0.3,0.1

Type RM Length L Ch R = 1 ,19277   ,468,468,468
BEGIN DESCRIPTION:
Rocky Cedar T5 38.0
END DESCRIPTION:
XS GIS Cut Line= 3
      2698375.97      6946660.98        2697776.        6946211.
      2697375.98      6945710.98
#Sta/Elev= 30
  4250.5  519.61  4252.3  519.61  4307.8  517.46    4314  516.11  4328.6  515.37
  4336.9  515.89  4436.9  509.71    4514   508.1  4543.2  505.82  4882.5  500.89
  4928.6     501  4943.2  500.17  4948.5  498.57  4948.7  498.07  4952.5  498.57
  4957.8   500.4  4993.2  499.32  5022.1  500.34  5078.1  499.67  5150.1  501.51
  5156.5  500.89    5307  506.33  5356.6  506.43    5363  507.18  5406.3  506.49
  5435.1  508.66  5519.9  511.03  5548.7  512.85  5604.8  513.45  5640.8  516.21
#Mann= 5 ,-1 , 0
  4250.5     .12       0  4252.3     .05       0  4882.5     .12       0
  4948.5     .07       0  4952.5     .12       0
Bank Sta=4948.5,4952.5
XS Rating Curve= 0 ,0
Exp/Cntr=0.3,0.1

Type RM Length L Ch R = 1 ,18809   ,443,443,443
BEGIN DESCRIPTION:
Rocky Cedar T5 37.0
END DESCRIPTION:
XS GIS Cut Line= 3
      2698475.99      6946460.99        2698026.        6945861.
      2697605.49      6945512.39
#Sta/Elev= 30
  4244.9  516.57  4294.9  514.78  4308.4  513.63  4316.8  511.86  4337.6   511.4
  4352.2  509.94  4416.8  509.06    4473  505.34  4516.8  504.82  4631.3  500.98
  4837.1  498.28  4866.8  499.15  4944.9  496.97  5006.5  496.84  5006.8  496.34
  5010.5  496.84  5059.4  497.79  5065.9  499.15  5094.5   501.3  5139.2  501.75
  5207.8  504.67  5228.7  507.54  5250.8  509.06  5292.7  508.61  5300.3  508.41
  5335.4  511.56  5371.6   510.3  5477.4  514.49    5506  514.19  5541.1  515.34
#Mann= 6 ,-1 , 0
  4244.9     .05       0  4837.1     .12       0  5006.5     .07       0
  5010.5     .12       0  5139.2     .05       0  5292.7     .12       0
Bank Sta=5006.5,5010.5
XS Rating Curve= 0 ,0
Exp/Cntr=0.3,0.1

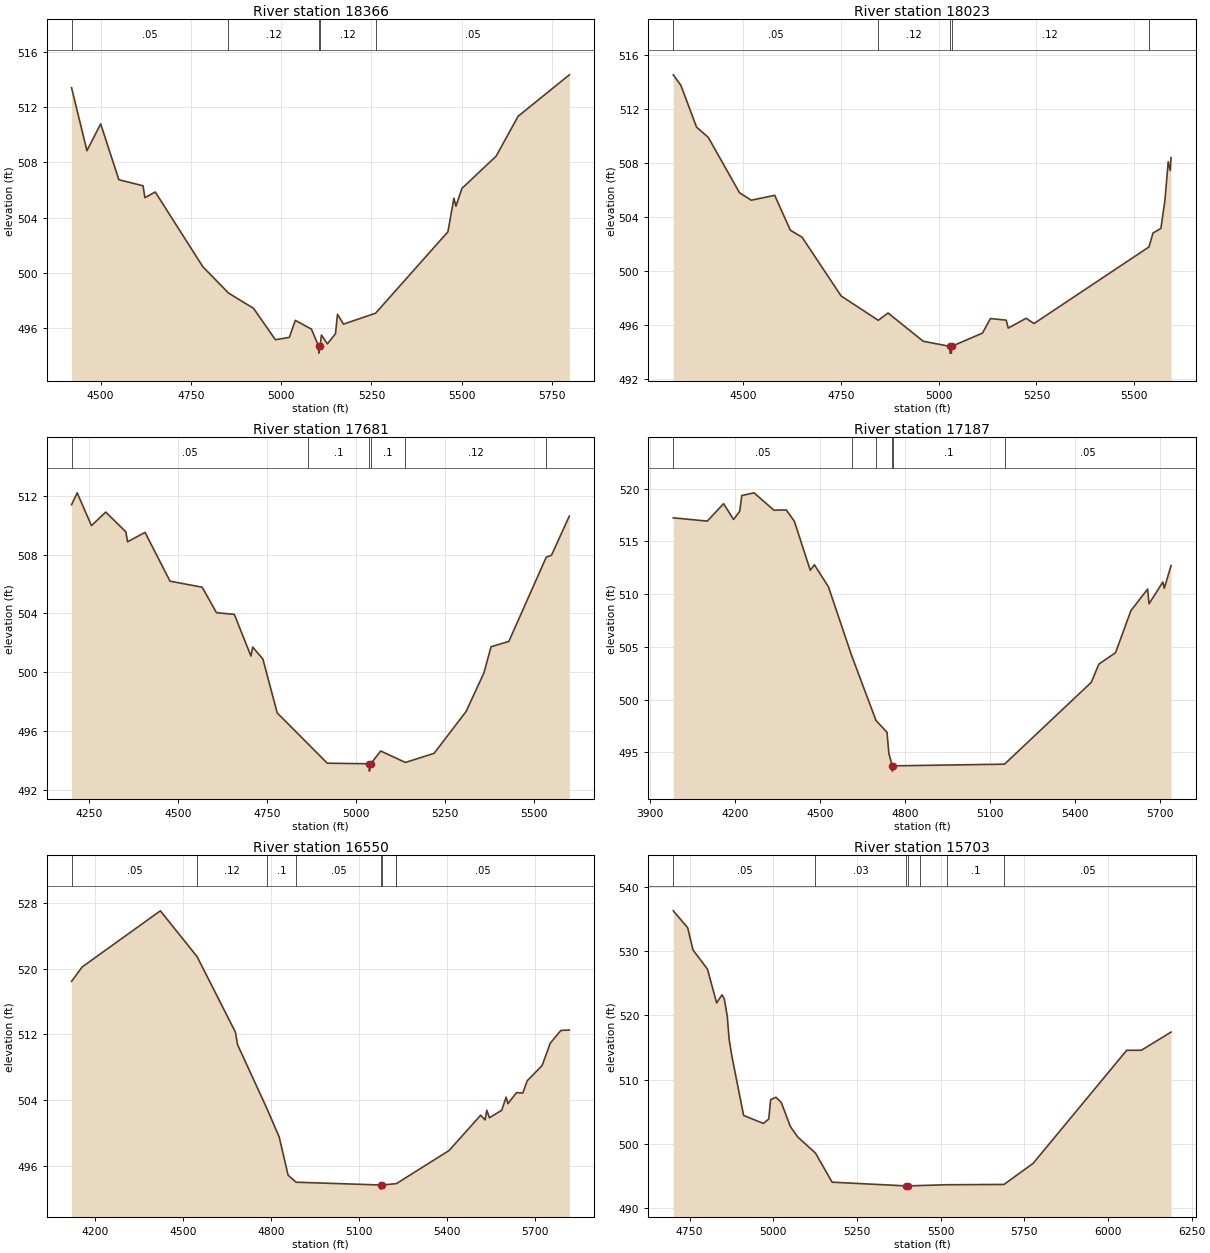
Type RM Length L Ch R = 1 ,18366   ,343,343,343
BEGIN DESCRIPTION:
Rocky Cedar T5 36.0
END DESCRIPTION:
XS GIS Cut Line= 3
        2698476.      6946360.98       2698403.3      6945785.16
      2697692.43      6945422.78
#Sta/Elev= 30
  4419.6   513.4  4462.2  508.84  4500.2  510.78  4550.6  506.74  4617.6   506.3
  4622.7  505.44  4651.4  505.85  4783.2  500.44  4854.1  498.54  4923.6  497.43
    4984  495.16  5022.6  495.33  5039.2  496.56  5083.7  495.93  5103.9  494.69
  5104.2  494.19  5107.9  494.69  5111.5   495.5  5128.1  494.86  5150.4   495.6
    5156     497  5172.6  496.29  5261.5  497.08  5461.7  502.97  5478.3   505.4
  5483.9  504.82  5500.5  506.11  5595.1  508.44  5656.1  511.33  5797.9  514.33
#Mann= 5 ,-1 , 0
  4419.6     .05       0  4854.1     .12       0  5103.9     .07       0
  5107.9     .12       0  5261.5     .05       0
Bank Sta=5103.9,5107.9
XS Rating Curve= 0 ,0
Exp/Cntr=0.3,0.1

Type RM Length L Ch R = 1 ,18023   ,342,342,342
BEGIN DESCRIPTION:
Rocky Cedar T5 35.0
END DESCRIPTION:
XS GIS Cut Line= 3
      2699205.49      6945486.82      2698526.29      6945486.12
       2697940.4      6945385.35
#Sta/Elev= 30
  4320.8  514.52  4340.3  513.74  4380.3  510.65  4410.3  509.89  4490.3  505.79
  4520.3  505.24  4580.3   505.6  4620.3  503.02  4650.3   502.5  4750.3  498.15
  4845.2  496.35  4870.3  496.89  4960.3   494.8  5028.7  494.42    5029  493.92
  5032.5  493.92  5032.7  494.42  5111.9   495.4  5132.2  496.48  5172.7  496.36
  5177.8  495.77  5223.5   496.5  5243.8  496.11    5538  501.78  5548.2  502.81
  5568.5  503.15  5578.7  505.21  5587.2  508.09  5592.3  507.44  5594.5  508.39
#Mann= 5 ,-1 , 0
  4320.8     .05       0  4845.2     .12       0  5028.7     .07       0
  5032.7     .12       0    5538     .05       0
Bank Sta=5028.7,5032.7
XS Rating Curve= 0 ,0
Exp/Cntr=0.3,0.1

Type RM Length L Ch R = 1 ,17681   ,494,494,494
BEGIN DESCRIPTION:
Rocky Cedar T5 34.0
END DESCRIPTION:
XS GIS Cut Line= 3
      2699271.74       6945229.1      2698475.85        6945161.
      2697875.95        6945161.
#Sta/Elev= 30
  4201.2  511.39    4217   512.2  4257.1  509.97  4297.3  510.89  4353.7  509.55
  4358.7  508.87  4407.7  509.51  4477.9  506.19  4568.3  505.78  4608.4  504.05
  4658.6  503.93  4705.3   501.1  4710.3  501.71  4738.9  500.89    4779  497.23
  4864.3  495.16  4919.6  493.81  5037.9  493.77  5038.1  493.27  5041.9  493.77
  5069.9  494.64  5139.2  493.86  5219.9  494.48  5309.9  497.33  5359.9  499.95
  5379.9  501.73  5429.9  502.09    5535  507.82  5549.9  507.96  5599.9  510.62
#Mann= 6 ,-1 , 0
  4201.2     .05       0  4864.3      .1       0  5037.9     .07       0
  5041.9      .1       0  5139.2     .12       0    5535     .05       0
Bank Sta=5037.9,5041.9
XS Rating Curve= 0 ,0
Exp/Cntr=0.3,0.1

Type RM Length L Ch R = 1 ,17187   ,637,637,637
BEGIN DESCRIPTION:
Rocky Cedar T5 33.0
END DESCRIPTION:
XS GIS Cut Line= 3
      2699218.82      6944074.54       2698425.6      6944711.17
      2697699.11      6944840.43
#Sta/Elev= 30
  3982.9  517.23  4102.7  516.92  4160.3  518.57  4195.5  517.07  4217.3  517.86
  4224.3  519.34  4267.5   519.6  4337.9  517.95  4381.1  517.98  4409.7  516.91
  4465.9  512.26  4480.3  512.78  4529.9  510.69  4611.3  504.21  4697.4  498.03
  4736.4   496.9    4743  494.88  4755.2  493.72  4755.4  493.22  4759.2  493.72
  5150.7  493.88  5456.7  501.64  5483.2  503.36  5542.2  504.45  5596.1  508.42
  5655.1  510.47  5660.2  509.08  5709.1  511.15  5714.1  510.55  5737.9  512.71
#Mann= 6 ,-1 , 0
  3982.9     .05       0  4611.3     .12       0  4697.4      .1       0
  4755.2     .05       0  4759.2      .1       0  5150.7     .05       0
Bank Sta=4755.2,4759.2
XS Rating Curve= 0 ,0
Exp/Cntr=0.3,0.1

Type RM Length L Ch R = 1 ,16550   ,847,847,847
BEGIN DESCRIPTION:
Rocky Cedar T5 32.0
END DESCRIPTION:
XS GIS Cut Line= 3
      2699194.83      6943970.11      2698326.09      6944105.96
      2697652.26       6944566.9
#Sta/Elev= 30
  4120.7  518.45  4156.9   520.2  4423.2  527.02  4548.4  521.45  4678.9  512.28
  4686.3  510.75  4785.2  503.08    4828  499.55  4858.4   494.9  4885.8  494.05
  5174.5  493.71  5174.7  493.21  5178.5  493.71  5224.7  493.87  5227.5  493.88
  5406.7   497.9  5514.4  502.19  5529.3  501.63  5535.3  502.79  5544.2  501.88
  5586.1  502.79  5601.1  504.39  5607.1  503.59  5636.9  504.94  5657.9  504.88
  5672.8  506.37  5723.6  508.22  5751.3  510.93  5787.6  512.49  5816.4  512.54
#Mann= 8 ,-1 , 0
  4120.7     .05       0  4548.4     .12       0  4785.2      .1       0
  4885.8     .05       0  5174.5     .03       0  5178.5     .05       0
  5224.7      .1       0  5227.5     .05       0
Bank Sta=5174.5,5178.5
XS Rating Curve= 0 ,0
Exp/Cntr=0.3,0.1

Type RM Length L Ch R = 1 ,15703   ,57,57,57
BEGIN DESCRIPTION:
Rocky Cedar T5 31.0
END DESCRIPTION:
XS GIS Cut Line= 3
      2698718.27      6943244.64      2698314.64      6943474.66
        2697414.      6943958.62
#Sta/Elev= 30
  4701.3  536.24  4744.3  533.61  4760.2  530.15  4803.4  527.18  4830.8  521.92
  4846.6  523.18  4853.5  522.59  4862.5  519.88  4868.2  516.23  4876.6  513.57
  4911.4  504.43  4970.5  503.19  4986.4  503.88  4992.1  506.88    5008  507.26
  5023.8  506.46  5051.2   502.7  5072.8   501.1  5125.8   498.6  5175.7  494.06
  5397.1  493.48  5397.3  492.98  5401.1  493.48  5438.6  493.54  5517.7  493.66
  5689.3  493.71  5776.5     497  6055.7  514.56  6099.6  514.57  6188.3  517.39
#Mann= 7 ,-1 , 0
  4701.3     .05       0  5125.8     .03       0  5397.1     .03       0
  5401.1     .03       0  5438.6     .05       0  5517.7      .1       0
  5689.3     .05       0
Bank Sta=5397.1,5401.1
XS Rating Curve= 0 ,0
Exp/Cntr=0.3,0.1

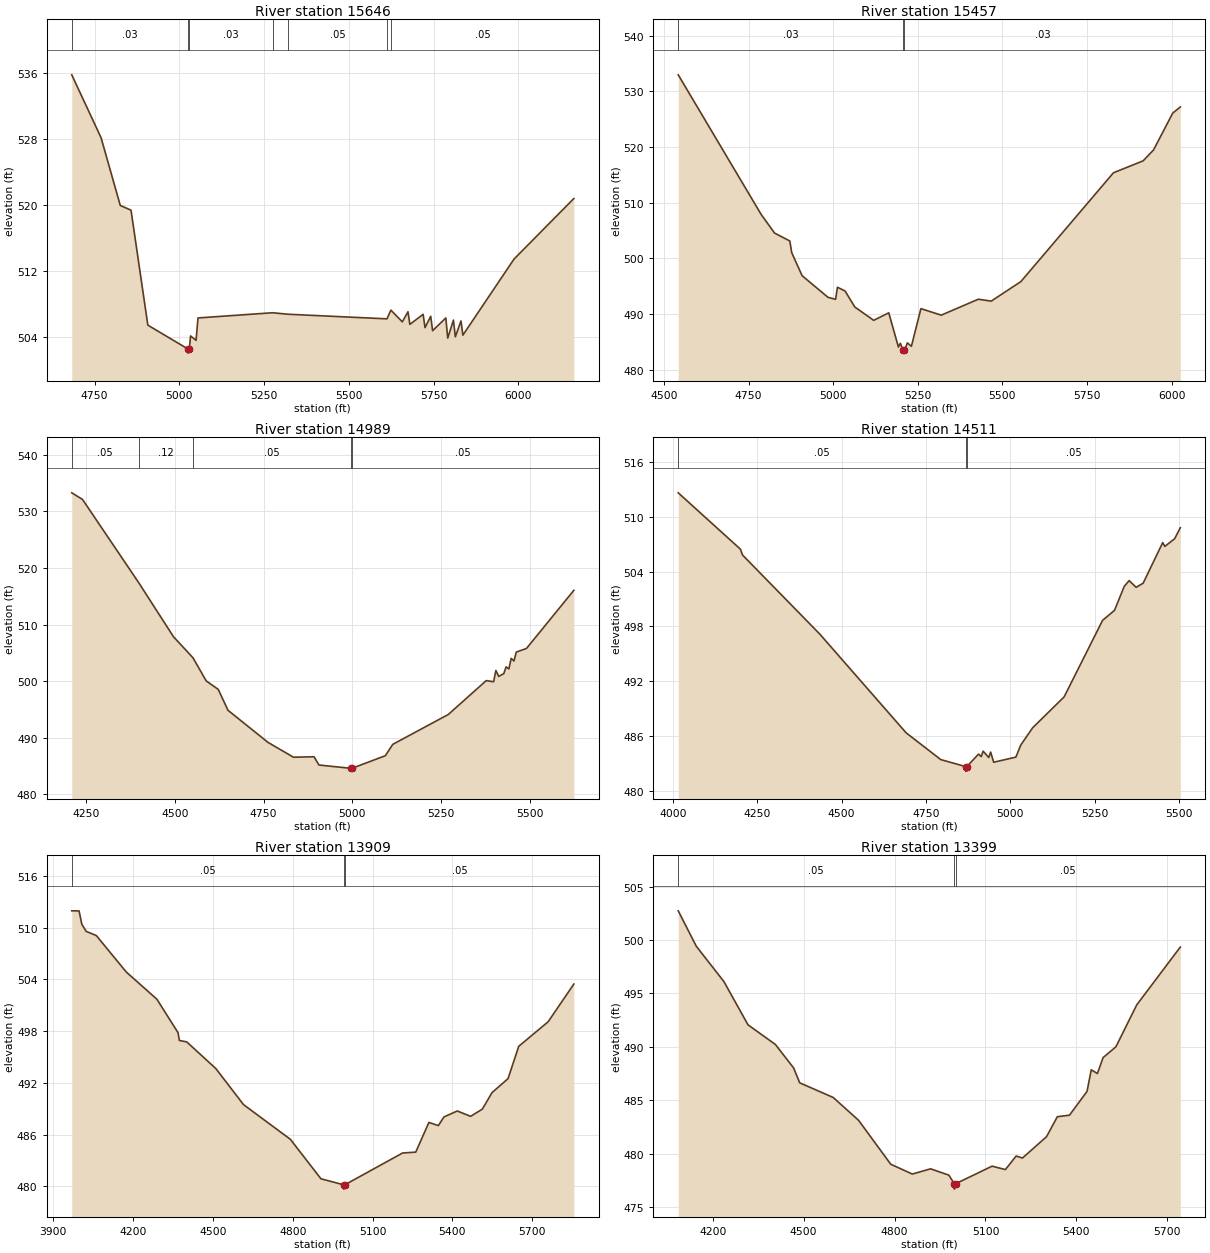
Type RM Length L Ch R = 1 ,15646   ,189,189,189
BEGIN DESCRIPTION:
Rocky Cedar T5 30.0
END DESCRIPTION:
XS GIS Cut Line= 3
       2698692.2       6943212.1      2698338.51      6943400.88
       2697372.8      6943884.82
#Sta/Elev= 30
  4682.7  535.74  4769.1  528.13  4825.8  519.92  4857.5  519.35  4907.1  505.43
  5025.5  502.54  5025.7  502.04  5029.5  502.54  5033.1  504.12  5049.4  503.59
  5055.1   506.3    5275  506.93  5320.3  506.75  5612.6  506.19    5624  507.25
  5657.8  505.83  5674.5  507.05  5680.1  505.52  5719.2  506.74  5724.8  505.13
  5741.6   506.5  5747.2  504.76  5786.2   506.3  5791.8  503.86  5808.6  506.04
  5814.2  504.02  5830.9  505.94  5836.5  504.22  5987.4  513.43  6163.8  520.76
#Mann= 7 ,-1 , 0
  4682.7     .03       0  5025.5     .03       0  5029.5     .03       0
    5275      .1       0  5320.3     .05       0  5612.6      .1       0
    5624     .05       0
Bank Sta=5025.5,5029.5
XS Rating Curve= 0 ,0
Exp/Cntr=0.3,0.1

Type RM Length L Ch R = 1 ,15457   ,468,468,468
BEGIN DESCRIPTION:
Rocky Cedar T5 29.0
END DESCRIPTION:
XS GIS Cut Line= 3
      2698634.84      6943160.05      2698023.77      6943458.64
      2697316.38      6943839.24
#Sta/Elev= 30
  4542.3  532.97  4787.5  507.88    4827  504.55    4872  503.13  4877.6  501.04
  4908.3   496.9  4984.6  493.02  5007.2  492.65  5012.7  494.82  5035.2  494.15
  5064.1  491.27  5119.8  488.88  5164.3  490.23  5192.9  484.07  5198.4  484.76
  5206.8  483.49  5207.1  482.99  5210.8  483.49  5219.4  484.83  5231.2  484.22
  5259.3  490.98  5319.4  489.81  5428.9  492.67  5467.1  492.33  5554.7  495.84
  5828.2  515.38  5915.8  517.52  5946.6  519.48  6003.4   526.1  6025.7   527.2
#Mann= 3 ,-1 , 0
  4542.3     .03       0  5206.8     .03       0  5210.8     .03       0
Bank Sta=5206.8,5210.8
XS Rating Curve= 0 ,0
Exp/Cntr=0.3,0.1

Type RM Length L Ch R = 1 ,14989   ,478,478,478
BEGIN DESCRIPTION:
Mapping XS ea710dad
END DESCRIPTION:
XS GIS Cut Line= 3
      2698615.58      6943005.93      2697843.04      6943179.53
      2697448.06      6943661.31
#Sta/Elev= 30
  4209.2  533.29  4239.5  532.12  4397.5  517.44  4495.8  507.86  4550.8  504.13
    4588  500.05  4621.9  498.55  4649.5  494.85  4762.2  489.18    4834  486.56
    4892  486.64  4905.7  485.18  4994.9   484.6  4995.2   484.1    4999   484.6
  5092.9  486.83  5113.7  488.83  5270.2  494.11  5377.1   500.1  5397.9   499.9
  5404.4  501.89  5412.3  500.84  5426.6  501.33  5433.1  502.53    5441  502.16
  5447.4  504.03  5455.3  503.57  5461.8  505.14  5490.5  505.78    5624  516.06
#Mann= 5 ,-1 , 0
  4209.2     .05       0  4397.5     .12       0  4550.8     .05       0
  4994.9     .03       0    4999     .05       0
Bank Sta=4994.9,4999
XS Rating Curve= 0 ,0
Exp/Cntr=0.3,0.1

Type RM Length L Ch R = 1 ,14511   ,602,602,602
BEGIN DESCRIPTION:
Mapping XS 98598c80
END DESCRIPTION:
XS GIS Cut Line= 3
      2698360.38      6942469.47      2697474.98      6942917.38
      2697170.19      6943308.75
#Sta/Elev= 30
  4015.6   512.6  4199.8  506.45  4206.4   505.8  4435.2  497.17    4691  486.39
  4793.8  483.46  4867.2   482.7  4867.5   482.2    4871   482.2  4871.3   482.7
  4905.8  484.06  4913.8  483.79  4919.4  484.38  4936.1  483.69  4941.7  484.28
  4950.7  483.17  5016.5  483.73    5031  485.05  5066.3  486.94  5159.5  490.31
  5273.5  498.67  5308.8  499.76  5337.7  502.38  5352.2  503.01    5373  502.28
  5393.8  502.73  5451.7  507.16  5458.1  506.75    5487  507.58  5503.9  508.79
#Mann= 3 ,-1 , 0
  4015.6     .05       0  4867.2     .03       0  4871.3     .05       0
Bank Sta=4867.2,4871.3
XS Rating Curve= 0 ,0
Exp/Cntr=0.3,0.1

Type RM Length L Ch R = 1 ,13909   ,510,510,510
BEGIN DESCRIPTION:
Mapping XS aecd6439
END DESCRIPTION:
XS GIS Cut Line= 4
      2698322.19      6942070.16      2697346.51       6942365.3
      2697082.62      6942650.02      2697041.11      6943127.36
#Sta/Elev= 30
  3969.7  511.96  3997.1  511.95  4007.5  510.41  4023.8  509.58    4062  509.09
  4174.7  504.86  4289.6  501.71  4368.9  497.84  4374.1  496.93  4401.8  496.76
  4511.1  493.67  4615.1  489.49  4791.1  485.47    4906  480.89  4991.5  480.19
  4991.8  479.69  4995.7  480.19    5213  483.88  5262.3  483.98  5311.7  487.42
  5347.4  487.06  5368.3  488.06  5418.4  488.75  5468.6  488.13  5512.6  488.97
  5548.9  490.88  5609.1   492.5  5649.3  496.25  5759.7  499.09  5856.4  503.47
#Mann= 3 ,-1 , 0
  3969.7     .05       0  4991.5     .04       0  4995.7     .05       0
Bank Sta=4991.5,4995.7
XS Rating Curve= 0 ,0
Exp/Cntr=0.3,0.1

Type RM Length L Ch R = 1 ,13399   ,599,599,599
BEGIN DESCRIPTION:
Mapping XS 020faae7
END DESCRIPTION:
XS GIS Cut Line= 4
       2698035.3      6941892.86      2697108.23      6941976.19
       2696861.7      6942156.75      2696785.31      6942569.96
#Sta/Elev= 30
  4086.3  502.73  4145.8  499.42  4237.2   496.1  4316.5  492.06  4406.9  490.22
  4467.1  488.02  4487.2  486.63  4597.6  485.26  4681.4  483.12  4787.5  479.01
  4858.7  478.09  4918.9  478.58  4979.2  477.99  4997.1  477.18  4997.5  476.68
  5001.4  477.18  5121.8  478.83  5165.8  478.51  5201.3  479.78  5222.1  479.59
  5301.6  481.59  5337.2  483.46  5377.2   483.6  5435.2  485.83    5449  487.85
  5469.4   487.5  5488.1  488.99  5530.4     490    5599  493.92  5742.9  499.34
#Mann= 3 ,-1 , 0
  4086.3     .05       0  4997.1     .04       0  5001.4     .05       0
Bank Sta=4997.1,5001.4
XS Rating Curve= 0 ,0
Exp/Cntr=0.3,0.1

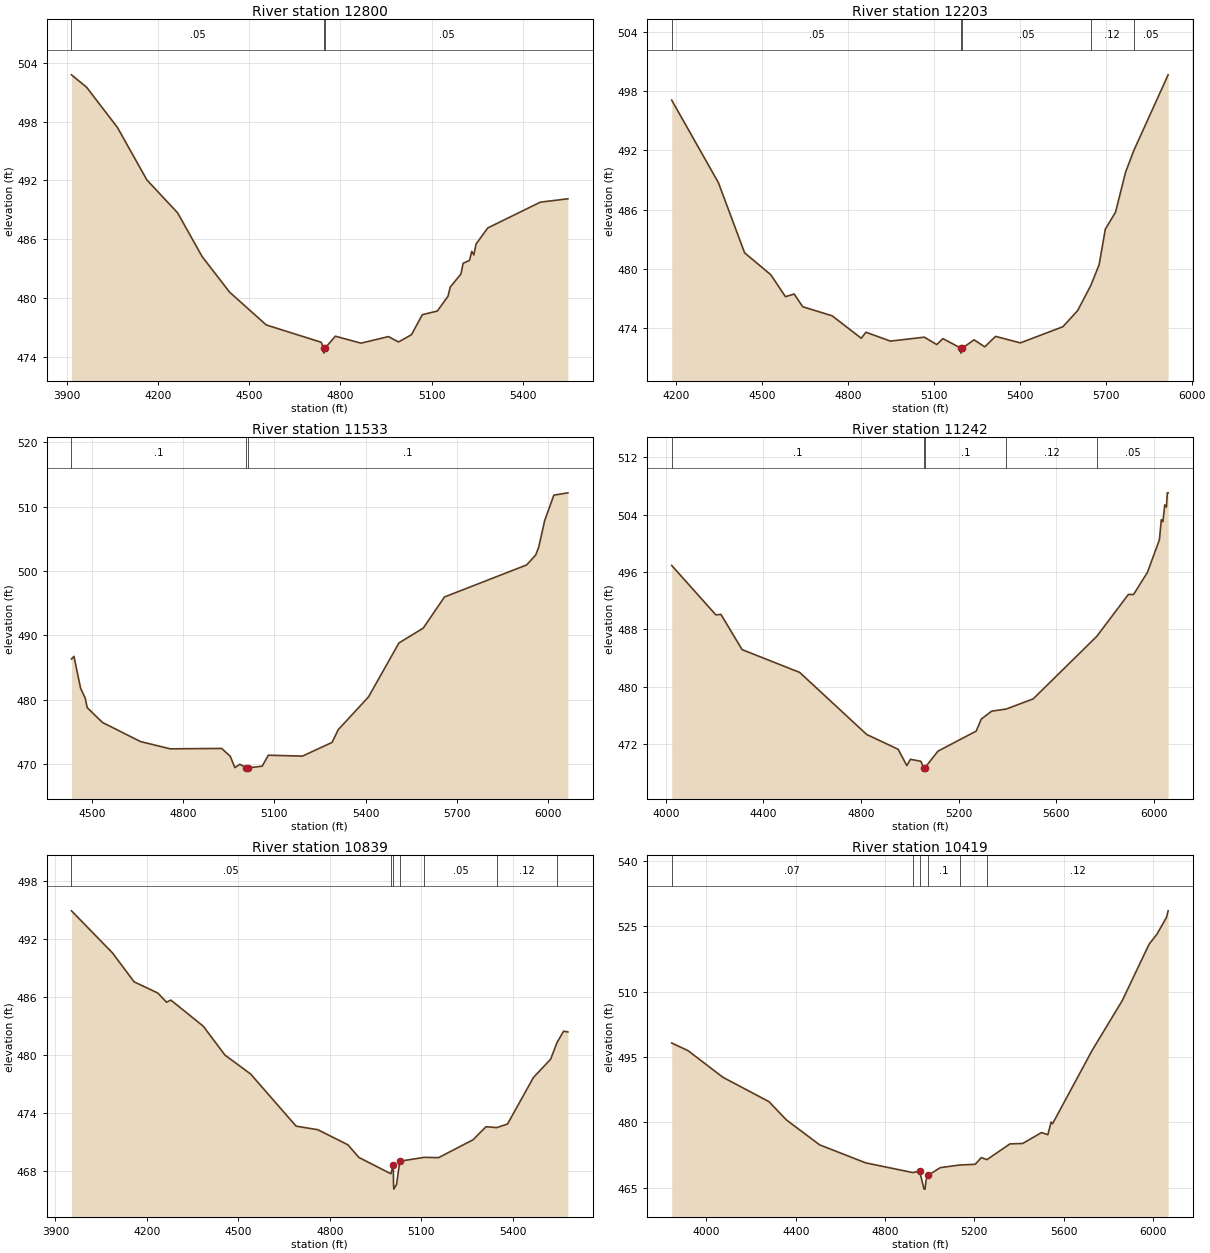
Type RM Length L Ch R = 1 ,12800   ,597,597,597
BEGIN DESCRIPTION:
Mapping XS e3f33c82
END DESCRIPTION:
XS GIS Cut Line= 4
      2698003.69      6941341.47      2696937.74      6941445.63
      2696718.99       6941650.5      2696687.74       6941910.9
#Sta/Elev= 30
  3915.4  502.79  3965.2  501.52  4066.8   497.4  4163.4  492.05  4264.7  488.68
  4345.1  484.22  4435.6  480.58  4556.1  477.23    4737  475.46  4744.9  474.85
  4745.2  474.35  4749.2  474.85  4783.4  476.08  4867.6  475.37    4958  476.04
  4991.3  475.49  5033.8  476.23  5069.5  478.28  5118.8  478.65    5154  480.16
  5161.3   481.1  5196.5  482.43  5203.8  483.53  5224.8  483.83  5232.1  484.75
    5239  484.39  5246.3   485.5  5284.7  487.14  5457.9  489.78  5548.4  490.12
#Mann= 3 ,-1 , 0
  3915.4     .05       0  4744.9     .04       0  4749.2     .05       0
Bank Sta=4744.9,4749.2
XS Rating Curve= 0 ,0
Exp/Cntr=0.3,0.1

Type RM Length L Ch R = 1 ,12203   ,670,670,670
BEGIN DESCRIPTION:
Rocky Cedar T5 23.0
END DESCRIPTION:
XS GIS Cut Line= 3
      2697875.98        6941061.        2697076.        6940911.
      2696275.99        6940461.
#Sta/Elev= 30
  4186.1  497.11  4348.9  488.74  4440.4  481.61    4532  479.38  4582.9  477.16
  4613.4  477.43  4643.1  476.14  4745.7  475.22  4847.4  472.94  4863.5  473.55
  4949.1  472.65  5067.3  473.05  5110.6   472.3  5132.3   472.9  5195.1  471.93
  5195.5  471.43  5199.5  471.93    5241  472.78  5278.2  472.07  5315.9  473.13
  5402.5  472.47  5550.7  474.11  5602.1  475.74  5648.1   478.3    5677  480.39
  5698.9  484.02  5734.3  485.73  5769.7  489.82  5798.4  492.01  5917.9  499.68
#Mann= 5 ,-1 , 0
  4186.1     .05       0  5195.1     .03       0  5199.5     .05       0
  5648.1     .12       0  5798.4     .05       0
Bank Sta=5195.1,5199.5
XS Rating Curve= 0 ,0
Exp/Cntr=0.3,0.1

Type RM Length L Ch R = 1 ,11533   ,291,291,291
BEGIN DESCRIPTION:
Rocky Cedar T5 22.0
END DESCRIPTION:
XS GIS Cut Line= 3
      2697575.97      6940510.98      2697075.82      6940240.93
       2696009.7      6940269.44
#Sta/Elev= 30
  4431.6  486.35  4439.7  486.75  4461.6  481.81    4477  480.25  4483.4  478.79
  4533.8  476.49  4658.9  473.53  4756.6   472.4  4926.1  472.46  4954.3  471.26
  4969.8  469.49    4986  470.01  5006.8  469.44  5007.8  468.94  5012.9  469.44
  5059.8  469.71  5079.9  471.41  5192.3  471.27  5289.9   473.4  5309.9  475.36
    5410  480.47    5510  488.83    5590  491.13  5660.1  495.97  5930.2  500.93
  5960.2  502.46  5970.2  503.66  5990.2  507.85  6020.2  511.77  6066.5  512.13
#Mann= 3 ,-1 , 0
  4431.6      .1       0  5006.8     .04       0  5012.9      .1       0
Bank Sta=5006.8,5012.9
XS Rating Curve= 0 ,0
Exp/Cntr=0.3,0.1

Type RM Length L Ch R = 1 ,11242   ,403,403,403
BEGIN DESCRIPTION:
Rocky Cedar T5 21.0
END DESCRIPTION:
XS GIS Cut Line= 3
      2698026.04      6940561.03        2697226.        6940011.
      2696425.99      6939310.99
#Sta/Elev= 30
  4024.5  496.93  4205.2  490.04  4226.2   490.1  4312.8  485.19  4548.8  482.01
  4823.5  473.35  4952.1  471.29  4987.9  469.01  5002.5  469.89  5045.2  469.62
  5056.3  468.74  5057.3  468.24  5062.6  468.74  5115.4  471.03    5272  473.82
  5292.9   475.5  5335.6  476.61  5395.1   476.9  5505.5  478.32  5765.8  487.03
  5895.6  492.89  5916.5  492.87  5973.4  495.95  6022.8  500.52  6030.4  503.31
    6037  503.03  6044.6  505.38  6051.3  505.07  6055.1  507.06  6058.4  507.06
#Mann= 5 ,-1 , 0
  4024.5      .1       0  5056.3     .04       0  5062.6      .1       0
  5395.1     .12       0  5765.8     .05       0
Bank Sta=5056.3,5062.6
XS Rating Curve= 0 ,0
Exp/Cntr=0.3,0.1

Type RM Length L Ch R = 1 ,10839   ,420,420,420
BEGIN DESCRIPTION:
Rocky Cedar T5 20.0
END DESCRIPTION:
XS GIS Cut Line= 3
      2698126.01      6940361.01        2697326.        6939661.
      2696926.01      6939261.01
#Sta/Elev= 30
  3952.6  494.89  4086.9  490.54  4158.1  487.54  4235.9  486.38  4264.4  485.43
  4278.6  485.65  4384.9  482.95  4456.1  479.96  4540.6  477.99  4689.6   472.6
  4760.8  472.23  4859.5  470.67  4895.6  469.36  5000.6  467.67  5008.5  468.61
  5009.2  466.58  5010.2  466.08  5019.2  466.58  5029.8  468.97    5110  469.37
  5157.1  469.34  5270.2  471.19  5312.6  472.54  5347.9  472.45  5383.3  472.82
  5468.2  477.64  5524.7  479.53  5545.7  481.26  5567.2  482.43  5581.3  482.35
#Mann= 7 ,-1 , 0
  3952.6     .05       0  5000.6     .12       0  5008.5     .04       0
  5029.8     .12       0    5110     .05       0  5347.9     .12       0
  5545.7     .05       0
Bank Sta=5008.5,5029.8
XS Rating Curve= 0 ,0
Exp/Cntr=0.3,0.1

Type RM Length L Ch R = 1 ,10419   ,164,164,164
BEGIN DESCRIPTION:
Rocky Cedar T5 19.0
END DESCRIPTION:
XS GIS Cut Line= 3
      2698306.96      6940262.54        2697576.        6939361.
      2696775.97      6938660.97
#Sta/Elev= 30
  3844.3  498.19  3917.2  496.45  4073.8  490.32    4280  484.73  4358.3  480.53
    4507  474.81  4713.2  470.68  4924.2  468.45  4954.6  468.79  4974.7  464.65
  4979.1  464.65  4983.4  466.65  4991.3  467.78  5047.2  469.58  5134.8  470.19
  5203.8  470.35  5231.3  471.89  5256.3  471.42  5359.4  475.03  5416.4  475.13
  5500.9  477.64  5529.3  477.15  5543.6  480.04  5550.2  479.66  5727.7  496.51
  5862.5  507.93    5983   520.9  6018.1  523.19  6060.8  527.06    6068  528.54
#Mann= 6 ,-1 , 0
  3844.3     .07       0  4924.2      .1       0  4954.6     .04       0
  4991.3      .1       0  5134.8     .05       0  5256.3     .12       0
Bank Sta=4954.6,4991.3
XS Rating Curve= 0 ,0
Exp/Cntr=0.3,0.1

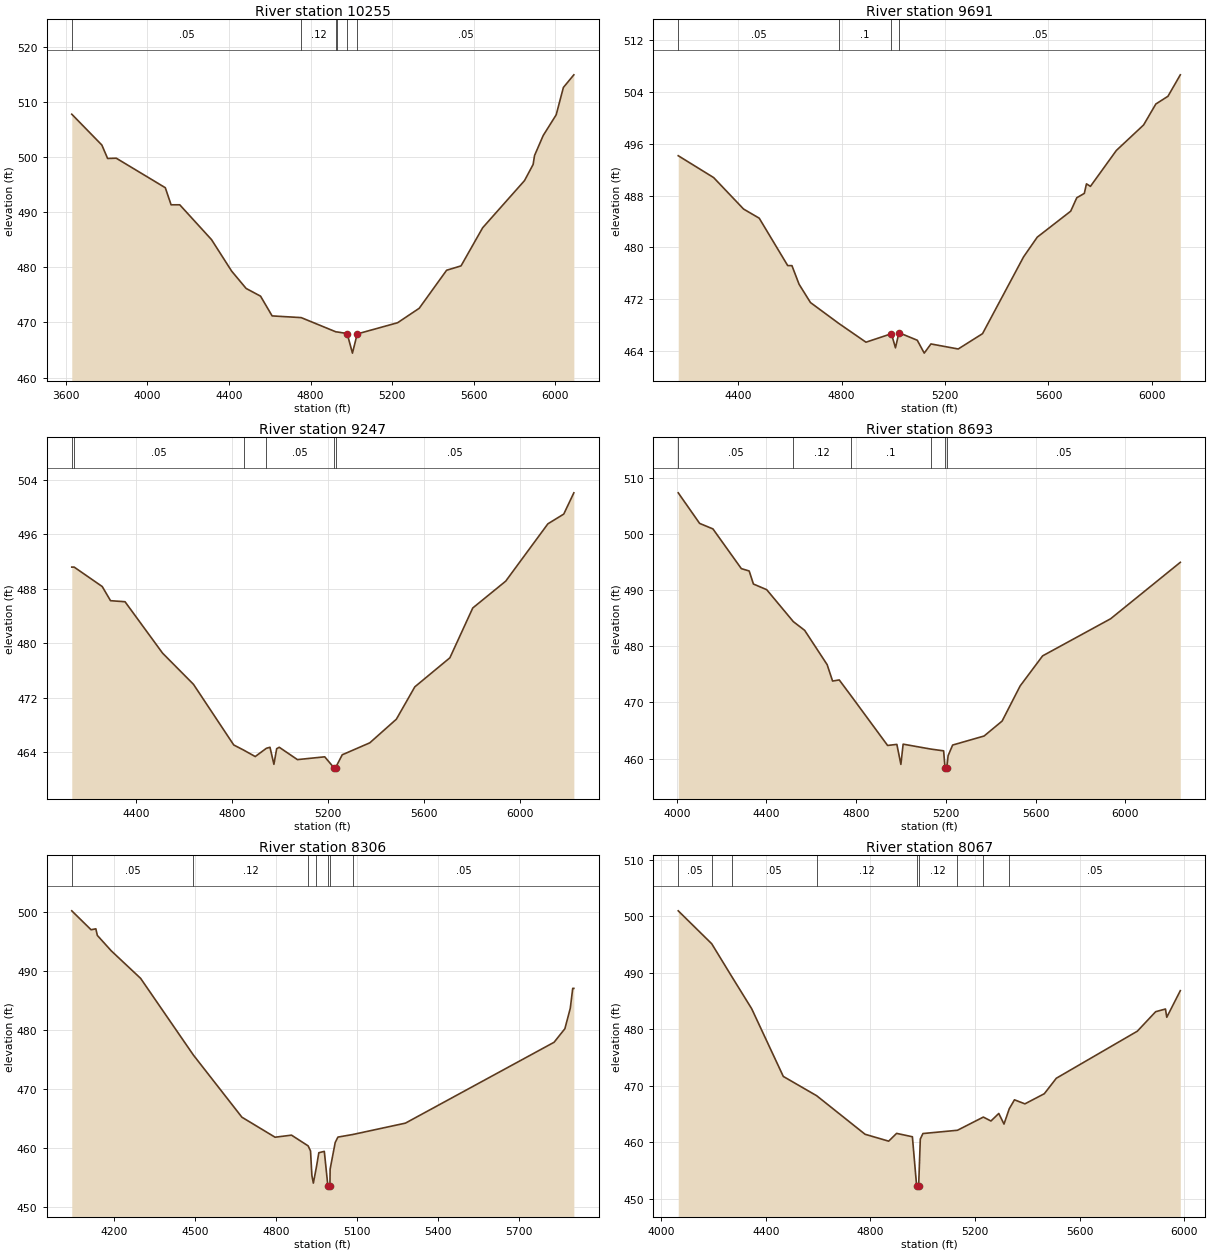
Type RM Length L Ch R = 1 ,10255   ,564,564,564
BEGIN DESCRIPTION:
Rocky Cedar T5 18.0
END DESCRIPTION:
XS GIS Cut Line= 3
      2698641.16      6940284.24      2697709.49      6939278.04
      2696944.13       6938500.4
#Sta/Elev= 30
  3628.7  507.77  3776.2  502.18  3804.5  499.74    3847  499.79  4087.4  494.44
  4115.8  491.34  4158.3  491.34  4314.2  485.02  4412.9  479.31  4483.8  476.17
  4554.6  474.77  4611.3  471.19  4753.9  470.88  4924.8  468.29  4930.6  468.28
  4979.3  467.99  5005.3  464.44  5028.6  467.92  5226.6  469.95  5332.7  472.57
  5467.1  479.47  5537.8  480.26  5643.8  487.17    5849  495.72  5891.4  498.65
  5898.4  500.28  5940.8   503.9  6004.5  507.66  6039.8  512.62  6091.1  514.91
#Mann= 6 ,-1 , 0
  3628.7     .05       0  4753.9     .12       0  4924.8      .1       0
  4930.6      .1       0  4979.3     .04       0  5028.6     .05       0
Bank Sta=4979.3,5028.6
XS Rating Curve= 0 ,0
Exp/Cntr=0.3,0.1

Type RM Length L Ch R = 1 ,9691    ,444,444,444
BEGIN DESCRIPTION:
Mapping XS 5f18fa11
END DESCRIPTION:
XS GIS Cut Line= 3
      2698486.94      6939623.09      2698104.99      6938898.24
      2697071.98      6938459.86
#Sta/Elev= 30
  4168.3  494.17  4305.2  490.79    4421  485.92  4481.4  484.51  4591.6  477.18
    4608  477.17  4635.6  474.29  4679.7  471.46  4788.6  468.25  4894.3  465.33
  4992.7  466.64  5008.3  464.46  5021.8   466.8  5092.7  465.63  5119.6  463.64
  5145.5  465.06    5251  464.28    5345  466.65  5503.9  478.54  5556.7  481.58
  5685.9  485.59  5709.5  487.67  5738.6  488.34  5746.9  489.82  5762.3  489.43
  5862.4  494.98  5967.9  498.93  6015.2  502.17    6062  503.36  6109.8  506.68
#Mann= 4 ,-1 , 0
  4168.3     .05       0  4788.6      .1       0  4992.7     .04       0
  5021.8     .05       0
Bank Sta=4992.7,5021.8
XS Rating Curve= 0 ,0
Exp/Cntr=0.3,0.1

Type RM Length L Ch R = 1 ,9247    ,554,554,554
BEGIN DESCRIPTION:
Mapping XS a6d916b4
END DESCRIPTION:
XS GIS Cut Line= 3
      2698759.51      6939335.76      2698370.61      6938554.49
      2697200.73      6938203.87
#Sta/Elev= 30
  4131.4  491.18  4141.4  491.18  4258.4  488.33  4293.1  486.25  4353.5   486.1
  4510.2  478.55    4639  473.98  4806.9  465.08  4848.1  464.33  4896.5  463.38
  4943.1  464.59  4958.1  464.74  4974.5  462.24    4986  464.53  4996.8  464.74
  5072.6  462.93  5186.4  463.34  5224.8  461.74  5225.9  461.24  5231.5  461.74
  5259.5  463.64  5374.3  465.39  5485.2  468.86  5562.2  473.61  5708.4  477.87
  5803.8  485.18  5941.3  489.12  6117.1  497.53  6183.3  498.96  6225.4  502.08
#Mann= 6 ,-1 , 0
  4131.4     .12       0  4141.4     .05       0  4848.1     .12       0
  4943.1     .05       0  5224.8     .04       0  5231.5     .05       0
Bank Sta=5224.8,5231.5
XS Rating Curve= 0 ,0
Exp/Cntr=0.3,0.1

Type RM Length L Ch R = 1 ,8693    ,387,387,387
BEGIN DESCRIPTION:
Mapping XS 4663edee
END DESCRIPTION:
XS GIS Cut Line= 3
      2699549.59      6938481.39      2698646.83      6938121.16
      2697383.84      6938021.33
#Sta/Elev= 30
  4006.8   507.3  4102.2  501.86  4161.5  500.88  4288.2  493.81  4323.2  493.39
  4342.1  491.07  4401.4  490.06  4520.2  484.37  4570.5  482.83  4670.9  476.72
  4695.1   473.8  4724.8     474  4778.6  471.12  4940.4  462.34  4981.7  462.53
  4999.7  458.97  5009.7  462.57  5133.9  461.69  5190.3  461.38  5196.7  458.27
  5197.8  457.77  5203.9  458.27  5210.3  460.52  5230.4  462.41  5370.8  464.02
  5451.1  466.68  5531.3  472.92  5631.6  478.28  5935.1  484.89  6245.7  494.93
#Mann= 6 ,-1 , 0
  4006.8     .05       0  4520.2     .12       0  4778.6      .1       0
  5133.9     .05       0  5196.7     .07       0  5203.9     .05       0
Bank Sta=5196.7,5203.9
XS Rating Curve= 0 ,0
Exp/Cntr=0.3,0.1

Type RM Length L Ch R = 1 ,8306    ,239,239,239
BEGIN DESCRIPTION:
Mapping XS 704d6669
END DESCRIPTION:
XS GIS Cut Line= 4
      2699468.04      6938104.68      2698863.84      6937830.36
      2698572.17      6937785.22      2697672.83      6937795.63
#Sta/Elev= 30
  4044.5  500.12    4116  496.92  4133.6  497.08  4139.1  495.97  4190.7  493.36
  4299.3  488.71  4494.5  475.76  4674.2  465.25  4796.9  461.87  4857.7  462.22
  4919.2  460.41  4928.1  459.55  4933.1  455.41  4938.6  454.12  4950.2  456.91
  4958.8  459.25  4979.1  459.48  4992.4   453.6  4993.6   453.1  4999.9   453.6
  5000.6  456.47  5019.4  460.97  5029.4  461.89  5084.6  462.33  5279.4  464.25
  5829.4  477.91  5869.4   480.2  5889.4  483.65  5898.5  487.02  5902.6  487.02
#Mann= 7 ,-1 , 0
  4044.5     .05       0  4494.5     .12       0  4919.2      .1       0
  4950.2     .12       0  4992.4     .07       0  4999.9     .12       0
  5084.6     .05       0
Bank Sta=4992.4,4999.9
XS Rating Curve= 0 ,0
Exp/Cntr=0.3,0.1

Type RM Length L Ch R = 1 ,8067    ,531,531,531
BEGIN DESCRIPTION:
Mapping XS f3873806
END DESCRIPTION:
XS GIS Cut Line= 3
      2699554.86      6937764.39      2698613.84      6937646.33
      2697641.66      6937667.16
#Sta/Elev= 30
  4064.6  500.99  4192.6  495.16  4268.8  489.39  4345.6  483.64  4466.6  471.64
  4594.3  468.22  4779.4  461.39  4869.7  460.17    4900  461.55  4960.4  460.95
  4976.8  452.17    4978  451.67  4984.3  452.17  4990.7  460.55  5000.7  461.52
  5132.8   462.1  5231.9  464.44  5260.9  463.74  5290.9  465.08  5310.9   463.2
    5331  465.91  5350.9   467.5  5390.9  466.78  5465.2  468.58    5511  471.32
    5821  479.66    5891  483.11  5928.6  483.59  5933.6  482.13  5985.4  486.84
#Mann= 9 ,-1 , 0
  4064.6     .05       0  4192.6     .12       0  4268.8     .05       0
  4594.3     .12       0  4976.8     .07       0  4984.3     .12       0
  5132.8      .1       0  5231.9     .12       0    5331     .05       0
Bank Sta=4976.8,4984.3
XS Rating Curve= 0 ,0
Exp/Cntr=0.3,0.1