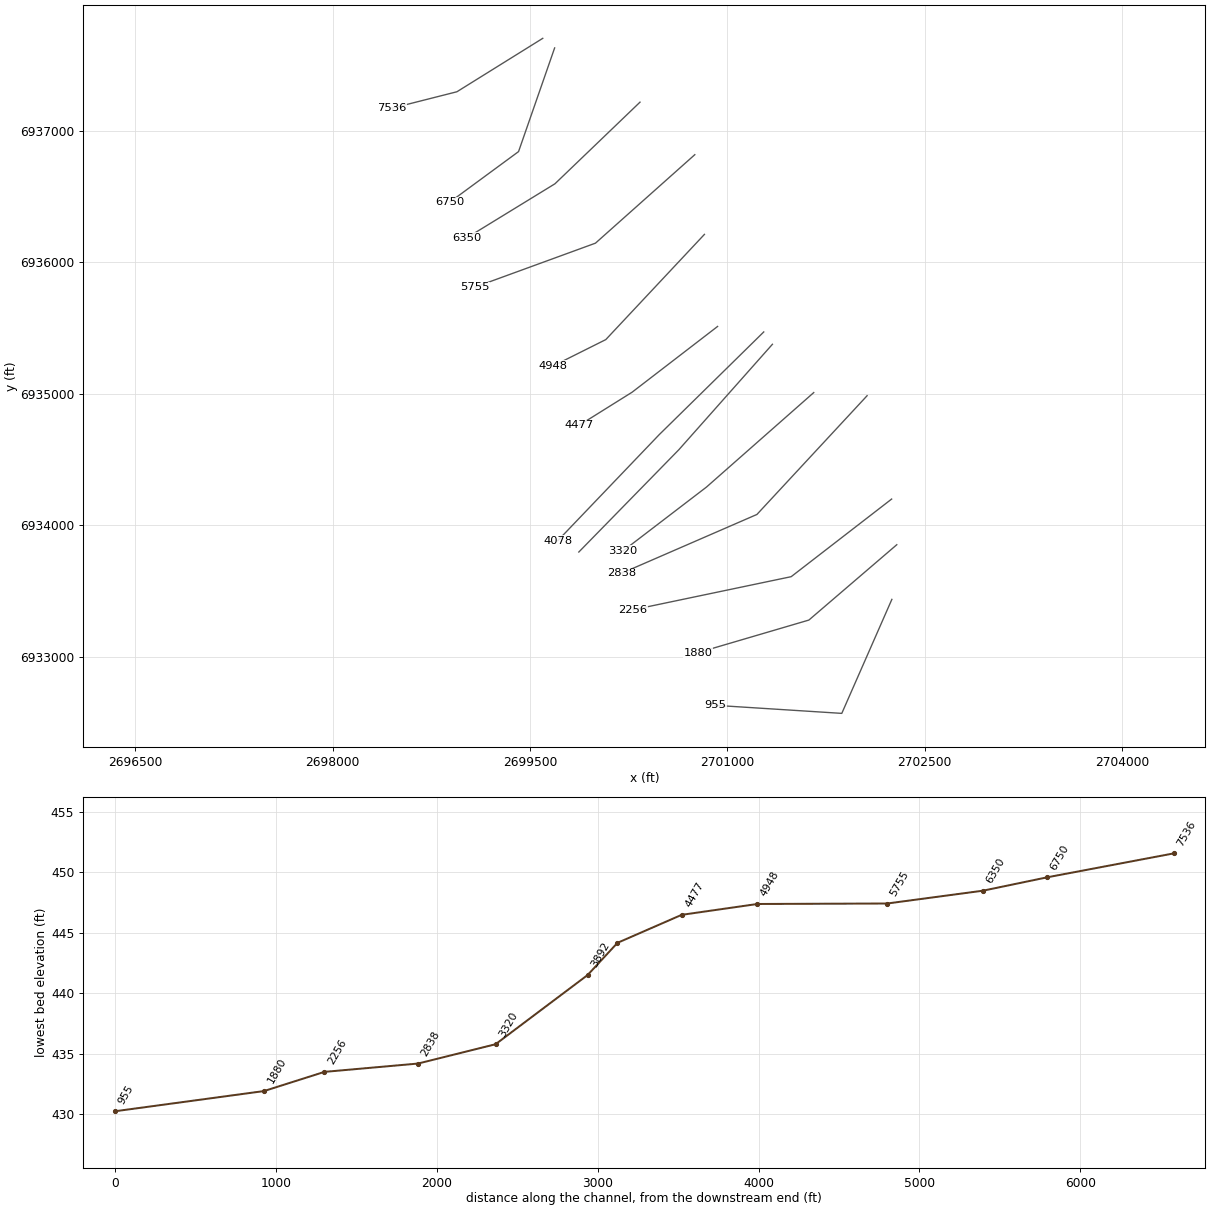
HEC-RAS study Rocky Cedar T5.prj: Rocky Cedar T5 Base Level Engineering

--- Rocky Cedar T5.g01 (geometry) --- (continued)

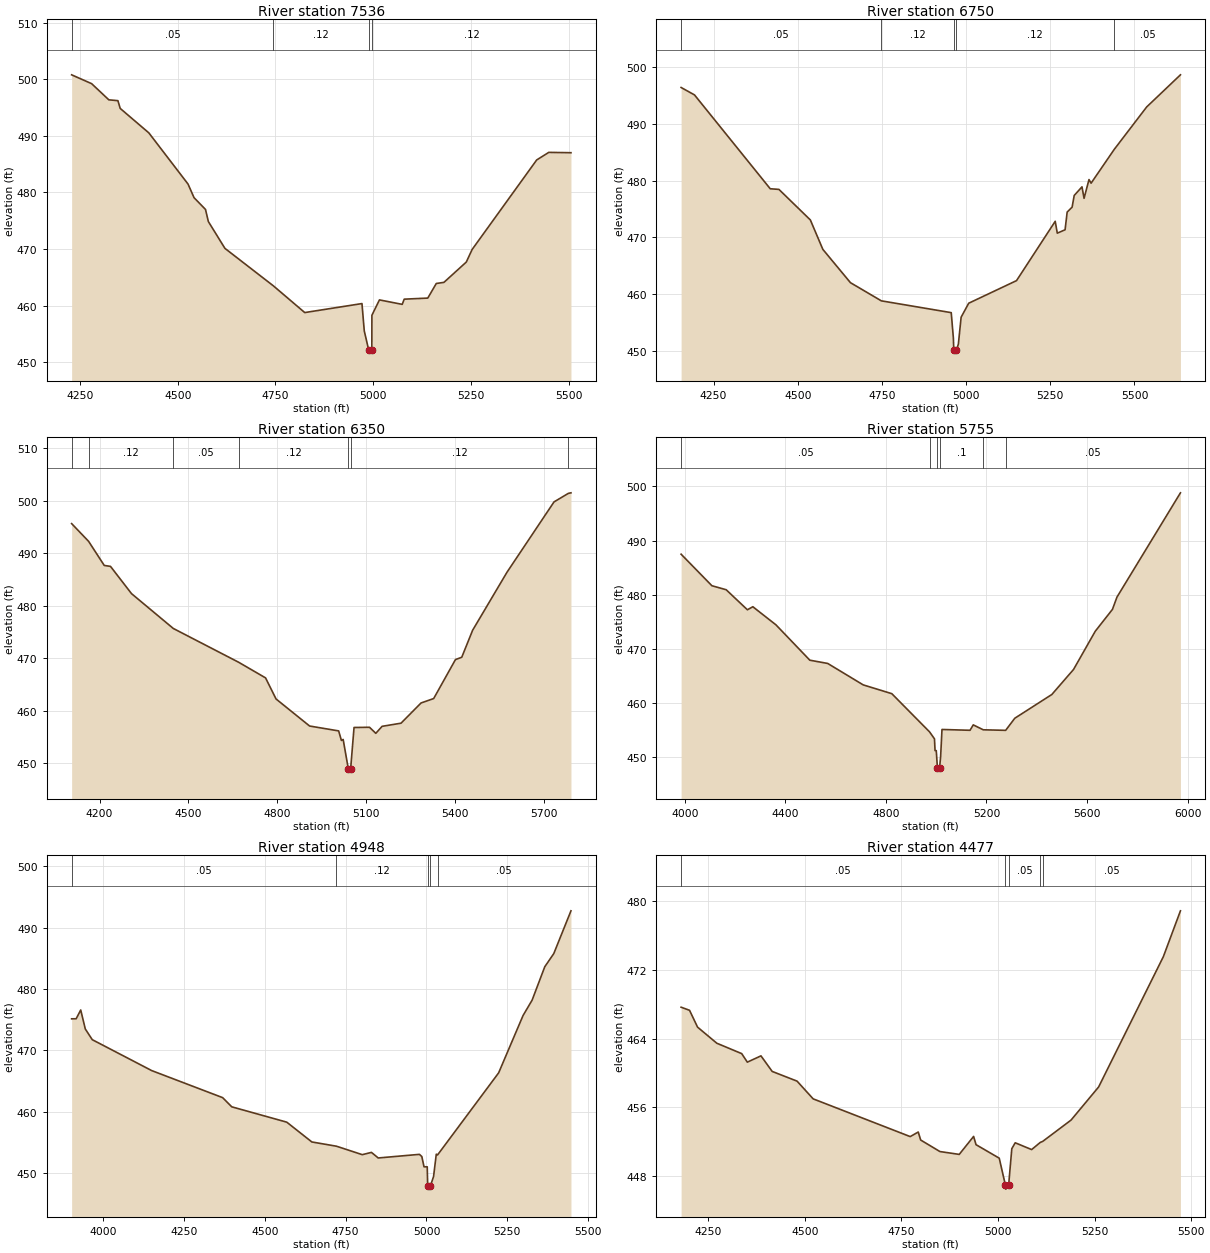
Type RM Length L Ch R = 1 ,7536    ,786,786,786
BEGIN DESCRIPTION:
Mapping XS bf1c37fa
END DESCRIPTION:
XS GIS Cut Line= 3
       2699596.8      6937701.52      2698944.05      6937295.29
      2698450.98      6937170.28
#Sta/Elev= 30
  4228.6  500.78  4279.7  499.22  4323.8  496.36    4347  496.21  4352.9  494.84
  4426.1  490.52  4526.4  481.47  4541.8  479.06  4571.1  476.98  4578.4  474.84
  4620.8   470.1    4745  463.46    4825  458.75  4971.4  460.34  4977.3   455.5
  4988.8  452.08  4989.9  451.58  4996.6  452.08  4996.8  458.27  5016.1  460.99
  5074.4   460.2  5079.5  461.12  5139.8  461.31  5161.5  463.89  5181.1  464.09
  5238.3  467.68  5253.3  469.91  5418.4  485.73  5449.3  487.07  5506.1  487.01
#Mann= 4 ,-1 , 0
  4228.6     .05       0    4745     .12       0  4988.8     .07       0
  4996.6     .12       0
Bank Sta=4988.8,4996.6
XS Rating Curve= 0 ,0
Exp/Cntr=0.3,0.1

Type RM Length L Ch R = 1 ,6750    ,400,400,400
BEGIN DESCRIPTION:
Mapping XS ec102487
END DESCRIPTION:
XS GIS Cut Line= 3
      2699687.11      6937628.62       2699412.8      6936840.43
      2698890.42      6936456.43
#Sta/Elev= 30
  4153.7  496.39  4193.5  495.08  4418.4  478.55  4444.2  478.44  4537.5  473.06
  4574.7  467.87  4656.6  462.01  4748.3  458.81  4955.9  456.73  4962.3  452.22
  4963.5   450.1  4964.7   449.6  4971.5   450.1  4977.1   451.2  4985.3  455.93
  5007.8  458.39  5149.8  462.37  5264.7  472.82  5270.9  470.73    5294  471.33
  5300.2  474.45  5314.9  475.31  5321.1  477.37  5344.2  478.89  5350.4  476.87
    5365  480.17  5371.2  479.53  5439.9  485.48  5536.3  492.96  5636.6  498.62
#Mann= 5 ,-1 , 0
  4153.7     .05       0  4748.3     .12       0  4963.5     .07       0
  4971.5     .12       0  5439.9     .05       0
Bank Sta=4963.5,4971.5
XS Rating Curve= 0 ,0
Exp/Cntr=0.3,0.1

Type RM Length L Ch R = 1 ,6350    ,595,595,595
BEGIN DESCRIPTION:
Mapping XS a047334a
END DESCRIPTION:
XS GIS Cut Line= 3
      2700336.18      6937216.35      2699689.48      6936595.69
      2699016.73      6936183.37
#Sta/Elev= 30
  4105.6  495.63  4162.9  492.25  4215.7  487.66  4236.8  487.48  4307.6   482.3
  4448.7  475.66  4669.1  469.23  4760.1  466.25  4795.6  462.23  4908.8  457.08
  5006.9  456.15  5016.2  454.33  5022.1  454.52  5039.3  448.99  5040.5  448.49
  5047.4  448.99  5058.8   456.8    5111  456.84  5132.3  455.69  5153.5  457.02
  5217.4  457.62    5285  461.47  5327.6  462.31  5401.1  469.73  5422.4  470.18
  5459.1  475.32  5575.2  486.38  5733.8  499.76  5782.3  501.39    5791  501.49
#Mann= 7 ,-1 , 0
  4105.6     .05       0  4162.9     .12       0  4448.7     .05       0
  4669.1     .12       0  5039.3     .07       0  5047.4     .12       0
  5782.3     .05       0
Bank Sta=5039.3,5047.4
XS Rating Curve= 0 ,0
Exp/Cntr=0.3,0.1

Type RM Length L Ch R = 1 ,5755    ,807,807,807
BEGIN DESCRIPTION:
Mapping XS a8a72d38
END DESCRIPTION:
XS GIS Cut Line= 3
      2700752.82      6936817.03      2699997.64       6936144.3
      2699081.87      6935810.12
#Sta/Elev= 30
  3985.4  487.48  4107.8  481.66  4164.6  480.92  4249.1  477.22  4270.8  477.78
  4362.8  474.43  4497.4  467.91  4568.5  467.31  4709.8  463.35  4823.5  461.73
  4973.6  454.68  4993.2  453.39  4995.5  451.22  5000.3  451.22  5005.1  447.93
  5006.3  447.43  5013.3  447.93  5017.7  450.12  5023.1  455.12  5134.6  454.97
  5147.5  455.97  5187.1  455.06  5276.4  454.96  5312.6  457.19  5460.1  461.58
  5546.4   466.2  5632.7  473.25  5701.1  477.29  5719.1  479.56  5971.6  498.81
#Mann= 6 ,-1 , 0
  3985.4     .05       0  4973.6      .1       0  5005.1     .07       0
  5013.3      .1       0  5187.1     .12       0  5276.4     .05       0
Bank Sta=5005.1,5013.3
XS Rating Curve= 0 ,0
Exp/Cntr=0.3,0.1

Type RM Length L Ch R = 1 ,4948    ,471,471,471
BEGIN DESCRIPTION:
Rocky Cedar T5 7.0
END DESCRIPTION:
XS GIS Cut Line= 3
      2700826.03      6936211.03        2700076.        6935411.
      2699676.03      6935211.02
#Sta/Elev= 30
    3903  475.16    3917  475.17  3931.1   476.6  3945.3   473.5  3966.8  471.76
  4150.5  466.72  4369.8  462.31  4398.1  460.81  4568.1  458.31  4645.7  455.08
  4721.7  454.39  4801.6  453.01  4829.9  453.38  4850.9  452.47  4978.4  453.06
  4985.7   452.7  4992.5  451.03  5002.4  451.03  5003.8  447.89    5005  447.39
  5012.2  447.89    5022  449.45  5030.4  453.09  5034.3  452.96  5223.2  466.35
  5298.7   475.7  5326.7  478.21  5365.8  483.65  5393.7   485.8  5446.8  492.77
#Mann= 5 ,-1 , 0
    3903     .05       0  4721.7     .12       0  5003.8     .07       0
  5012.2     .12       0  5034.3     .05       0
Bank Sta=5003.8,5012.2
XS Rating Curve= 0 ,0
Exp/Cntr=0.3,0.1

Type RM Length L Ch R = 1 ,4477    ,399,399,399
BEGIN DESCRIPTION:
Rocky Cedar T5 6.0
END DESCRIPTION:
XS GIS Cut Line= 3
      2700926.03      6935511.02        2700276.        6935011.
        2699876.        6934761.
#Sta/Elev= 30
  4179.9  467.65  4201.7  467.29  4222.5  465.33  4272.3  463.46  4336.7  462.25
  4351.2  461.26  4386.5  461.99  4415.5  460.18  4479.9  459.05  4521.5  456.99
  4772.6   452.6  4793.4  453.13  4799.7   452.2  4849.5  450.86  4899.4  450.53
  4936.6  452.62  4942.9  451.66  5002.9  450.09  5018.7  446.99  5019.9  446.49
  5027.3  446.99  5035.4  451.19  5044.2  451.88  5086.7  451.09  5109.3  451.93
  5115.3  452.04  5188.7  454.52    5260  458.37  5427.5  473.53  5471.7  478.86
#Mann= 5 ,-1 , 0
  4179.9     .05       0  5018.7     .04       0  5027.3     .05       0
  5109.3     .12       0  5115.3     .05       0
Bank Sta=5018.7,5027.3
XS Rating Curve= 0 ,0
Exp/Cntr=0.3,0.1

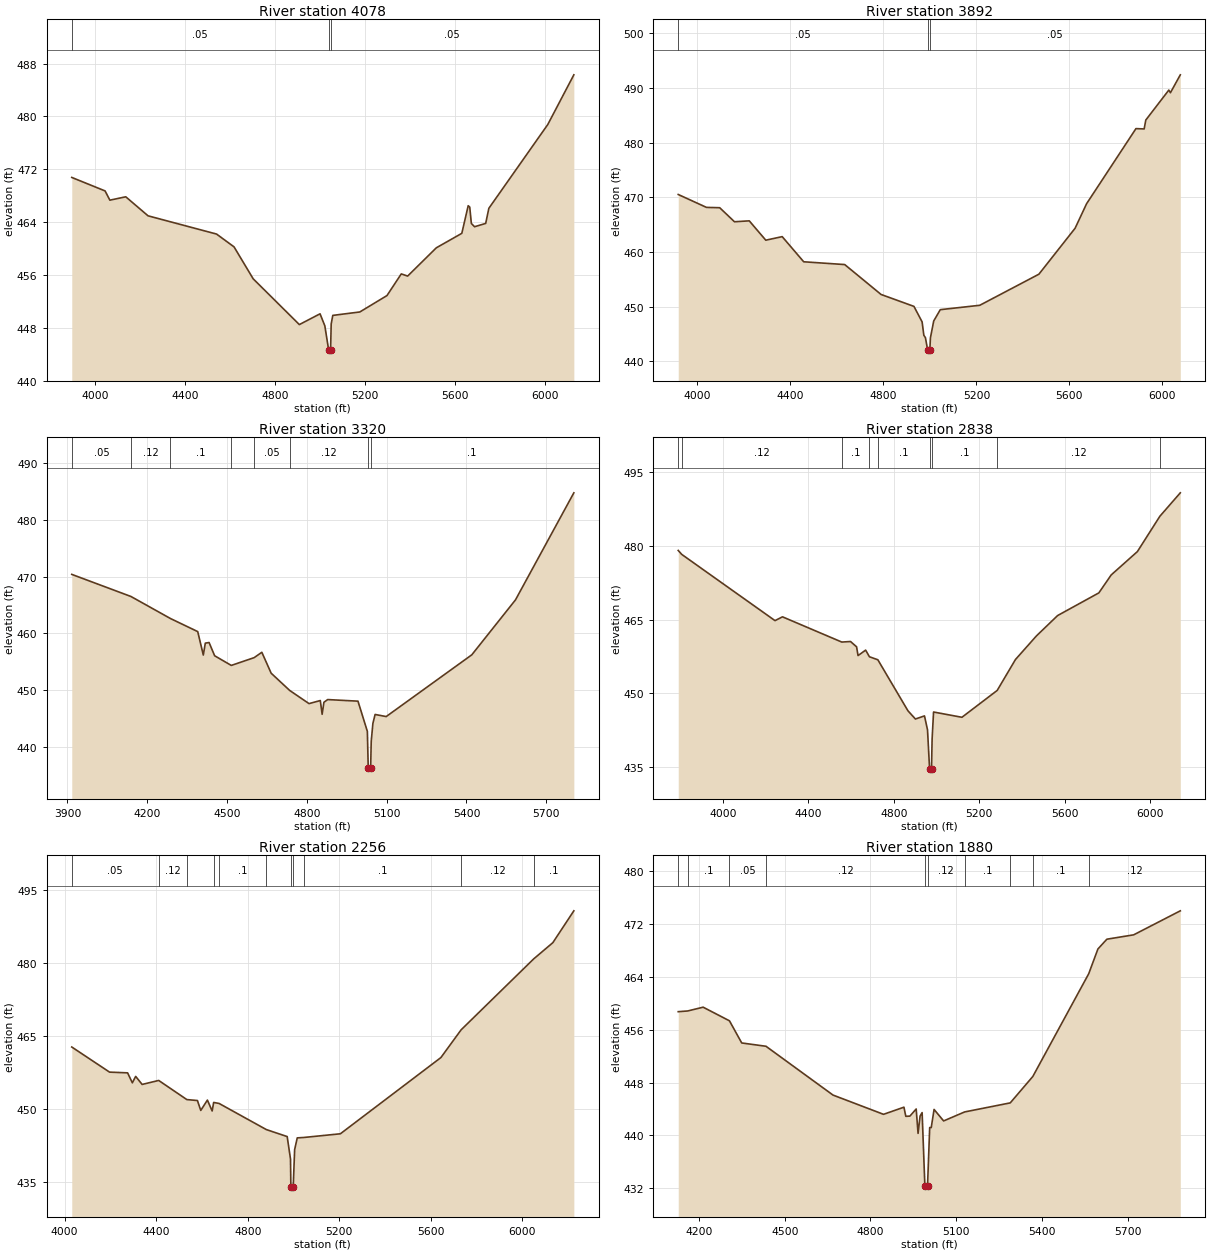
Type RM Length L Ch R = 1 ,4078    ,186,186,186
BEGIN DESCRIPTION:
Mapping XS 9d57e1ab
END DESCRIPTION:
XS GIS Cut Line= 3
      2701276.95      6935469.27      2700481.78        6934688.
      2699710.95      6933882.44
#Sta/Elev= 30
  3897.4  470.76  4045.3  468.72  4066.6  467.32  4137.2  467.83  4236.2  464.95
  4540.4  462.19  4618.1  460.25    4703  455.42  4908.1  448.49    5000  450.12
  5021.3   448.3  5038.1  444.67  5039.3  444.17  5046.8  444.67  5049.5  448.59
  5056.6  449.88  5176.7   450.4  5297.2  452.88  5360.7  456.16    5389  455.83
  5516.4  460.11  5629.6   462.3  5657.9  466.48  5664.8  466.27    5672  463.79
  5686.2   463.3  5735.6   463.8  5749.7  466.09  6011.4  478.77  6127.1  486.29
#Mann= 3 ,-1 , 0
  3897.4     .05       0  5038.1     .04       0  5046.8     .05       0
Bank Sta=5038.1,5046.8
XS Rating Curve= 0 ,0
Exp/Cntr=0.3,0.1

Type RM Length L Ch R = 1 ,3892    ,572,572,572
BEGIN DESCRIPTION:
Mapping XS 9d11b866
END DESCRIPTION:
XS GIS Cut Line= 3
      2701342.91      6935375.51      2700631.09      6934573.41
      2699871.05      6933796.02
#Sta/Elev= 30
  3917.6  470.52  4039.1  468.16    4096   468.1  4159.6  465.53  4223.1   465.7
  4294.2  462.16  4364.8  462.81  4457.3  458.21  4633.7   457.7  4790.1  452.23
  4931.5  450.05  4966.6  447.21  4974.1  444.76  4980.8  444.34  4990.8     442
  4992.1   441.5  4999.7     442  5002.4   444.3  5016.5  447.38  5044.8  449.45
  5214.6  450.25    5469  455.94  5624.6  464.34  5674.2  468.84  5886.4  482.57
  5921.7  482.51  5928.8  484.14  6027.8  489.62  6034.8  489.14  6077.2  492.41
#Mann= 3 ,-1 , 0
  3917.6     .05       0  4990.8     .03       0  4999.7     .05       0
Bank Sta=4990.8,4999.7
XS Rating Curve= 0 ,0
Exp/Cntr=0.3,0.1

Type RM Length L Ch R = 1 ,3320    ,482,482,482
BEGIN DESCRIPTION:
Mapping XS cc5cad3d
END DESCRIPTION:
XS GIS Cut Line= 3
       2701657.1      6935008.29      2700841.16      6934289.56
      2700205.73      6933803.44
#Sta/Elev= 30
  3916.3  470.39  4138.8   466.5  4287.4  462.62  4389.8  460.32  4410.8   456.2
  4418.3  458.29  4432.5   458.4  4453.4  456.07    4516  454.37    4602  455.74
  4630.8  456.68  4665.9     453  4735.7  449.96  4808.2  447.65  4850.6  448.19
  4857.5  445.77  4864.2  447.89  4878.4  448.36  4992.2  448.08  5027.5  442.76
  5030.8  436.27  5032.1  435.77  5039.8  436.27    5042     441  5048.3  444.17
  5056.6  445.74  5098.3  445.37  5420.2  456.24  5584.3   465.9  5803.7  484.74
#Mann= 8 ,-1 , 0
  3916.3     .05       0  4138.8     .12       0  4287.4      .1       0
    4516     .12       0    4602     .05       0  4735.7     .12       0
  5030.8     .07       0  5039.8      .1       0
Bank Sta=5030.8,5039.8
XS Rating Curve= 0 ,0
Exp/Cntr=0.3,0.1

Type RM Length L Ch R = 1 ,2838    ,582,582,582
BEGIN DESCRIPTION:
Mapping XS 8485669d
END DESCRIPTION:
XS GIS Cut Line= 3
       2702062.7      6934984.43      2701225.01      6934081.63
      2700197.98      6933635.28
#Sta/Elev= 30
  3790.8  479.05  3807.2  478.25    4244  464.78  4279.1  465.55  4556.7  460.42
  4597.7  460.53  4626.1  459.45  4632.9  457.67  4668.5  458.78  4686.2  457.43
  4725.6  456.82  4866.5  446.45  4901.6  444.77  4944.1   445.4  4958.3  442.57
  4967.9  434.67  4969.2  434.17    4977  434.67  4979.8  440.71  4986.6  446.19
  5119.4  445.12  5284.6  450.58  5370.2  456.87  5468.4  461.67  5567.6  465.81
  5760.7  470.42  5818.5  474.07  5941.2  478.82  6046.4     486  6142.2  490.77
#Mann= 9 ,-1 , 0
  3790.8     .05       0  3807.2     .12       0  4556.7      .1       0
  4686.2     .12       0  4725.6      .1       0  4967.9     .07       0
    4977      .1       0  5284.6     .12       0  6046.4      .1       0
Bank Sta=4967.9,4977
XS Rating Curve= 0 ,0
Exp/Cntr=0.3,0.1

Type RM Length L Ch R = 1 ,2256    ,376,376,376
BEGIN DESCRIPTION:
Mapping XS fee3a7fb
END DESCRIPTION:
XS GIS Cut Line= 3
      2702249.29       6934198.8      2701485.43      6933608.54
      2700283.14       6933356.8
#Sta/Elev= 30
  4031.1  462.68  4196.2  457.52    4275  457.37  4295.8  455.32  4310.3  456.64
  4338.6  454.99  4410.9  455.81  4533.8  451.88  4580.2  451.68  4594.7  449.65
  4623.7  451.77  4644.5  449.54  4651.1  451.29  4674.9  451.08  4881.4  445.71
  4972.3  444.28  4986.8  439.67  4988.4  433.98  4989.7  433.48  4997.5  433.98
  4998.7  433.98  5004.9   441.6  5016.3  444.01  5044.6  444.09  5204.7  444.85
  5643.9  460.51  5732.3  466.21  6049.1  480.77  6133.1  484.12  6224.8  490.66
#Mann= 11 ,-1 , 0
  4031.1     .05       0  4410.9     .12       0  4533.8      .1       0
  4651.1     .12       0  4674.9      .1       0  4881.4     .12       0
  4988.4     .07       0  4997.5     .12       0  5044.6      .1       0
  5732.3     .12       0  6049.1      .1       0
Bank Sta=4988.4,4997.5
XS Rating Curve= 0 ,0
Exp/Cntr=0.3,0.1

Type RM Length L Ch R = 1 ,1880    ,925,925,925
BEGIN DESCRIPTION:
Mapping XS ec8f8005
END DESCRIPTION:
XS GIS Cut Line= 3
      2702288.41      6933851.62      2701619.98      6933278.68
      2700779.48      6933031.73
#Sta/Elev= 30
  4127.5  458.72  4160.7  458.83  4214.6   459.4  4306.7  457.34  4349.6  453.99
  4434.5  453.49    4669  446.11  4845.7   443.2  4917.1  444.28  4923.6   442.9
  4937.9  442.93  4959.9  444.01  4966.5  440.32  4973.6  442.94  4980.7  443.46
  4990.3  432.39  4991.6  431.89  4999.6  432.39  5007.2   441.2  5012.6   441.2
  5022.5  443.94  5055.9   442.2  5129.3  443.56    5289  444.93  5367.9  448.92
  5563.4  464.45  5595.7   468.2    5627  469.68  5720.8  470.34  5883.9  473.97
#Mann= 10 ,-1 , 0
  4127.5     .05       0  4160.7      .1       0  4306.7     .05       0
  4434.5     .12       0  4990.3     .07       0  4999.6     .12       0
  5129.3      .1       0    5289     .12       0  5367.9      .1       0
  5563.4     .12       0
Bank Sta=4990.3,4999.6
XS Rating Curve= 0 ,0
Exp/Cntr=0.3,0.1

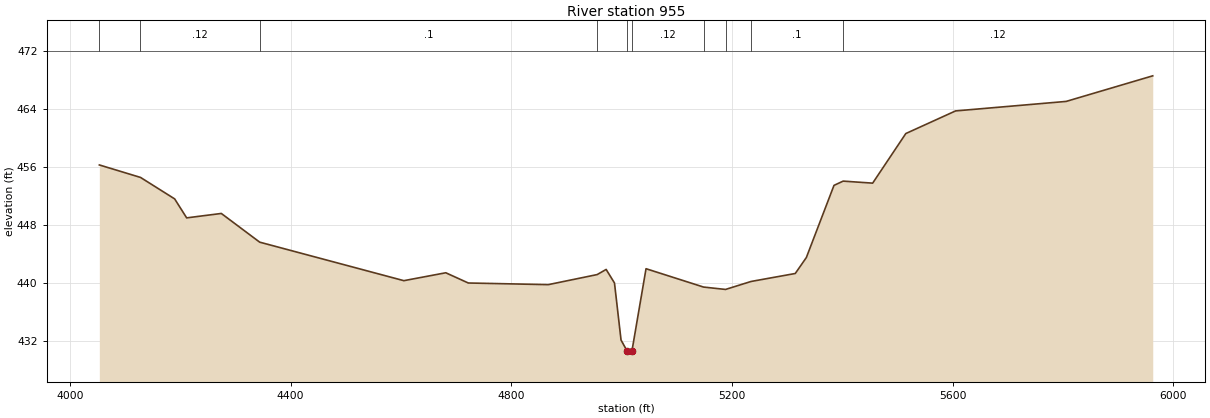
Type RM Length L Ch R = 1 ,955     ,0,0,0
BEGIN DESCRIPTION:
Rocky Cedar T5 1.0
END DESCRIPTION:
XS GIS Cut Line= 3
      2702250.99      6933435.98       2701870.3       6932569.3
      2700909.34      6932630.42
#Sta/Elev= 30
  4053.4  456.31    4128  454.59  4189.9  451.63  4211.7  449.01  4274.5  449.62
  4344.1  445.66  4605.4  440.35  4681.4  441.44  4722.2  440.03  4867.1   439.8
  4955.8  441.19  4972.1   441.9  4987.2  440.03  4999.1  432.16  5009.6  430.72
    5011  430.22    5019  430.72  5044.4     442  5148.6  439.47  5188.5  439.14
  5234.8  440.24  5314.9  441.34    5335  443.54  5385.1  453.49  5401.7  454.08
  5455.2   453.8  5515.3  460.64  5605.5  463.76  5805.9  465.07  5962.9   468.6
#Mann= 10 ,-1 , 0
  4053.4      .1       0    4128     .12       0  4344.1      .1       0
  4955.8     .12       0  5009.6     .07       0    5019     .12       0
  5148.6      .1       0  5188.5     .12       0  5234.8      .1       0
  5401.7     .12       0
Bank Sta=5009.6,5019
XS Rating Curve= 0 ,0
Exp/Cntr=0.3,0.1

Chan Stop Cuts=-1
Use User Specified Reach Order=0
Composite Channel Slope=5