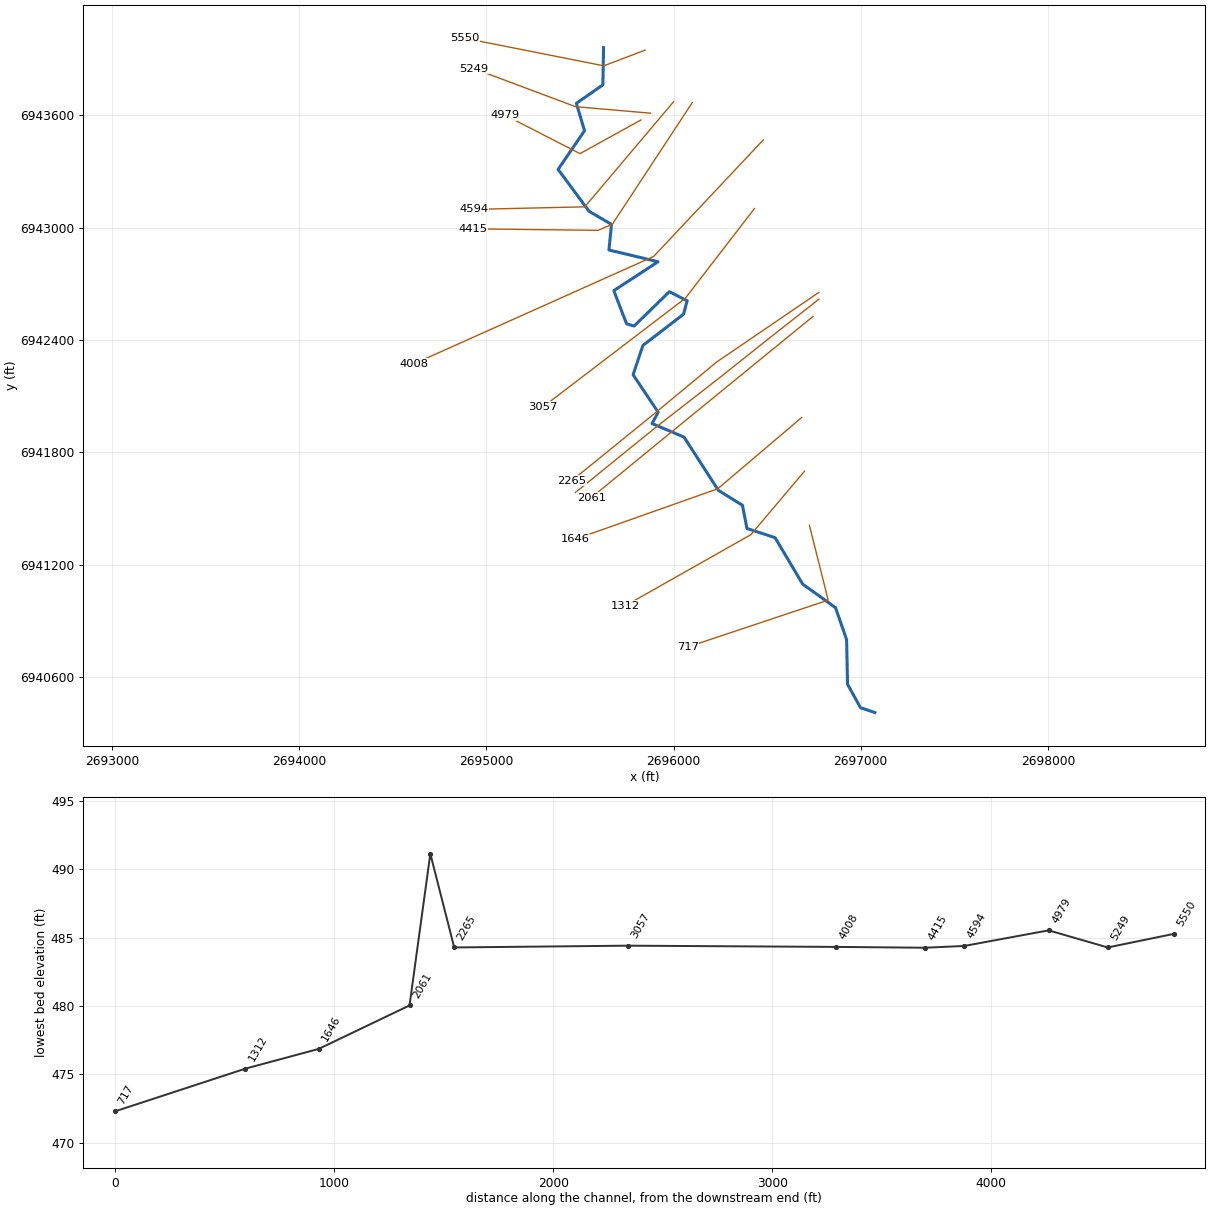
--- Rocky Cedar T5_1.prj (project) ---

Proj Title=Rocky Cedar T5_1 Base Level Engineering
Current Plan=p01
Default Exp/Contr=0.3,0.1
English Units
Geom File=g01
Flow File=f01
Plan File=p01
Y Axis Title=Elevation
X Axis Title(PF)=Main Channel Distance
X Axis Title(XS)=Station
BEGIN DESCRIPTION:
Rocky Cedar T5_1
END DESCRIPTION:
DSS Export Rating Curves= 0
DSS Export Rating Curve Sorted= 0
DSS Export Volume Flow Curves= 0
DXF OffsetX= 0
DXF OffsetY= 0
DXF ScaleX= 1
DXF ScaleY= 10

--- Rocky Cedar T5_1.p01 (plan) ---

Plan Title=Multiple Run
Short Identifier=Multiple
Geom File=g01
Flow File=f01
Subcritical Flow
K Sum by GR= 0
Std Step Tol= 0.01
Critical Tol= 0.01
Num of Std Step Trials= 20
Max Error Tol= 0.3
Flow Tol Ratio= 0.001
Split Flow NTrial= 30
Split Flow Tol= 0.02
Split Flow Ratio= 0.02
Log Output Level= 0
Friction Slope Method= 1
Unsteady Friction Slope Method= 2
Unsteady Bridges Friction Slope Method= 1
Parabolic Critical Depth
Global Vel Dist=  1 , 1 , 1
Global Log Level= 0
CheckData=True
Encroach Param= -1, 0, 0, 0
BEGIN DESCRIPTION:
Multiple Run
END DESCRIPTION:

--- Rocky Cedar T5_1.f01 (steady flow) ---

Flow Title=Multiple
Number of Profiles=7
Profile Names=10-year,25-year,50-year,1pct_min,100-year,1pct_plu,500-year
River Rch & RM= Rocky Cedar T5_1,Reach-1,5550
     477     624     740     436     870    1735    1198
River Rch & RM= Rocky Cedar T5_1,Reach-1,2156
     525     691     823     486     971    1936    1347
Boundary for River Rch & Prof#=Rocky Cedar T5_1,Reach-1,1
Up Type=0
Dn Type=3
Dn Slope=0.005
Boundary for River Rch & Prof#=Rocky Cedar T5_1,Reach-1,2
Up Type=0
Dn Type=3
Dn Slope=0.005
Boundary for River Rch & Prof#=Rocky Cedar T5_1,Reach-1,3
Up Type=0
Dn Type=3
Dn Slope=0.005
Boundary for River Rch & Prof#=Rocky Cedar T5_1,Reach-1,4
Up Type=0
Dn Type=3
Dn Slope=0.005
Boundary for River Rch & Prof#=Rocky Cedar T5_1,Reach-1,5
Up Type=0
Dn Type=3
Dn Slope=0.005
Boundary for River Rch & Prof#=Rocky Cedar T5_1,Reach-1,6
Up Type=0
Dn Type=3
Dn Slope=0.005
Boundary for River Rch & Prof#=Rocky Cedar T5_1,Reach-1,7
Up Type=0
Dn Type=3
Dn Slope=0.005

--- Rocky Cedar T5_1.g01 (geometry) ---

Geom Title=Existing Conditions
Program Version=4.10

River Reach=Rocky Cedar T5_1,Reach-1
Reach XY= 30
        2695626.        6943961.      2695622.56      6943762.25
      2695480.99      6943663.54      2695524.37      6943517.04
      2695383.28      6943310.91      2695548.87      6943087.17
      2695668.61      6943017.33       2695654.9      6942880.59
      2695917.25      6942817.84      2695680.98      6942663.55
      2695749.01      6942486.53      2695789.22      6942474.36
      2695977.68      6942657.92      2696072.99      6942609.63
       2696053.3      6942537.54      2695836.38       6942371.1
      2695784.05      6942214.29      2695917.98      6942014.32
      2695885.17      6941954.01      2696056.27      6941881.51
      2696239.49      6941597.44      2696368.25      6941517.45
      2696392.27      6941393.79      2696542.79      6941344.56
      2696689.47      6941097.43      2696865.49      6940970.81
      2696924.78       6940800.5      2696929.75      6940562.55
      2696998.72      6940437.15        2697076.        6940411.

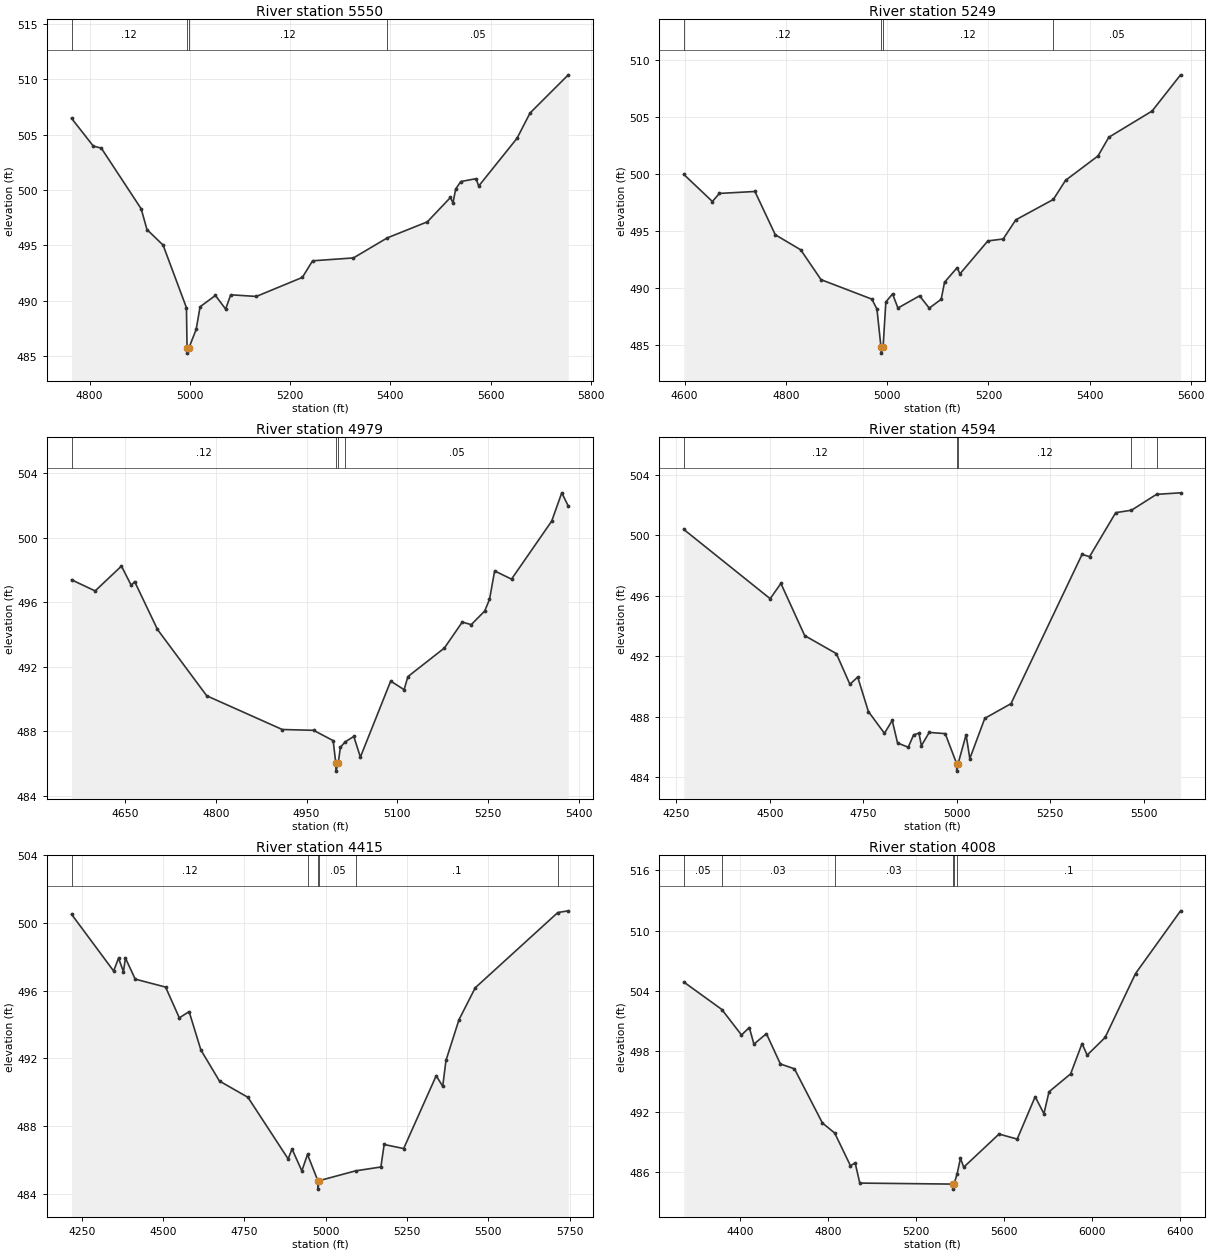
Type RM Length L Ch R = 1 ,5550    ,301,301,301
BEGIN DESCRIPTION:
Rocky Cedar T5_1 9.0
END DESCRIPTION:
XS GIS Cut Line= 3
      2695846.61      6943947.08      2695627.82      6943863.73
      2694885.77      6944010.74
#Sta/Elev= 30
  4764.1  506.49  4807.6  503.97  4823.5  503.79    4903  498.31  4914.6  496.43
  4946.7  495.03  4993.3  489.37  4994.5  485.77  4994.8  485.27  4998.5  485.77
  5012.7  487.42  5020.5  489.46  5051.1  490.48  5071.4  489.25  5081.6  490.54
  5132.6  490.39  5224.4  492.11  5244.8  493.61  5326.3  493.87  5393.7  495.68
  5473.6  497.13  5519.7  499.33  5524.8  498.84  5530.2   500.1  5540.4  500.77
  5570.9  501.03    5576  500.36  5652.5  504.68  5678.4  506.96  5754.7  510.41
#Mann= 4 ,-1 , 0
  4764.1     .12       0  4994.5     .07       0  4998.5     .12       0
  5393.7     .05       0
Bank Sta=4994.5,4998.5
XS Rating Curve= 0 ,0
Exp/Cntr=0.3,0.1

Type RM Length L Ch R = 1 ,5249    ,270,270,270
BEGIN DESCRIPTION:
Rocky Cedar T5_1 8.0
END DESCRIPTION:
XS GIS Cut Line= 3
        2695876.        6943611.      2695475.91      6943645.79
      2694933.32      6943849.03
#Sta/Elev= 30
  4598.4  499.97  4654.9  497.59  4668.7   498.3  4738.9  498.47  4779.1  494.67
  4829.3  493.35  4869.4  490.73  4969.8  489.02  4979.8  488.15  4987.9  484.78
  4988.1  484.28  4991.9  484.78  4997.4  488.77  5010.6  489.48  5021.3  488.24
    5064  489.31  5083.1  488.23  5106.7  489.01  5113.3   490.5  5138.3  491.79
  5143.6  491.23  5198.8  494.13  5229.1   494.3    5254  495.98  5328.1  497.77
  5352.3  499.45  5416.4  501.59  5437.7  503.23  5523.1  505.53  5579.4  508.71
#Mann= 4 ,-1 , 0
  4598.4     .12       0  4987.9     .07       0  4991.9     .12       0
  5328.1     .05       0
Bank Sta=4987.9,4991.9
XS Rating Curve= 0 ,0
Exp/Cntr=0.3,0.1

Type RM Length L Ch R = 1 ,4979    ,385,385,385
BEGIN DESCRIPTION:
Mapping XS fddec6e6
END DESCRIPTION:
XS GIS Cut Line= 3
      2695825.69      6943574.64      2695500.21      6943394.98
      2695100.07      6943600.25
#Sta/Elev= 30
  4561.4  497.39  4600.5   496.7    4644  498.24  4660.1  497.05  4665.8  497.28
  4703.6  494.31    4785   490.2  4909.9  488.11  4961.7  488.06  4994.1  487.42
  4998.4  486.03  4998.7  485.53  5002.4  486.03  5006.1  487.01  5013.8  487.34
  5028.2  487.68  5039.1   486.4  5089.2  491.11  5111.4  490.58  5117.7  491.39
    5178  493.16  5207.6  494.77  5222.4  494.61  5244.6  495.45  5252.6  496.17
  5261.1  497.94    5289  497.43  5355.5  501.03  5372.1  502.78  5382.9  501.96
#Mann= 4 ,-1 , 0
  4561.4     .12       0  4998.4     .07       0  5002.4     .12       0
  5013.8     .05       0
Bank Sta=4998.4,5002.4
XS Rating Curve= 0 ,0
Exp/Cntr=0.3,0.1

Type RM Length L Ch R = 1 ,4594    ,179,179,179
BEGIN DESCRIPTION:
Rocky Cedar T5_1 7.0
END DESCRIPTION:
XS GIS Cut Line= 3
      2696000.37      6943672.13        2695526.        6943111.
      2694932.63      6943097.44
#Sta/Elev= 30
  4270.1  500.37  4501.1  495.79  4529.7   496.8  4593.4  493.35    4678  492.16
  4714.3  490.13  4735.1  490.61  4763.7  488.33  4806.6  486.89  4827.4  487.74
  4841.7  486.25  4870.3  485.97  4884.6  486.79  4898.9   486.9  4905.4  486.07
  4926.3  486.95  4969.1  486.87  4999.6  484.89  4999.9  484.39  5003.6  484.89
  5024.9  486.79  5034.9  485.22  5074.9  487.88  5144.9  488.85    5335  498.72
    5355  498.57    5425  501.48  5467.1  501.64  5534.1  502.69  5598.4  502.79
#Mann= 5 ,-1 , 0
  4270.1     .12       0  4999.6     .07       0  5003.6     .12       0
  5467.1     .05       0  5534.1     .12       0
Bank Sta=4999.6,5003.6
XS Rating Curve= 0 ,0
Exp/Cntr=0.3,0.1

Type RM Length L Ch R = 1 ,4415    ,407,407,407
BEGIN DESCRIPTION:
Mapping XS 8b5f1654
END DESCRIPTION:
XS GIS Cut Line= 4
      2696100.06      6943667.45      2695672.96      6943017.95
        2695597.       6942985.4      2694930.03      6942993.44
#Sta/Elev= 30
  4218.6  500.52  4348.1  497.16  4363.2  497.92  4378.3  497.12  4384.3  497.93
  4414.5  496.68  4507.8  496.21    4550  494.39  4580.1  494.76  4616.3  492.49
  4673.5  490.65  4760.9  489.69  4884.4  486.05  4896.5  486.63  4926.6  485.34
    4944  486.31  4975.8  484.76  4976.1  484.26  4979.8  484.76  5091.7  485.34
  5169.6  485.57  5179.6   486.9  5239.6  486.66  5339.6  490.97  5359.6  490.34
  5369.6  491.87  5409.6  494.28  5459.6  496.17  5713.4  500.62  5745.6  500.72
#Mann= 6 ,-1 , 0
  4218.6     .12       0    4944     .05       0  4975.8     .03       0
  4979.8     .05       0  5091.7      .1       0  5713.4     .05       0
Bank Sta=4975.8,4979.8
XS Rating Curve= 0 ,0
Exp/Cntr=0.3,0.1

Type RM Length L Ch R = 1 ,4008    ,951,951,951
BEGIN DESCRIPTION:
Mapping XS bb261b61
END DESCRIPTION:
XS GIS Cut Line= 3
      2696479.46      6943468.24      2695893.88      6942846.08
      2694612.88      6942272.86
#Sta/Elev= 30
  4144.2  504.89  4317.2  502.16  4406.4  499.63    4442  500.37    4463  498.72
  4519.7  499.76  4583.2  496.75  4647.1  496.27  4774.2  490.89  4830.1  489.89
  4901.6  486.65  4923.1  486.92  4944.1  484.92  5368.1  484.82  5368.4  484.32
  5372.1  484.82  5386.1   485.8  5401.6  487.38  5416.5   486.5  5576.9  489.79
  5659.4  489.29  5741.2   493.5  5780.9  491.81  5804.1  493.99  5902.4  495.77
  5954.2  498.78  5977.4  497.63    6059  499.38  6197.2  505.73    6402  511.96
#Mann= 6 ,-1 , 0
  4144.2     .05       0  4317.2     .03       0  4830.1     .03       0
  5368.1     .03       0  5372.1     .03       0  5386.1      .1       0
Bank Sta=5368.1,5372.1
XS Rating Curve= 0 ,0
Exp/Cntr=0.3,0.1

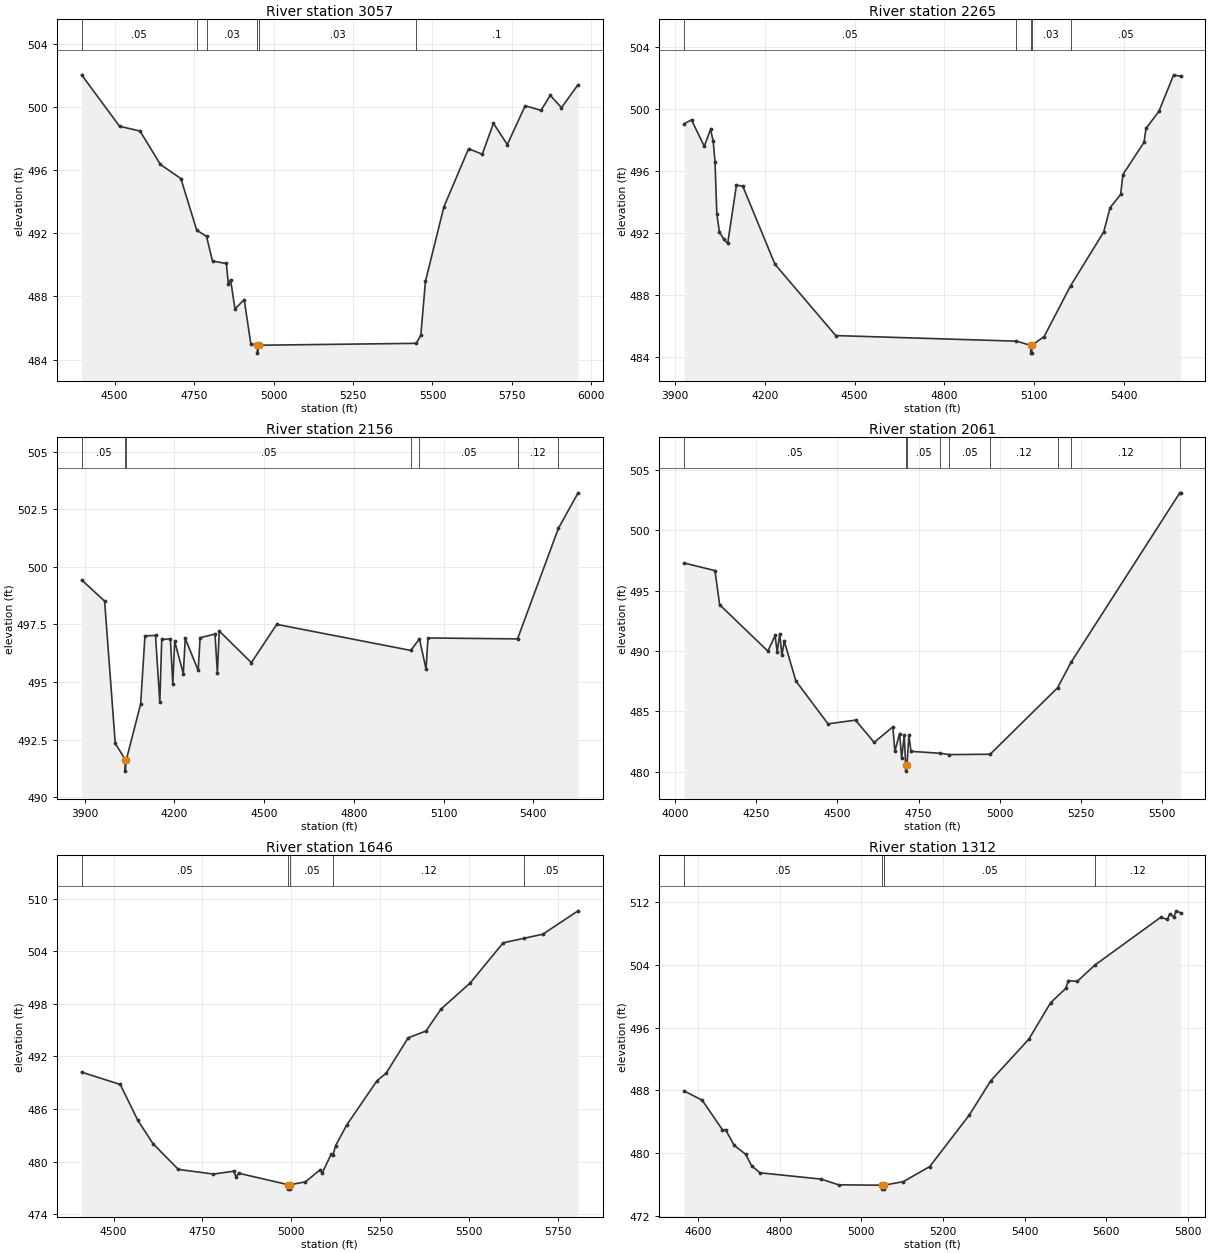
Type RM Length L Ch R = 1 ,3057    ,792,792,792
BEGIN DESCRIPTION:
Mapping XS 7c4aeacb
END DESCRIPTION:
XS GIS Cut Line= 3
      2696432.69      6943102.09      2696062.89       6942622.9
      2695301.98      6942042.47
#Sta/Elev= 30
    4396  502.04  4515.4  498.78  4579.7  498.48    4644  496.36  4708.3  495.47
  4758.2   492.2  4789.1   491.8  4807.9  490.24  4851.4  490.09  4857.7   488.8
  4864.7  489.06  4878.6  487.21  4907.6   487.8  4928.4  485.01  4949.1  484.91
  4949.3  484.41  4953.1  484.91  5449.4  485.03  5463.4  485.55    5478  488.96
  5536.1  493.68  5613.7  497.36  5656.7  497.01    5692  498.97  5735.6  497.62
  5791.8  500.08  5841.7  499.79  5870.8  500.74  5906.1  499.96  5958.3  501.42
#Mann= 6 ,-1 , 0
    4396     .05       0  4758.2     .03       0  4789.1     .03       0
  4949.1     .03       0  4953.1     .03       0  5449.4      .1       0
Bank Sta=4949.1,4953.1
XS Rating Curve= 0 ,0
Exp/Cntr=0.3,0.1

Type RM Length L Ch R = 1 ,2265    ,109,109,109
BEGIN DESCRIPTION:
Mapping XS a2b48f2f
END DESCRIPTION:
XS GIS Cut Line= 4
      2696776.41      6942654.14      2696229.55      6942281.75
      2695896.22      6942005.71      2695456.08      6941648.91
#Sta/Elev= 30
  3929.6  499.04  3954.3  499.29    3997  497.59    4018  498.68  4026.9  497.92
  4032.9  496.61    4039  493.24  4047.8  492.07  4062.8   491.6  4075.3  491.34
  4104.7  495.09  4125.7  495.03  4233.5     490  4436.9  485.41  5041.3  485.05
  5089.1  484.78  5089.3  484.28  5092.8  484.28  5093.1  484.78  5134.2  485.35
  5222.4  488.61  5333.2  492.07  5354.8  493.64    5390  494.49  5397.6  495.77
  5468.3  497.85  5474.8  498.74  5517.9  499.83  5567.4  502.19  5590.6  502.09
#Mann= 5 ,-1 , 0
  3929.6     .05       0  5041.3     .03       0  5089.1     .03       0
  5093.1     .03       0  5222.4     .05       0
Bank Sta=5089.1,5093.1
XS Rating Curve= 0 ,0
Exp/Cntr=0.3,0.1

Type RM Length L Ch R = 1 ,2156    ,95,95,95
BEGIN DESCRIPTION:
Mapping XS 34b4688a
END DESCRIPTION:
XS GIS Cut Line= 5
      2696776.46      6942617.71      2696484.76      6942388.52
      2696255.59      6942206.23      2695904.03       6941932.8
        2695476.      6941585.93
#Sta/Elev= 30
  3889.9  499.43  3966.8  498.51  4002.3  492.34  4035.5  491.63  4035.8  491.13
  4039.5  491.63  4087.3  494.04  4101.7     497    4137  497.02  4151.4  494.11
  4157.8  496.85  4186.7  496.87  4194.8  494.91  4201.1  496.76    4230  495.36
  4236.4  496.89  4279.7   495.5  4286.1  496.92  4335.9  497.08  4343.8   495.4
  4350.2  497.21  4457.5  495.84  4542.4   497.5  4990.4  496.37  5019.5  496.87
  5041.6  495.56    5048  496.91  5347.5  496.87  5484.3  501.67    5550  503.21
#Mann= 7 ,-1 , 0
  3889.9     .05       0  4035.5     .07       0  4039.5     .05       0
  4990.4     .12       0  5019.5     .05       0  5347.5     .12       0
  5484.3     .05       0
Bank Sta=4035.5,4039.5
XS Rating Curve= 0 ,0
Exp/Cntr=0.3,0.1

Type RM Length L Ch R = 1 ,2061    ,415,415,415
BEGIN DESCRIPTION:
Mapping XS c31bfdae
END DESCRIPTION:
XS GIS Cut Line= 3
      2696745.04      6942525.71      2696050.56      6941959.27
      2695560.58      6941558.18
#Sta/Elev= 30
  4027.9   497.3  4122.9  496.67  4137.3  493.84  4285.9  489.99  4308.2  491.29
  4314.6  489.92  4322.5  491.44    4329  489.63  4336.4  490.82  4372.1  487.52
  4471.2  483.96  4555.9  484.27  4613.3  482.42  4670.8  483.71  4677.2  481.69
  4691.6  483.16    4698  481.12    4706  483.03  4710.4  480.54  4710.7  480.04
  4714.4  480.54  4720.3  483.01  4726.8  481.68  4817.2  481.52  4844.5  481.41
  4970.6  481.44  5178.3  486.95  5219.5  489.05  5554.9  503.12  5557.3  503.12
#Mann= 9 ,-1 , 0
  4027.9     .05       0  4710.4     .07       0  4714.4     .05       0
  4817.2     .12       0  4844.5     .05       0  4970.6     .12       0
  5178.3     .05       0  5219.5     .12       0  5554.9     .05       0
Bank Sta=4710.4,4714.4
XS Rating Curve= 0 ,0
Exp/Cntr=0.3,0.1

Type RM Length L Ch R = 1 ,1646    ,334,334,334
BEGIN DESCRIPTION:
Mapping XS 738ee612
END DESCRIPTION:
XS GIS Cut Line= 3
      2696684.25      6941985.97      2696236.32      6941605.76
      2695472.35      6941335.51
#Sta/Elev= 30
  4409.9   490.2  4518.6   488.8    4568  484.72  4610.8  482.05  4682.2  479.11
  4781.1  478.58  4838.2   478.9  4844.8  478.29  4852.5  478.67  4992.2  477.36
  4992.4  476.86  4995.9  476.86  4996.2  477.36  5040.2  477.69    5082  479.09
  5087.3   478.7  5112.9  480.87  5117.6  480.71  5125.1  481.83  5156.9  484.21
  5241.8  489.23  5267.4  490.08  5329.2  494.11  5379.6   494.9  5422.1  497.41
    5504  500.37  5596.8  504.95  5656.6  505.48  5708.5  505.93  5807.8   508.6
#Mann= 5 ,-1 , 0
  4409.9     .05       0  4992.2     .03       0  4996.2     .05       0
  5117.6     .12       0  5656.6     .05       0
Bank Sta=4992.2,4996.2
XS Rating Curve= 0 ,0
Exp/Cntr=0.3,0.1

Type RM Length L Ch R = 1 ,1312    ,595,595,595
BEGIN DESCRIPTION:
Mapping XS 419ad38d
END DESCRIPTION:
XS GIS Cut Line= 3
      2696699.89      6941699.54      2696413.41      6941360.96
      2695741.54      6940980.76
#Sta/Elev= 30
  4566.4  487.94  4610.7  486.76  4660.2  482.99  4667.9     483  4688.7  481.02
  4717.3  479.85  4731.6  478.39  4752.4   477.5  4901.9   476.7  4944.4  475.97
  5050.9  475.92  5051.2  475.42  5054.7  475.42  5054.9  475.92  5102.9  476.37
  5167.8   478.3  5264.6  484.87  5317.2  489.25  5410.3  494.54  5463.7  499.19
    5501  501.03    5507  502.02  5528.7  501.91  5572.3     504  5733.6   510.1
  5749.5  509.81  5755.3  510.51  5765.3  510.14  5771.2  510.91  5781.9  510.66
#Mann= 4 ,-1 , 0
  4566.4     .05       0  5050.9     .04       0  5054.9     .05       0
  5572.3     .12       0
Bank Sta=5050.9,5054.9
XS Rating Curve= 0 ,0
Exp/Cntr=0.3,0.1

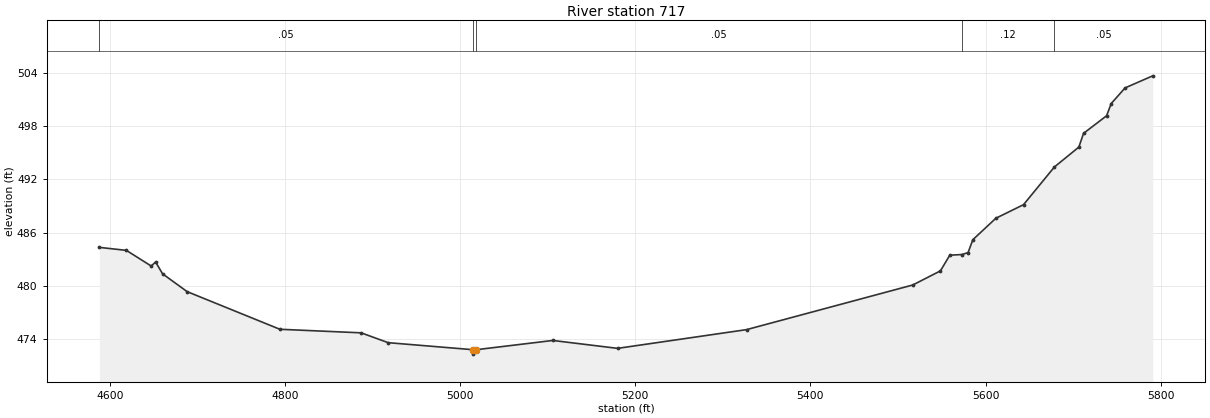
Type RM Length L Ch R = 1 ,717     ,0,0,0
BEGIN DESCRIPTION:
Rocky Cedar T5_1 1.0
END DESCRIPTION:
XS GIS Cut Line= 3
        2696726.      6941411.01      2696826.33      6941011.31
      2696075.98      6940760.99
#Sta/Elev= 30
  4587.9  484.33  4618.8  483.99  4647.1  482.23  4652.2  482.68  4660.1  481.35
  4688.2  479.34  4794.1   475.1  4886.9   474.7  4917.8  473.59  5014.5   472.8
  5014.7   472.3  5018.5   472.8  5105.8  473.84  5179.8  472.95  5327.1  475.06
  5516.9  480.09  5548.5  481.68  5559.2  483.45  5572.9  483.52  5580.1  483.74
  5585.5  485.19  5611.8  487.61  5643.4  489.14  5678.7  493.39  5706.6  495.63
    5712  497.18  5738.3  499.16  5743.6  500.54  5759.4   502.3    5791  503.66
#Mann= 5 ,-1 , 0
  4587.9     .05       0  5014.5     .03       0  5018.5     .05       0
  5572.9     .12       0  5678.7     .05       0
Bank Sta=5014.5,5018.5
XS Rating Curve= 0 ,0
Exp/Cntr=0.3,0.1

Chan Stop Cuts=-1
Use User Specified Reach Order=0
Composite Channel Slope=5