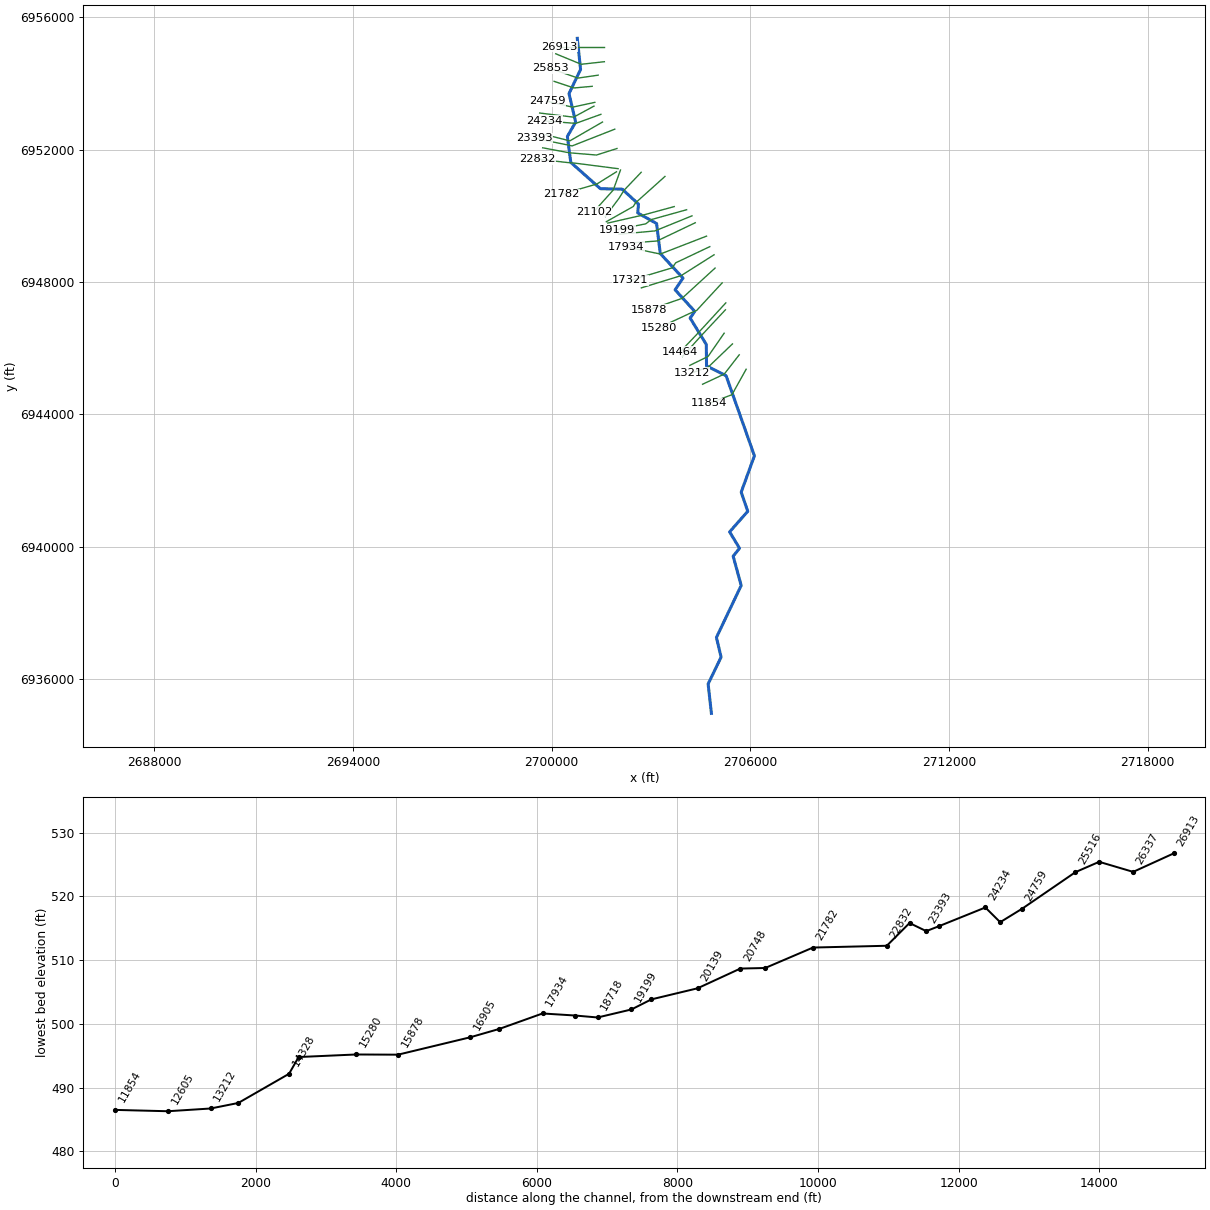
--- Rocky Cedar T6.prj (project) ---

Proj Title=Rocky Cedar T6 Base Level Engineering
Current Plan=p01
Default Exp/Contr=0.3,0.1
English Units
Geom File=g01
Flow File=f01
Plan File=p01
BEGIN DESCRIPTION:
Rocky Cedar T6
END DESCRIPTION:

--- Rocky Cedar T6.p01 (plan) ---

Plan Title=Multiple Run
Short Identifier=Multiple
Geom File=g01
Flow File=f01
Subcritical Flow
K Sum by GR= 0
Std Step Tol= 0.01
Critical Tol= 0.01
Num of Std Step Trials= 20
Max Error Tol= 0.3
Flow Tol Ratio= 0.001
Split Flow NTrial= 30
Split Flow Tol= 0.02
Split Flow Ratio= 0.02
Log Output Level= 0
Friction Slope Method= 1
Unsteady Friction Slope Method= 2
Unsteady Bridges Friction Slope Method= 1
Parabolic Critical Depth
Global Vel Dist=  1 , 1 , 1
Global Log Level= 0
CheckData=True
Encroach Param= -1, 0, 0, 0
BEGIN DESCRIPTION:
Multiple Run
END DESCRIPTION:

--- Rocky Cedar T6.f01 (steady flow) ---

Flow Title=Multiple
Number of Profiles=7
Profile Names=10-year,25-year,50-year,1pct_min,100-year,1pct_plu,500-year
River Rch & RM= Rocky Cedar T6,Reach-1,26913
     599     799     961     573    1144    2282    1619
River Rch & RM= Rocky Cedar T6,Reach-1,25853
     694     933    1126     674    1345    2683    1916
River Rch & RM= Rocky Cedar T6,Reach-1,23569
    1061    1454    1777    1075    2146    4281    3127
River Rch & RM= Rocky Cedar T6,Reach-1,17321
    1250    1723    2114    1283    2560    5108    3755
River Rch & RM= Rocky Cedar T6,Reach-1,11076
    1797    2523    3135    1924    3840    7661    5762
River Rch & RM= Rocky Cedar T6,Reach-1,3539
    2057    2899    3611    2220    4430    8839    6672
Boundary for River Rch & Prof#=Rocky Cedar T6,Reach-1,1
Up Type=0
Dn Type=3
Dn Slope=0.005
Boundary for River Rch & Prof#=Rocky Cedar T6,Reach-1,2
Up Type=0
Dn Type=3
Dn Slope=0.005
Boundary for River Rch & Prof#=Rocky Cedar T6,Reach-1,3
Up Type=0
Dn Type=3
Dn Slope=0.005
Boundary for River Rch & Prof#=Rocky Cedar T6,Reach-1,4
Up Type=0
Dn Type=3
Dn Slope=0.005
Boundary for River Rch & Prof#=Rocky Cedar T6,Reach-1,5
Up Type=0
Dn Type=3
Dn Slope=0.005
Boundary for River Rch & Prof#=Rocky Cedar T6,Reach-1,6
Up Type=0
Dn Type=3
Dn Slope=0.005
Boundary for River Rch & Prof#=Rocky Cedar T6,Reach-1,7
Up Type=0
Dn Type=3
Dn Slope=0.005

--- Rocky Cedar T6.g01 (geometry) ---

Geom Title=Existing Conditions

River Reach=Rocky Cedar T6,Reach-1
Reach XY= 30
      2700776.00      6955361.00      2700874.95      6954421.44
      2700525.55      6953690.98      2700726.61      6952831.04
      2700475.85      6952395.76      2700579.48      6951612.27
      2701473.69      6950816.61      2702132.19      6950803.19
      2702623.57      6950352.89      2702602.09      6950083.71
      2703171.04      6949763.54      2703281.42      6948858.33
      2703968.49      6948114.15      2703729.46      6947762.03
      2704322.88      6947109.37      2704183.78      6946907.94
      2704672.45      6946109.53      2704679.09      6945462.63
      2705270.53      6945163.45      2706125.32      6942745.16
      2705725.95      6941645.66      2705923.85      6941066.90
      2705376.66      6940445.72      2705674.93      6939950.47
      2705483.08      6939711.02      2705725.62      6938826.15
      2704978.07      6937255.14      2705118.92      6936661.00
      2704727.06      6935850.56      2704826.00      6934961.00

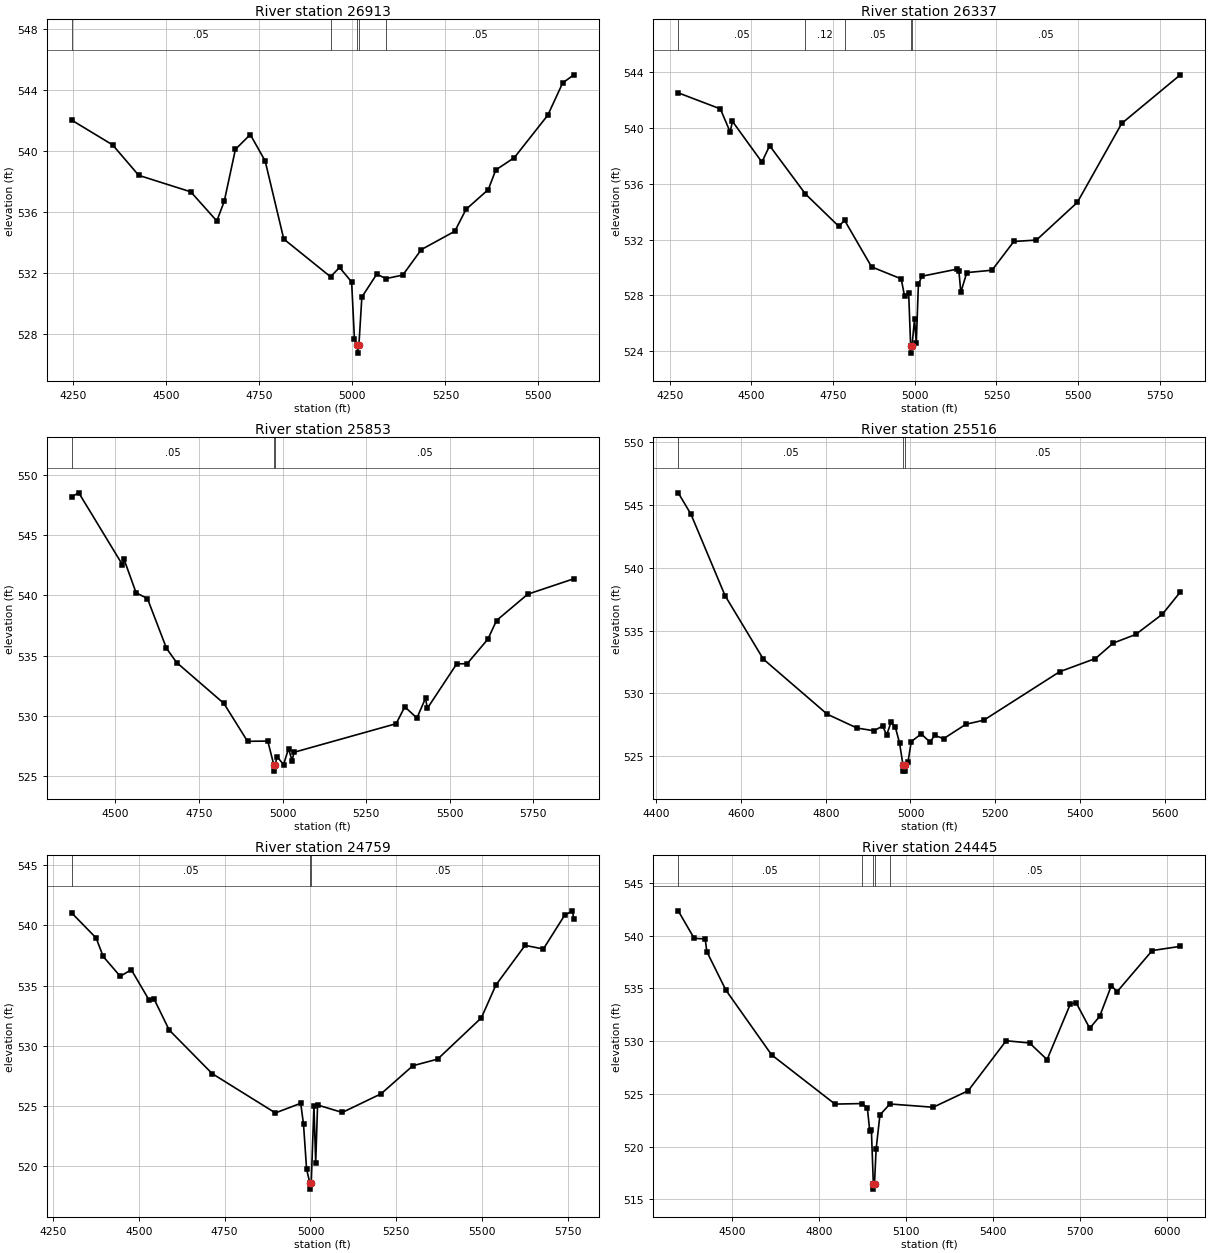
Type RM Length L Ch R = 1,26913,576,576,576
BEGIN DESCRIPTION:
Rocky Cedar T6 50.0
END DESCRIPTION:
XS GIS Cut Line= 3
      2701576.04      6955111.00      2700826.00      6955111.00
      2700226.04      6955111.00
#Sta/Elev= 30
  4245.4  542.01  4355.4  540.39  4425.4  538.40  4565.4  537.32  4635.4  535.41
  4655.4  536.70  4685.4  540.10  4725.4  541.07  4765.4  539.34  4815.4  534.23
  4941.2  531.76  4965.4  532.37  4997.9  531.42  5005.4  527.70  5013.4  527.26
  5013.7  526.76  5017.4  527.26  5025.4  530.43  5065.4  531.93  5090.3  531.64
  5135.4  531.87  5185.4  533.54  5275.4  534.74  5305.4  536.17  5365.4  537.47
  5385.4  538.75  5435.4  539.56  5525.4  542.34  5565.4  544.45  5595.4  544.98
#Mann=5,-1,0
  4245.4    0.05       0  4941.2    0.12       0  5013.4    0.07       0
  5017.4    0.12       0  5090.3    0.05       0
Bank Sta=5013.4,5017.4
Exp/Cntr=0.3,0.1

Type RM Length L Ch R = 1,26337,484,484,484
BEGIN DESCRIPTION:
Mapping XS 7910d335
END DESCRIPTION:
XS GIS Cut Line= 3
      2701593.97      6954654.62      2700896.01      6954576.49
      2700125.13      6954894.21
#Sta/Elev= 30
  4276.3  542.51  4405.1  541.36  4435.3  539.70  4442.0  540.47  4532.2  537.55
  4556.0  538.72  4665.6  535.26  4767.3  532.95  4785.4  533.37  4867.9  530.04
  4958.5  529.18  4968.6  527.96  4981.3  528.18  4987.4  524.36  4987.7  523.86
  4991.4  524.36  4999.2  526.28  5004.6  524.58  5011.1  528.80  5021.9  529.37
  5129.7  529.88  5135.1  529.71  5140.9  528.22  5159.1  529.63  5236.3  529.80
  5303.1  531.86  5372.2  531.96  5497.3  534.66  5633.2  540.32  5812.4  543.80
#Mann=5,-1,0
  4276.3    0.05       0  4665.6    0.12       0  4785.4    0.05       0
  4987.4    0.03       0  4991.4    0.05       0
Bank Sta=4987.4,4991.4
Exp/Cntr=0.3,0.1

Type RM Length L Ch R = 1,25853,337,337,337
BEGIN DESCRIPTION:
Mapping XS 24c14fad
END DESCRIPTION:
XS GIS Cut Line= 3
      2701406.40      6954248.36      2700797.05      6954159.82
      2699959.80      6954451.04
#Sta/Elev= 30
  4369.3  548.19  4390.3  548.50  4520.5  542.56  4525.6  543.00  4561.7  540.22
  4595.7  539.74  4652.6  535.62  4683.0  534.44  4824.4  531.05  4895.2  527.91
  4955.8  527.93  4974.0  525.94  4974.3  525.44  4978.0  525.94  4983.1  526.65
  5003.0  525.98  5017.9  527.31  5028.5  526.29  5034.1  527.00  5339.8  529.37
  5365.6  530.77  5402.0  529.84  5427.8  531.49  5433.1  530.64  5521.1  534.33
  5552.2  534.34  5614.4  536.38  5640.2  537.92  5733.5  540.10  5871.5  541.38
#Mann=3,-1,0
  4369.3    0.05       0  4974.0    0.04       0  4978.0    0.05       0
Bank Sta=4974,4978
Exp/Cntr=0.3,0.1

Type RM Length L Ch R = 1,25516,757,757,757
BEGIN DESCRIPTION:
Rocky Cedar T6 47.0
END DESCRIPTION:
XS GIS Cut Line= 3
      2701226.01      6953911.00      2700676.00      6953861.00
      2700076.03      6954060.99
#Sta/Elev= 30
  4452.0  545.96  4482.1  544.25  4562.5  537.78  4652.8  532.73  4803.5  528.35
  4873.7  527.25  4913.9  527.03  4934.0  527.41  4944.0  526.71  4954.1  527.72
  4964.1  527.33  4974.2  526.07  4982.2  524.32  4982.4  523.82  4985.9  523.82
  4986.2  524.32  4994.2  524.56  5001.8  526.17  5025.4  526.78  5046.4  526.12
  5057.0  526.67  5078.1  526.40  5130.8  527.55  5172.9  527.87  5352.1  531.73
  5436.5  532.78  5478.6  534.01  5531.3  534.69  5594.6  536.31  5636.7  538.07
#Mann=3,-1,0
  4452.0    0.05       0  4982.2    0.03       0  4986.2    0.05       0
Bank Sta=4982.2,4986.2
Exp/Cntr=0.3,0.1

Type RM Length L Ch R = 1,24759,314,314,314
BEGIN DESCRIPTION:
Mapping XS b5d3a4d4
END DESCRIPTION:
XS GIS Cut Line= 3
      2701305.34      6953426.76      2700633.42      6953280.91
      2699879.63      6953457.66
#Sta/Elev= 30
  4305.1  541.03  4376.1  538.95  4396.5  537.42  4446.3  535.77  4478.4  536.32
  4529.5  533.83  4544.6  533.89  4588.7  531.31  4713.7  527.69  4897.9  524.42
  4971.7  525.22  4979.8  523.48  4988.8  519.75  4998.3  518.59  4998.5  518.09
  5002.3  518.59  5010.2  525.01  5015.3  520.30  5020.8  525.08  5092.7  524.46
  5205.7  526.01  5298.2  528.34  5370.3  528.89  5497.6  532.32  5540.1  535.05
  5624.9  538.34  5678.2  538.04  5739.8  540.83  5762.6  541.21  5766.9  540.55
#Mann=3,-1,0
  4305.1    0.05       0  4998.3    0.03       0  5002.3    0.05       0
Bank Sta=4998.3,5002.3
Exp/Cntr=0.3,0.1

Type RM Length L Ch R = 1,24445,211,211,211
BEGIN DESCRIPTION:
Mapping XS d093d3f0
END DESCRIPTION:
XS GIS Cut Line= 3
      2701279.28      6953312.18      2700664.67      6952978.83
      2699639.83      6953103.68
#Sta/Elev= 30
  4313.7  542.37  4368.6  539.76  4406.7  539.70  4412.3  538.50  4477.9  534.85
  4635.8  528.70  4854.4  524.03  4947.6  524.08  4965.9  523.68  4974.2  521.48
  4979.9  521.56  4986.6  516.46  4986.9  515.96  4990.6  516.46  4996.1  519.74
  5009.3  523.00  5043.7  524.04  5192.9  523.73  5313.8  525.30  5444.7  530.04
  5525.3  529.83  5585.8  528.25  5666.4  533.55  5686.5  533.62  5732.8  531.23
  5767.1  532.35  5807.4  535.26  5827.5  534.70  5948.4  538.60  6045.3  539.00
#Mann=5,-1,0
  4313.7    0.05       0  4947.6    0.12       0  4986.6    0.07       0
  4990.6    0.12       0  5043.7    0.05       0
Bank Sta=4986.6,4990.6
Exp/Cntr=0.3,0.1

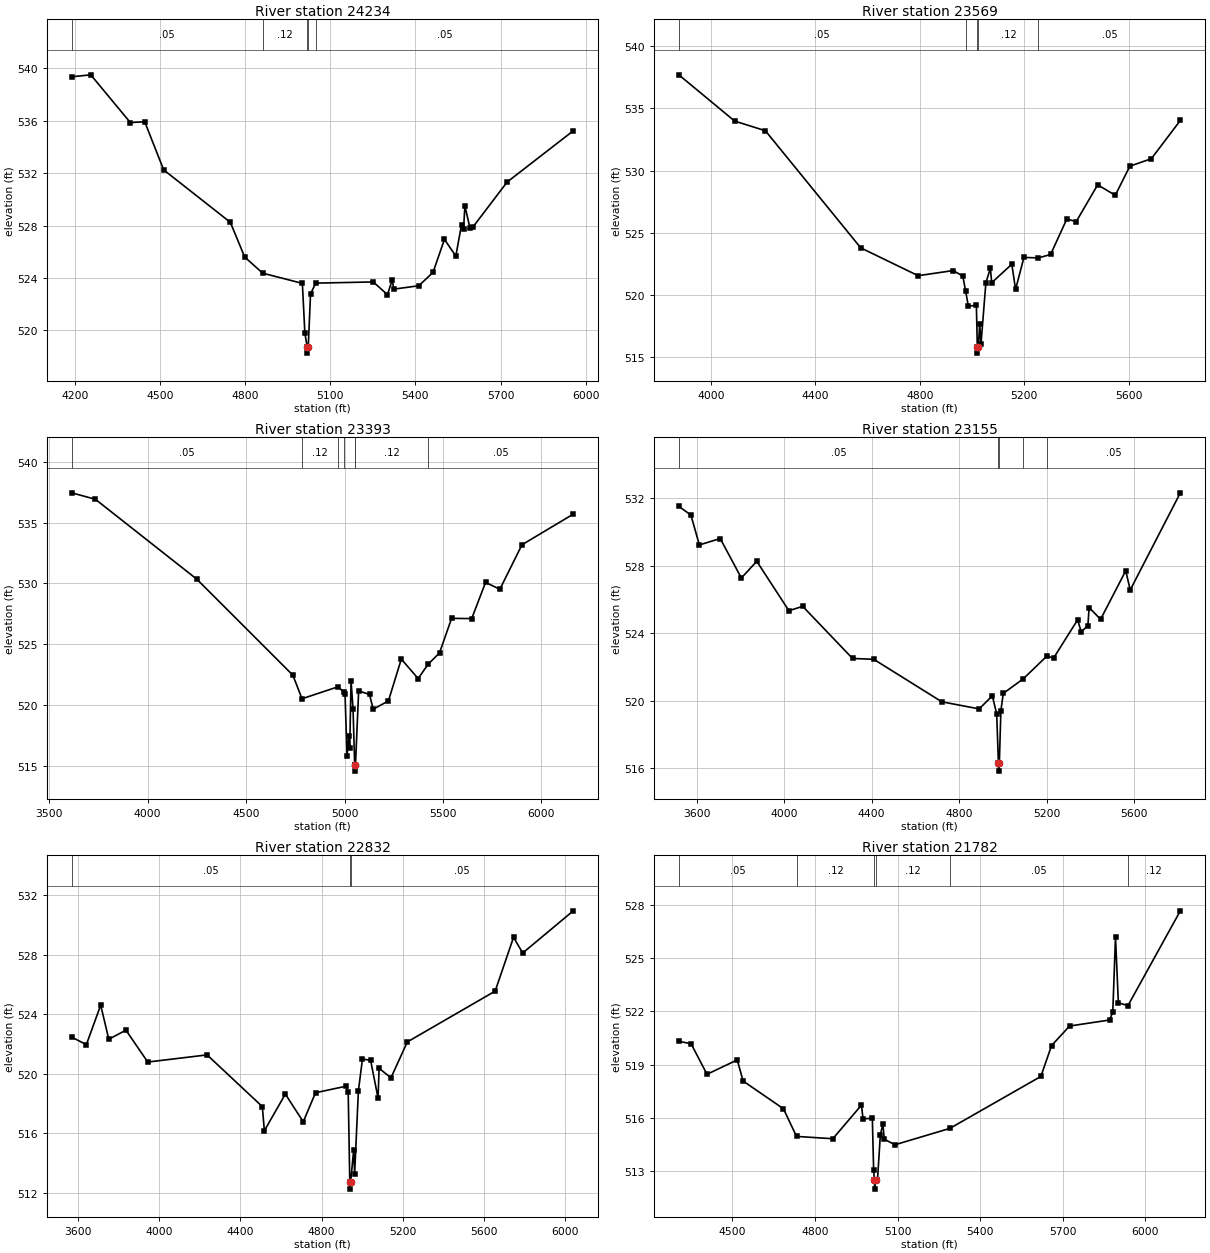
Type RM Length L Ch R = 1,24234,665,665,665
BEGIN DESCRIPTION:
Mapping XS e06e1595
END DESCRIPTION:
XS GIS Cut Line= 3
      2701488.98      6953064.60      2700728.56      6952790.29
      2699773.70      6952866.68
#Sta/Elev= 30
  4189.7  539.35  4256.7  539.50  4396.0  535.86  4446.7  535.92  4513.4  532.25
  4748.2  528.25  4798.8  525.60  4862.2  524.37  5001.9  523.59  5010.7  519.81
  5018.7  518.77  5019.0  518.27  5022.7  518.77  5030.7  522.80  5049.2  523.61
  5251.5  523.70  5301.6  522.73  5318.6  523.87  5323.6  523.15  5412.0  523.41
  5462.1  524.43  5502.3  526.95  5542.4  525.67  5562.4  528.07  5569.4  527.71
  5574.4  529.50  5592.5  527.78  5602.6  527.89  5723.0  531.32  5956.0  535.23
#Mann=5,-1,0
  4189.7    0.05       0  4862.2    0.12       0  5018.7    0.07       0
  5022.7    0.12       0  5049.2    0.05       0
Bank Sta=5018.7,5022.7
Exp/Cntr=0.3,0.1

Type RM Length L Ch R = 1,23569,176,176,176
BEGIN DESCRIPTION:
Mapping XS 7e0347a7
END DESCRIPTION:
XS GIS Cut Line= 3
      2701537.62      6952831.98      2700551.47      6952262.51
      2699794.55      6952453.48
#Sta/Elev= 30
  3877.5  537.70  4091.2  533.98  4208.9  533.20  4573.7  523.78  4793.4  521.54
  4926.9  521.95  4964.2  521.52  4975.4  520.28  4985.7  519.08  5016.3  519.17
  5019.9  515.81  5020.2  515.31  5024.0  515.81  5028.8  517.69  5034.0  516.07
  5052.8  520.99  5069.9  522.13  5075.0  520.98  5152.0  522.46  5166.3  520.43
  5198.2  523.01  5253.7  522.97  5300.4  523.25  5362.5  526.10  5398.4  525.89
  5480.5  528.85  5547.9  528.01  5603.7  530.35  5685.8  530.95  5796.9  534.03
#Mann=5,-1,0
  3877.5    0.05       0  4975.4    0.12       0  5019.9    0.07       0
  5024.0    0.12       0  5253.7    0.05       0
Bank Sta=5019.9,5024
Exp/Cntr=0.3,0.1

Type RM Length L Ch R = 1,23393,238,238,238
BEGIN DESCRIPTION:
Mapping XS c1b37578
END DESCRIPTION:
XS GIS Cut Line= 3
      2701907.74      6952615.64      2700621.27      6952110.43
      2699480.81      6952344.77
#Sta/Elev= 30
  3615.0  537.44  3735.0  536.91  4250.7  530.33  4737.6  522.45  4784.1  520.51
  4968.2  521.50  4994.9  521.05  5002.5  520.94  5012.7  515.77  5021.3  517.47
  5026.4  516.46  5033.1  521.99  5043.3  519.65  5051.5  515.06  5051.8  514.56
  5055.6  515.06  5071.7  521.16  5127.1  520.86  5145.4  519.65  5222.8  520.33
  5288.3  523.77  5373.9  522.17  5424.4  523.35  5482.3  524.28  5543.6  527.12
  5645.7  527.10  5716.2  530.08  5788.6  529.51  5900.9  533.17  6161.4  535.69
#Mann=7,-1,0
  3615.0    0.05       0  4784.1    0.12       0  4968.2    0.05       0
  4994.9    0.12       0  5051.5    0.07       0  5055.6    0.12       0
  5424.4    0.05       0
Bank Sta=5051.5,5055.6
Exp/Cntr=0.3,0.1

Type RM Length L Ch R = 1,23155,323,323,323
BEGIN DESCRIPTION:
Mapping XS 81d4062d
END DESCRIPTION:
XS GIS Cut Line= 4
      2701975.40      6952032.29      2701355.64      6951834.39
      2700532.72      6951902.09      2699730.81      6952053.10
#Sta/Elev= 30
  3518.6  531.53  3573.9  531.01  3612.5  529.24  3707.9  529.62  3804.5  527.28
  3874.9  528.27  4021.9  525.34  4084.8  525.60  4312.6  522.51  4409.6  522.46
  4720.7  519.94  4891.3  519.52  4951.5  520.29  4971.5  519.23  4979.4  516.33
  4979.8  515.83  4983.7  516.33  4990.7  519.42  5001.7  520.44  5092.8  521.30
  5200.8  522.65  5231.4  522.53  5341.4  524.80  5357.9  524.09  5388.4  524.46
  5393.9  525.53  5446.3  524.83  5561.4  527.71  5581.8  526.57  5810.9  532.33
#Mann=5,-1,0
  3518.6    0.05       0  4979.4    0.05       0  4983.7    0.05       0
  5092.8    0.12       0  5200.8    0.05       0
Bank Sta=4979.4,4983.7
Exp/Cntr=0.3,0.1

Type RM Length L Ch R = 1,22832,1050,1050,1050
BEGIN DESCRIPTION:
Mapping XS 4651756f
END DESCRIPTION:
XS GIS Cut Line= 4
      2702007.56      6951422.17      2700704.60      6951589.59
      2700454.60      6951610.43      2699553.54      6951714.60
#Sta/Elev= 30
  3569.0  522.46  3641.1  521.96  3711.7  524.61  3751.5  522.32  3836.1  522.93
  3943.6  520.79  4236.0  521.27  4508.2  517.80  4518.3  516.18  4621.6  518.64
  4709.9  516.78  4770.4  518.73  4921.4  519.17  4931.4  518.77  4939.2  512.76
  4939.7  512.26  4943.7  512.76  4958.2  514.87  4963.2  513.30  4981.6  518.85
  5001.7  520.99  5041.8  520.91  5078.6  518.36  5083.6  520.37  5142.2  519.73
  5222.7  522.14  5655.6  525.55  5746.2  529.16  5791.5  528.11  6040.6  530.94
#Mann=3,-1,0
  3569.0    0.05       0  4939.2    0.03       0  4943.7    0.05       0
Bank Sta=4939.2,4943.7
Exp/Cntr=0.3,0.1

Type RM Length L Ch R = 1,21782,680,680,680
BEGIN DESCRIPTION:
Mapping XS ce9a5016
END DESCRIPTION:
XS GIS Cut Line= 3
      2701960.66      6951328.41      2701366.93      6950958.63
      2700289.92      6950646.45
#Sta/Elev= 30
  4305.8  520.31  4350.4  520.17  4408.2  518.45  4517.9  519.26  4539.2  518.07
  4685.5  516.51  4733.2  514.95  4865.0  514.82  4968.8  516.71  4974.7  515.94
  5008.4  515.97  5013.1  513.05  5016.0  512.48  5016.5  511.98  5020.5  512.48
  5027.1  512.50  5037.5  515.04  5046.6  515.64  5051.9  514.79  5090.6  514.48
  5289.6  515.40  5620.3  518.33  5659.1  520.07  5724.6  521.17  5870.4  521.51
  5881.4  521.98  5891.2  526.19  5901.6  522.48  5936.4  522.32  6126.6  527.66
#Mann=6,-1,0
  4305.8    0.05       0  4733.2    0.12       0  5016.0    0.07       0
  5020.5    0.12       0  5289.6    0.05       0  5936.4    0.12       0
Bank Sta=5016,5020.5
Exp/Cntr=0.3,0.1

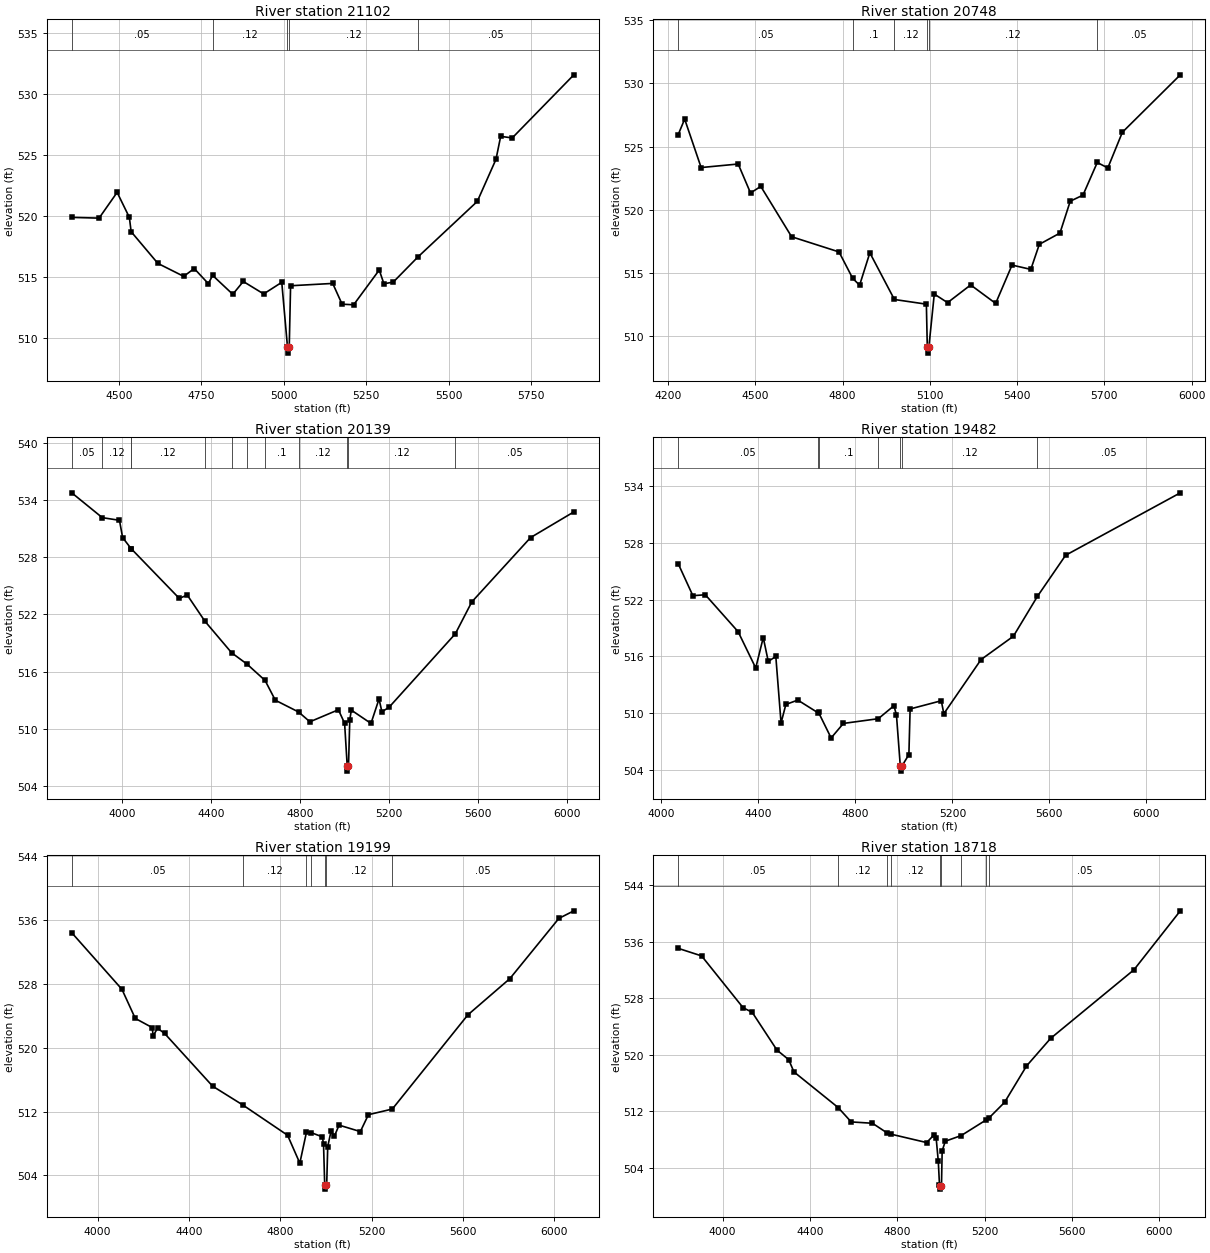
Type RM Length L Ch R = 1,21102,354,354,354
BEGIN DESCRIPTION:
Mapping XS b61f0e09
END DESCRIPTION:
XS GIS Cut Line= 3
      2702080.46      6951380.48      2701861.72      6950776.33
      2701273.19      6950120.10
#Sta/Elev= 30
  4356.4  519.89  4439.3  519.83  4494.1  521.94  4531.2  519.89  4536.6  518.72
  4617.8  516.12  4696.2  515.06  4728.1  515.70  4771.0  514.46  4783.9  515.14
  4845.1  513.59  4877.0  514.64  4938.9  513.62  4993.8  514.57  5011.2  509.27
  5012.0  508.77  5016.5  509.27  5020.6  514.29  5148.5  514.48  5176.9  512.78
  5212.0  512.73  5289.7  515.58  5303.9  514.45  5332.3  514.59  5406.8  516.64
  5587.3  521.20  5644.1  524.65  5658.3  526.53  5693.4  526.40  5880.4  531.57
#Mann=5,-1,0
  4356.4    0.05       0  4783.9    0.12       0  5011.2    0.07       0
  5016.5    0.12       0  5406.8    0.05       0
Bank Sta=5011.2,5016.5
Exp/Cntr=0.3,0.1

Type RM Length L Ch R = 1,20748,609,609,609
BEGIN DESCRIPTION:
Mapping XS 7b10596e
END DESCRIPTION:
XS GIS Cut Line= 4
      2702705.46      6951312.79      2702184.63      6950765.92
      2702038.80      6950531.54      2701622.78      6949975.11
#Sta/Elev= 30
  4235.2  525.96  4257.3  527.18  4313.9  523.35  4441.3  523.63  4483.7  521.34
  4519.0  521.86  4625.0  517.88  4787.9  516.68  4835.0  514.59  4858.7  514.05
  4893.9  516.61  4978.3  512.92  5088.2  512.55  5091.4  509.18  5092.2  508.68
  5096.9  509.18  5115.4  513.35  5161.1  512.67  5240.5  514.07  5326.4  512.61
  5382.7  515.64  5447.3  515.30  5476.5  517.28  5547.4  518.17  5582.8  520.69
  5626.6  521.17  5675.7  523.75  5712.0  523.32  5762.0  526.14  5961.2  530.68
#Mann=6,-1,0
  4235.2    0.05       0  4835.0     0.1       0  4978.3    0.12       0
  5091.4    0.07       0  5096.9    0.12       0  5675.7    0.05       0
Bank Sta=5091.4,5096.9
Exp/Cntr=0.3,0.1

Type RM Length L Ch R = 1,20139,657,657,657
BEGIN DESCRIPTION:
Mapping XS 3e178f57
END DESCRIPTION:
XS GIS Cut Line= 4
      2703423.36      6951186.94      2702533.59      6950388.31
      2702468.49      6950279.81      2701652.51      6949819.73
#Sta/Elev= 30
  3772.1  534.74  3909.4  532.14  3986.7  531.86  4000.9  530.05  4039.6  528.88
  4039.7  528.88  4255.8  523.68  4291.7  524.03  4371.0  521.29  4491.3  517.98
  4560.7  516.79  4641.8  515.08  4687.9  513.01  4792.3  511.78  4843.5  510.75
  4971.6  512.01  4999.6  510.60  5011.5  506.08  5012.4  505.58  5017.1  506.08
  5022.9  510.96  5029.9  511.97  5118.3  510.58  5154.5  513.14  5167.4  511.80
  5199.2  512.26  5497.8  519.97  5571.9  523.31  5836.3  530.05  6031.0  532.74
#Mann=12,-1,0
  3772.1    0.05       0  3909.4    0.12       0  4039.6     0.1       0
  4039.7    0.12       0  4371.0    0.05       0  4491.3     0.1       0
  4560.7    0.12       0  4641.8     0.1       0  4792.3    0.12       0
  5011.5    0.07       0  5017.1    0.12       0  5497.8    0.05       0
Bank Sta=5011.5,5017.1
Exp/Cntr=0.3,0.1

Type RM Length L Ch R = 1,19482,283,283,283
BEGIN DESCRIPTION:
Mapping XS 136b22e1
END DESCRIPTION:
XS GIS Cut Line= 3
      2703704.29      6950276.62      2702814.55      6950033.57
      2701694.79      6949777.50
#Sta/Elev= 30
  4069.2  525.79  4129.6  522.41  4180.8  522.51  4316.2  518.60  4388.8  514.76
  4419.9  517.98  4440.6  515.45  4471.7  515.98  4493.3  508.94  4513.2  510.90
  4562.4  511.36  4646.2  510.01  4647.9  510.06  4699.8  507.35  4750.5  508.89
  4894.5  509.39  4958.9  510.76  4969.3  509.79  4985.3  504.34  4986.2  503.84
  4991.0  504.34  5020.6  505.59  5025.7  510.42  5154.2  511.29  5164.8  509.92
  5318.3  515.65  5451.7  518.12  5551.1  522.35  5667.1  526.69  6140.2  533.30
#Mann=7,-1,0
  4069.2    0.05       0  4646.2    0.12       0  4647.9     0.1       0
  4894.5    0.12       0  4985.3    0.07       0  4991.0    0.12       0
  5551.1    0.05       0
Bank Sta=4985.3,4991
Exp/Cntr=0.3,0.1

Type RM Length L Ch R = 1,19199,481,481,481
BEGIN DESCRIPTION:
Mapping XS 851eb1bb
END DESCRIPTION:
XS GIS Cut Line= 4
      2704077.60      6950181.14      2703005.53      6949881.66
      2702844.93      6949755.79      2701981.26      6949582.19
#Sta/Elev= 30
  3887.2  534.43  4106.9  527.33  4165.2  523.68  4238.8  522.54  4243.9  521.50
  4262.6  522.45  4293.8  521.79  4503.8  515.18  4637.0  512.80  4832.0  509.02
  4885.6  505.52  4914.5  509.38  4935.3  509.35  4984.2  508.82  4989.4  507.91
  4994.6  502.76  4995.5  502.26  5000.3  502.76  5003.2  502.76  5007.8  507.60
  5022.2  509.52  5036.7  508.89  5057.5  510.29  5150.6  509.48  5185.9  511.60
  5290.6  512.31  5621.5  524.13  5805.1  528.67  6019.8  536.23  6085.3  537.18
#Mann=7,-1,0
  3887.2    0.05       0  4637.0    0.12       0  4914.5     0.1       0
  4935.3    0.12       0  4994.6    0.07       0  5000.3    0.12       0
  5290.6    0.05       0
Bank Sta=4994.6,5000.3
Exp/Cntr=0.3,0.1

Type RM Length L Ch R = 1,18718,323,323,323
BEGIN DESCRIPTION:
Mapping XS 454a1ac1
END DESCRIPTION:
XS GIS Cut Line= 3
      2704239.58      6949996.52      2703119.82      6949540.80
      2702034.74      6949440.98
#Sta/Elev= 30
  3797.3  535.07  3904.3  534.00  4094.3  526.67  4135.9  526.02  4249.4  520.67
  4303.0  519.32  4327.0  517.59  4529.2  512.55  4589.2  510.51  4686.5  510.32
  4754.1  508.94  4769.6  508.79  4934.4  507.59  4969.2  508.70  4978.0  508.27
  4987.9  504.92  4993.3  501.64  4996.6  501.50  4997.6  501.00  5002.5  501.50
  5005.6  506.42  5020.1  507.78  5092.8  508.58  5206.9  510.79  5220.0  511.07
  5291.3  513.28  5391.7  518.42  5502.1  522.33  5883.8  532.04  6095.9  540.38
#Mann=9,-1,0
  3797.3    0.05       0  4529.2    0.12       0  4754.1    0.05       0
  4769.6    0.12       0  4996.6    0.07       0  5002.5    0.12       0
  5092.8    0.05       0  5206.9    0.12       0  5220.0    0.05       0
Bank Sta=4996.6,5002.5
Exp/Cntr=0.3,0.1

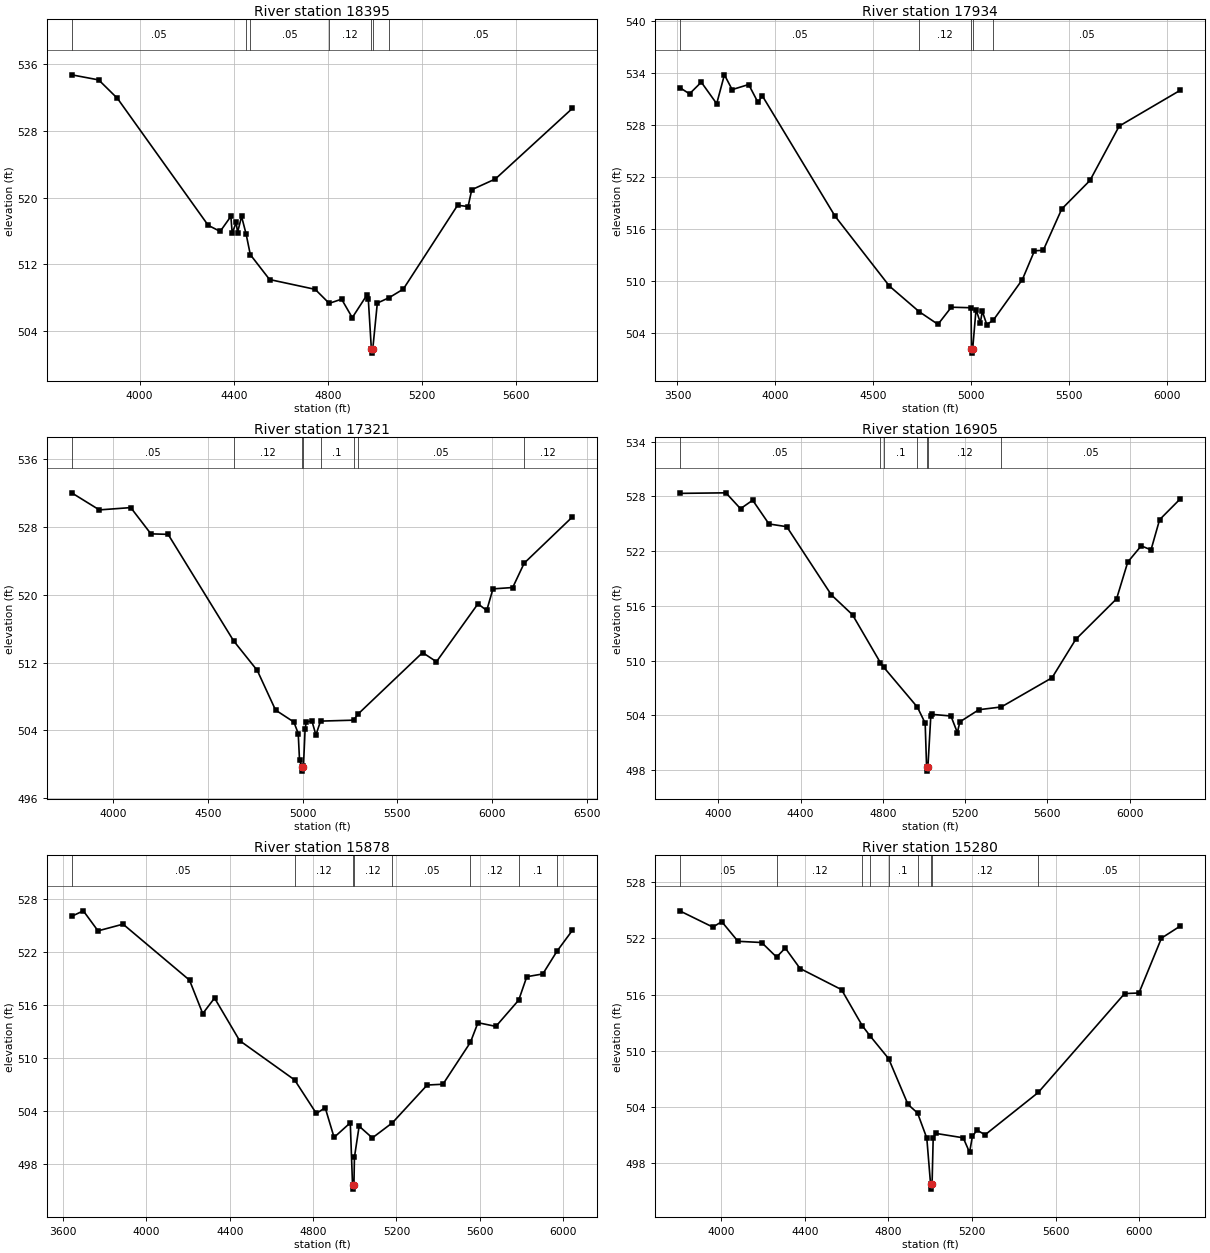
Type RM Length L Ch R = 1,18395,461,461,461
BEGIN DESCRIPTION:
Mapping XS 76eff44e
END DESCRIPTION:
XS GIS Cut Line= 3
      2704339.44      6949788.20      2703184.92      6949236.98
      2702339.78      6949171.97
#Sta/Elev= 30
  3711.6  534.74  3826.2  534.13  3905.9  531.91  4291.5  516.66  4342.4  515.93
  4387.8  517.74  4393.4  515.73  4410.5  517.01  4416.0  515.78  4433.2  517.73
  4452.3  515.64  4470.4  513.14  4552.2  510.15  4746.0  508.97  4805.5  507.29
  4858.2  507.79  4903.5  505.57  4966.0  508.30  4971.6  507.79  4984.6  501.81
  4985.6  501.31  4990.6  501.81  5009.9  507.32  5060.6  507.98  5120.3  509.00
  5350.9  519.07  5395.5  518.92  5411.1  520.94  5511.4  522.23  5838.6  530.71
#Mann=7,-1,0
  3711.6    0.05       0  4452.3    0.12       0  4470.4    0.05       0
  4805.5    0.12       0  4984.6    0.07       0  4990.6    0.12       0
  5060.6    0.05       0
Bank Sta=4984.6,4990.6
Exp/Cntr=0.3,0.1

Type RM Length L Ch R = 1,17934,613,613,613
BEGIN DESCRIPTION:
Mapping XS 6f57709d
END DESCRIPTION:
XS GIS Cut Line= 3
      2704678.84      6949383.68      2703283.01      6948842.02
      2702246.58      6949060.76
#Sta/Elev= 30
  3511.5  532.35  3561.6  531.62  3621.8  532.97  3700.4  530.48  3739.8  533.82
  3779.4  532.11  3863.8  532.70  3911.4  530.62  3932.9  531.41  4304.8  517.47
  4582.5  509.38  4734.6  506.42  4830.2  504.96  4898.3  506.94  4999.0  506.88
  5001.4  502.13  5002.4  501.63  5007.5  502.13  5024.5  506.66  5046.6  505.16
  5056.8  506.47  5079.4  504.93  5113.0  505.45  5261.2  510.14  5323.1  513.47
  5367.8  513.52  5462.2  518.30  5606.3  521.60  5755.6  527.89  6068.0  532.04
#Mann=5,-1,0
  3511.5    0.05       0  4734.6    0.12       0  5001.4    0.07       0
  5007.5    0.12       0  5113.0    0.05       0
Bank Sta=5001.4,5007.5
Exp/Cntr=0.3,0.1

Type RM Length L Ch R = 1,17321,416,416,416
BEGIN DESCRIPTION:
Mapping XS 4b715445
END DESCRIPTION:
XS GIS Cut Line= 4
      2704777.84      6949065.99      2703746.56      6948576.39
      2703642.39      6948425.35      2702378.18      6948045.57
#Sta/Elev= 30
  3779.3  531.98  3925.2  529.97  4091.3  530.24  4197.7  527.15  4288.6  527.09
  4634.4  514.56  4759.8  511.06  4856.2  506.40  4953.1  504.99  4976.0  503.64
  4982.8  500.52  4994.5  499.71  4995.6  499.21  5000.9  499.71  5003.8  499.87
  5012.5  504.22  5018.7  505.02  5048.4  505.11  5069.4  503.47  5094.0  505.10
  5268.5  505.21  5291.6  505.92  5633.1  513.17  5706.2  512.09  5925.5  518.91
  5971.8  518.13  6004.8  520.67  6109.1  520.83  6169.8  523.70  6424.4  529.14
#Mann=8,-1,0
  3779.3    0.05       0  4634.4    0.12       0  4994.5    0.07       0
  5000.9    0.12       0  5094.0     0.1       0  5268.5    0.12       0
  5291.6    0.05       0  6169.8    0.12       0
Bank Sta=4994.5,5000.9
Exp/Cntr=0.3,0.1

Type RM Length L Ch R = 1,16905,1027,1027,1027
BEGIN DESCRIPTION:
Mapping XS ca1b890b
END DESCRIPTION:
XS GIS Cut Line= 3
      2704905.81      6948819.43      2703911.05      6948189.24
      2702709.50      6947819.93
#Sta/Elev= 30
  3811.9  528.32  4036.6  528.38  4107.6  526.64  4166.8  527.57  4245.9  524.97
  4332.5  524.67  4549.3  517.20  4652.2  515.02  4787.9  509.77  4804.8  509.25
  4967.7  504.90  5005.5  503.15  5012.4  498.39  5013.5  497.89  5018.9  498.39
  5033.0  503.94  5038.2  504.11  5130.8  503.93  5162.1  502.11  5174.3  503.29
  5266.8  504.62  5375.7  504.92  5622.5  508.12  5737.5  512.32  5936.3  516.77
  5990.7  520.80  6056.1  522.57  6103.7  522.13  6145.5  525.44  6246.5  527.73
#Mann=7,-1,0
  3811.9    0.05       0  4787.9    0.12       0  4804.8     0.1       0
  4967.7    0.12       0  5012.4    0.07       0  5018.9    0.12       0
  5375.7    0.05       0
Bank Sta=5012.4,5018.9
Exp/Cntr=0.3,0.1

Type RM Length L Ch R = 1,15878,598,598,598
BEGIN DESCRIPTION:
Mapping XS 6f0697ba
END DESCRIPTION:
XS GIS Cut Line= 3
      2704937.10      6948418.41      2703937.09      6947501.74
      2702949.27      6947158.60
#Sta/Elev= 30
  3641.8  526.06  3697.6  526.68  3768.0  524.41  3888.2  525.17  4207.0  518.83
  4270.5  515.04  4327.2  516.80  4447.5  511.98  4711.3  507.53  4815.6  503.73
  4858.1  504.38  4900.7  501.02  4978.4  502.67  4989.2  495.66  4990.3  495.16
  4995.9  495.66  4998.4  498.78  5020.9  502.29  5084.2  500.96  5180.8  502.68
  5347.3  506.95  5423.0  507.04  5554.7  511.78  5591.0  514.01  5677.0  513.59
  5786.6  516.57  5825.3  519.22  5902.1  519.53  5970.6  522.12  6044.1  524.47
#Mann=8,-1,0
  3641.8    0.05       0  4711.3    0.12       0  4989.2    0.07       0
  4995.9    0.12       0  5180.8    0.05       0  5554.7    0.12       0
  5786.6     0.1       0  5970.6    0.12       0
Bank Sta=4989.2,4995.9
Exp/Cntr=0.3,0.1

Type RM Length L Ch R = 1,15280,816,816,816
BEGIN DESCRIPTION:
Mapping XS 6fe9205a
END DESCRIPTION:
XS GIS Cut Line= 4
      2705150.66      6947970.51      2704379.80      6947137.16
      2704228.76      6947074.66      2703233.93      6946611.10
#Sta/Elev= 30
  3801.3  524.96  3960.0  523.22  4002.6  523.80  4080.2  521.70  4193.6  521.57
  4265.0  520.01  4306.5  520.98  4377.4  518.79  4575.8  516.53  4674.6  512.69
  4711.3  511.61  4801.2  509.15  4893.9  504.25  4939.6  503.33  4983.9  500.65
  5002.1  495.69  5003.2  495.19  5009.1  495.69  5014.5  500.68  5027.2  501.15
  5158.2  500.68  5188.6  499.12  5202.3  500.85  5224.4  501.50  5262.8  501.00
  5517.3  505.53  5930.7  516.11  5999.3  516.17  6107.0  522.04  6197.5  523.34
#Mann=9,-1,0
  3801.3    0.05       0  4265.0    0.12       0  4674.6    0.05       0
  4711.3    0.12       0  4801.2     0.1       0  4939.6    0.12       0
  5002.1    0.07       0  5009.1    0.12       0  5517.3    0.05       0
Bank Sta=5002.1,5009.1
Exp/Cntr=0.3,0.1

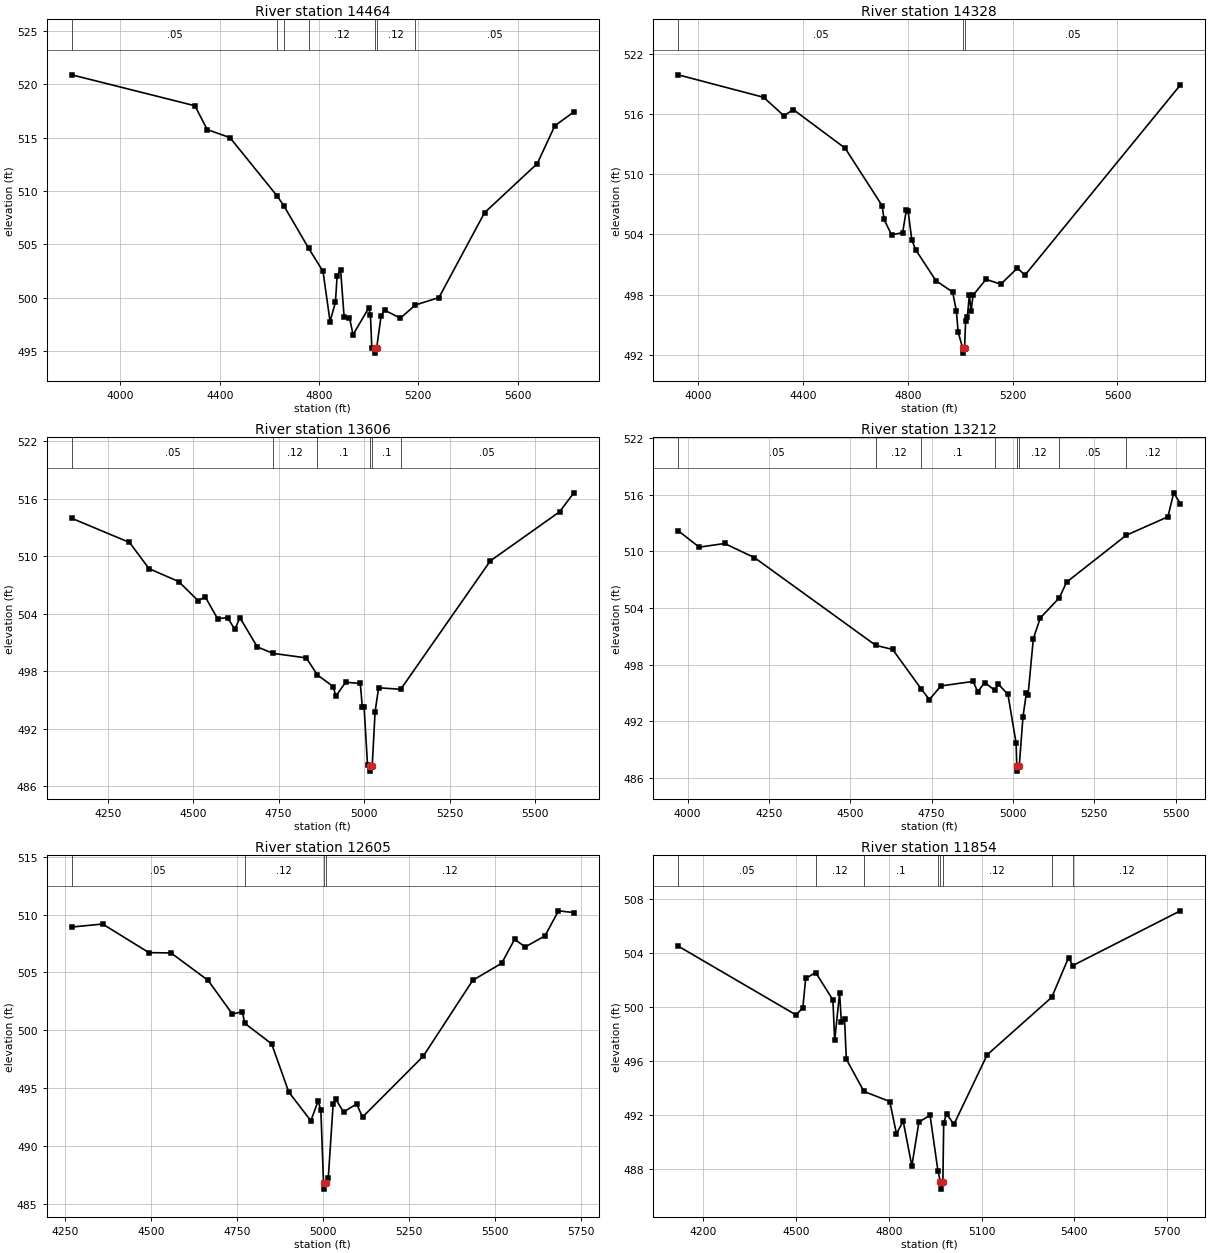
Type RM Length L Ch R = 1,14464,136,136,136
BEGIN DESCRIPTION:
Mapping XS 5663241d
END DESCRIPTION:
XS GIS Cut Line= 3
      2705261.39      6947366.51      2704443.71      6946475.92
      2703881.25      6945887.41
#Sta/Elev= 30
  3803.8  520.88  4300.0  517.98  4349.5  515.75  4441.4  514.99  4630.7  509.54
  4658.5  508.60  4758.8  504.60  4816.2  502.45  4844.6  497.75  4866.2  499.56
  4873.0  502.04  4887.1  502.59  4901.3  498.14  4922.9  498.12  4937.1  496.52
  5000.6  499.03  5007.4  498.32  5012.8  495.29  5025.2  495.29  5026.3  494.79
  5032.5  495.29  5050.0  498.25  5064.1  498.82  5128.0  498.07  5188.1  499.30
  5283.3  500.00  5467.3  507.96  5679.6  512.56  5750.4  516.11  5826.9  517.40
#Mann=7,-1,0
  3803.8    0.05       0  4630.7    0.12       0  4658.5    0.05       0
  4758.8    0.12       0  5025.2    0.07       0  5032.5    0.12       0
  5188.1    0.05       0
Bank Sta=5025.2,5032.5
Exp/Cntr=0.3,0.1

Type RM Length L Ch R = 1,14328,722,722,722
BEGIN DESCRIPTION:
Mapping XS 61ad9c3d
END DESCRIPTION:
XS GIS Cut Line= 3
      2705250.15      6947157.35      2704512.29      6946367.41
      2703952.42      6945746.77
#Sta/Elev= 30
  3923.1  519.92  4248.8  517.68  4326.9  515.83  4362.1  516.46  4560.4  512.60
  4701.6  506.86  4708.9  505.49  4737.3  503.97  4779.8  504.17  4793.9  506.42
  4800.8  506.30  4814.9  503.46  4829.1  502.49  4906.8  499.39  4970.8  498.25
  4984.9  496.37  4991.8  494.26  5009.0  492.66  5010.1  492.16  5016.3  492.66
  5020.2  495.33  5026.9  495.75  5034.4  497.96  5041.1  496.36  5048.6  497.93
  5097.9  499.52  5154.7  499.04  5218.2  500.65  5246.6  499.93  5839.9  518.90
#Mann=3,-1,0
  3923.1    0.05       0  5009.0    0.05       0  5016.3    0.05       0
Bank Sta=5009,5016.3
Exp/Cntr=0.3,0.1

Type RM Length L Ch R = 1,13606,394,394,394
BEGIN DESCRIPTION:
Mapping XS 86d972b4
END DESCRIPTION:
XS GIS Cut Line= 3
      2705211.06      6946449.85      2704724.96      6945746.75
      2704173.72      6945477.64
#Sta/Elev= 30
  4145.0  513.97  4313.8  511.45  4371.1  508.71  4457.6  507.37  4514.4  505.37
  4535.3  505.77  4571.2  503.50  4600.9  503.59  4621.8  502.37  4636.7  503.60
  4687.4  500.55  4733.7  499.87  4830.7  499.40  4863.4  497.62  4909.5  496.41
  4917.2  495.40  4946.0  496.86  4988.8  496.73  4994.5  494.30  4999.8  494.30
  5009.8  488.26  5016.1  488.08  5017.2  487.58  5023.5  488.08  5032.0  493.79
  5042.3  496.28  5106.9  496.12  5368.8  509.52  5571.5  514.65  5613.2  516.63
#Mann=6,-1,0
  4145.0    0.05       0  4733.7    0.12       0  4863.4     0.1       0
  5016.1    0.07       0  5023.5     0.1       0  5106.9    0.05       0
Bank Sta=5016.1,5023.5
Exp/Cntr=0.3,0.1

Type RM Length L Ch R = 1,13212,607,607,607
BEGIN DESCRIPTION:
Mapping XS 93838b83
END DESCRIPTION:
XS GIS Cut Line= 3
      2705461.96      6946126.40      2704732.77      6945427.59
      2704230.12      6945249.93
#Sta/Elev= 30
  3971.1  512.19  4035.6  510.45  4113.6  510.84  4205.4  509.34  4578.3  500.04
  4630.0  499.61  4717.1  495.46  4742.9  494.29  4778.4  495.74  4877.5  496.22
  4891.6  495.11  4912.7  496.10  4943.6  495.29  4955.1  495.93  4984.4  494.84
  5009.5  489.68  5011.6  487.21  5012.7  486.71  5019.1  487.21  5030.7  492.48
  5040.9  494.96  5046.2  494.77  5062.5  500.75  5083.7  502.94  5142.4  505.08
  5164.6  506.74  5347.9  511.71  5476.1  513.67  5494.0  516.21  5514.2  515.07
#Mann=8,-1,0
  3971.1    0.05       0  4578.3    0.12       0  4717.1     0.1       0
  4943.6    0.12       0  5011.6    0.07       0  5019.1    0.12       0
  5142.4    0.05       0  5347.9    0.12       0
Bank Sta=5011.6,5019.1
Exp/Cntr=0.3,0.1

Type RM Length L Ch R = 1,12605,751,751,751
BEGIN DESCRIPTION:
Mapping XS bf6266bf
END DESCRIPTION:
XS GIS Cut Line= 3
      2705665.95      6945796.54      2705214.55      6945214.92
      2704560.12      6944907.21
#Sta/Elev= 30
  4269.0  508.92  4358.5  509.18  4493.3  506.71  4557.6  506.68  4665.3  504.31
  4735.9  501.40  4764.9  501.61  4771.5  500.61  4850.0  498.83  4899.7  494.67
  4964.0  492.18  4984.9  493.88  4993.0  493.13  5000.8  486.78  5002.0  486.28
  5008.4  486.78  5014.7  487.28  5028.7  493.61  5036.8  494.03  5058.9  492.94
  5097.1  493.64  5114.1  492.50  5290.9  497.77  5434.6  504.32  5518.6  505.79
  5556.2  507.86  5587.0  507.20  5644.6  508.16  5683.7  510.32  5728.4  510.17
#Mann=4,-1,0
  4269.0    0.05       0  4771.5    0.12       0  5000.8    0.07       0
  5008.4    0.12       0
Bank Sta=5000.8,5008.4
Exp/Cntr=0.3,0.1

Type RM Length L Ch R = 1,11854,778,778,778
BEGIN DESCRIPTION:
Mapping XS 49c27270
END DESCRIPTION:
XS GIS Cut Line= 3
      2705875.86      6945360.96      2705446.39      6944591.16
      2704751.63      6944328.66
#Sta/Elev= 30
  4118.5  504.52  4500.0  499.41  4521.7  499.96  4530.7  502.12  4563.2  502.56
  4618.8  500.53  4624.6  497.52  4640.5  501.04  4646.3  498.86  4656.5  499.12
  4662.3  496.13  4719.3  493.74  4802.8  492.99  4824.5  490.59  4846.2  491.54
  4874.2  488.21  4897.1  491.47  4933.1  491.97  4958.8  487.82  4966.9  486.99
  4968.1  486.49  4974.6  486.99  4977.3  491.42  4986.8  492.08  5010.2  491.29
  5118.0  496.46  5327.0  500.73  5381.2  503.67  5395.0  503.08  5742.7  507.14
#Mann=8,-1,0
  4118.5    0.05       0  4563.2    0.12       0  4719.3     0.1       0
  4958.8    0.12       0  4966.9    0.07       0  4974.6    0.12       0
  5327.0     0.1       0  5395.0    0.12       0
Bank Sta=4966.9,4974.6
Exp/Cntr=0.3,0.1