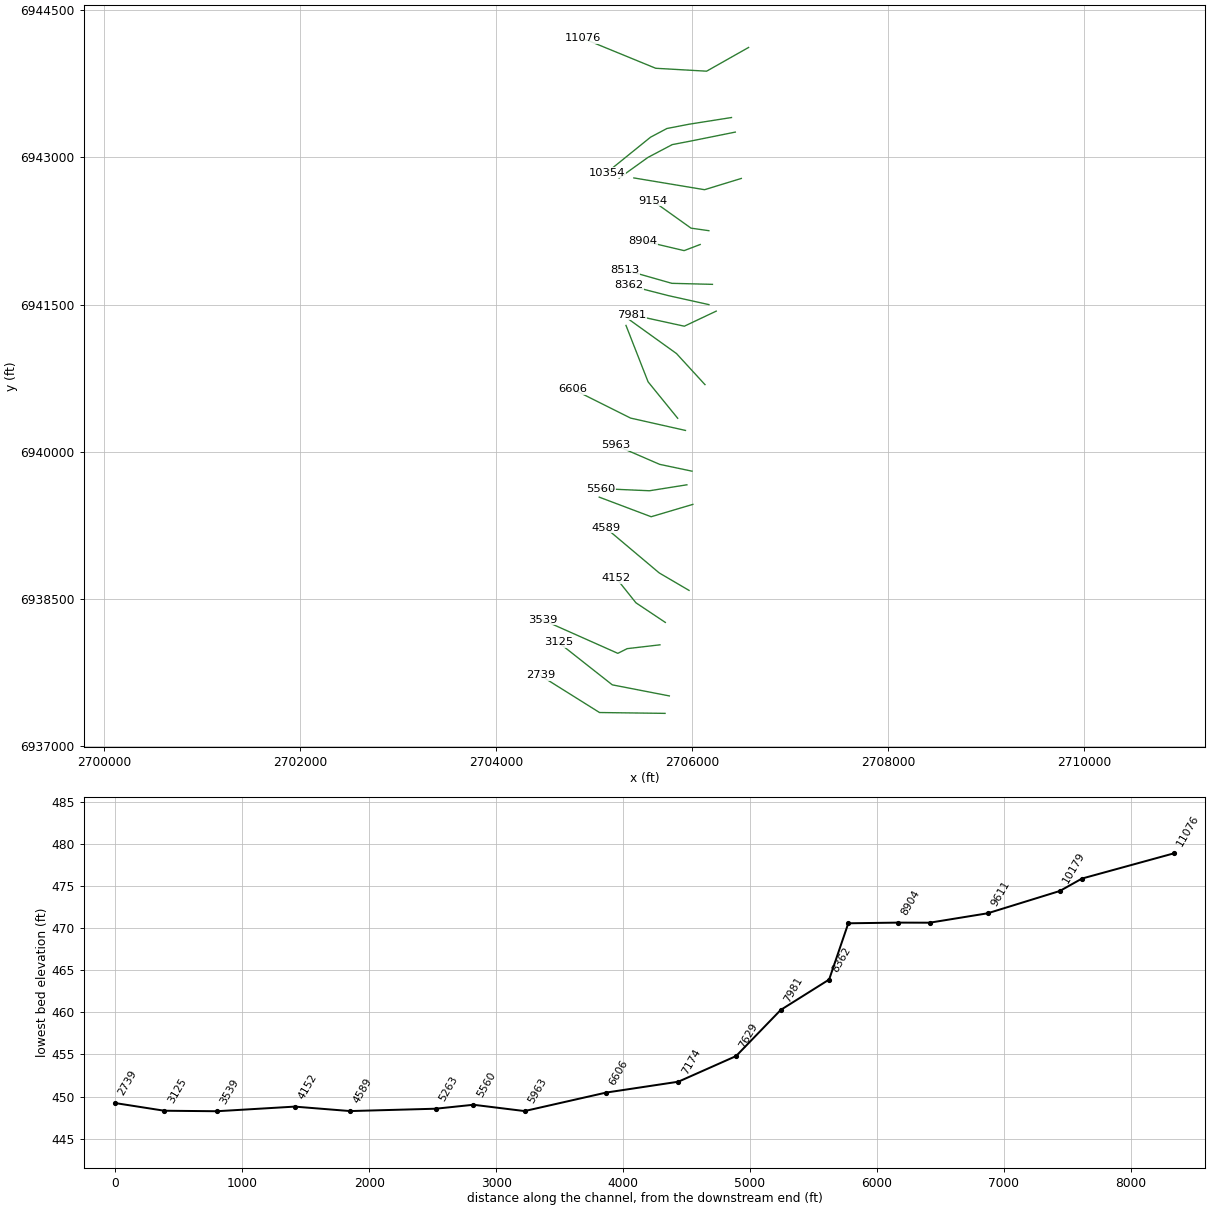
HEC-RAS study Rocky Cedar T6.prj: Rocky Cedar T6 Base Level Engineering

--- Rocky Cedar T6.g01 (geometry) --- (continued)

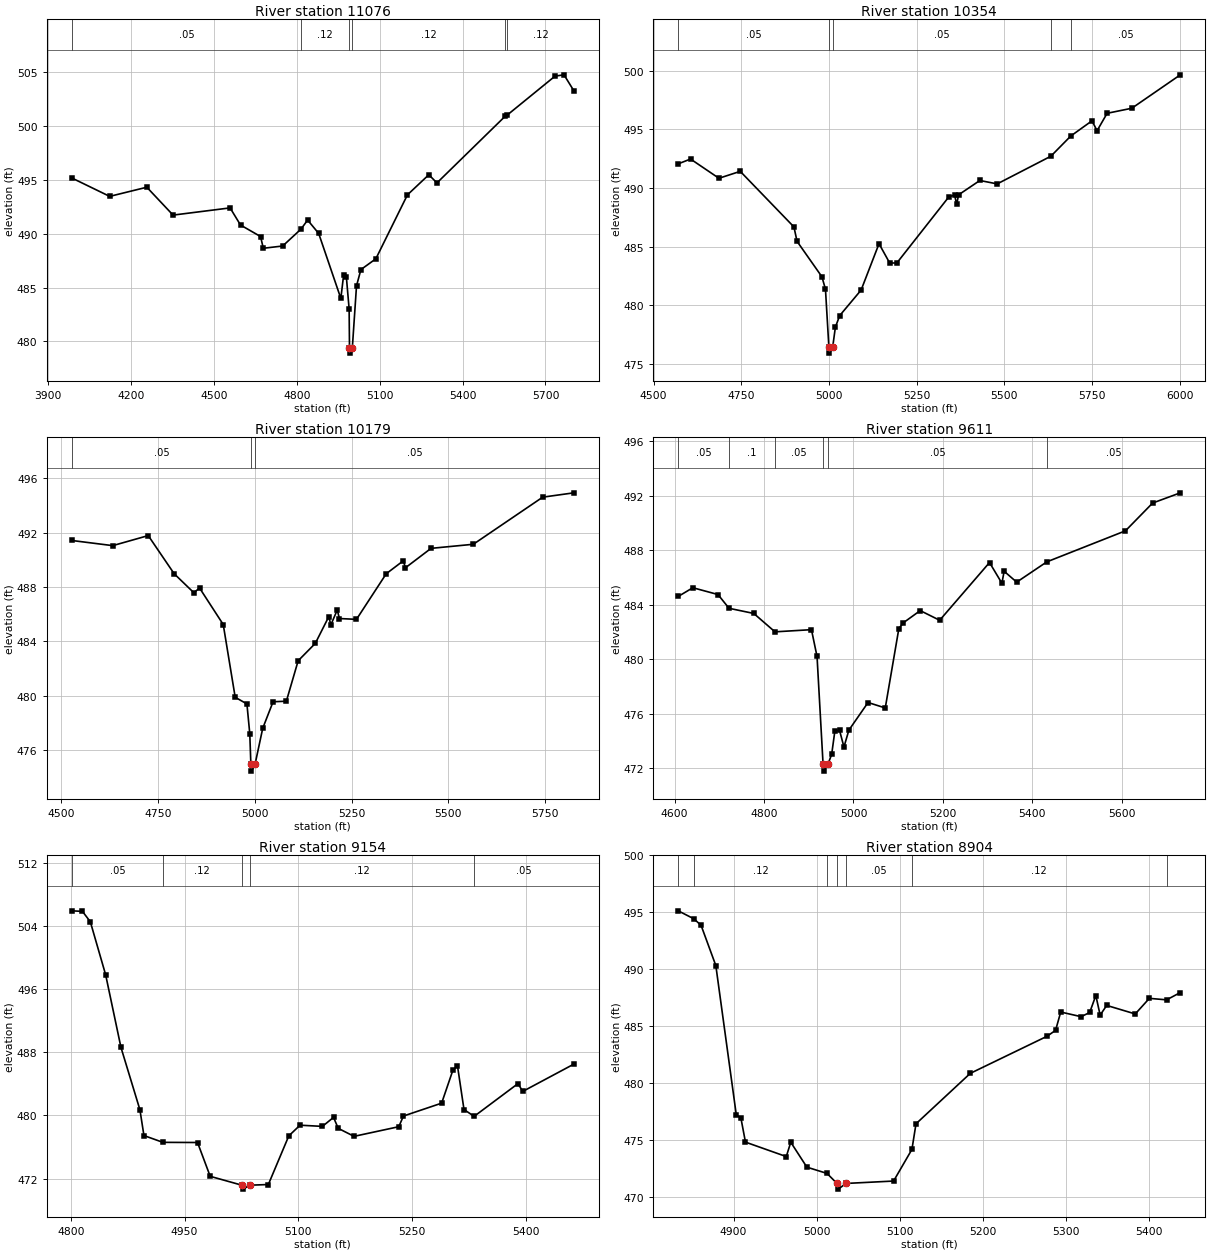
Type RM Length L Ch R = 1,11076,722,722,722
BEGIN DESCRIPTION:
Mapping XS b3c2576f
END DESCRIPTION:
XS GIS Cut Line= 4
      2706575.06      6944120.90      2706147.12      6943879.06
      2705628.06      6943908.77      2704883.08      6944213.89
#Sta/Elev= 30
  3986.2  495.18  4123.4  493.47  4257.7  494.32  4352.7  491.73  4559.0  492.40
  4596.7  490.81  4669.2  489.74  4679.2  488.65  4749.3  488.86  4815.6  490.43
  4839.5  491.27  4879.5  490.03  4959.7  483.99  4969.7  486.15  4979.7  485.98
  4989.7  483.01  4991.0  479.41  4992.5  478.91  5001.3  479.41  5016.4  485.16
  5032.3  486.67  5086.3  487.67  5200.6  493.61  5278.0  495.48  5307.4  494.72
  5554.5  500.92  5562.5  501.04  5734.7  504.64  5767.1  504.76  5802.7  503.28
#Mann=6,-1,0
  3986.2    0.05       0  4815.6    0.12       0  4991.0    0.07       0
  5001.3    0.12       0  5554.5     0.1       0  5562.5    0.12       0
Bank Sta=4991,5001.3
Exp/Cntr=0.3,0.1

Type RM Length L Ch R = 1,10354,175,175,175
BEGIN DESCRIPTION:
Mapping XS 9d59ffa3
END DESCRIPTION:
XS GIS Cut Line= 5
      2706400.66      6943406.76      2705970.98      6943339.05
      2705741.82      6943294.78      2705575.15      6943206.24
      2705128.33      6942845.14
#Sta/Elev= 30
  4570.1  492.06  4605.2  492.47  4686.2  490.83  4746.9  491.42  4900.0  486.68
  4908.9  485.45  4979.8  482.43  4989.9  481.37  4999.7  476.42  5001.2  475.92
  5010.4  476.42  5018.2  478.14  5030.5  479.12  5091.6  481.30  5142.6  485.25
  5173.1  483.60  5193.5  483.61  5341.9  489.25  5358.2  489.40  5363.9  488.60
  5369.6  489.42  5430.1  490.64  5479.6  490.35  5632.6  492.71  5689.3  494.43
  5749.9  495.73  5764.3  494.88  5793.0  496.37  5863.4  496.80  6001.7  499.65
#Mann=5,-1,0
  4570.1    0.05       0  4999.7    0.03       0  5010.4    0.05       0
  5632.6    0.12       0  5689.3    0.05       0
Bank Sta=4999.7,5010.4
Exp/Cntr=0.3,0.1

Type RM Length L Ch R = 1,10179,568,568,568
BEGIN DESCRIPTION:
Mapping XS 278e94b6
END DESCRIPTION:
XS GIS Cut Line= 5
      2706439.75      6943258.33      2705986.61      6943167.18
      2705796.50      6943130.72      2705549.11      6943000.51
      2705254.85      6942789.58
#Sta/Elev= 30
  4526.9  491.43  4632.7  491.05  4724.5  491.79  4791.5  488.98  4842.4  487.58
  4857.1  487.93  4918.3  485.24  4949.2  479.88  4979.5  479.39  4986.9  477.19
  4989.7  474.94  4991.2  474.44  5000.5  474.94  5020.3  477.59  5047.1  479.55
  5081.4  479.59  5111.9  482.57  5156.2  483.85  5190.9  485.81  5196.5  485.22
  5212.9  486.31  5218.5  485.68  5262.6  485.62  5339.5  488.98  5383.5  489.93
  5389.2  489.42  5455.3  490.85  5564.5  491.15  5743.8  494.62  5824.3  494.94
#Mann=3,-1,0
  4526.9    0.05       0  4989.7    0.04       0  5000.5    0.05       0
Bank Sta=4989.7,5000.5
Exp/Cntr=0.3,0.1

Type RM Length L Ch R = 1,9611,457,457,457
BEGIN DESCRIPTION:
Rocky Cedar T6 13.0
END DESCRIPTION:
XS GIS Cut Line= 3
      2706500.97      6942785.99      2706126.17      6942671.15
      2705404.97      6942791.10
#Sta/Elev= 30
  4608.0  484.62  4640.7  485.26  4696.9  484.76  4721.6  483.75  4777.0  483.37
  4824.4  482.02  4906.0  482.18  4918.5  480.21  4932.0  472.29  4933.5  471.79
  4942.8  472.29  4951.2  473.02  4958.3  474.72  4968.8  474.79  4978.7  473.56
  4989.7  474.80  5032.6  476.83  5071.1  476.43  5101.5  482.26  5111.7  482.69
  5149.3  483.58  5192.8  482.87  5304.3  487.11  5332.0  485.59  5337.0  486.47
  5365.1  485.67  5432.5  487.16  5608.4  489.44  5669.2  491.48  5731.1  492.23
#Mann=6,-1,0
  4608.0    0.05       0  4721.6     0.1       0  4824.4    0.05       0
  4932.0    0.07       0  4942.8    0.05       0  5432.5    0.05       0
Bank Sta=4932,4942.8
Exp/Cntr=0.3,0.1

Type RM Length L Ch R = 1,9154,250,250,250
BEGIN DESCRIPTION:
Mapping XS 2a9121e4
END DESCRIPTION:
XS GIS Cut Line= 3
      2706170.24      6942253.33      2705987.91      6942279.37
      2705598.67      6942557.03
#Sta/Elev= 30
  4801.2  505.89  4815.3  505.82  4825.7  504.50  4845.9  497.79  4866.1  488.60
  4891.1  480.71  4896.4  477.45  4921.4  476.59  4967.1  476.57  4983.8  472.29
  5025.5  471.17  5027.0  470.67  5036.4  471.17  5060.5  471.25  5087.5  477.41
  5102.3  478.76  5131.8  478.61  5146.5  479.75  5152.7  478.36  5173.6  477.35
  5232.6  478.57  5238.7  479.92  5289.1  481.55  5303.9  485.71  5310.0  486.28
  5318.6  480.74  5332.0  479.88  5389.9  484.03  5396.0  483.03  5463.5  486.49
#Mann=5,-1,0
  4801.2    0.05       0  4921.4    0.12       0  5025.5    0.07       0
  5036.4    0.12       0  5332.0    0.05       0
Bank Sta=5025.5,5036.4
Exp/Cntr=0.3,0.1

Type RM Length L Ch R = 1,8904,391,391,391
BEGIN DESCRIPTION:
Mapping XS cbb81fbc
END DESCRIPTION:
XS GIS Cut Line= 3
      2706081.71      6942112.72      2705917.60      6942050.21
      2705499.69      6942148.84
#Sta/Elev= 30
  4833.3  495.13  4852.1  494.43  4860.8  493.86  4878.6  490.32  4903.3  477.18
  4908.7  476.97  4914.3  474.81  4963.5  473.54  4968.9  474.80  4988.3  472.61
  5012.6  472.06  5024.6  471.18  5026.1  470.68  5035.5  471.18  5092.8  471.39
  5114.9  474.17  5119.8  476.42  5185.2  480.85  5277.7  484.11  5288.0  484.63
  5294.2  486.24  5318.8  485.83  5329.1  486.20  5336.5  487.69  5341.7  485.97
  5349.6  486.82  5384.0  486.07  5401.0  487.44  5421.8  487.31  5438.3  487.95
#Mann=7,-1,0
  4833.3    0.05       0  4852.1    0.12       0  5012.6    0.05       0
  5024.6    0.07       0  5035.5    0.05       0  5114.9    0.12       0
  5421.8    0.05       0
Bank Sta=5024.6,5035.5
Exp/Cntr=0.3,0.1

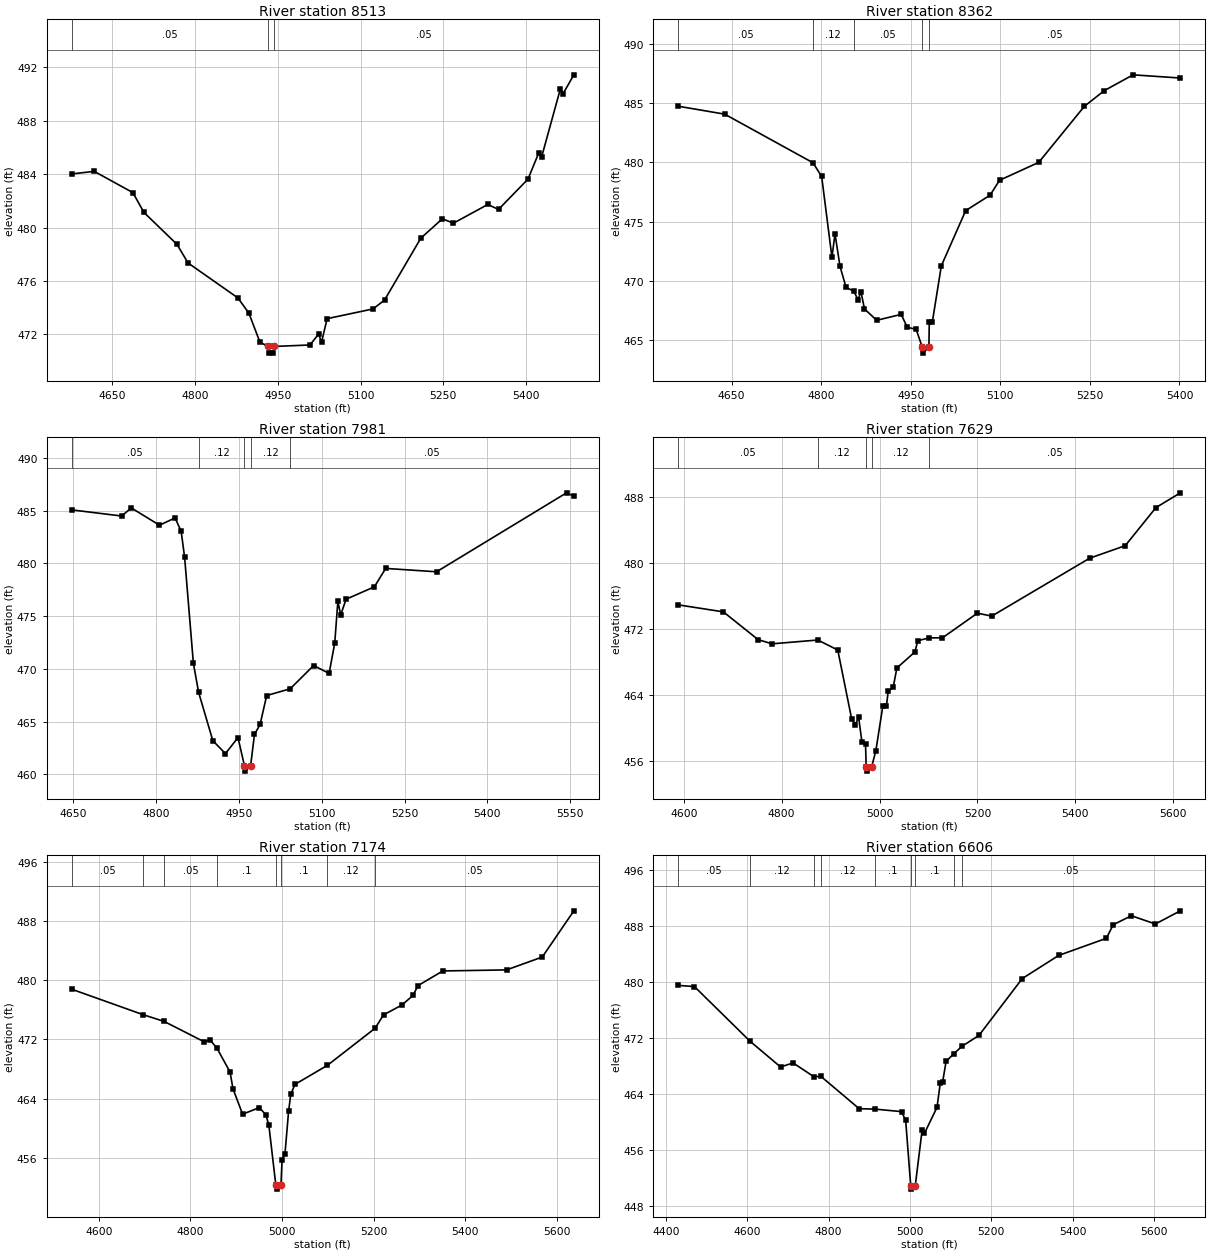
Type RM Length L Ch R = 1,8513,151,151,151
BEGIN DESCRIPTION:
Mapping XS 2006ba25
END DESCRIPTION:
XS GIS Cut Line= 3
      2706206.67      6941706.46      2705792.60      6941716.87
      2705316.07      6941852.28
#Sta/Elev= 30
  4576.9  484.02  4617.6  484.21  4687.6  482.62  4707.6  481.14  4767.6  478.74
  4787.6  477.35  4877.7  474.74  4897.7  473.60  4917.7  471.43  4932.1  471.10
  4933.6  470.60  4941.7  470.60  4943.2  471.10  5008.4  471.21  5024.2  472.03
  5029.4  471.41  5039.5  473.18  5122.7  473.91  5143.5  474.57  5209.3  479.21
  5248.3  480.66  5268.3  480.33  5330.6  481.73  5350.0  481.36  5403.4  483.63
  5423.0  485.60  5428.2  485.30  5462.1  490.39  5467.2  490.04  5486.5  491.44
#Mann=3,-1,0
  4576.9    0.05       0  4932.1   0.035       0  4943.2    0.05       0
Bank Sta=4932.1,4943.2
Exp/Cntr=0.3,0.1

Type RM Length L Ch R = 1,8362,381,381,381
BEGIN DESCRIPTION:
Mapping XS e491f02b
END DESCRIPTION:
XS GIS Cut Line= 3
      2706170.48      6941499.94      2705759.00      6941591.09
      2705352.79      6941695.25
#Sta/Elev= 30
  4560.6  484.75  4638.4  484.08  4786.2  479.98  4800.8  478.82  4818.0  471.99
  4823.1  473.98  4831.5  471.24  4841.7  469.45  4854.4  469.15  4861.6  468.43
  4866.7  469.07  4872.5  467.64  4892.9  466.68  4933.9  467.18  4944.2  466.09
  4959.0  465.92  4969.3  464.41  4970.8  463.91  4980.4  464.41  4981.0  466.56
  4986.2  466.56  5001.2  471.28  5042.0  475.94  5082.8  477.24  5098.7  478.50
  5164.3  480.01  5240.7  484.74  5274.2  486.07  5322.3  487.40  5401.4  487.13
#Mann=5,-1,0
  4560.6    0.05       0  4786.2    0.12       0  4854.4    0.05       0
  4969.3   0.035       0  4980.4    0.05       0
Bank Sta=4969.3,4980.4
Exp/Cntr=0.3,0.1

Type RM Length L Ch R = 1,7981,352,352,352
BEGIN DESCRIPTION:
Mapping XS b4f916b3
END DESCRIPTION:
XS GIS Cut Line= 3
      2706245.12      6941433.54      2705919.59      6941279.89
      2705383.11      6941397.09
#Sta/Elev= 30
  4647.4  485.08  4737.9  484.50  4755.1  485.27  4806.2  483.63  4834.5  484.32
  4845.5  483.04  4851.7  480.60  4867.6  470.53  4877.1  467.77  4902.8  463.19
  4925.6  461.96  4948.4  463.48  4960.1  460.80  4961.6  460.30  4971.2  460.80
  4978.2  463.78  4988.4  464.73  5000.3  467.47  5042.9  468.11  5085.3  470.32
  5113.4  469.57  5123.6  472.47  5129.2  476.42  5134.3  475.11  5144.1  476.61
  5195.3  477.78  5215.8  479.53  5307.9  479.21  5543.3  486.70  5556.5  486.39
#Mann=5,-1,0
  4647.4    0.05       0  4877.1    0.12       0  4960.1    0.07       0
  4971.2    0.12       0  5042.9    0.05       0
Bank Sta=4960.1,4971.2
Exp/Cntr=0.3,0.1

Type RM Length L Ch R = 1,7629,455,455,455
BEGIN DESCRIPTION:
Mapping XS d971ec44
END DESCRIPTION:
XS GIS Cut Line= 3
      2706130.23      6940684.65      2705839.46      6941001.46
      2705355.55      6941348.66
#Sta/Elev= 30
  4588.8  474.95  4681.0  474.10  4751.9  470.74  4780.3  470.23  4873.9  470.69
  4914.7  469.48  4943.1  461.12  4950.3  460.43  4957.3  461.32  4964.0  458.36
  4971.4  458.12  4972.7  455.31  4974.2  454.81  4983.8  455.31  4992.4  457.26
  5006.6  462.64  5014.0  462.66  5017.7  464.48  5027.9  464.96  5035.4  467.30
  5072.1  469.24  5078.3  470.61  5101.4  470.95  5128.6  470.96  5199.8  473.94
  5229.3  473.59  5429.2  480.60  5501.9  482.12  5564.6  486.73  5614.4  488.52
#Mann=5,-1,0
  4588.8    0.05       0  4873.9    0.12       0  4972.7    0.07       0
  4983.8    0.12       0  5101.4    0.05       0
Bank Sta=4972.7,4983.8
Exp/Cntr=0.3,0.1

Type RM Length L Ch R = 1,7174,568,568,568
BEGIN DESCRIPTION:
Mapping XS 24a9fbc3
END DESCRIPTION:
XS GIS Cut Line= 3
      2705851.99      6940341.67      2705549.89      6940713.23
      2705324.91      6941287.78
#Sta/Elev= 30
  4541.0  478.76  4696.3  475.33  4742.7  474.41  4829.0  471.69  4843.4  471.87
  4858.0  470.79  4886.5  467.57  4892.9  465.31  4913.9  461.88  4950.4  462.77
  4964.8  461.79  4971.2  460.38  4986.5  452.26  4988.0  451.76  4997.6  452.26
  5000.0  455.73  5006.4  456.55  5014.3  462.30  5019.0  464.57  5028.2  465.91
  5099.0  468.48  5203.1  473.49  5221.5  475.30  5261.4  476.62  5285.8  477.92
  5296.7  479.25  5350.9  481.23  5490.0  481.37  5568.0  483.11  5636.9  489.35
#Mann=8,-1,0
  4541.0    0.05       0  4696.3    0.12       0  4742.7    0.05       0
  4858.0     0.1       0  4986.5    0.07       0  4997.6     0.1       0
  5099.0    0.12       0  5203.1    0.05       0
Bank Sta=4986.5,4997.6
Exp/Cntr=0.3,0.1

Type RM Length L Ch R = 1,6606,643,643,643
BEGIN DESCRIPTION:
Mapping XS 83024ab0
END DESCRIPTION:
XS GIS Cut Line= 3
      2705931.34      6940217.62      2705371.46      6940343.48
      2704781.18      6940638.62
#Sta/Elev= 30
  4430.5  479.54  4470.3  479.37  4607.2  471.56  4682.0  467.90  4712.7  468.48
  4763.3  466.53  4781.3  466.55  4875.3  461.94  4913.3  461.89  4979.2  461.53
  4989.4  460.27  5001.8  450.97  5003.4  450.47  5013.0  450.97  5029.8  458.90
  5035.4  458.41  5066.4  462.14  5074.5  465.62  5080.1  465.71  5088.7  468.69
  5107.6  469.79  5128.5  470.88  5169.5  472.40  5275.8  480.51  5365.2  483.81
  5482.6  486.26  5499.4  488.20  5544.1  489.48  5603.0  488.30  5664.3  490.18
#Mann=9,-1,0
  4430.5    0.05       0  4607.2    0.12       0  4763.3     0.1       0
  4781.3    0.12       0  4913.3     0.1       0  5001.8    0.07       0
  5013.0     0.1       0  5107.6    0.12       0  5128.5    0.05       0
Bank Sta=5001.8,5013
Exp/Cntr=0.3,0.1

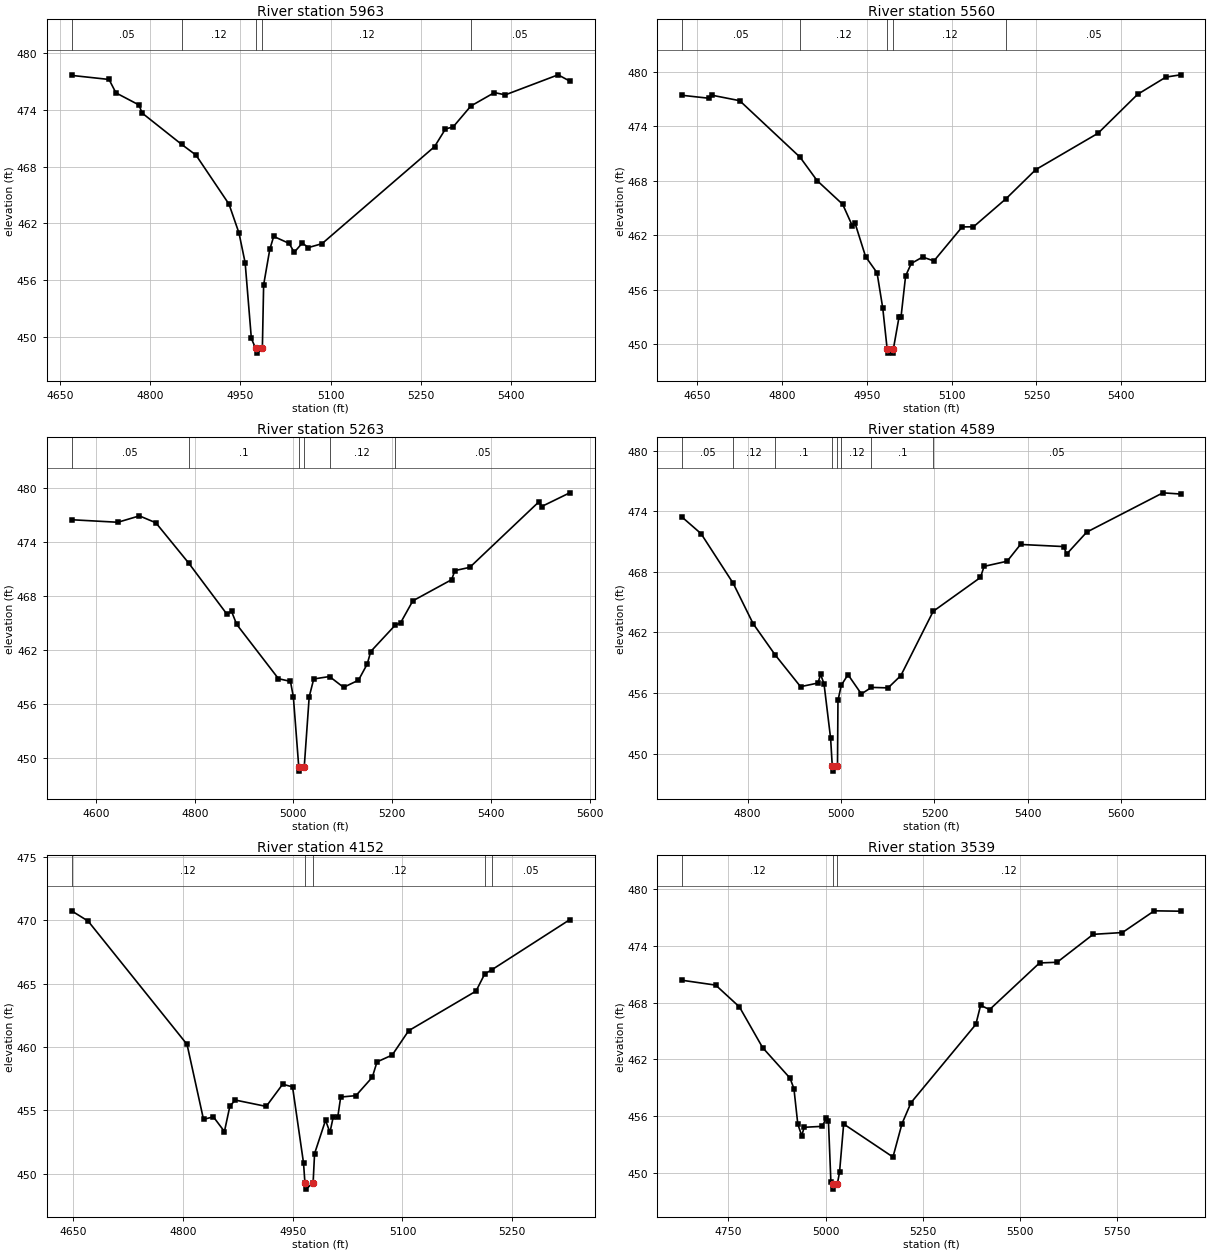
Type RM Length L Ch R = 1,5963,403,403,403
BEGIN DESCRIPTION:
Mapping XS ac891f1c
END DESCRIPTION:
XS GIS Cut Line= 3
      2705998.15      6939802.40      2705668.34      6939871.84
      2705218.30      6940066.56
#Sta/Elev= 30
  4669.7  477.66  4731.9  477.23  4743.4  475.81  4781.7  474.53  4786.8  473.68
  4852.7  470.35  4876.3  469.23  4931.2  464.03  4947.8  460.97  4958.0  457.83
  4968.3  449.83  4975.4  448.77  4977.0  448.27  4986.6  448.77  4988.7  455.49
  4998.9  459.24  5005.4  460.62  5031.1  459.88  5039.5  458.94  5052.9  459.92
  5063.0  459.44  5085.6  459.85  5272.6  470.12  5290.7  471.99  5303.5  472.21
  5332.9  474.42  5372.0  475.84  5390.1  475.60  5477.8  477.72  5497.1  477.06
#Mann=5,-1,0
  4669.7    0.05       0  4852.7    0.12       0  4975.4    0.07       0
  4986.6    0.12       0  5332.9    0.05       0
Bank Sta=4975.4,4986.6
Exp/Cntr=0.3,0.1

Type RM Length L Ch R = 1,5560,297,297,297
BEGIN DESCRIPTION:
Mapping XS 4e4197d7
END DESCRIPTION:
XS GIS Cut Line= 3
      2705946.12      6939663.50      2705564.17      6939602.74
      2705070.20      6939624.40
#Sta/Elev= 30
  4623.7  477.43  4670.4  477.11  4675.5  477.45  4725.1  476.84  4831.9  470.61
  4862.1  468.03  4907.3  465.42  4924.3  463.06  4929.3  463.32  4947.8  459.66
  4968.1  457.87  4978.2  453.98  4985.9  449.52  4987.5  449.02  4995.6  449.02
  4997.1  449.52  5007.0  453.00  5010.5  453.00  5018.6  457.52  5028.6  458.90
  5048.7  459.61  5068.7  459.18  5118.7  462.93  5138.7  462.94  5196.5  466.05
  5248.8  469.24  5359.0  473.25  5429.0  477.54  5479.1  479.44  5504.9  479.69
#Mann=5,-1,0
  4623.7    0.05       0  4831.9    0.12       0  4985.9    0.07       0
  4997.1    0.12       0  5196.5    0.05       0
Bank Sta=4985.9,4997.1
Exp/Cntr=0.3,0.1

Type RM Length L Ch R = 1,5263,674,674,674
BEGIN DESCRIPTION:
Mapping XS 8c29bc54
END DESCRIPTION:
XS GIS Cut Line= 3
      2706006.83      6939463.84      2705581.53      6939337.98
      2705052.05      6939537.62
#Sta/Elev= 30
  4550.5  476.48  4644.3  476.20  4688.0  476.91  4721.3  476.14  4787.6  471.68
  4864.7  466.03  4874.7  466.29  4885.1  464.85  4969.7  458.82  4994.0  458.52
  4999.9  456.80  5010.8  449.05  5012.3  448.55  5022.0  449.05  5032.0  456.81
  5041.2  458.79  5073.2  459.06  5101.6  457.86  5131.8  458.65  5149.6  460.45
  5156.7  461.84  5206.2  464.76  5217.1  465.02  5242.0  467.47  5320.6  469.82
  5327.2  470.83  5357.4  471.19  5497.8  478.49  5503.1  477.95  5559.9  479.47
#Mann=6,-1,0
  4550.5    0.05       0  4787.6     0.1       0  5010.8    0.07       0
  5022.0     0.1       0  5073.2    0.12       0  5206.2    0.05       0
Bank Sta=5010.8,5022
Exp/Cntr=0.3,0.1

Type RM Length L Ch R = 1,4589,437,437,437
BEGIN DESCRIPTION:
Mapping XS c22e4d0f
END DESCRIPTION:
XS GIS Cut Line= 3
      2705967.78      6938587.13      2705664.00      6938765.06
      2705117.13      6939225.13
#Sta/Elev= 30
  4660.2  473.39  4700.2  471.78  4769.1  466.86  4811.7  462.87  4858.7  459.79
  4913.3  456.63  4950.5  456.99  4956.3  457.85  4963.6  456.89  4977.7  451.50
  4981.2  448.77  4982.7  448.27  4992.4  448.77  4993.4  455.27  5000.6  456.78
  5014.9  457.82  5043.5  455.91  5065.1  456.56  5100.7  456.51  5128.1  457.73
  5197.3  464.09  5298.5  467.44  5306.3  468.54  5355.7  469.05  5384.3  470.71
  5476.6  470.50  5483.2  469.76  5526.1  471.93  5689.2  475.82  5726.9  475.70
#Mann=8,-1,0
  4660.2    0.05       0  4769.1    0.12       0  4858.7     0.1       0
  4981.2    0.07       0  4992.4     0.1       0  5000.6    0.12       0
  5065.1     0.1       0  5197.3    0.05       0
Bank Sta=4981.2,4992.4
Exp/Cntr=0.3,0.1

Type RM Length L Ch R = 1,4152,613,613,613
BEGIN DESCRIPTION:
Rocky Cedar T6 3.0
END DESCRIPTION:
XS GIS Cut Line= 3
      2705726.04      6938260.97      2705426.00      6938461.00
      2705225.97      6938711.03
#Sta/Elev= 30
  4647.8  470.74  4670.4  469.93  4805.6  460.21  4828.1  454.30  4841.6  454.50
  4856.7  453.34  4864.2  455.36  4871.7  455.82  4913.8  455.32  4936.3  457.07
  4949.8  456.86  4964.8  450.86  4966.7  449.30  4968.2  448.80  4977.9  449.30
  4979.9  451.60  4994.9  454.23  5000.9  453.27  5005.4  454.49  5011.6  454.49
  5015.6  456.06  5036.4  456.17  5058.8  457.62  5065.2  458.83  5086.0  459.37
  5108.5  461.29  5200.5  464.41  5212.4  465.76  5222.6  466.11  5328.6  470.04
#Mann=5,-1,0
  4647.8    0.12       0  4966.7    0.07       0  4977.9    0.12       0
  5212.4     0.1       0  5222.6    0.05       0
Bank Sta=4966.7,4977.9
Exp/Cntr=0.3,0.1

Type RM Length L Ch R = 1,3539,414,414,414
BEGIN DESCRIPTION:
Mapping XS 898b820f
END DESCRIPTION:
XS GIS Cut Line= 4
      2705671.32      6938032.57      2705337.14      6937993.51
      2705241.66      6937945.76      2704474.31      6938286.75
#Sta/Elev= 30
  4631.2  470.37  4717.1  469.86  4778.2  467.55  4837.9  463.24  4908.4  460.01
  4918.5  458.90  4928.5  455.14  4938.6  453.91  4944.9  454.80  4991.3  454.90
  5001.8  455.77  5007.4  455.45  5013.7  449.05  5018.2  448.75  5019.9  448.25
  5030.1  448.75  5036.0  450.04  5046.6  455.15  5173.6  451.65  5196.8  455.18
  5220.1  457.41  5387.0  465.70  5399.3  467.72  5422.5  467.27  5551.1  472.21
  5596.3  472.28  5689.3  475.24  5764.5  475.43  5846.6  477.73  5914.1  477.69
#Mann=3,-1,0
  4631.2    0.12       0  5018.2    0.07       0  5030.1    0.12       0
Bank Sta=5018.2,5030.1
Exp/Cntr=0.3,0.1

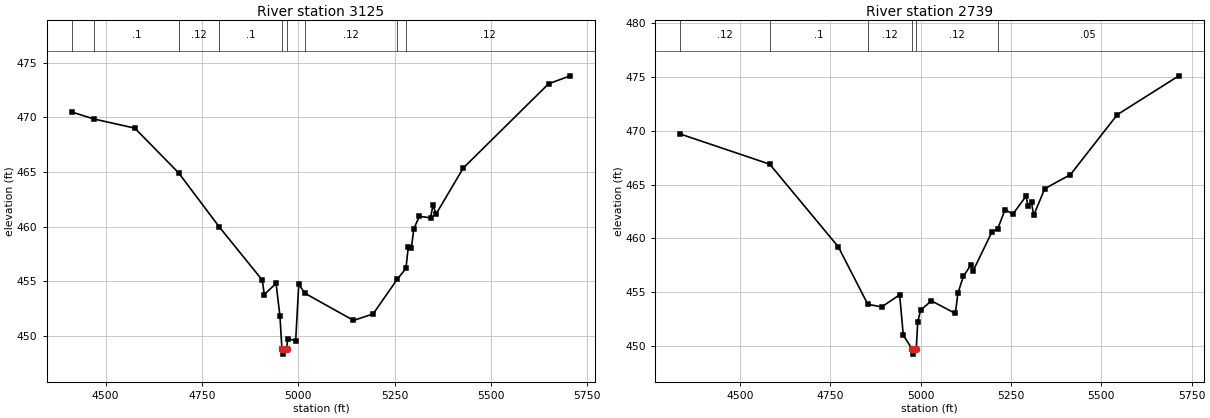
Type RM Length L Ch R = 1,3125,386,386,386
BEGIN DESCRIPTION:
Mapping XS 639b2a39
END DESCRIPTION:
XS GIS Cut Line= 3
      2705766.84      6937511.74      2705185.23      6937624.58
      2704634.05      6938058.59
#Sta/Elev= 30
  4411.7  470.50  4470.1  469.85  4575.5  469.02  4689.4  464.92  4795.5  459.94
  4906.6  455.09  4911.7  453.77  4942.3  454.79  4952.4  451.79  4957.5  448.81
  4959.1  448.31  4969.4  448.81  4972.8  449.74  4993.2  449.52  5001.2  454.70
  5017.5  453.88  5143.2  451.40  5194.1  451.99  5256.4  455.15  5279.3  456.16
  5285.4  458.13  5293.5  458.04  5299.8  459.80  5314.3  460.94  5343.2  460.80
  5349.5  461.96  5357.6  461.15  5428.1  465.36  5649.5  473.08  5705.7  473.81
#Mann=9,-1,0
  4411.7    0.12       0  4470.1     0.1       0  4689.4    0.12       0
  4795.5     0.1       0  4957.5    0.07       0  4969.4     0.1       0
  5017.5    0.12       0  5256.4    0.05       0  5279.3    0.12       0
Bank Sta=4957.5,4969.4
Exp/Cntr=0.3,0.1

Type RM Length L Ch R = 1,2739,274,274,274
BEGIN DESCRIPTION:
Mapping XS a6f5a928
END DESCRIPTION:
XS GIS Cut Line= 3
      2705723.44      6937333.79      2705055.03      6937342.47
      2704451.73      6937720.07
#Sta/Elev= 30
  4334.4  469.70  4582.1  466.89  4771.9  459.21  4853.6  453.86  4891.9  453.61
  4941.9  454.74  4951.9  450.98  4975.9  449.72  4977.6  449.22  4987.8  449.72
  4991.9  452.22  4999.9  453.31  5029.8  454.18  5096.1  453.00  5102.9  454.87
  5118.2  456.45  5139.4  457.54  5145.3  456.98  5197.2  460.58  5213.5  460.90
  5233.7  462.67  5255.0  462.23  5291.5  463.91  5297.4  463.00  5306.8  463.34
  5312.7  462.12  5343.4  464.61  5414.6  465.92  5544.4  471.50  5714.6  475.11
#Mann=6,-1,0
  4334.4    0.12       0  4582.1     0.1       0  4853.6    0.12       0
  4975.9    0.07       0  4987.8    0.12       0  5213.5    0.05       0
Bank Sta=4975.9,4987.8
Exp/Cntr=0.3,0.1