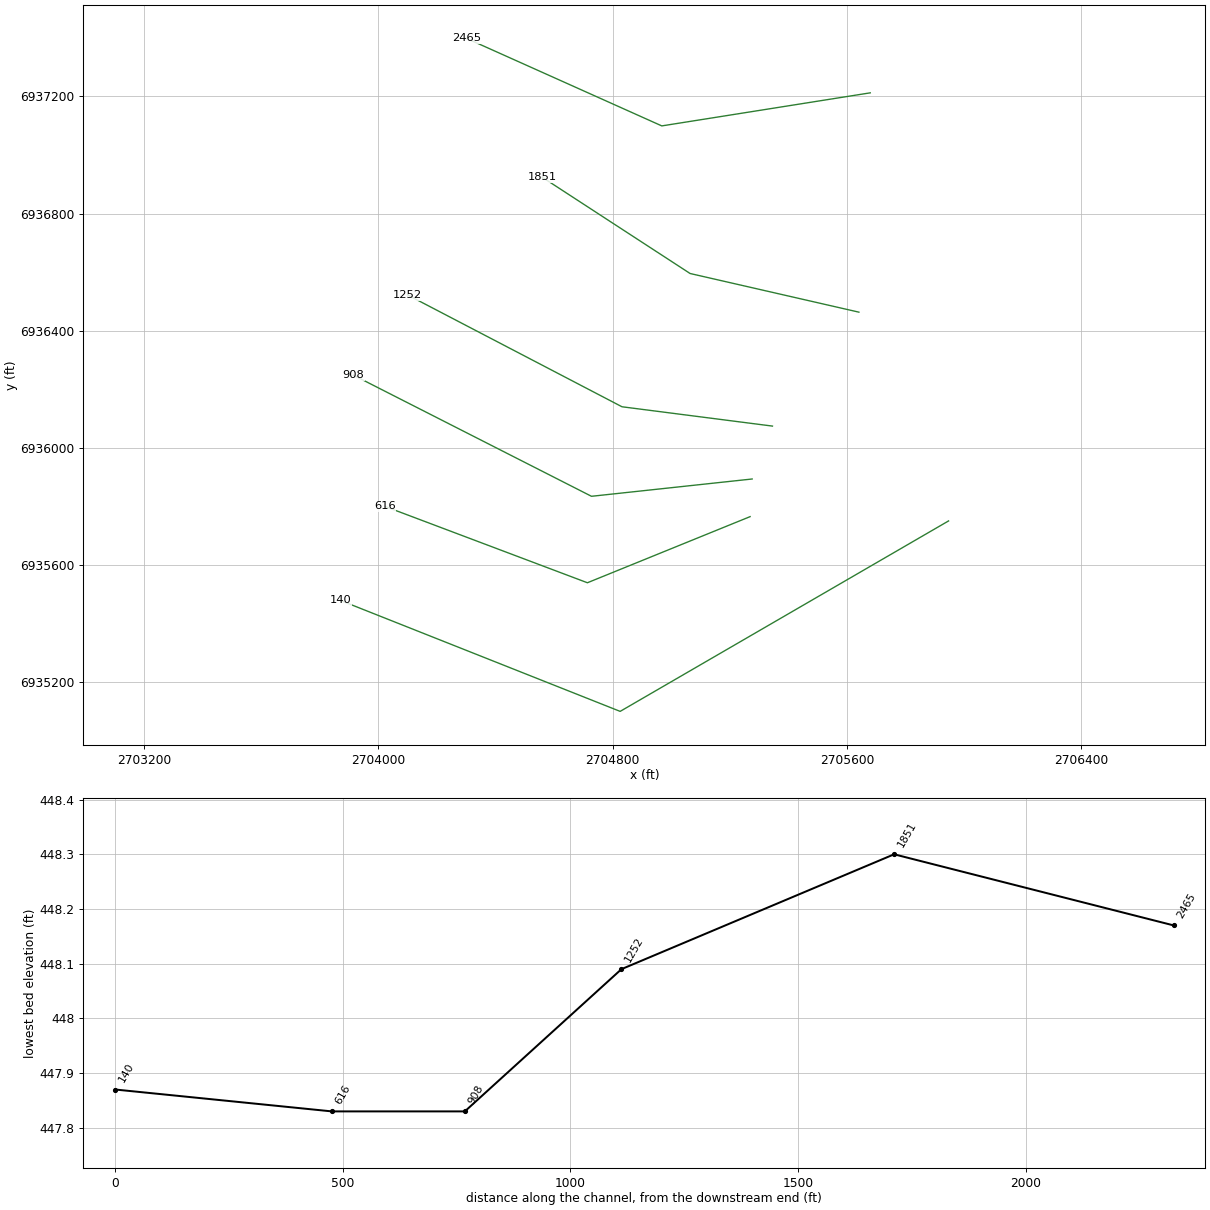
HEC-RAS study Rocky Cedar T6.prj: Rocky Cedar T6 Base Level Engineering

--- Rocky Cedar T6.g01 (geometry) --- (continued)

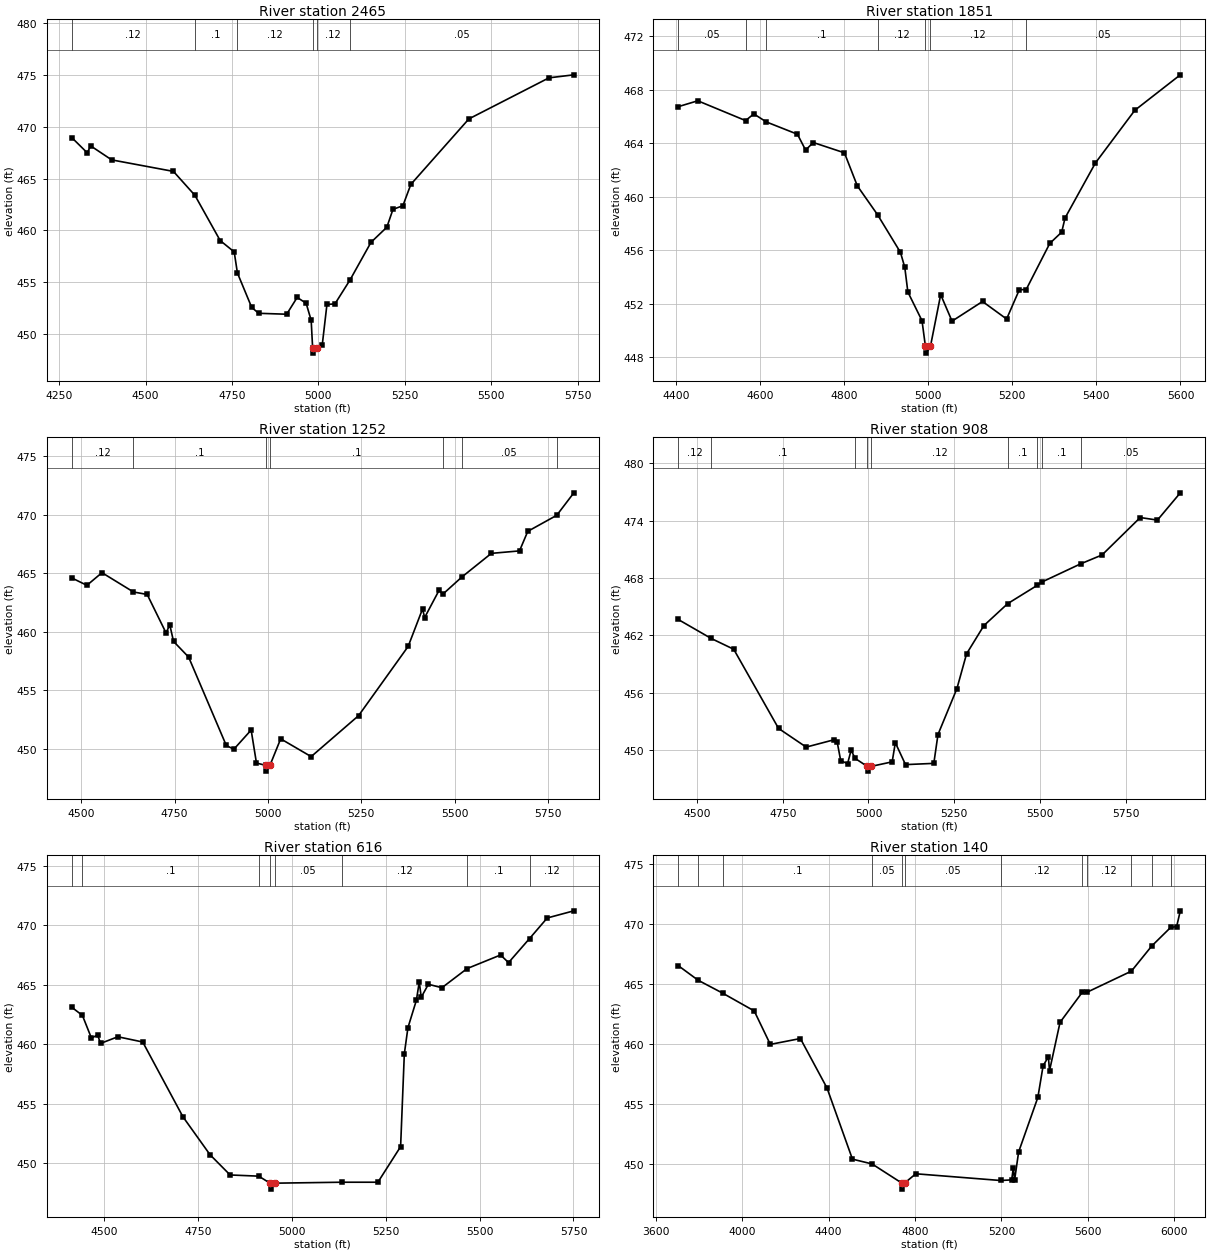
Type RM Length L Ch R = 1,2465,614,614,614
BEGIN DESCRIPTION:
Mapping XS a33c1f31
END DESCRIPTION:
XS GIS Cut Line= 3
      2705680.06      6937212.26      2704968.22      6937099.41
      2704300.42      6937398.62
#Sta/Elev= 30
  4286.7  468.95  4331.5  467.48  4341.4  468.15  4402.2  466.80  4580.8  465.69
  4643.0  463.38  4716.1  459.02  4756.6  457.93  4765.9  455.90  4807.2  452.58
  4827.4  452.01  4908.4  451.92  4938.8  453.54  4964.7  452.98  4979.3  451.33
  4983.5  448.67  4985.1  448.17  4995.4  448.67  5011.4  448.98  5024.9  452.86
  5048.1  452.92  5091.6  455.22  5152.3  458.85  5198.2  460.31  5215.9  462.03
  5244.6  462.38  5267.7  464.44  5435.5  470.75  5667.3  474.71  5739.2  475.00
#Mann=6,-1,0
  4286.7    0.12       0  4643.0     0.1       0  4765.9    0.12       0
  4983.5    0.07       0  4995.4    0.12       0  5091.6    0.05       0
Bank Sta=4983.5,4995.4
Exp/Cntr=0.3,0.1

Type RM Length L Ch R = 1,1851,599,599,599
BEGIN DESCRIPTION:
Mapping XS 0059bfa3
END DESCRIPTION:
XS GIS Cut Line= 3
      2705641.30      6936463.65      2705064.92      6936595.59
      2704559.49      6936924.47
#Sta/Elev= 30
  4405.4  466.72  4451.9  467.16  4565.6  465.68  4585.2  466.18  4614.9  465.58
  4688.9  464.66  4708.3  463.48  4726.7  464.04  4800.7  463.27  4831.4  460.80
  4879.4  458.65  4934.0  455.83  4944.3  454.71  4951.6  452.87  4985.3  450.72
  4993.4  448.80  4995.1  448.30  5005.3  448.80  5029.7  452.67  5056.7  450.69
  5129.2  452.16  5186.5  450.85  5216.8  453.04  5233.0  453.05  5289.2  456.50
  5317.5  457.34  5325.5  458.40  5397.9  462.52  5491.5  466.45  5599.7  469.10
#Mann=7,-1,0
  4405.4    0.05       0  4565.6    0.12       0  4614.9     0.1       0
  4879.4    0.12       0  4993.4    0.07       0  5005.3    0.12       0
  5233.0    0.05       0
Bank Sta=4993.4,5005.3
Exp/Cntr=0.3,0.1

Type RM Length L Ch R = 1,1252,344,344,344
BEGIN DESCRIPTION:
Mapping XS 5f4d4aad
END DESCRIPTION:
XS GIS Cut Line= 3
      2705346.13      6936074.76      2704832.28      6936140.73
      2704100.34      6936522.31
#Sta/Elev= 30
  4475.1  464.59  4515.6  463.96  4555.9  465.04  4640.2  463.39  4676.9  463.18
  4727.3  459.90  4737.4  460.58  4747.4  459.17  4787.8  457.83  4888.6  450.28
  4908.8  449.96  4955.1  451.60  4969.3  448.78  4993.6  448.59  4995.3  448.09
  5005.5  448.59  5034.1  450.85  5115.7  449.33  5242.6  452.83  5375.2  458.74
  5413.7  461.94  5419.4  461.21  5457.9  463.53  5467.9  463.20  5518.6  464.66
  5597.9  466.69  5673.2  466.90  5695.3  468.57  5772.8  469.94  5818.6  471.86
#Mann=7,-1,0
  4475.1    0.12       0  4640.2     0.1       0  4993.6    0.07       0
  5005.5     0.1       0  5467.9    0.12       0  5518.6    0.05       0
  5772.8    0.12       0
Bank Sta=4993.6,5005.5
Exp/Cntr=0.3,0.1

Type RM Length L Ch R = 1,908,292,292,292
BEGIN DESCRIPTION:
Mapping XS 3d2f6002
END DESCRIPTION:
XS GIS Cut Line= 3
      2705276.76      6935894.21      2704728.12      6935835.17
      2703915.65      6936248.35
#Sta/Elev= 30
  4445.5  463.67  4541.5  461.69  4607.2  460.56  4737.9  452.29  4818.4  450.34
  4900.0  451.11  4908.9  450.84  4919.0  448.93  4939.1  448.61  4949.2  450.01
  4961.4  449.15  4996.2  448.33  4997.9  447.83  5008.3  448.33  5069.0  448.80
  5078.2  450.80  5107.9  448.51  5190.4  448.64  5202.5  451.65  5257.7  456.45
  5285.8  460.08  5336.3  463.03  5405.5  465.32  5492.4  467.25  5505.8  467.59
  5618.2  469.48  5680.7  470.41  5792.0  474.32  5842.1  474.05  5908.8  476.90
#Mann=9,-1,0
  4445.5    0.12       0  4541.5     0.1       0  4961.4    0.12       0
  4996.2    0.07       0  5008.3    0.12       0  5405.5     0.1       0
  5492.4    0.05       0  5505.8     0.1       0  5618.2    0.05       0
Bank Sta=4996.2,5008.3
Exp/Cntr=0.3,0.1

Type RM Length L Ch R = 1,616,476,476,476
BEGIN DESCRIPTION:
Mapping XS 3d993474
END DESCRIPTION:
XS GIS Cut Line= 3
      2705269.78      6935765.73      2704714.23      6935540.04
      2704023.22      6935800.46
#Sta/Elev= 30
  4412.9  463.11  4441.3  462.42  4465.4  460.51  4481.7  460.79  4489.5  460.07
  4535.7  460.63  4602.0  460.19  4709.1  453.91  4781.4  450.72  4834.9  449.02
  4911.1  448.92  4941.4  448.33  4943.1  447.83  4953.5  448.33  5132.4  448.41
  5228.8  448.41  5289.3  451.40  5299.2  459.19  5308.8  461.39  5331.3  463.69
  5339.0  465.23  5344.3  463.95  5363.3  465.04  5399.4  464.75  5466.6  466.36
  5555.7  467.50  5577.0  466.86  5632.9  468.88  5680.1  470.61  5751.0  471.21
#Mann=8,-1,0
  4412.9    0.12       0  4441.3     0.1       0  4911.1    0.05       0
  4941.4    0.03       0  4953.5    0.05       0  5132.4    0.12       0
  5466.6     0.1       0  5632.9    0.12       0
Bank Sta=4941.4,4953.5
Exp/Cntr=0.3,0.1

Type RM Length L Ch R = 1,140,0,0,0
BEGIN DESCRIPTION:
Rocky Cedar T6 1.0
END DESCRIPTION:
XS GIS Cut Line= 3
      2705947.54      6935751.14      2704826.05      6935101.02
      2703870.24      6935479.99
#Sta/Elev= 30
  3703.7  466.51  3795.9  465.29  3908.8  464.22  4055.5  462.73  4130.0  459.94
  4269.2  460.43  4392.6  456.30  4510.2  450.37  4601.1  449.97  4739.3  448.37
  4741.0  447.87  4751.4  448.37  4803.6  449.15  5195.8  448.59  5247.5  448.64
  5255.3  449.67  5260.7  448.59  5279.6  450.97  5368.7  455.52  5393.0  458.16
  5417.3  458.90  5422.7  457.75  5471.4  461.78  5574.4  464.29  5596.2  464.29
  5801.8  466.05  5896.1  468.15  5983.2  469.69  6011.2  469.77  6028.2  471.08
#Mann=12,-1,0
  3703.7    0.05       0  3795.9    0.12       0  3908.8     0.1       0
  4601.1    0.05       0  4739.3    0.03       0  4751.4    0.05       0
  5195.8    0.12       0  5574.4     0.1       0  5596.2    0.12       0
  5801.8    0.05       0  5896.1    0.12       0  5983.2     0.1       0
Bank Sta=4739.3,4751.4
Exp/Cntr=0.3,0.1

Chan Stop Cuts=-1