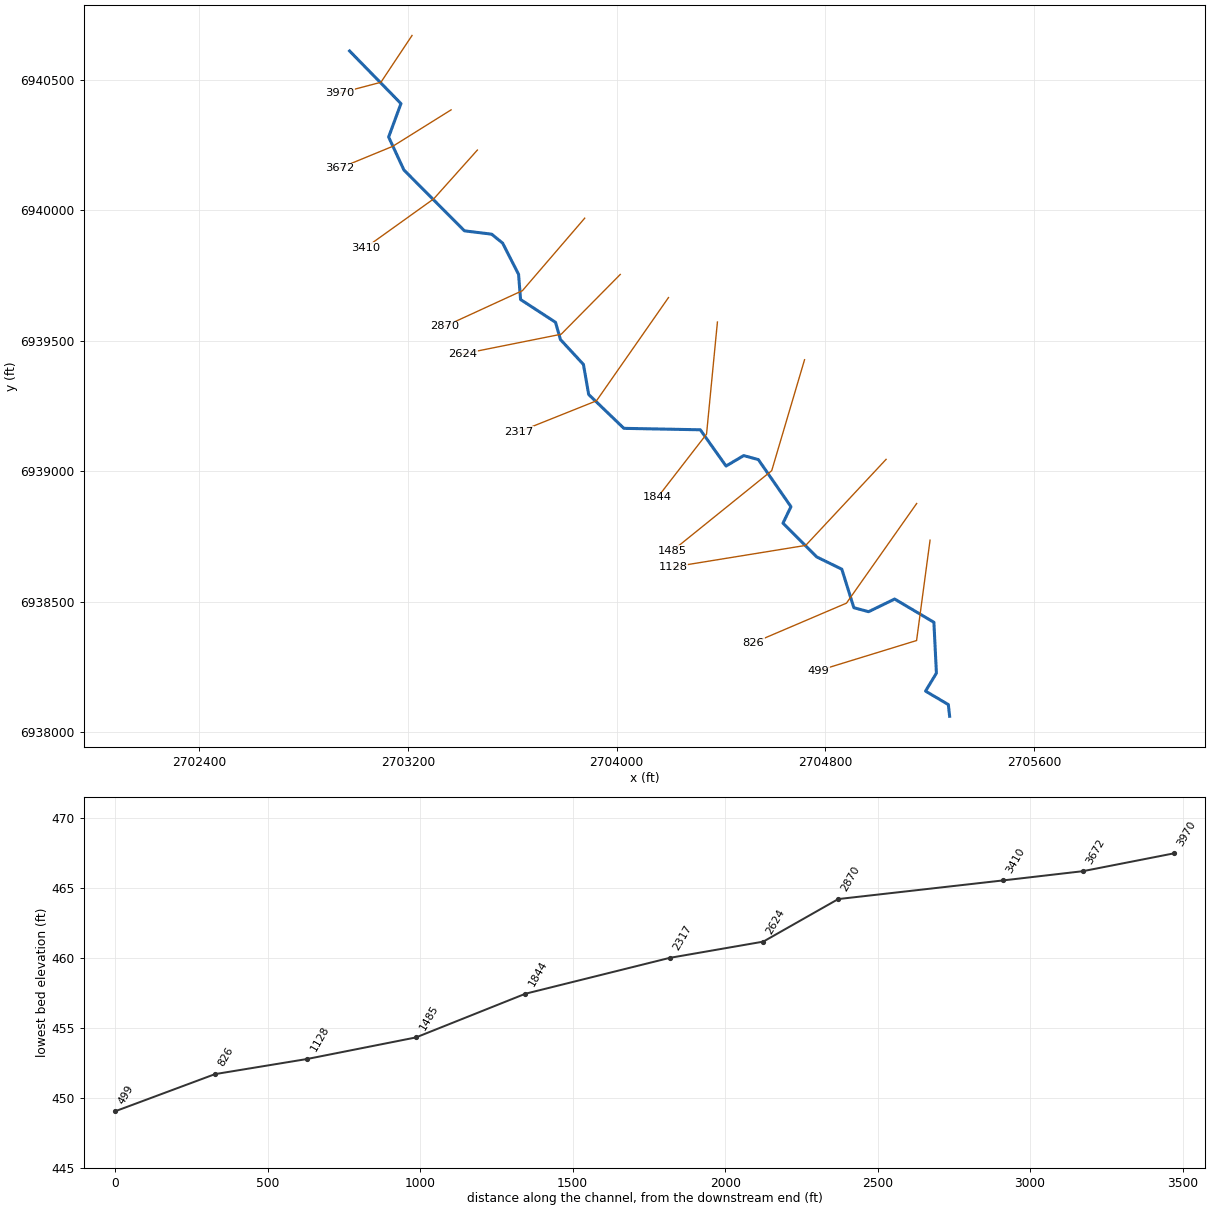
--- Rocky Cedar T6_1.prj (project) ---

Proj Title=Rocky Cedar T6_1 Base Level Engineering
Current Plan=p01
Default Exp/Contr=0.3,0.1
English Units
Geom File=g01
Flow File=f01
Plan File=p01
BEGIN DESCRIPTION:
Rocky Cedar T6_1
END DESCRIPTION:

--- Rocky Cedar T6_1.p01 (plan) ---

Plan Title=Multiple Run
Short Identifier=Multiple
Geom File=g01
Flow File=f01
Subcritical Flow
K Sum by GR= 0
Std Step Tol= 0.01
Critical Tol= 0.01
Num of Std Step Trials= 20
Max Error Tol= 0.3
Flow Tol Ratio= 0.001
Split Flow NTrial= 30
Split Flow Tol= 0.02
Split Flow Ratio= 0.02
Log Output Level= 0
Friction Slope Method= 1
Unsteady Friction Slope Method= 2
Unsteady Bridges Friction Slope Method= 1
Parabolic Critical Depth
Global Vel Dist=  1 , 1 , 1
Global Log Level= 0
CheckData=True
Encroach Param= -1, 0, 0, 0
BEGIN DESCRIPTION:
Multiple Run
END DESCRIPTION:

--- Rocky Cedar T6_1.f01 (steady flow) ---

Flow Title=Multiple
Number of Profiles=7
Profile Names=10-year,25-year,50-year,1pct_min,100-year,1pct_plu,500-year
River Rch & RM= Rocky Cedar T6_1,Reach-1,3970
     636     854    1032     618    1234    2462    1762
Boundary for River Rch & Prof#=Rocky Cedar T6_1,Reach-1,1
Up Type=0
Dn Type=3
Dn Slope=0.005
Boundary for River Rch & Prof#=Rocky Cedar T6_1,Reach-1,2
Up Type=0
Dn Type=3
Dn Slope=0.005
Boundary for River Rch & Prof#=Rocky Cedar T6_1,Reach-1,3
Up Type=0
Dn Type=3
Dn Slope=0.005
Boundary for River Rch & Prof#=Rocky Cedar T6_1,Reach-1,4
Up Type=0
Dn Type=3
Dn Slope=0.005
Boundary for River Rch & Prof#=Rocky Cedar T6_1,Reach-1,5
Up Type=0
Dn Type=3
Dn Slope=0.005
Boundary for River Rch & Prof#=Rocky Cedar T6_1,Reach-1,6
Up Type=0
Dn Type=3
Dn Slope=0.005
Boundary for River Rch & Prof#=Rocky Cedar T6_1,Reach-1,7
Up Type=0
Dn Type=3
Dn Slope=0.005

--- Rocky Cedar T6_1.g01 (geometry) ---

Geom Title=Existing Conditions

River Reach=Rocky Cedar T6_1,Reach-1
Reach XY= 30
      2702976.00      6940611.00      2703172.87      6940409.37
      2703125.71      6940281.18      2703184.14      6940154.94
      2703416.22      6939921.52      2703520.29      6939908.92
      2703562.55      6939874.63      2703623.67      6939755.03
      2703631.42      6939658.33      2703765.35      6939570.99
      2703784.19      6939504.98      2703872.37      6939409.50
      2703892.46      6939294.25      2704027.46      6939164.54
      2704320.33      6939159.02      2704418.99      6939020.03
      2704486.64      6939060.11      2704542.71      6939044.79
      2704667.75      6938864.23      2704637.24      6938801.00
      2704766.34      6938671.79      2704862.74      6938624.65
      2704908.87      6938477.03      2704965.25      6938461.72
      2705065.32      6938510.25      2705215.66      6938421.12
      2705225.34      6938226.15      2705183.68      6938157.35
      2705270.99      6938105.67      2705276.00      6938061.00

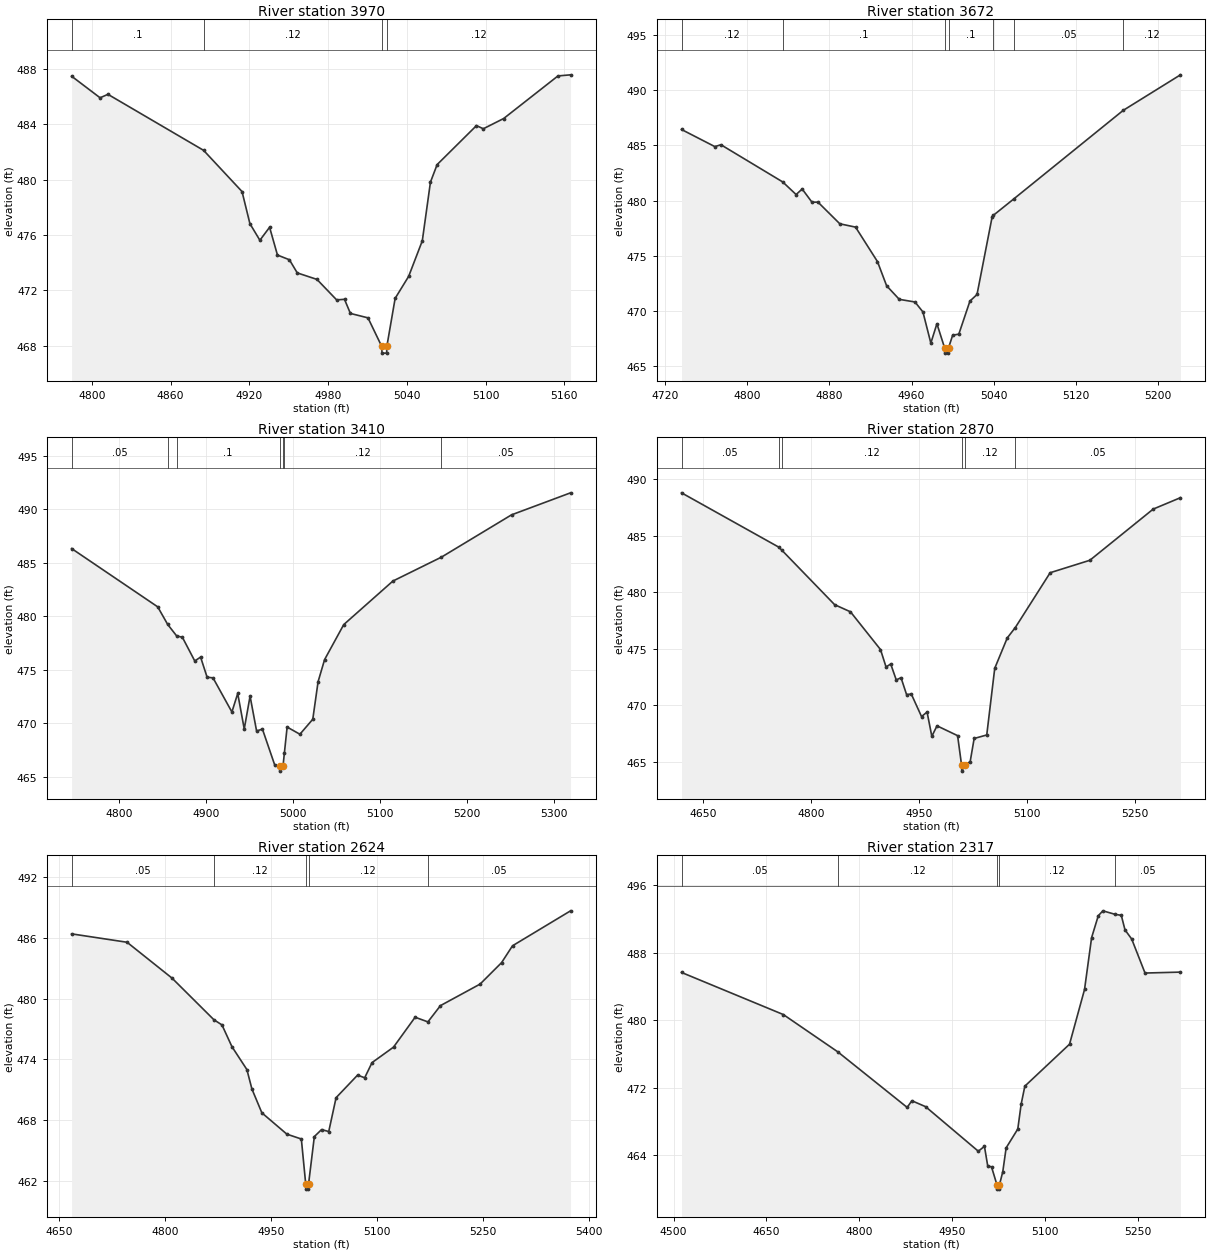
Type RM Length L Ch R = 1,3970,298,298,298
BEGIN DESCRIPTION:
Rocky Cedar T6_1 9.0
END DESCRIPTION:
XS GIS Cut Line= 3
      2703215.36      6940670.47      2703096.05      6940491.02
      2702936.67      6940449.09
#Sta/Elev= 30
  4784.5  487.47  4806.2  485.91  4812.2  486.16  4885.1  482.11  4914.4  479.13
  4920.4  476.81  4928.0  475.61  4935.4  476.55  4941.4  474.54  4950.5  474.20
  4956.5  473.25  4971.5  472.78  4986.5  471.30  4992.5  471.34  4997.0  470.32
  5010.4  470.00  5020.8  467.95  5021.1  467.45  5024.6  467.45  5024.8  467.95
  5031.1  471.41  5041.4  473.00  5051.8  475.57  5058.0  479.81  5063.1  481.08
  5093.1  483.90  5098.3  483.67  5113.8  484.41  5155.2  487.49  5164.8  487.57
#Mann=4,-1,0
  4784.5     0.1       0  4885.1    0.12       0  5020.8    0.07       0
  5024.8    0.12       0
Bank Sta=5020.8,5024.8
Exp/Cntr=0.3,0.1

Type RM Length L Ch R = 1,3672,262,262,262
BEGIN DESCRIPTION:
Rocky Cedar T6_1 8.0
END DESCRIPTION:
XS GIS Cut Line= 3
      2703365.10      6940385.30      2703141.03      6940245.37
      2702936.70      6940161.34
#Sta/Elev= 30
  4736.4  486.43  4768.8  484.88  4774.7  485.05  4834.8  481.68  4847.8  480.54
  4853.7  481.04  4863.2  479.85  4869.1  479.85  4890.3  477.89  4905.6  477.59
  4926.9  474.47  4935.8  472.28  4948.1  471.05  4963.4  470.81  4971.1  469.91
  4978.8  467.09  4984.7  468.84  4992.1  466.68  4992.3  466.18  4995.8  466.18
  4996.1  466.68  5000.0  467.80  5006.0  467.90  5016.8  470.89  5023.7  471.49
  5038.4  478.52  5039.6  478.66  5059.8  480.17  5165.8  488.16  5221.5  491.38
#Mann=7,-1,0
  4736.4    0.12       0  4834.8     0.1       0  4992.1    0.07       0
  4996.1     0.1       0  5039.6    0.12       0  5059.8    0.05       0
  5165.8    0.12       0
Bank Sta=4992.1,4996.1
Exp/Cntr=0.3,0.1

Type RM Length L Ch R = 1,3410,540,540,540
BEGIN DESCRIPTION:
Rocky Cedar T6_1 7.0
END DESCRIPTION:
XS GIS Cut Line= 3
      2703465.76      6940231.19      2703298.56      6940044.24
      2703036.08      6939856.21
#Sta/Elev= 30
  4745.0  486.33  4844.0  480.88  4855.5  479.23  4865.7  478.17  4872.4  478.03
  4886.6  475.82  4893.3  476.18  4900.8  474.30  4907.6  474.24  4929.3  471.05
  4936.0  472.78  4943.5  469.46  4950.2  472.53  4957.7  469.27  4964.4  469.45
  4978.6  466.08  4984.1  466.02  4984.3  465.52  4988.1  466.02  4989.7  467.25
  4992.8  469.64  5007.5  468.97  5022.3  470.37  5028.4  473.88  5035.9  475.95
  5057.9  479.22  5114.4  483.29  5170.3  485.53  5250.8  489.48  5318.7  491.54
#Mann=7,-1,0
  4745.0    0.05       0  4855.5    0.12       0  4865.7     0.1       0
  4984.1    0.07       0  4988.1     0.1       0  4989.7    0.12       0
  5170.3    0.05       0
Bank Sta=4984.1,4988.1
Exp/Cntr=0.3,0.1

Type RM Length L Ch R = 1,2870,246,246,246
BEGIN DESCRIPTION:
Mapping XS ed0fd72b
END DESCRIPTION:
XS GIS Cut Line= 3
      2703877.24      6939970.15      2703638.53      6939692.37
      2703341.58      6939555.82
#Sta/Elev= 30
  4619.8  488.82  4754.7  484.02  4758.9  483.76  4832.5  478.92  4854.5  478.29
  4896.2  474.95  4903.9  473.41  4910.4  473.67  4918.1  472.26  4924.7  472.46
  4932.4  470.97  4939.0  471.01  4953.2  469.02  4960.9  469.42  4967.5  467.27
  4974.7  468.20  5003.3  467.33  5008.9  464.69  5009.1  464.19  5012.9  464.69
  5020.8  465.04  5026.3  467.08  5043.8  467.39  5054.9  473.29  5072.3  475.98
  5083.5  476.90  5131.9  481.75  5187.0  482.85  5275.0  487.38  5312.9  488.39
#Mann=6,-1,0
  4619.8    0.05       0  4754.7     0.1       0  4758.9    0.12       0
  5008.9    0.07       0  5012.9    0.12       0  5083.5    0.05       0
Bank Sta=5008.9,5012.9
Exp/Cntr=0.3,0.1

Type RM Length L Ch R = 1,2624,307,307,307
BEGIN DESCRIPTION:
Mapping XS b0370280
END DESCRIPTION:
XS GIS Cut Line= 3
      2704013.55      6939754.46      2703786.97      6939525.27
      2703410.21      6939449.92
#Sta/Elev= 30
  4667.9  486.41  4746.4  485.58  4810.1  482.03  4869.4  477.91  4880.8  477.40
  4894.9  475.25  4916.1  472.98  4923.2  471.06  4937.3  468.70  4972.7  466.59
  4993.2  466.11  4999.4  461.65  4999.6  461.15  5003.1  461.15  5003.4  461.65
  5011.6  466.35  5021.8  467.04  5032.0  466.85  5042.4  470.20  5072.8  472.43
  5082.9  472.17  5093.3  473.67  5123.7  475.20  5154.3  478.16  5172.4  477.70
  5190.2  479.31  5246.3  481.44  5276.7  483.56  5292.2  485.23  5374.4  488.69
#Mann=5,-1,0
  4667.9    0.05       0  4869.4    0.12       0  4999.4    0.07       0
  5003.4    0.12       0  5172.4    0.05       0
Bank Sta=4999.4,5003.4
Exp/Cntr=0.3,0.1

Type RM Length L Ch R = 1,2317,473,473,473
BEGIN DESCRIPTION:
Mapping XS 8a47a95f
END DESCRIPTION:
XS GIS Cut Line= 3
      2704198.41      6939665.87      2703922.38      6939270.06
      2703622.90      6939150.27
#Sta/Elev= 30
  4512.9  485.66  4677.2  480.67  4765.1  476.25  4877.0  469.67  4884.6  470.46
  4906.7  469.76  4991.8  464.48  5001.7  465.06  5007.0  462.73  5013.1  462.63
  5021.9  460.49  5022.1  459.99  5025.6  459.99  5025.9  460.49  5031.3  462.06
  5036.7  464.88  5055.5  467.11  5060.9  470.04  5066.9  472.19  5139.0  477.16
  5163.2  483.64  5174.6  489.78  5185.4  492.38  5192.8  492.96  5212.7  492.54
  5222.5  492.43  5228.5  490.70  5239.3  489.62  5260.8  485.59  5318.0  485.70
#Mann=5,-1,0
  4512.9    0.05       0  4765.1    0.12       0  5021.9    0.07       0
  5025.9    0.12       0  5212.7    0.05       0
Bank Sta=5021.9,5025.9
Exp/Cntr=0.3,0.1

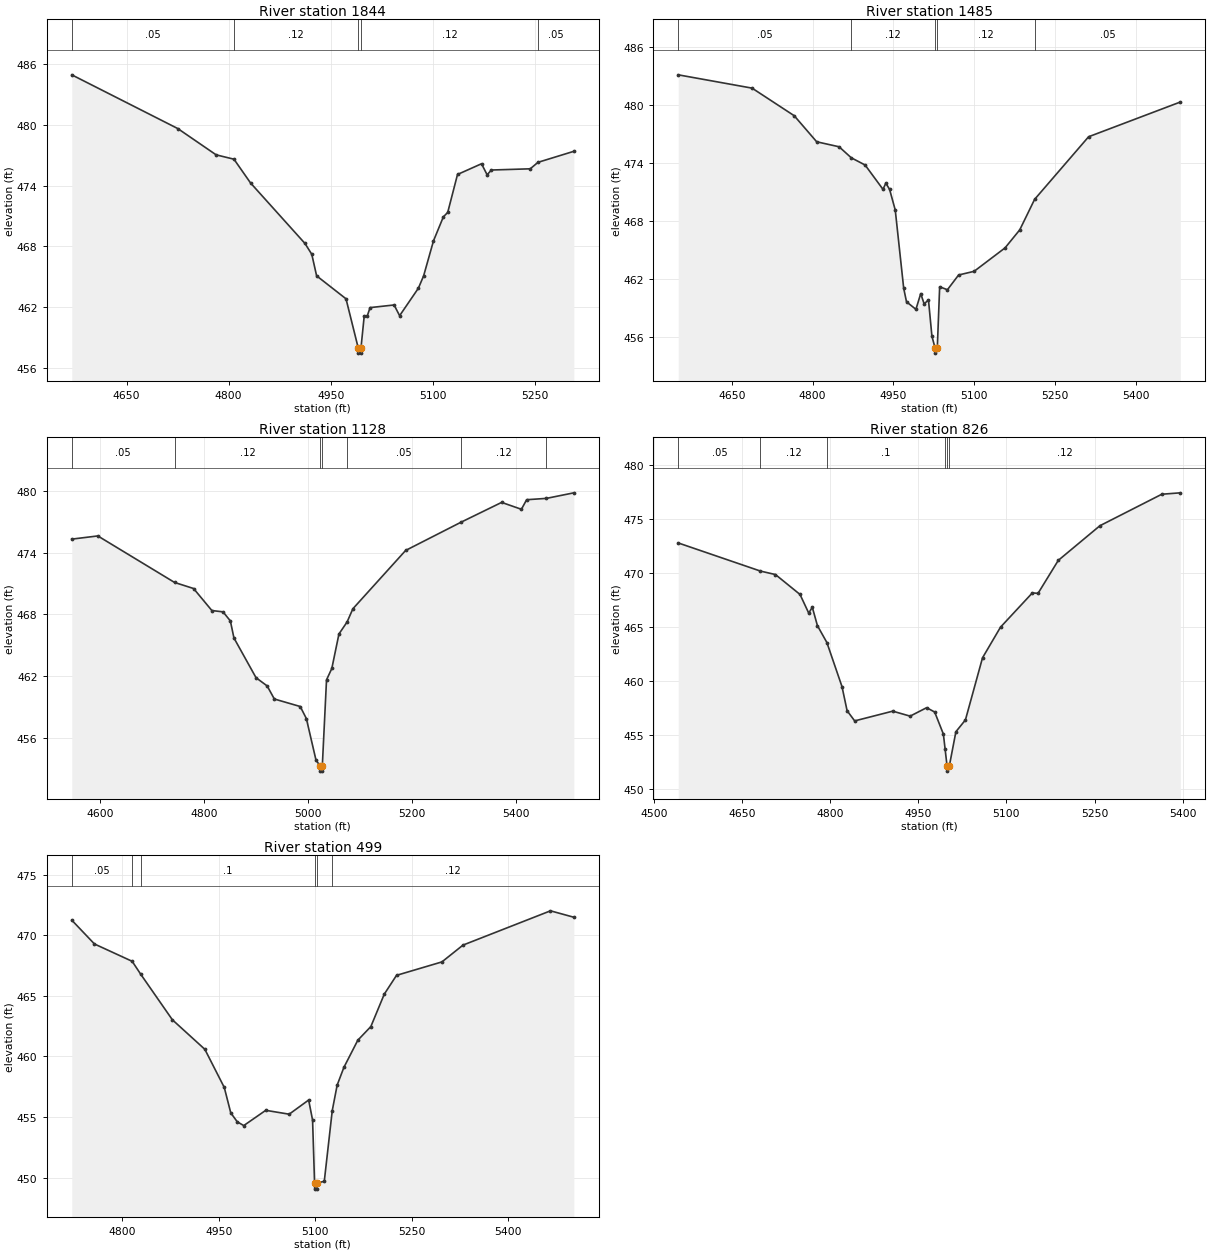
Type RM Length L Ch R = 1,1844,359,359,359
BEGIN DESCRIPTION:
Mapping XS 5b845117
END DESCRIPTION:
XS GIS Cut Line= 3
      2704385.93      6939572.17      2704344.26      6939142.46
      2704156.76      6938900.28
#Sta/Elev= 30
  4569.4  484.94  4725.2  479.63  4781.6  477.03  4807.8  476.60  4832.2  474.25
  4912.2  468.27  4922.2  467.20  4929.3  465.07  4972.5  462.80  4990.5  457.93
  4990.8  457.43  4994.3  457.43  4994.5  457.93  4999.3  461.12  5003.8  461.12
  5007.9  461.93  5043.2  462.19  5051.3  461.13  5078.9  463.85  5086.6  465.07
  5101.1  468.53  5115.6  470.90  5122.0  471.34  5136.4  475.09  5171.7  476.15
  5179.9  475.06  5186.2  475.53  5243.3  475.65  5254.7  476.29  5307.4  477.38
#Mann=5,-1,0
  4569.4    0.05       0  4807.8    0.12       0  4990.5    0.07       0
  4994.5    0.12       0  5254.7    0.05       0
Bank Sta=4990.5,4994.5
Exp/Cntr=0.3,0.1

Type RM Length L Ch R = 1,1485,357,357,357
BEGIN DESCRIPTION:
Mapping XS 57bc2204
END DESCRIPTION:
XS GIS Cut Line= 3
      2704719.90      6939427.59      2704594.04      6939002.27
      2704213.28      6938695.06
#Sta/Elev= 30
  4550.3  483.16  4687.5  481.78  4765.8  478.92  4807.5  476.22  4849.2  475.70
  4871.8  474.56  4897.5  473.81  4930.7  471.29  4936.0  471.93  4943.0  471.28
  4953.5  469.14  4969.2  461.02  4974.4  459.63  4991.9  458.85  5000.8  460.48
  5007.2  459.41  5015.2  459.83  5021.6  456.07  5027.6  454.81  5027.8  454.31
  5031.6  454.81  5036.0  461.19  5050.4  460.88  5071.2  462.41  5100.0  462.79
  5157.5  465.22  5184.8  467.09  5212.4  470.25  5312.7  476.74  5483.1  480.34
#Mann=5,-1,0
  4550.3    0.05       0  4871.8    0.12       0  5027.6    0.07       0
  5031.6    0.12       0  5212.4    0.05       0
Bank Sta=5027.6,5031.6
Exp/Cntr=0.3,0.1

Type RM Length L Ch R = 1,1128,302,302,302
BEGIN DESCRIPTION:
Mapping XS c39726aa
END DESCRIPTION:
XS GIS Cut Line= 3
      2705032.40      6939045.66      2704724.25      6938715.81
      2704216.39      6938633.34
#Sta/Elev= 30
  4545.7  475.32  4595.8  475.63  4743.4  471.11  4780.0  470.52  4815.2  468.38
  4836.7  468.25  4850.8  467.37  4857.7  465.71  4900.2  461.85  4921.6  461.05
  4935.4  459.78  4985.2  459.05  4997.0  457.88  5015.6  453.83  5023.7  453.27
  5024.0  452.77  5027.5  452.77  5027.7  453.27  5035.8  461.64  5046.0  462.75
  5059.7  466.10  5075.4  467.27  5086.5  468.55  5188.0  474.22  5294.4  476.96
  5372.7  478.89  5410.7  478.22  5420.8  479.15  5458.8  479.28  5511.6  479.82
#Mann=7,-1,0
  4545.7    0.05       0  4743.4    0.12       0  5023.7    0.07       0
  5027.7    0.12       0  5075.4    0.05       0  5294.4    0.12       0
  5458.8    0.05       0
Bank Sta=5023.7,5027.7
Exp/Cntr=0.3,0.1

Type RM Length L Ch R = 1,826,327,327,327
BEGIN DESCRIPTION:
Mapping XS bc0d3944
END DESCRIPTION:
XS GIS Cut Line= 3
      2705149.62      6938876.44      2704880.50      6938494.46
      2704524.63      6938342.56
#Sta/Elev= 30
  4541.7  472.77  4681.6  470.17  4707.1  469.85  4748.9  468.01  4763.7  466.29
  4769.8  466.83  4778.5  465.13  4794.6  463.57  4820.3  459.50  4829.0  457.27
  4841.9  456.33  4906.6  457.23  4936.2  456.77  4964.3  457.55  4978.0  457.15
  4992.8  455.11  4995.8  453.70  4999.0  452.19  4999.2  451.69  5003.0  452.19
  5014.1  455.33  5030.3  456.42  5059.4  462.16  5090.0  464.99  5144.3  468.16
  5153.8  468.11  5188.3  471.16  5259.1  474.36  5364.4  477.27  5395.9  477.40
#Mann=6,-1,0
  4541.7    0.05       0  4681.6    0.12       0  4794.6     0.1       0
  4995.8    0.12       0  4999.0    0.07       0  5003.0    0.12       0
Bank Sta=4999,5003
Exp/Cntr=0.3,0.1

Type RM Length L Ch R = 1,499,0,0,0
BEGIN DESCRIPTION:
Rocky Cedar T6_1 1.0
END DESCRIPTION:
XS GIS Cut Line= 3
      2705201.00      6938736.03      2705149.31      6938351.23
      2704774.27      6938235.99
#Sta/Elev= 30
  4721.3  471.26  4756.6  469.29  4815.2  467.86  4828.4  466.80  4877.7  463.03
  4928.2  460.59  4958.4  457.44  4968.5  455.34  4978.6  454.60  4988.7  454.29
  5022.9  455.55  5059.3  455.23  5089.6  456.40  5095.7  454.74  5098.8  449.54
  5099.0  449.04  5102.5  449.04  5102.8  449.54  5113.9  449.69  5126.3  455.53
  5133.9  457.63  5144.4  459.10  5166.0  461.34  5186.3  462.47  5207.2  465.15
  5226.2  466.70  5296.8  467.81  5329.6  469.20  5465.6  472.03  5501.9  471.50
#Mann=6,-1,0
  4721.3    0.05       0  4815.2    0.12       0  4828.4     0.1       0
  5098.8    0.07       0  5102.8     0.1       0  5126.3    0.12       0
Bank Sta=5098.8,5102.8
Exp/Cntr=0.3,0.1

Chan Stop Cuts=-1