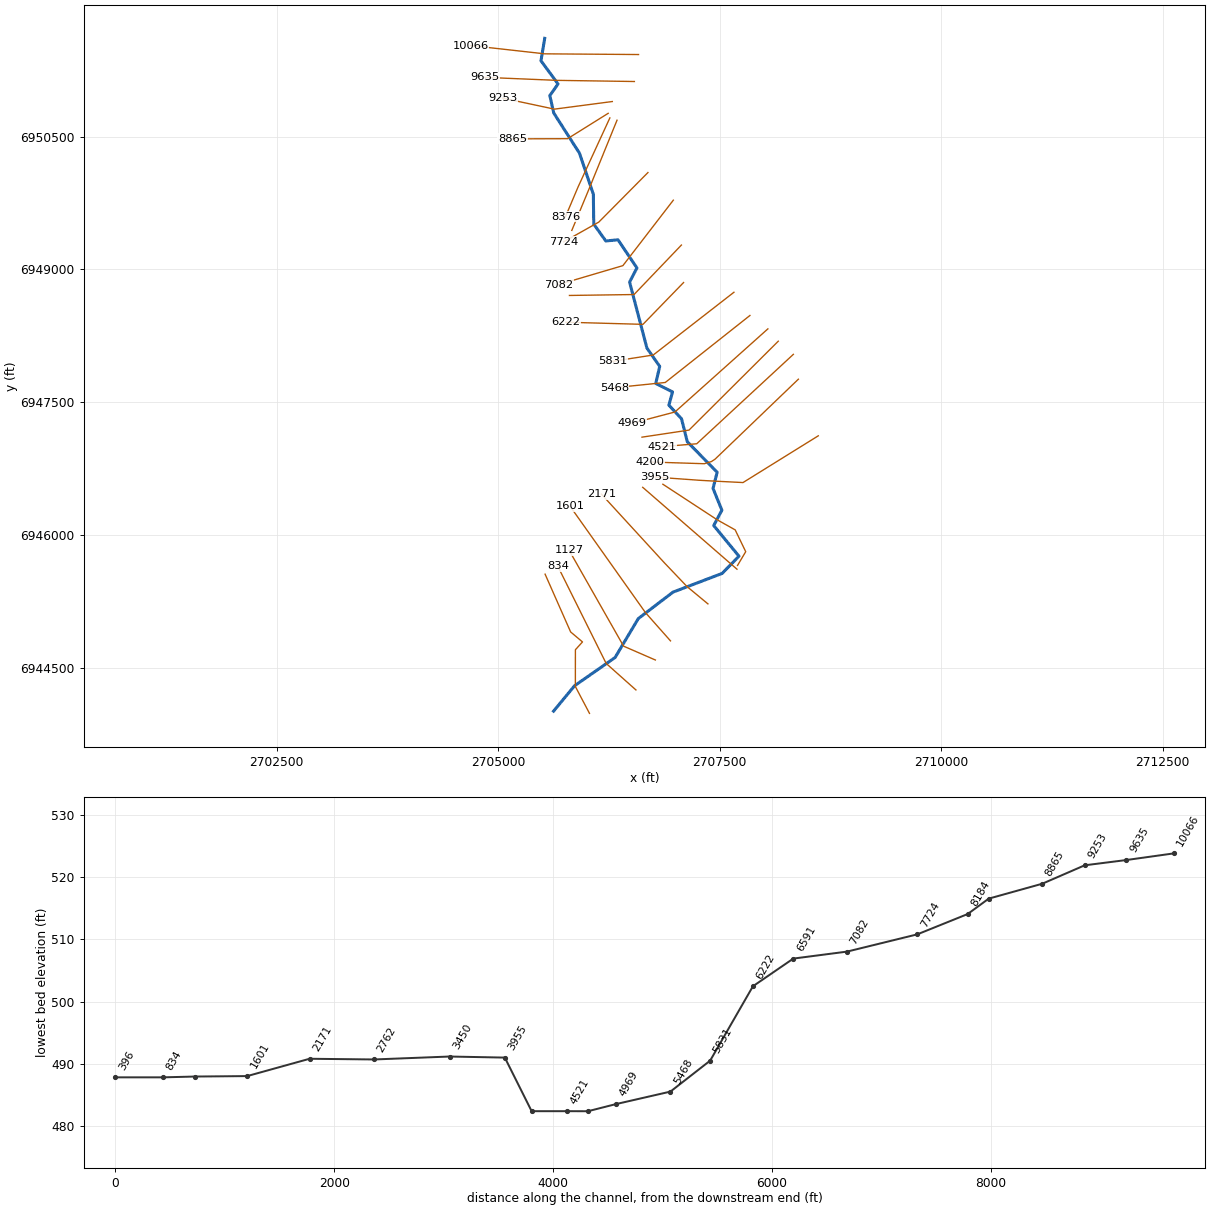
--- Rocky Cedar T6_2.prj (project) ---

Proj Title=Rocky Cedar T6_2 Base Level Engineering
Current Plan=p01
Default Exp/Contr=0.3,0.1
English Units
Geom File=g01
Flow File=f01
Plan File=p01
Y Axis Title=Elevation
X Axis Title(PF)=Main Channel Distance
X Axis Title(XS)=Station
BEGIN DESCRIPTION:
Rocky Cedar T6_2
END DESCRIPTION:
DSS Export Rating Curves= 0
DSS Export Rating Curve Sorted= 0
DSS Export Volume Flow Curves= 0
DXF OffsetX= 0
DXF OffsetY= 0
DXF ScaleX= 1
DXF ScaleY= 10

--- Rocky Cedar T6_2.p01 (plan) ---

Plan Title=Multiple Run
Short Identifier=Multiple
Geom File=g01
Flow File=f01
Subcritical Flow
K Sum by GR= 0
Std Step Tol= 0.01
Critical Tol= 0.01
Num of Std Step Trials= 20
Max Error Tol= 0.3
Flow Tol Ratio= 0.001
Split Flow NTrial= 30
Split Flow Tol= 0.02
Split Flow Ratio= 0.02
Log Output Level= 0
Friction Slope Method= 1
Unsteady Friction Slope Method= 2
Unsteady Bridges Friction Slope Method= 1
Parabolic Critical Depth
Global Vel Dist=  1 , 1 , 1
Global Log Level= 0
CheckData=True
Encroach Param= -1, 0, 0, 0
BEGIN DESCRIPTION:
Multiple Run
END DESCRIPTION:

--- Rocky Cedar T6_2.f01 (steady flow) ---

Flow Title=Multiple
Number of Profiles=7
Profile Names=10-year,25-year,50-year,1pct_min,100-year,1pct_plu,500-year
River Rch & RM= Rocky Cedar T6_2,Reach-1,10066
     468     610     720     422     842    1680    1149
River Rch & RM= Rocky Cedar T6_2,Reach-1,5831
     584     771     920     544    1084    2164    1506
Boundary for River Rch & Prof#=Rocky Cedar T6_2,Reach-1,1
Up Type=0
Dn Type=3
Dn Slope=0.005
Boundary for River Rch & Prof#=Rocky Cedar T6_2,Reach-1,2
Up Type=0
Dn Type=3
Dn Slope=0.005
Boundary for River Rch & Prof#=Rocky Cedar T6_2,Reach-1,3
Up Type=0
Dn Type=3
Dn Slope=0.005
Boundary for River Rch & Prof#=Rocky Cedar T6_2,Reach-1,4
Up Type=0
Dn Type=3
Dn Slope=0.005
Boundary for River Rch & Prof#=Rocky Cedar T6_2,Reach-1,5
Up Type=0
Dn Type=3
Dn Slope=0.005
Boundary for River Rch & Prof#=Rocky Cedar T6_2,Reach-1,6
Up Type=0
Dn Type=3
Dn Slope=0.005
Boundary for River Rch & Prof#=Rocky Cedar T6_2,Reach-1,7
Up Type=0
Dn Type=3
Dn Slope=0.005

--- Rocky Cedar T6_2.g01 (geometry) ---

Geom Title=Existing Conditions
Program Version=4.10

River Reach=Rocky Cedar T6_2,Reach-1
Reach XY= 30
        2705526.        6951611.      2705483.83      6951357.58
      2705676.16      6951095.76      2705583.81      6950964.41
      2705628.25      6950766.93        2705918.      6950314.33
      2706074.91      6949850.46      2706079.62       6949512.5
      2706215.63      6949321.98      2706353.14      6949335.09
      2706566.87      6949017.72      2706484.06      6948857.71
      2706679.62       6948112.5       2706824.2      6947904.89
      2706779.36      6947712.25      2706968.65      6947617.38
      2706927.62      6947467.04      2707070.17       6947313.3
       2707135.3      6947054.33      2707472.33      6946709.42
      2707425.96      6946526.34      2707525.96      6946281.03
      2707433.67      6946107.34      2707718.93        6945761.
      2707528.43      6945566.52      2706973.71      6945355.15
      2706581.59      6945055.39      2706320.38      6944616.62
      2705862.79      6944297.37        2705626.        6944011.

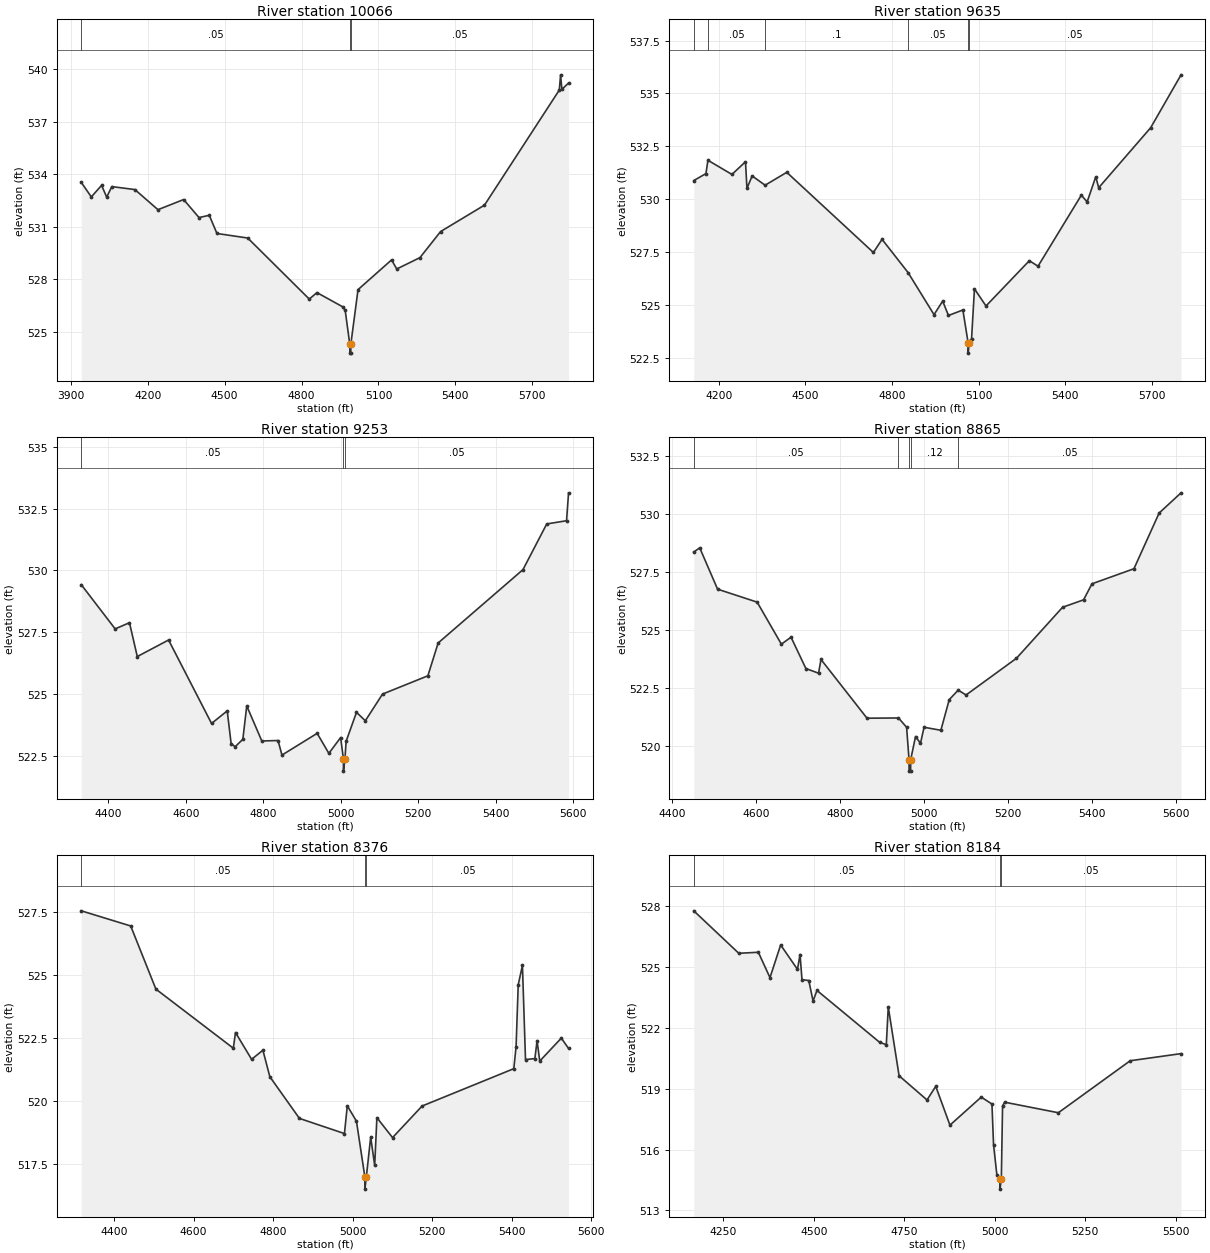
Type RM Length L Ch R = 1 ,10066   ,431,431,431
BEGIN DESCRIPTION:
Rocky Cedar T6_2 19.0
END DESCRIPTION:
XS GIS Cut Line= 3
      2706585.07      6951427.99       2705526.3      6951435.96
      2704690.11      6951529.45
#Sta/Elev= 30
  3941.2  533.54  3980.3  532.71  4020.3  533.37  4040.3   532.7  4060.3   533.3
  4150.3  533.13  4240.3  531.98  4340.3  532.56  4400.3  531.53  4440.3  531.66
  4470.3  530.62  4590.3  530.36  4830.3  526.87  4860.3  527.24  4960.3  526.43
  4970.3  526.23  4988.3  524.28  4988.6  523.78  4992.1  523.78  4992.3  524.28
  5020.4  527.41  5151.2  529.11  5171.4  528.59  5261.9  529.24  5342.4  530.73
  5513.5  532.24  5805.3  538.82  5810.3  539.69  5815.4  538.86  5841.4  539.22
#Mann= 3 ,-1 , 0
  3941.2     .05       0  4988.3     .05       0  4992.3     .05       0
Bank Sta=4988.3,4992.3
XS Rating Curve= 0 ,0
Exp/Cntr=0.3,0.1

Type RM Length L Ch R = 1 ,9635    ,382,382,382
BEGIN DESCRIPTION:
Mapping XS 85d21ee4
END DESCRIPTION:
XS GIS Cut Line= 3
      2706538.18       6951123.3      2705663.18      6951136.33
      2704850.88      6951170.17
#Sta/Elev= 30
  4113.1  530.88  4155.3  531.21  4162.1  531.84  4245.3  531.17  4292.3  531.77
  4297.3  530.51  4315.3   531.1  4360.2  530.66  4435.3  531.27  4735.3  527.48
  4765.4   528.1  4855.5  526.53  4945.4  524.54  4975.4  525.18  4995.4   524.5
  5045.4  524.76  5063.4  523.22  5063.7  522.72  5067.4  523.22  5075.5  523.41
  5085.5  525.76  5125.5  524.95  5275.6  527.09  5305.7  526.83  5455.8  530.19
  5475.8  529.87  5505.8  531.06  5515.8  530.54    5696  533.38  5801.2  535.88
#Mann= 6 ,-1 , 0
  4113.1    .075       0  4162.1     .05       0  4360.2      .1       0
  4855.5     .05       0  5063.4     .03       0  5067.4     .05       0
Bank Sta=5063.4,5067.4
XS Rating Curve= 0 ,0
Exp/Cntr=0.3,0.1

Type RM Length L Ch R = 1 ,9253    ,388,388,388
BEGIN DESCRIPTION:
Mapping XS 2a78a195
END DESCRIPTION:
XS GIS Cut Line= 3
      2706289.26      6950897.18      2705635.62      6950811.24
      2705050.94      6950935.97
#Sta/Elev= 30
  4330.6  529.42    4418  527.63  4454.9  527.88  4475.1  526.51  4555.8  527.18
  4666.7   523.8  4707.1  524.31  4717.2  522.98  4727.7  522.86  4747.4  523.16
  4757.5  524.51  4796.4  523.09  4838.2  523.11  4848.3  522.52  4939.1   523.4
  4969.3  522.59  4999.7  523.23  5006.8  522.37    5007  521.87  5010.8  522.37
  5013.9  523.08  5040.6  524.25  5063.4  523.91  5107.8  524.99  5224.7  525.73
  5251.3  527.06  5470.1  530.03  5531.4  531.88  5582.5  532.01  5587.7  533.14
#Mann= 3 ,-1 , 0
  4330.6     .05       0  5006.8     .04       0  5010.8     .05       0
Bank Sta=5006.8,5010.8
XS Rating Curve= 0 ,0
Exp/Cntr=0.3,0.1

Type RM Length L Ch R = 1 ,8865    ,489,489,489
BEGIN DESCRIPTION:
Mapping XS 87b1e0c3
END DESCRIPTION:
XS GIS Cut Line= 3
       2706242.4      6950763.94      2705784.49      6950477.47
      2705163.83       6950475.3
#Sta/Elev= 30
  4451.8  528.35    4466  528.53  4508.5  526.75  4602.8  526.19  4660.5  524.38
  4683.5  524.68  4718.9  523.33    4749  523.13  4754.9  523.72  4864.5  521.19
  4939.5   521.2  4958.8   520.8  4964.6  519.41  4964.8  518.91  4968.3  518.91
  4968.6  519.41  4980.1   520.4  4991.9  520.11  5000.4   520.8  5040.4  520.67
  5060.4  521.99  5081.7   522.4  5100.4  522.19  5220.4  523.77  5330.4  525.97
  5380.4  526.29  5400.4  526.98  5500.4  527.63  5560.4  530.03  5612.6   530.9
#Mann= 5 ,-1 , 0
  4451.8     .05       0  4939.5     .12       0  4964.6     .07       0
  4968.6     .12       0  5081.7     .05       0
Bank Sta=4964.6,4968.6
XS Rating Curve= 0 ,0
Exp/Cntr=0.3,0.1

Type RM Length L Ch R = 1 ,8376    ,192,192,192
BEGIN DESCRIPTION:
Mapping XS 97e53b27
END DESCRIPTION:
XS GIS Cut Line= 4
      2706261.49      6950712.21      2706003.67       6950152.3
      2705902.11      6949930.94      2705759.64       6949594.2
#Sta/Elev= 30
  4317.4  527.54  4441.7  526.94  4505.1  524.44  4699.8   522.1  4705.3  522.72
  4745.8  521.66  4774.2  522.02  4791.7  520.97  4866.1  519.32  4979.3  518.72
  4986.5  519.82  5009.5  519.21  5030.5  517.02  5030.7  516.52  5034.5  517.02
  5045.3  518.58  5055.4  517.46  5060.9  519.35  5100.3  518.56  5174.6  519.81
  5405.3  521.29    5411  522.16  5416.4  524.61    5427  525.38  5434.7  521.65
  5458.3  521.69  5463.8   522.4  5470.5  521.59  5524.8   522.5    5543  522.09
#Mann= 3 ,-1 , 0
  4317.4     .05       0  5030.5     .04       0  5034.5     .05       0
Bank Sta=5030.5,5034.5
XS Rating Curve= 0 ,0
Exp/Cntr=0.3,0.1

Type RM Length L Ch R = 1 ,8184    ,460,460,460
BEGIN DESCRIPTION:
Mapping XS 97957e15
END DESCRIPTION:
XS GIS Cut Line= 3
      2706342.21      6950686.15      2706029.71      6949917.92
      2705831.79      6949441.35
#Sta/Elev= 30
  4168.8  527.75  4293.1  525.66  4347.1  525.71  4379.2  524.46  4408.7  526.07
  4455.1  524.87  4462.2   525.6  4467.6  524.36  4486.3  524.32  4498.2  523.31
    4509  523.83  4681.8  521.28  4700.4  521.16  4705.8  523.02  4735.7  519.63
  4812.8  518.44  4836.9  519.11  4876.1   517.2  4962.5  518.58  4992.1  518.24
  4996.5  516.23  5005.7  514.75    5014  514.55  5014.2  514.05    5018  514.55
  5021.4  518.15  5027.3  518.33  5175.4  517.81  5373.8  520.37  5514.2  520.72
#Mann= 3 ,-1 , 0
  4168.8     .05       0    5014     .03       0    5018     .05       0
Bank Sta=5014,5018
XS Rating Curve= 0 ,0
Exp/Cntr=0.3,0.1

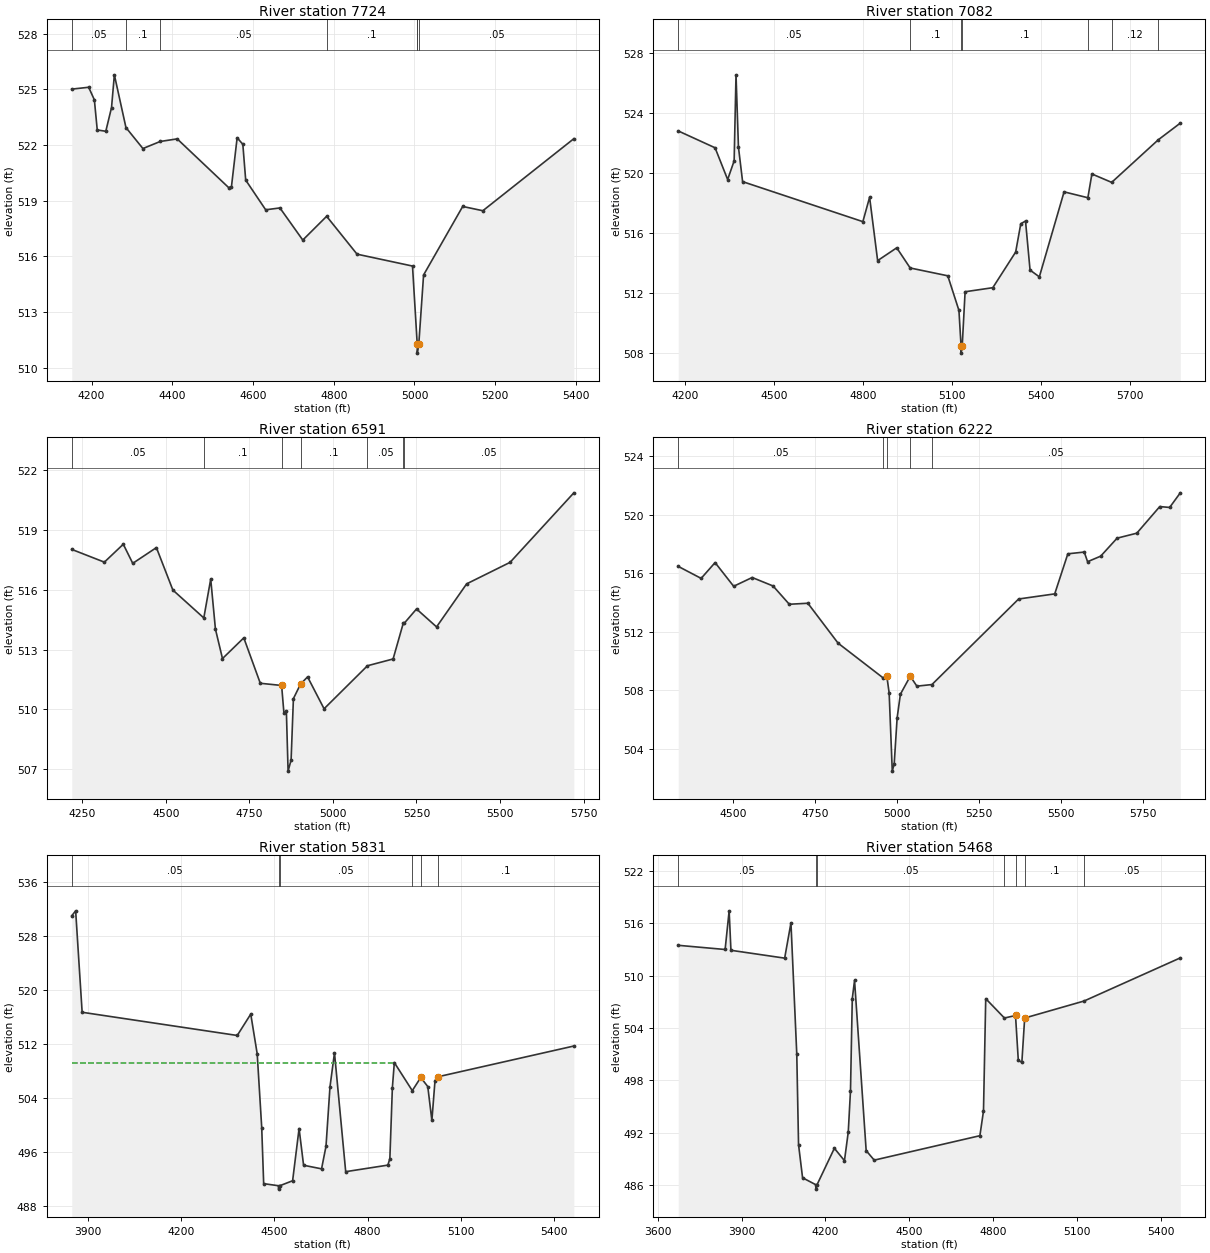
Type RM Length L Ch R = 1 ,7724    ,642,642,642
BEGIN DESCRIPTION:
Mapping XS df42fd54
END DESCRIPTION:
XS GIS Cut Line= 3
       2706691.2      6950095.04      2706136.48      6949535.11
      2705739.48      6949311.96
#Sta/Elev= 30
  4151.1  525.01    4193  525.11  4207.1  524.43  4214.2  522.81  4235.4  522.74
  4249.6  524.02  4256.6  525.78  4285.3  522.94  4327.3  521.81  4370.2  522.19
  4412.2  522.33  4539.5  519.71  4546.6  519.75  4560.7  522.39  4574.8  522.04
  4581.9  520.11  4631.4  518.51  4666.7  518.61  4723.3  516.88  4782.4  518.16
  4857.7  516.12  4995.1  515.48  5006.4   511.4  5006.7  511.29  5006.9  510.79
  5010.7  511.29  5022.5     515  5119.4  518.69  5169.3  518.46  5394.7  522.34
#Mann= 7 ,-1 , 0
  4151.1     .05       0  4285.3      .1       0  4370.2     .05       0
  4782.4      .1       0  5006.4     .05       0  5006.7     .07       0
  5010.7     .05       0
Bank Sta=5006.7,5010.7
XS Rating Curve= 0 ,0
Exp/Cntr=0.3,0.1

Type RM Length L Ch R = 1 ,7082    ,491,491,491
BEGIN DESCRIPTION:
Mapping XS 79344ea5
END DESCRIPTION:
XS GIS Cut Line= 3
      2706977.88      6949782.98       2706408.4      6949043.36
      2705680.14      6948828.34
#Sta/Elev= 30
    4178  522.79  4302.2  521.67  4344.6  519.56  4366.5   520.8  4372.8  526.52
    4381  521.72    4395  519.42  4800.5  516.76  4823.2  518.38  4850.3  514.17
  4914.7  515.02    4960  513.68  5086.8  513.16  5124.4  510.86  5131.5  508.52
  5131.8  508.02  5135.5  508.52  5145.2   512.1  5238.6  512.37  5315.7  514.74
  5332.9  516.62  5348.9   516.8  5364.2  513.54  5395.5  513.09  5478.9  518.74
  5559.1  518.35  5572.7  519.93  5639.4  519.37  5796.4   522.2  5870.8  523.31
#Mann= 7 ,-1 , 0
    4178     .05       0    4960      .1       0  5131.5     .07       0
  5135.5      .1       0  5559.1     .05       0  5639.4     .12       0
  5796.4     .05       0
Bank Sta=5131.5,5135.5
XS Rating Curve= 0 ,0
Exp/Cntr=0.3,0.1

Type RM Length L Ch R = 1 ,6591    ,369,369,369
BEGIN DESCRIPTION:
Mapping XS e58180b9
END DESCRIPTION:
XS GIS Cut Line= 3
      2707068.97      6949275.97      2706534.27      6948716.97
       2705805.1      6948706.55
#Sta/Elev= 30
  4218.2  518.03  4315.8  517.39  4372.4  518.29  4400.7  517.33  4471.5  518.12
  4520.8  515.99  4613.4  514.59  4634.1  516.54  4648.2  514.03  4669.3  512.55
  4733.1  513.59  4782.5  511.31  4846.3   511.2  4853.3   509.8  4860.5  509.92
  4865.7   506.9  4874.7  507.46  4881.6  510.54    4903  511.27    4924  511.63
  4973.4  510.03  5103.3  512.19    5180  512.53  5210.5  514.33  5213.2  514.32
  5250.1  515.04  5310.1  514.14  5400.1   516.3  5530.1  517.38    5721  520.87
#Mann= 7 ,-1 , 0
  4218.2     .05       0  4613.4      .1       0  4846.3     .07       0
    4903      .1       0  5103.3     .05       0  5210.5     .12       0
  5213.2     .05       0
Bank Sta=4846.3,4903
XS Rating Curve= 0 ,0
Exp/Cntr=0.3,0.1

Type RM Length L Ch R = 1 ,6222    ,391,391,391
BEGIN DESCRIPTION:
Mapping XS 7e00708a
END DESCRIPTION:
XS GIS Cut Line= 3
      2707093.29      6948852.37      2706634.96      6948380.16
      2705763.46      6948404.47
#Sta/Elev= 30
  4333.3  516.46  4403.1  515.64  4445.6  516.72  4502.2   515.1  4558.6   515.7
  4622.3  515.12  4671.7  513.87  4728.3  513.94  4820.4  511.21  4958.5  508.82
  4968.8  508.98    4976   507.8  4985.5  502.46  4991.4  502.96  5000.3   506.1
  5010.3  507.72  5040.3  508.95  5060.4  508.27  5106.4  508.38  5370.5  514.23
  5480.5  514.58  5520.5  517.32  5570.5  517.44  5580.6  516.78  5620.6  517.16
  5670.6  518.39  5730.6  518.73  5800.6  520.55  5830.7  520.49  5863.2  521.49
#Mann= 5 ,-1 , 0
  4333.3     .05       0  4958.5      .1       0  4968.8     .07       0
  5040.3      .1       0  5106.4     .05       0
Bank Sta=4968.8,5040.3
XS Rating Curve= 0 ,0
Exp/Cntr=0.3,0.1

Type RM Length L Ch R = 1 ,5831    ,363,363,363
BEGIN DESCRIPTION:
Mapping XS 816b6954
END DESCRIPTION:
XS GIS Cut Line= 3
      2707662.08      6948742.78      2706750.92      6948033.79
      2706294.35      6947962.61
#Sta/Elev= 30
  3847.4  530.94  3859.9  531.67  3880.8  516.67  4380.2  513.24  4423.7   516.4
  4444.5  510.51    4459  499.61  4465.3  491.33  4513.1  491.02  4513.3  490.52
  4517.1  491.02  4558.5  491.76  4579.3  499.48  4593.8  494.05  4651.7  493.52
    4666  496.86  4678.8  505.64  4693.3  510.67  4729.4   493.1  4865.2  494.07
  4871.6  495.03  4879.7  505.53    4886  509.23  4943.8  505.08  4971.1  507.03
  4993.7  505.68  5006.9  500.67    5017  506.58  5027.1  507.14    5464  511.68
#Mann= 6 ,-1 , 0
  3847.4     .05       0  4513.1     .07       0  4517.1     .05       0
  4943.8      .1       0  4971.1     .05       0  5027.1      .1       0
#XS Ineff= 2 , 0
       0  4886.1  509.23               0
Permanent Ineff=
       F       F
Bank Sta=4971.1,5027.1
XS Rating Curve= 0 ,0
Exp/Cntr=0.3,0.1

Type RM Length L Ch R = 1 ,5468    ,499,499,499
BEGIN DESCRIPTION:
Mapping XS ba132c45
END DESCRIPTION:
XS GIS Cut Line= 3
      2707842.38      6948480.28      2706886.51      6947723.41
      2706311.87      6947664.39
#Sta/Elev= 30
    3673  513.48  3840.8     513  3855.2  517.43  3861.6  512.91  4053.9  512.01
  4076.4  516.05  4097.2  501.05  4103.6  490.63    4118  486.85  4165.7  486.05
  4165.9  485.55  4169.7  486.05  4231.8  490.23  4267.9  488.81  4281.5  492.09
  4289.5  496.82  4295.9  507.37    4304  509.46  4345.6  489.96  4374.4  488.87
  4752.6  491.67  4765.5   494.5  4773.5  507.37  4840.4  505.15  4880.1  505.44
  4890.1  500.29  4902.8  500.08  4912.9  505.15  5125.6   507.1  5469.9  512.04
#Mann= 7 ,-1 , 0
    3673     .05       0  4165.7     .07       0  4169.7     .05       0
  4840.4      .1       0  4880.1     .05       0  4912.9      .1       0
  5125.6     .05       0
#XS Ineff= 2 , 0
       0  4773.5  507.37               0
Permanent Ineff=
       F       F
Bank Sta=4880.1,4912.9
XS Rating Curve= 0 ,0
Exp/Cntr=0.3,0.1

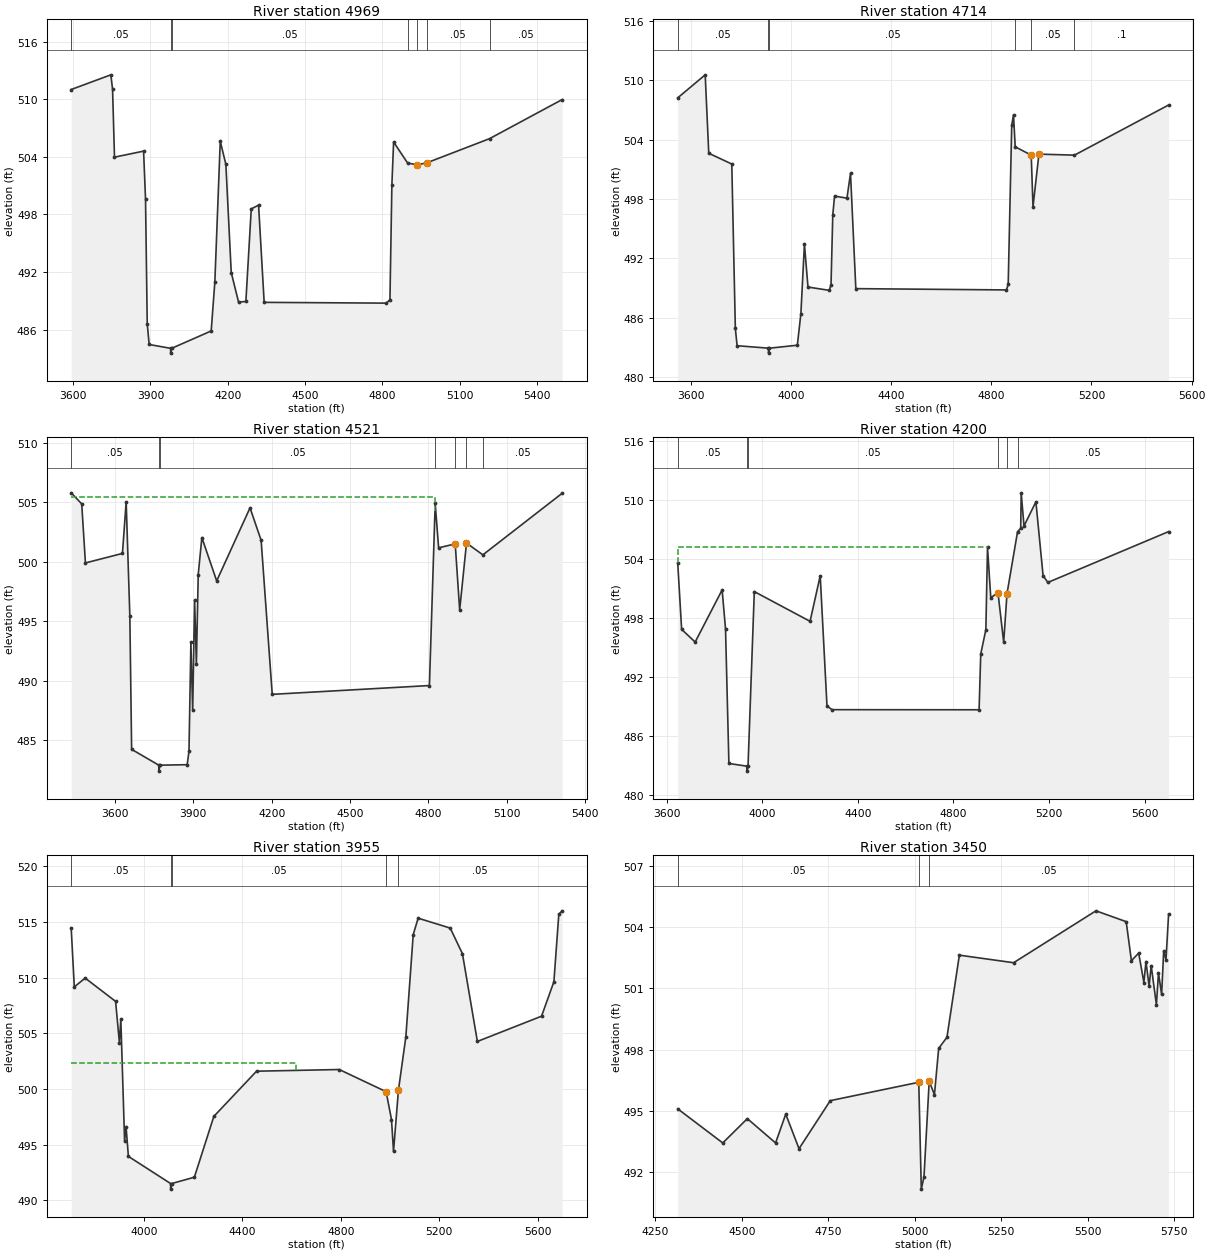
Type RM Length L Ch R = 1 ,4969    ,255,255,255
BEGIN DESCRIPTION:
Mapping XS 6e61cda4
END DESCRIPTION:
XS GIS Cut Line= 3
      2708045.01      6948329.11      2706995.89      6947390.08
        2706515.      6947263.35
#Sta/Elev= 30
  3592.7  511.01  3746.5  512.54  3753.2  511.05  3760.7  503.96  3873.6  504.59
  3881.1  499.62  3887.8  486.58  3895.3  484.44  3978.5  484.04  3978.8  483.54
  3982.5  484.04    4136  485.85  4150.2  490.96  4171.2  505.61  4192.9  503.22
  4213.8  491.94  4242.2  488.86  4270.6  488.92  4291.5  498.57  4319.9  498.96
  4341.6  488.83  4815.6  488.75  4829.8  489.09  4837.3  501.08    4844  505.54
  4898.6  503.34    4936  503.17  4971.9  503.36  5216.5  505.89    5498  509.96
#Mann= 7 ,-1 , 0
  3592.7     .05       0  3978.5     .07       0  3982.5     .05       0
  4898.6      .1       0    4936     .05       0  4971.9     .05       0
  5216.5     .05       0
#XS Ineff= 2 , 0
       0    4844  505.54               0
Permanent Ineff=
       F       F
Bank Sta=4936,4971.9
XS Rating Curve= 0 ,0
Exp/Cntr=0.3,0.1

Type RM Length L Ch R = 1 ,4714    ,193,193,193
BEGIN DESCRIPTION:
Mapping XS 8b3725a6
END DESCRIPTION:
XS GIS Cut Line= 3
       2708162.4      6948189.79      2707154.74      6947185.65
      2706624.16      6947105.89
#Sta/Elev= 30
  3548.9  508.21  3658.6  510.54  3672.8  502.61  3764.7  501.52  3778.9   484.9
  3785.9  483.15  3911.2   482.9  3911.4   482.4  3915.2   482.9  4026.3   483.2
  4040.5   486.4  4054.6  493.41  4068.8  489.08  4153.6  488.75  4160.7   489.3
  4167.7  496.36  4174.8  498.28  4224.3  498.07  4238.5  500.58  4259.7  488.92
  4860.7  488.79  4867.8  489.34  4881.9  505.45    4889  506.48  4895.8  503.26
  4959.7  502.42  4966.8   497.2  4990.4  502.52  5132.4  502.42    5508  507.49
#Mann= 6 ,-1 , 0
  3548.9     .05       0  3911.2     .07       0  3915.2     .05       0
  4895.8      .1       0  4959.7     .05       0  5132.4      .1       0
#XS Ineff= 2 , 0
       0    4889  506.48               0
Permanent Ineff=
       F       F
Bank Sta=4959.7,4990.4
XS Rating Curve= 0 ,0
Exp/Cntr=0.3,0.1

Type RM Length L Ch R = 1 ,4521    ,321,321,321
BEGIN DESCRIPTION:
Mapping XS 5f4b6b04
END DESCRIPTION:
XS GIS Cut Line= 3
      2708332.68      6948041.26      2707241.98      6947031.14
      2706851.33      6946998.58
#Sta/Elev= 30
  3432.9  505.79  3473.1  504.86  3487.3   499.9    3629   500.7  3643.2  505.04
  3657.3  495.42  3664.1  484.24  3768.2  482.91  3768.4  482.41  3772.2  482.91
  3876.7  482.95  3883.6  484.07  3890.9  493.22  3897.7  487.51  3905.1  496.78
  3911.9  491.44    3919  498.92  3932.9  502.03  3989.6  498.39  4117.2  504.53
  4159.7   501.8  4202.2  488.86  4803.7   489.6  4825.8   504.9  4838.9  501.17
  4902.4   501.5  4919.5  495.95  4945.6  501.57  5008.3  500.58  5311.5  505.75
#Mann= 7 ,-1 , 0
  3432.9     .05       0  3768.2     .07       0  3772.2     .05       0
  4825.8      .1       0  4902.4     .05       0  4945.6      .1       0
  5008.3     .05       0
#XS Ineff= 2 , 0
       0  4824.7  505.46               0
Permanent Ineff=
       F       F
Bank Sta=4902.4,4945.6
XS Rating Curve= 0 ,0
Exp/Cntr=0.3,0.1

Type RM Length L Ch R = 1 ,4200    ,245,245,245
BEGIN DESCRIPTION:
Mapping XS dd93b978
END DESCRIPTION:
XS GIS Cut Line= 5
      2708389.35       6947760.7      2707448.93      6946857.16
      2707407.65      6946830.09      2707327.14      6946805.79
      2706710.94      6946825.32
#Sta/Elev= 30
  3646.5  503.64  3662.9  496.85  3719.5  495.56  3832.4  500.87  3846.6  496.88
  3860.7  483.19  3936.7  482.91  3936.9  482.41  3940.7  482.91    3967   500.7
  4200.3  497.67  4242.8  502.31  4271.1  489.05  4292.2  488.67  4907.6  488.66
  4914.5  494.35  4935.9  496.81  4942.8   505.2  4956.4  500.08  4986.6  500.59
  5010.5  495.54  5024.4  500.49  5068.5   506.8  5081.7  507.14  5083.7  510.76
  5095.5  507.38  5145.3  509.84  5175.3  502.33  5195.3  501.63  5700.6  506.81
#Mann= 6 ,-1 , 0
  3646.5     .05       0  3936.7     .03       0  3940.7     .05       0
  4986.6     .05       0  5024.4      .1       0  5068.5     .05       0
#XS Ineff= 2 , 0
       0  4942.8   505.2               0
Permanent Ineff=
       F       F
Bank Sta=4986.6,5024.4
XS Rating Curve= 0 ,0
Exp/Cntr=0.3,0.1

Type RM Length L Ch R = 1 ,3955    ,505,505,505
BEGIN DESCRIPTION:
Mapping XS 05f3fa59
END DESCRIPTION:
XS GIS Cut Line= 5
      2708614.17      6947121.14      2707764.24      6946592.99
      2707467.39      6946607.85      2707274.97       6946618.6
      2706772.67      6946654.74
#Sta/Elev= 30
  3704.4  514.42    3717  509.17  3761.1  509.96  3884.7  507.87  3900.1  504.17
  3905.9   506.3  3921.3  495.32  3927.2  496.63  3936.7  493.95  4108.2  491.51
  4108.5  491.01  4112.2  491.51  4204.7  492.08  4283.8  497.54  4457.3   501.6
  4793.4  501.75  4983.6  499.76  5005.5  497.26  5013.7  494.39  5033.7  499.89
  5063.8  504.68  5093.8  513.87  5113.8  515.34  5244.1  514.45  5293.7  512.15
  5354.4  504.27  5615.1  506.54  5665.2  509.63  5685.2  515.68  5698.6     516
#Mann= 5 ,-1 , 0
  3704.4     .05       0  4108.2     .04       0  4112.2     .05       0
  4983.6     .05       0  5033.7     .05       0
#XS Ineff= 2 , 0
       0  4619.1  502.35               0
Permanent Ineff=
       F       F
Bank Sta=4983.6,5033.7
XS Rating Curve= 0 ,0
Exp/Cntr=0.3,0.1

Type RM Length L Ch R = 1 ,3450    ,688,688,688
BEGIN DESCRIPTION:
Mapping XS 5b8d20f3
END DESCRIPTION:
XS GIS Cut Line= 5
      2707702.67      6945656.97      2707794.91      6945812.24
      2707675.92      6946058.46      2707474.16      6946171.61
      2706859.65      6946574.14
#Sta/Elev= 30
  4314.6  495.11  4444.9  493.44    4516  494.63  4597.7  493.44  4627.1  494.85
  4665.5  493.16  4755.9  495.51  5011.9  496.41  5019.2  491.18    5027  491.78
  5042.1  496.47  5057.2   495.8  5069.5  498.07  5093.4  498.61  5129.3  502.63
  5286.2  502.26  5524.4   504.8  5611.9  504.27    5627  502.36    5648  502.73
  5663.1  501.29  5669.1  502.32  5678.2  501.11  5684.2  502.12  5699.3   500.2
  5705.3  501.76  5714.4  500.71  5720.4  502.85    5727   502.4  5734.6  504.64
#Mann= 3 ,-1 , 0
  4314.6     .05       0  5011.9     .04       0  5042.1     .05       0
Bank Sta=5011.9,5042.1
XS Rating Curve= 0 ,0
Exp/Cntr=0.3,0.1

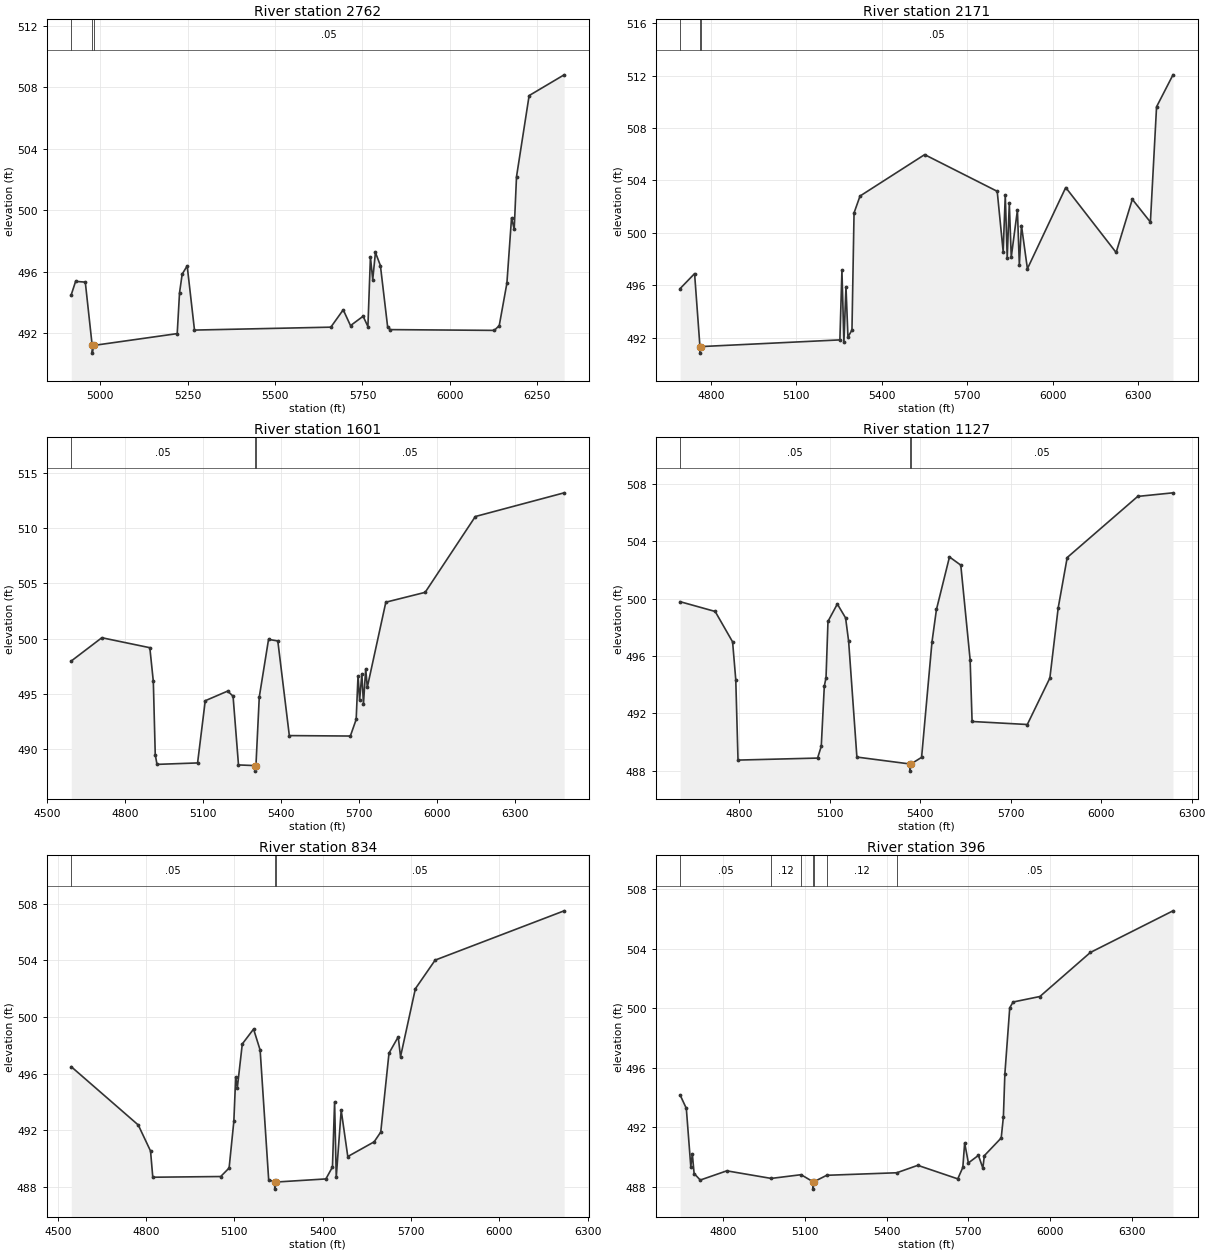
Type RM Length L Ch R = 1 ,2762    ,591,591,591
BEGIN DESCRIPTION:
Mapping XS 0ce27c31
END DESCRIPTION:
XS GIS Cut Line= 2
      2707696.21      6945614.34      2706632.46      6946539.07
#Sta/Elev= 30
  4917.2  494.52  4929.5  495.38  4957.2  495.33  4976.9  491.21  4977.2  490.71
  4980.9  491.21  5220.1  491.98  5226.7  494.63  5234.3  495.85  5248.6  496.39
  5269.5  492.21  5659.5   492.4  5694.9  493.53  5715.7   492.5  5751.8  493.11
  5765.5  492.44  5772.7  496.96  5779.3  495.49    5787  497.26  5801.2  496.41
  5822.1  492.38  5829.7  492.24  6126.9  492.19  6141.1   492.5    6163  495.26
  6176.3  499.52  6183.9  498.77  6190.5  502.19  6226.6  507.47  6326.7  508.82
#Mann= 3 ,-1 , 0
  4917.2     .05       0  4976.9     .03       0  4980.9     .05       0
Bank Sta=4976.9,4980.9
XS Rating Curve= 0 ,0
Exp/Cntr=0.3,0.1

Type RM Length L Ch R = 1 ,2171    ,570,570,570
BEGIN DESCRIPTION:
Mapping XS d4fca2b2
END DESCRIPTION:
XS GIS Cut Line= 4
      2707368.36      6945222.42      2707132.53      6945417.91
      2706877.48       6945685.7      2706165.68      6946462.58
#Sta/Elev= 30
    4692  495.75  4742.6  496.89  4761.4  491.32  4761.6  490.82  4765.4  491.32
  5252.6  491.83  5259.8  497.13  5266.7  491.64    5274  495.89  5280.9  492.05
    5295  492.58  5302.3  501.52  5323.3  502.81  5550.1  505.97  5804.8  503.17
  5825.7  498.57  5833.1  502.87  5839.9  498.11  5847.3  502.24  5854.1  498.15
  5875.7  501.73  5882.5  497.55  5889.9  500.56  5910.8  497.26  6045.3  503.46
  6222.2   498.5    6279  502.56  6342.5  500.82  6364.1  509.62  6421.8  512.06
#Mann= 3 ,-1 , 0
    4692     .05       0  4761.4     .03       0  4765.4     .05       0
Bank Sta=4761.4,4765.4
XS Rating Curve= 0 ,0
Exp/Cntr=0.3,0.1

Type RM Length L Ch R = 1 ,1601    ,474,474,474
BEGIN DESCRIPTION:
Mapping XS dac30448
END DESCRIPTION:
XS GIS Cut Line= 3
      2706945.79      6944804.59      2706663.97      6945122.85
      2705812.86      6946324.34
#Sta/Elev= 30
    4592  497.99  4709.5  500.09  4894.3  499.19  4907.8  496.14  4915.2  489.53
  4921.9  488.65  5078.2  488.78  5107.7   494.4  5193.9  495.27  5214.8  494.81
  5235.7   488.6  5298.9  488.54  5299.2  488.04  5302.9  488.54  5315.7  494.73
  5351.4  499.94  5387.1   499.8  5431.4  491.25  5666.4  491.21  5688.8  492.71
  5695.9  496.63  5702.1  494.46  5710.7  496.83  5716.9  494.11  5725.5  497.29
  5731.6  495.61    5803   503.3  5954.4  504.19  6147.6  511.04  6489.5  513.18
#Mann= 3 ,-1 , 0
    4592     .05       0  5298.9     .03       0  5302.9     .05       0
Bank Sta=5298.9,5302.9
XS Rating Curve= 0 ,0
Exp/Cntr=0.3,0.1

Type RM Length L Ch R = 1 ,1127    ,293,293,293
BEGIN DESCRIPTION:
Mapping XS 48af2443
END DESCRIPTION:
XS GIS Cut Line= 3
      2706775.03      6944588.53      2706416.35      6944744.86
      2705802.33      6945826.11
#Sta/Elev= 30
  4603.4  499.78  4719.5   499.1  4777.3  496.98  4787.8  494.35  4795.3  488.74
  5059.2  488.88  5071.4   489.7  5081.5  493.89  5087.2  494.49  5093.7  498.41
  5124.7  499.62  5152.1  498.65  5162.2  497.02  5189.6  488.95    5365  488.47
  5365.2  487.97    5369  488.47  5404.2  488.93  5438.7  496.98  5453.5  499.24
  5496.7   502.9  5534.2  502.33  5565.2  495.73  5571.7  491.43  5754.9  491.22
  5829.7  494.46  5857.3  499.35  5887.2  502.86  6121.1  507.12  6238.1  507.37
#Mann= 3 ,-1 , 0
  4603.4     .05       0    5365     .03       0    5369     .05       0
Bank Sta=5365,5369
XS Rating Curve= 0 ,0
Exp/Cntr=0.3,0.1

Type RM Length L Ch R = 1 ,834     ,438,438,438
BEGIN DESCRIPTION:
Mapping XS fd270ff3
END DESCRIPTION:
XS GIS Cut Line= 3
      2706555.74       6944250.2      2706219.46      6944549.87
      2705674.62      6945645.77
#Sta/Elev= 30
    4546  496.48  4773.4  492.37  4815.2  490.53  4822.8  488.68  5053.5  488.73
  5082.1  489.33  5098.2  492.63  5104.5  495.76  5110.1  495.01  5126.9  498.09
  5165.2  499.14  5187.5  497.66  5216.5  488.51  5236.9  488.34  5237.2  487.84
  5240.9  488.34  5410.9  488.56  5433.2   489.4  5440.5  494.01  5446.1  488.68
  5462.9  493.41  5485.3  490.14  5574.9  491.18  5597.3  491.87  5625.3  497.44
  5656.6  498.59  5664.5  497.19  5714.9  501.99  5782.1  504.01  6220.3  507.49
#Mann= 3 ,-1 , 0
    4546     .05       0  5236.9     .03       0  5240.9     .05       0
Bank Sta=5236.9,5240.9
XS Rating Curve= 0 ,0
Exp/Cntr=0.3,0.1

Type RM Length L Ch R = 1 ,396     ,0,0,0
BEGIN DESCRIPTION:
Mapping XS b3dd6695
END DESCRIPTION:
XS GIS Cut Line= 6
      2706031.36      6943985.64      2705872.16      6944288.52
      2705872.37       6944704.3      2705952.35      6944792.71
      2705818.54      6944905.54      2705530.29       6945558.2
#Sta/Elev= 30
  4641.4  494.16    4664  493.27  4680.4  489.36  4686.1   490.2  4692.6  488.89
  4715.2  488.45  4812.7  489.07  4975.7  488.56  5085.5  488.81  5129.1  488.34
  5129.4  487.84  5133.1  488.34  5179.6  488.77    5437  488.94  5514.3  489.44
  5661.1  488.53  5679.7   489.3  5686.4  490.95  5700.1   489.6    5737  490.11
  5753.3  489.25  5758.7  490.09  5820.7  491.28  5828.7   492.7  5834.1  495.58
    5852  500.03  5864.4  500.42  5962.8  500.79  6148.1  503.75  6451.7  506.55
#Mann= 7 ,-1 , 0
  4641.4     .05       0  4975.7     .12       0  5085.5     .05       0
  5129.1     .07       0  5133.1     .05       0  5179.6     .12       0
    5437     .05       0
Bank Sta=5129.1,5133.1
XS Rating Curve= 0 ,0
Exp/Cntr=0.3,0.1

Chan Stop Cuts=-1
Use User Specified Reach Order=0
Composite Channel Slope=5