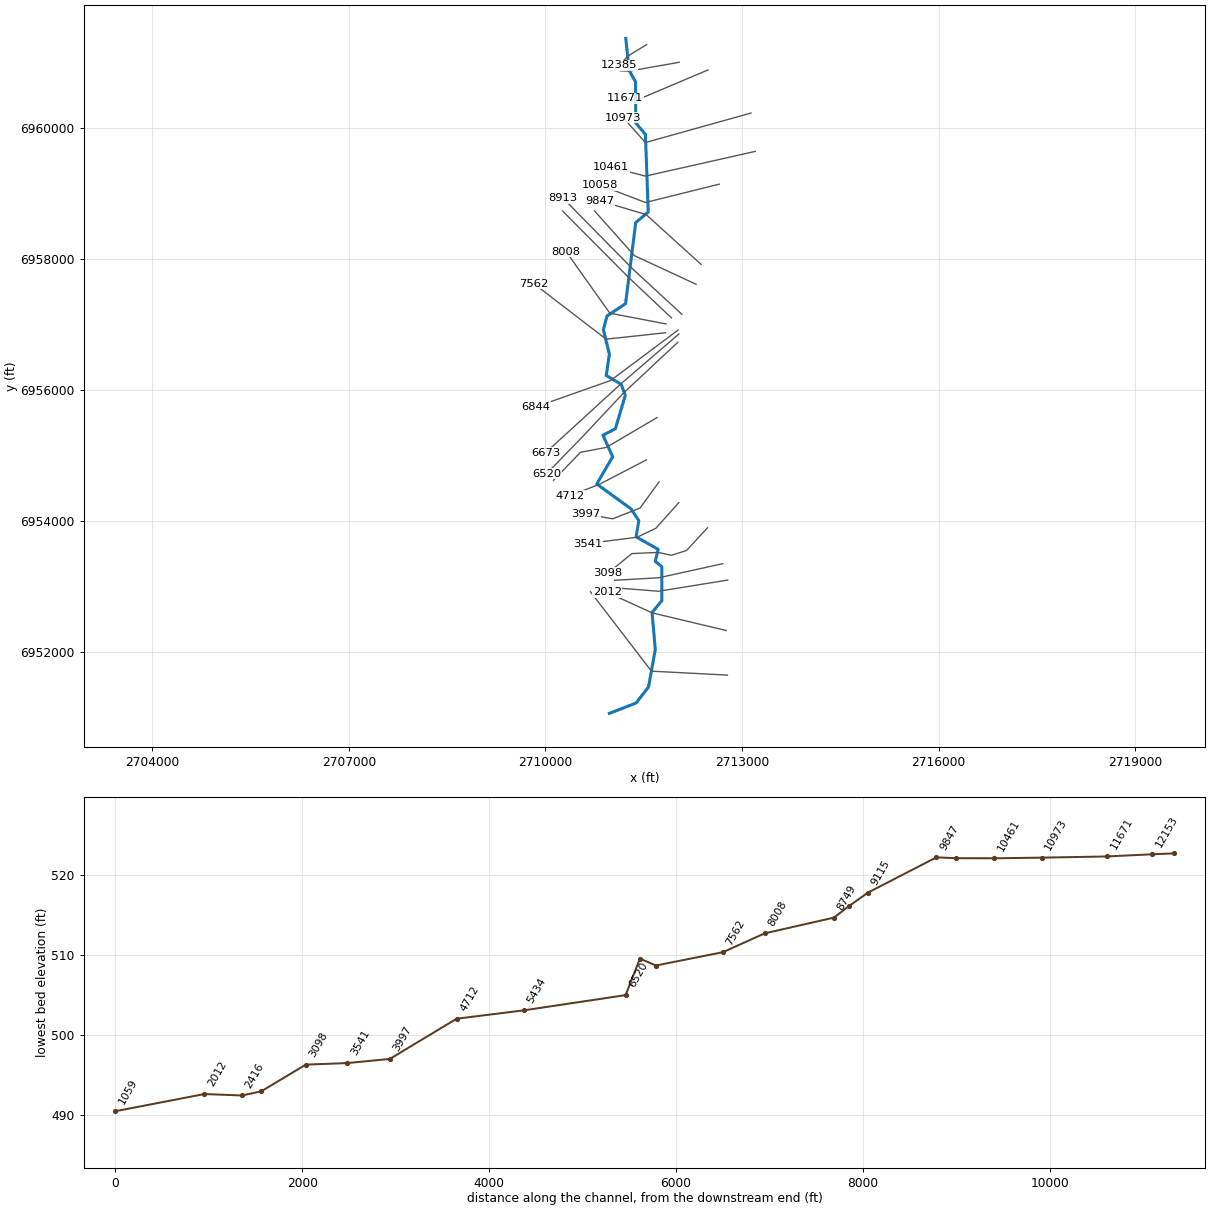
--- Rocky Cedar T7.prj (project) ---

Proj Title=Rocky Cedar T7 Base Level Engineering
Current Plan=p01
Default Exp/Contr=0.3,0.1
English Units
Geom File=g01
Flow File=f01
Plan File=p01
Y Axis Title=Elevation
X Axis Title(PF)=Main Channel Distance
X Axis Title(XS)=Station
BEGIN DESCRIPTION:
Rocky Cedar T7
END DESCRIPTION:
DSS Export Rating Curves= 0
DSS Export Rating Curve Sorted= 0
DSS Export Volume Flow Curves= 0
DXF OffsetX= 0
DXF OffsetY= 0
DXF ScaleX= 1
DXF ScaleY= 10

--- Rocky Cedar T7.p01 (plan) ---

Plan Title=Multiple Run
Short Identifier=Multiple
Geom File=g01
Flow File=f01
Subcritical Flow
K Sum by GR= 0
Std Step Tol= 0.01
Critical Tol= 0.01
Num of Std Step Trials= 20
Max Error Tol= 0.3
Flow Tol Ratio= 0.001
Split Flow NTrial= 30
Split Flow Tol= 0.02
Split Flow Ratio= 0.02
Log Output Level= 0
Friction Slope Method= 1
Unsteady Friction Slope Method= 2
Unsteady Bridges Friction Slope Method= 1
Parabolic Critical Depth
Global Vel Dist=  1 , 1 , 1
Global Log Level= 0
CheckData=True
Encroach Param= -1, 0, 0, 0
BEGIN DESCRIPTION:
Multiple Run
END DESCRIPTION:

--- Rocky Cedar T7.f01 (steady flow) ---

Flow Title=Multiple
Number of Profiles=7
Profile Names=10-year,25-year,50-year,1pct_min,100-year,1pct_plu,500-year
River Rch & RM= Rocky Cedar T7,Reach-1,12385
     612     815     978     582    1162    2318    1638
River Rch & RM= Rocky Cedar T7,Reach-1,9847
    1003    1371    1673    1011    2016    4023    2930
Boundary for River Rch & Prof#=Rocky Cedar T7,Reach-1,1
Up Type=0
Dn Type=3
Dn Slope=0.005
Boundary for River Rch & Prof#=Rocky Cedar T7,Reach-1,2
Up Type=0
Dn Type=3
Dn Slope=0.005
Boundary for River Rch & Prof#=Rocky Cedar T7,Reach-1,3
Up Type=0
Dn Type=3
Dn Slope=0.005
Boundary for River Rch & Prof#=Rocky Cedar T7,Reach-1,4
Up Type=0
Dn Type=3
Dn Slope=0.005
Boundary for River Rch & Prof#=Rocky Cedar T7,Reach-1,5
Up Type=0
Dn Type=3
Dn Slope=0.005
Boundary for River Rch & Prof#=Rocky Cedar T7,Reach-1,6
Up Type=0
Dn Type=3
Dn Slope=0.005
Boundary for River Rch & Prof#=Rocky Cedar T7,Reach-1,7
Up Type=0
Dn Type=3
Dn Slope=0.005

--- Rocky Cedar T7.g01 (geometry) ---

Geom Title=Existing Conditions
Program Version=4.10

River Reach=Rocky Cedar T7  ,Reach-1
Reach XY= 30
        2711226.        6961361.       2711277.2       6960871.5
      2711375.49      6960695.79      2711377.05      6960071.43
      2711525.62      6959895.84      2711568.74       6958710.7
      2711377.64      6958549.17      2711222.49      6957312.25
      2710939.37      6957124.32      2710884.08       6956914.3
      2710976.21      6956540.79      2710927.61      6956217.02
      2711156.57      6956081.64      2711218.44        6955911.
      2711066.83      6955404.01      2710877.43      6955304.81
        2711026.      6954976.47      2710783.31      6954560.89
      2711306.36      6954181.47      2711425.06      6954000.52
      2711383.64      6953754.54      2711720.71      6953563.68
       2711675.7      6953381.34      2711775.11      6953300.66
       2711776.4      6952781.13      2711627.05      6952600.57
      2711676.23      6952035.93      2711572.46      6951462.46
      2711382.41      6951218.77        2710976.        6951061.

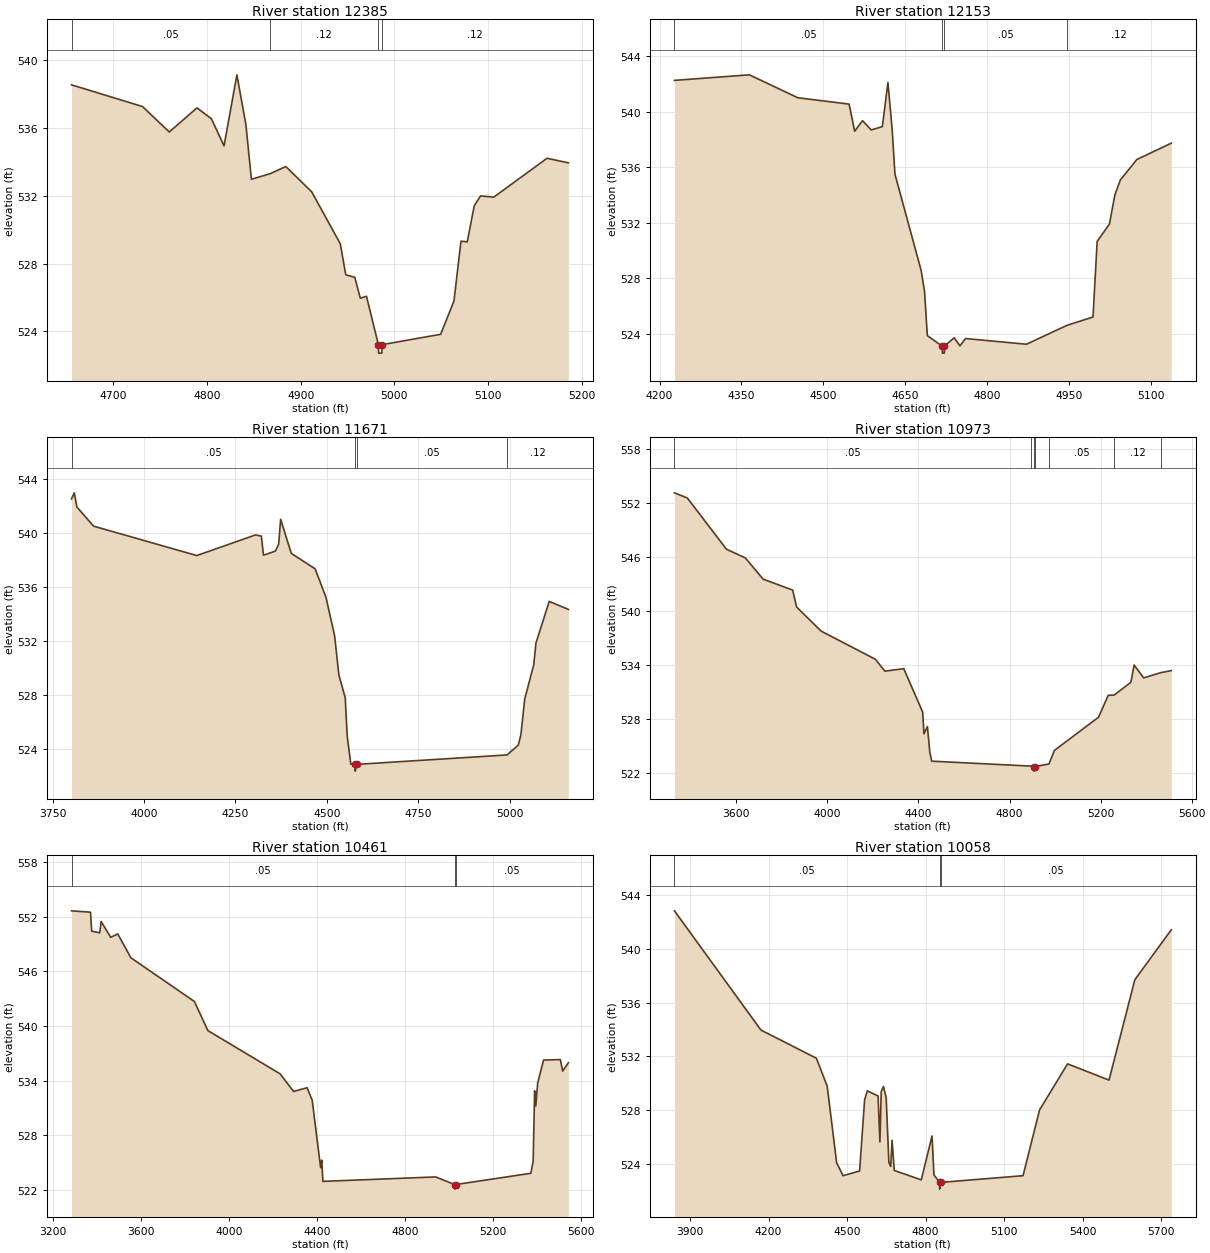
Type RM Length L Ch R = 1 ,12385   ,232,232,232
BEGIN DESCRIPTION:
Rocky Cedar T7 19.0
END DESCRIPTION:
XS GIS Cut Line= 3
      2711545.18      6961265.76      2711256.47      6961090.25
      2711128.03      6960946.56
#Sta/Elev= 30
  4655.2  538.54    4731  537.26  4759.6  535.76  4789.2  537.18  4804.6  536.54
  4818.1  534.94  4831.8  539.13  4841.4  536.21  4847.3  532.97  4867.3   533.3
  4884.1  533.72  4911.7  532.23  4942.2  529.17  4948.1  527.34  4957.7  527.19
  4963.6  525.96  4970.2  526.07  4982.9  523.22  4983.1  522.72  4986.6  522.72
  4986.9  523.22  5049.4  523.83  5063.6  525.79  5071.1  529.32  5077.8  529.28
  5085.3  531.41    5092  531.99  5106.2  531.92    5163  534.21  5185.8  533.94
#Mann= 4 ,-1 , 0
  4655.2     .05       0  4867.3     .12       0  4982.9     .07       0
  4986.9     .12       0
Bank Sta=4982.9,4986.9
XS Rating Curve= 0 ,0
Exp/Cntr=0.3,0.1

Type RM Length L Ch R = 1 ,12153   ,482,482,482
BEGIN DESCRIPTION:
Rocky Cedar T7 18.0
END DESCRIPTION:
XS GIS Cut Line= 3
      2712041.19      6960995.55        2711276.        6960861.
      2711142.78      6960864.81
#Sta/Elev= 30
  4227.3  542.25  4364.6  542.65  4453.3     541  4547.3  540.54  4557.5  538.59
  4571.9  539.35  4587.9  538.68  4608.2  538.92  4618.4   542.1  4626.2  538.69
  4631.3  535.49  4679.3  528.56  4685.5  527.04  4690.6  523.87  4717.9  523.11
  4718.2  522.61  4721.7  522.61  4721.9  523.11  4739.8  523.72  4750.4  523.13
  4760.5  523.66  4872.2  523.25  4946.4  524.61  4994.1  525.21  5001.7  530.65
  5024.2  531.91  5034.2  534.01  5044.2  535.08  5074.3  536.55  5137.5  537.73
#Mann= 4 ,-1 , 0
  4227.3     .05       0  4717.9     .07       0  4721.9     .05       0
  4946.4     .12       0
Bank Sta=4717.9,4721.9
XS Rating Curve= 0 ,0
Exp/Cntr=0.3,0.1

Type RM Length L Ch R = 1 ,11671   ,698,698,698
BEGIN DESCRIPTION:
Rocky Cedar T7 17.0
END DESCRIPTION:
XS GIS Cut Line= 3
      2712479.51      6960878.35        2711376.        6960411.
      2711219.61      6960447.99
#Sta/Elev= 30
  3801.6  542.52  3809.2  542.97  3816.3  541.92    3862   540.5  4144.2  538.32
    4305  539.85  4320.9  539.76  4326.7  538.35  4359.3  538.65  4368.2  539.16
  4373.7  541.01  4402.8  538.48  4467.9  537.34  4497.5  535.24  4521.2  532.39
    4533  529.46  4550.3  527.78  4555.7  524.95  4565.6  522.85  4577.4  522.84
  4577.6  522.34  4581.4  522.84    4993  523.54  5023.7  524.27  5030.8  525.03
  5041.1  527.66    5066  530.23  5071.9  531.82  5108.3  534.92  5160.7  534.33
#Mann= 4 ,-1 , 0
  3801.6     .05       0  4577.4     .07       0  4581.4     .05       0
    4993     .12       0
Bank Sta=4577.4,4581.4
XS Rating Curve= 0 ,0
Exp/Cntr=0.3,0.1

Type RM Length L Ch R = 1 ,10973   ,512,512,512
BEGIN DESCRIPTION:
Rocky Cedar T7 16.0
END DESCRIPTION:
XS GIS Cut Line= 3
      2713136.34      6960220.94      2711526.01      6959771.01
      2711185.47      6960151.46
#Sta/Elev= 30
    3328  553.17  3384.5   552.6  3556.8  546.89  3639.2  545.93  3717.8  543.56
  3847.5  542.34  3864.8  540.46  3972.1  537.78  4210.9  534.64  4252.4  533.32
  4335.5  533.59  4418.6  528.75  4423.9  526.35  4439.3  527.15  4449.7  524.32
    4458   523.3    4893  522.75  4907.4  522.69  4907.7  522.19  4911.4  522.69
  4973.4  522.99  4997.4   524.5    5191  528.19  5233.6  530.63  5259.8  530.66
  5333.1  532.08  5347.3     534  5389.2  532.57  5464.2  533.15  5510.6  533.38
#Mann= 7 ,-1 , 0
    3328     .05       0    4893     .12       0  4907.4     .04       0
  4911.4     .12       0  4973.4     .05       0  5259.8     .12       0
  5464.2     .05       0
Bank Sta=4907.4,4911.4
XS Rating Curve= 0 ,0
Exp/Cntr=0.3,0.1

Type RM Length L Ch R = 1 ,10461   ,403,403,403
BEGIN DESCRIPTION:
Rocky Cedar T7 15.0
END DESCRIPTION:
XS GIS Cut Line= 3
      2713201.03      6959636.01        2711526.      6959258.71
      2711000.92      6959393.88
#Sta/Elev= 30
    3283  552.66  3369.5  552.51  3374.7  550.43  3411.2  550.25  3417.9  551.48
  3461.2  549.75  3493.2  550.13  3552.8  547.51  3841.7  542.71  3903.2  539.51
  4231.2  534.77  4292.7  532.83  4354.2  533.24  4377.5  531.86  4415.7  524.46
  4420.8   525.3    4426  522.96  4938.5  523.45  5025.5  522.61  5025.8  522.11
  5029.5  522.61  5371.7  523.85  5382.1   525.2  5388.7   532.9  5393.9  531.24
  5402.7  533.77  5429.4  536.28  5505.7  536.33  5516.3  535.07  5542.2  535.98
#Mann= 3 ,-1 , 0
    3283     .05       0  5025.5     .03       0  5029.5     .05       0
Bank Sta=5025.5,5029.5
XS Rating Curve= 0 ,0
Exp/Cntr=0.3,0.1

Type RM Length L Ch R = 1 ,10058   ,211,211,211
BEGIN DESCRIPTION:
Rocky Cedar T7 14.0
END DESCRIPTION:
XS GIS Cut Line= 3
      2712650.98        6959136.      2711525.91      6958855.96
      2710835.98      6959119.93
#Sta/Elev= 30
  3840.6  542.85  4171.1  533.97  4382.8  531.87  4424.1   529.8  4460.2  524.09
  4484.7  523.12    4548  523.47  4567.1  528.76  4577.4  529.44  4618.6  529.06
  4625.5  525.64  4630.6  529.38  4639.2  529.77  4649.5  528.94  4659.8  524.11
  4666.8  523.81    4672  525.76  4680.4  523.51  4783.5  522.81  4824.7  526.08
    4832  523.18  4853.6  522.62  4853.9  522.12  4857.6  522.62  5172.3  523.12
  5235.5  528.02  5342.5  531.45  5500.8  530.24  5599.5  537.72  5738.7  541.44
#Mann= 3 ,-1 , 0
  3840.6     .05       0  4853.6     .03       0  4857.6     .05       0
#XS Ineff= 2 , 0
       0  4577.4  529.44               0
Permanent Ineff=
       F       F
Bank Sta=4853.6,4857.6
XS Rating Curve= 0 ,0
Exp/Cntr=0.3,0.1

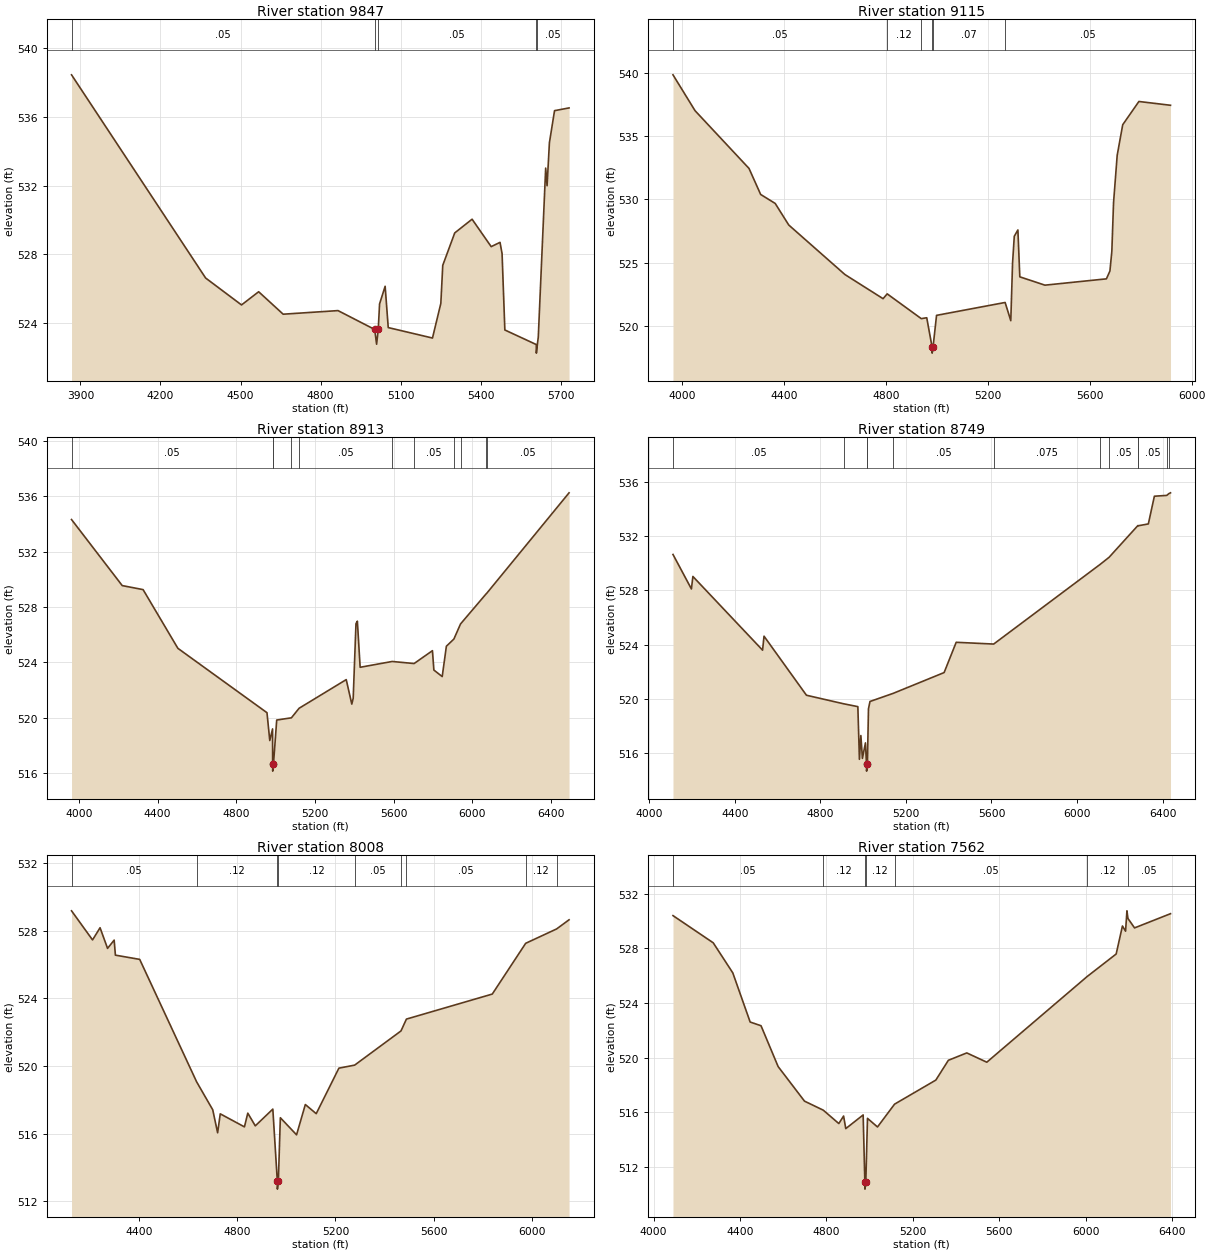
Type RM Length L Ch R = 1 ,9847    ,732,732,732
BEGIN DESCRIPTION:
Rocky Cedar T7 13.0
END DESCRIPTION:
XS GIS Cut Line= 3
      2712376.03      6957910.98      2711536.15      6958671.88
      2710835.45      6958880.52
#Sta/Elev= 30
  3866.7  538.46  4369.2  526.61  4503.7  525.04  4567.9  525.81  4659.8   524.5
  4865.3  524.71  5002.7  523.61  5009.9  522.75 5016.06  523.61    5021   525.1
  5041.9  526.13  5053.5  523.72  5219.3  523.11  5250.6  525.13  5257.8  527.35
  5302.7  529.24  5367.7  530.04  5439.3  528.44  5472.4  528.69  5480.1  528.03
  5490.5  523.58  5608.3  522.73  5608.6  522.23  5612.3  522.73  5615.8  523.17
  5643.5  533.02  5648.7  531.99  5657.5   534.5  5676.7  536.37  5731.1  536.53
#Mann= 5 ,-1 , 0
  3866.7     .05       0  5002.7     .03       0 5016.06     .05       0
  5608.3     .03       0  5612.3     .05       0
#XS Ineff= 2 , 0
       0                  5367.7       0  530.04
Permanent Ineff=
       F       F
Bank Sta=5002.7,5016.06
XS Rating Curve= 0 ,0
Exp/Cntr=0.3,0.1

Type RM Length L Ch R = 1 ,9115    ,202,202,202
BEGIN DESCRIPTION:
Rocky Cedar T7 12.0
END DESCRIPTION:
XS GIS Cut Line= 3
      2712298.09      6957608.84      2711359.11      6958044.43
       2710748.6      6958728.66
#Sta/Elev= 30
  3964.9  539.86  4051.5  537.02  4263.2  532.45  4308.9  530.39  4365.9  529.68
  4419.2  527.97  4639.6  524.05  4789.2  522.14  4805.4  522.52  4939.1  520.56
  4960.5  520.63  4981.4  518.33  4981.7  517.83  4985.4  518.33    4999  520.82
  5268.1  521.84  5290.3   520.4  5297.3  524.97    5304  527.08  5318.2  527.58
  5325.7  523.87  5424.3  523.21  5665.5  523.71  5679.3  524.33  5686.8  525.89
  5693.5  529.73  5707.8  533.49  5729.5  535.91    5793  537.75    5917  537.45
#Mann= 6 ,-1 , 0
  3964.9     .05       0  4805.4     .12       0  4939.1     .07       0
  4981.4     .05       0  4985.4     .07       0  5268.1     .05       0
#XS Ineff= 2 , 0
       0                  5318.2       0  527.58
Permanent Ineff=
       F       F
Bank Sta=4981.4,4985.4
XS Rating Curve= 0 ,0
Exp/Cntr=0.3,0.1

Type RM Length L Ch R = 1 ,8913    ,164,164,164
BEGIN DESCRIPTION:
Rocky Cedar T7 11.0
END DESCRIPTION:
XS GIS Cut Line= 3
      2712080.83      6957151.63      2711327.34       6957846.1
       2710271.8        6958919.
#Sta/Elev= 30
  3962.2  534.32  4219.9  529.55    4326  529.26  4502.9  525.02    4956  520.37
  4970.2  518.36  4984.4   519.2  4984.8  516.65  4985.1  516.15  4988.9  516.65
  5005.5  519.84  5080.2     520  5119.3  520.69    5359  522.76  5387.3  520.99
  5394.4  521.41  5408.5   526.8  5415.6  526.98  5429.7  523.65  5592.7  524.07
  5704.1  523.92  5797.4  524.85  5804.6  523.45    5847  522.98  5868.2  525.17
  5906.4  525.69  5940.2  526.78  6069.6  528.94  6074.3  529.01    6492  536.25
#Mann= 11 ,-1 , 0
  3962.2     .05       0  4984.8     .05       0  4988.9     .05       0
  5080.2      .1       0  5119.3     .05       0  5592.7    .075       0
  5704.1     .05       0  5906.4    .075       0  5940.2     .05       0
  6069.6    .075       0  6074.3     .05       0
Bank Sta=4984.8,4988.9
XS Rating Curve= 0 ,0
Exp/Cntr=0.3,0.1

Type RM Length L Ch R = 1 ,8749    ,741,741,741
BEGIN DESCRIPTION:
Rocky Cedar T7 10.0
END DESCRIPTION:
XS GIS Cut Line= 3
      2711922.83      6957096.17      2711276.37      6957705.84
      2710263.11      6958724.65
#Sta/Elev= 30
  4111.4  530.65  4197.5  528.11  4204.4  529.03  4530.1   523.6  4536.9  524.63
  4735.2  520.28  4909.1  519.65  4975.5  519.44  4982.8  515.56  4989.6  517.31
  4996.8  515.63    5011  516.77    5016  515.19  5016.3  514.69  5020.1  515.19
  5025.1  519.28  5032.2  519.82  5140.9  520.42  5378.7  521.95  5435.2  524.18
  5610.4  524.05  6108.1  529.92  6149.7  530.44  6284.5  532.78  6285.3  532.76
  6333.3   532.9  6361.5  534.94  6419.3     535  6429.2  535.13  6436.9  535.19
#Mann= 12 ,-1 , 0
  4111.4     .05       0  4909.1     .12       0    5016     .07       0
  5020.1     .12       0  5140.9     .05       0  5610.4    .075       0
  6108.1     .12       0  6149.7     .05       0  6284.5    .075       0
  6285.3     .05       0  6419.3    .075       0  6429.2     .05       0
Bank Sta=5016,5020.1
XS Rating Curve= 0 ,0
Exp/Cntr=0.3,0.1

Type RM Length L Ch R = 1 ,8008    ,446,446,446
BEGIN DESCRIPTION:
Rocky Cedar T7 9.0
END DESCRIPTION:
XS GIS Cut Line= 3
      2711839.91      6957003.07      2710982.48      6957167.76
      2710316.46       6958105.5
#Sta/Elev= 30
  4126.9  529.17  4212.3  527.45  4242.9  528.17  4273.4  526.95  4300.2  527.44
  4305.3  526.55  4404.1   526.3  4635.7  519.06  4701.1  517.41    4721  516.05
  4731.7  517.17    4830   516.4  4843.7  517.21  4874.2  516.46  4945.5  517.45
  4963.7  513.22  4964.1  512.72    4968  513.22  4976.1  516.94    5042  515.93
  5077.7  517.72    5122  517.18  5214.2  519.87  5278.3  520.05  5466.7  522.07
  5488.8  522.77    5838  524.25  5973.8  527.25  6099.7   528.1  6150.2  528.64
#Mann= 9 ,-1 , 0
  4126.9     .05       0  4635.7     .12       0  4963.7     .07       0
    4968     .12       0  5278.3     .05       0  5466.7     .12       0
  5488.8     .05       0  5973.8     .12       0  6099.7     .05       0
Bank Sta=4963.7,4968
XS Rating Curve= 0 ,0
Exp/Cntr=0.3,0.1

Type RM Length L Ch R = 1 ,7562    ,718,718,718
BEGIN DESCRIPTION:
Rocky Cedar T7 8.0
END DESCRIPTION:
XS GIS Cut Line= 3
      2711831.17      6956868.52       2710926.1      6956771.05
       2709821.7      6957619.36
#Sta/Elev= 30
  4089.7  530.39  4275.9   528.4  4366.5   526.2  4446.9   522.6  4497.2  522.33
  4576.4  519.34  4698.4  516.81  4785.3  516.15  4857.3  515.17  4879.4  515.72
  4889.5   514.8  4969.9   515.8  4977.8  510.87  4978.2  510.37  4982.2  510.87
    4990  515.55  5036.3  514.92  5115.4  516.59  5306.3  518.35  5364.4   519.8
  5449.6  520.34  5542.3  519.66  6006.7  525.93  6141.1  527.58  6170.1  529.63
  6184.6  529.25  6190.9  530.74  6195.6  530.18  6226.2  529.49  6392.6  530.53
#Mann= 7 ,-1 , 0
  4089.7     .05       0  4785.3     .12       0  4977.8     .07       0
  4982.2     .12       0  5115.4     .05       0  6006.7     .12       0
  6195.6     .05       0
Bank Sta=4977.8,4982.2
XS Rating Curve= 0 ,0
Exp/Cntr=0.3,0.1

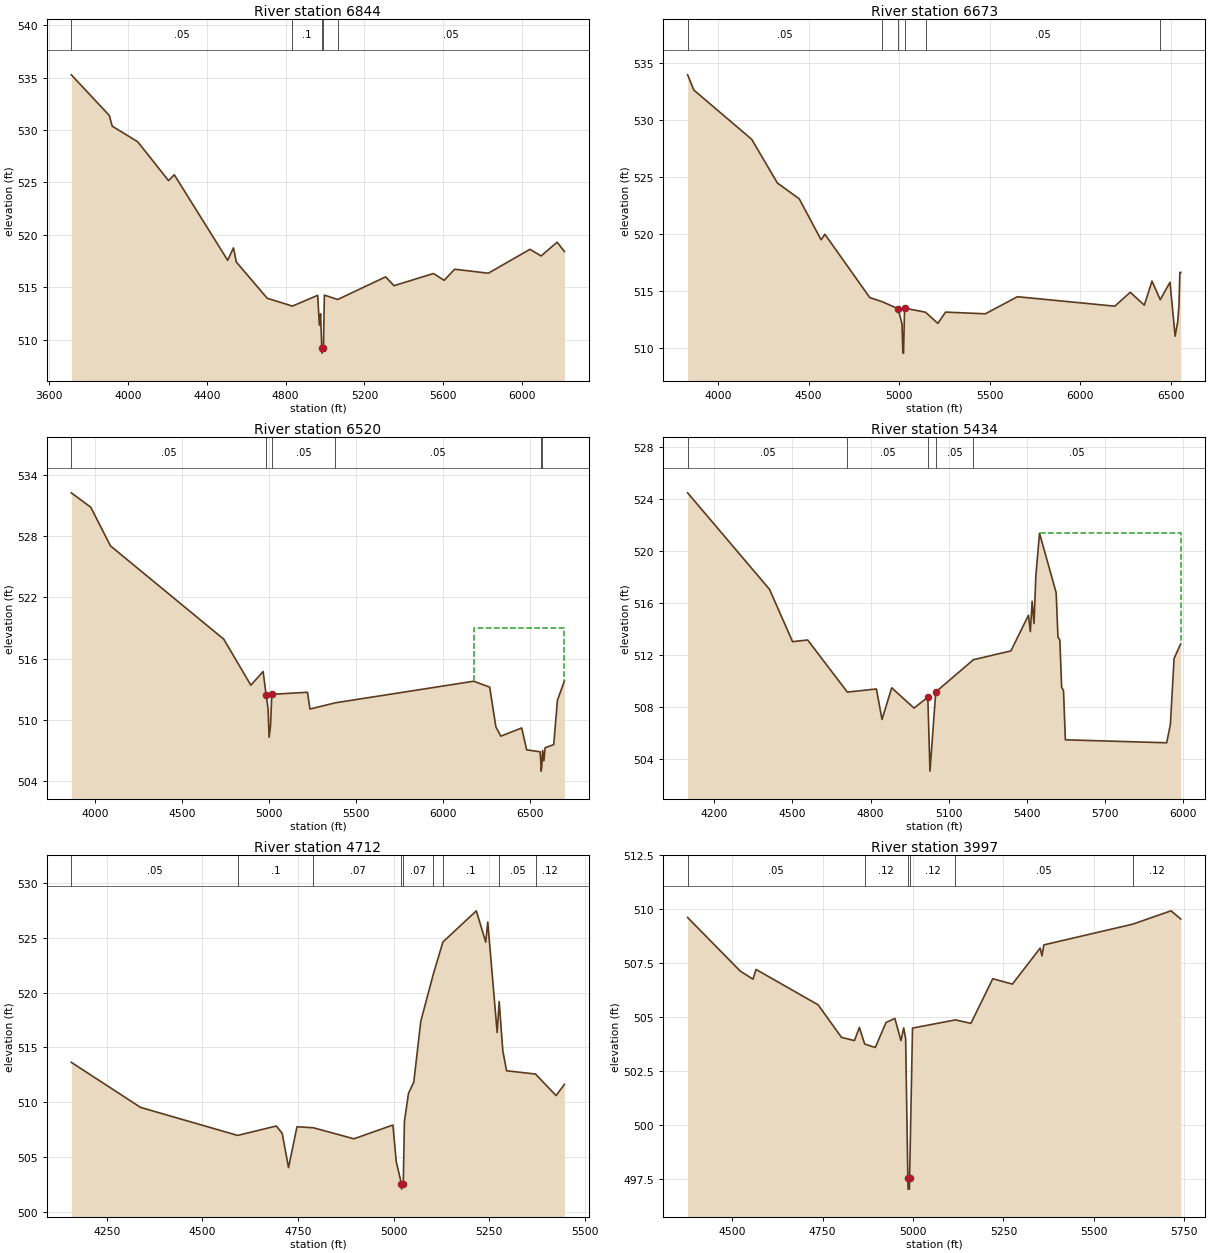
Type RM Length L Ch R = 1 ,6844    ,171,171,171
BEGIN DESCRIPTION:
Rocky Cedar T7 7.0
END DESCRIPTION:
XS GIS Cut Line= 3
      2712025.97      6956910.98      2710995.71      6956140.49
      2709850.97      6955735.99
#Sta/Elev= 30
  3713.5  535.27  3906.2  531.39  3920.8  530.37  4050.1  528.88  4206.4  525.17
  4235.6  525.73  4506.5  517.56  4535.7  518.75  4550.1   517.4  4706.6  513.94
  4834.8  513.19  4962.9  514.22  4971.3  511.37  4977.5  512.45  4983.6   509.2
  4984.1   508.7  4988.1   509.2  4992.1  509.31  4996.7  514.24  5064.1  513.82
  5307.3  515.98  5349.7  515.14  5549.8   516.3  5604.2  515.65  5657.3  516.71
  5828.1  516.33  6039.2  518.61  6095.7  517.98    6177  519.29  6214.1   518.4
#Mann= 5 ,-1 , 0
  3713.5     .05       0  4834.8      .1       0  4983.6     .07       0
  4988.1      .1       0  5064.1     .05       0
Bank Sta=4983.6,4988.1
XS Rating Curve= 0 ,0
Exp/Cntr=0.3,0.1

Type RM Length L Ch R = 1 ,6673    ,153,153,153
BEGIN DESCRIPTION:
Rocky Cedar T7 6.0
END DESCRIPTION:
XS GIS Cut Line= 3
       2712036.4      6956849.09      2711150.01      6956088.33
      2710003.78      6955039.01
#Sta/Elev= 30
  3831.9  533.99  3866.4  532.65  4185.7  528.33  4327.3   524.5    4448  523.11
  4568.7  519.51  4589.6     520  4837.6  514.44  4906.2  514.08  4993.5  513.47
  5015.2  512.13  5020.2  509.57  5023.8  509.57  5029.4  513.52  5145.1  513.16
  5213.2  512.18  5255.7  513.17  5475.3  513.02  5652.2  514.52    6190  513.69
  6275.1  514.91  6352.8  513.78  6395.3  515.89  6440.8  514.26  6494.6  515.79
    6523  511.06  6537.1  512.33  6543.9  513.68  6549.1  516.65    6554  516.65
#Mann= 6 ,-1 , 0
  3831.9     .05       0  4906.2     .07       0  4993.5     .04       0
  5029.4     .07       0  5145.1     .05       0  6440.8     .12       0
Bank Sta=4993.5,5029.4
XS Rating Curve= 0 ,0
Exp/Cntr=0.3,0.1

Type RM Length L Ch R = 1 ,6520    ,1086,1086,1086
BEGIN DESCRIPTION:
Rocky Cedar T7 5.0
END DESCRIPTION:
XS GIS Cut Line= 4
      2712020.76      6956724.08      2711190.22      6955947.71
      2710561.08      6955277.08      2710019.68      6954720.24
#Sta/Elev= 30
  3863.1  532.21  3974.9   530.8  4088.2  527.02  4738.9   517.9  4894.7   513.4
  4965.1  514.74  4981.9 512.489  4993.4   511.1  4999.5  508.31  5007.9   509.5
  5014.8  512.51  5219.9  512.71  5234.1  511.07  5379.9  511.68    6175  513.79
  6266.8  513.21  6302.3  509.32  6330.6  508.42  6450.7  509.22    6479  507.08
  6556.7  506.89  6561.7   505.5  6562.1     505  6566.2   505.5  6570.9  507.03
  6578.1  506.01    6585  507.29  6634.6  507.59  6655.8  511.93  6696.2  513.83
#Mann= 6 ,-1 , 0
  3863.1     .05       0  4981.9     .03       0  5014.8     .05       0
  5379.9     .05       0  6561.7     .04       0  6566.2     .05       0
#XS Ineff= 2 , 0
       0                    6175       0     519
Permanent Ineff=
       F       F
Bank Sta=4981.9,5014.8
XS Rating Curve= 0 ,0
Exp/Cntr=0.3,0.1

Type RM Length L Ch R = 1 ,5434    ,722,722,722
BEGIN DESCRIPTION:
Rocky Cedar T7 4.0
END DESCRIPTION:
XS GIS Cut Line= 4
      2711703.06      6955574.78      2710927.81      6955118.66
      2710536.38      6955045.15      2710123.24      6954617.46
#Sta/Elev= 30
  4098.2  524.51  4412.6  517.08  4500.9  513.06  4558.9  513.19  4711.1  509.18
  4822.7  509.42  4844.2  507.07  4881.3  509.51  4967.1  507.95  5019.9  508.79
  5028.2   503.1  5050.4  509.19  5194.8  511.67  5338.8  512.35  5406.2  515.09
  5413.4  513.83  5420.3  516.17  5427.5  514.45  5434.5  518.12  5448.6   521.4
  5512.4  516.83  5519.4   513.4  5526.6  513.19  5533.5  509.55  5540.7  509.29
  5547.7  505.51  5936.6  505.28  5950.8  506.69  5964.9  511.76  5990.6  512.91
#Mann= 5 ,-1 , 0
  4098.2     .05       0  4711.1     .05       0  5019.9     .04       0
  5050.4     .05       0  5194.8     .05       0
#XS Ineff= 2 , 0
       0                  5448.6       0   521.4
Permanent Ineff=
       F       F
Bank Sta=5019.9,5050.4
XS Rating Curve= 0 ,0
Exp/Cntr=0.3,0.1

Type RM Length L Ch R = 1 ,4712    ,715,715,715
BEGIN DESCRIPTION:
Rocky Cedar T7 3.0
END DESCRIPTION:
XS GIS Cut Line= 3
        2711542.      6954929.35      2710821.82      6954555.57
      2710375.65      6954382.96
#Sta/Elev= 30
    4157  513.64  4338.2  509.52  4591.8  506.96  4693.3  507.82  4708.6  507.14
  4725.1  504.02  4747.2  507.75  4790.1  507.66  4896.1  506.65  4998.2  507.91
  5006.8  504.57  5020.4  502.55  5020.9  502.05  5025.2  502.55  5028.3  508.26
    5039  510.82  5052.7  511.82  5071.1   517.4  5103.9  521.71  5128.9  524.64
  5216.3  527.49  5240.9  524.63  5246.2  526.47  5270.8  516.37  5276.1   519.2
  5285.6  514.69  5295.4  512.87  5371.1  512.57    5425   510.6  5446.8  511.63
#Mann= 9 ,-1 , 0
    4157     .05       0  4591.8      .1       0  4790.1     .07       0
  5020.4     .05       0  5025.2     .07       0  5103.9     .05       0
  5128.9      .1       0  5276.1     .05       0  5371.1     .12       0
Bank Sta=5020.4,5025.2
XS Rating Curve= 0 ,0
Exp/Cntr=0.3,0.1

Type RM Length L Ch R = 1 ,3997    ,456,456,456
BEGIN DESCRIPTION:
Mapping XS af31761e
END DESCRIPTION:
XS GIS Cut Line= 4
      2711735.16      6954595.09      2711443.47      6954194.01
       2711026.8      6954029.95      2710612.77      6954100.26
#Sta/Elev= 30
  4376.7  509.62  4521.9  507.14  4557.4  506.76  4565.9  507.21  4737.5  505.57
  4802.2  504.06    4838  503.91  4851.6  504.52  4866.3  503.75  4895.6  503.59
  4925.4  504.75  4949.8  504.94  4966.6  503.91  4974.2   504.5  4979.6     504
  4985.7  497.52  4986.3  497.02    4990  497.02  4990.5  497.52  4998.6  504.49
  5117.2  504.87  5160.1  504.71  5220.6  506.78  5274.8  506.53  5351.6   508.2
  5356.7  507.84  5361.8  508.35  5607.3  509.31  5713.4  509.93  5740.4  509.55
#Mann= 6 ,-1 , 0
  4376.7     .05       0  4866.3     .12       0  4985.7     .07       0
  4990.5     .12       0  5117.2     .05       0  5607.3     .12       0
Bank Sta=4985.7,4990.5
XS Rating Curve= 0 ,0
Exp/Cntr=0.3,0.1

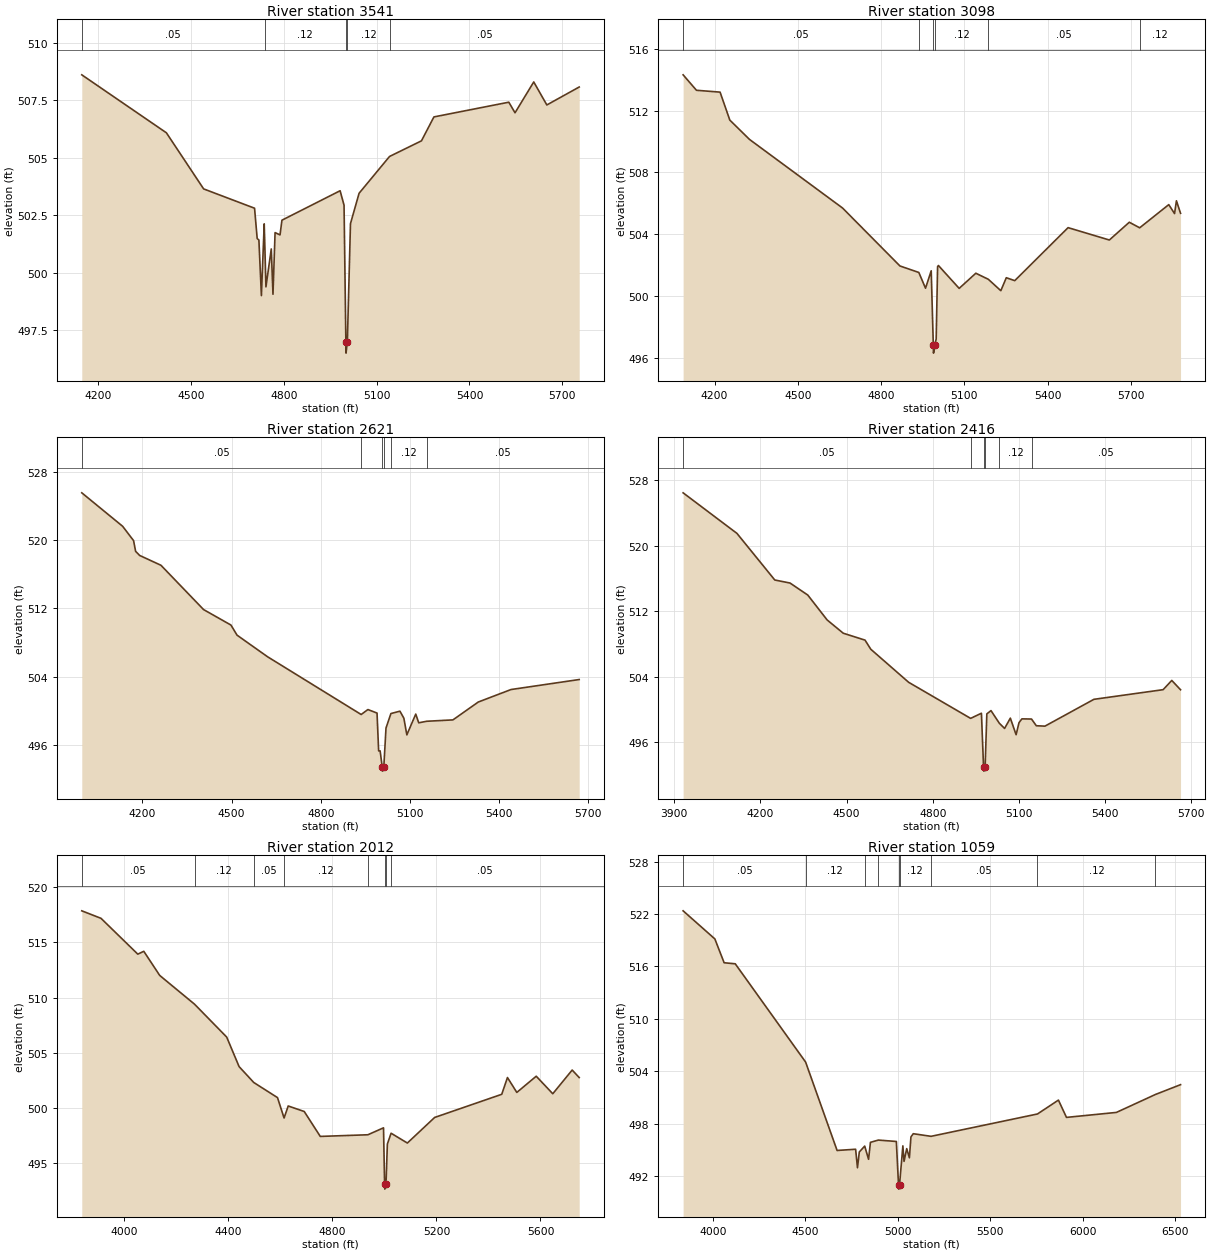
Type RM Length L Ch R = 1 ,3541    ,443,443,443
BEGIN DESCRIPTION:
Mapping XS 379b3b09
END DESCRIPTION:
XS GIS Cut Line= 4
      2712035.49      6954277.35      2711683.92      6953884.12
      2711397.46       6953748.7      2710640.29      6953652.43
#Sta/Elev= 30
  4147.1   508.6  4420.5  506.08  4540.9  503.64  4705.5   502.8    4714  501.48
  4719.5  501.42  4727.6     499  4736.7  502.12  4738.1  501.44  4742.3  499.38
  4759.5  501.03    4765  499.06  4771.8  501.74  4787.8  501.64    4794  502.28
    4982  503.56  4994.7  502.93  5000.6     497  5001.1   496.5  5005.4     497
  5015.5  502.13  5043.3  503.45  5141.7  505.05  5244.9  505.73  5285.2  506.77
  5527.2  507.41  5547.3  506.95  5607.8  508.29  5650.1  507.29  5754.7  508.07
#Mann= 5 ,-1 , 0
  4147.1     .05       0  4738.1     .12       0  5000.6     .07       0
  5005.4     .12       0  5141.7     .05       0
Bank Sta=5000.6,5005.4
XS Rating Curve= 0 ,0
Exp/Cntr=0.3,0.1

Type RM Length L Ch R = 1 ,3098    ,477,477,477
BEGIN DESCRIPTION:
Mapping XS aa79ce1e
END DESCRIPTION:
XS GIS Cut Line= 6
      2712472.67      6953892.26      2712152.38      6953545.94
      2711923.21      6953473.02      2711720.09      6953517.29
      2711319.05      6953499.06      2710954.49      6953202.21
#Sta/Elev= 30
  4086.8  514.32  4134.8  513.32  4219.9   513.2    4255  511.39  4325.9  510.14
  4661.1   505.7  4867.8  501.95  4935.8  501.53  4959.9  500.51  4980.4  501.64
    4988  496.81  4988.7  496.31  4993.3  496.81  4998.3  497.23  5003.4  501.91
  5006.4  501.98  5081.1   500.5  5141.1  501.48    5186  501.09  5231.2  500.35
  5250.9  501.19  5281.3     501  5473.4  504.43  5622.1  503.63  5693.9  504.78
  5731.3  504.42  5836.1  505.92  5856.9  505.34  5863.7  506.17  5878.5  505.36
#Mann= 6 ,-1 , 0
  4086.8     .05       0  4935.8     .12       0    4988     .07       0
  4993.3     .12       0    5186     .05       0  5731.3     .12       0
Bank Sta=4988,4993.3
XS Rating Curve= 0 ,0
Exp/Cntr=0.3,0.1

Type RM Length L Ch R = 1 ,2621    ,205,205,205
BEGIN DESCRIPTION:
Mapping XS 15a93e30
END DESCRIPTION:
XS GIS Cut Line= 3
      2712706.16      6953345.41      2711730.51      6953130.14
      2711056.91      6953091.94
#Sta/Elev= 30
    3996  525.51  4133.4   521.6  4170.3  519.92  4177.1  518.67  4190.7  518.19
  4262.4  517.04  4405.8  511.86  4497.9  510.05  4518.4  508.87  4620.8  506.35
  4936.1  499.59  4958.8  500.17  4989.5  499.76  4994.9  495.34  4999.9  495.34
  5006.9  493.47  5007.7  492.97  5012.3  493.47  5019.7  498.01  5036.2   499.7
  5066.5  499.98  5079.8  499.16  5089.8  497.21  5119.8  499.64  5129.8  498.62
  5156.7   498.8  5244.9  498.96  5330.2  501.05  5440.3  502.51  5669.8  503.68
#Mann= 6 ,-1 , 0
    3996     .05       0  4936.1      .1       0  5006.9     .07       0
  5012.3      .1       0  5036.2     .12       0  5156.7     .05       0
Bank Sta=5006.9,5012.3
XS Rating Curve= 0 ,0
Exp/Cntr=0.3,0.1

Type RM Length L Ch R = 1 ,2416    ,404,404,404
BEGIN DESCRIPTION:
Mapping XS e6c618ee
END DESCRIPTION:
XS GIS Cut Line= 3
      2712780.89      6953094.77       2711725.3      6952924.63
      2711065.56      6952976.71
#Sta/Elev= 30
  3931.2  526.48  4118.5  521.52  4250.2  515.82  4303.2  515.45    4365  513.98
  4432.5  510.93  4488.6  509.31  4564.2  508.47  4584.4  507.35  4716.1  503.31
  4931.7   498.9  4969.3  499.53  4976.7  492.95  4977.5  492.45  4982.1  492.95
  4988.1  499.45  5002.6  499.85  5031.5  498.31  5049.9  497.67  5069.9  498.93
    5090   496.9    5100  498.37  5110.1  498.84  5143.6  498.82  5160.2     498
  5190.3  497.95  5360.8  501.23  5601.6  502.41  5631.7  503.54  5662.2   502.4
#Mann= 6 ,-1 , 0
  3931.2     .05       0  4931.7      .1       0  4976.7     .07       0
  4982.1      .1       0  5031.5     .12       0  5143.6     .05       0
Bank Sta=4976.7,4982.1
XS Rating Curve= 0 ,0
Exp/Cntr=0.3,0.1

Type RM Length L Ch R = 1 ,2012    ,953,953,953
BEGIN DESCRIPTION:
Mapping XS 4e16231b
END DESCRIPTION:
XS GIS Cut Line= 3
      2712757.93      6952325.45      2711628.07      6952594.76
       2710945.1      6952906.58
#Sta/Elev= 30
  3836.6  517.87  3910.5  517.19    4052  513.94    4075   514.2  4136.2  512.01
  4270.2   509.4  4393.7  506.42  4441.4  503.74  4497.8   502.3    4589  500.93
  4614.3  499.08  4630.2  500.17  4691.8  499.67  4753.5  497.41  4936.5  497.56
  4996.6  498.19  5000.7  493.13  5001.5  492.63  5006.2  493.13  5011.4  496.72
  5025.7   497.7  5088.3  496.81  5193.2  499.13  5451.1  501.23  5473.1  502.75
  5509.1   501.4  5583.7  502.87  5647.3  501.28  5721.9  503.43  5748.9  502.75
#Mann= 8 ,-1 , 0
  3836.6     .05       0  4270.2     .12       0  4497.8     .05       0
  4614.3     .12       0  4936.5      .1       0  5000.7     .07       0
  5006.2      .1       0  5025.7     .05       0
Bank Sta=5000.7,5006.2
XS Rating Curve= 0 ,0
Exp/Cntr=0.3,0.1

Type RM Length L Ch R = 1 ,1059    ,0,0,0
BEGIN DESCRIPTION:
Rocky Cedar T7 1.0
END DESCRIPTION:
XS GIS Cut Line= 3
      2712777.42      6951645.11      2711617.86      6951704.94
      2710686.94      6952917.26
#Sta/Elev= 30
  3838.9  522.37  4010.5  519.15  4060.6  516.42  4120.7   516.3  4501.2  505.04
  4671.4  494.91  4771.6  495.05  4781.6  492.93  4791.6  494.74  4820.7  495.41
  4841.6   493.9  4851.7  495.84  4894.6   496.1  4991.8  495.94  5003.5  490.98
  5004.3  490.48  5009.1  490.98  5027.1  495.44  5033.4  493.66  5047.9  495.12
  5062.4  494.07  5070.7  496.46  5083.3  496.83  5179.5  496.53  5754.8  499.09
  5868.2  500.68  5911.7   498.7  6181.8  499.27  6392.1  501.32  6528.5  502.45
#Mann= 9 ,-1 , 0
  3838.9     .05       0  4501.2     .12       0  4820.7      .1       0
  4894.6     .12       0  5003.5     .07       0  5009.1     .12       0
  5179.5     .05       0  5754.8     .12       0  6392.1     .05       0
Bank Sta=5003.5,5009.1
XS Rating Curve= 0 ,0
Exp/Cntr=0.3,0.1

Chan Stop Cuts=-1
Use User Specified Reach Order=0
Composite Channel Slope=5