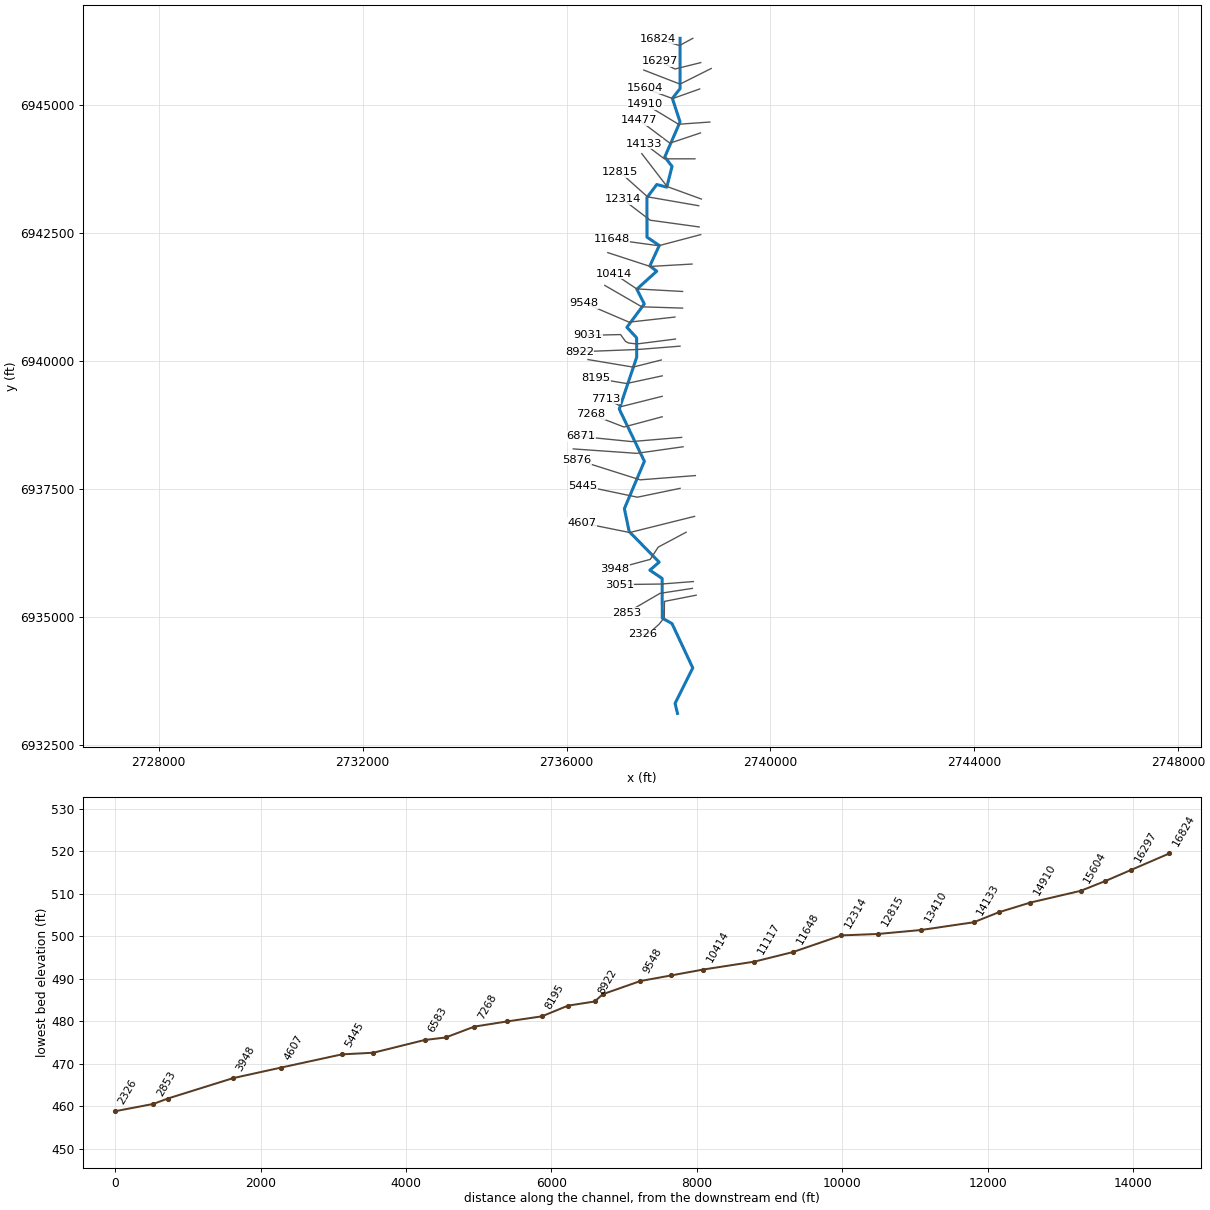
--- Sycamore Branch.prj (project) ---

Proj Title=Sycamore Branch Base Level Engineering
Current Plan=p01
Default Exp/Contr=0.3,0.1
English Units
Geom File=g01
Flow File=f01
Plan File=p01
BEGIN DESCRIPTION:
Sycamore Branch
END DESCRIPTION:

--- Sycamore Branch.p01 (plan) ---

Plan Title=Multiple Run
Short Identifier=Multiple
Geom File=g01
Flow File=f01
Subcritical Flow
K Sum by GR= 0
Std Step Tol= 0.01
Critical Tol= 0.01
Num of Std Step Trials= 20
Max Error Tol= 0.3
Flow Tol Ratio= 0.001
Split Flow NTrial= 30
Split Flow Tol= 0.02
Split Flow Ratio= 0.02
Log Output Level= 0
Friction Slope Method= 1
Unsteady Friction Slope Method= 2
Unsteady Bridges Friction Slope Method= 1
Parabolic Critical Depth
Global Vel Dist=  1 , 1 , 1
Global Log Level= 0
CheckData=True
Encroach Param= -1, 0, 0, 0
BEGIN DESCRIPTION:
Multiple Run
END DESCRIPTION:

--- Sycamore Branch.f01 (steady flow) ---

Flow Title=Multiple
Number of Profiles=7
Profile Names=10-year,25-year,50-year,1pct_min,100-year,1pct_plu,500-year
River Rch & RM= Sycamore Branch,Reach-1,16824
     267     341     399     232     464     925     627
River Rch & RM= Sycamore Branch,Reach-1,14133
     524     696     833     496     990    1975    1399
River Rch & RM= Sycamore Branch,Reach-1,7268
     680     914    1104     662    1320    2635    1894
Boundary for River Rch & Prof#=Sycamore Branch,Reach-1,1
Up Type=0
Dn Type=3
Dn Slope=0.005
Boundary for River Rch & Prof#=Sycamore Branch,Reach-1,2
Up Type=0
Dn Type=3
Dn Slope=0.005
Boundary for River Rch & Prof#=Sycamore Branch,Reach-1,3
Up Type=0
Dn Type=3
Dn Slope=0.005
Boundary for River Rch & Prof#=Sycamore Branch,Reach-1,4
Up Type=0
Dn Type=3
Dn Slope=0.005
Boundary for River Rch & Prof#=Sycamore Branch,Reach-1,5
Up Type=0
Dn Type=3
Dn Slope=0.005
Boundary for River Rch & Prof#=Sycamore Branch,Reach-1,6
Up Type=0
Dn Type=3
Dn Slope=0.005
Boundary for River Rch & Prof#=Sycamore Branch,Reach-1,7
Up Type=0
Dn Type=3
Dn Slope=0.005

--- Sycamore Branch.g01 (geometry) ---

Geom Title=Existing Conditions

River Reach=Sycamore Branch,Reach-1
Reach XY= 30
      2738226.00      6946311.00      2738225.62      6945326.16
      2738075.37      6945135.92      2738225.99      6944676.47
      2737925.93      6943990.99      2738068.50      6943807.87
      2737965.66      6943400.76      2737769.00      6943452.17
      2737576.19      6943195.91      2737577.62      6942422.81
      2737818.94      6942261.00      2737633.20      6941860.70
      2737768.49      6941757.85      2737377.58      6941404.95
      2737524.49      6941117.38      2737183.31      6940660.90
      2737373.94      6940455.15      2737375.48      6940076.22
      2737033.53      6939061.01      2737526.30      6938040.66
      2737133.98      6937114.33      2737228.06      6936666.85
      2737816.77      6936067.54      2737633.20      6935911.30
      2737874.52      6935749.51      2737877.50      6934972.53
      2738067.87      6934867.08      2738475.30      6934000.30
      2738128.14      6933305.04      2738176.00      6933111.00

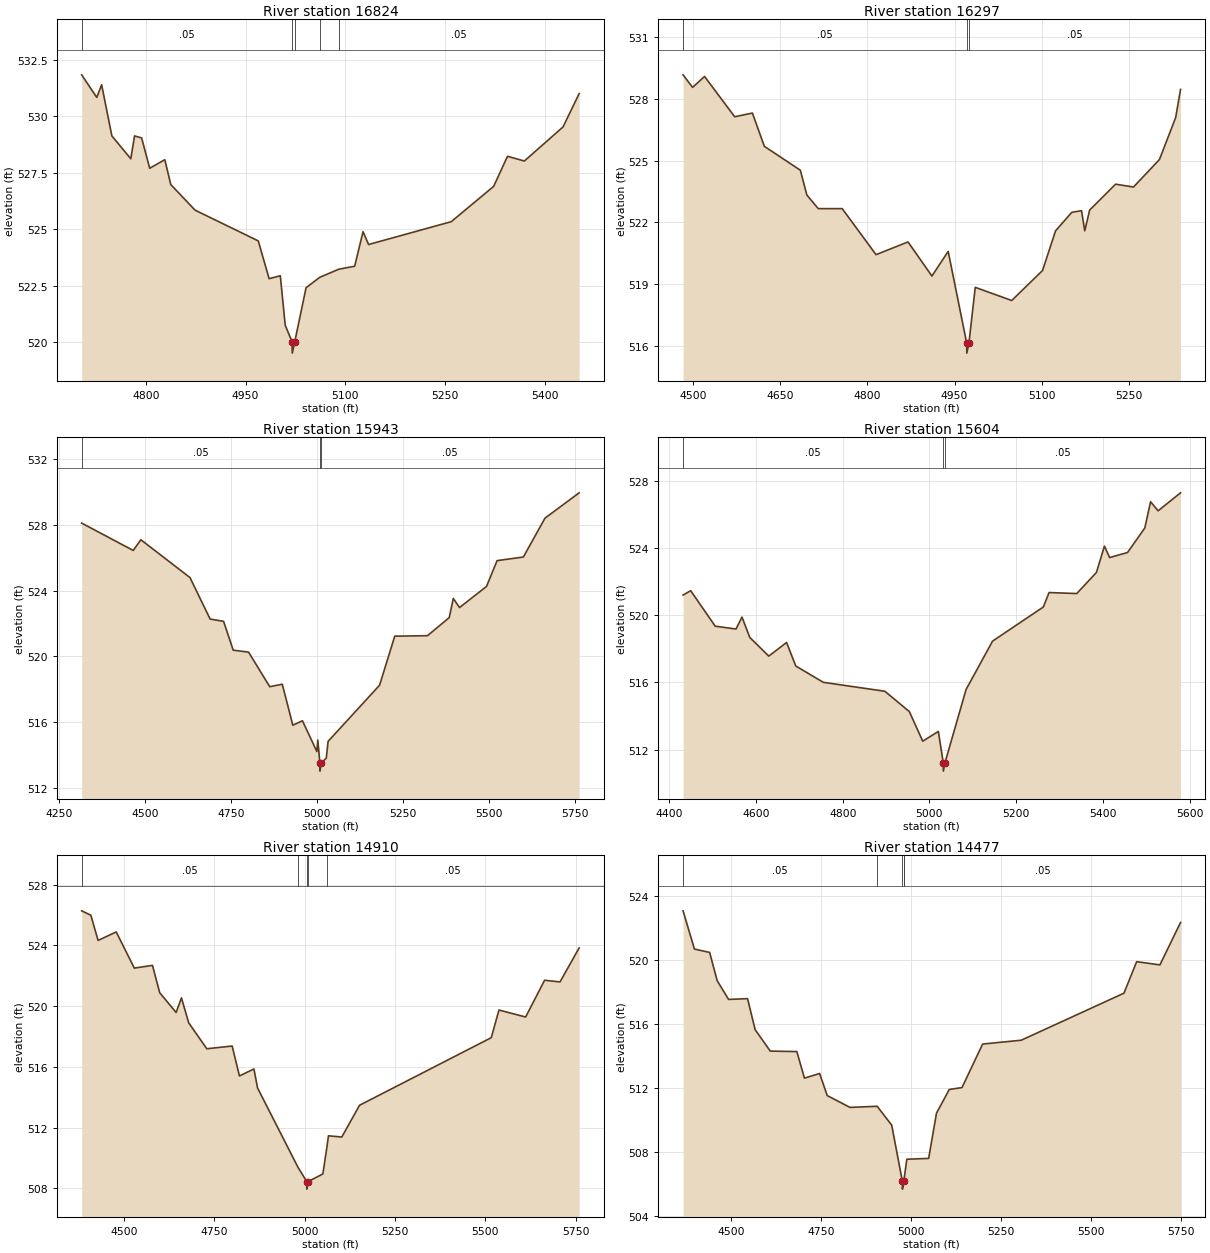
Type RM Length L Ch R = 1,16824,527,527,527
BEGIN DESCRIPTION:
Sycamore Branch 30.0
END DESCRIPTION:
XS GIS Cut Line= 3
      2738476.00      6946311.00      2738215.16      6946170.66
      2737782.93      6946299.76
#Sta/Elev= 30
  4703.8  531.83  4726.5  530.83  4733.8  531.39  4749.2  529.13  4777.6  528.12
  4783.3  529.13  4793.9  529.04  4806.0  527.70  4828.7  528.08  4837.7  526.98
  4874.1  525.85  4969.1  524.49  4985.4  522.82  5002.2  522.95  5009.6  520.76
  5019.9  520.03  5020.2  519.53  5023.9  520.03  5040.9  522.42  5061.4  522.88
  5090.2  523.24  5113.9  523.37  5126.5  524.90  5134.8  524.33  5259.0  525.34
  5322.7  526.90  5343.5  528.23  5368.8  528.02  5427.0  529.53  5451.1  531.00
#Mann=5,-1,0
  4703.8    0.05       0  5019.9    0.04       0  5023.9    0.05       0
  5061.4    0.12       0  5090.2    0.05       0
Bank Sta=5019.9,5023.9
Exp/Cntr=0.3,0.1

Type RM Length L Ch R = 1,16297,354,354,354
BEGIN DESCRIPTION:
Sycamore Branch 29.0
END DESCRIPTION:
XS GIS Cut Line= 3
      2738631.94      6945836.22      2738126.00      6945711.00
      2737826.02      6945860.99
#Sta/Elev= 30
  4482.5  529.18  4498.9  528.57  4519.5  529.10  4571.4  527.14  4601.9  527.32
  4622.5  525.70  4684.4  524.54  4695.7  523.33  4715.3  522.67  4756.5  522.67
  4814.8  520.43  4869.8  521.05  4911.0  519.39  4939.0  520.59  4970.8  516.14
  4971.1  515.64  4974.8  516.14  4985.6  518.84  5048.4  518.20  5101.5  519.66
  5123.9  521.59  5151.8  522.49  5168.6  522.57  5174.2  521.59  5182.6  522.60
  5227.3  523.86  5258.1  523.72  5302.8  525.06  5330.7  527.10  5339.1  528.47
#Mann=3,-1,0
  4482.5    0.05       0  4970.8    0.04       0  4974.8    0.05       0
Bank Sta=4970.8,4974.8
Exp/Cntr=0.3,0.1

Type RM Length L Ch R = 1,15943,339,339,339
BEGIN DESCRIPTION:
Sycamore Branch 28.0
END DESCRIPTION:
XS GIS Cut Line= 3
      2738837.63      6945721.63      2738226.06      6945415.97
      2737514.75      6945690.37
#Sta/Elev= 30
  4316.3  528.10  4466.1  526.44  4488.4  527.09  4631.2  524.79  4689.7  522.27
  4728.9  522.13  4756.8  520.38  4801.5  520.26  4863.0  518.16  4899.5  518.31
  4930.1  515.82  4958.1  516.09  5000.0  514.22  5002.7  514.92  5008.8  513.53
  5009.0  513.03  5012.8  513.53  5027.4  513.82  5032.7  514.84  5182.3  518.25
  5226.4  521.23  5321.6  521.26  5384.8  522.36  5396.6  523.52  5414.8  522.97
  5493.1  524.25  5523.9  525.82  5600.3  526.04  5663.1  528.40  5762.4  529.94
#Mann=3,-1,0
  4316.3    0.05       0  5008.8    0.04       0  5012.8    0.05       0
Bank Sta=5008.8,5012.8
Exp/Cntr=0.3,0.1

Type RM Length L Ch R = 1,15604,694,694,694
BEGIN DESCRIPTION:
Sycamore Branch 27.0
END DESCRIPTION:
XS GIS Cut Line= 3
      2738611.09      6945320.60      2738081.05      6945133.26
      2737531.06      6945333.26
#Sta/Elev= 30
  4431.8  521.19  4449.4  521.45  4505.9  519.34  4553.9  519.17  4567.7  519.88
  4585.7  518.67  4629.5  517.56  4670.5  518.37  4691.8  516.97  4755.4  516.00
  4897.2  515.47  4953.7  514.26  4984.6  512.50  5020.6  513.08  5031.9  511.22
  5032.2  510.72  5035.9  511.22  5084.5  515.57  5145.6  518.45  5262.7  520.48
  5276.0  521.34  5339.8  521.28  5385.1  522.53  5403.7  524.10  5415.6  523.42
  5456.9  523.72  5496.8  525.18  5510.1  526.74  5527.4  526.20  5579.2  527.27
#Mann=3,-1,0
  4431.8    0.05       0  5031.9    0.04       0  5035.9    0.05       0
Bank Sta=5031.9,5035.9
Exp/Cntr=0.3,0.1

Type RM Length L Ch R = 1,14910,433,433,433
BEGIN DESCRIPTION:
Sycamore Branch 26.0
END DESCRIPTION:
XS GIS Cut Line= 3
      2738811.38      6944674.41      2738196.21      6944631.01
      2737545.77      6945023.34
#Sta/Elev= 30
  4383.3  526.27  4408.7  525.98  4428.8  524.32  4478.9  524.88  4529.0  522.50
  4579.2  522.68  4599.2  520.88  4644.6  519.58  4659.4  520.54  4679.4  518.90
  4729.5  517.19  4799.7  517.37  4819.8  515.40  4859.9  515.86  4869.9  514.61
  4981.7  509.39  5005.9  508.45  5006.1  507.95  5009.9  508.45  5050.6  508.95
  5061.2  510.62  5066.1  511.46  5103.0  511.38  5152.1  513.47  5516.5  517.92
  5537.8  519.74  5611.6  519.28  5664.0  521.70  5706.7  521.59  5759.6  523.83
#Mann=5,-1,0
  4383.3    0.05       0  4981.7    0.12       0  5005.9    0.07       0
  5009.9    0.12       0  5061.2    0.05       0
Bank Sta=5005.9,5009.9
Exp/Cntr=0.3,0.1

Type RM Length L Ch R = 1,14477,344,344,344
BEGIN DESCRIPTION:
Sycamore Branch 25.0
END DESCRIPTION:
XS GIS Cut Line= 3
      2738626.01      6944461.00      2738026.00      6944261.00
      2737425.97      6944711.02
#Sta/Elev= 30
  4367.0  523.07  4398.6  520.68  4440.8  520.47  4461.9  518.70  4493.5  517.53
  4546.2  517.58  4567.3  515.64  4609.4  514.30  4683.2  514.27  4704.3  512.61
  4746.5  512.90  4767.6  511.52  4830.8  510.78  4906.5  510.85  4946.8  509.67
  4976.4  506.17  4976.6  505.67  4980.4  506.17  4982.3  506.48  4988.9  507.54
  5049.5  507.59  5071.3  510.42  5106.8  511.90  5142.2  512.02  5199.5  514.74
  5306.8  514.98  5592.2  517.92  5627.6  519.89  5692.2  519.69  5749.5  522.34
#Mann=5,-1,0
  4367.0    0.05       0  4906.5    0.12       0  4976.4    0.04       0
  4980.4    0.12       0  4982.3    0.05       0
Bank Sta=4976.4,4980.4
Exp/Cntr=0.3,0.1

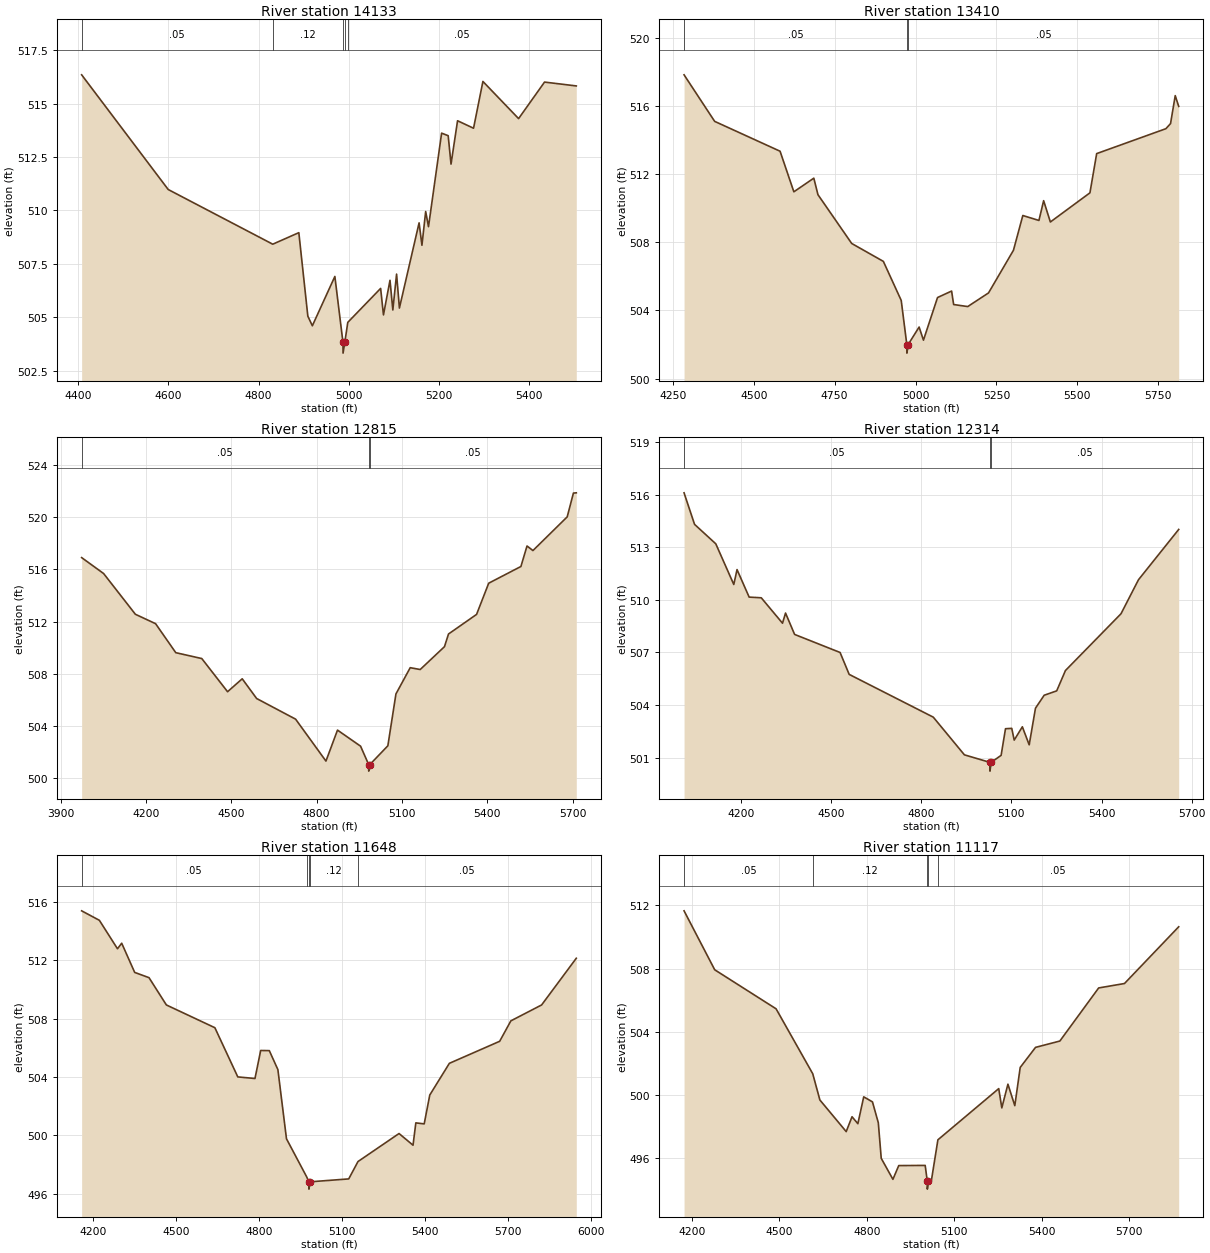
Type RM Length L Ch R = 1,14133,723,723,723
BEGIN DESCRIPTION:
Sycamore Branch 24.0
END DESCRIPTION:
XS GIS Cut Line= 3
      2738518.17      6943954.82      2737918.17      6943954.82
      2737519.61      6944253.73
#Sta/Elev= 30
  4407.3  516.35  4599.5  510.98  4831.6  508.42  4889.5  508.96  4909.5  505.05
  4919.5  504.60  4969.5  506.91  4987.5  503.82  4987.7  503.32  4991.5  503.82
  4998.2  504.76  5071.1  506.35  5077.4  505.11  5091.9  506.73  5098.2  505.34
  5106.5  507.02  5112.8  505.43  5156.5  509.42  5162.8  508.37  5171.1  509.95
  5177.4  509.24  5206.5  513.62  5221.1  513.50  5227.4  512.17  5241.9  514.20
  5277.4  513.85  5298.2  516.04  5377.4  514.30  5435.0  516.01  5505.5  515.83
#Mann=5,-1,0
  4407.3    0.05       0  4831.6    0.12       0  4987.5    0.04       0
  4991.5    0.12       0  4998.2    0.05       0
Bank Sta=4987.5,4991.5
Exp/Cntr=0.3,0.1

Type RM Length L Ch R = 1,13410,595,595,595
BEGIN DESCRIPTION:
Sycamore Branch 23.0
END DESCRIPTION:
XS GIS Cut Line= 3
      2738644.93      6943168.11      2737972.56      6943412.19
      2737475.69      6944056.07
#Sta/Elev= 30
  4284.7  517.82  4379.3  515.09  4581.4  513.34  4624.0  510.96  4685.7  511.76
  4698.5  510.79  4802.8  507.93  4900.6  506.88  4955.8  504.59  4973.1  502.00
  4973.3  501.50  4977.1  502.00  5011.1  503.03  5024.5  502.26  5068.0  504.76
  5111.5  505.14  5117.8  504.35  5161.3  504.23  5225.6  505.03  5302.6  507.53
  5331.6  509.57  5381.4  509.28  5395.9  510.44  5416.7  509.19  5539.0  510.90
  5559.8  513.20  5773.6  514.66  5788.1  514.96  5802.6  516.60  5813.3  515.97
#Mann=3,-1,0
  4284.7    0.05       0  4973.1    0.04       0  4977.1    0.05       0
Bank Sta=4973.1,4977.1
Exp/Cntr=0.3,0.1

Type RM Length L Ch R = 1,12815,501,501,501
BEGIN DESCRIPTION:
Mapping XS e01d1851
END DESCRIPTION:
XS GIS Cut Line= 3
      2738592.09      6943037.81      2737588.57      6943211.43
      2737050.69      6943690.32
#Sta/Elev= 30
  3974.1  516.91  4051.3  515.69  4163.0  512.57  4234.0  511.85  4305.0  509.63
  4396.4  509.18  4487.0  506.64  4538.5  507.63  4589.2  506.12  4726.1  504.54
  4832.8  501.33  4873.4  503.70  4954.5  502.47  4983.0  501.06  4983.2  500.56
  4987.0  501.06  5050.4  502.50  5078.8  506.47  5129.0  508.48  5164.1  508.34
  5249.4  510.09  5263.6  511.06  5362.2  512.56  5404.9  514.95  5518.1  516.23
  5539.5  517.80  5560.4  517.45  5680.8  520.03  5702.6  521.85  5712.7  521.87
#Mann=3,-1,0
  3974.1    0.05       0  4983.0    0.04       0  4987.0    0.05       0
Bank Sta=4983,4987
Exp/Cntr=0.3,0.1

Type RM Length L Ch R = 1,12314,666,666,666
BEGIN DESCRIPTION:
Sycamore Branch 20.0
END DESCRIPTION:
XS GIS Cut Line= 3
      2738600.72      6942622.89      2737638.92      6942754.83
      2737100.90      6943164.42
#Sta/Elev= 30
  4010.0  516.11  4045.0  514.31  4115.7  513.20  4175.6  510.88  4186.4  511.73
  4226.7  510.16  4267.1  510.12  4337.8  508.67  4347.9  509.25  4378.1  508.03
  4529.5  507.00  4559.8  505.75  4839.8  503.31  4943.4  501.16  5028.4  500.73
  5028.6  500.23  5032.4  500.73  5065.7  501.13  5080.3  502.65  5101.1  502.67
  5109.3  502.00  5136.4  502.76  5159.2  501.73  5180.1  503.82  5209.1  504.56
  5250.8  504.81  5279.9  505.97  5464.9  509.21  5523.1  511.15  5657.0  514.02
#Mann=3,-1,0
  4010.0    0.05       0  5028.4    0.04       0  5032.4    0.05       0
Bank Sta=5028.4,5032.4
Exp/Cntr=0.3,0.1

Type RM Length L Ch R = 1,11648,531,531,531
BEGIN DESCRIPTION:
Mapping XS 7763dd1c
END DESCRIPTION:
XS GIS Cut Line= 3
      2738631.15      6942472.73      2737806.45      6942255.70
      2736881.96      6942381.57
#Sta/Elev= 30
  4159.8  515.38  4223.8  514.73  4289.2  512.78  4304.4  513.16  4351.3  511.16
  4403.0  510.80  4465.7  508.93  4640.8  507.37  4723.5  504.00  4785.6  503.89
  4806.2  505.81  4837.3  505.80  4868.3  504.50  4899.3  499.76  4972.5  497.14
  4980.0  496.81  4980.3  496.31  4984.0  496.81  5124.0  497.01  5157.5  498.20
  5305.7  500.12  5356.2  499.32  5366.3  500.85  5396.5  500.78  5416.7  502.76
  5487.4  504.93  5669.0  506.44  5709.4  507.84  5820.4  508.93  5945.6  512.13
#Mann=5,-1,0
  4159.8    0.05       0  4972.5    0.12       0  4980.0    0.07       0
  4984.0    0.12       0  5157.5    0.05       0
Bank Sta=4980,4984
Exp/Cntr=0.3,0.1

Type RM Length L Ch R = 1,11117,703,703,703
BEGIN DESCRIPTION:
Mapping XS e388e12d
END DESCRIPTION:
XS GIS Cut Line= 3
      2738460.95      6941897.19      2737640.65      6941850.32
      2736809.20      6942120.54
#Sta/Elev= 30
  4173.8  511.66  4278.9  507.93  4489.3  505.46  4615.0  501.35  4639.5  499.69
  4729.7  497.69  4749.7  498.63  4769.7  498.19  4789.8  499.89  4819.8  499.57
  4839.8  498.25  4849.8  496.00  4889.9  494.67  4909.9  495.54  5000.5  495.55
  5007.7  494.55  5007.9  494.05  5011.7  494.55  5021.4  494.55  5044.1  497.17
  5252.7  500.41  5263.2  499.19  5284.2  500.69  5307.8  499.33  5326.3  501.75
  5378.9  503.02  5462.2  503.42  5595.3  506.78  5683.8  507.06  5869.7  510.65
#Mann=5,-1,0
  4173.8    0.05       0  4615.0    0.12       0  5007.7    0.07       0
  5011.7    0.12       0  5044.1    0.05       0
Bank Sta=5007.7,5011.7
Exp/Cntr=0.3,0.1

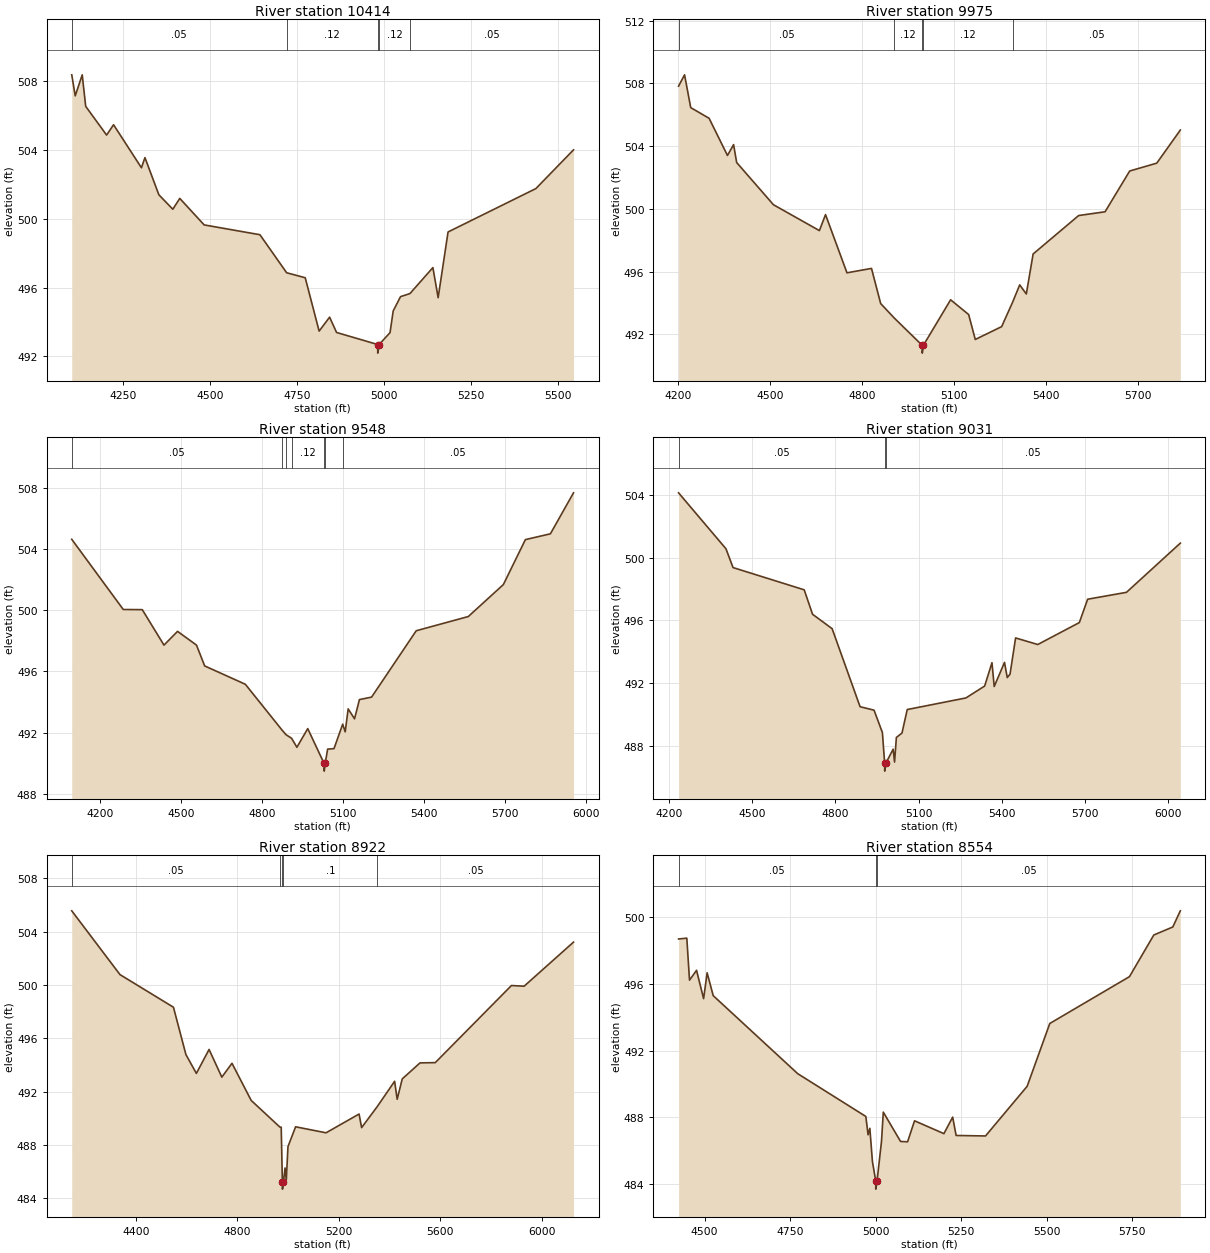
Type RM Length L Ch R = 1,10414,439,439,439
BEGIN DESCRIPTION:
Sycamore Branch 18.0
END DESCRIPTION:
XS GIS Cut Line= 3
      2738276.03      6941361.00      2737376.00      6941411.00
      2736925.96      6941711.03
#Sta/Elev= 30
  4102.4  508.36  4112.4  507.14  4132.5  508.36  4142.5  506.53  4202.6  504.86
  4222.6  505.46  4302.7  502.96  4312.8  503.55  4352.8  501.39  4392.9  500.55
  4412.9  501.18  4483.0  499.64  4643.3  499.07  4720.1  496.86  4773.5  496.57
  4813.5  493.47  4843.6  494.28  4863.6  493.39  4981.8  492.69  4982.0  492.19
  4985.8  492.69  5017.3  493.38  5026.4  494.64  5047.4  495.47  5074.5  495.65
  5140.5  497.16  5155.6  495.41  5184.1  499.23  5436.5  501.75  5544.7  504.00
#Mann=5,-1,0
  4102.4    0.05       0  4720.1    0.12       0  4981.8    0.07       0
  4985.8    0.12       0  5074.5    0.05       0
Bank Sta=4981.8,4985.8
Exp/Cntr=0.3,0.1

Type RM Length L Ch R = 1,9975,427,427,427
BEGIN DESCRIPTION:
Sycamore Branch 17.0
END DESCRIPTION:
XS GIS Cut Line= 3
      2738275.64      6941035.87      2737476.00      6941061.00
      2736749.40      6941479.42
#Sta/Elev= 30
  4200.6  507.83  4220.2  508.55  4240.3  506.46  4300.3  505.78  4360.3  503.41
  4380.3  504.10  4390.3  502.96  4510.4  500.27  4660.5  498.62  4680.5  499.64
  4750.5  495.93  4830.6  496.21  4860.6  493.97  4904.8  493.05  4996.1  491.31
  4996.4  490.81  5000.1  491.31  5089.0  494.21  5147.9  493.27  5169.5  491.68
  5255.7  492.50  5291.5  494.06  5314.6  495.16  5336.2  494.58  5358.4  497.13
  5507.1  499.58  5593.3  499.82  5673.8  502.42  5762.2  502.92  5839.1  505.03
#Mann=5,-1,0
  4200.6    0.05       0  4904.8    0.12       0  4996.1    0.07       0
  5000.1    0.12       0  5291.5    0.05       0
Bank Sta=4996.1,5000.1
Exp/Cntr=0.3,0.1

Type RM Length L Ch R = 1,9548,517,517,517
BEGIN DESCRIPTION:
Sycamore Branch 16.0
END DESCRIPTION:
XS GIS Cut Line= 3
      2738125.97      6940861.00      2737226.00      6940761.00
      2736347.17      6941136.27
#Sta/Elev= 30
  4094.4  504.64  4285.5  500.05  4356.0  500.04  4436.5  497.72  4486.8  498.62
  4557.2  497.72  4587.4  496.36  4738.3  495.16  4874.6  492.16  4889.3  491.86
  4909.8  491.63  4929.5  491.04  4969.7  492.26  5030.5  489.98  5030.8  489.48
  5034.5  489.98  5043.5  490.92  5067.1  490.95  5099.3  492.55  5108.6  492.05
  5119.7  493.55  5143.3  492.90  5161.5  494.16  5206.5  494.32  5372.1  498.66
  5565.3  499.59  5695.3  501.68  5777.0  504.62  5869.8  505.00  5955.5  507.68
#Mann=7,-1,0
  4094.4    0.05       0  4874.6    0.12       0  4889.3     0.1       0
  4909.8    0.12       0  5030.5    0.07       0  5034.5    0.12       0
  5099.3    0.05       0
Bank Sta=5030.5,5034.5
Exp/Cntr=0.3,0.1

Type RM Length L Ch R = 1,9031,109,109,109
BEGIN DESCRIPTION:
Sycamore Branch 15.0
END DESCRIPTION:
XS GIS Cut Line= 6
      2738135.67      6940430.79      2737376.05      6940334.44
      2737216.44      6940353.29      2737156.38      6940384.34
      2737059.47      6940518.21      2736411.71      6940503.71
#Sta/Elev= 30
  4234.3  504.13  4405.3  500.56  4430.9  499.36  4687.6  497.94  4717.8  496.38
  4788.4  495.46  4889.2  490.48  4939.6  490.26  4969.8  488.83  4977.9  486.87
  4978.1  486.37  4981.9  486.87  5008.6  487.77  5013.6  486.95  5020.2  488.52
  5040.4  488.80  5059.4  490.30  5271.1  491.04  5338.7  491.80  5365.1  493.29
  5373.2  491.77  5410.3  493.31  5420.3  492.34  5430.3  492.56  5450.3  494.87
  5530.3  494.45  5680.3  495.85  5710.3  497.34  5850.4  497.78  6044.7  500.92
#Mann=3,-1,0
  4234.3    0.05       0  4977.9    0.05       0  4981.9    0.05       0
Bank Sta=4977.9,4981.9
Exp/Cntr=0.3,0.1

Type RM Length L Ch R = 1,8922,368,368,368
BEGIN DESCRIPTION:
Sycamore Branch 14.0
END DESCRIPTION:
XS GIS Cut Line= 3
      2738225.54      6940291.81      2737402.64      6940226.70
      2736251.56      6940182.43
#Sta/Elev= 30
  4147.9  505.57  4338.0  500.78  4548.7  498.33  4597.9  494.77  4639.0  493.36
  4689.1  495.16  4739.3  493.08  4779.4  494.12  4855.1  491.33  4968.1  489.33
  4973.4  489.32  4978.0  485.17  4978.3  484.67  4982.0  485.17  4988.4  486.26
  4993.4  485.36  5000.0  487.86  5030.1  489.35  5150.1  488.90  5280.2  490.31
  5290.2  489.29  5351.9  490.87  5420.3  492.77  5430.4  491.42  5450.4  492.95
  5520.4  494.15  5580.5  494.17  5880.7  499.96  5930.7  499.91  6125.3  503.22
#Mann=5,-1,0
  4147.9    0.05       0  4968.1     0.1       0  4978.0    0.07       0
  4982.0     0.1       0  5351.9    0.05       0
Bank Sta=4978,4982
Exp/Cntr=0.3,0.1

Type RM Length L Ch R = 1,8554,359,359,359
BEGIN DESCRIPTION:
Mapping XS 16e022ea
END DESCRIPTION:
XS GIS Cut Line= 3
      2737857.01      6940021.21      2737303.63      6939882.32
      2736419.56      6940029.67
#Sta/Elev= 30
  4424.1  498.70  4448.2  498.75  4456.1  496.23  4476.7  496.82  4497.3  495.12
  4507.6  496.67  4525.4  495.30  4772.3  490.62  4971.6  488.05  4978.1  486.95
  4983.3  487.34  4990.8  485.35  5000.4  484.19  5000.6  483.69  5004.4  484.19
  5017.3  486.55  5022.6  488.31  5073.1  486.55  5093.6  486.53  5113.9  487.79
  5199.8  487.02  5225.4  488.01  5235.5  486.91  5321.4  486.88  5443.1  489.86
  5509.3  493.63  5742.2  496.44  5813.4  498.94  5868.9  499.42  5890.9  500.39
#Mann=3,-1,0
  4424.1    0.05       0  5000.4    0.04       0  5004.4    0.05       0
Bank Sta=5000.4,5004.4
Exp/Cntr=0.3,0.1

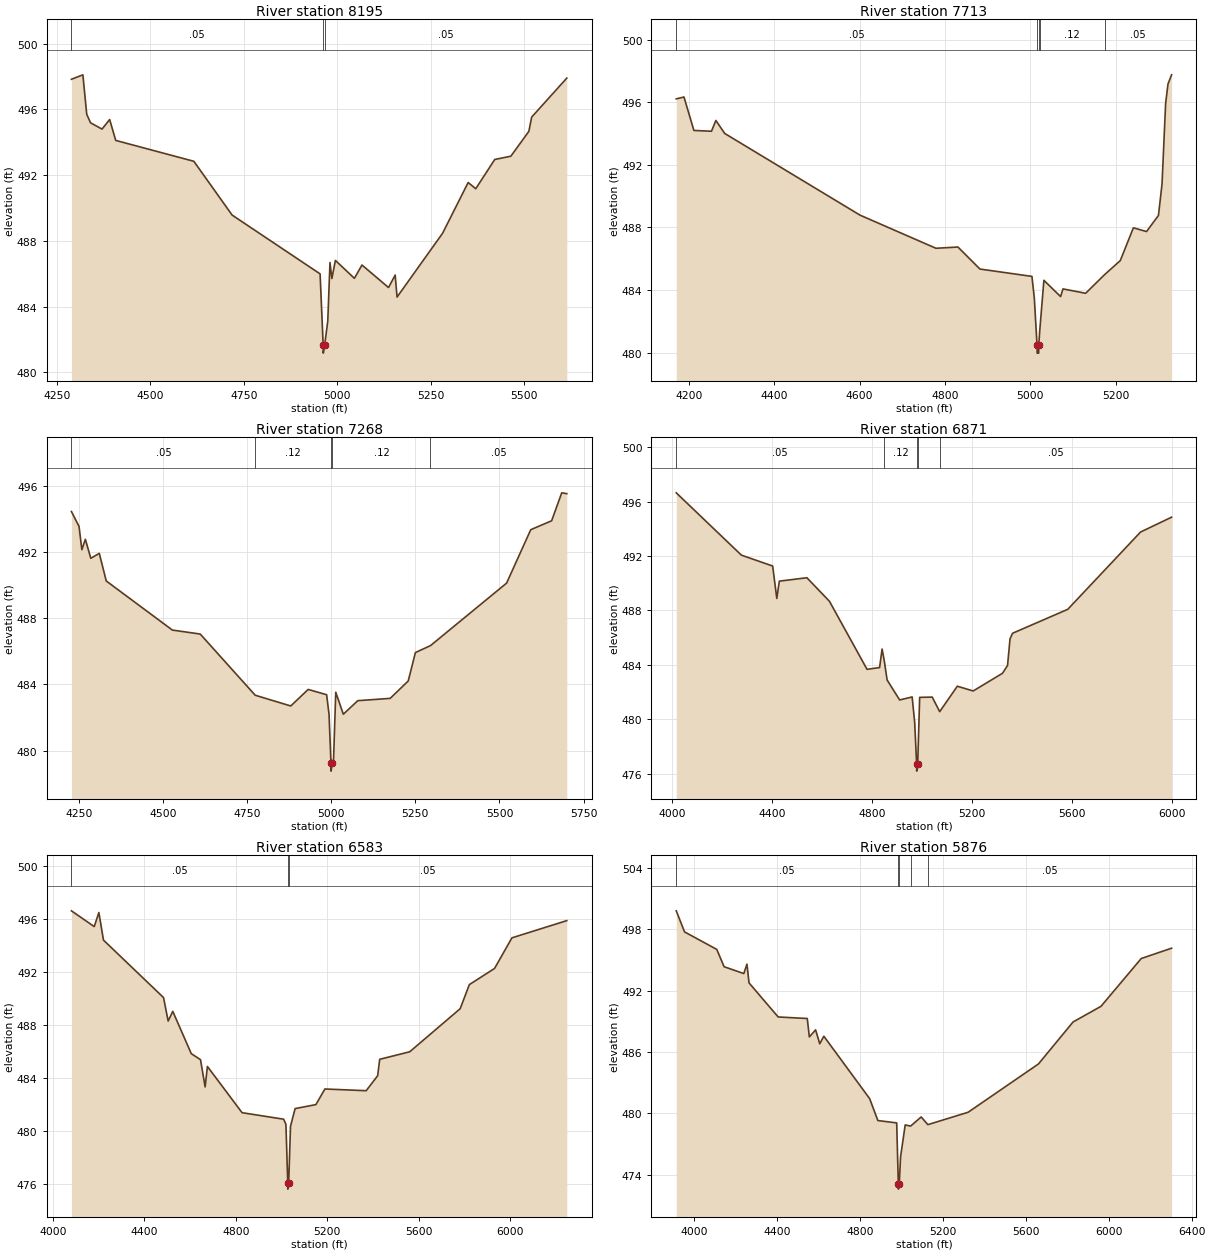
Type RM Length L Ch R = 1,8195,482,482,482
BEGIN DESCRIPTION:
Sycamore Branch 13.0
END DESCRIPTION:
XS GIS Cut Line= 3
      2737875.95      6939710.99      2737176.00      6939561.00
      2736576.02      6939661.00
#Sta/Elev= 30
  4289.4  497.83  4320.0  498.10  4330.3  495.70  4340.5  495.18  4371.2  494.80
  4391.6  495.38  4407.8  494.11  4616.6  492.84  4718.9  489.57  4954.1  485.99
  4962.3  481.67  4962.6  481.17  4966.3  481.67  4974.6  483.11  4980.5  486.68
  4985.6  485.71  4995.0  486.81  5045.8  485.72  5066.1  486.53  5137.0  485.16
  5154.8  485.92  5159.8  484.58  5281.5  488.46  5349.9  491.55  5370.2  491.17
  5420.9  492.95  5464.0  493.15  5512.1  494.66  5519.7  495.53  5613.5  497.90
#Mann=3,-1,0
  4289.4    0.05       0  4962.3    0.04       0  4966.3    0.05       0
Bank Sta=4962.3,4966.3
Exp/Cntr=0.3,0.1

Type RM Length L Ch R = 1,7713,445,445,445
BEGIN DESCRIPTION:
Sycamore Branch 12.0
END DESCRIPTION:
XS GIS Cut Line= 3
      2737876.02      6939311.01      2737076.00      6939111.00
      2736775.96      6939261.02
#Sta/Elev= 30
  4170.6  496.23  4188.7  496.35  4211.9  494.21  4253.1  494.16  4263.4  494.85
  4284.0  494.02  4601.0  488.79  4778.8  486.67  4830.3  486.75  4881.9  485.34
  5003.6  484.87  5009.2  483.48  5015.6  480.46  5015.9  479.96  5019.4  479.96
  5019.6  480.46  5021.8  481.36  5031.6  484.62  5070.7  483.58  5076.3  484.07
  5129.4  483.79  5174.0  484.99  5210.5  485.88  5241.2  487.98  5272.0  487.74
  5299.9  488.77  5308.3  490.79  5316.7  495.93  5322.3  497.19  5330.7  497.77
#Mann=5,-1,0
  4170.6    0.05       0  5015.6    0.04       0  5019.6    0.05       0
  5021.8    0.12       0  5174.0    0.05       0
Bank Sta=5015.6,5019.6
Exp/Cntr=0.3,0.1

Type RM Length L Ch R = 1,7268,397,397,397
BEGIN DESCRIPTION:
Sycamore Branch 11.0
END DESCRIPTION:
XS GIS Cut Line= 3
      2737875.99      6938911.00      2737126.00      6938711.00
      2736476.02      6938960.99
#Sta/Elev= 30
  4227.6  494.46  4250.2  493.56  4258.6  492.15  4269.0  492.78  4285.2  491.63
  4310.4  491.93  4331.1  490.26  4527.7  487.29  4610.5  487.05  4773.9  483.35
  4879.6  482.70  4931.4  483.70  4986.3  483.38  4993.4  482.20  4999.2  479.26
  4999.5  478.76  5003.3  479.26  5006.5  479.26  5013.4  483.53  5035.9  482.20
  5078.8  483.02  5175.2  483.16  5228.8  484.21  5250.2  485.93  5295.0  486.35
  5521.3  490.13  5593.1  493.36  5655.2  493.90  5685.2  495.59  5700.2  495.54
#Mann=5,-1,0
  4227.6    0.05       0  4773.9    0.12       0  4999.2    0.07       0
  5003.3    0.12       0  5295.0    0.05       0
Bank Sta=4999.2,5003.3
Exp/Cntr=0.3,0.1

Type RM Length L Ch R = 1,6871,288,288,288
BEGIN DESCRIPTION:
Sycamore Branch 10.0
END DESCRIPTION:
XS GIS Cut Line= 3
      2738257.23      6938508.12      2737275.97      6938425.83
      2736282.35      6938525.48
#Sta/Elev= 30
  4015.3  496.64  4276.2  492.06  4401.3  491.26  4417.9  488.88  4428.0  490.15
  4538.4  490.40  4628.7  488.67  4779.2  483.67  4829.4  483.80  4839.4  485.16
  4848.2  484.30  4859.5  482.89  4909.7  481.42  4959.8  481.64  4969.9  479.77
  4977.8  476.69  4978.1  476.19  4982.0  476.69  4989.9  481.61  5040.2  481.63
  5070.1  480.56  5140.7  482.43  5204.1  482.08  5321.6  483.38  5341.7  483.95
  5351.7  485.91  5361.8  486.32  5582.9  488.08  5874.3  493.76  5998.6  494.85
#Mann=5,-1,0
  4015.3    0.05       0  4848.2    0.12       0  4977.8    0.07       0
  4982.0    0.12       0  5070.1    0.05       0
Bank Sta=4977.8,4982
Exp/Cntr=0.3,0.1

Type RM Length L Ch R = 1,6583,707,707,707
BEGIN DESCRIPTION:
Sycamore Branch 9.0
END DESCRIPTION:
XS GIS Cut Line= 3
      2738284.71      6938324.30      2737375.55      6938195.81
      2736131.07      6938282.64
#Sta/Elev= 30
  4081.8  496.61  4181.5  495.42  4201.7  496.48  4221.9  494.40  4484.5  490.06
  4504.7  488.29  4524.9  489.02  4605.7  485.83  4646.2  485.37  4666.3  483.32
  4676.4  484.86  4827.9  481.37  5009.6  480.88  5019.6  480.49  5027.5  476.10
  5027.8  475.60  5031.7  476.10  5039.6  480.34  5059.7  481.68  5150.6  481.98
  5190.0  483.16  5370.4  483.03  5420.6  484.16  5429.6  485.40  5560.9  485.97
  5781.4  489.22  5821.5  491.04  5931.8  492.26  6007.7  494.57  6247.5  495.87
#Mann=3,-1,0
  4081.8    0.05       0  5027.5    0.04       0  5031.7    0.05       0
Bank Sta=5027.5,5031.7
Exp/Cntr=0.3,0.1

Type RM Length L Ch R = 1,5876,431,431,431
BEGIN DESCRIPTION:
Sycamore Branch 8.0
END DESCRIPTION:
XS GIS Cut Line= 3
      2738526.01      6937761.00      2737443.52      6937677.66
      2736200.63      6938069.87
#Sta/Elev= 30
  3914.3  499.79  3954.4  497.73  4109.8  496.02  4145.0  494.33  4240.1  493.66
  4255.3  494.58  4265.3  492.75  4405.8  489.42  4546.2  489.27  4556.2  487.47
  4586.3  488.16  4606.4  486.80  4626.1  487.54  4847.1  481.44  4886.7  479.30
  4977.5  479.07  4985.3  473.10  4985.7  472.60  4989.7  473.10  4996.2  475.76
  5018.4  478.87  5044.7  478.76  5095.6  479.65  5127.9  478.90  5322.0  480.11
  5661.2  484.83  5828.1  488.93  5962.8  490.46  6156.8  495.13  6303.3  496.14
#Mann=5,-1,0
  3914.3    0.05       0  4985.3    0.04       0  4989.7    0.05       0
  5044.7    0.12       0  5127.9    0.05       0
Bank Sta=4985.3,4989.7
Exp/Cntr=0.3,0.1

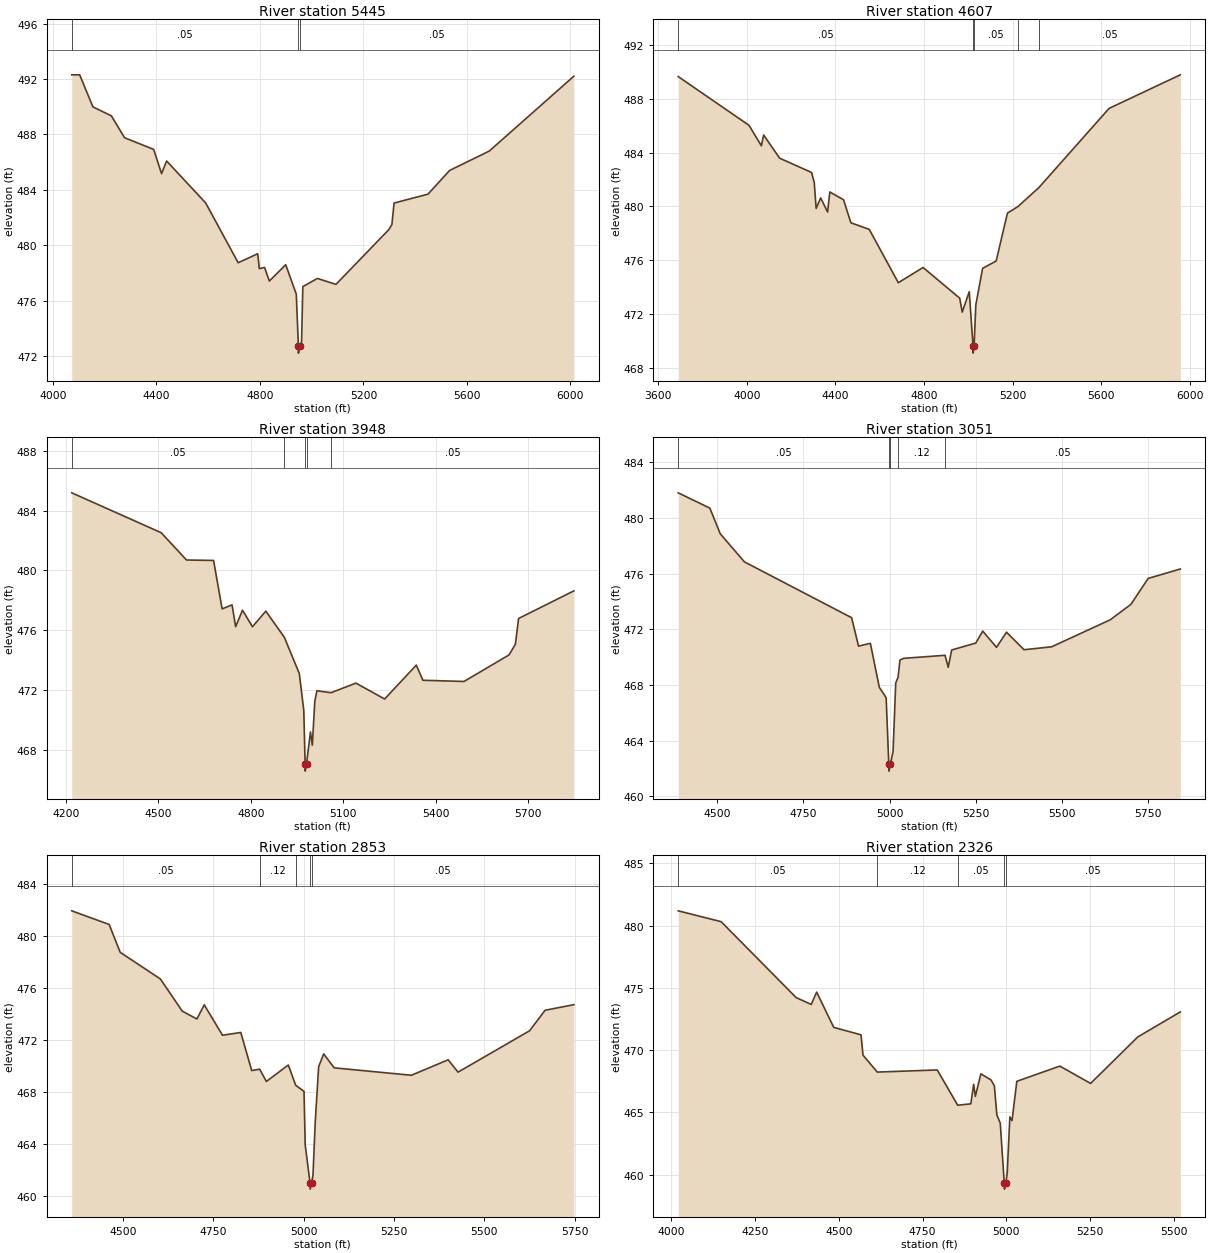
Type RM Length L Ch R = 1,5445,838,838,838
BEGIN DESCRIPTION:
Sycamore Branch 7.0
END DESCRIPTION:
XS GIS Cut Line= 3
      2738225.97      6937510.99      2737388.70      6937338.20
      2736326.02      6937561.00
#Sta/Elev= 30
  4072.8  492.30  4103.4  492.30  4154.5  489.99  4225.9  489.34  4277.0  487.76
  4389.3  486.92  4419.9  485.17  4439.5  486.08  4590.3  483.06  4716.0  478.74
  4791.4  479.39  4797.7  478.32  4818.1  478.40  4836.5  477.42  4899.8  478.60
  4940.7  476.47  4948.7  472.72  4949.1  472.22  4953.2  472.72  4960.9  473.00
  4966.0  477.02  5022.4  477.61  5093.9  477.18  5298.3  481.13  5310.2  481.50
  5318.7  483.05  5449.8  483.69  5533.3  485.40  5686.6  486.80  6013.5  492.20
#Mann=3,-1,0
  4072.8    0.05       0  4948.7    0.04       0  4953.2    0.05       0
Bank Sta=4948.7,4953.2
Exp/Cntr=0.3,0.1

Type RM Length L Ch R = 1,4607,659,659,659
BEGIN DESCRIPTION:
Sycamore Branch 6.0
END DESCRIPTION:
XS GIS Cut Line= 3
      2738510.19      6936963.19      2737239.37      6936647.68
      2736300.98      6936836.00
#Sta/Elev= 30
  3690.6  489.64  4010.1  486.02  4065.8  484.50  4076.2  485.30  4148.3  483.58
  4292.5  482.52  4304.7  481.76  4313.1  479.85  4333.7  480.63  4364.7  479.58
  4375.0  481.07  4436.8  480.49  4470.1  478.78  4552.9  478.29  4684.1  474.33
  4795.9  475.46  4961.3  473.18  4972.6  472.15  5004.3  473.66  5021.6  469.60
  5022.0  469.10  5026.1  469.60  5034.0  472.68  5064.6  475.40  5125.8  475.94
  5176.8  479.50  5223.8  479.98  5318.9  481.40  5635.8  487.28  5957.1  489.77
#Mann=5,-1,0
  3690.6    0.05       0  5021.6    0.04       0  5026.1    0.05       0
  5223.8    0.12       0  5318.9    0.05       0
Bank Sta=5021.6,5026.1
Exp/Cntr=0.3,0.1

Type RM Length L Ch R = 1,3948,897,897,897
BEGIN DESCRIPTION:
Mapping XS a3685052
END DESCRIPTION:
XS GIS Cut Line= 4
      2738345.47      6936653.26      2737796.90      6936361.61
      2737640.65      6936122.03      2736942.71      6935934.52
#Sta/Elev= 30
  4219.1  485.18  4509.4  482.52  4591.6  480.70  4679.5  480.67  4707.2  477.44
  4739.5  477.71  4751.1  476.25  4773.4  477.35  4805.7  476.25  4849.1  477.29
  4909.4  475.54  4957.8  473.13  4972.4  470.66  4976.6  467.12  4977.0  466.62
  4981.2  467.12  4994.0  469.23  5000.0  468.35  5008.2  471.29  5015.1  471.98
  5061.0  471.85  5141.6  472.49  5234.8  471.43  5337.7  473.69  5359.0  472.68
  5492.5  472.60  5638.6  474.37  5659.3  475.08  5669.7  476.80  5849.1  478.64
#Mann=5,-1,0
  4219.1    0.05       0  4909.4    0.12       0  4976.6    0.07       0
  4981.2    0.12       0  5061.0    0.05       0
Bank Sta=4976.6,4981.2
Exp/Cntr=0.3,0.1

Type RM Length L Ch R = 1,3051,198,198,198
BEGIN DESCRIPTION:
Mapping XS 5ad1b935
END DESCRIPTION:
XS GIS Cut Line= 3
      2738487.57      6935688.70      2737855.59      6935640.08
      2737032.70      6935629.67
#Sta/Elev= 30
  4386.7  481.81  4478.5  480.71  4508.6  478.87  4578.8  476.85  4889.8  472.84
  4909.8  470.80  4944.2  471.00  4970.0  467.85  4990.0  467.09  4997.7  462.32
  4998.2  461.82  5002.5  462.32  5010.1  463.25  5017.8  468.15  5024.6  468.56
  5030.1  469.80  5040.1  469.92  5160.8  470.14  5170.1  469.28  5180.1  470.52
  5250.2  471.02  5270.2  471.88  5310.2  470.71  5339.2  471.80  5390.2  470.54
  5470.2  470.75  5640.2  472.69  5700.2  473.80  5750.2  475.66  5843.5  476.34
#Mann=5,-1,0
  4386.7    0.05       0  4997.7    0.05       0  5002.5    0.05       0
  5024.6    0.12       0  5160.8    0.05       0
Bank Sta=4997.7,5002.5
Exp/Cntr=0.3,0.1

Type RM Length L Ch R = 1,2853,527,527,527
BEGIN DESCRIPTION:
Mapping XS 38b15205
END DESCRIPTION:
XS GIS Cut Line= 3
      2738468.41      6935555.36      2737833.02      6935458.14
      2737187.18      6935083.14
#Sta/Elev= 30
  4358.2  481.96  4461.8  480.91  4492.1  478.77  4603.4  476.72  4664.1  474.24
  4704.6  473.64  4724.8  474.73  4775.4  472.39  4826.0  472.60  4856.3  469.67
  4878.2  469.78  4896.8  468.83  4957.5  470.10  4978.0  468.54  5001.0  468.07
  5004.3  463.95  5017.6  461.05  5018.2  460.55  5022.4  461.05  5025.8  461.64
  5032.2  465.79  5041.5  469.97  5055.4  470.95  5084.6  469.88  5298.2  469.31
  5400.0  470.50  5427.3  469.55  5625.2  472.73  5668.2  474.31  5747.8  474.74
#Mann=5,-1,0
  4358.2    0.05       0  4878.2    0.12       0  4978.0    0.05       0
  5017.6    0.05       0  5022.4    0.05       0
Bank Sta=5017.6,5022.4
Exp/Cntr=0.3,0.1

Type RM Length L Ch R = 1,2326,129,129,129
BEGIN DESCRIPTION:
Mapping XS cb85e283
END DESCRIPTION:
XS GIS Cut Line= 6
      2738541.65      6935422.04      2737920.08      6935300.50
      2737916.61      6934981.06      2737812.28      6934852.50
      2737618.00      6934678.97      2737500.52      6934658.24
#Sta/Elev= 30
  4020.2  481.18  4148.2  480.31  4372.4  474.21  4417.3  473.66  4433.5  474.65
  4484.5  471.82  4566.0  471.22  4571.9  469.59  4614.5  468.23  4793.6  468.40
  4854.6  465.57  4893.8  465.68  4902.3  467.25  4907.3  466.28  4923.9  468.09
  4954.0  467.60  4964.0  467.14  4971.5  464.80  4981.7  464.13  4993.6  459.33
  4994.2  458.83  4998.5  459.33  5002.5  460.14  5010.4  464.63  5016.8  464.33
  5031.2  467.49  5159.5  468.71  5251.4  467.32  5392.7  471.06  5519.3  473.06
#Mann=5,-1,0
  4020.2    0.05       0  4614.5    0.12       0  4854.6    0.05       0
  4993.6    0.05       0  4998.5    0.05       0
Bank Sta=4993.6,4998.5
Exp/Cntr=0.3,0.1