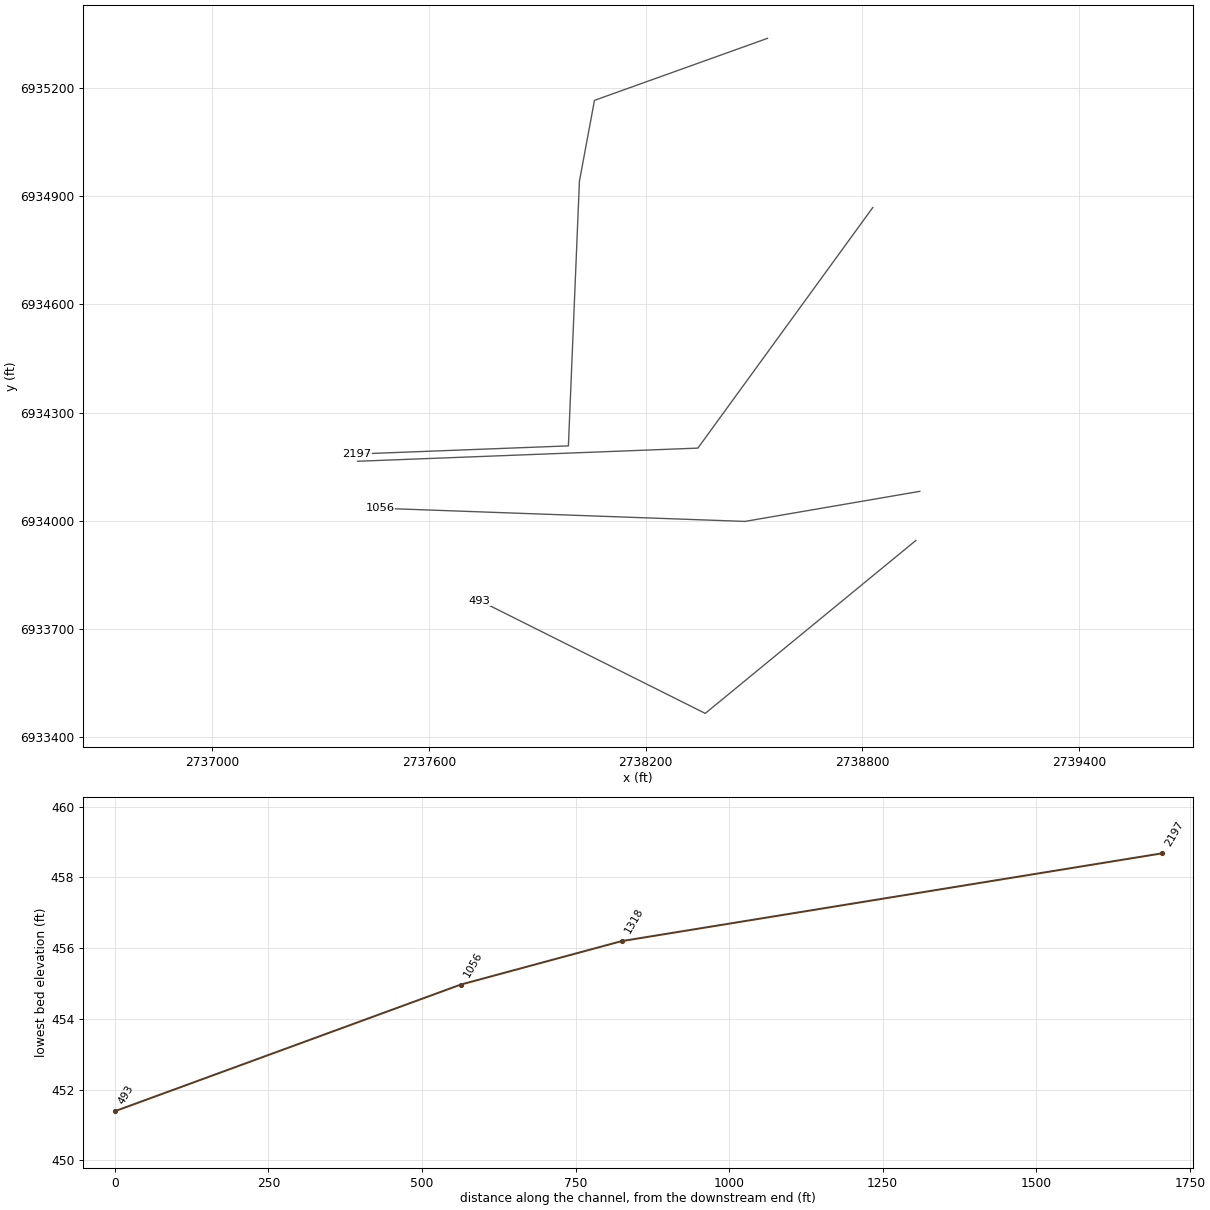
HEC-RAS study Sycamore Branch.prj: Sycamore Branch Base Level Engineering

--- Sycamore Branch.g01 (geometry) --- (continued)

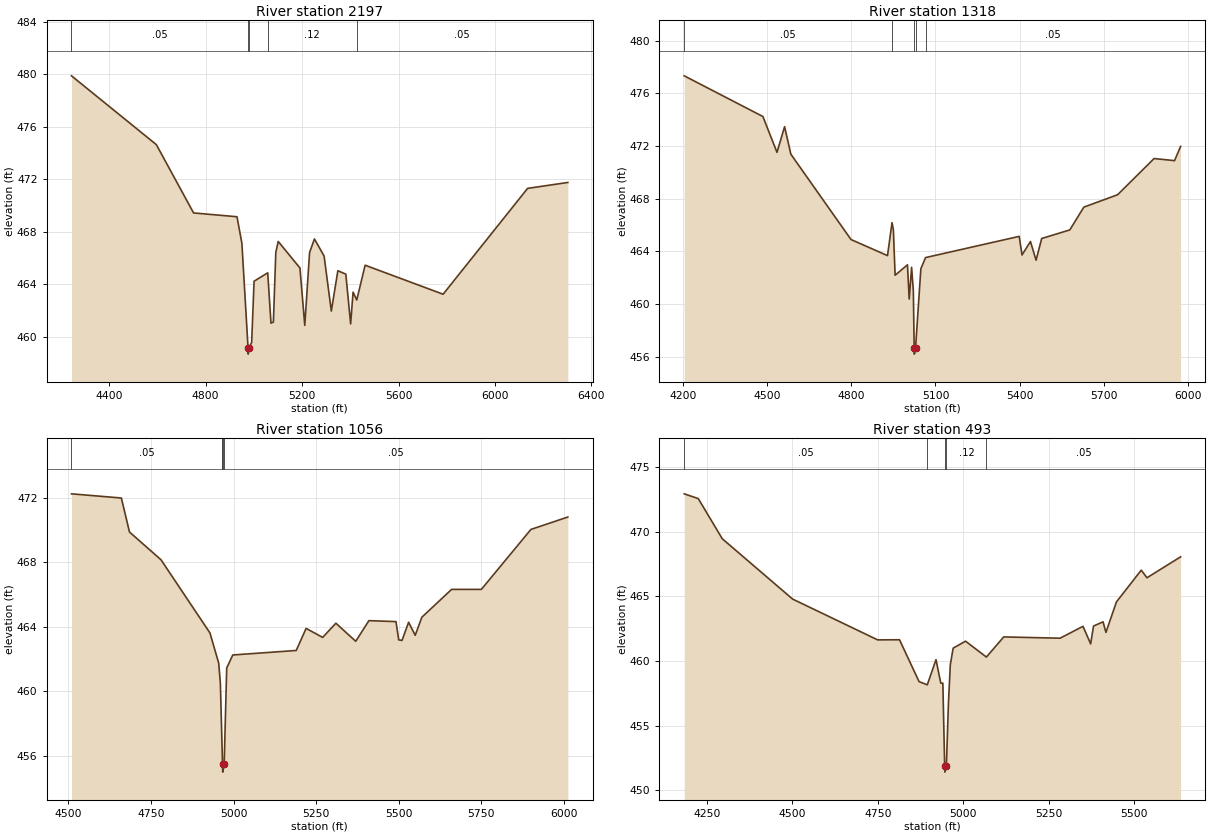
Type RM Length L Ch R = 1,2197,879,879,879
BEGIN DESCRIPTION:
Mapping XS 4d44e49a
END DESCRIPTION:
XS GIS Cut Line= 5
      2738537.25      6935336.97      2738058.04      6935165.08
      2738016.38      6934941.13      2737985.83      6934207.73
      2737399.29      6934185.14
#Sta/Elev= 30
  4244.1  479.87  4596.0  474.63  4750.3  469.43  4930.3  469.14  4950.6  467.12
  4976.1  459.18  4976.7  458.68  4981.0  459.18  4991.1  459.57  5001.1  464.23
  5057.7  464.87  5071.2  461.04  5081.2  461.12  5091.2  466.41  5101.2  467.26
  5191.3  465.24  5211.3  460.87  5231.3  466.42  5251.4  467.45  5291.4  466.15
  5321.4  461.96  5348.5  465.03  5381.5  464.77  5401.5  460.98  5411.5  463.40
  5426.9  462.80  5461.5  465.45  5784.9  463.24  6135.2  471.30  6302.0  471.75
#Mann=5,-1,0
  4244.1    0.05       0  4976.1    0.04       0  4981.0    0.05       0
  5057.7    0.12       0  5426.9    0.05       0
Bank Sta=4976.1,4981
Exp/Cntr=0.3,0.1

Type RM Length L Ch R = 1,1318,262,262,262
BEGIN DESCRIPTION:
Mapping XS 84e61c62
END DESCRIPTION:
XS GIS Cut Line= 3
      2738828.88      6934868.21      2738344.50      6934201.54
      2737401.77      6934165.08
#Sta/Elev= 30
  4205.4  477.33  4485.5  474.24  4535.7  471.52  4562.8  473.47  4585.1  471.38
  4799.3  464.90  4929.2  463.68  4945.3  466.18  4950.1  465.66  4956.3  462.19
  5000.3  462.98  5006.5  460.38  5015.0  462.79  5021.2  461.02  5024.2  456.70
  5024.8  456.20  5029.2  456.70  5048.0  462.68  5064.7  463.53  5398.2  465.14
  5408.2  463.73  5438.3  464.75  5458.3  463.33  5478.3  464.98  5578.4  465.63
  5628.4  467.36  5748.5  468.30  5878.6  471.05  5951.4  470.89  5972.9  471.97
#Mann=5,-1,0
  4205.4    0.05       0  4945.3    0.12       0  5024.2    0.07       0
  5029.2    0.12       0  5064.7    0.05       0
Bank Sta=5024.2,5029.2
Exp/Cntr=0.3,0.1

Type RM Length L Ch R = 1,1056,563,563,563
BEGIN DESCRIPTION:
Mapping XS 4e88e43d
END DESCRIPTION:
XS GIS Cut Line= 3
      2738959.05      6934081.74      2738474.71      6933998.42
      2737464.32      6934034.87
#Sta/Elev= 30
  4509.4  472.24  4660.4  471.98  4685.0  469.87  4780.3  468.15  4928.5  463.61
  4955.0  461.74  4960.1  460.48  4964.9  456.78  4966.1  455.86  4966.6  455.47
  4967.2  454.97  4971.6  455.47  4979.3  461.43  4997.7  462.24  5189.7  462.52
  5219.7  463.89  5269.7  463.33  5309.8  464.21  5369.8  463.09  5409.8  464.37
  5491.7  464.31  5499.9  463.18  5509.9  463.14  5529.9  464.27  5549.9  463.46
  5569.9  464.58  5660.0  466.31  5750.1  466.31  5900.1  470.03  6011.9  470.80
#Mann=5,-1,0
  4509.4    0.05       0  4964.9    0.12       0  4966.1    0.05       0
  4966.6    0.04       0  4971.6    0.05       0
Bank Sta=4966.6,4971.6
Exp/Cntr=0.3,0.1

Type RM Length L Ch R = 1,493,0,0,0
BEGIN DESCRIPTION:
Sycamore Branch 1.0
END DESCRIPTION:
XS GIS Cut Line= 3
      2738948.27      6933945.71      2738364.90      6933466.52
      2737740.46      6933778.74
#Sta/Elev= 30
  4183.3  472.94  4224.4  472.57  4294.7  469.46  4500.6  464.79  4749.6  461.63
  4813.5  461.64  4870.8  458.40  4894.8  458.15  4920.4  460.10  4934.3  458.28
  4940.4  458.28  4945.7  451.89  4946.3  451.39  4950.8  451.89  4956.6  456.61
  4962.2  459.70  4970.6  460.99  5006.9  461.53  5067.8  460.30  5118.7  461.86
  5283.6  461.76  5350.7  462.68  5373.1  461.32  5381.5  462.70  5409.4  463.03
  5417.8  462.21  5448.6  464.57  5521.2  467.03  5538.0  466.44  5636.4  468.06
#Mann=5,-1,0
  4183.3    0.05       0  4894.8    0.12       0  4945.7    0.07       0
  4950.8    0.12       0  5067.8    0.05       0
Bank Sta=4945.7,4950.8
Exp/Cntr=0.3,0.1

Chan Stop Cuts=-1