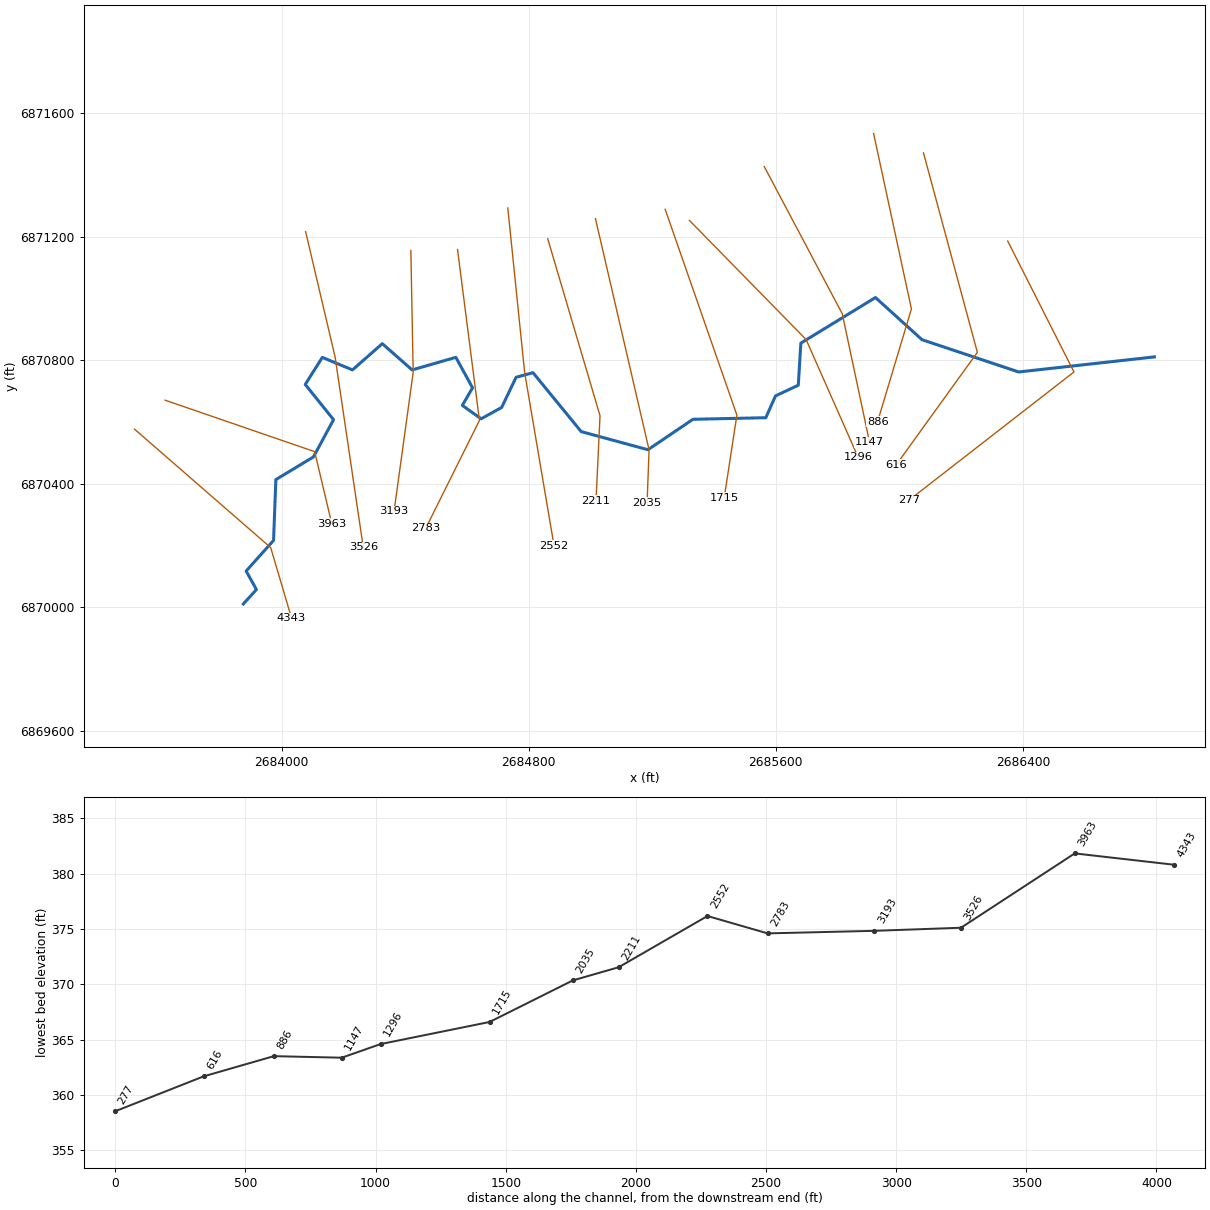
--- Walnut T1.prj (project) ---

Proj Title=Walnut T1 Base Level Engineering
Current Plan=p01
Default Exp/Contr=0.3,0.1
English Units
Geom File=g01
Flow File=f01
Plan File=p01
BEGIN DESCRIPTION:
Walnut T1
END DESCRIPTION:

--- Walnut T1.p01 (plan) ---

Plan Title=Multiple Run
Short Identifier=Multiple
Geom File=g01
Flow File=f01
Subcritical Flow
K Sum by GR= 0
Std Step Tol= 0.01
Critical Tol= 0.01
Num of Std Step Trials= 20
Max Error Tol= 0.3
Flow Tol Ratio= 0.001
Split Flow NTrial= 30
Split Flow Tol= 0.02
Split Flow Ratio= 0.02
Log Output Level= 0
Friction Slope Method= 1
Unsteady Friction Slope Method= 2
Unsteady Bridges Friction Slope Method= 1
Parabolic Critical Depth
Global Vel Dist=  1 , 1 , 1
Global Log Level= 0
CheckData=True
Encroach Param= -1, 0, 0, 0
BEGIN DESCRIPTION:
Multiple Run
END DESCRIPTION:

--- Walnut T1.f01 (steady flow) ---

Flow Title=Multiple
Number of Profiles=7
Profile Names=10-year,25-year,50-year,1pct_min,100-year,1pct_plu,500-year
River Rch & RM= Walnut T1,Reach-1,4343
     533     715     863     517    1032    2060    1476
River Rch & RM= Walnut T1,Reach-1,3526
     812    1117    1370     833    1663    3318    2449
Boundary for River Rch & Prof#=Walnut T1,Reach-1,1
Up Type=0
Dn Type=3
Dn Slope=0.005
Boundary for River Rch & Prof#=Walnut T1,Reach-1,2
Up Type=0
Dn Type=3
Dn Slope=0.005
Boundary for River Rch & Prof#=Walnut T1,Reach-1,3
Up Type=0
Dn Type=3
Dn Slope=0.005
Boundary for River Rch & Prof#=Walnut T1,Reach-1,4
Up Type=0
Dn Type=3
Dn Slope=0.005
Boundary for River Rch & Prof#=Walnut T1,Reach-1,5
Up Type=0
Dn Type=3
Dn Slope=0.005
Boundary for River Rch & Prof#=Walnut T1,Reach-1,6
Up Type=0
Dn Type=3
Dn Slope=0.005
Boundary for River Rch & Prof#=Walnut T1,Reach-1,7
Up Type=0
Dn Type=3
Dn Slope=0.005

--- Walnut T1.g01 (geometry) ---

Geom Title=Existing Conditions

River Reach=Walnut T1,Reach-1
Reach XY= 30
      2683876.00      6870011.00      2683918.48      6870057.67
      2683885.21      6870117.66      2683973.92      6870216.85
      2683981.36      6870413.70      2684103.15      6870487.17
      2684168.16      6870607.76      2684076.54      6870721.70
      2684131.82      6870809.42      2684229.41      6870768.85
      2684326.00      6870853.88      2684422.58      6870768.83
      2684564.16      6870809.49      2684618.23      6870710.93
      2684585.18      6870653.95      2684646.01      6870610.50
      2684712.50      6870647.31      2684759.15      6870745.02
      2684813.92      6870759.89      2684969.94      6870569.14
      2685186.19      6870510.45      2685331.86      6870608.93
      2685567.69      6870614.09      2685599.06      6870684.62
      2685672.89      6870719.32      2685681.19      6870855.55
      2685922.77      6871003.17      2686073.63      6870866.54
      2686386.51      6870762.22      2686826.00      6870811.00

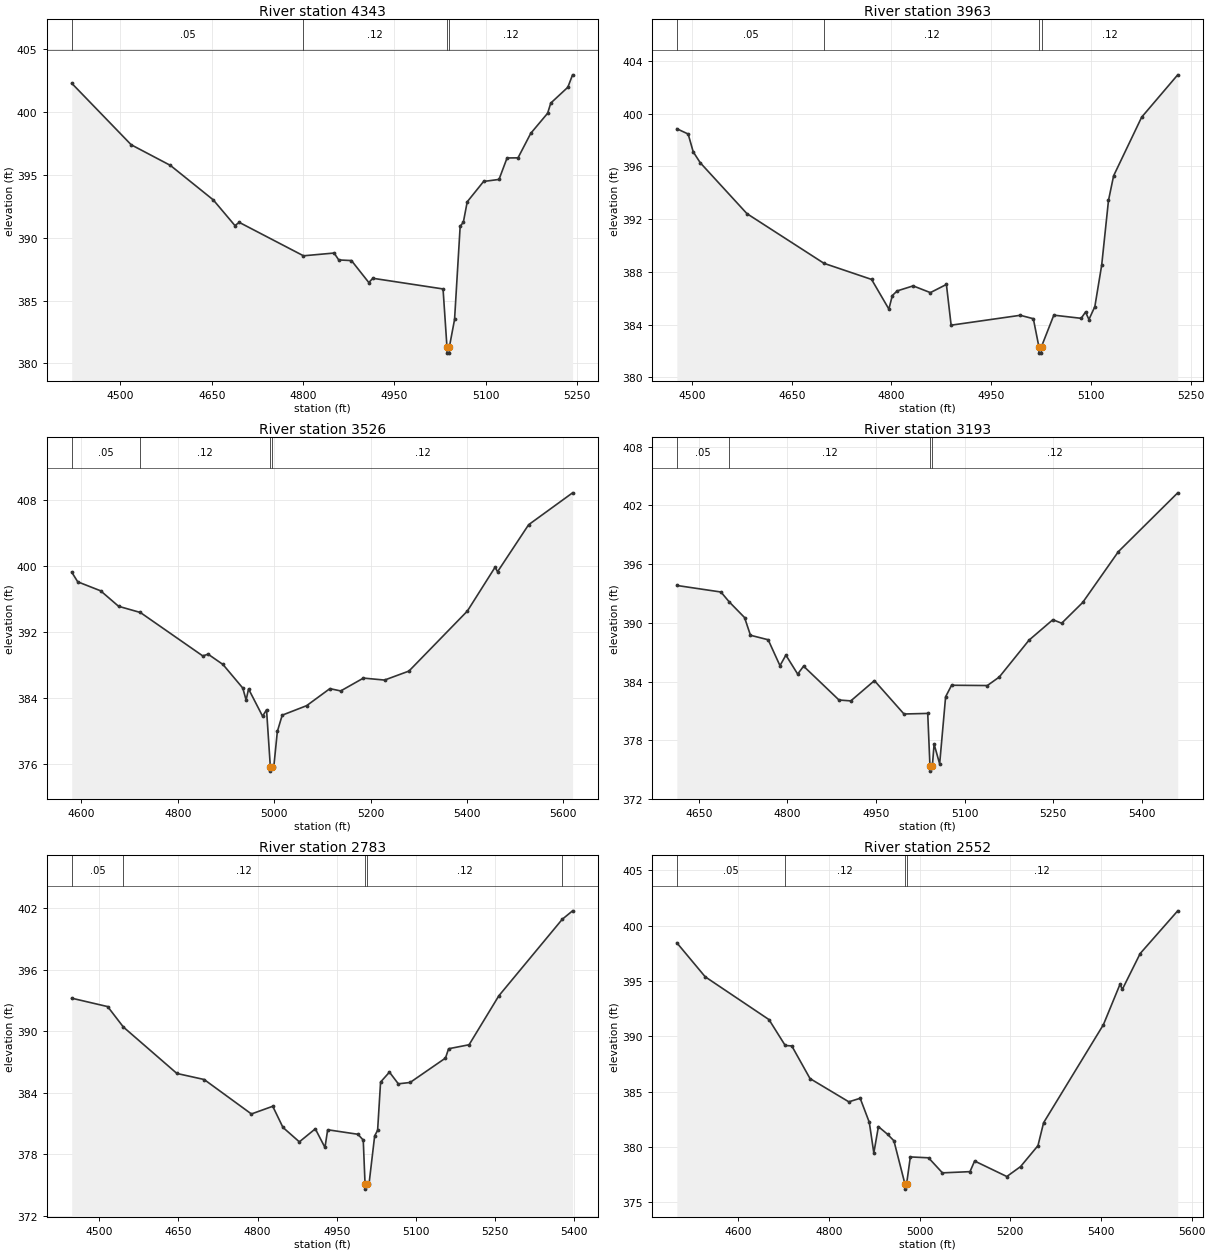
Type RM Length L Ch R = 1,4343,380,380,380
BEGIN DESCRIPTION:
Walnut T1 10.0
END DESCRIPTION:
XS GIS Cut Line= 3
      2683523.79      6870577.03      2683964.73      6870193.37
      2684032.18      6869965.11
#Sta/Elev= 30
  4420.0  402.31  4517.7  397.41  4582.0  395.77  4652.5  393.02  4688.0  390.98
  4695.2  391.23  4800.6  388.57  4850.9  388.79  4858.5  388.24  4879.4  388.19
  4907.9  386.44  4914.5  386.78  5029.8  385.93  5036.2  381.32  5036.5  380.82
  5040.0  380.82  5040.2  381.32  5048.7  383.50  5057.9  390.92  5063.1  391.24
  5069.5  392.87  5096.4  394.49  5121.7  394.65  5134.9  396.36  5152.9  396.37
  5173.8  398.32  5201.5  399.92  5206.7  400.73  5234.7  401.99  5242.5  402.98
#Mann=4,-1,0
  4420.0    0.05       0  4800.6    0.12       0  5036.2    0.07       0
  5040.2    0.12       0
Bank Sta=5036.2,5040.2
Exp/Cntr=0.3,0.1

Type RM Length L Ch R = 1,3963,437,437,437
BEGIN DESCRIPTION:
Walnut T1 9.0
END DESCRIPTION:
XS GIS Cut Line= 3
      2683622.74      6870670.80      2684107.10      6870504.14
      2684162.65      6870269.76
#Sta/Elev= 30
  4477.3  398.86  4494.3  398.46  4501.9  397.11  4512.5  396.28  4582.7  392.42
  4698.6  388.65  4770.1  387.43  4796.1  385.18  4801.3  386.21  4808.6  386.56
  4832.6  386.94  4858.5  386.43  4882.6  387.05  4889.7  383.96  4993.7  384.71
  5013.3  384.45  5021.6  382.34  5021.8  381.84  5025.3  381.84  5025.6  382.34
  5044.1  384.72  5085.2  384.48  5091.8  384.96  5096.9  384.39  5105.8  385.37
  5116.1  388.52  5126.3  393.42  5134.0  395.29  5176.2  399.74  5230.4  402.95
#Mann=4,-1,0
  4477.3    0.05       0  4698.6    0.12       0  5021.6    0.07       0
  5025.6    0.12       0
Bank Sta=5021.6,5025.6
Exp/Cntr=0.3,0.1

Type RM Length L Ch R = 1,3526,333,333,333
BEGIN DESCRIPTION:
Walnut T1 8.0
END DESCRIPTION:
XS GIS Cut Line= 3
      2684077.73      6871216.45      2684173.21      6870810.63
      2684264.24      6870195.13
#Sta/Elev= 30
  4580.1  399.27  4592.6  398.09  4640.1  397.00  4677.4  395.12  4722.5  394.37
  4852.0  389.10  4863.1  389.31  4893.9  388.06  4935.0  385.20  4941.9  383.75
  4947.0  385.09  4976.1  381.78  4984.3  382.57  4992.2  375.62  4992.5  375.12
  4996.2  375.62  4999.3  375.62  5006.7  379.93  5016.8  381.91  5067.4  383.06
  5115.7  385.13  5138.2  384.85  5185.3  386.41  5229.1  386.17  5279.7  387.26
  5401.0  394.55  5458.5  399.87  5463.5  399.31  5528.0  405.02  5619.2  408.89
#Mann=4,-1,0
  4580.1    0.05       0  4722.5    0.12       0  4992.2    0.07       0
  4996.2    0.12       0
Bank Sta=4992.2,4996.2
Exp/Cntr=0.3,0.1

Type RM Length L Ch R = 1,3193,410,410,410
BEGIN DESCRIPTION:
Walnut T1 7.0
END DESCRIPTION:
XS GIS Cut Line= 3
      2684418.44      6871155.68      2684426.00      6870761.00
      2684364.18      6870311.48
#Sta/Elev= 30
  4612.6  393.82  4687.3  393.15  4701.2  392.15  4727.3  390.54  4737.3  388.73
  4767.3  388.27  4787.3  385.62  4797.3  386.70  4817.3  384.76  4827.3  385.57
  4887.3  382.11  4907.3  382.02  4947.3  384.09  4997.4  380.68  5037.6  380.74
  5041.4  375.34  5041.6  374.84  5045.4  375.34  5048.4  377.60  5057.8  375.58
  5067.9  382.44  5078.0  383.62  5138.6  383.59  5158.8  384.46  5209.2  388.23
  5249.6  390.32  5264.5  389.96  5300.1  392.08  5360.6  397.28  5461.1  403.29
#Mann=4,-1,0
  4612.6    0.05       0  4701.2    0.12       0  5041.4    0.07       0
  5045.4    0.12       0
Bank Sta=5041.4,5045.4
Exp/Cntr=0.3,0.1

Type RM Length L Ch R = 1,2783,231,231,231
BEGIN DESCRIPTION:
Walnut T1 6.0
END DESCRIPTION:
XS GIS Cut Line= 3
      2684569.59      6871158.57      2684640.54      6870605.22
      2684466.42      6870255.56
#Sta/Elev= 30
  4448.0  393.23  4516.1  392.41  4545.8  390.42  4647.2  385.89  4698.8  385.30
  4788.3  381.94  4828.7  382.69  4848.0  380.63  4879.1  379.22  4909.3  380.49
  4927.6  378.67  4932.7  380.40  4990.0  379.96  5000.1  379.39  5003.5  375.11
  5003.7  374.61  5007.5  375.11  5011.0  375.11  5021.7  379.80  5027.3  380.35
  5032.9  385.05  5049.7  386.02  5066.5  384.88  5088.8  385.01  5155.8  387.39
  5161.7  388.30  5200.5  388.69  5256.8  393.46  5377.0  400.93  5396.5  401.75
#Mann=5,-1,0
  4448.0    0.05       0  4545.8    0.12       0  5003.5    0.07       0
  5007.5    0.12       0  5377.0    0.05       0
Bank Sta=5003.5,5007.5
Exp/Cntr=0.3,0.1

Type RM Length L Ch R = 1,2552,341,341,341
BEGIN DESCRIPTION:
Walnut T1 5.0
END DESCRIPTION:
XS GIS Cut Line= 3
      2684732.34      6871293.19      2684786.87      6870760.67
      2684882.08      6870199.39
#Sta/Elev= 30
  4464.7  398.44  4527.2  395.37  4667.9  391.50  4703.7  389.16  4718.2  389.12
  4758.4  386.17  4844.0  384.07  4869.0  384.39  4889.1  382.22  4899.1  379.45
  4909.2  381.83  4929.3  381.14  4943.4  380.55  4967.5  376.68  4967.8  376.18
  4971.5  376.68  4979.6  379.09  5019.8  379.01  5050.4  377.65  5111.2  377.76
  5121.4  378.72  5192.4  377.32  5222.8  378.22  5261.1  380.11  5273.5  382.18
  5405.4  391.04  5442.1  394.70  5447.1  394.23  5486.5  397.47  5569.3  401.33
#Mann=4,-1,0
  4464.7    0.05       0  4703.7    0.12       0  4967.5    0.07       0
  4971.5    0.12       0
Bank Sta=4967.5,4971.5
Exp/Cntr=0.3,0.1

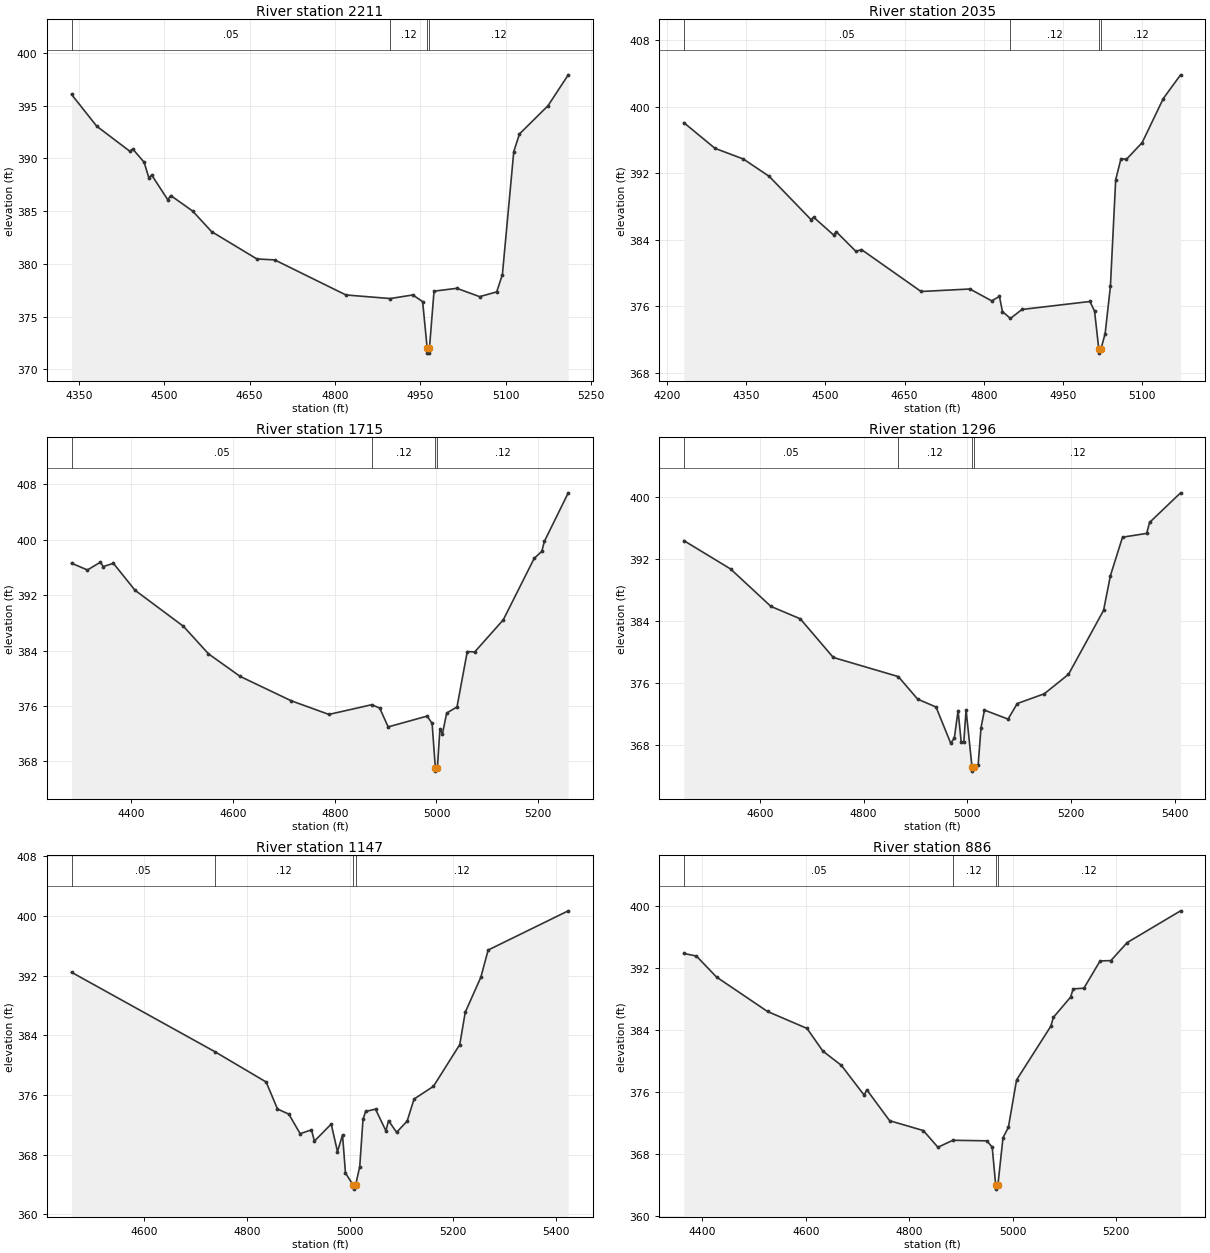
Type RM Length L Ch R = 1,2211,176,176,176
BEGIN DESCRIPTION:
Mapping XS f64b6ff3
END DESCRIPTION:
XS GIS Cut Line= 3
      2684861.68      6871193.35      2685030.95      6870620.41
      2685017.96      6870345.44
#Sta/Elev= 30
  4337.1  396.06  4381.3  393.05  4439.6  390.67  4444.8  390.88  4464.7  389.63
  4472.9  388.17  4478.1  388.41  4506.2  386.08  4511.4  386.48  4549.9  385.01
  4583.2  383.06  4662.8  380.47  4694.1  380.38  4819.2  377.06  4897.0  376.72
  4936.7  377.06  4954.0  376.43  4961.9  372.05  4962.2  371.55  4965.7  371.55
  4966.0  372.05  4974.0  377.42  5014.0  377.69  5054.1  376.90  5084.1  377.35
  5094.1  378.99  5114.1  390.64  5124.1  392.31  5174.2  394.98  5209.8  397.91
#Mann=4,-1,0
  4337.1    0.05       0  4897.0    0.12       0  4961.9    0.07       0
  4966.0    0.12       0
Bank Sta=4961.9,4966
Exp/Cntr=0.3,0.1

Type RM Length L Ch R = 1,2035,320,320,320
BEGIN DESCRIPTION:
Mapping XS cdcb34cb
END DESCRIPTION:
XS GIS Cut Line= 3
      2685016.20      6871258.44      2685189.81      6870509.74
      2685183.30      6870338.33
#Sta/Elev= 30
  4232.2  398.07  4291.2  394.98  4344.8  393.70  4393.8  391.61  4472.8  386.42
  4477.9  386.70  4515.5  384.57  4520.6  384.96  4558.1  382.58  4568.4  382.81
  4681.2  377.77  4773.6  378.07  4814.7  376.65  4829.5  377.17  4835.2  375.36
  4850.2  374.53  4872.2  375.61  5000.8  376.57  5009.5  375.41  5017.5  370.86
  5017.8  370.36  5021.6  370.86  5029.5  372.70  5039.5  378.38  5049.5  391.21
  5059.5  393.74  5069.6  393.65  5099.6  395.67  5139.6  400.97  5172.3  403.82
#Mann=4,-1,0
  4232.2    0.05       0  4850.2    0.12       0  5017.5    0.07       0
  5021.6    0.12       0
Bank Sta=5017.5,5021.6
Exp/Cntr=0.3,0.1

Type RM Length L Ch R = 1,1715,419,419,419
BEGIN DESCRIPTION:
Mapping XS 951ab686
END DESCRIPTION:
XS GIS Cut Line= 3
      2685241.88      6871288.85      2685474.10      6870622.58
      2685433.06      6870354.78
#Sta/Elev= 30
  4282.6  396.60  4313.9  395.62  4339.6  396.75  4344.9  396.11  4365.0  396.58
  4407.4  392.70  4502.7  387.49  4551.9  383.52  4614.0  380.27  4714.5  376.75
  4788.6  374.78  4872.7  376.18  4888.4  375.70  4905.1  372.98  4981.7  374.54
  4991.5  373.49  4997.8  367.10  4998.1  366.60  5001.9  367.10  5006.8  372.65
  5011.8  371.97  5020.1  374.98  5040.4  375.86  5060.6  383.85  5075.2  383.79
  5131.4  388.43  5192.1  397.29  5207.0  398.30  5212.3  399.76  5259.1  406.75
#Mann=4,-1,0
  4282.6    0.05       0  4872.7    0.12       0  4997.8    0.07       0
  5001.9    0.12       0
Bank Sta=4997.8,5001.9
Exp/Cntr=0.3,0.1

Type RM Length L Ch R = 1,1296,149,149,149
BEGIN DESCRIPTION:
Mapping XS 8b09972f
END DESCRIPTION:
XS GIS Cut Line= 3
      2685320.46      6871252.78      2685698.05      6870867.37
      2685866.99      6870485.31
#Sta/Elev= 30
  4453.6  394.37  4543.6  390.71  4621.5  385.87  4678.0  384.27  4741.6  379.28
  4866.9  376.81  4904.2  373.90  4939.6  372.88  4967.9  368.21  4974.9  368.86
  4982.1  372.42  4988.1  368.38  4993.2  368.38  4997.5  372.51  5009.0  365.10
  5009.3  364.60  5013.2  365.10  5020.8  365.40  5026.3  370.19  5032.9  372.48
  5078.4  371.32  5096.2  373.33  5148.3  374.59  5194.9  377.10  5262.5  385.36
  5275.7  389.85  5299.0  394.81  5345.6  395.30  5351.1  396.71  5410.9  400.54
#Mann=4,-1,0
  4453.6    0.05       0  4866.9    0.12       0  5009.0    0.07       0
  5013.2    0.12       0
Bank Sta=5009,5013.2
Exp/Cntr=0.3,0.1

Type RM Length L Ch R = 1,1147,261,261,261
BEGIN DESCRIPTION:
Mapping XS d868b1eb
END DESCRIPTION:
XS GIS Cut Line= 3
      2685562.62      6871427.31      2685815.24      6870950.71
      2685903.58      6870535.01
#Sta/Elev= 30
  4459.4  392.46  4737.6  381.81  4837.3  377.74  4859.3  374.12  4881.3  373.43
  4903.3  370.81  4925.3  371.32  4931.0  369.81  4963.6  372.10  4975.8  368.40
  4985.6  370.64  4991.3  365.53  5006.6  363.87  5007.0  363.37  5010.8  363.87
  5019.0  366.39  5025.3  372.71  5030.4  373.79  5049.6  374.10  5069.8  371.19
  5074.9  372.56  5090.5  370.99  5111.0  372.49  5124.5  375.46  5162.1  377.16
  5213.2  382.76  5223.8  387.09  5254.1  391.79  5268.3  395.44  5423.8  400.70
#Mann=4,-1,0
  4459.4    0.05       0  4737.6    0.12       0  5006.6    0.07       0
  5010.8    0.12       0
Bank Sta=5006.6,5010.8
Exp/Cntr=0.3,0.1

Type RM Length L Ch R = 1,886,270,270,270
BEGIN DESCRIPTION:
Mapping XS 24017f9b
END DESCRIPTION:
XS GIS Cut Line= 3
      2685916.79      6871534.09      2686039.20      6870966.33
      2685929.83      6870601.78
#Sta/Elev= 30
  4363.9  393.85  4388.2  393.52  4427.3  390.81  4525.9  386.38  4602.3  384.20
  4633.0  381.28  4668.7  379.45  4712.9  375.61  4718.0  376.30  4762.2  372.32
  4827.4  371.05  4855.7  368.90  4884.5  369.80  4950.3  369.73  4960.7  368.92
  4967.5  364.01  4967.8  363.51  4971.7  364.01  4981.6  370.13  4992.0  371.46
  5007.9  377.57  5074.0  384.47  5079.2  385.63  5112.3  388.22  5117.5  389.29
  5138.2  389.38  5169.5  392.89  5190.4  392.93  5221.9  395.25  5325.3  399.34
#Mann=4,-1,0
  4363.9    0.05       0  4884.5    0.12       0  4967.5    0.07       0
  4971.7    0.12       0
Bank Sta=4967.5,4971.7
Exp/Cntr=0.3,0.1

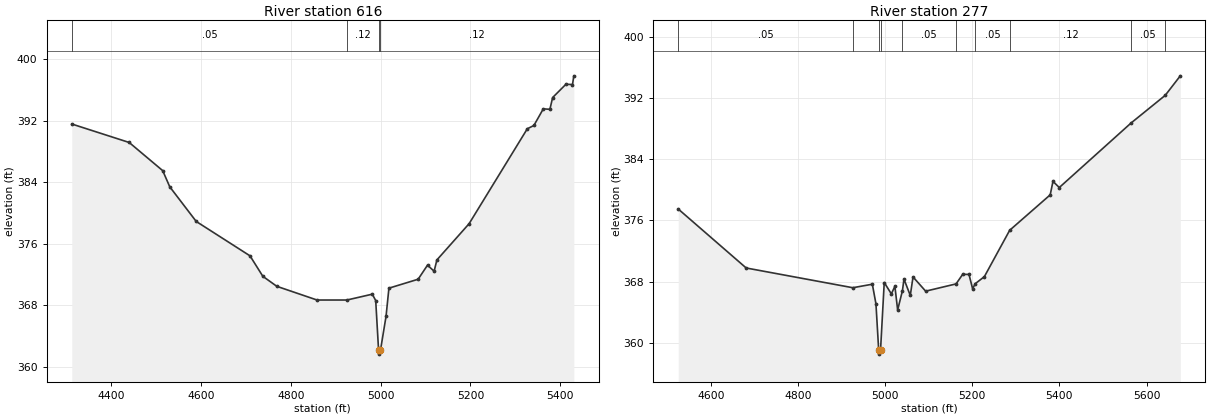
Type RM Length L Ch R = 1,616,339,339,339
BEGIN DESCRIPTION:
Mapping XS c708d7f2
END DESCRIPTION:
XS GIS Cut Line= 3
      2686078.25      6871471.57      2686252.74      6870825.71
      2685990.35      6870461.99
#Sta/Elev= 30
  4312.6  391.58  4440.4  389.18  4515.0  385.52  4530.7  383.42  4589.6  378.92
  4709.3  374.45  4737.9  371.79  4769.0  370.49  4858.5  368.71  4925.0  368.71
  4981.5  369.47  4989.1  368.64  4995.5  362.18  4995.8  361.68  4999.7  362.18
  5012.1  366.59  5018.5  370.25  5083.5  371.41  5104.4  373.24  5119.1  372.45
  5125.3  373.92  5197.0  378.63  5326.5  390.96  5341.2  391.39  5362.1  393.55
  5376.8  393.49  5382.9  395.02  5412.4  396.74  5427.1  396.71  5430.1  397.84
#Mann=4,-1,0
  4312.6    0.05       0  4925.0    0.12       0  4995.5    0.07       0
  4999.7    0.12       0
Bank Sta=4995.5,4999.7
Exp/Cntr=0.3,0.1

Type RM Length L Ch R = 1,277,0,0,0
BEGIN DESCRIPTION:
Walnut T1 1.0
END DESCRIPTION:
XS GIS Cut Line= 3
      2686350.99      6871186.02      2686565.49      6870762.22
      2686030.52      6870346.35
#Sta/Elev= 30
  4525.0  377.50  4681.0  369.79  4925.8  367.21  4970.6  367.67  4978.9  365.10
  4985.2  359.03  4985.5  358.53  4989.4  359.03  4997.9  367.89  5014.2  366.41
  5022.4  367.39  5028.7  364.30  5039.7  366.83  5043.2  368.34  5057.7  366.20
  5064.0  368.62  5093.0  366.76  5162.8  367.71  5178.0  368.96  5192.5  368.95
  5200.7  367.09  5207.1  367.75  5227.8  368.66  5285.9  374.72  5378.9  379.35
  5385.3  381.11  5399.8  380.31  5564.7  388.75  5643.0  392.36  5677.6  394.91
#Mann=10,-1,0
  4525.0    0.05       0  4925.8    0.12       0  4985.2    0.07       0
  4989.4    0.12       0  5039.7    0.05       0  5162.8    0.12       0
  5207.1    0.05       0  5285.9    0.12       0  5564.7    0.05       0
  5643.0    0.12       0
Bank Sta=4985.2,4989.4
Exp/Cntr=0.3,0.1

Chan Stop Cuts=-1