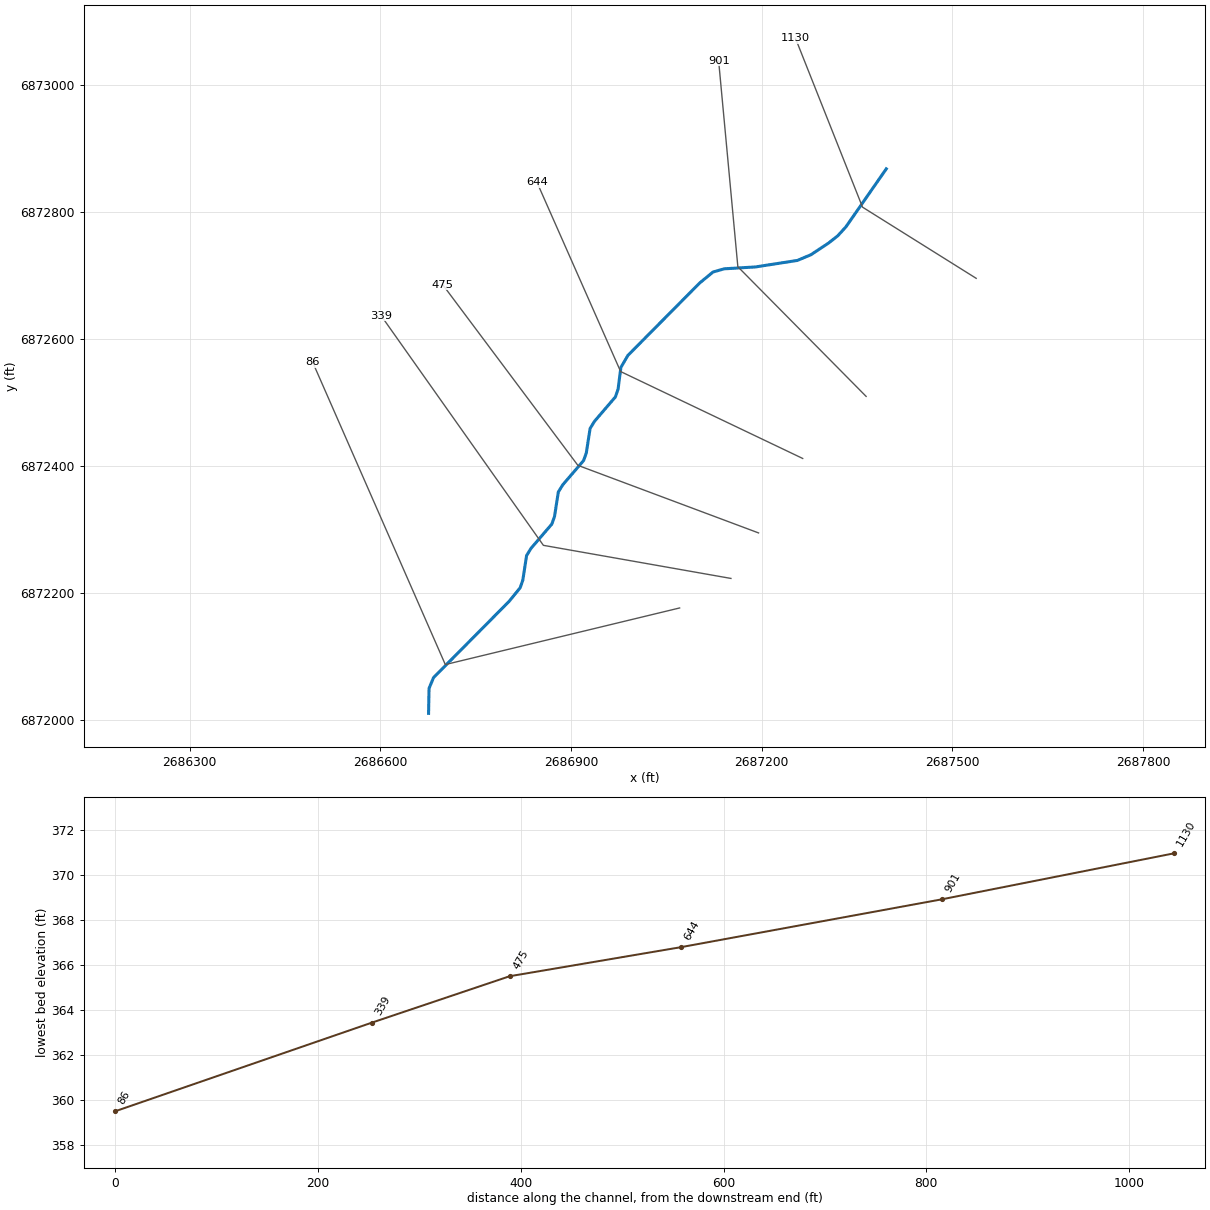
--- Walnut T2.prj (project) ---

Proj Title=Walnut T2 Base Level Engineering
Current Plan=p01
Default Exp/Contr=0.3,0.1
English Units
Geom File=g01
Flow File=f01
Plan File=p01
BEGIN DESCRIPTION:
Walnut T2
END DESCRIPTION:

--- Walnut T2.p01 (plan) ---

Plan Title=Multiple Run
Short Identifier=Multiple
Geom File=g01
Flow File=f01
Subcritical Flow
K Sum by GR= 0
Std Step Tol= 0.01
Critical Tol= 0.01
Num of Std Step Trials= 20
Max Error Tol= 0.3
Flow Tol Ratio= 0.001
Split Flow NTrial= 30
Split Flow Tol= 0.02
Split Flow Ratio= 0.02
Log Output Level= 0
Friction Slope Method= 1
Unsteady Friction Slope Method= 2
Unsteady Bridges Friction Slope Method= 1
Parabolic Critical Depth
Global Vel Dist=  1 , 1 , 1
Global Log Level= 0
CheckData=True
Encroach Param= -1, 0, 0, 0
BEGIN DESCRIPTION:
Multiple Run
END DESCRIPTION:

--- Walnut T2.f01 (steady flow) ---

Flow Title=Multiple
Number of Profiles=7
Profile Names=10-year,25-year,50-year,1pct_min,100-year,1pct_plu,500-year
River Rch & RM= Walnut T2,Reach-1,1130
     416     546     650     384     766    1529    1064
Boundary for River Rch & Prof#=Walnut T2,Reach-1,1
Up Type=0
Dn Type=3
Dn Slope=0.005
Boundary for River Rch & Prof#=Walnut T2,Reach-1,2
Up Type=0
Dn Type=3
Dn Slope=0.005
Boundary for River Rch & Prof#=Walnut T2,Reach-1,3
Up Type=0
Dn Type=3
Dn Slope=0.005
Boundary for River Rch & Prof#=Walnut T2,Reach-1,4
Up Type=0
Dn Type=3
Dn Slope=0.005
Boundary for River Rch & Prof#=Walnut T2,Reach-1,5
Up Type=0
Dn Type=3
Dn Slope=0.005
Boundary for River Rch & Prof#=Walnut T2,Reach-1,6
Up Type=0
Dn Type=3
Dn Slope=0.005
Boundary for River Rch & Prof#=Walnut T2,Reach-1,7
Up Type=0
Dn Type=3
Dn Slope=0.005

--- Walnut T2.g01 (geometry) ---

Geom Title=Existing Conditions

River Reach=Walnut T2,Reach-1
Reach XY= 30
      2687396.18      6872867.77      2687332.76      6872776.60
      2687319.99      6872762.58      2687305.23      6872750.94
      2687277.71      6872732.70      2687256.30      6872723.70
      2687190.12      6872713.42      2687141.17      6872710.50
      2687123.56      6872705.45      2687102.47      6872688.11
      2686989.62      6872574.22      2686978.61      6872555.37
      2686974.14      6872520.86      2686969.90      6872508.81
      2686937.08      6872470.55      2686930.16      6872459.28
      2686924.19      6872420.84      2686919.92      6872408.80
      2686887.08      6872370.55      2686880.16      6872359.28
      2686874.19      6872320.84      2686869.92      6872308.80
      2686837.10      6872270.54      2686830.19      6872259.26
      2686824.34      6872220.78      2686820.17      6872208.70
      2686802.99      6872187.53      2686683.76      6872067.21
      2686676.75      6872050.24      2686676.00      6872011.00

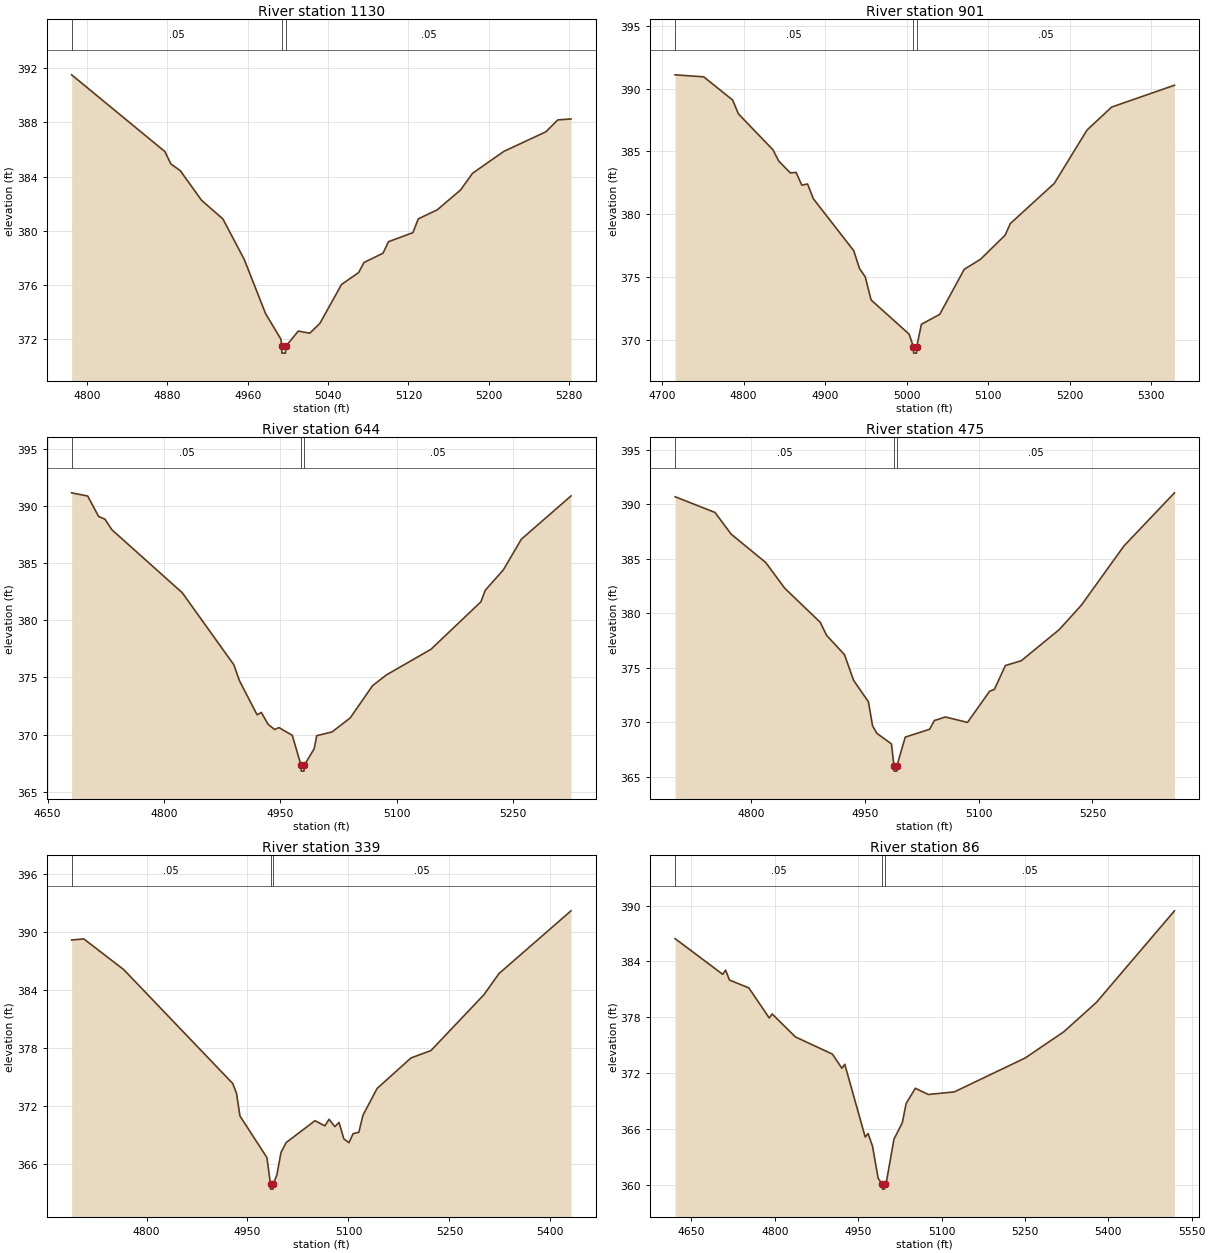
Type RM Length L Ch R = 1,1130,229,229,229
BEGIN DESCRIPTION:
Walnut T2 2.0
END DESCRIPTION:
XS GIS Cut Line= 3
      2687537.65      6872695.55      2687358.82      6872807.52
      2687253.36      6873073.16
#Sta/Elev= 30
  4784.9  391.52  4877.7  385.85  4883.6  384.94  4893.0  384.44  4914.2  382.25
  4935.4  380.87  4956.6  377.89  4977.9  373.87  4993.2  371.98  4993.9  371.46
  4994.1  370.96  4997.6  370.96  4997.9  371.46  5010.4  372.59  5021.8  372.43
  5031.9  373.16  5053.4  376.03  5070.4  376.91  5075.8  377.66  5094.7  378.34
  5100.1  379.19  5124.4  379.86  5129.8  380.88  5148.7  381.55  5171.8  383.01
  5183.8  384.25  5214.8  385.86  5256.7  387.31  5268.6  388.19  5281.7  388.26
#Mann=3,-1,0
  4784.9    0.05       0  4993.9    0.04       0  4997.9    0.05       0
Bank Sta=4993.9,4997.9
Exp/Cntr=0.3,0.1

Type RM Length L Ch R = 1,901,257,257,257
BEGIN DESCRIPTION:
Mapping XS 2d441eca
END DESCRIPTION:
XS GIS Cut Line= 3
      2687364.48      6872509.77      2687162.65      6872713.78
      2687132.42      6873037.69
#Sta/Elev= 30
  4716.0  391.11  4751.1  390.95  4786.5  389.10  4793.6  388.00  4836.0  385.13
  4843.1  384.23  4857.3  383.29  4864.3  383.33  4871.4  382.31  4878.4  382.41
  4885.5  381.23  4935.0  377.09  4942.1  375.67  4949.1  375.01  4956.3  373.16
  5003.0  370.43  5008.2  369.42  5008.5  368.92  5012.0  368.92  5012.2  369.42
  5018.0  371.22  5040.4  372.01  5070.5  375.60  5090.6  376.41  5120.7  378.33
  5127.0  379.25  5181.0  382.46  5221.1  386.71  5251.3  388.54  5328.3  390.28
#Mann=3,-1,0
  4716.0    0.05       0  5008.2    0.04       0  5012.2    0.05       0
Bank Sta=5008.2,5012.2
Exp/Cntr=0.3,0.1

Type RM Length L Ch R = 1,644,169,169,169
BEGIN DESCRIPTION:
Mapping XS b16c1b87
END DESCRIPTION:
XS GIS Cut Line= 3
      2687264.68      6872412.11      2686978.19      6872548.85
      2686846.33      6872847.15
#Sta/Elev= 30
  4680.9  391.14  4701.6  390.86  4715.7  389.07  4723.8  388.84  4732.8  387.91
  4823.5  382.40  4890.0  376.10  4897.2  374.71  4919.9  371.73  4925.4  371.93
  4934.3  370.88  4942.6  370.44  4948.1  370.61  4965.3  369.93  4976.6  367.30
  4976.9  366.80  4980.4  366.80  4980.6  367.30  4993.5  368.76  4996.8  369.90
  5016.6  370.23  5039.9  371.45  5068.7  374.27  5086.5  375.21  5144.1  377.46
  5208.4  381.61  5214.0  382.62  5237.3  384.40  5260.6  387.09  5324.5  390.87
#Mann=3,-1,0
  4680.9    0.05       0  4976.6    0.04       0  4980.6    0.05       0
Bank Sta=4976.6,4980.6
Exp/Cntr=0.3,0.1

Type RM Length L Ch R = 1,475,136,136,136
BEGIN DESCRIPTION:
Mapping XS 0f2df8e7
END DESCRIPTION:
XS GIS Cut Line= 3
      2687195.23      6872294.93      2686910.91      6872401.28
      2686698.23      6872685.57
#Sta/Elev= 30
  4699.6  390.69  4752.2  389.25  4773.5  387.26  4819.2  384.65  4844.1  382.30
  4891.0  379.17  4899.4  377.97  4923.0  376.20  4935.0  373.84  4954.6  371.87
  4960.0  369.67  4965.7  368.98  4984.9  368.01  4988.2  366.01  4988.5  365.51
  4992.0  365.51  4992.2  366.01  5003.1  368.63  5035.2  369.35  5041.5  370.15
  5056.0  370.48  5085.2  369.98  5114.4  372.84  5120.7  373.01  5135.2  375.20
  5156.1  375.64  5206.1  378.49  5235.3  380.73  5291.5  386.17  5358.2  391.05
#Mann=3,-1,0
  4699.6    0.05       0  4988.2    0.04       0  4992.2    0.05       0
Bank Sta=4988.2,4992.2
Exp/Cntr=0.3,0.1

Type RM Length L Ch R = 1,339,253,253,253
BEGIN DESCRIPTION:
Mapping XS 4edd6f71
END DESCRIPTION:
XS GIS Cut Line= 3
      2687151.78      6872223.33      2686856.66      6872275.41
      2686601.41      6872636.65
#Sta/Elev= 30
  4688.7  389.16  4706.9  389.27  4766.2  386.10  4928.1  374.35  4933.7  373.34
  4938.8  371.00  4978.9  366.70  4984.2  363.95  4984.4  363.45  4987.9  363.45
  4988.2  363.95  4993.7  364.93  4999.8  367.24  5007.5  368.26  5050.3  370.51
  5065.0  369.98  5071.2  370.66  5079.8  369.90  5086.0  370.33  5093.2  368.64
  5100.7  368.24  5106.9  369.17  5115.5  369.32  5121.6  371.08  5142.6  373.84
  5193.0  376.99  5222.6  377.75  5301.3  383.51  5323.6  385.69  5430.7  392.17
#Mann=3,-1,0
  4688.7    0.05       0  4984.2    0.04       0  4988.2    0.05       0
Bank Sta=4984.2,4988.2
Exp/Cntr=0.3,0.1

Type RM Length L Ch R = 1,86,0,0,0
BEGIN DESCRIPTION:
Walnut T2 1.0
END DESCRIPTION:
XS GIS Cut Line= 3
      2687071.04      6872176.88      2686702.35      6872087.80
      2686493.81      6872563.17
#Sta/Elev= 30
  4620.7  386.44  4706.3  382.61  4711.5  383.06  4718.5  381.99  4753.3  381.15
  4790.1  377.91  4795.2  378.35  4837.1  375.88  4903.7  374.03  4920.8  372.51
  4925.9  372.94  4962.7  365.12  4967.8  365.49  4975.7  364.17  4986.0  360.69
  4993.6  360.02  4993.8  359.52  4997.3  359.52  4997.6  360.02  5000.0  360.02
  5014.4  364.88  5029.5  366.66  5036.3  368.72  5052.9  370.36  5076.3  369.69
  5123.0  369.97  5250.7  373.62  5320.2  376.44  5378.5  379.58  5519.1  389.43
#Mann=3,-1,0
  4620.7    0.05       0  4993.6    0.04       0  4997.6    0.05       0
Bank Sta=4993.6,4997.6
Exp/Cntr=0.3,0.1

Chan Stop Cuts=-1