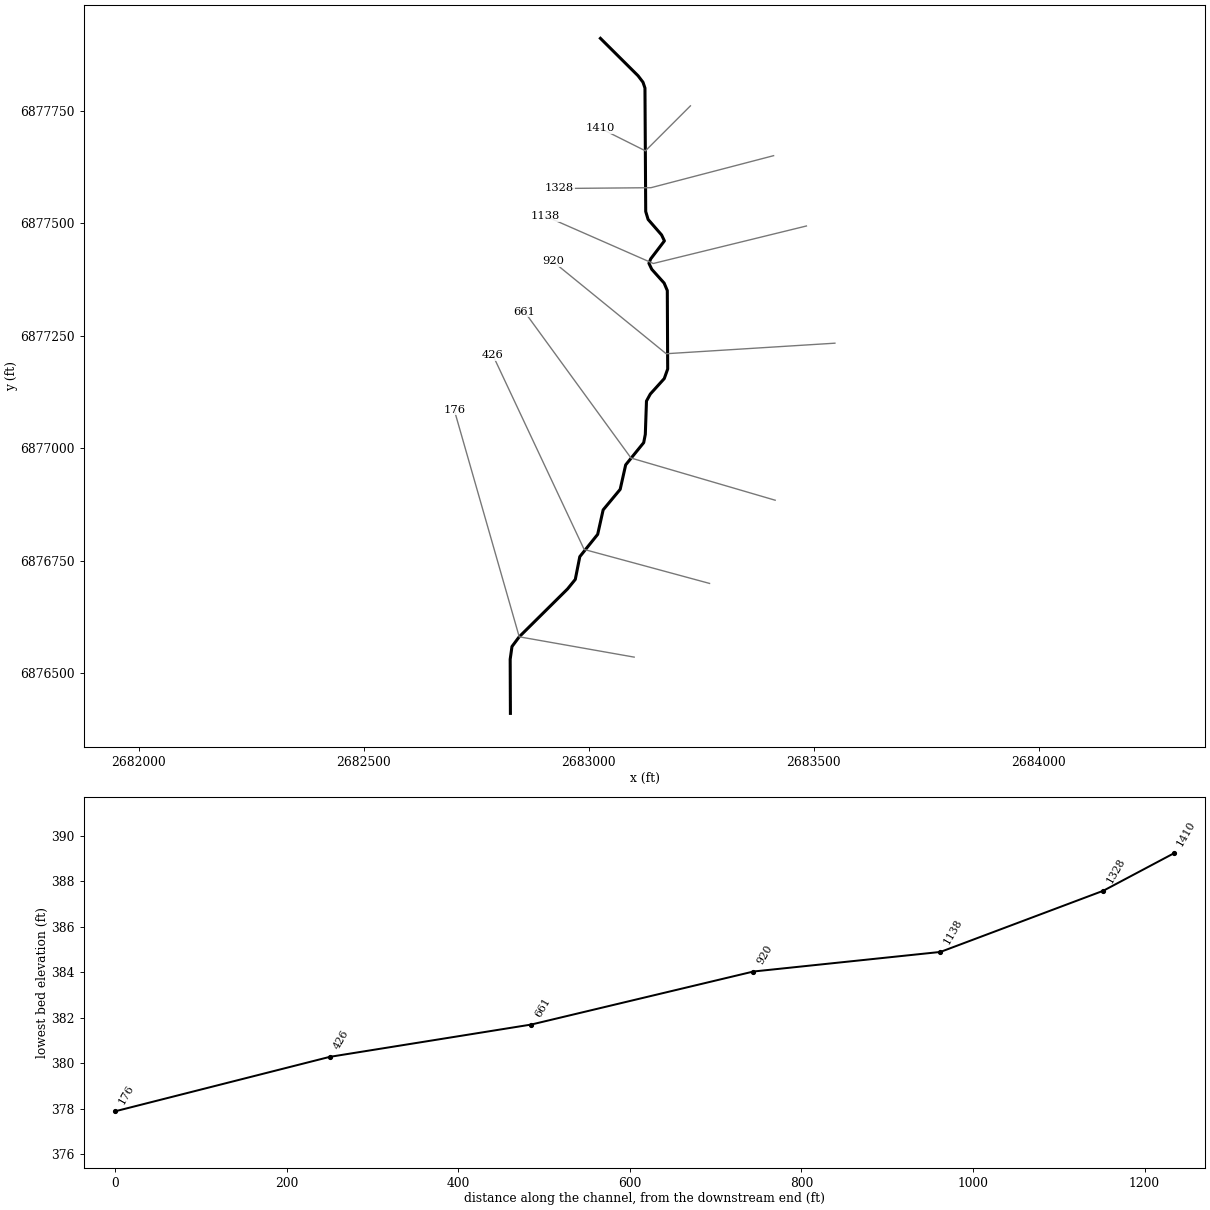
--- Walnut T3.prj (project) ---

Proj Title=Walnut T3 Base Level Engineering
Current Plan=p01
Default Exp/Contr=0.3,0.1
English Units
Geom File=g01
Flow File=f01
Plan File=p01
BEGIN DESCRIPTION:
Walnut T3
END DESCRIPTION:

--- Walnut T3.p01 (plan) ---

Plan Title=Multiple Run
Short Identifier=Multiple
Geom File=g01
Flow File=f01
Subcritical Flow
K Sum by GR= 0
Std Step Tol= 0.01
Critical Tol= 0.01
Num of Std Step Trials= 20
Max Error Tol= 0.3
Flow Tol Ratio= 0.001
Split Flow NTrial= 30
Split Flow Tol= 0.02
Split Flow Ratio= 0.02
Log Output Level= 0
Friction Slope Method= 1
Unsteady Friction Slope Method= 2
Unsteady Bridges Friction Slope Method= 1
Parabolic Critical Depth
Global Vel Dist=  1 , 1 , 1
Global Log Level= 0
CheckData=True
Encroach Param= -1, 0, 0, 0
BEGIN DESCRIPTION:
Multiple Run
END DESCRIPTION:

--- Walnut T3.f01 (steady flow) ---

Flow Title=Multiple
Number of Profiles=7
Profile Names=10-year,25-year,50-year,1pct_min,100-year,1pct_plu,500-year
River Rch & RM= Walnut T3,Reach-1,1410
     190     237     273     157     312     623     407
Boundary for River Rch & Prof#=Walnut T3,Reach-1,1
Up Type=0
Dn Type=3
Dn Slope=0.005
Boundary for River Rch & Prof#=Walnut T3,Reach-1,2
Up Type=0
Dn Type=3
Dn Slope=0.005
Boundary for River Rch & Prof#=Walnut T3,Reach-1,3
Up Type=0
Dn Type=3
Dn Slope=0.005
Boundary for River Rch & Prof#=Walnut T3,Reach-1,4
Up Type=0
Dn Type=3
Dn Slope=0.005
Boundary for River Rch & Prof#=Walnut T3,Reach-1,5
Up Type=0
Dn Type=3
Dn Slope=0.005
Boundary for River Rch & Prof#=Walnut T3,Reach-1,6
Up Type=0
Dn Type=3
Dn Slope=0.005
Boundary for River Rch & Prof#=Walnut T3,Reach-1,7
Up Type=0
Dn Type=3
Dn Slope=0.005

--- Walnut T3.g01 (geometry) ---

Geom Title=Existing Conditions

River Reach=Walnut T3,Reach-1
Reach XY= 30
      2683026.00      6877911.00      2683109.67      6877827.81
      2683120.60      6877813.48      2683124.98      6877800.58
      2683126.65      6877526.16      2683132.00      6877508.55
      2683161.93      6877474.16      2683168.21      6877460.90
      2683137.83      6877421.05      2683133.79      6877411.10
      2683140.07      6877397.84      2683167.56      6877367.19
      2683174.63      6877350.57      2683175.48      6877176.22
      2683167.86      6877154.94      2683136.89      6877120.63
      2683128.36      6877105.02      2683125.77      6877031.09
      2683122.17      6877012.58      2683082.12      6876963.18
      2683069.92      6876908.80      2683032.08      6876863.20
      2683019.92      6876808.80      2682980.19      6876759.26
      2682970.17      6876708.70      2682952.99      6876687.53
      2682845.60      6876581.16      2682829.50      6876559.55
      2682825.48      6876531.21      2682826.00      6876411.00

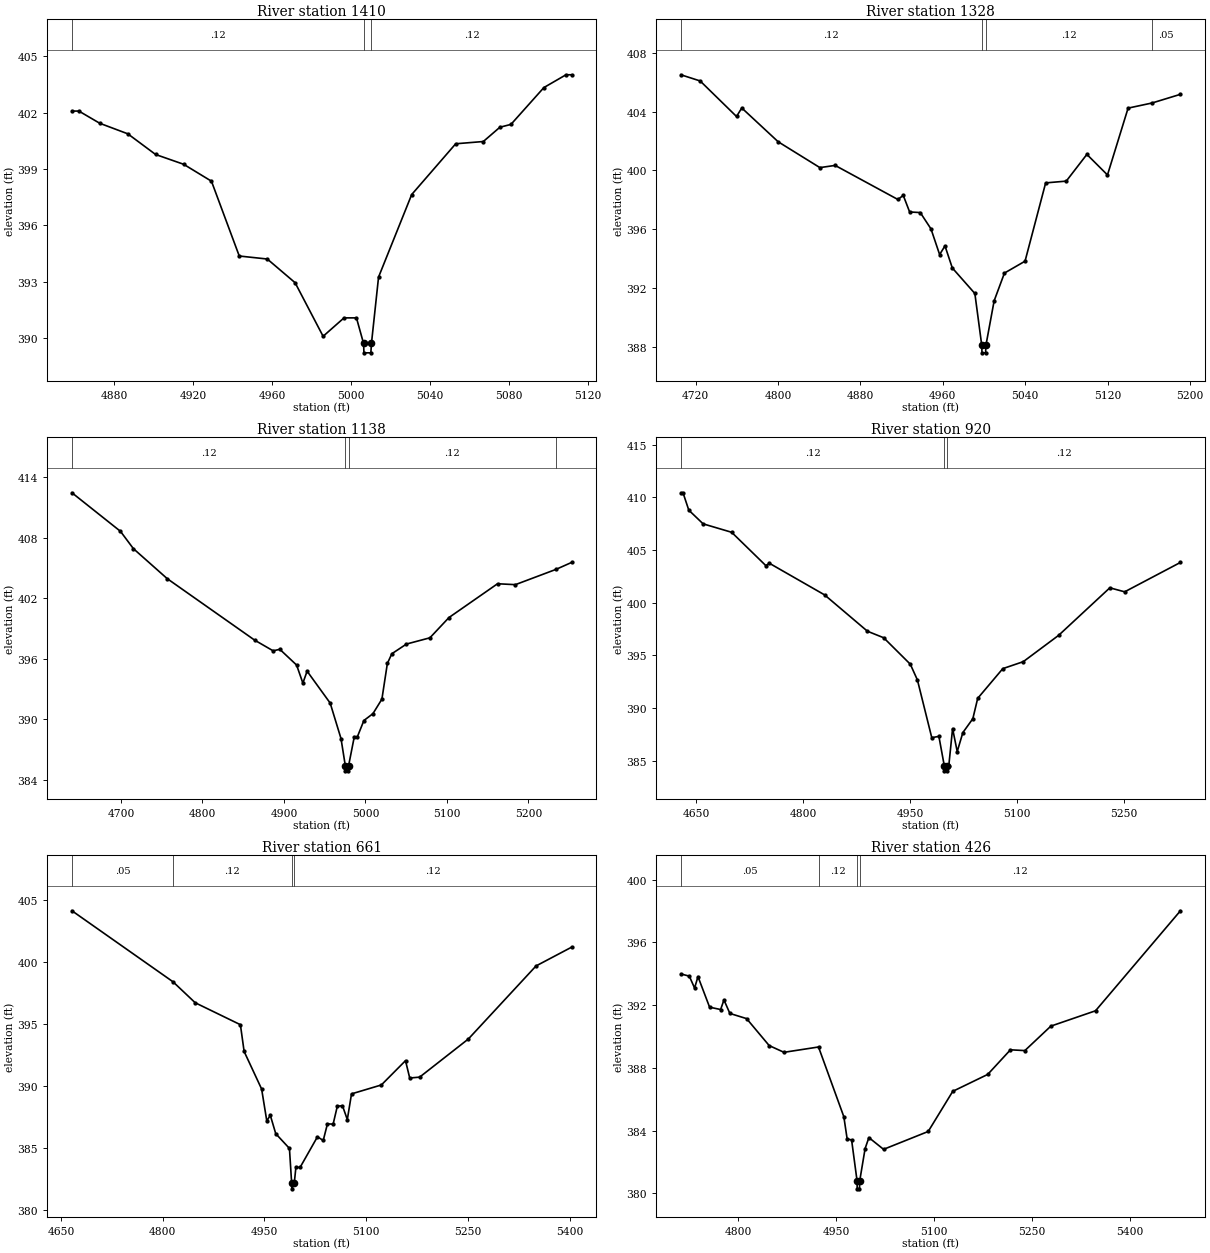
Type RM Length L Ch R = 1,1410,82,82,82
BEGIN DESCRIPTION:
Walnut T3 2.0
END DESCRIPTION:
XS GIS Cut Line= 3
      2683225.99      6877760.99      2683126.00      6877661.00
      2683026.01      6877710.99
#Sta/Elev= 26
  4858.6  402.08  4862.1  402.08  4872.7  401.43  4886.9  400.87  4901.0  399.77
  4915.2  399.25  4929.3  398.35  4943.4  394.37  4957.6  394.21  4971.7  392.95
  4985.9  390.10  4996.5  391.08  5002.8  391.08  5006.4  389.72  5006.6  389.22
  5010.1  389.22  5010.4  389.72  5014.0  393.25  5030.8  397.64  5053.1  400.34
  5067.1  400.46  5075.5  401.22  5081.1  401.37  5097.8  403.33  5109.0  404.01
  5111.8  404.01
#Mann=3,-1,0
  4858.6    0.12       0  5006.4    0.07       0  5010.4    0.12       0
Bank Sta=5006.4,5010.4
Exp/Cntr=0.3,0.1

Type RM Length L Ch R = 1,1328,190,190,190
BEGIN DESCRIPTION:
Mapping XS 2542b52d
END DESCRIPTION:
XS GIS Cut Line= 3
      2683410.81      6877650.27      2683138.27      6877579.09
      2682935.16      6877577.36
#Sta/Elev= 30
  4705.8  406.51  4724.5  406.09  4759.8  403.67  4764.9  404.25  4800.2  401.95
  4840.7  400.19  4855.5  400.34  4916.4  398.02  4921.6  398.30  4927.8  397.17
  4938.1  397.13  4948.5  396.02  4956.9  394.27  4962.1  394.86  4969.2  393.36
  4991.1  391.62  4997.8  388.08  4998.0  387.58  5001.5  387.58  5001.8  388.08
  5009.8  391.12  5019.8  393.01  5039.8  393.82  5059.8  399.15  5079.8  399.27
  5099.8  401.09  5119.8  399.69  5139.8  404.24  5163.1  404.59  5190.6  405.18
#Mann=4,-1,0
  4705.8    0.12       0  4997.8    0.07       0  5001.8    0.12       0
  5163.1    0.05       0
Bank Sta=4997.8,5001.8
Exp/Cntr=0.3,0.1

Type RM Length L Ch R = 1,1138,218,218,218
BEGIN DESCRIPTION:
Mapping XS b93c87ba
END DESCRIPTION:
XS GIS Cut Line= 3
      2683483.77      6877494.03      2683143.47      6877410.69
      2682902.87      6877516.28
#Sta/Elev= 30
  4639.8  412.46  4699.3  408.64  4715.2  406.92  4756.8  403.94  4864.0  397.85
  4886.7  396.79  4894.9  396.94  4915.5  395.38  4923.2  393.59  4928.4  394.77
  4956.7  391.61  4970.0  388.09  4975.3  385.39  4975.5  384.89  4979.0  384.89
  4979.3  385.39  4986.3  388.27  4990.1  388.27  4998.1  389.88  5009.2  390.56
  5020.2  392.00  5026.9  395.54  5032.4  396.50  5050.3  397.46  5079.1  398.08
  5102.5  400.09  5162.1  403.44  5184.0  403.35  5233.7  404.86  5252.9  405.55
#Mann=4,-1,0
  4639.8    0.12       0  4975.3    0.07       0  4979.3    0.12       0
  5233.7    0.05       0
Bank Sta=4975.3,4979.3
Exp/Cntr=0.3,0.1

Type RM Length L Ch R = 1,920,259,259,259
BEGIN DESCRIPTION:
Mapping XS 06cc9d45
END DESCRIPTION:
XS GIS Cut Line= 3
      2683547.09      6877233.60      2683172.12      6877210.17
      2682920.28      6877415.28
#Sta/Elev= 30
  4628.6  410.42  4631.6  410.42  4639.7  408.77  4659.8  407.47  4699.8  406.67
  4747.7  403.51  4752.7  403.73  4830.1  400.73  4890.2  397.28  4913.0  396.66
  4950.3  394.15  4960.3  392.65  4980.4  387.18  4990.4  387.30  4997.9  384.53
  4998.1  384.03  5001.6  384.03  5001.9  384.53  5004.3  384.53  5009.6  388.04
  5016.1  385.86  5024.0  387.66  5038.0  388.98  5044.8  390.91  5080.0  393.73
  5108.7  394.39  5158.3  396.89  5230.1  401.40  5250.9  401.02  5329.1  403.81
#Mann=3,-1,0
  4628.6    0.12       0  4997.9    0.07       0  5001.9    0.12       0
Bank Sta=4997.9,5001.9
Exp/Cntr=0.3,0.1

Type RM Length L Ch R = 1,661,235,235,235
BEGIN DESCRIPTION:
Mapping XS 2b3a6de5
END DESCRIPTION:
XS GIS Cut Line= 3
      2683414.32      6876884.65      2683094.00      6876978.40
      2682857.02      6877303.91
#Sta/Elev= 30
  4666.2  404.13  4815.2  398.40  4847.9  396.71  4914.5  394.94  4920.0  392.78
  4945.8  389.75  4953.4  387.18  4958.6  387.63  4966.6  386.15  4986.8  384.96
  4990.0  382.20  4990.3  381.70  4994.0  382.20  4996.3  383.43  5002.5  383.43
  5028.1  385.90  5036.6  385.60  5042.8  386.94  5051.2  386.92  5057.4  388.37
  5065.0  388.40  5072.1  387.29  5078.3  389.36  5122.3  390.08  5157.9  392.04
  5164.1  390.64  5178.7  390.71  5250.6  393.79  5350.3  399.68  5402.6  401.19
#Mann=4,-1,0
  4666.2    0.05       0  4815.2    0.12       0  4990.0    0.07       0
  4994.0    0.12       0
Bank Sta=4990,4994
Exp/Cntr=0.3,0.1

Type RM Length L Ch R = 1,426,250,250,250
BEGIN DESCRIPTION:
Mapping XS c26baae0
END DESCRIPTION:
XS GIS Cut Line= 3
      2683268.50      6876699.75      2682989.83      6876775.27
      2682787.07      6877206.79
#Sta/Elev= 30
  4712.3  393.99  4725.2  393.85  4733.3  393.09  4738.5  393.82  4756.3  391.87
  4773.2  391.72  4778.3  392.33  4787.4  391.47  4813.0  391.14  4847.6  389.42
  4870.3  388.99  4923.2  389.33  4962.0  384.88  4967.1  383.46  4973.9  383.40
  4982.3  380.78  4982.5  380.28  4986.0  380.28  4986.3  380.78  4994.6  382.85
  5000.4  383.55  5022.9  382.80  5091.3  383.94  5128.9  386.50  5182.5  387.58
  5217.3  389.15  5239.4  389.10  5279.2  390.66  5347.7  391.64  5477.8  398.02
#Mann=4,-1,0
  4712.3    0.05       0  4923.2    0.12       0  4982.3    0.07       0
  4986.3    0.12       0
Bank Sta=4982.3,4986.3
Exp/Cntr=0.3,0.1

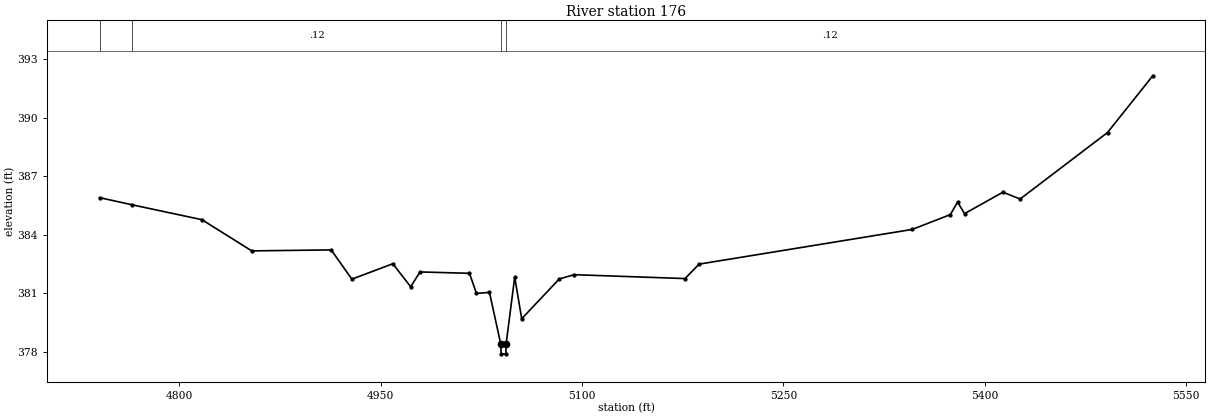
Type RM Length L Ch R = 1,176,0,0,0
BEGIN DESCRIPTION:
Walnut T3 1.0
END DESCRIPTION:
XS GIS Cut Line= 3
      2683101.04      6876535.99      2682845.60      6876581.16
      2682701.01      6877085.96
#Sta/Elev= 30
  4740.6  385.90  4765.0  385.53  4816.8  384.77  4853.9  383.17  4913.1  383.22
  4928.5  381.72  4959.0  382.51  4972.3  381.33  4979.3  382.09  5016.1  382.02
  5021.3  380.99  5031.0  381.04  5039.4  378.39  5039.7  377.89  5043.2  377.89
  5043.4  378.39  5049.8  381.83  5055.0  379.69  5083.0  381.73  5094.0  381.95
  5176.7  381.75  5187.1  382.49  5345.9  384.27  5374.3  385.03  5379.7  385.67
  5384.9  385.08  5413.5  386.18  5426.3  385.83  5491.4  389.24  5525.1  392.15
#Mann=4,-1,0
  4740.6    0.05       0  4765.0    0.12       0  5039.4    0.07       0
  5043.4    0.12       0
Bank Sta=5039.4,5043.4
Exp/Cntr=0.3,0.1

Chan Stop Cuts=-1