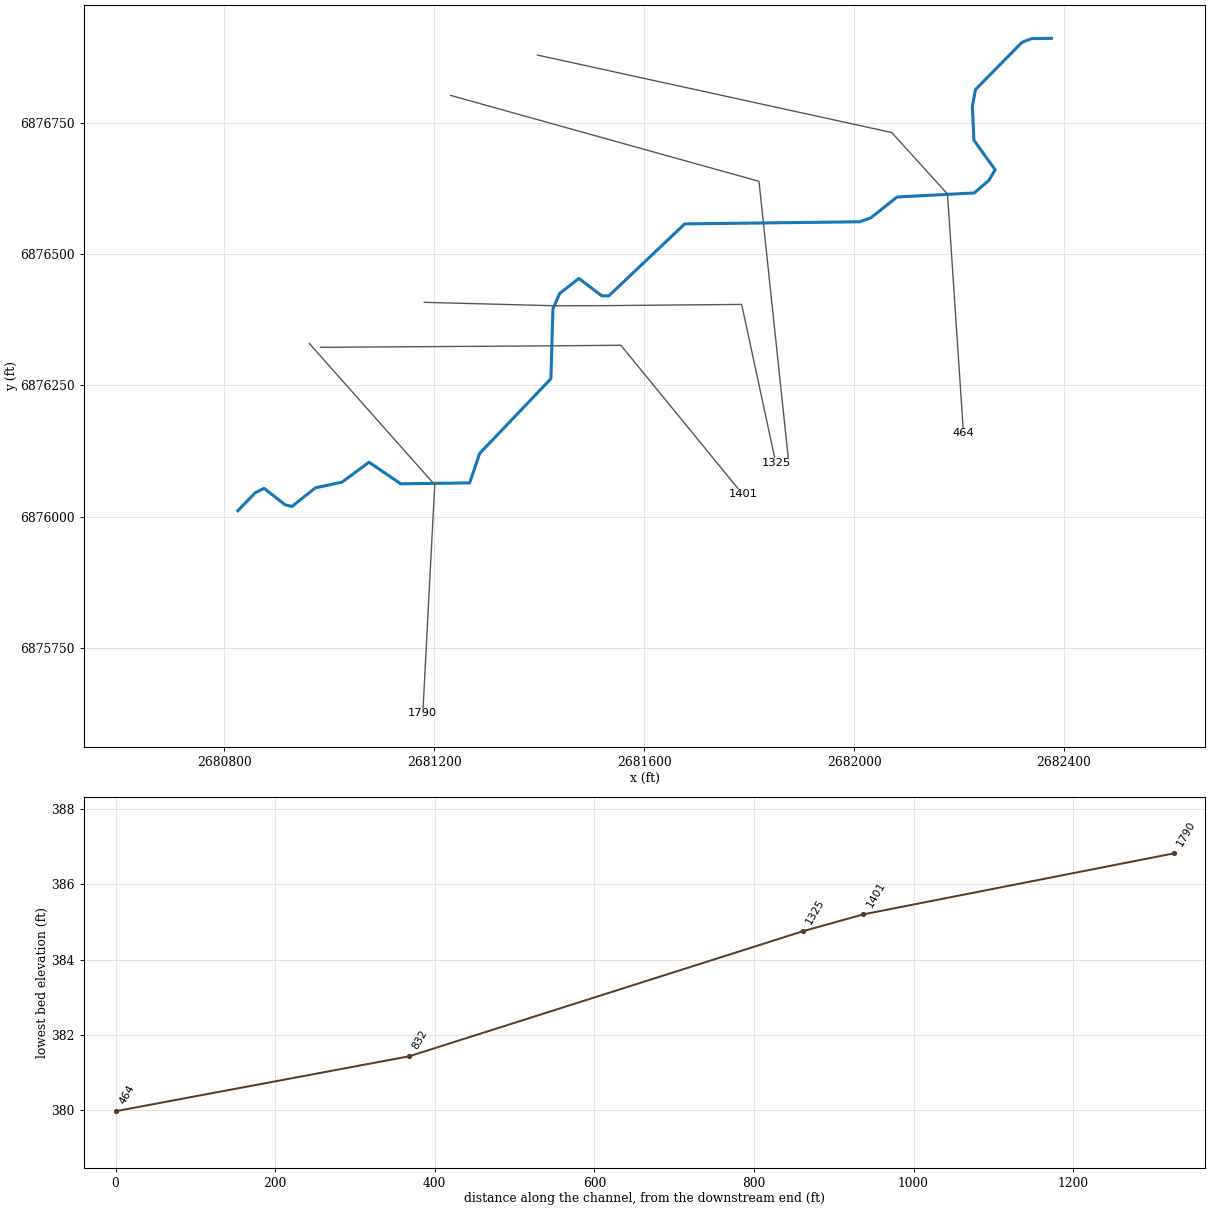
--- Walnut T4.prj (project) ---

Proj Title=Walnut T4 Base Level Engineering
Current Plan=p01
Default Exp/Contr=0.3,0.1
English Units
Geom File=g01
Flow File=f01
Plan File=p01
BEGIN DESCRIPTION:
Walnut T4
END DESCRIPTION:

--- Walnut T4.p01 (plan) ---

Plan Title=Multiple Run
Short Identifier=Multiple
Geom File=g01
Flow File=f01
Subcritical Flow
K Sum by GR= 0
Std Step Tol= 0.01
Critical Tol= 0.01
Num of Std Step Trials= 20
Max Error Tol= 0.3
Flow Tol Ratio= 0.001
Split Flow NTrial= 30
Split Flow Tol= 0.02
Split Flow Ratio= 0.02
Log Output Level= 0
Friction Slope Method= 1
Unsteady Friction Slope Method= 2
Unsteady Bridges Friction Slope Method= 1
Parabolic Critical Depth
Global Vel Dist=  1 , 1 , 1
Global Log Level= 0
CheckData=True
Encroach Param= -1, 0, 0, 0
BEGIN DESCRIPTION:
Multiple Run
END DESCRIPTION:

--- Walnut T4.f01 (steady flow) ---

Flow Title=Multiple
Number of Profiles=7
Profile Names=10-year,25-year,50-year,1pct_min,100-year,1pct_plu,500-year
River Rch & RM= Walnut T4,Reach-1,1790
     522     700     844     506    1010    2014    1442
Boundary for River Rch & Prof#=Walnut T4,Reach-1,1
Up Type=0
Dn Type=3
Dn Slope=0.005
Boundary for River Rch & Prof#=Walnut T4,Reach-1,2
Up Type=0
Dn Type=3
Dn Slope=0.005
Boundary for River Rch & Prof#=Walnut T4,Reach-1,3
Up Type=0
Dn Type=3
Dn Slope=0.005
Boundary for River Rch & Prof#=Walnut T4,Reach-1,4
Up Type=0
Dn Type=3
Dn Slope=0.005
Boundary for River Rch & Prof#=Walnut T4,Reach-1,5
Up Type=0
Dn Type=3
Dn Slope=0.005
Boundary for River Rch & Prof#=Walnut T4,Reach-1,6
Up Type=0
Dn Type=3
Dn Slope=0.005
Boundary for River Rch & Prof#=Walnut T4,Reach-1,7
Up Type=0
Dn Type=3
Dn Slope=0.005

--- Walnut T4.g01 (geometry) ---

Geom Title=Existing Conditions

River Reach=Walnut T4,Reach-1
Reach XY= 30
      2680826.00      6876011.00      2680859.22      6876045.31
      2680875.99      6876053.77      2680915.94      6876022.55
      2680929.23      6876019.12      2680973.71      6876054.66
      2681024.35      6876065.39      2681075.99      6876103.47
      2681136.45      6876062.37      2681267.69      6876064.06
      2681286.91      6876120.37      2681422.46      6876262.47
      2681426.40      6876396.11      2681439.37      6876425.10
      2681475.75      6876453.54      2681519.31      6876420.62
      2681532.66      6876420.31      2681677.46      6876557.46
      2682010.78      6876561.52      2682032.06      6876569.14
      2682081.94      6876608.73      2682229.01      6876616.46
      2682256.91      6876640.47      2682268.78      6876660.65
      2682228.37      6876716.88      2682225.34      6876781.08
      2682231.38      6876813.44      2682319.76      6876903.25
      2682337.83      6876910.41      2682376.00      6876911.00

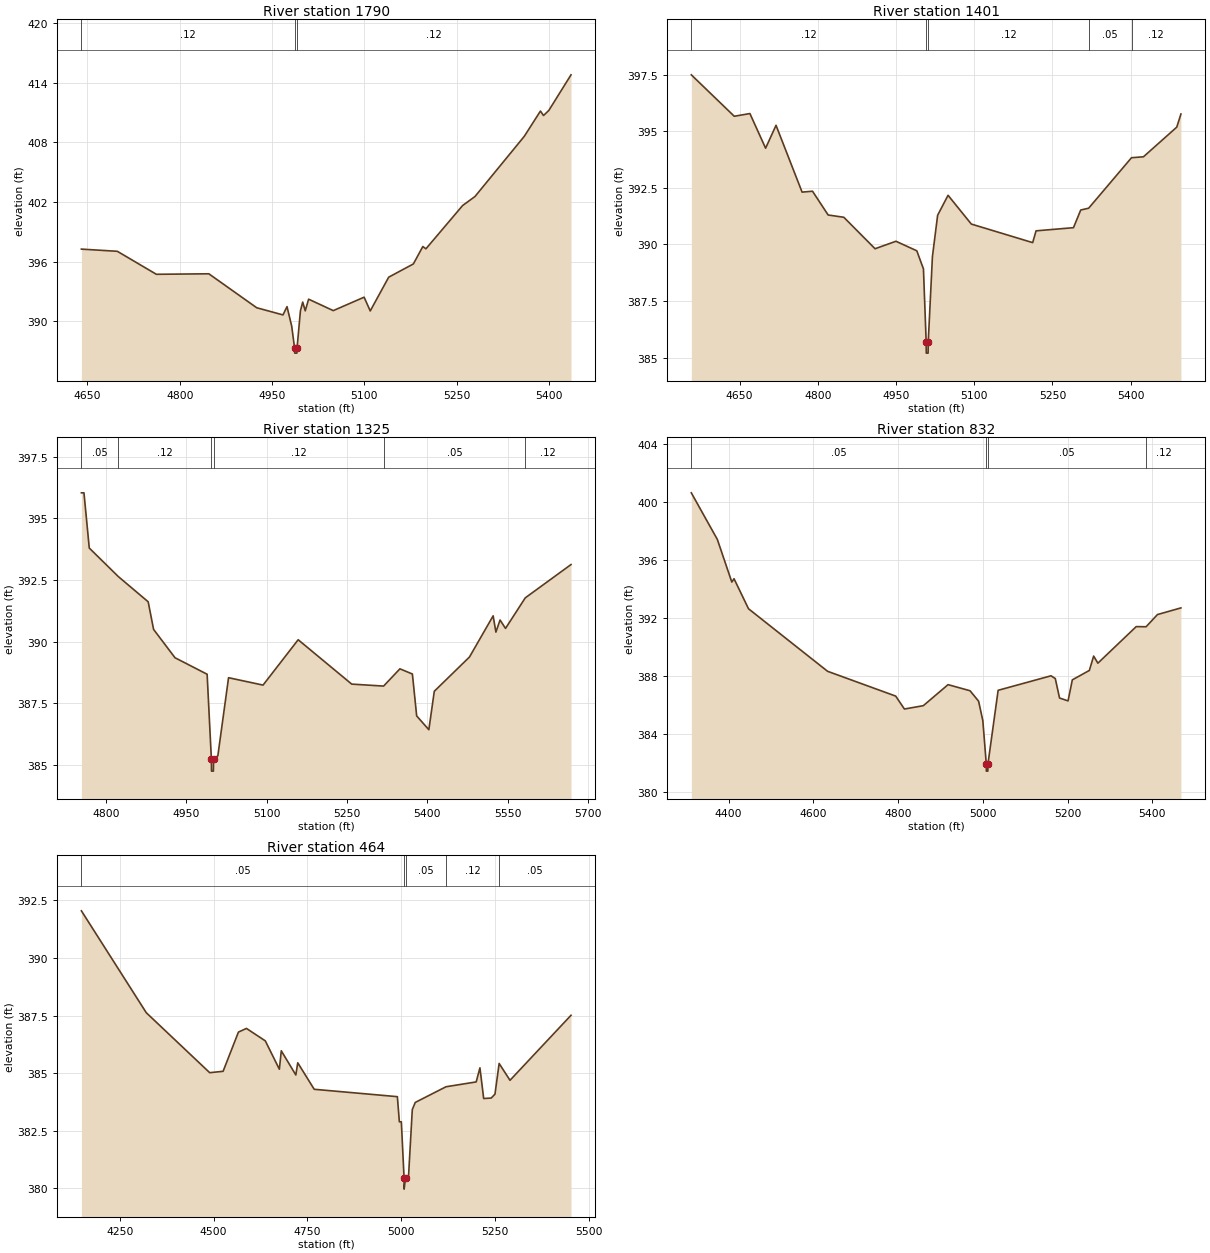
Type RM Length L Ch R = 1,1790,389,389,389
BEGIN DESCRIPTION:
Walnut T4 3.0
END DESCRIPTION:
XS GIS Cut Line= 3
      2680962.27      6876329.68      2681201.19      6876060.52
      2681178.48      6875625.01
#Sta/Elev= 30
  4640.1  397.27  4698.5  397.05  4762.0  394.74  4847.3  394.79  4925.1  391.38
  4967.8  390.66  4974.4  391.49  4982.0  389.53  4986.7  387.32  4986.9  386.82
  4990.4  386.82  4990.7  387.32  4996.2  391.07  4999.9  391.95  5004.0  391.07
  5009.5  392.24  5049.6  391.09  5099.7  392.44  5109.7  391.06  5139.7  394.45
  5179.8  395.78  5195.2  397.53  5200.2  397.30  5259.9  401.65  5279.9  402.55
  5360.0  408.59  5386.4  411.14  5391.4  410.69  5400.1  411.21  5436.1  414.78
#Mann=3,-1,0
  4640.1    0.12       0  4986.7    0.07       0  4990.7    0.12       0
Bank Sta=4986.7,4990.7
Exp/Cntr=0.3,0.1

Type RM Length L Ch R = 1,1401,76,76,76
BEGIN DESCRIPTION:
Mapping XS 778b197d
END DESCRIPTION:
XS GIS Cut Line= 4
      2680983.55      6876322.37      2681426.67      6876325.19
      2681555.77      6876326.30      2681788.03      6876042.19
#Sta/Elev= 30
  4557.4  397.49  4639.8  395.66  4669.8  395.78  4699.9  394.25  4719.9  395.26
  4769.9  392.31  4789.9  392.35  4819.9  391.30  4849.9  391.20  4909.9  389.81
  4949.9  390.14  4989.9  389.72  5002.7  388.92  5007.9  385.70  5008.1  385.20
  5011.6  385.20  5011.9  385.70  5019.9  389.46  5029.9  391.29  5049.9  392.17
  5094.5  390.90  5212.2  390.08  5218.7  390.60  5290.5  390.74  5304.4  391.52
  5319.6  391.60  5401.8  393.83  5424.7  393.87  5488.6  395.18  5496.6  395.76
#Mann=5,-1,0
  4557.4    0.12       0  5007.9    0.07       0  5011.9    0.12       0
  5319.6    0.05       0  5401.8    0.12       0
Bank Sta=5007.9,5011.9
Exp/Cntr=0.3,0.1

Type RM Length L Ch R = 1,1325,493,493,493
BEGIN DESCRIPTION:
Mapping XS c1b09457
END DESCRIPTION:
XS GIS Cut Line= 5
      2681181.30      6876408.11      2681430.86      6876401.48
      2681520.36      6876401.72      2681785.90      6876404.11
      2681851.13      6876101.46
#Sta/Elev= 30
  4754.0  396.04  4758.8  396.04  4768.7  393.80  4823.1  392.64  4878.7  391.62
  4888.8  390.50  4928.8  389.35  4988.8  388.68  4996.7  385.25  4997.0  384.75
  5000.5  384.75  5000.7  385.25  5008.8  385.37  5028.8  388.54  5093.2  388.24
  5158.8  390.08  5258.8  388.28  5318.3  388.20  5348.8  388.90  5372.1  388.69
  5380.1  386.99  5402.8  386.43  5413.0  387.99  5478.7  389.38  5522.9  391.05
  5528.0  390.39  5535.8  390.88  5546.0  390.54  5582.9  391.78  5668.3  393.13
#Mann=6,-1,0
  4754.0    0.05       0  4823.1    0.12       0  4996.7    0.07       0
  5000.7    0.12       0  5318.3    0.05       0  5582.9    0.12       0
Bank Sta=4996.7,5000.7
Exp/Cntr=0.3,0.1

Type RM Length L Ch R = 1,832,368,368,368
BEGIN DESCRIPTION:
Mapping XS 5f49afba
END DESCRIPTION:
XS GIS Cut Line= 3
      2681231.29      6876802.31      2681818.89      6876638.61
      2681876.33      6876096.11
#Sta/Elev= 30
  4312.0  400.61  4373.4  397.40  4407.6  394.46  4412.8  394.69  4447.0  392.62
  4633.6  388.31  4794.4  386.60  4814.9  385.71  4859.5  385.94  4917.9  387.39
  4969.8  386.97  4990.0  386.25  5000.0  384.91  5008.1  381.93  5008.3  381.43
  5011.8  381.43  5012.1  381.93  5036.1  387.00  5160.9  388.00  5171.0  387.81
  5181.0  386.47  5201.1  386.27  5211.2  387.72  5251.4  388.37  5261.5  389.36
  5271.5  388.87  5362.0  391.39  5385.3  391.38  5412.1  392.22  5467.5  392.68
#Mann=4,-1,0
  4312.0    0.05       0  5008.1    0.03       0  5012.1    0.05       0
  5385.3    0.12       0
Bank Sta=5008.1,5012.1
Exp/Cntr=0.3,0.1

Type RM Length L Ch R = 1,464,0,0,0
BEGIN DESCRIPTION:
Mapping XS a0351126
END DESCRIPTION:
XS GIS Cut Line= 4
      2681396.86      6876879.14      2682071.73      6876731.58
      2682178.06      6876614.39      2682208.44      6876158.65
#Sta/Elev= 30
  4147.2  392.04  4320.3  387.62  4489.4  385.02  4525.1  385.08  4566.0  386.78
  4587.4  386.94  4637.7  386.40  4675.2  385.17  4680.3  385.97  4719.1  384.92
  4724.2  385.45  4768.1  384.30  4989.9  383.98  4995.2  382.89  5000.5  382.89
  5007.7  380.47  5007.9  379.97  5011.7  380.47  5019.7  380.54  5029.7  383.42
  5037.6  383.73  5119.7  384.41  5200.1  384.62  5210.1  385.23  5220.1  383.90
  5240.2  383.92  5250.2  384.09  5261.3  385.42  5290.3  384.69  5453.0  387.51
#Mann=5,-1,0
  4147.2    0.05       0  5007.7    0.03       0  5011.7    0.05       0
  5119.7    0.12       0  5261.3    0.05       0
Bank Sta=5007.7,5011.7
Exp/Cntr=0.3,0.1

Chan Stop Cuts=-1