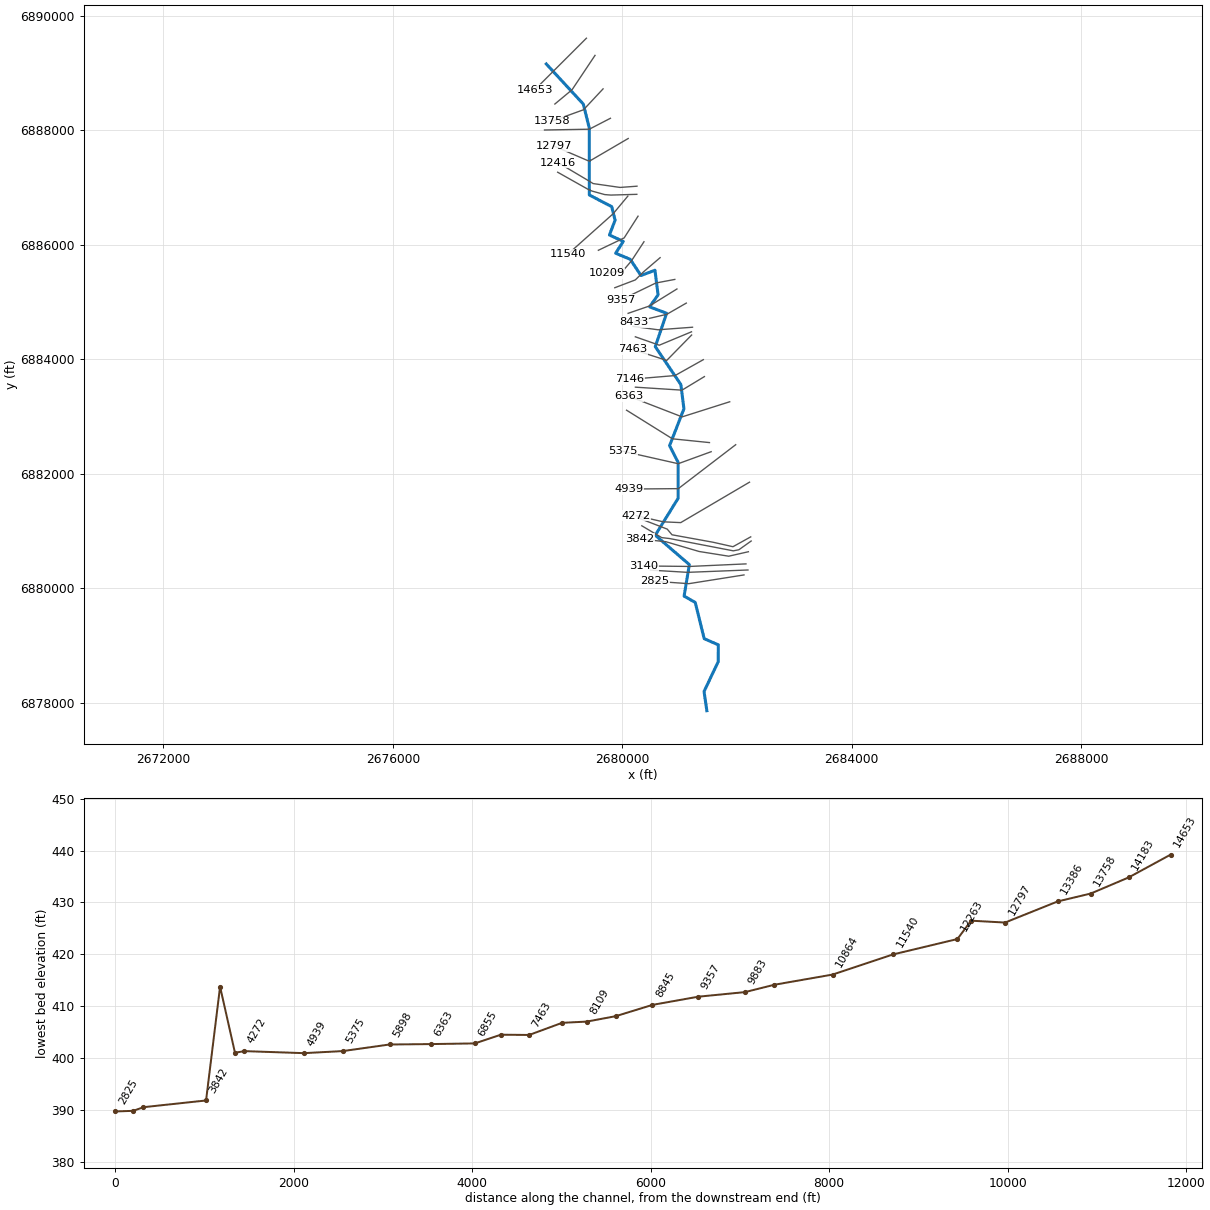
--- Walnut T5.prj (project) ---

Proj Title=Walnut T5 Base Level Engineering
Current Plan=p01
Default Exp/Contr=0.3,0.1
English Units
Geom File=g01
Flow File=f01
Plan File=p01
Y Axis Title=Elevation
X Axis Title(PF)=Main Channel Distance
X Axis Title(XS)=Station
BEGIN DESCRIPTION:
Walnut T5
END DESCRIPTION:
DSS Export Rating Curves= 0
DSS Export Rating Curve Sorted= 0
DSS Export Volume Flow Curves= 0
DXF OffsetX= 0
DXF OffsetY= 0
DXF ScaleX= 1
DXF ScaleY= 10

--- Walnut T5.p01 (plan) ---

Plan Title=Multiple Run
Short Identifier=Multiple
Geom File=g01
Flow File=f01
Subcritical Flow
K Sum by GR= 0
Std Step Tol= 0.01
Critical Tol= 0.01
Num of Std Step Trials= 20
Max Error Tol= 0.3
Flow Tol Ratio= 0.001
Split Flow NTrial= 30
Split Flow Tol= 0.02
Split Flow Ratio= 0.02
Log Output Level= 0
Friction Slope Method= 1
Unsteady Friction Slope Method= 2
Unsteady Bridges Friction Slope Method= 1
Parabolic Critical Depth
Global Vel Dist=  1 , 1 , 1
Global Log Level= 0
CheckData=True
Encroach Param= -1, 0, 0, 0
BEGIN DESCRIPTION:
Multiple Run
END DESCRIPTION:

--- Walnut T5.f01 (steady flow) ---

Flow Title=Multiple
Number of Profiles=7
Profile Names=10-year,25-year,50-year,1pct_min,100-year,1pct_plu,500-year
River Rch & RM= Walnut T5,Reach-1,14653
     439     579     691     409     816    1628    1138
River Rch & RM= Walnut T5,Reach-1,13758
     761    1039    1267     767    1530    3052    2229
River Rch & RM= Walnut T5,Reach-1,11540
     939    1289    1577     956    1907    3804    2787
River Rch & RM= Walnut T5,Reach-1,3842
    1034    1428    1754    1067    2129    4247    3136
River Rch & RM= Walnut T5,Reach-1,1106
    1185    1648    2034    1243    2479    4947    3684
Boundary for River Rch & Prof#=Walnut T5,Reach-1,1
Up Type=0
Dn Type=3
Dn Slope=0.005
Boundary for River Rch & Prof#=Walnut T5,Reach-1,2
Up Type=0
Dn Type=3
Dn Slope=0.005
Boundary for River Rch & Prof#=Walnut T5,Reach-1,3
Up Type=0
Dn Type=3
Dn Slope=0.005
Boundary for River Rch & Prof#=Walnut T5,Reach-1,4
Up Type=0
Dn Type=3
Dn Slope=0.005
Boundary for River Rch & Prof#=Walnut T5,Reach-1,5
Up Type=0
Dn Type=3
Dn Slope=0.005
Boundary for River Rch & Prof#=Walnut T5,Reach-1,6
Up Type=0
Dn Type=3
Dn Slope=0.005
Boundary for River Rch & Prof#=Walnut T5,Reach-1,7
Up Type=0
Dn Type=3
Dn Slope=0.005

--- Walnut T5.g01 (geometry) ---

Geom Title=Existing Conditions
Program Version=4.10

River Reach=Walnut T5       ,Reach-1
Reach XY= 30
        2678676.        6889161.      2679322.24      6888459.44
      2679425.95      6888040.96      2679427.05      6886871.43
      2679816.83        6886668.      2679876.11       6886431.1
      2679777.37      6886172.53      2680018.79      6886060.74
      2679885.12      6885854.24      2680139.64      6885747.71
      2680327.25      6885464.36      2680570.82      6885556.44
      2680625.55      6885126.65      2680477.88      6884916.68
      2680774.39      6884804.98      2680577.03      6884221.45
      2681022.18      6883559.42       2681076.2      6883135.92
      2680826.04      6882490.97        2680975.      6882200.71
       2680974.8       6881571.5      2680576.24      6880926.22
       2681170.6      6880413.43      2681079.04      6879862.42
      2681272.94      6879752.72      2681429.41      6879119.17
        2681676.        6879011.      2681673.85      6878716.97
      2681426.66      6878195.14        2681476.        6877861.

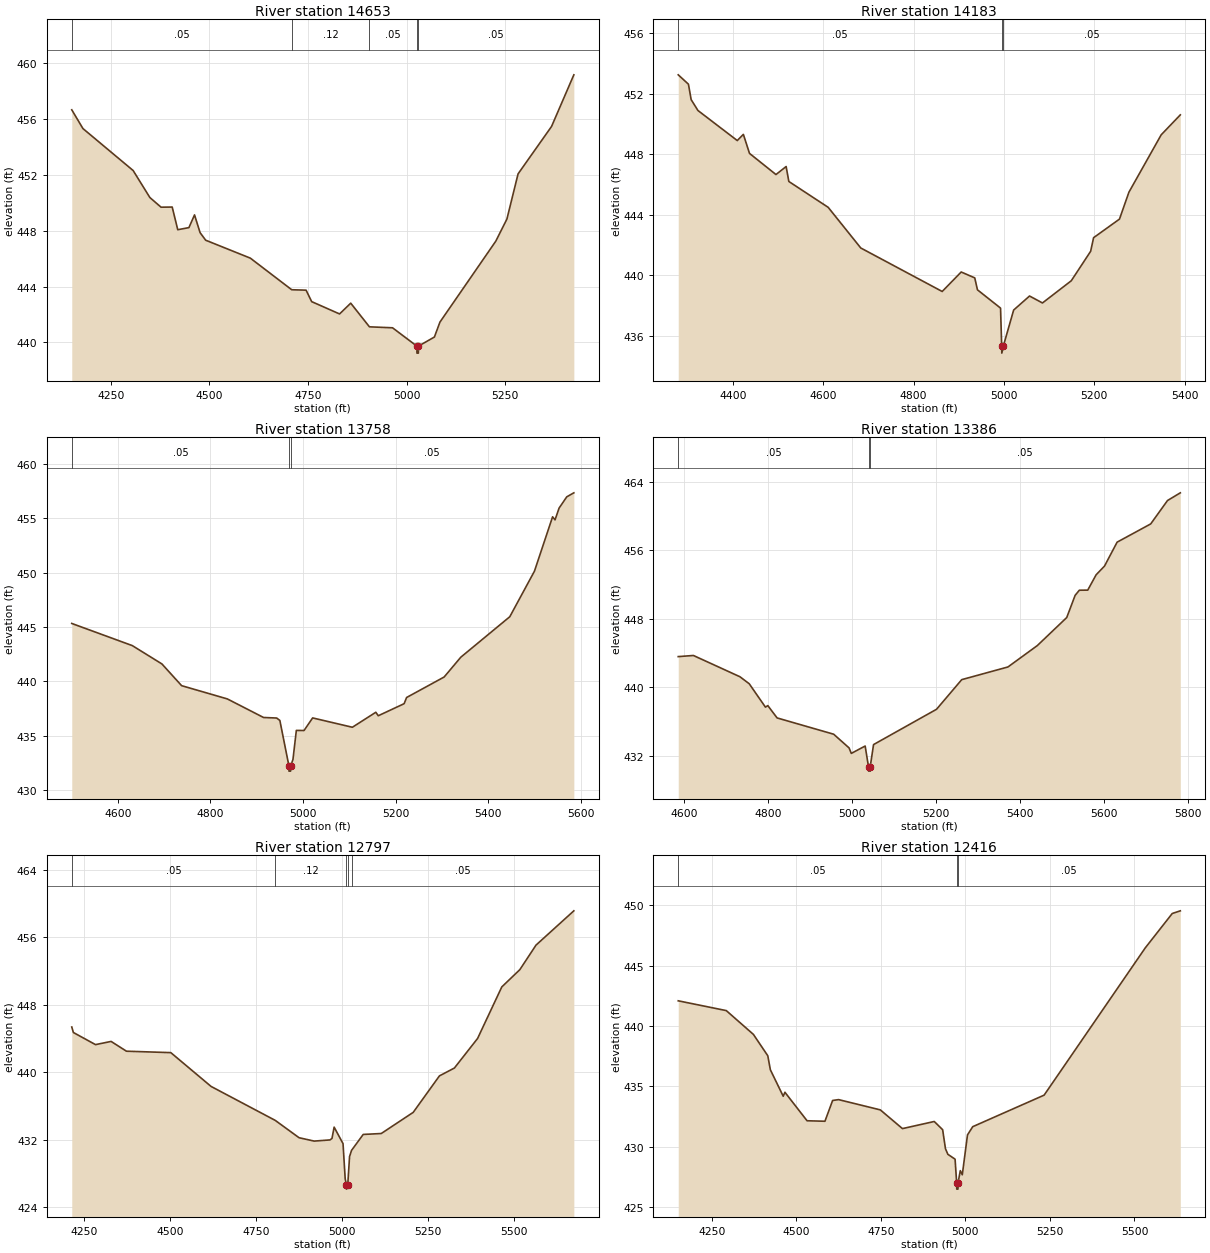
Type RM Length L Ch R = 1 ,14653   ,470,470,470
BEGIN DESCRIPTION:
Walnut T5 26.0
END DESCRIPTION:
XS GIS Cut Line= 3
      2679376.03      6889611.03        2678776.        6889011.
      2678476.03      6888711.03
#Sta/Elev= 30
  4151.4  456.63  4179.7  455.29    4307  452.29  4349.4  450.36  4377.7  449.67
    4406  449.68  4420.1  448.06  4448.4  448.21  4462.6  449.12  4476.7  447.85
  4490.9  447.31    4604  446.03    4709  443.77  4745.4  443.74  4759.6  442.92
  4830.3  442.04  4858.6  442.81    4906  441.12  4964.6  441.05  5026.3  439.74
  5026.5  439.24    5030  439.24  5030.3  439.74  5070.7  440.39  5084.8  441.46
  5226.3  447.24  5254.5  448.82  5282.8  452.05  5367.7  455.44  5424.2  459.13
#Mann= 5 ,-1 , 0
  4151.4     .05       0    4709     .12       0    4906     .05       0
  5026.3     .04       0  5030.3     .05       0
Bank Sta=5026.3,5030.3
XS Rating Curve= 0 ,0
Exp/Cntr=0.3,0.1

Type RM Length L Ch R = 1 ,14183   ,425,425,425
BEGIN DESCRIPTION:
Walnut T5 25.0
END DESCRIPTION:
XS GIS Cut Line= 3
      2679526.01      6889311.02        2679126.        6888711.
      2678826.04      6888461.03
#Sta/Elev= 30
  4279.1  453.26  4301.7  452.64  4307.7  451.62  4322.7   450.9  4409.8  448.91
  4423.3  449.32  4436.9  448.06  4495.5  446.66    4518  447.19    4524   446.2
  4611.1  444.49  4683.2   441.8  4863.5  438.92  4905.6  440.21  4935.6  439.82
  4941.6  439.03  4992.7  437.82  4995.2  435.34  4995.5  434.84  4999.2  435.34
  5021.7  437.69  5056.9  438.62  5085.5  438.16  5149.3  439.63  5192.2  441.58
  5198.7  442.48    5256  443.71  5276.9  445.49  5348.4  449.29  5390.7  450.61
#Mann= 3 ,-1 , 0
  4279.1     .05       0  4995.2     .03       0  4999.2     .05       0
Bank Sta=4995.2,4999.2
XS Rating Curve= 0 ,0
Exp/Cntr=0.3,0.1

Type RM Length L Ch R = 1 ,13758   ,372,372,372
BEGIN DESCRIPTION:
Walnut T5 24.0
END DESCRIPTION:
XS GIS Cut Line= 3
       2679666.3      6888725.75        2679326.        6888361.
      2678775.98      6888160.99
#Sta/Elev= 30
  4500.8  445.33  4631.5  443.29  4695.5   441.6    4738   439.6  4836.7  438.38
  4914.9  436.67  4943.2  436.62  4950.1   436.4  4969.6  432.23  4969.8  431.73
  4973.3  431.73  4973.6  432.23  4978.4   432.8  4985.7  435.48  5002.3  435.47
  5020.9  436.63  5106.7  435.77  5157.3  437.15  5162.6  436.83  5218.4  437.94
  5223.8  438.51  5304.9   440.4  5340.8  442.22  5446.6  445.95  5499.8  450.14
    5539  455.15  5544.3  454.87    5553  455.95  5569.6  456.99  5584.9  457.36
#Mann= 3 ,-1 , 0
  4500.8     .05       0  4969.6     .03       0  4973.6     .05       0
Bank Sta=4969.6,4973.6
XS Rating Curve= 0 ,0
Exp/Cntr=0.3,0.1

Type RM Length L Ch R = 1 ,13386   ,589,589,589
BEGIN DESCRIPTION:
Walnut T5 23.0
END DESCRIPTION:
XS GIS Cut Line= 3
      2679794.75      6888211.86       2679426.5      6888021.17
      2678645.53      6888007.01
#Sta/Elev= 30
  4585.3  443.57  4621.5   443.7  4732.2  441.22  4754.4   440.4    4793  437.67
  4798.6  437.85  4820.8  436.41  4955.5  434.51  4992.2  432.91  4997.5  432.27
  5030.5  433.13  5038.5   430.7  5038.8   430.2  5042.3   430.2  5042.5   430.7
  5050.5   433.3  5200.5  437.42  5260.5  440.88  5370.6  442.36  5440.6  444.86
  5510.6  448.13  5530.6  450.72  5540.6  451.32  5560.6  451.33  5580.6  453.12
  5600.6  454.14  5630.6  456.93  5710.6  459.06  5750.6  461.79  5781.1  462.69
#Mann= 3 ,-1 , 0
  4585.3     .05       0  5038.5     .04       0  5042.5     .05       0
Bank Sta=5038.5,5042.5
XS Rating Curve= 0 ,0
Exp/Cntr=0.3,0.1

Type RM Length L Ch R = 1 ,12797   ,381,381,381
BEGIN DESCRIPTION:
Walnut T5 22.0
END DESCRIPTION:
XS GIS Cut Line= 3
      2680104.68      6887858.58        2679426.        6887461.
      2678806.93      6887728.37
#Sta/Elev= 30
  4213.4  445.37  4218.1  444.72  4282.5  443.28  4327.8  443.66  4372.5   442.5
  4501.6  442.33  4618.7  438.32  4805.4  434.29  4874.8  432.23  4918.8  431.83
  4964.8  431.97  4970.6  432.15  4976.8  433.49  5002.7  431.53    5009  427.36
  5012.4  426.63  5012.7  426.13  5016.4  426.63  5021.7     430  5027.5  430.73
  5061.4  432.62  5113.9  432.73  5206.9  435.24  5283.2  439.57  5326.7   440.5
  5394.2  444.01  5464.7  450.13  5517.2  452.18  5564.2  455.09  5674.3  459.16
#Mann= 5 ,-1 , 0
  4213.4     .05       0  4805.4     .12       0  5012.4     .07       0
  5016.4     .12       0  5027.5     .05       0
Bank Sta=5012.4,5016.4
XS Rating Curve= 0 ,0
Exp/Cntr=0.3,0.1

Type RM Length L Ch R = 1 ,12416   ,153,153,153
BEGIN DESCRIPTION:
Mapping XS e1acd76e
END DESCRIPTION:
XS GIS Cut Line= 5
      2680257.72      6887025.25      2679962.53      6887003.54
      2679493.78      6887070.82      2679365.75      6887148.94
      2678879.61      6887437.58
#Sta/Elev= 30
  4150.6  442.08  4292.7  441.27  4372.9   439.3  4415.5  437.53  4423.1  436.37
  4461.1  434.18  4466.1  434.51  4531.6  432.15  4584.5  432.11  4607.2  433.83
  4624.9   433.9  4748.3  433.05  4813.8   431.5  4907.8  432.09  4932.6  431.41
    4941  429.83  4948.1  429.37  4969.4  428.97  4974.1  426.99  4974.4  426.49
  4977.9  426.49  4978.1  426.99  4984.8  428.02  4990.7  427.68  5006.1  430.98
  5021.6  431.66  5232.7  434.27  5531.8  446.46  5611.7  449.31  5635.5  449.53
#Mann= 3 ,-1 , 0
  4150.6     .05       0  4974.1     .03       0  4978.1     .05       0
Bank Sta=4974.1,4978.1
XS Rating Curve= 0 ,0
Exp/Cntr=0.3,0.1

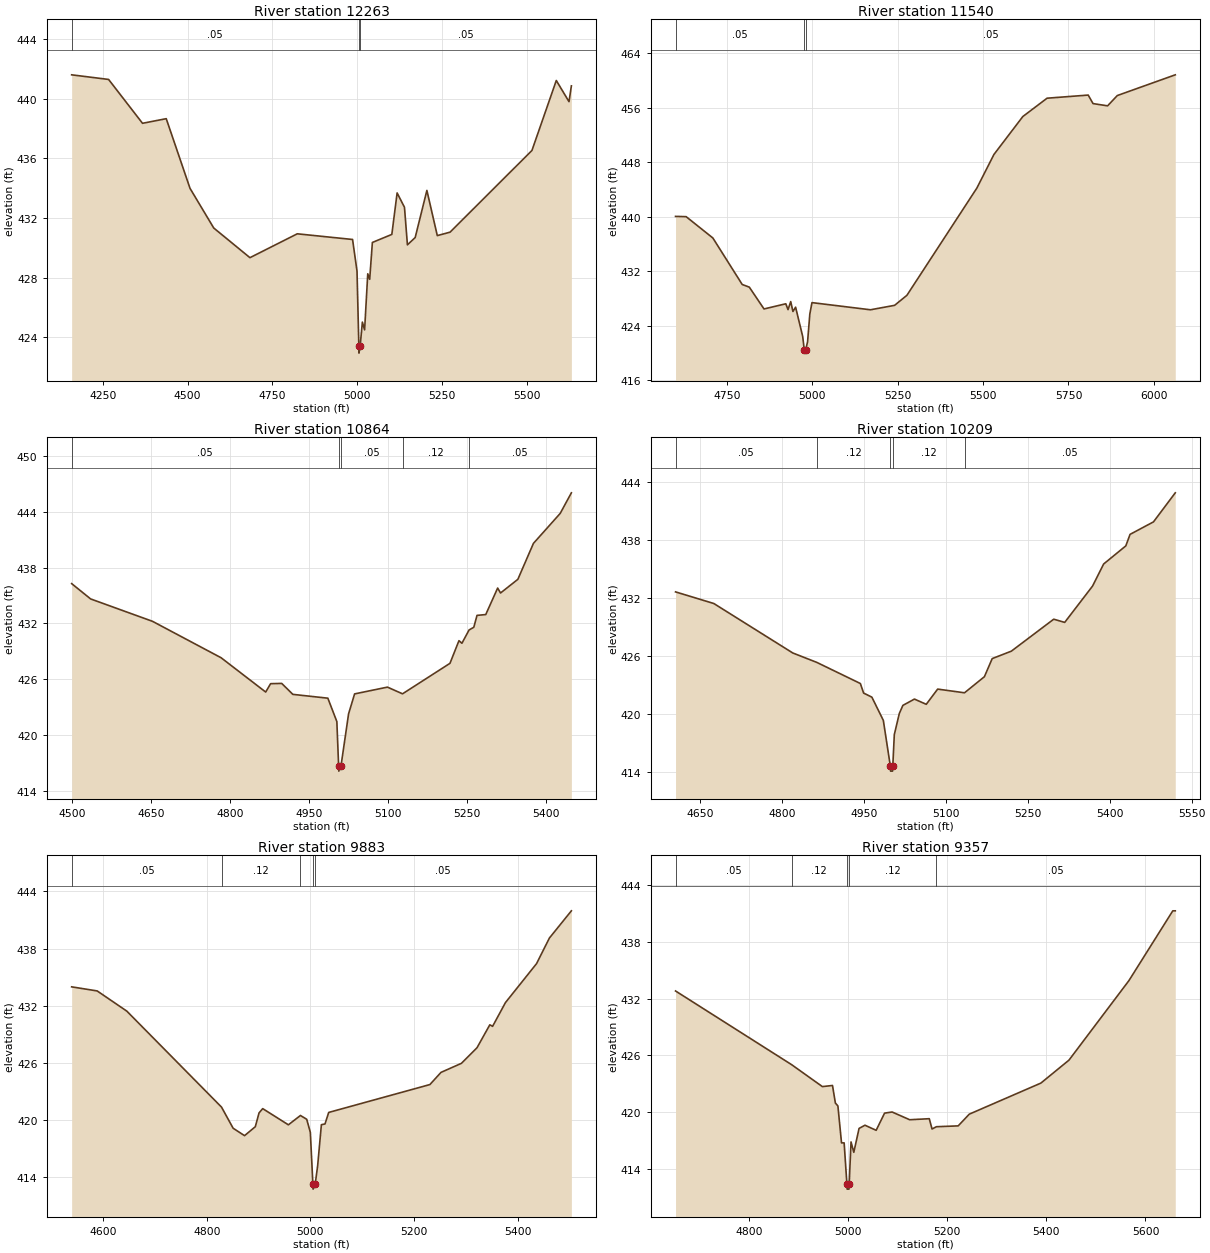
Type RM Length L Ch R = 1 ,12263   ,723,723,723
BEGIN DESCRIPTION:
Mapping XS 49bbe7bb
END DESCRIPTION:
XS GIS Cut Line= 6
      2680254.92      6886883.03      2679801.37      6886870.01
      2679695.03      6886878.69      2679475.84      6886939.45
      2679417.25      6886963.32      2678874.74       6887269.3
#Sta/Elev= 30
  4158.2  441.61  4267.2   441.3  4367.2  438.36  4437.2  438.67  4507.3     434
  4577.3  431.34  4684.1  429.35  4823.7  430.95  4986.8  430.57  4999.9  428.45
  5005.3  423.45  5005.6  422.95  5009.3  423.45  5015.7  425.03  5022.3  424.51
  5031.6  428.27  5037.3   427.9  5045.2  430.37  5102.6  430.91  5118.2  433.69
  5139.9  432.73  5148.6  430.21  5171.5   430.7    5206  433.86  5236.7  430.83
  5274.3  431.06  5515.9  436.54  5587.7  441.23  5625.2  439.81  5632.2  440.87
#Mann= 3 ,-1 , 0
  4158.2     .05       0  5005.3     .03       0  5009.3     .05       0
Bank Sta=5005.3,5009.3
XS Rating Curve= 0 ,0
Exp/Cntr=0.3,0.1

Type RM Length L Ch R = 1 ,11540   ,676,676,676
BEGIN DESCRIPTION:
Mapping XS bb5ed43c
END DESCRIPTION:
XS GIS Cut Line= 3
      2680098.66      6886852.63      2679842.95      6886544.52
      2679051.02      6885836.02
#Sta/Elev= 30
  4599.6  440.03  4630.7  439.99  4708.9  436.86  4794.8  430.04  4815.6  429.65
  4858.6  426.45  4922.4  427.21  4928.9  426.35  4936.8  427.53  4943.3  426.08
  4951.1  426.71  4971.9  422.41  4976.4  420.47  4976.8  419.97  4980.7  420.47
  4986.2  421.65  4992.7  425.69    4999  427.38  5170.3  426.33  5240.9  426.98
  5276.9  428.45  5481.7  444.18  5531.8  449.12  5616.3  454.68  5687.3  457.37
  5807.7  457.83  5821.9  456.58  5864.5  456.25  5892.9  457.76  6062.6   460.8
#Mann= 3 ,-1 , 0
  4599.6     .05       0  4976.4     .03       0  4980.7     .05       0
Bank Sta=4976.4,4980.7
XS Rating Curve= 0 ,0
Exp/Cntr=0.3,0.1

Type RM Length L Ch R = 1 ,10864   ,655,655,655
BEGIN DESCRIPTION:
Mapping XS e75527b2
END DESCRIPTION:
XS GIS Cut Line= 3
      2680276.17      6886501.48        2680034.      6886121.31
      2679584.33      6885905.57
#Sta/Elev= 30
  4499.5  436.27  4535.6  434.62  4653.2  432.21  4783.5  428.29  4868.2   424.6
  4877.5   425.5  4898.6  425.53  4919.8  424.35  4986.3  423.94  5003.4  421.42
  5006.8  416.59  5007.1  416.09  5011.1  416.59  5025.7  422.26  5037.1   424.4
  5099.5  425.13  5128.2  424.41  5218.3  427.69  5235.4  430.13    5241  429.85
  5254.6  431.28  5263.6  431.57  5269.7  432.85  5286.3  432.94  5308.9  435.79
  5314.4  435.26  5347.3  436.73  5376.9   440.6  5427.7  443.82    5449  446.04
#Mann= 5 ,-1 , 0
  4499.5     .05       0  5006.8     .03       0  5011.1     .05       0
  5128.2     .12       0  5254.6     .05       0
Bank Sta=5006.8,5011.1
XS Rating Curve= 0 ,0
Exp/Cntr=0.3,0.1

Type RM Length L Ch R = 1 ,10209   ,326,326,326
BEGIN DESCRIPTION:
Mapping XS 4bfb5c9e
END DESCRIPTION:
XS GIS Cut Line= 4
      2680379.49      6886054.46        2680159.      6885717.66
      2680018.38      6885552.73      2679726.69      6885502.38
#Sta/Elev= 30
  4604.7  432.63  4674.8  431.43  4819.5  426.32  4863.4  425.35  4943.2  423.17
  4949.2  422.18  4964.3  421.76  4985.3  419.36  4998.2  414.62  4998.6  414.12
  5002.2  414.12  5002.6  414.62  5005.4  417.89  5014.5  420.06  5021.1  420.91
  5042.3  421.56  5063.9  421.02  5084.8  422.59    5134  422.21  5170.4  423.87
  5184.7  425.74  5219.8  426.51  5297.4  429.81  5317.5  429.48  5368.5  433.23
  5388.8  435.51  5429.4  437.38  5437.2  438.57  5480.1  439.86    5520  442.86
#Mann= 5 ,-1 , 0
  4604.7     .05       0  4863.4     .12       0  4998.2     .07       0
  5002.6     .12       0    5134     .05       0
Bank Sta=4998.2,5002.6
XS Rating Curve= 0 ,0
Exp/Cntr=0.3,0.1

Type RM Length L Ch R = 1 ,9883    ,526,526,526
BEGIN DESCRIPTION:
Mapping XS bc3b76a6
END DESCRIPTION:
XS GIS Cut Line= 4
      2680660.71      6885776.12      2680374.28      6885530.92
      2680228.88      6885387.69      2679870.93      6885251.02
#Sta/Elev= 30
  4539.3  433.97  4588.6  433.54  4645.7  431.42  4828.5  421.33  4850.9  419.11
  4872.9  418.33  4893.7  419.27  4900.9  420.72    4908  421.17  4957.5  419.47
  4980.8  420.45  4992.9  420.05  4999.9  418.67  5004.8  413.21  5005.2  412.71
  5009.2  413.21    5014  415.17  5021.2  419.48  5028.2  419.56  5035.3  420.77
  5230.6   423.7    5252  424.98  5291.4  425.93  5321.5  427.57  5346.2  429.98
  5351.6  429.82  5376.3  432.31  5436.4  436.41  5461.2   439.1  5503.6  441.96
#Mann= 5 ,-1 , 0
  4539.3     .05       0  4828.5     .12       0  4980.8     .05       0
  5004.8     .03       0  5009.2     .05       0
Bank Sta=5004.8,5009.2
XS Rating Curve= 0 ,0
Exp/Cntr=0.3,0.1

Type RM Length L Ch R = 1 ,9357    ,512,512,512
BEGIN DESCRIPTION:
Mapping XS 65dd7a3e
END DESCRIPTION:
XS GIS Cut Line= 3
      2680917.25      6885396.23      2680585.22      6885333.29
      2679981.93      6885040.33
#Sta/Elev= 30
  4651.5  432.81  4885.9     425  4947.9  422.68  4968.3   422.8  4974.1  420.94
  4979.2  420.63  4986.5  416.72  4991.8  416.72  4997.4  412.32  4997.9  411.82
  5001.5  411.82  5001.9  412.32  5005.7  416.82  5011.3  415.72  5021.9  418.25
  5033.8  418.59  5056.4  418.05  5073.4  419.87  5088.6  419.99  5124.1  419.17
  5163.6  419.28  5169.2  418.19    5178  418.43    5222  418.52  5244.3  419.76
  5388.8  423.05  5445.5  425.48  5566.6  433.91  5655.1   441.3  5660.1   441.3
#Mann= 5 ,-1 , 0
  4651.5     .05       0  4885.9     .12       0  4997.4     .07       0
  5001.9     .12       0    5178     .05       0
Bank Sta=4997.4,5001.9
XS Rating Curve= 0 ,0
Exp/Cntr=0.3,0.1

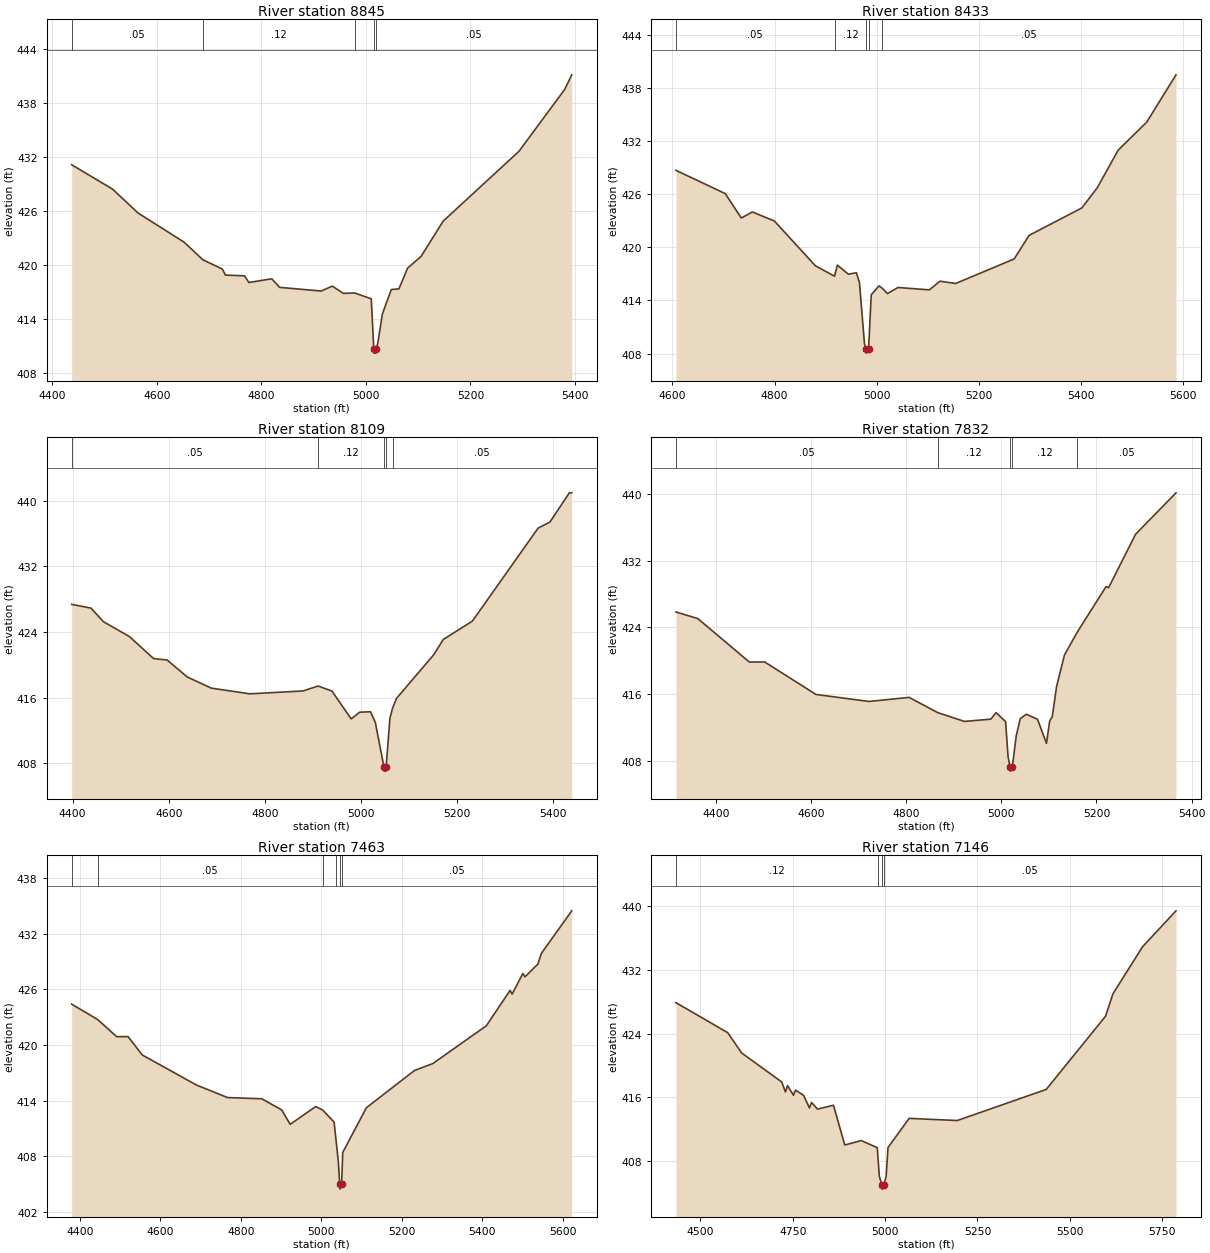
Type RM Length L Ch R = 1 ,8845    ,412,412,412
BEGIN DESCRIPTION:
Mapping XS d757931f
END DESCRIPTION:
XS GIS Cut Line= 3
      2680954.17      6885229.14      2680474.54      6884931.82
      2680103.42      6884803.77
#Sta/Elev= 30
    4437  431.15  4515.1  428.45  4564.3  425.78  4652.1  422.56  4688.1   420.6
  4725.4  419.57  4731.3   418.9  4767.9  418.82    4776  418.08  4819.9  418.49
  4834.9  417.54  4914.4  417.13  4935.7  417.68  4956.9  416.87  4978.4  416.92
  5010.3  416.27  5015.1  410.74  5015.6  410.24  5019.2  410.24  5019.6  410.74
  5022.7  411.31  5031.5  414.57  5048.6   417.3  5063.2  417.37  5079.8  419.68
  5105.5  420.97  5147.9  424.89  5292.9  432.64  5380.6  439.52  5393.9  441.13
#Mann= 5 ,-1 , 0
    4437     .05       0  4688.1     .12       0  4978.4     .05       0
  5015.1     .03       0  5019.6     .05       0
Bank Sta=5015.1,5019.6
XS Rating Curve= 0 ,0
Exp/Cntr=0.3,0.1

Type RM Length L Ch R = 1 ,8433    ,324,324,324
BEGIN DESCRIPTION:
Mapping XS 42da2199
END DESCRIPTION:
XS GIS Cut Line= 3
      2681117.33       6884982.6       2680778.8      6884787.29
      2680205.92      6884652.75
#Sta/Elev= 30
  4606.8  428.69  4703.3  426.07  4734.8  423.31  4756.4  423.99  4799.5  422.98
  4879.9  417.92  4917.4  416.74    4923  417.99  4944.5  416.97  4960.3  417.13
  4966.2  416.03  4976.1  409.08  4979.6  408.56  4980.1  408.06  4984.1  408.56
  4989.3  414.65  5004.5  415.65  5010.7  415.39  5021.1  414.78  5041.6  415.47
  5103.2   415.2  5123.8  416.18  5154.6  415.92  5269.2  418.69  5298.4  421.35
  5401.6  424.44  5431.9  426.72    5473  430.98  5528.8  434.13  5586.1  439.47
#Mann= 5 ,-1 , 0
  4606.8     .05       0  4917.4     .12       0  4979.6     .07       0
  4984.1     .12       0  5010.7     .05       0
Bank Sta=4979.6,4984.1
XS Rating Curve= 0 ,0
Exp/Cntr=0.3,0.1

Type RM Length L Ch R = 1 ,8109    ,277,277,277
BEGIN DESCRIPTION:
Walnut T5 13.0
END DESCRIPTION:
XS GIS Cut Line= 3
      2681225.96        6884561.      2680625.53      6884516.19
      2680191.15      6884575.39
#Sta/Elev= 30
  4397.9  427.36    4438  426.91    4464  425.25  4518.2  423.43  4568.3  420.75
  4596.4  420.58  4638.5   418.5  4688.7  417.14  4768.9  416.45  4879.2   416.8
  4910.7   417.4  4939.4  416.79  4979.5  413.39  4997.3  414.21  5019.7  414.26
  5029.8  412.95  5047.7  407.52  5048.2  407.02  5051.8  407.02  5052.2  407.52
  5060.1   413.5  5065.7  414.72  5073.9   415.9  5151.3  421.22  5171.1  423.08
  5231.7  425.32  5368.4  436.66  5393.1  437.41  5433.4  440.97  5438.4  440.97
#Mann= 5 ,-1 , 0
  4397.9     .05       0  4910.7     .12       0  5047.7     .07       0
  5052.2     .12       0  5065.7     .05       0
Bank Sta=5047.7,5052.2
XS Rating Curve= 0 ,0
Exp/Cntr=0.3,0.1

Type RM Length L Ch R = 1 ,7832    ,369,369,369
BEGIN DESCRIPTION:
Walnut T5 12.0
END DESCRIPTION:
XS GIS Cut Line= 3
      2681208.33      6884481.12      2680646.27      6884246.75
      2680229.26      6884393.67
#Sta/Elev= 30
    4316  425.86  4361.9  425.07  4470.2  419.86  4502.7  419.86  4610.4  415.97
  4721.9  415.13  4806.1  415.62  4866.4  413.79  4922.4  412.74  4977.9  413.01
  4988.9  413.79  5008.9  412.72  5014.2  408.49  5018.4  407.28  5018.9  406.78
    5023  407.28  5031.3     411  5039.8  413.07  5052.5   413.6  5076.1  412.99
  5094.9  410.11  5101.7  412.81    5107  413.31  5116.1  416.92  5132.7   420.7
  5159.6  423.44  5220.2  428.91  5225.5  428.77  5282.1  435.17  5367.1  440.14
#Mann= 5 ,-1 , 0
    4316     .05       0  4866.4     .12       0  5018.4     .07       0
    5023     .12       0  5159.6     .05       0
Bank Sta=5018.4,5023
XS Rating Curve= 0 ,0
Exp/Cntr=0.3,0.1

Type RM Length L Ch R = 1 ,7463    ,317,317,317
BEGIN DESCRIPTION:
Walnut T5 11.0
END DESCRIPTION:
XS GIS Cut Line= 3
      2681210.49      6884424.68      2680776.19      6883981.08
      2680184.01      6884172.97
#Sta/Elev= 30
  4379.2   424.4  4444.1  422.73  4491.1  420.89  4519.4   420.9  4554.6  418.92
  4689.1  415.68  4766.8  414.32  4851.7  414.19  4901.3  412.99  4922.4  411.43
  4986.1  413.35  5003.7  412.96  5031.7  411.67  5036.2  409.85  5042.3  407.39
  5045.7  404.94  5046.1  404.44  5050.3  404.94  5053.2   408.4  5111.9  413.22
  5231.5  417.24  5277.1  417.99  5410.3  422.07  5469.1  425.88  5474.3  425.48
    5501  427.71  5506.3  427.35  5538.3  428.72  5546.8  429.86  5622.5  434.47
#Mann= 6 ,-1 , 0
  4379.2     .12       0  4444.1     .05       0  5003.7     .12       0
  5036.2     .05       0  5045.7     .05       0  5050.3     .05       0
Bank Sta=5045.7,5050.3
XS Rating Curve= 0 ,0
Exp/Cntr=0.3,0.1

Type RM Length L Ch R = 1 ,7146    ,291,291,291
BEGIN DESCRIPTION:
Walnut T5 10.0
END DESCRIPTION:
XS GIS Cut Line= 3
      2681414.54      6883994.16      2680920.76      6883716.49
      2680135.83      6883650.39
#Sta/Elev= 30
  4433.5  427.87  4573.9   424.1  4611.5  421.56  4719.9  417.93  4730.1  416.67
  4735.8  417.47  4751.8  416.26  4757.5   416.9  4779.2  416.25  4795.1  414.67
  4800.8  415.36  4816.8  414.52  4860.1  415.01  4890.7  410.02  4935.3  410.58
  4978.7  409.69  4981.9  407.66  4984.4  406.08  4991.7  404.99  4992.1  404.49
  4996.3  404.99  5002.9  406.14  5007.8   409.7    5065  413.36  5195.4  413.09
  5436.3  416.99  5596.8  426.16  5616.9  428.97  5697.2  434.88  5787.7  439.38
#Mann= 4 ,-1 , 0
  4433.5     .12       0  4981.9     .05       0  4991.7     .03       0
  4996.3     .05       0
Bank Sta=4991.7,4996.3
XS Rating Curve= 0 ,0
Exp/Cntr=0.3,0.1

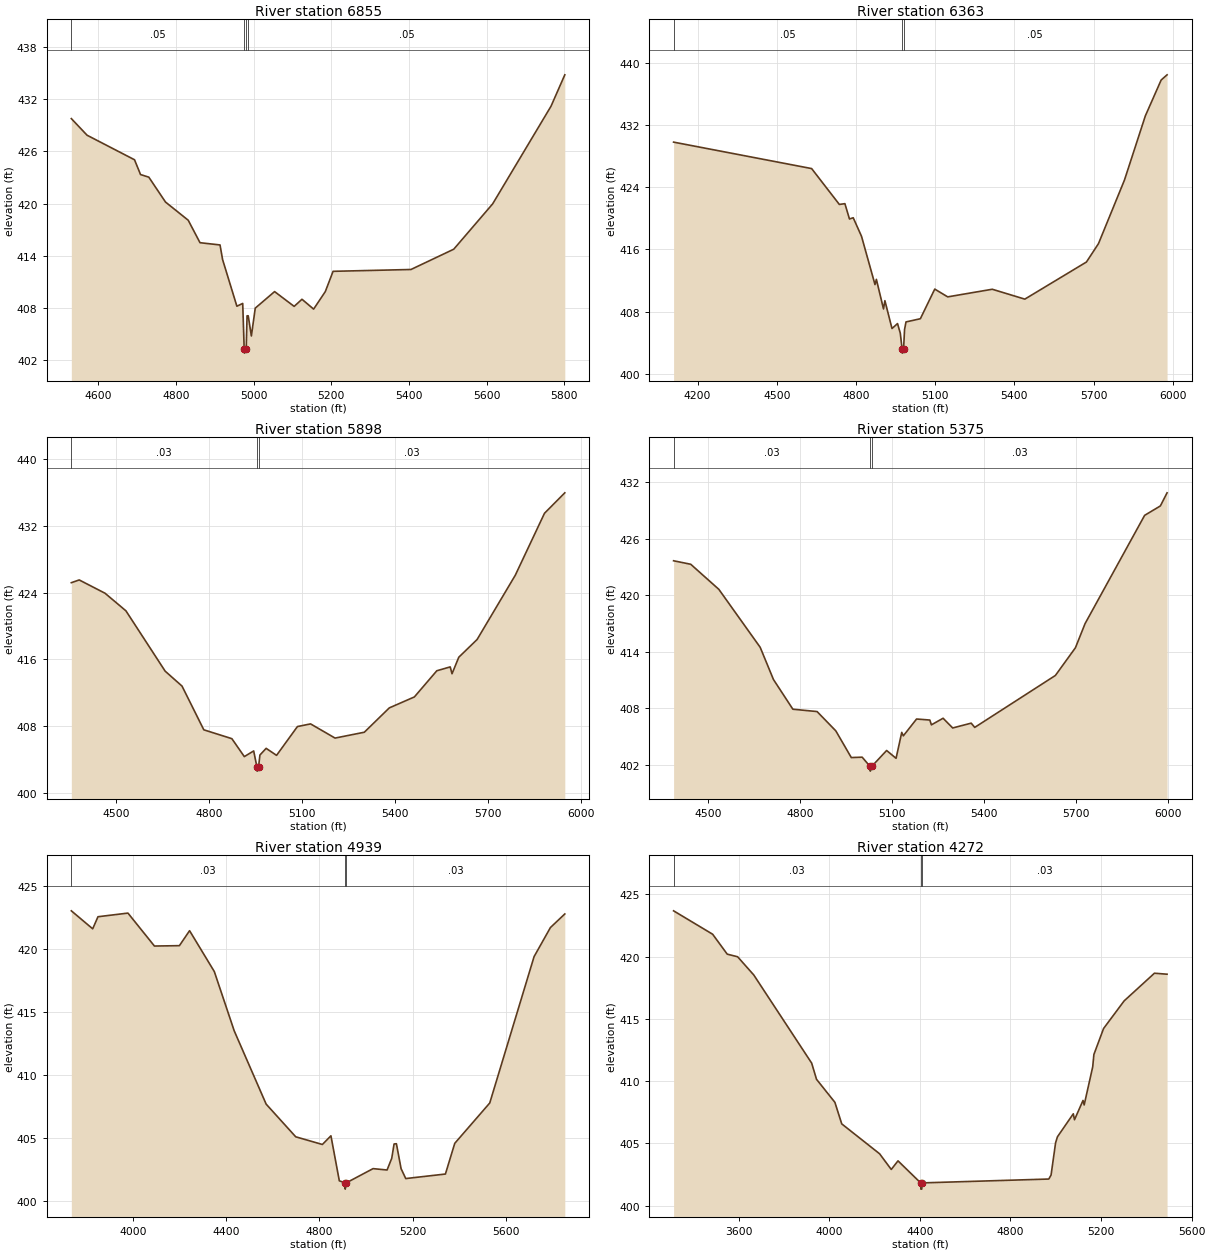
Type RM Length L Ch R = 1 ,6855    ,492,492,492
BEGIN DESCRIPTION:
Mapping XS 1eb9ea06
END DESCRIPTION:
XS GIS Cut Line= 3
      2681433.33      6883698.44      2681042.68      6883461.45
      2680230.57      6883513.51
#Sta/Elev= 30
  4530.4  429.76  4570.9  427.85  4693.1  425.03  4708.6  423.33  4729.9  423.03
  4772.9  420.17  4831.4  418.08  4861.7   415.5  4913.3  415.24  4919.9  413.56
  4956.7   408.2  4971.7  408.52  4975.5  403.31  4976.2  402.81  4980.7  403.31
  4982.9   407.1  4985.9   407.1    4994  404.78    5004  407.98  5053.8  409.88
  5104.2  408.18  5124.3     409  5154.3  407.87  5184.4  409.88  5204.4  412.21
  5404.9  412.42  5515.1  414.75  5615.3  419.96  5765.6  431.18  5801.1  434.79
#Mann= 4 ,-1 , 0
  4530.4     .05       0  4975.5     .03       0  4980.7     .05       0
  4985.9     .05       0
Bank Sta=4975.5,4980.7
XS Rating Curve= 0 ,0
Exp/Cntr=0.3,0.1

Type RM Length L Ch R = 1 ,6363    ,465,465,465
BEGIN DESCRIPTION:
Mapping XS fb878539
END DESCRIPTION:
XS GIS Cut Line= 3
      2681874.26      6883258.32      2681044.42      6882994.43
      2680113.82      6883355.56
#Sta/Elev= 30
  4109.1   429.8  4631.9   426.4  4736.9  421.79  4757.9  421.89  4775.2  419.92
  4789.4  420.08  4820.8   417.7  4871.9  411.49  4877.1  412.16  4904.1  408.36
  4909.4  409.42  4936.3  405.84  4957.2  406.48  4967.7  405.24  4974.7  403.18
  4975.4  402.68    4980  403.18  4983.9  405.72  4989.3  406.69  5043.7   407.1
  5098.2  410.91  5147.3  409.91    5316  410.89  5439.4  409.62  5672.7  414.39
  5718.3  416.75  5816.8  424.93  5895.9  433.18  5955.7  437.78  5978.1  438.45
#Mann= 3 ,-1 , 0
  4109.1     .05       0  4974.7     .03       0    4980     .05       0
Bank Sta=4974.7,4980
XS Rating Curve= 0 ,0
Exp/Cntr=0.3,0.1

Type RM Length L Ch R = 1 ,5898    ,523,523,523
BEGIN DESCRIPTION:
Walnut T5 9.0
END DESCRIPTION:
XS GIS Cut Line= 3
      2681521.23      6882545.21        2680876.        6882611.
      2680075.98      6883111.01
#Sta/Elev= 30
  4355.8  425.18  4381.2  425.51  4464.4  423.92  4531.9  421.81  4658.5  414.58
  4712.9  412.79  4783.2  407.55  4873.7  406.49  4913.9  404.34  4944.1  405.02
  4954.5   403.1  4955.2   402.6  4959.8   403.1  4964.2  404.53  4984.3  405.33
  5017.9  404.49  5085.2  407.94  5127.6  408.26  5206.6  406.56    5301  407.26
  5381.7  410.18  5462.5  411.49    5535  414.63  5578.1  415.09    5584  414.27
  5605.8  416.25  5664.8  418.37    5788  426.07  5882.3   433.5  5947.8  435.95
#Mann= 3 ,-1 , 0
  4355.8     .03       0  4954.5     .03       0  4959.8     .03       0
Bank Sta=4954.5,4959.8
XS Rating Curve= 0 ,0
Exp/Cntr=0.3,0.1

Type RM Length L Ch R = 1 ,5375    ,436,436,436
BEGIN DESCRIPTION:
Walnut T5 8.0
END DESCRIPTION:
XS GIS Cut Line= 3
      2681551.02      6882386.01      2680976.51      6882176.26
      2680004.72      6882395.91
#Sta/Elev= 30
  4388.4  423.65  4444.2  423.28  4535.8  420.62  4670.5  414.47  4713.8  411.05
    4777   407.9  4855.9  407.65    4917   405.6  4967.4  402.77  5002.8  402.81
  5028.5  401.83  5029.3  401.33    5034  401.83  5082.5  403.52  5113.3  402.69
  5131.8  405.44  5136.9  405.07  5180.1  406.86  5223.3  406.75  5228.4  406.24
  5266.5  406.94  5297.8  405.91    5358  406.42  5369.6  405.97  5632.4  411.48
  5697.7  414.42  5729.1  416.98  5923.2  428.47  5974.5  429.47  5996.3  430.86
#Mann= 3 ,-1 , 0
  4388.4     .03       0  5028.5     .03       0    5034     .03       0
Bank Sta=5028.5,5034
XS Rating Curve= 0 ,0
Exp/Cntr=0.3,0.1

Type RM Length L Ch R = 1 ,4939    ,667,667,667
BEGIN DESCRIPTION:
Mapping XS f8c2fa61
END DESCRIPTION:
XS GIS Cut Line= 3
      2681978.45      6882507.95      2680978.67      6881740.53
      2680124.45      6881733.58
#Sta/Elev= 30
    3737  423.06  3828.5  421.63  3851.2  422.59  3979.6  422.88  4093.1  420.26
  4200.1  420.29  4243.7  421.48  4349.7  418.23  4434.9  413.52  4571.8  407.69
  4698.6  405.09  4812.8  404.48  4849.4  405.17  4885.4  401.59  4909.8  401.43
  4910.6  400.93  4915.3  401.43    5030  402.56    5090  402.45    5110  403.38
    5120  404.52    5130  404.54    5150  402.56    5170  401.77    5340  402.13
    5380  404.57    5530  407.78    5720  419.42    5790  421.73  5851.6  422.81
#Mann= 3 ,-1 , 0
    3737     .03       0  4909.8     .03       0  4915.3     .03       0
Bank Sta=4909.8,4915.3
XS Rating Curve= 0 ,0
Exp/Cntr=0.3,0.1

Type RM Length L Ch R = 1 ,4272    ,106,106,106
BEGIN DESCRIPTION:
Mapping XS 9c985993
END DESCRIPTION:
XS GIS Cut Line= 4
      2682219.57       6881853.5      2681020.33      6881146.78
      2680714.78      6881160.67      2680246.03       6881268.3
#Sta/Elev= 30
  3312.6  423.67    3485  421.79  3549.4  420.19  3595.3  419.98  3666.5  418.52
  3922.2  411.44  3943.6  410.14  4024.8  408.29    4055  406.56  4222.1  404.16
  4273.6   402.9  4303.4  403.59  4403.5  401.82  4404.4  401.32  4408.3  401.32
  4409.1  401.82  4969.2  402.13  4979.2  402.45  4999.2  405.04  5007.3  405.52
  5077.4  407.37  5082.6  406.89  5120.3  408.44  5125.4  408.08  5163.1  411.14
  5168.3  412.13  5211.1  414.22    5302  416.44  5435.7  418.66  5491.4  418.58
#Mann= 3 ,-1 , 0
  3312.6     .03       0  4403.5     .03       0  4409.1     .03       0
Bank Sta=4403.5,4409.1
XS Rating Curve= 0 ,0
Exp/Cntr=0.3,0.1

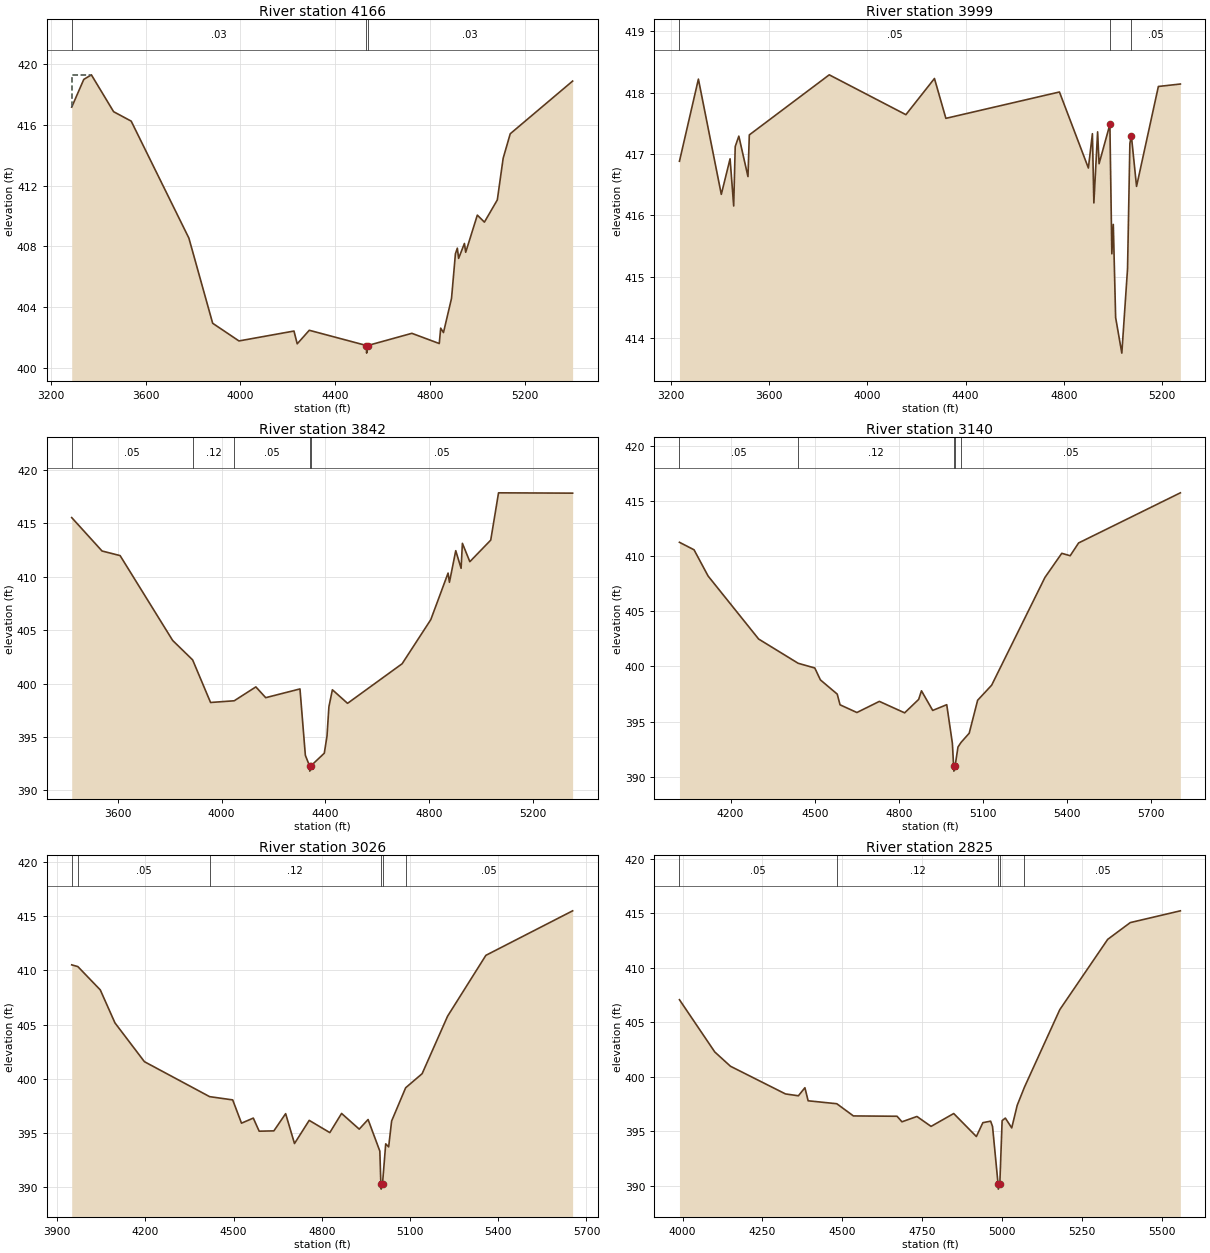
Type RM Length L Ch R = 1 ,4166    ,167,167,167
BEGIN DESCRIPTION:
Mapping XS b4e0803d
END DESCRIPTION:
XS GIS Cut Line= 6
      2682240.56      6880898.01      2681930.92      6880725.77
      2681584.57       6880803.9      2680868.42       6880934.1
      2680785.09      6881033.06       2680274.7      6881230.97
#Sta/Elev= 30
  3288.1  417.15  3339.1  418.97  3371.1  419.27    3465  416.85  3539.2  416.23
  3782.8  408.55  3883.2  402.96  3994.2   401.8  4226.4  402.45  4240.1  401.61
    4291   402.5  4532.3   401.5  4533.1     401  4537.9   401.5  4724.1   402.3
  4839.8  401.63  4845.8  402.64  4857.6  402.35  4891.6   404.6    4908  407.52
  4916.1  407.89  4921.5  407.22    4946   408.2  4951.4  407.62  5000.5  410.06
  5030.4   409.6  5084.9  411.06  5109.5  413.79  5139.4   415.4  5402.8  418.86
#Mann= 3 ,-1 , 0
  3288.1     .03       0  4532.3     .03       0  4537.9     .03       0
#XS Ineff= 2 , 0
       0  3371.1  419.27               0
Permanent Ineff=
       F       F
Bank Sta=4532.3,4537.9
XS Rating Curve= 0 ,0
Exp/Cntr=0.3,0.1

Type RM Length L Ch R = 1 ,3999    ,157,157,157
BEGIN DESCRIPTION:
Mapping XS 90f27047
END DESCRIPTION:
XS GIS Cut Line= 6
      2682248.81      6880825.49      2682034.66      6880672.82
      2681937.43      6880653.72      2680822.85        6880869.
      2680689.17      6880884.62      2680341.93      6881091.23
#Sta/Elev= 30
  3235.9  416.88    3313  418.22  3406.2  416.34  3441.9  416.92  3456.6  416.15
  3462.8  417.12  3477.5  417.29  3514.7  416.63  3520.2  417.31  3845.4  418.29
  4157.3  417.64  4273.5  418.23    4320  417.58  4782.1  418.01  4899.8  416.77
  4916.2  417.33  4922.1   416.2  4937.4  417.36  4943.3  416.84  4987.3  417.48
  4995.3  415.37  5001.2  415.85  5010.7  414.33  5035.9  413.75  5059.2  415.13
  5068.7  417.17  5074.6   417.3  5095.8  416.47  5184.6   418.1  5274.1  418.14
#Mann= 3 ,-1 , 0
  3235.9     .05       0  4987.3     .04       0  5074.6     .05       0
Bank Sta=4987.3,5074.6
XS Rating Curve= 0 ,0
Exp/Cntr=0.3,0.1

Type RM Length L Ch R = 1 ,3842    ,702,702,702
BEGIN DESCRIPTION:
Mapping XS 106c1bd8
END DESCRIPTION:
XS GIS Cut Line= 5
        2682200.      6880638.09      2681857.14      6880559.97
      2681340.65      6880642.44      2680759.05      6880813.88
      2680311.99      6880859.45
#Sta/Elev= 30
  3422.5  415.55  3539.4  412.42    3609  411.99  3811.6  404.04  3888.5  402.22
  3957.6  398.23  4048.8  398.39  4132.2  399.69  4170.2  398.68  4302.2   399.5
  4322.9  393.28    4339   392.3  4339.9   391.8  4344.6   392.3  4395.9  393.48
  4406.3  395.08  4413.7  397.83  4427.1  399.42  4485.5  398.15  4695.9  401.86
  4806.3  405.99  4872.9  410.35  4878.2  409.49  4902.5  412.45  4923.1   410.8
  4928.1  413.14  4956.8  411.42  5037.3  413.44  5067.4  417.87  5352.9  417.84
#Mann= 5 ,-1 , 0
  3422.5     .05       0  3888.5     .12       0  4048.8     .05       0
    4339     .04       0  4344.6     .05       0
Bank Sta=4339,4344.6
XS Rating Curve= 0 ,0
Exp/Cntr=0.3,0.1

Type RM Length L Ch R = 1 ,3140    ,114,114,114
BEGIN DESCRIPTION:
Walnut T5 2.0
END DESCRIPTION:
XS GIS Cut Line= 3
      2682157.96      6880425.63      2681176.67      6880381.08
      2680373.21       6880389.4
#Sta/Elev= 30
  4017.7  411.27  4069.7  410.59  4119.8  408.21    4300  402.49  4440.8  400.29
  4500.2  399.86  4520.2  398.78  4580.2  397.49  4590.2  396.52  4650.3  395.82
  4730.4  396.83  4820.5  395.79  4870.5  397.01  4880.5  397.79  4920.6  396.01
  4970.6  396.53  4990.7  393.03    4995     391  4995.9   390.5  5000.6     391
  5010.7  392.69  5021.7  393.11  5050.7  393.94  5080.7  396.93  5130.7   398.3
  5320.7  408.08  5380.7  410.27  5410.7  410.05  5440.7  411.21  5803.5  415.76
#Mann= 5 ,-1 , 0
  4017.7     .05       0  4440.8     .12       0    4995     .07       0
  5000.6     .12       0  5021.7     .05       0
Bank Sta=4995,5000.6
XS Rating Curve= 0 ,0
Exp/Cntr=0.3,0.1

Type RM Length L Ch R = 1 ,3026    ,201,201,201
BEGIN DESCRIPTION:
Mapping XS f994fe8b
END DESCRIPTION:
XS GIS Cut Line= 3
      2682192.99      6880319.12       2681138.3      6880277.88
      2680491.57      6880316.95
#Sta/Elev= 30
  3949.6  410.51  3970.5  410.35  4046.7   408.2  4096.7  405.15  4196.8  401.57
  4418.6  398.34    4497  398.04    4527  395.89  4567.1  396.36  4587.1  395.15
  4637.1  395.18  4677.1  396.77  4707.2  394.01  4757.2  396.15  4827.3  395.02
  4867.3  396.79  4927.3  395.34  4957.4  396.23  4997.4  393.31  5000.9   390.3
  5001.8   389.8  5006.5   390.3  5017.4  393.98  5027.4   393.7  5037.5  396.09
  5085.2  399.16  5141.2  400.46  5227.8  405.77    5358  411.39    5653   415.5
#Mann= 6 ,-1 , 0
  3949.6     .12       0  3970.5     .05       0  4418.6     .12       0
  5000.9     .07       0  5006.5     .12       0  5085.2     .05       0
Bank Sta=5000.9,5006.5
XS Rating Curve= 0 ,0
Exp/Cntr=0.3,0.1

Type RM Length L Ch R = 1 ,2825    ,517,517,517
BEGIN DESCRIPTION:
Mapping XS 6ca38119
END DESCRIPTION:
XS GIS Cut Line= 3
      2682123.69      6880232.81      2681161.93      6880080.04
      2680569.61       6880121.6
#Sta/Elev= 30
  3990.2  407.07  4100.8  402.27  4149.9  400.96    4322  398.42  4362.5  398.25
  4382.8  398.99  4392.9  397.79  4482.6  397.52  4534.6   396.4  4671.2  396.37
  4686.5  395.86  4733.4  396.35  4777.6  395.44  4848.5  396.62  4919.4  394.51
  4939.7  395.78    4964  395.92    4970  395.43  4987.2  390.18  4988.1  389.68
  4992.8  390.18    5000  395.97  5010.1   396.2  5030.1   395.3  5047.2  397.38
    5070  399.05  5180.5  406.16  5330.4  412.61    5401  414.15  5557.8  415.23
#Mann= 5 ,-1 , 0
  3990.2     .05       0  4482.6     .12       0  4987.2     .07       0
  4992.8     .12       0    5070     .05       0
Bank Sta=4987.2,4992.8
XS Rating Curve= 0 ,0
Exp/Cntr=0.3,0.1