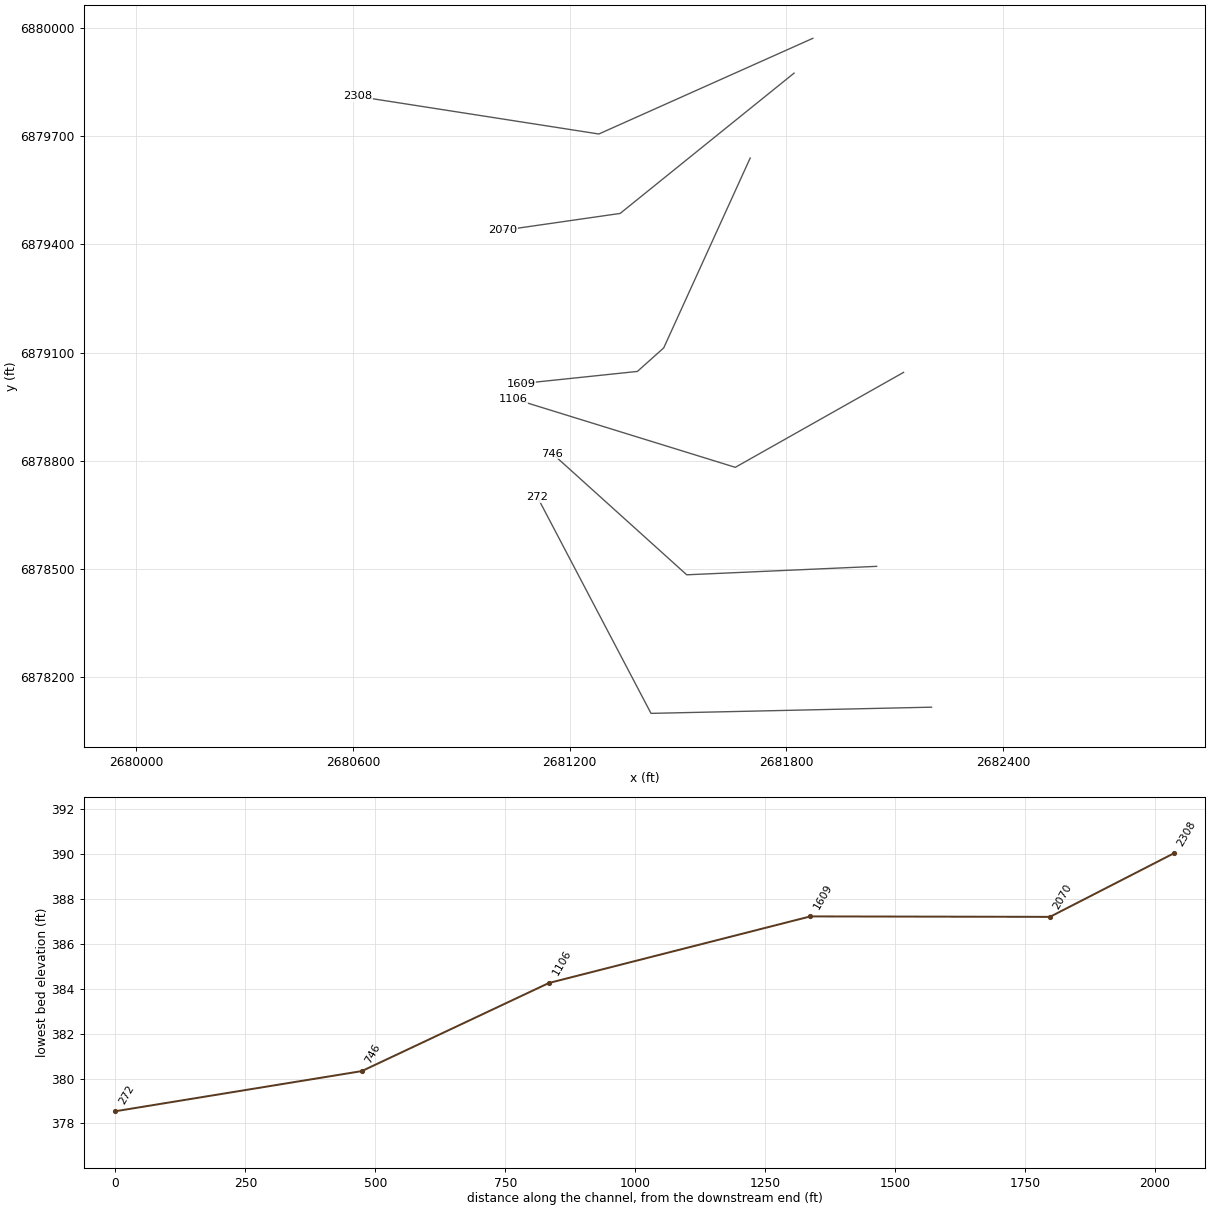
HEC-RAS study Walnut T5.prj: Walnut T5 Base Level Engineering

--- Walnut T5.g01 (geometry) --- (continued)

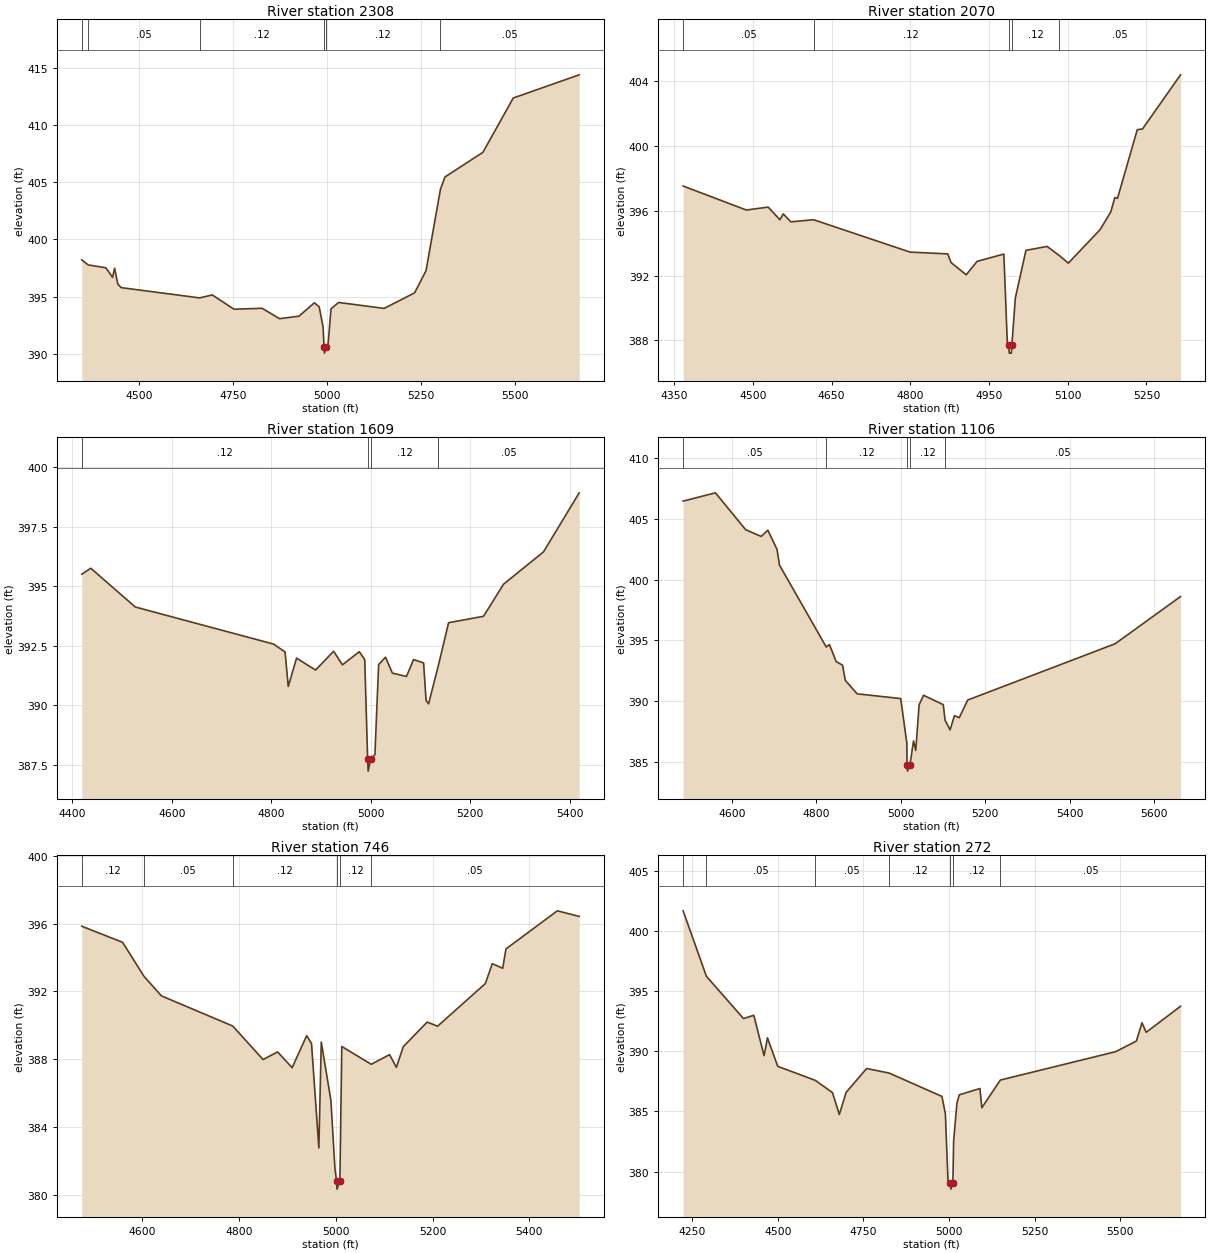
Type RM Length L Ch R = 1 ,2308    ,238,238,238
BEGIN DESCRIPTION:
Mapping XS 56035afd
END DESCRIPTION:
XS GIS Cut Line= 3
      2681873.63      6879970.46      2681280.85      6879705.47
      2680612.43      6879809.64
#Sta/Elev= 30
  4346.3  398.21  4363.4  397.77  4410.6  397.52  4428.3  396.68  4433.8  397.48
  4442.3  396.09  4451.5  395.78  4660.3  394.88  4694.2  395.14  4751.9  393.89
    4827  393.97  4873.4  393.06  4925.3  393.28  4966.2  394.45    4979   394.1
  4989.4  392.34  4992.1  390.54  4992.9  390.04  4997.7  390.54  5002.3  390.64
  5010.6  393.93  5030.9  394.48  5152.3  393.96  5233.3  395.32  5263.8  397.26
  5302.3   404.4  5314.3  405.48  5415.5  407.64  5496.4   412.4  5672.1  414.43
#Mann= 6 ,-1 , 0
  4346.3     .12       0  4363.4     .05       0  4660.3     .12       0
  4992.1     .07       0  4997.7     .12       0  5302.3     .05       0
Bank Sta=4992.1,4997.7
XS Rating Curve= 0 ,0
Exp/Cntr=0.3,0.1

Type RM Length L Ch R = 1 ,2070    ,461,461,461
BEGIN DESCRIPTION:
Mapping XS 3150a0b1
END DESCRIPTION:
XS GIS Cut Line= 3
      2681821.68      6879874.09      2681339.88      6879485.42
      2681014.37      6879438.55
#Sta/Elev= 30
  4367.2  397.53  4487.6  396.05  4529.3  396.23  4551.6  395.45    4558  395.81
  4572.4  395.32  4615.9  395.45  4799.6  393.45  4871.5  393.34  4877.9   392.8
  4906.7  392.05  4927.5  392.88  4978.4  393.33  4985.1  387.78  4987.7  387.71
  4988.7  387.21  4992.7  387.21  4993.7  387.71  5000.3  390.62  5020.5  393.56
  5060.9   393.8  5084.3  393.23  5101.3  392.77  5161.9  394.84  5182.1  395.93
  5189.9  396.82    5195  396.77  5232.6  401.01  5242.7  401.06  5315.1   404.4
#Mann= 5 ,-1 , 0
  4367.2     .05       0  4615.9     .12       0  4987.7     .07       0
  4993.7     .12       0  5084.3     .05       0
Bank Sta=4987.7,4993.7
XS Rating Curve= 0 ,0
Exp/Cntr=0.3,0.1

Type RM Length L Ch R = 1 ,1609    ,503,503,503
BEGIN DESCRIPTION:
Mapping XS 41496800
END DESCRIPTION:
XS GIS Cut Line= 4
      2681700.13      6879638.91      2681460.54      6879112.85
      2681387.62      6879047.75      2681064.69      6879013.89
#Sta/Elev= 30
  4418.7  395.51  4436.8  395.76  4526.3  394.13  4804.6  392.57  4827.6  392.24
    4834  390.79  4850.7  391.98  4888.9  391.48  4925.3  392.27  4942.9   391.7
  4976.9  392.25  4987.8  391.92  4993.7  387.73  4994.7  387.23  4999.7  387.73
  5008.3  387.93  5015.8  391.71  5029.6  392.02  5043.4  391.35  5071.8  391.21
    5086  391.92  5106.2  391.78  5111.2   390.2  5116.3  390.06  5135.9  391.67
  5156.5  393.47  5226.8  393.74  5267.1  395.09  5347.5  396.45  5419.2  398.93
#Mann= 4 ,-1 , 0
  4418.7     .12       0  4993.7     .07       0  4999.7     .12       0
  5135.9     .05       0
Bank Sta=4993.7,4999.7
XS Rating Curve= 0 ,0
Exp/Cntr=0.3,0.1

Type RM Length L Ch R = 1 ,1106    ,360,360,360
BEGIN DESCRIPTION:
Mapping XS f012decc
END DESCRIPTION:
XS GIS Cut Line= 3
      2682125.04      6879045.15      2681658.89      6878782.12
      2681044.26      6878972.24
#Sta/Elev= 30
  4484.3  406.44  4560.9  407.12  4632.5  404.09  4669.2  403.54  4685.1  404.05
  4706.8  402.47  4712.8  401.17  4823.5  394.45    4831  394.66  4846.9  393.26
  4862.1  392.96  4868.5  391.72  4896.6  390.61  4999.9  390.22  5014.4  386.55
  5014.9  384.76    5016  384.26  5021.7  384.76  5030.2  386.74  5035.5  385.96
  5043.5  389.71    5054  390.49  5100.7  389.72  5105.1  388.43  5116.8  387.65
  5127.2  388.82  5138.6  388.65  5158.6   390.1  5507.9  394.72  5662.9   398.6
#Mann= 5 ,-1 , 0
  4484.3     .05       0  4823.5     .12       0  5014.9     .07       0
  5021.7     .12       0  5105.1     .05       0
Bank Sta=5014.9,5021.7
XS Rating Curve= 0 ,0
Exp/Cntr=0.3,0.1

Type RM Length L Ch R = 1 ,746     ,474,474,474
BEGIN DESCRIPTION:
Mapping XS b3d42cbf
END DESCRIPTION:
XS GIS Cut Line= 3
      2682050.34      6878507.81      2681524.34      6878484.38
      2681151.91      6878820.35
#Sta/Elev= 30
  4474.9  395.85  4559.3   394.9  4603.3   392.9  4639.4  391.74  4786.8  389.96
  4849.6  387.98  4879.6  388.43  4909.7   387.5  4939.7  389.39  4949.7  388.93
  4964.9  382.76  4969.9  389.01  4989.8  385.57  4998.1  381.56  5001.4  380.83
  5002.5  380.33  5008.4  380.83  5012.3  388.75  5073.2   387.7    5111  388.27
  5125.2  387.52  5139.4  388.74  5188.7  390.19  5210.4  389.95  5309.1  392.47
  5323.3  393.64  5344.9  393.37  5351.6  394.51  5457.8  396.76    5503  396.43
#Mann= 6 ,-1 , 0
  4474.9     .12       0  4603.3     .05       0  4786.8     .12       0
  5001.4     .07       0  5008.4     .12       0  5073.2     .05       0
Bank Sta=5001.4,5008.4
XS Rating Curve= 0 ,0
Exp/Cntr=0.3,0.1

Type RM Length L Ch R = 1 ,272     ,0,0,0
BEGIN DESCRIPTION:
Walnut T5 1.0
END DESCRIPTION:
XS GIS Cut Line= 3
       2682202.5      6878117.71      2681425.39      6878100.53
      2681110.65      6878699.81
#Sta/Elev= 30
  4222.7  401.66  4290.8  396.22  4399.2  392.71  4429.3  392.98  4459.3  389.63
  4469.3  391.11  4499.3  388.74  4608.8  387.58  4659.3  386.56  4679.3  384.74
  4699.3  386.58  4759.3  388.56  4825.1  388.18  4979.4  386.24  4989.4  384.79
  4997.2   379.1  5004.3  379.04  5005.4  378.54  5011.3  379.04  5013.5  382.54
  5023.1  385.67  5029.9  386.37  5090.4   386.9    5096   385.3  5150.1   387.6
  5487.2  389.96  5547.7  390.84  5564.1  392.36  5576.6  391.57  5676.9  393.73
#Mann= 7 ,-1 , 0
  4222.7     .05       0  4290.8     .05       0  4608.8     .05       0
  4825.1     .12       0  5004.3     .07       0  5011.3     .12       0
  5150.1     .05       0
Bank Sta=5004.3,5011.3
XS Rating Curve= 0 ,0
Exp/Cntr=0.3,0.1

Chan Stop Cuts=-1
Use User Specified Reach Order=0
Composite Channel Slope=5