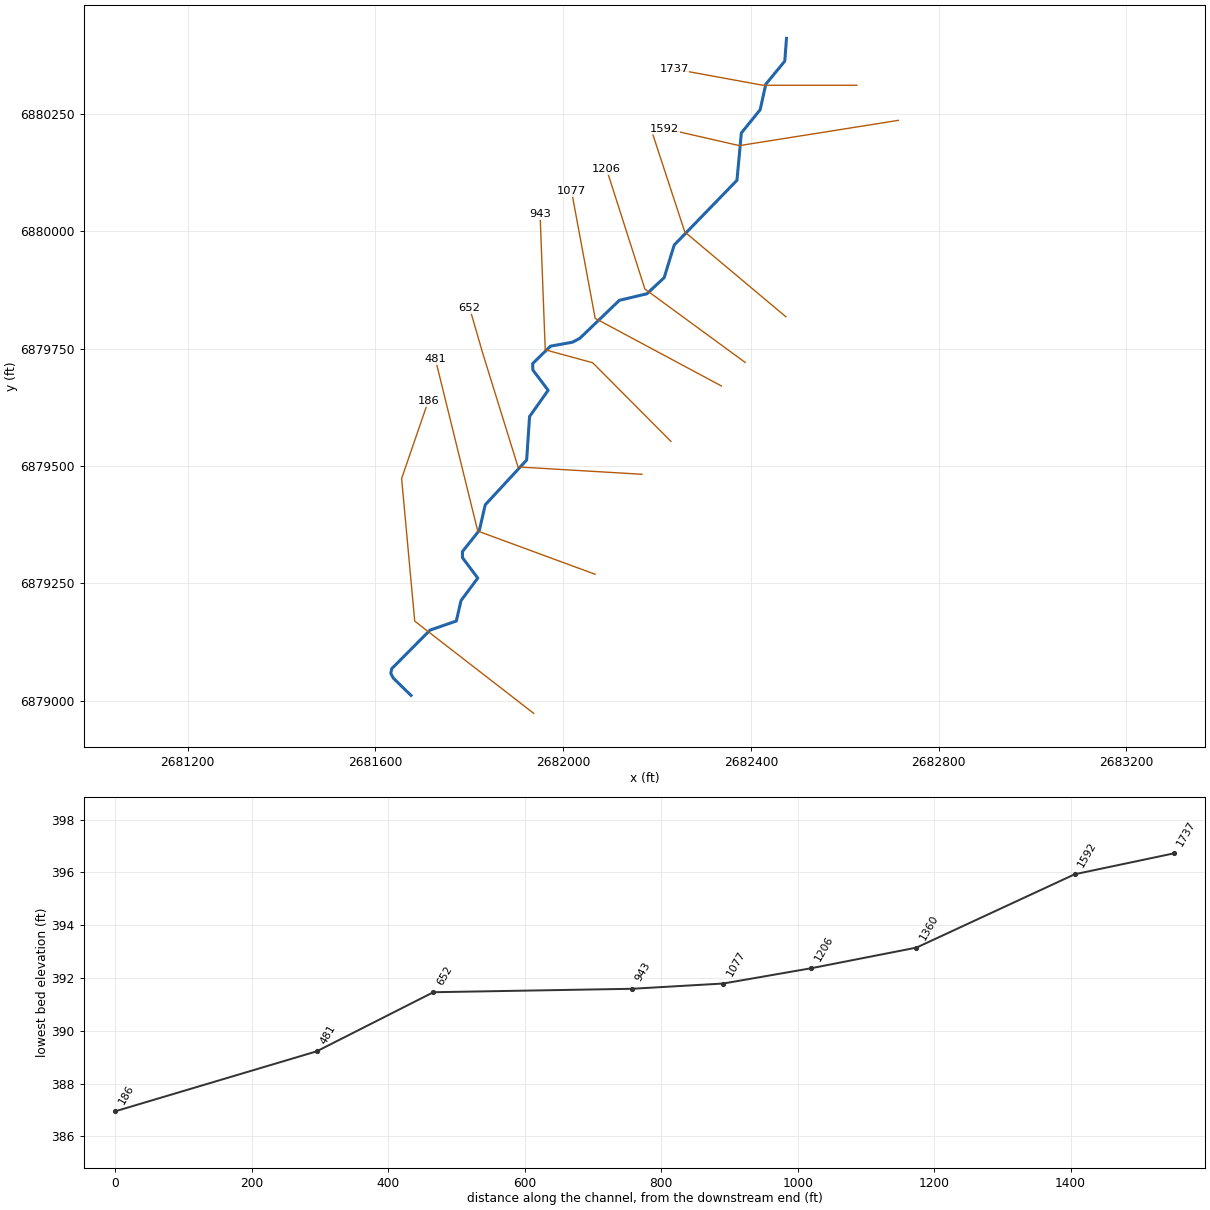
--- Walnut T5_1.prj (project) ---

Proj Title=Walnut T5_1 Base Level Engineering
Current Plan=p01
Default Exp/Contr=0.3,0.1
English Units
Geom File=g01
Flow File=f01
Plan File=p01
Y Axis Title=Elevation
X Axis Title(PF)=Main Channel Distance
X Axis Title(XS)=Station
BEGIN DESCRIPTION:
Walnut T5_1
END DESCRIPTION:
DSS Export Rating Curves= 0
DSS Export Rating Curve Sorted= 0
DSS Export Volume Flow Curves= 0
DXF OffsetX= 0
DXF OffsetY= 0
DXF ScaleX= 1
DXF ScaleY= 10

--- Walnut T5_1.p01 (plan) ---

Plan Title=Multiple Run
Short Identifier=Multiple
Geom File=g01
Flow File=f01
Subcritical Flow
K Sum by GR= 0
Std Step Tol= 0.01
Critical Tol= 0.01
Num of Std Step Trials= 20
Max Error Tol= 0.3
Flow Tol Ratio= 0.001
Split Flow NTrial= 30
Split Flow Tol= 0.02
Split Flow Ratio= 0.02
Log Output Level= 0
Friction Slope Method= 1
Unsteady Friction Slope Method= 2
Unsteady Bridges Friction Slope Method= 1
Parabolic Critical Depth
Global Vel Dist=  1 , 1 , 1
Global Log Level= 0
CheckData=True
Encroach Param= -1, 0, 0, 0
BEGIN DESCRIPTION:
Multiple Run
END DESCRIPTION:

--- Walnut T5_1.f01 (steady flow) ---

Flow Title=Multiple
Number of Profiles=7
Profile Names=10-year,25-year,50-year,1pct_min,100-year,1pct_plu,500-year
River Rch & RM= Walnut T5_1,Reach-1,1737
     321     415     490     287     573    1144     784
Boundary for River Rch & Prof#=Walnut T5_1,Reach-1,1
Up Type=0
Dn Type=3
Dn Slope=0.005
Boundary for River Rch & Prof#=Walnut T5_1,Reach-1,2
Up Type=0
Dn Type=3
Dn Slope=0.005
Boundary for River Rch & Prof#=Walnut T5_1,Reach-1,3
Up Type=0
Dn Type=3
Dn Slope=0.005
Boundary for River Rch & Prof#=Walnut T5_1,Reach-1,4
Up Type=0
Dn Type=3
Dn Slope=0.005
Boundary for River Rch & Prof#=Walnut T5_1,Reach-1,5
Up Type=0
Dn Type=3
Dn Slope=0.005
Boundary for River Rch & Prof#=Walnut T5_1,Reach-1,6
Up Type=0
Dn Type=3
Dn Slope=0.005
Boundary for River Rch & Prof#=Walnut T5_1,Reach-1,7
Up Type=0
Dn Type=3
Dn Slope=0.005

--- Walnut T5_1.g01 (geometry) ---

Geom Title=Existing Conditions

River Reach=Walnut T5_1,Reach-1
Reach XY= 30
      2682476.00      6880411.00      2682472.40      6880362.49
      2682431.95      6880313.25      2682419.90      6880258.81
      2682379.83      6880209.41      2682370.48      6880108.57
      2682236.79      6879970.66      2682215.35      6879901.00
      2682178.54      6879866.75      2682119.98      6879852.82
      2682035.64      6879771.80      2682019.87      6879763.54
      2681973.17      6879755.15      2681935.18      6879717.95
      2681935.53      6879704.50      2681968.19      6879661.11
      2681928.55      6879605.11      2681922.38      6879512.50
      2681834.14      6879417.04      2681821.56      6879362.65
      2681785.58      6879317.55      2681785.75      6879304.28
      2681818.25      6879261.05      2681782.54      6879212.96
      2681772.53      6879169.50      2681716.55      6879150.12
      2681634.76      6879067.69      2681632.94      6879057.68
      2681638.50      6879047.67      2681676.00      6879011.00

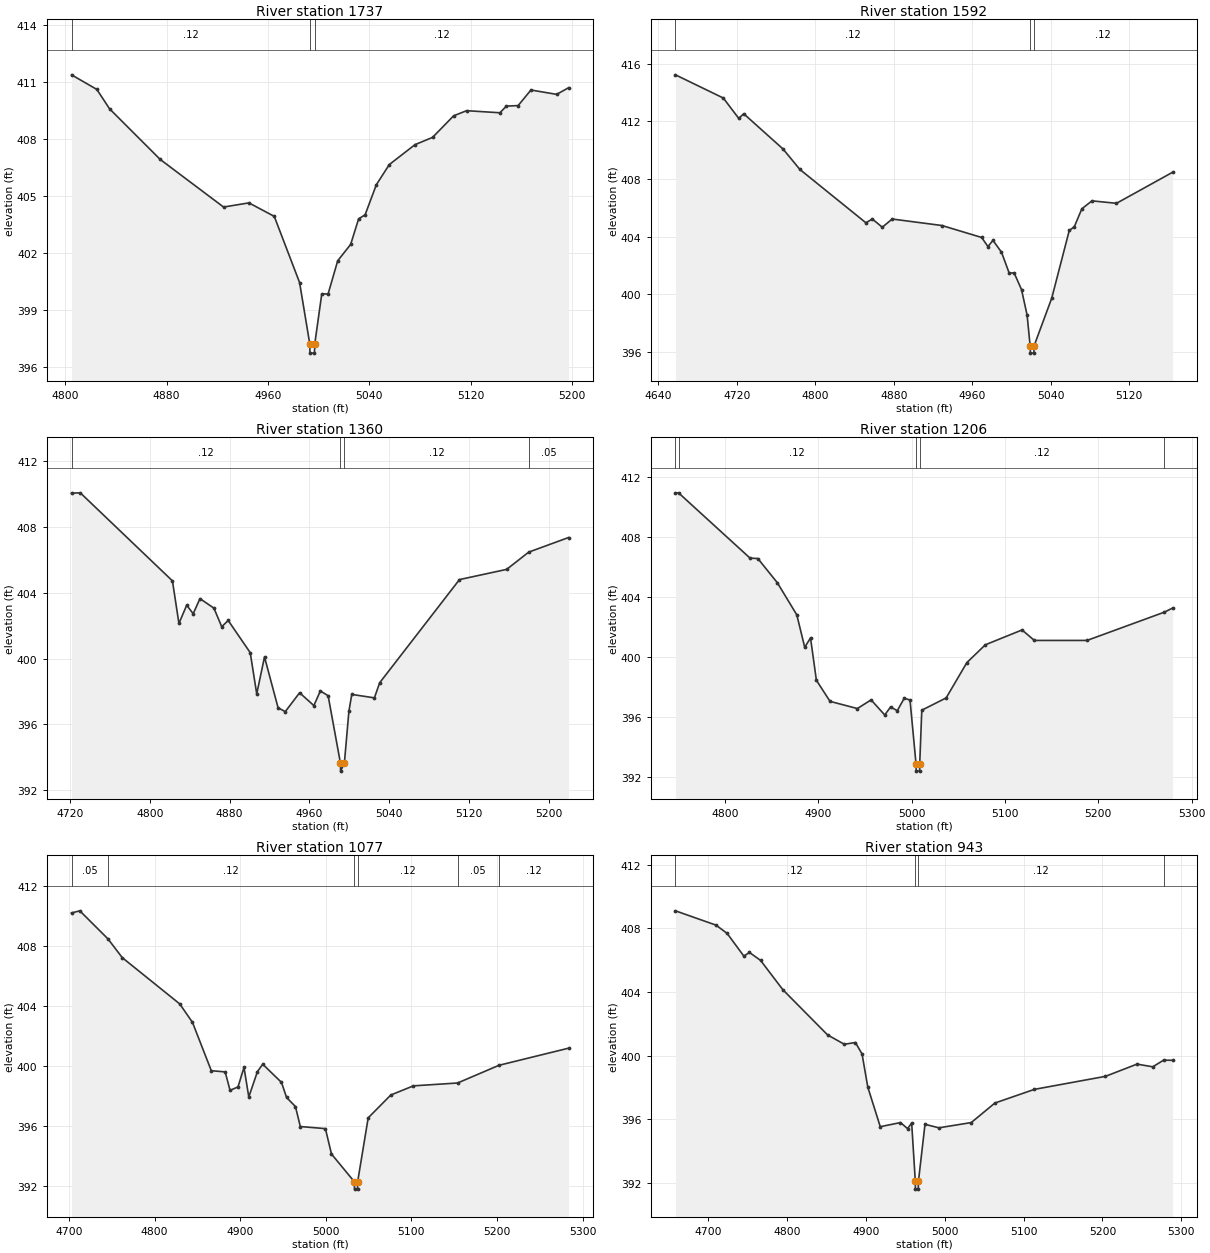
Type RM Length L Ch R = 1,1737,145,145,145
BEGIN DESCRIPTION:
Walnut T5_1 2.0
END DESCRIPTION:
XS GIS Cut Line= 3
      2682625.97      6880311.00      2682426.00      6880311.00
      2682236.80      6880345.59
#Sta/Elev= 30
  4804.9  411.39  4824.9  410.62  4834.9  409.60  4874.9  406.93  4924.9  404.42
  4944.9  404.64  4964.9  403.93  4984.9  400.44  4992.9  397.22  4993.1  396.72
  4996.6  396.72  4996.9  397.22  5002.4  399.84  5007.4  399.84  5015.0  401.59
  5025.2  402.45  5031.5  403.80  5036.6  404.01  5045.5  405.60  5055.7  406.66
  5076.0  407.71  5089.8  408.09  5106.5  409.23  5116.7  409.50  5143.0  409.39
  5148.1  409.74  5157.4  409.77  5167.5  410.59  5187.8  410.36  5197.2  410.71
#Mann=3,-1,0
  4804.9    0.12       0  4992.9    0.07       0  4996.9    0.12       0
Bank Sta=4992.9,4996.9
Exp/Cntr=0.3,0.1

Type RM Length L Ch R = 1,1592,232,232,232
BEGIN DESCRIPTION:
Mapping XS 64217d29
END DESCRIPTION:
XS GIS Cut Line= 3
      2682714.20      6880236.22      2682375.68      6880182.40
      2682215.96      6880218.86
#Sta/Elev= 30
  4657.5  415.23  4706.3  413.62  4722.0  412.21  4727.1  412.53  4767.1  410.09
  4784.3  408.67  4851.6  404.97  4858.2  405.23  4868.3  404.66  4878.4  405.23
  4929.1  404.78  4969.6  403.95  4976.0  403.32  4981.1  403.75  4989.8  402.93
  4997.6  401.49  5002.7  401.49  5010.2  400.34  5015.9  398.57  5019.0  396.43
  5019.3  395.93  5022.8  395.93  5023.0  396.43  5041.0  399.74  5058.9  404.44
  5064.0  404.69  5071.7  405.94  5082.0  406.49  5107.0  406.32  5164.1  408.47
#Mann=3,-1,0
  4657.5    0.12       0  5019.0    0.07       0  5023.0    0.12       0
Bank Sta=5019,5023
Exp/Cntr=0.3,0.1

Type RM Length L Ch R = 1,1360,154,154,154
BEGIN DESCRIPTION:
Mapping XS 262799ab
END DESCRIPTION:
XS GIS Cut Line= 3
      2682474.67      6879817.79      2682259.36      6879998.37
      2682191.66      6880204.94
#Sta/Elev= 30
  4721.5  410.07  4730.3  410.09  4822.7  404.73  4829.2  402.14  4837.0  403.25
  4843.5  402.73  4850.3  403.65  4864.3  403.07  4872.1  401.94  4878.6  402.32
  4900.7  400.36  4907.2  397.85  4915.0  400.10  4928.6  397.01  4935.8  396.77
  4950.2  397.92  4964.5  397.14  4971.0  398.03  4978.8  397.74  4991.1  393.65
  4991.3  393.15  4995.1  393.65  4999.6  396.78  5002.5  397.82  5025.2  397.61
  5030.5  398.53  5110.5  404.81  5157.8  405.43  5179.9  406.48  5219.9  407.37
#Mann=4,-1,0
  4721.5    0.12       0  4991.1    0.07       0  4995.1    0.12       0
  5179.9    0.05       0
Bank Sta=4991.1,4995.1
Exp/Cntr=0.3,0.1

Type RM Length L Ch R = 1,1206,129,129,129
BEGIN DESCRIPTION:
Mapping XS a426d3b3
END DESCRIPTION:
XS GIS Cut Line= 3
      2682387.84      6879720.59      2682174.29      6879876.85
      2682092.71      6880132.01
#Sta/Elev= 30
  4747.0  410.96  4750.3  410.96  4826.9  406.60  4835.3  406.57  4856.2  404.95
  4877.0  402.81  4885.5  400.64  4891.7  401.27  4898.0  398.44  4912.6  397.03
  4941.9  396.55  4956.6  397.13  4971.2  396.12  4977.4  396.65  4984.7  396.41
  4992.1  397.24  4998.3  397.12  5004.7  392.87  5005.0  392.37  5008.5  392.37
  5008.7  392.87  5010.9  396.44  5037.0  397.26  5059.2  399.62  5079.0  400.81
  5118.3  401.80  5131.5  401.10  5187.9  401.10  5270.8  402.99  5279.5  403.26
#Mann=5,-1,0
  4747.0    0.05       0  4750.3    0.12       0  5004.7    0.07       0
  5008.7    0.12       0  5270.8    0.05       0
Bank Sta=5004.7,5008.7
Exp/Cntr=0.3,0.1

Type RM Length L Ch R = 1,1077,134,134,134
BEGIN DESCRIPTION:
Mapping XS 4a821486
END DESCRIPTION:
XS GIS Cut Line= 3
      2682337.45      6879670.27      2682068.39      6879814.35
      2682018.04      6880085.19
#Sta/Elev= 30
  4702.9  410.19  4712.6  410.33  4745.5  408.46  4762.2  407.21  4829.3  404.13
  4844.2  402.90  4866.2  399.68  4882.4  399.60  4888.1  398.37  4897.4  398.60
  4904.4  399.90  4910.0  397.93  4920.1  399.62  4926.3  400.11  4948.2  398.90
  4954.1  397.90  4964.5  397.29  4970.2  395.96  4999.5  395.82  5006.6  394.13
  5033.2  392.29  5033.5  391.79  5037.0  391.79  5037.2  392.29  5049.5  396.54
  5075.9  398.06  5102.3  398.67  5153.9  398.86  5202.3  400.04  5283.6  401.18
#Mann=6,-1,0
  4702.9    0.05       0  4745.5    0.12       0  5033.2    0.07       0
  5037.2    0.12       0  5153.9    0.05       0  5202.3    0.12       0
Bank Sta=5033.2,5037.2
Exp/Cntr=0.3,0.1

Type RM Length L Ch R = 1,943,291,291,291
BEGIN DESCRIPTION:
Mapping XS 98210ff4
END DESCRIPTION:
XS GIS Cut Line= 4
      2682229.84      6879552.20      2682063.03      6879719.82
      2681962.00      6879747.37      2681951.00      6880035.96
#Sta/Elev= 30
  4658.8  409.11  4710.2  408.21  4724.3  407.69  4745.5  406.26  4752.6  406.49
  4766.7  405.99  4795.0  404.14  4851.6  401.30  4872.8  400.71  4886.9  400.82
  4895.3  400.10  4902.6  398.01  4918.4  395.52  4944.0  395.78  4953.0  395.40
  4958.2  395.75  4962.8  392.09  4963.0  391.59  4966.5  391.59  4966.8  392.09
  4975.1  395.67  4992.7  395.45  5033.7  395.78  5063.7  397.01  5113.7  397.87
  5203.8  398.69  5243.8  399.46  5263.8  399.29  5277.5  399.71  5288.8  399.70
#Mann=4,-1,0
  4658.8    0.12       0  4962.8    0.07       0  4966.8    0.12       0
  5277.5    0.05       0
Bank Sta=4962.8,4966.8
Exp/Cntr=0.3,0.1

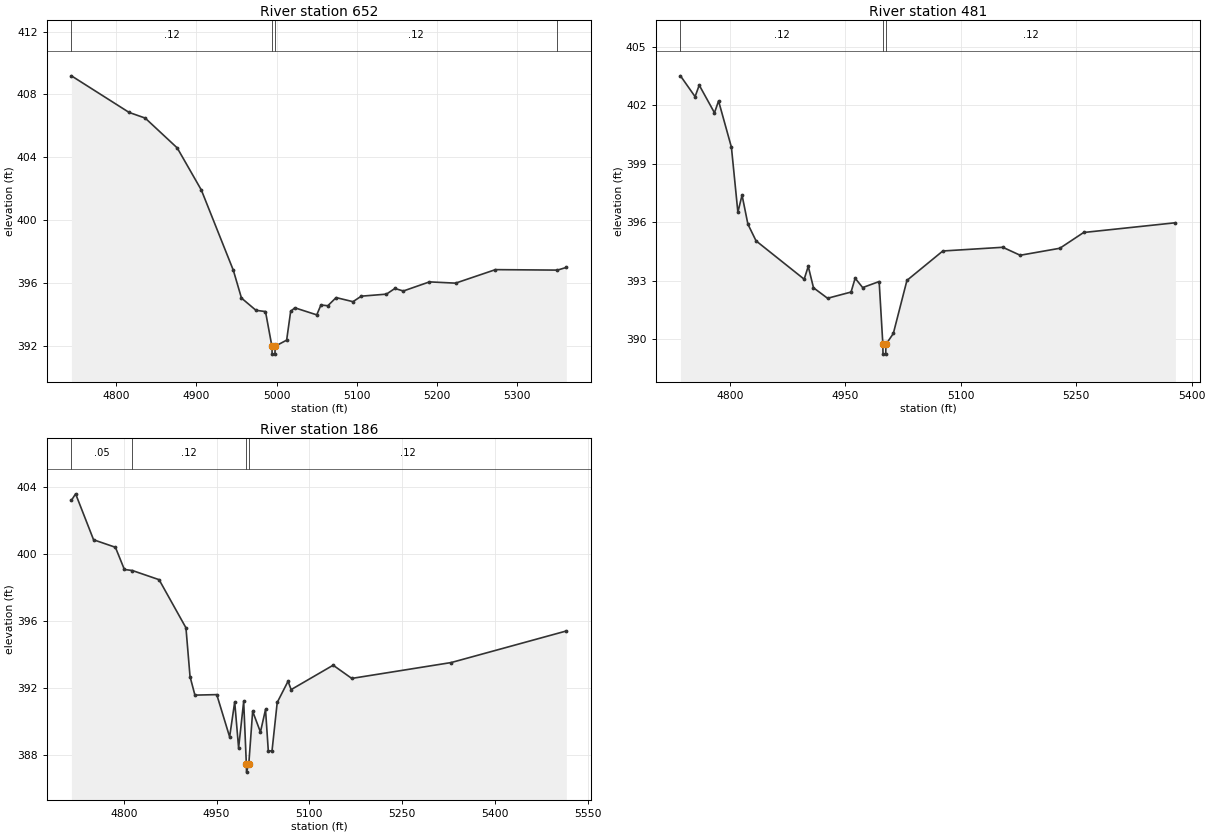
Type RM Length L Ch R = 1,652,171,171,171
BEGIN DESCRIPTION:
Mapping XS d8b75160
END DESCRIPTION:
XS GIS Cut Line= 4
      2682167.89      6879482.20      2681903.98      6879497.82
      2681828.95      6879739.59      2681801.00      6879836.00
#Sta/Elev= 30
  4743.9  409.18  4815.9  406.85  4836.0  406.49  4876.0  404.59  4906.1  401.91
  4946.1  396.79  4956.2  395.03  4974.3  394.25  4986.2  394.17  4994.2  391.96
  4994.5  391.46  4998.0  391.46  4998.2  391.96  5012.6  392.35  5017.6  394.18
  5022.8  394.41  5050.2  393.96  5055.4  394.59  5064.0  394.54  5074.4  395.06
  5095.4  394.80  5105.8  395.15  5137.2  395.28  5147.7  395.64  5158.3  395.48
  5190.9  396.06  5223.5  395.98  5273.3  396.84  5350.7  396.81  5361.8  396.98
#Mann=4,-1,0
  4743.9    0.12       0  4994.2    0.07       0  4998.2    0.12       0
  5350.7    0.05       0
Bank Sta=4994.2,4998.2
Exp/Cntr=0.3,0.1

Type RM Length L Ch R = 1,481,295,295,295
BEGIN DESCRIPTION:
Mapping XS 996d2b83
END DESCRIPTION:
XS GIS Cut Line= 3
      2682068.17      6879269.17      2681818.18      6879361.18
      2681728.09      6879726.76
#Sta/Elev= 30
  4736.0  403.52  4755.0  402.45  4760.4  403.04  4780.2  401.62  4785.5  402.23
  4802.2  399.85  4810.6  396.51  4816.0  397.39  4823.6  395.90  4834.2  395.04
  4896.7  393.07  4902.0  393.73  4908.8  392.63  4927.1  392.09  4957.6  392.41
  4962.9  393.12  4972.7  392.64  4994.1  392.95  4998.9  389.72  4999.1  389.22
  5002.6  389.22  5002.9  389.72  5012.5  390.28  5030.2  393.01  5076.8  394.52
  5154.7  394.71  5177.3  394.30  5228.8  394.66  5259.7  395.47  5378.9  395.97
#Mann=3,-1,0
  4736.0    0.12       0  4998.9    0.07       0  5002.9    0.12       0
Bank Sta=4998.9,5002.9
Exp/Cntr=0.3,0.1

Type RM Length L Ch R = 1,186,0,0,0
BEGIN DESCRIPTION:
Walnut T5_1 1.0
END DESCRIPTION:
XS GIS Cut Line= 4
      2681937.52      6878972.74      2681683.90      6879169.26
      2681656.00      6879473.06      2681712.60      6879637.56
#Sta/Elev= 30
  4715.5  403.22  4722.3  403.61  4751.3  400.86  4786.6  400.41  4801.1  399.08
  4813.9  399.02  4857.2  398.47  4900.6  395.59  4907.2  392.67  4915.1  391.56
  4950.4  391.59  4971.2  389.06  4979.4  391.15  4985.7  388.40  4993.9  391.18
  4998.2  387.45  4998.5  386.95  5002.2  387.45  5008.4  390.59  5021.0  389.35
  5029.2  390.70  5033.7  388.22  5039.7  388.22  5048.1  391.12  5065.6  392.39
  5070.6  391.89  5138.5  393.35  5168.6  392.56  5329.3  393.51  5515.4  395.40
#Mann=4,-1,0
  4715.5    0.05       0  4813.9    0.12       0  4998.2    0.07       0
  5002.2    0.12       0
Bank Sta=4998.2,5002.2
Exp/Cntr=0.3,0.1

Chan Stop Cuts=-1