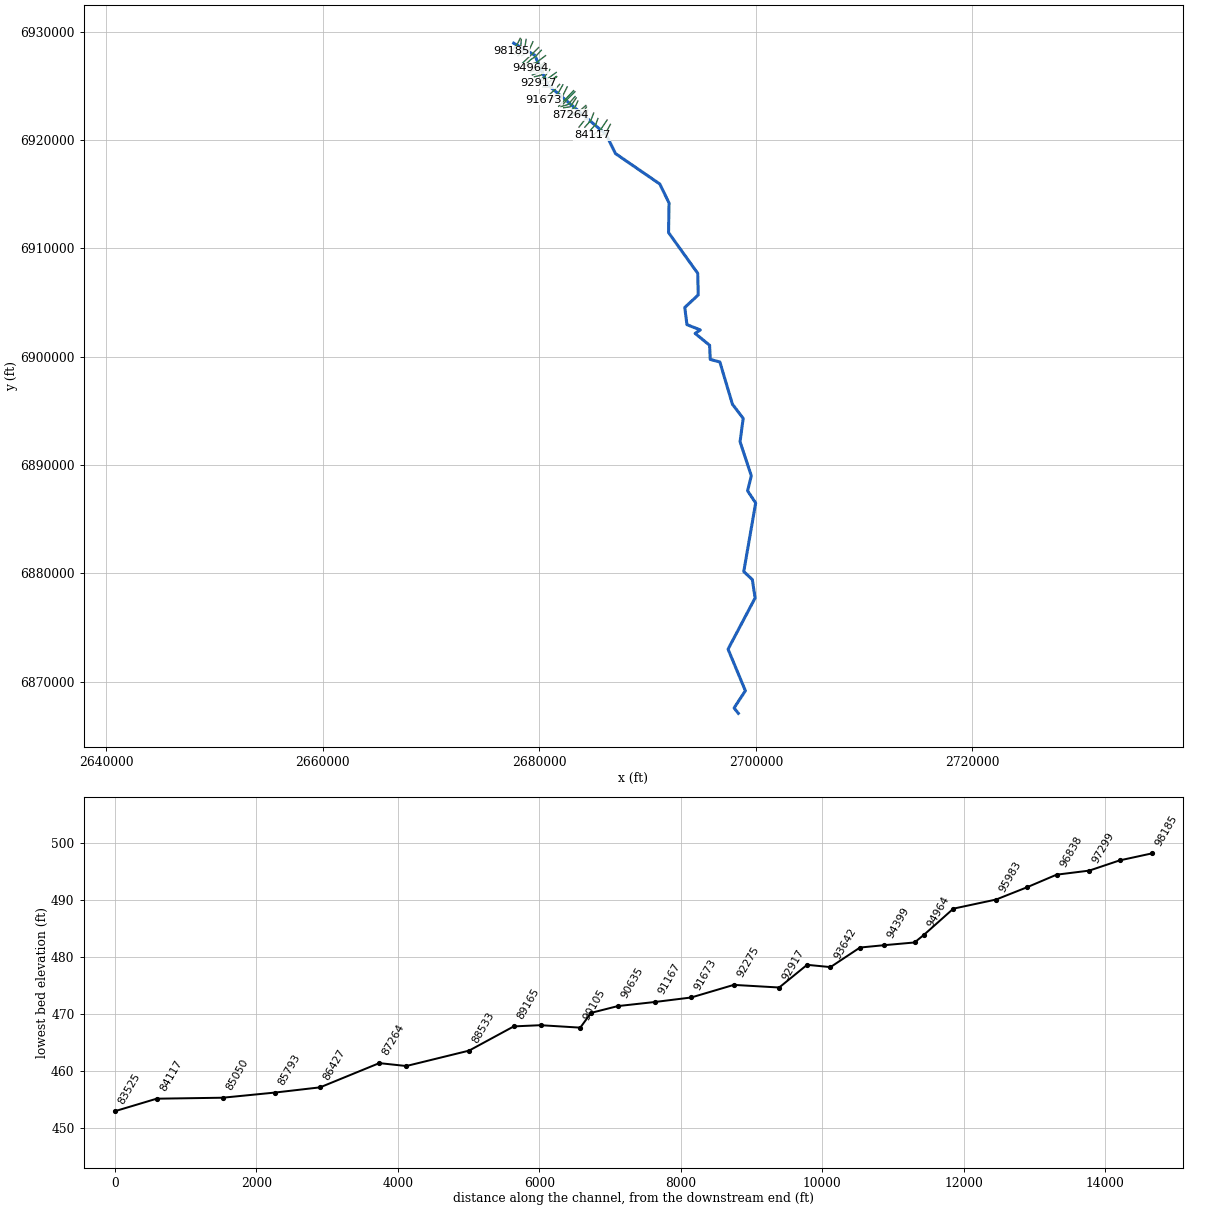
--- Williams Creek.prj (project) ---

Proj Title=Williams Creek Base Level Engineering
Current Plan=p01
Default Exp/Contr=0.3,0.1
English Units
Geom File=g01
Flow File=f01
Plan File=p01
Y Axis Title=Elevation
X Axis Title(PF)=Main Channel Distance
X Axis Title(XS)=Station
BEGIN DESCRIPTION:
Williams Creek
END DESCRIPTION:
DSS Export Rating Curves= 0
DSS Export Rating Curve Sorted= 0
DSS Export Volume Flow Curves= 0
DXF OffsetX= 0
DXF OffsetY= 0
DXF ScaleX= 1
DXF ScaleY= 10

--- Williams Creek.p01 (plan) ---

Plan Title=Multiple Run
Short Identifier=Multiple
Geom File=g01
Flow File=f01
Subcritical Flow
K Sum by GR= 0
Std Step Tol= 0.01
Critical Tol= 0.01
Num of Std Step Trials= 20
Max Error Tol= 0.3
Flow Tol Ratio= 0.001
Split Flow NTrial= 30
Split Flow Tol= 0.02
Split Flow Ratio= 0.02
Log Output Level= 0
Friction Slope Method= 1
Unsteady Friction Slope Method= 2
Unsteady Bridges Friction Slope Method= 1
Parabolic Critical Depth
Global Vel Dist=  1 , 1 , 1
Global Log Level= 0
CheckData=True
Encroach Param= -1, 0, 0, 0
BEGIN DESCRIPTION:
Multiple Run
END DESCRIPTION:

--- Williams Creek.f01 (steady flow) ---

Flow Title=Multiple
Program Version=4.10
Number of Profiles= 7
Profile Names=10-year,25-year,50-year,1pct_min,100-year,1pct_plu,500-year
River Rch & RM=Williams Creek,Reach-1         ,98185
     600     805     971     582    1161    2316    1657
River Rch & RM=Williams Creek,Reach-1         ,95379
     948    1304    1599     971    1938    3866    2846
River Rch & RM=Williams Creek,Reach-1         ,91673
    1363    1912    2374    1459    2911    5809    4379
River Rch & RM=Williams Creek,Reach-1         ,90635
    1483    2081    2585    1588    3168    6322    4763
River Rch & RM=Williams Creek,Reach-1         ,86427
    1869    2639    3292    2028    4046    8074    6119
River Rch & RM=Williams Creek,Reach-1         ,77648
    2318    3302    4142    2564    5117   10209    7816
River Rch & RM=Williams Creek,Reach-1         ,75749
    2520    3600    4526    2808    5602   11178    8591
River Rch & RM=Williams Creek,Reach-1         ,73180
    2672    3819    4802    2979    5943   11858    9112
River Rch & RM=Williams Creek,Reach-1         ,68400
    2723    3886    4880    3023    6032   12035    9222
River Rch & RM=Williams Creek,Reach-1         ,65415
    3110    4455    5610    3482    6948   13864   10668
River Rch & RM=Williams Creek,Reach-1         ,59782
    3132    4480    5634    3493    6970   13907   10674
River Rch & RM=Williams Creek,Reach-1         ,50049
    4249    6137    7771    4846    9669   19293   14982
River Rch & RM=Williams Creek,Reach-1         ,43713
    4353    6286    7958    4962    9900   19754   15334
River Rch & RM=Williams Creek,Reach-1         ,38825
    4364    6291    7956    4954    9884   19721   15268
River Rch & RM=Williams Creek,Reach-1         ,30011
    4552    6570    8314    5180   10336   20623   15985
River Rch & RM=Williams Creek,Reach-1         ,29435
    5041    7288    9235    5760   11493   22931   17809
River Rch & RM=Williams Creek,Reach-1         ,19883
    5128    7414    9393    5858   11687   23320   18105
River Rch & RM=Williams Creek,Reach-1         ,18550
    5318    7690    9745    6078   12128   24198   18791
River Rch & RM=Williams Creek,Reach-1         ,11131
    5492    7945   10071    6283   12535   25012   19428
River Rch & RM=Williams Creek,Reach-1         ,8883
    5457    7880    9976    6214   12399   24740   19164
Boundary for River Rch & Prof#=Williams Creek,Reach-1         , 1
Up Type= 0
Dn Type= 3
Dn Slope=0.00054
Boundary for River Rch & Prof#=Williams Creek,Reach-1         , 2
Up Type= 0
Dn Type= 3
Dn Slope=0.00054
Boundary for River Rch & Prof#=Williams Creek,Reach-1         , 3
Up Type= 0
Dn Type= 3
Dn Slope=0.00054
Boundary for River Rch & Prof#=Williams Creek,Reach-1         , 4
Up Type= 0
Dn Type= 3
Dn Slope=0.00054
Boundary for River Rch & Prof#=Williams Creek,Reach-1         , 5
Up Type= 0
Dn Type= 3
Dn Slope=0.00054
Boundary for River Rch & Prof#=Williams Creek,Reach-1         , 6
Up Type= 0
Dn Type= 3
Dn Slope=0.00054
Boundary for River Rch & Prof#=Williams Creek,Reach-1         , 7
Up Type= 0
Dn Type= 3
Dn Slope=0.00054
DSS Import GetInterval= 0
DSS Import GetPeak= 0
DSS Import FillOption= 0

--- Williams Creek.g01 (geometry) ---

Geom Title=Existing Conditions
Program Version=4.10

River Reach=Williams Creek  ,Reach-1
Reach XY= 30
        2677626.        6928961.      2679570.42      6927855.42
      2680780.76      6925116.58      2686152.98      6920534.47
        2687031.      6918766.01      2691120.82      6915955.56
       2691975.3       6914200.3      2691928.84      6911469.01
      2694622.57      6907709.78      2694672.96      6905712.42
       2693427.2       6904550.5      2693627.95      6902966.49
      2694859.85      6902477.57      2694383.46      6902157.44
      2695720.94      6901063.32      2695781.28      6899758.29
      2696670.63      6899513.77      2697829.53      6895612.45
      2698822.69      6894309.27      2698533.81      6892157.59
      2699575.01      6889000.72      2699228.19      6887616.91
      2699976.07      6886492.88        2698876.        6880161.
      2699667.12      6879417.49      2699924.98      6877721.42
      2697426.07      6872990.97       2699025.3      6869150.24
      2697983.77      6867564.44        2698376.        6867061.

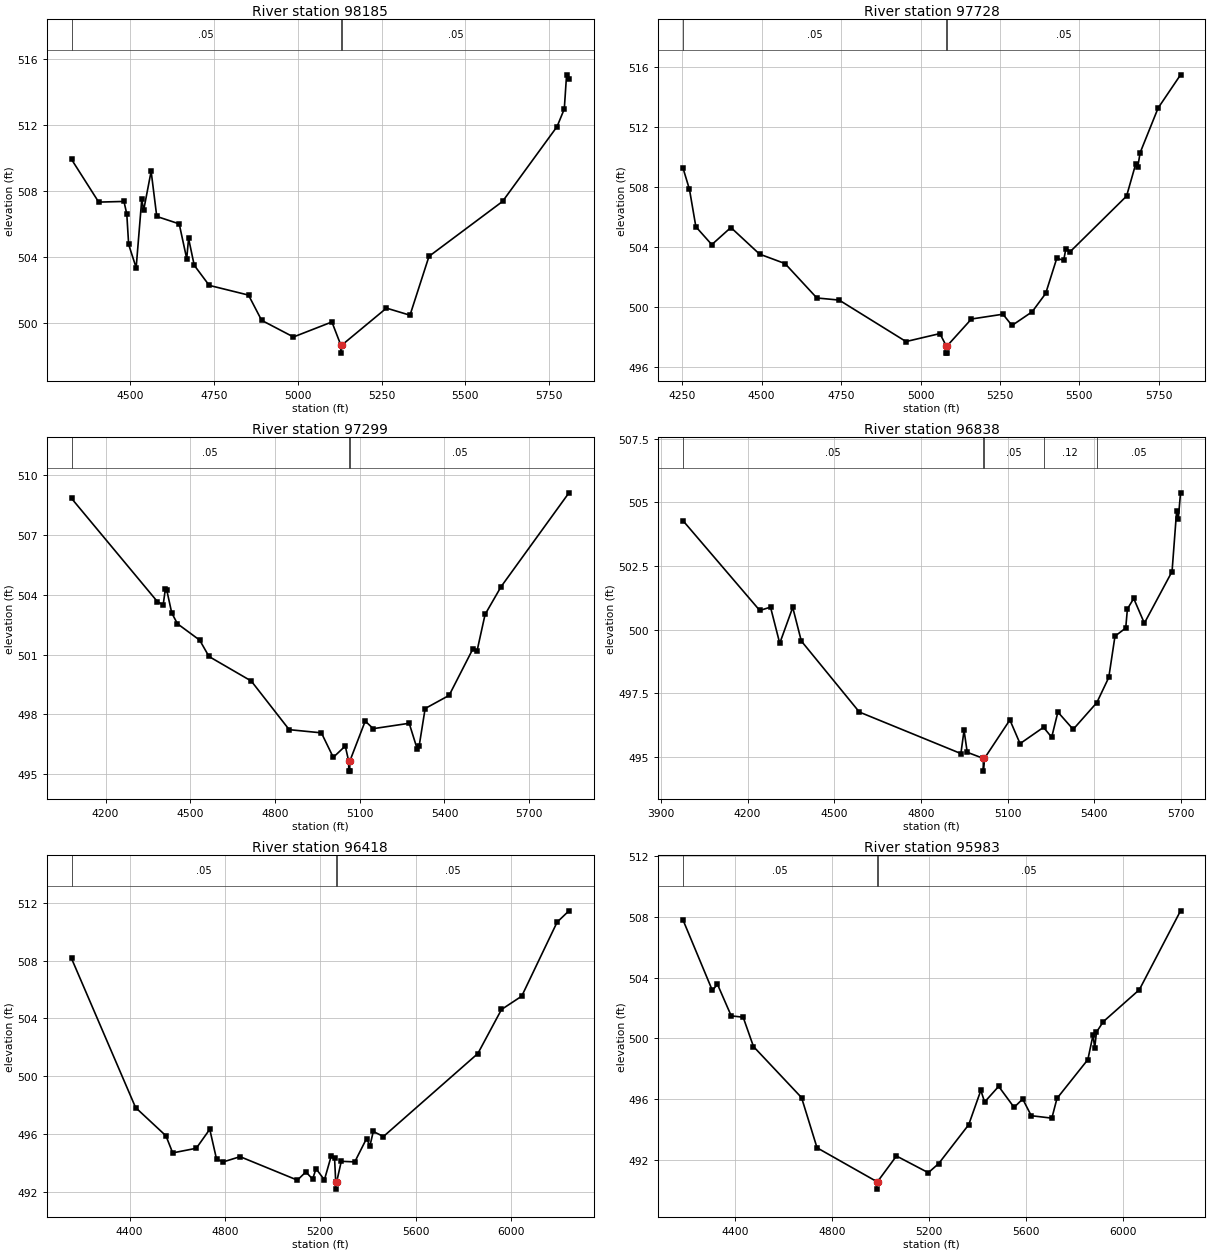
Type RM Length L Ch R = 1 ,98185   ,457,457,457
BEGIN DESCRIPTION:
Williams Creek 148.0
END DESCRIPTION:
XS GIS Cut Line= 3
        2678226.        6929411.        2677926.        6928811.
      2677375.98      6928210.98
#Sta/Elev= 30
  4324.5  509.92  4405.6  507.33    4481  507.37  4489.4  506.61    4495  504.76
  4517.4  503.35  4534.1   507.5  4539.7  506.83  4562.1   509.2  4578.9  506.46
  4645.9  506.01  4668.3   503.9  4673.9  505.13  4690.7   503.5  4735.4  502.28
  4852.8  501.69  4891.9  500.16  4986.9  499.15  5101.7  500.06  5128.1  498.67
  5128.3  498.17  5132.1  498.67  5264.5   500.9  5334.8  500.47  5391.5  504.04
    5611  507.37  5773.8  511.91  5795.4  512.98  5802.2  515.05  5809.3  514.77
#Mann= 3 ,-1 , 0
  4324.5     .05       0  5128.1     .03       0  5132.1     .05       0
Bank Sta=5128.1,5132.1
XS Rating Curve= 0 ,0
Exp/Cntr=0.3,0.1

Type RM Length L Ch R = 1 ,97728   ,429,429,429
BEGIN DESCRIPTION:
Williams Creek 147.0
END DESCRIPTION:
XS GIS Cut Line= 3
        2678326.      6929310.99        2678276.        6928561.
        2677726.        6927961.
#Sta/Elev= 30
  4252.8  509.23  4272.8  507.83  4292.9  505.35    4343  504.16  4403.1   505.3
  4493.3  503.53  4573.5   502.9  4673.7  500.61  4743.9  500.47  4954.3  497.71
  5060.9  498.24  5080.5  497.44  5080.7  496.94  5084.2  496.94  5084.5  497.44
  5160.2  499.21  5259.4  499.53  5287.8  498.78  5351.3  499.69  5393.9  500.91
    5429  503.26  5450.6  503.11  5457.4  503.89  5471.5   503.7  5648.5  507.39
  5676.9   509.5  5683.7  509.32  5691.1  510.27  5747.8  513.25  5818.4  515.46
#Mann= 3 ,-1 , 0
  4252.8     .05       0  5080.5     .03       0  5084.5     .05       0
Bank Sta=5080.5,5084.5
XS Rating Curve= 0 ,0
Exp/Cntr=0.3,0.1

Type RM Length L Ch R = 1 ,97299   ,461,461,461
BEGIN DESCRIPTION:
Williams Creek 146.0
END DESCRIPTION:
XS GIS Cut Line= 3
        2678776.        6929311.        2678626.        6928411.
      2678026.03      6927811.03
#Sta/Elev= 30
  4079.7  508.83  4383.8  503.65  4404.1  503.49  4411.7  504.27  4416.8  504.23
  4434.5  503.08  4454.8  502.54  4533.4  501.72  4566.3   500.9  4715.9  499.67
  4850.2  497.23  4964.2  497.07  5006.3  495.84  5048.7  496.41  5060.8  495.65
  5061.1  495.15  5064.6  495.15  5064.8  495.65  5119.4  497.66  5147.7  497.28
    5275  497.55  5303.2  496.27  5310.3  496.41  5331.5  498.29  5416.4  498.95
  5501.2   501.3  5515.4  501.19  5543.7  503.01  5600.2   504.4  5840.6  509.11
#Mann= 3 ,-1 , 0
  4079.7     .05       0  5060.8     .03       0  5064.8     .05       0
Bank Sta=5060.8,5064.8
XS Rating Curve= 0 ,0
Exp/Cntr=0.3,0.1

Type RM Length L Ch R = 1 ,96838   ,420,420,420
BEGIN DESCRIPTION:
Williams Creek 145.0
END DESCRIPTION:
XS GIS Cut Line= 3
      2679401.26      6929096.51        2678976.        6928161.
      2678375.96      6927810.98
#Sta/Elev= 30
  3976.7  504.27    4242  500.75  4279.3  500.88  4311.2  499.46  4356.2  500.87
  4385.9  499.55  4586.9  496.76  4938.4  495.13  4949.4  496.04  4960.4  495.18
    5016  494.94  5016.2  494.44    5020  494.94  5108.1  496.45  5143.3  495.52
  5224.5  496.16  5252.8  495.77  5274.3  496.76  5327.2  496.08  5409.1  497.13
  5450.5  498.12    5472  499.74  5509.2  500.06    5515  500.81  5536.9  501.22
  5573.7  500.25  5669.6  502.28  5685.3  504.64  5691.1  504.34    5699  505.37
#Mann= 5 ,-1 , 0
  3976.7     .05       0    5016     .03       0    5020     .05       0
  5224.5     .12       0  5409.1     .05       0
Bank Sta=5016,5020
XS Rating Curve= 0 ,0
Exp/Cntr=0.3,0.1

Type RM Length L Ch R = 1 ,96418   ,435,435,435
BEGIN DESCRIPTION:
Williams Creek 144.0
END DESCRIPTION:
XS GIS Cut Line= 3
      2679925.99      6928560.99        2679326.        6927961.
      2678425.97      6927110.97
#Sta/Elev= 30
  4156.5  508.14  4425.2  497.85  4552.5   495.9  4580.8  494.72  4679.7  495.04
  4736.3  496.35  4764.6   494.3  4792.9   494.1  4863.6  494.46  5103.9  492.84
  5139.5  493.41  5167.8  492.91    5182  493.63  5217.2  492.86  5245.5  494.49
  5259.7   494.4  5264.6  492.72  5264.8  492.22  5268.6  492.72    5288  494.14
  5344.6   494.1    5394  495.71  5408.2  495.21  5422.3   496.2  5464.8  495.85
  5860.9  501.58    5960  504.62  6044.9  505.54  6193.4  510.65    6243  511.43
#Mann= 3 ,-1 , 0
  4156.5     .05       0  5264.6     .03       0  5268.6     .05       0
Bank Sta=5264.6,5268.6
XS Rating Curve= 0 ,0
Exp/Cntr=0.3,0.1

Type RM Length L Ch R = 1 ,95983   ,604,604,604
BEGIN DESCRIPTION:
Williams Creek 143.0
END DESCRIPTION:
XS GIS Cut Line= 4
      2680176.01      6928311.02        2679626.        6927711.
      2679206.66      6927453.62      2678667.12      6926939.58
#Sta/Elev= 30
    4186  507.77  4306.6  503.15  4327.5  503.56  4384.3  501.48  4433.6  501.39
  4476.1  499.46  4674.4   496.1  4738.2   492.8  4984.1  490.58  4984.3  490.08
  4988.1  490.58  5065.7  492.26  5197.1  491.16  5239.7  491.76  5363.7  494.32
  5413.7  496.58  5429.2  495.81  5487.2  496.84  5550.8  495.46  5586.3  496.01
  5621.6  494.91  5706.5  494.75  5727.7  496.05  5854.9   498.6  5876.3  500.21
  5883.3  499.37  5890.5  500.41  5918.8   501.1  6067.3   503.2  6237.2  508.39
#Mann= 3 ,-1 , 0
    4186     .05       0  4984.1     .03       0  4988.1     .05       0
Bank Sta=4984.1,4988.1
XS Rating Curve= 0 ,0
Exp/Cntr=0.3,0.1

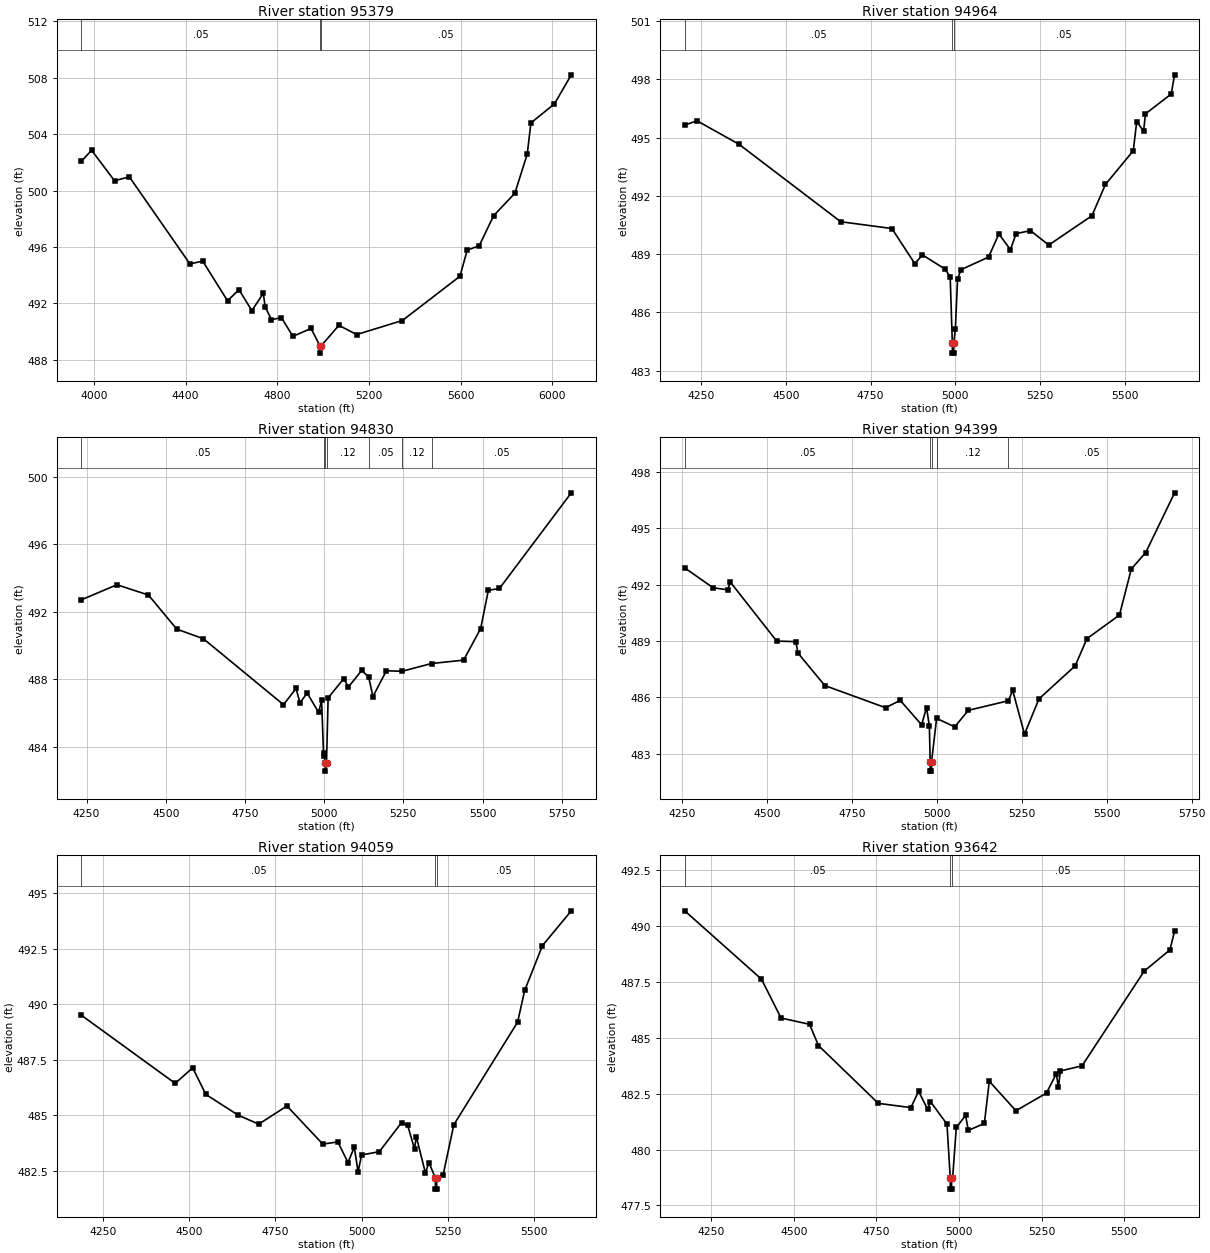
Type RM Length L Ch R = 1 ,95379   ,415,415,415
BEGIN DESCRIPTION:
Williams Creek 142.0
END DESCRIPTION:
XS GIS Cut Line= 3
      2680567.06      6927812.56      2679728.43      6927177.63
      2678692.41      6926853.53
#Sta/Elev= 30
  3945.6  502.09  3990.2  502.86  4090.1   500.7  4154.6  500.98  4418.8  494.81
    4475     495  4583.2  492.19  4633.1  492.98  4689.3  491.49  4739.2  492.72
  4747.5  491.76  4774.7  490.85  4818.3     491  4868.2  489.67  4947.3  490.23
  4986.9  488.98  4987.2  488.48  4990.9  488.98    5069  490.45  5146.7   489.8
  5345.8  490.79  5597.3  493.93  5628.7  495.78  5681.1  496.09  5744.5  498.23
  5836.6  499.81  5890.6  502.58  5906.8   504.8  6009.4  506.15    6083  508.21
#Mann= 3 ,-1 , 0
  3945.6     .05       0  4986.9     .03       0  4990.9     .05       0
Bank Sta=4986.9,4990.9
XS Rating Curve= 0 ,0
Exp/Cntr=0.3,0.1

Type RM Length L Ch R = 1 ,94964   ,134,134,134
BEGIN DESCRIPTION:
Williams Creek 141.0
END DESCRIPTION:
XS GIS Cut Line= 3
      2680479.31      6927124.15      2679762.35       6926774.2
      2679126.04      6926661.01
#Sta/Elev= 30
  4202.2  495.65  4238.6  495.87  4362.4  494.66  4662.1  490.67  4812.9  490.32
  4880.5  488.51    4903  488.96  4970.6  488.22  4984.8  487.81  4991.1   484.4
  4991.4   483.9  4994.9   483.9  4995.1   484.4    5000  485.13  5006.5  487.72
  5016.6   488.2  5097.9  488.85  5128.3  490.04  5162.5  489.23  5179.1  490.06
  5221.5  490.21  5275.4  489.47  5402.6  490.98  5442.3  492.59  5524.5  494.33
  5534.6  495.83  5554.9  495.34  5560.4  496.23  5636.2  497.25  5646.3  498.24
#Mann= 3 ,-1 , 0
  4202.2     .05       0  4991.1     .03       0  4995.1     .05       0
Bank Sta=4991.1,4995.1
XS Rating Curve= 0 ,0
Exp/Cntr=0.3,0.1

Type RM Length L Ch R = 1 ,94830   ,431,431,431
BEGIN DESCRIPTION:
Mapping XS 7207de61
END DESCRIPTION:
XS GIS Cut Line= 5
      2680531.35      6926970.48      2679921.56      6926716.58
      2679830.41      6926666.67      2679671.99      6926506.08
      2679155.46       6926299.9
#Sta/Elev= 30
  4233.9  492.71  4346.1   493.6  4445.5  492.99  4534.7  490.97  4618.8   490.4
  4871.7  486.49  4911.5  487.45  4923.6  486.59  4946.4  487.18  4982.6  486.03
    4992  486.74    4998  483.63  4999.9  483.43  5003.5  483.05  5003.8  482.55
  5007.5  483.05  5012.6  486.89  5062.1  488.04  5076.2  487.53  5118.7  488.52
  5140.7  488.12    5154  486.97  5196.4   488.5    5246  488.47  5338.9  488.93
  5440.2  489.13    5494     491  5518.3  493.27  5553.4  493.38  5780.1  499.05
#Mann= 7 ,-1 , 0
  4233.9     .05       0  4999.9     .12       0  5003.5     .07       0
  5007.5     .12       0  5140.7     .05       0    5246     .12       0
  5338.9     .05       0
Bank Sta=5003.5,5007.5
XS Rating Curve= 0 ,0
Exp/Cntr=0.3,0.1

Type RM Length L Ch R = 1 ,94399   ,340,340,340
BEGIN DESCRIPTION:
Mapping XS bd372290
END DESCRIPTION:
XS GIS Cut Line= 3
      2680448.25      6926876.96      2680010.75      6926298.83
       2679347.4      6926025.69
#Sta/Elev= 30
  4257.4   492.9    4341  491.84  4384.7  491.73    4391  492.16  4528.2     489
  4584.5  488.97  4590.9  488.36  4669.8  486.63  4848.7  485.45  4891.9  485.84
  4954.9  484.54  4969.4  485.46  4977.7  484.48  4980.2  482.57  4980.5  482.07
    4984  482.07  4984.2  482.57    4999  484.88  5052.4  484.43  5092.6  485.31
  5210.2  485.82  5223.1  486.37  5257.9  484.04  5300.4  485.92    5407  487.68
  5441.8  489.13  5537.5  490.39  5572.3  492.84  5614.8  493.72  5699.8   496.9
#Mann= 5 ,-1 , 0
  4257.4     .05       0  4980.2     .07       0  4984.2     .05       0
    4999     .12       0  5210.2     .05       0
Bank Sta=4980.2,4984.2
XS Rating Curve= 0 ,0
Exp/Cntr=0.3,0.1

Type RM Length L Ch R = 1 ,94059   ,417,417,417
BEGIN DESCRIPTION:
Mapping XS 8dd20369
END DESCRIPTION:
XS GIS Cut Line= 3
      2680534.19      6926699.88      2680159.19      6926007.17
      2679544.57      6925863.93
#Sta/Elev= 30
  4188.5   489.5  4460.1  486.43  4510.8  487.13  4548.9  485.93  4642.1     485
    4702  484.59  4783.8  485.41  4887.5  483.69  4931.2  483.79  4960.5  482.86
  4978.8  483.55  4989.8  482.44    5000   483.2  5051.4  483.35  5115.8  484.66
  5133.5  484.53  5153.2  483.47  5158.4  484.03  5184.8  482.39  5195.1  482.86
  5213.6  482.16  5213.9  481.66  5217.4  481.66  5217.6  482.16  5236.2  482.31
    5267  484.56  5451.8  489.19  5472.3  490.62  5523.7  492.64  5607.3  494.21
#Mann= 3 ,-1 , 0
  4188.5     .05       0  5213.6     .04       0  5217.6     .05       0
Bank Sta=5213.6,5217.6
XS Rating Curve= 0 ,0
Exp/Cntr=0.3,0.1

Type RM Length L Ch R = 1 ,93642   ,331,331,331
BEGIN DESCRIPTION:
Mapping XS d9fcc4cd
END DESCRIPTION:
XS GIS Cut Line= 3
      2680961.27      6926541.01      2680495.13      6925876.96
       2679940.7      6925496.93
#Sta/Elev= 30
  4169.3  490.69  4401.8  487.63    4461  485.89  4547.3  485.61  4574.3  484.66
  4755.6  482.07  4854.1  481.88  4877.6  482.61  4904.6  481.81  4913.3  482.15
  4963.5  481.14  4973.4  478.73  4973.7  478.23  4977.3  478.23  4977.7  478.73
  4980.6  478.73  4991.7  480.99  5019.8  481.53  5028.1  480.86  5076.7  481.17
  5091.6  483.06  5172.2  481.74  5264.9  482.53  5294.7   483.4  5300.8  482.79
  5306.9  483.52  5372.5  483.75  5560.7  487.99  5638.5  488.94  5652.8  489.78
#Mann= 3 ,-1 , 0
  4169.3     .05       0  4973.4     .04       0  4977.7     .05       0
Bank Sta=4973.4,4977.7
XS Rating Curve= 0 ,0
Exp/Cntr=0.3,0.1

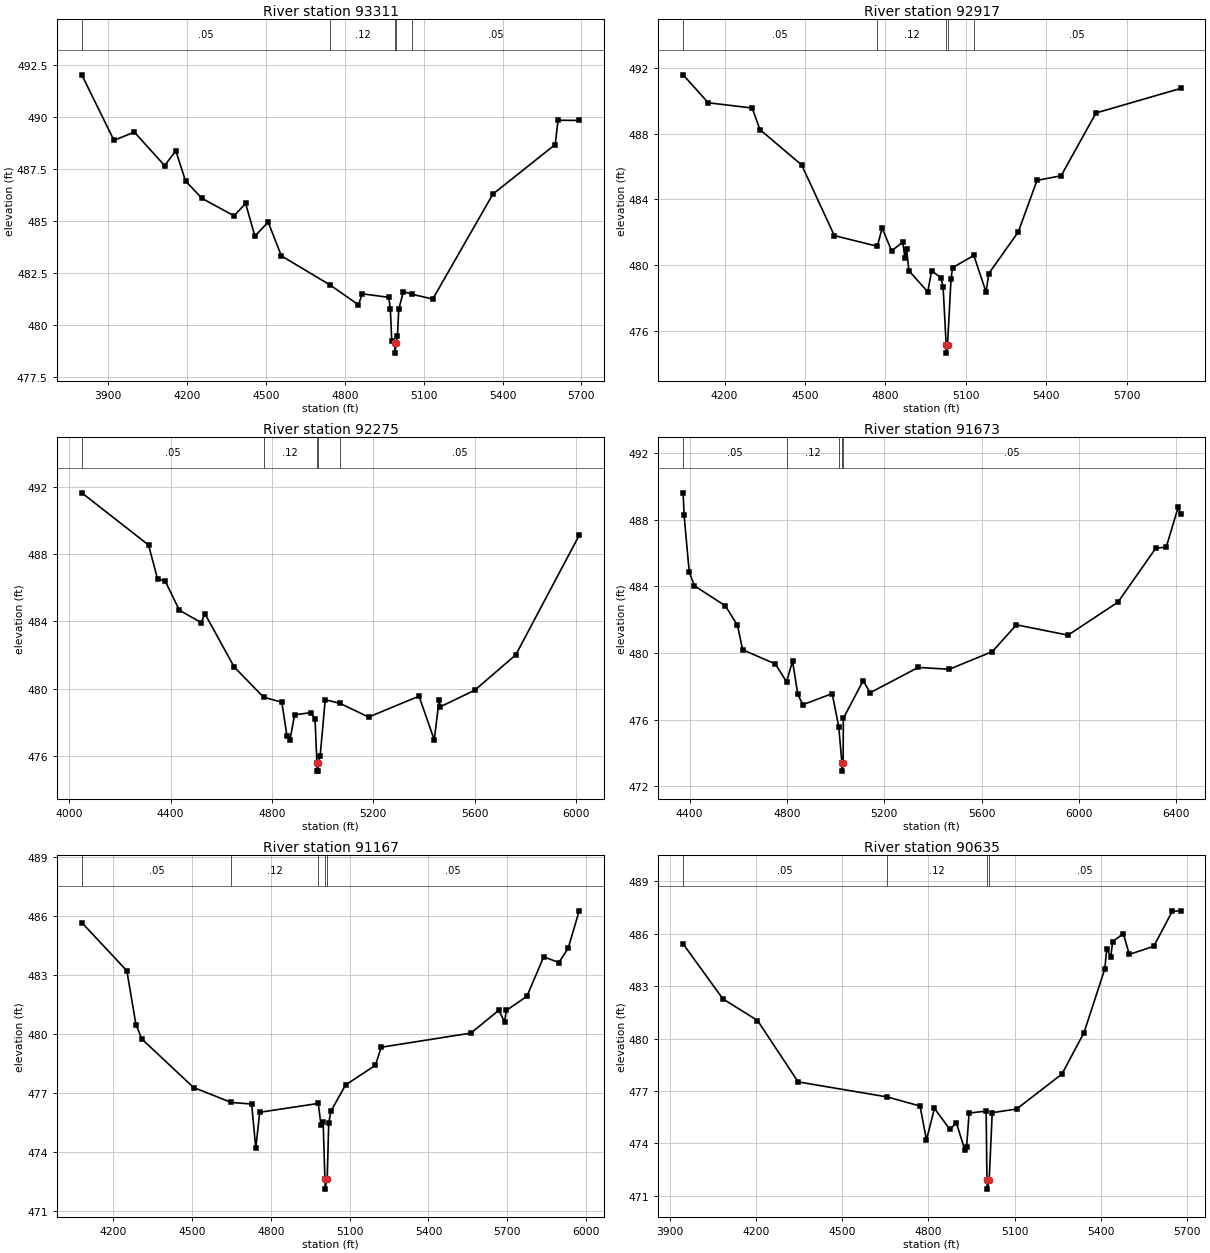
Type RM Length L Ch R = 1 ,93311   ,394,394,394
BEGIN DESCRIPTION:
Mapping XS e97e4630
END DESCRIPTION:
XS GIS Cut Line= 3
      2681556.25      6926260.64      2680597.95      6925569.69
      2679896.54      6925451.63
#Sta/Elev= 30
  3798.9  492.05  3921.4  488.89  3998.8  489.29  4114.1  487.67  4156.7  488.39
  4193.7  486.93  4256.5  486.09  4378.6  485.25  4422.1  485.85  4457.7  484.27
    4508  484.95  4558.3  483.32  4744.4  481.91  4851.6  480.96  4866.3  481.49
  4966.9  481.32    4973  480.75  4978.4  479.21  4989.9  479.13  4990.6  478.63
  4994.9  479.13    5000  479.45  5005.1  480.76  5022.9   481.6  5054.9  481.47
  5134.4  481.24  5363.3   486.3  5600.4  488.69    5611  489.86  5691.6  489.85
#Mann= 5 ,-1 , 0
  3798.9     .05       0  4744.4     .12       0  4989.9     .07       0
  4994.9     .12       0  5054.9     .05       0
Bank Sta=4989.9,4994.9
XS Rating Curve= 0 ,0
Exp/Cntr=0.3,0.1

Type RM Length L Ch R = 1 ,92917   ,642,642,642
BEGIN DESCRIPTION:
Mapping XS 99e9b11d
END DESCRIPTION:
XS GIS Cut Line= 4
      2681542.38      6925885.65      2680788.92      6925298.85
      2680712.53      6925253.71      2679900.53       6925243.3
#Sta/Elev= 30
  4045.6  491.58  4139.4  489.88  4303.1  489.56  4332.1  488.25  4487.7   486.1
  4609.8   481.8  4770.1  481.15  4788.1  482.26  4823.4  480.87    4865   481.4
  4873.1  480.41  4879.5  481.01  4887.6  479.67  4958.2  478.38  4972.7  479.65
    5008  479.24  5015.6  478.65    5027  475.15  5027.6  474.65    5032  475.15
  5045.1  479.16  5050.9  479.85  5130.3  480.59  5175.9  478.36  5185.9  479.49
  5295.9  482.02  5365.9  485.16  5455.9  485.44  5585.9  489.26  5901.4  490.75
#Mann= 5 ,-1 , 0
  4045.6     .05       0  4770.1     .12       0    5027     .07       0
    5032     .12       0  5130.3     .05       0
Bank Sta=5027,5032
XS Rating Curve= 0 ,0
Exp/Cntr=0.3,0.1

Type RM Length L Ch R = 1 ,92275   ,602,602,602
BEGIN DESCRIPTION:
Mapping XS fe036f84
END DESCRIPTION:
XS GIS Cut Line= 4
      2681603.73      6925871.18      2681169.71      6925263.55
       2681121.1      6924867.72      2680305.11      6924923.28
#Sta/Elev= 30
  4049.5  491.63  4313.1  488.53  4348.7  486.51  4378.2  486.41  4434.8  484.66
  4520.8  483.93  4535.5  484.45  4651.1  481.29  4767.1   479.5  4839.1   479.2
  4859.2  477.22    4871  476.94  4889.5  478.45  4952.3  478.58  4970.1  478.23
  4977.6  475.61  4978.2  475.11    4982  475.11  4982.6  475.61  4990.2  475.98
  5010.4  479.35  5069.2  479.13  5181.6  478.32  5380.6  479.56  5440.7  476.97
  5459.9  479.31  5464.9  478.93  5601.1  479.92  5762.5  482.01  6012.9  489.11
#Mann= 5 ,-1 , 0
  4049.5     .05       0  4767.1     .12       0  4977.6     .07       0
  4982.6     .12       0  5069.2     .05       0
Bank Sta=4977.6,4982.6
XS Rating Curve= 0 ,0
Exp/Cntr=0.3,0.1

Type RM Length L Ch R = 1 ,91673   ,506,506,506
BEGIN DESCRIPTION:
Mapping XS af068d43
END DESCRIPTION:
XS GIS Cut Line= 3
      2681865.57      6925156.99      2681416.41      6924672.14
      2680407.21       6923726.4
#Sta/Elev= 30
  4373.1  489.62  4377.1  488.27  4398.1  484.87  4419.7  484.03  4546.7  482.83
  4596.5  481.66  4617.5  480.19  4751.9  479.34  4797.9  478.27  4822.8  479.51
  4844.3  477.51  4865.3  476.89  4985.5  477.56  5012.6  475.57  5025.5   473.4
  5026.1   472.9  5030.6   473.4  5031.4  476.07    5113  478.34  5141.4  477.61
  5339.2  479.13  5466.7  479.02  5643.5  480.08  5742.7  481.69  5954.7  481.07
  6159.8  483.05  6315.6   486.3  6358.1  486.35  6407.5  488.76  6417.1  488.36
#Mann= 5 ,-1 , 0
  4373.1     .05       0  4797.9     .12       0  5012.6     .05       0
  5025.5     .07       0  5030.6     .05       0
Bank Sta=5025.5,5030.6
XS Rating Curve= 0 ,0
Exp/Cntr=0.3,0.1

Type RM Length L Ch R = 1 ,91167   ,532,532,532
BEGIN DESCRIPTION:
Mapping XS e4cf8177
END DESCRIPTION:
XS GIS Cut Line= 3
      2682168.53      6925120.34      2681710.22      6924311.35
      2680956.75      6923710.66
#Sta/Elev= 30
  4080.3  485.68  4251.9  483.23  4286.4  480.49  4309.4  479.75  4505.9  477.29
  4649.8  476.53  4726.7  476.45  4742.6  474.21  4757.6  476.03  4980.4  476.48
  4990.7   475.4    4999  475.55  5005.8  472.62  5006.9  472.12  5012.8  472.62
  5014.4  472.62  5020.3  475.47  5028.3  476.08  5084.3  477.42    5198  478.42
  5220.1  479.34  5561.6  480.06  5667.7  481.22  5689.7  480.63  5696.1  481.21
  5774.5  481.93  5838.6  483.94  5896.2  483.65  5931.5  484.37  5973.7  486.28
#Mann= 5 ,-1 , 0
  4080.3     .05       0  4649.8     .12       0  4980.4     .05       0
  5005.8     .03       0  5012.8     .05       0
Bank Sta=5005.8,5012.8
XS Rating Curve= 0 ,0
Exp/Cntr=0.3,0.1

Type RM Length L Ch R = 1 ,90635   ,378,378,378
BEGIN DESCRIPTION:
Mapping XS 25be7b63
END DESCRIPTION:
XS GIS Cut Line= 3
      2682571.34      6924932.91      2682102.58      6923995.38
      2681557.46      6923578.73
#Sta/Elev= 30
  3944.6  485.41    4083  482.27  4203.9  481.03  4345.7  477.52  4656.3  476.66
  4770.6  476.14    4793   474.2  4820.9  476.01  4874.7   474.8  4897.1  475.19
  4927.1  473.61  4932.7  473.77  4941.8  475.74  5001.1  475.85  5003.9  471.89
  5005.1  471.39  5011.7  471.89  5022.3  475.76  5107.5  475.97  5265.4  477.97
  5342.4  480.34    5415  483.99  5421.3  485.12  5435.8  484.68  5442.1  485.54
  5479.4     486  5500.2  484.81  5585.5  485.27  5649.9  487.27  5678.9   487.3
#Mann= 4 ,-1 , 0
  3944.6     .05       0  4656.3     .12       0  5003.9     .07       0
  5011.7     .05       0
Bank Sta=5003.9,5011.7
XS Rating Curve= 0 ,0
Exp/Cntr=0.3,0.1

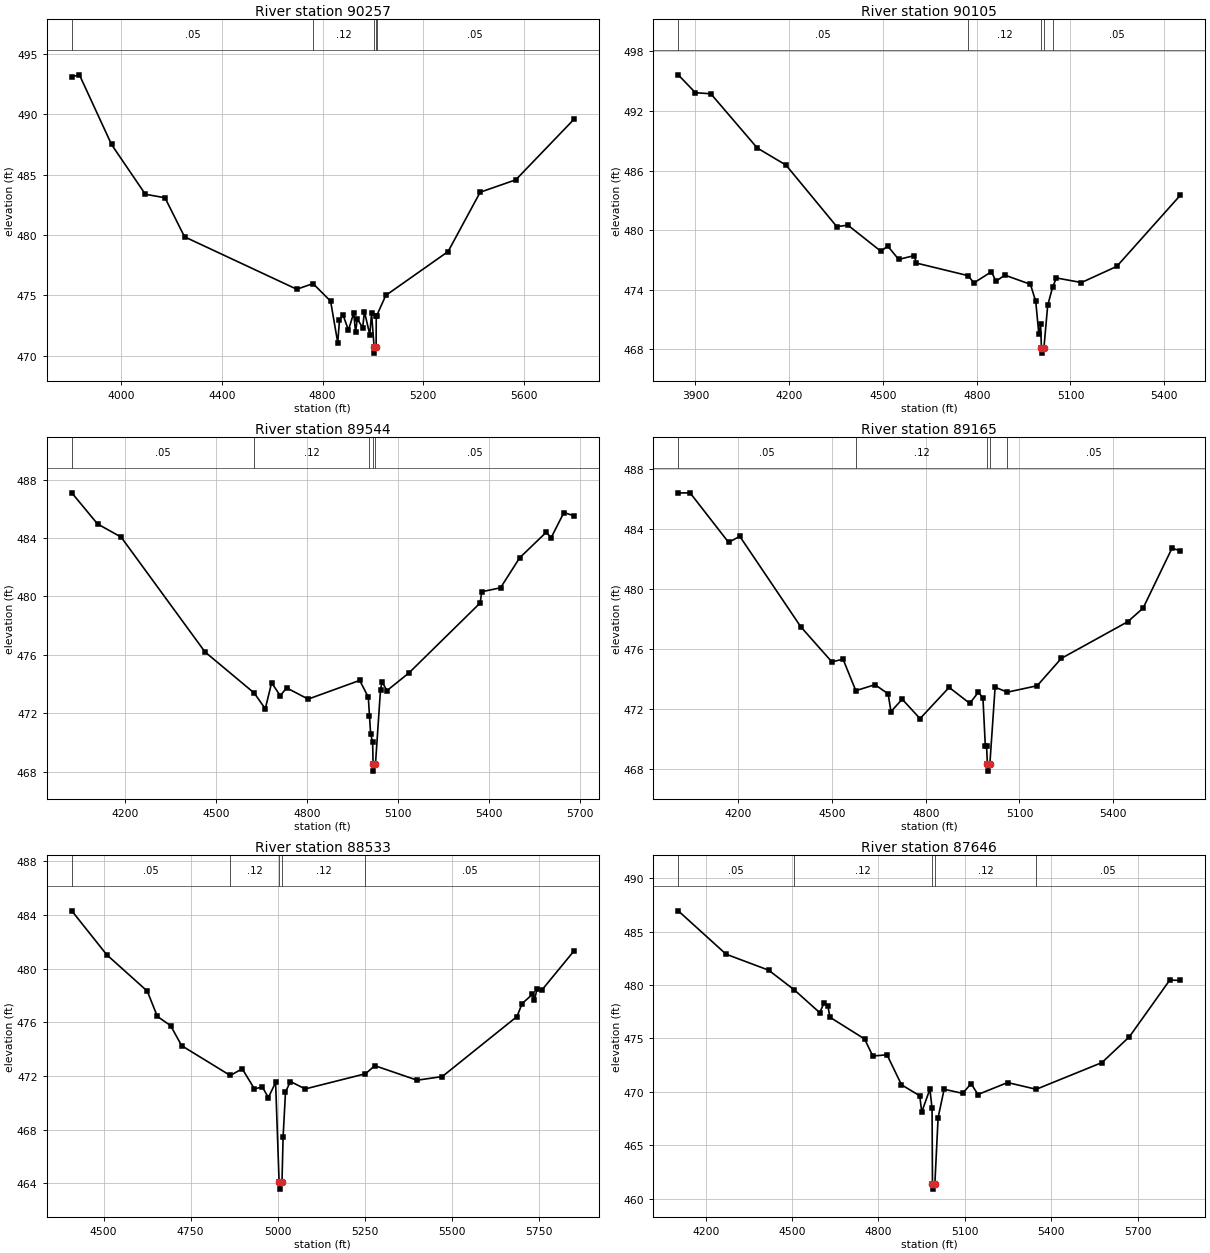
Type RM Length L Ch R = 1 ,90257   ,152,152,152
BEGIN DESCRIPTION:
Mapping XS fea30a29
END DESCRIPTION:
XS GIS Cut Line= 3
       2683158.1      6924582.15       2682324.8      6923700.24
      2681783.15      6923137.76
#Sta/Elev= 30
  3803.6  493.13    3834  493.29  3961.5  487.51  4095.8  483.38  4173.9  483.09
  4251.5  479.85  4697.3   475.5  4761.9  475.97  4831.7  474.51    4860  471.07
  4866.9  472.92    4881  473.37  4902.5  472.11  4923.5  473.53  4930.8  471.94
  4937.7  473.03  4959.1  472.31    4966  473.64  4987.4  471.73  4994.3  473.52
  5004.5   470.7  5005.7   470.2  5012.4   470.7    5013  473.31  5014.7  473.31
  5050.9  474.99  5298.4  478.63  5425.7  483.55  5567.2  484.58  5797.8  489.59
#Mann= 5 ,-1 , 0
  3803.6     .05       0  4761.9     .12       0  5004.5     .07       0
  5012.4     .12       0  5014.7     .05       0
Bank Sta=5004.5,5012.4
XS Rating Curve= 0 ,0
Exp/Cntr=0.3,0.1

Type RM Length L Ch R = 1 ,90105   ,561,561,561
BEGIN DESCRIPTION:
Mapping XS e64f6b0a
END DESCRIPTION:
XS GIS Cut Line= 4
      2683286.61      6924478.03      2682484.52      6923686.35
      2682446.33      6923606.49      2682169.79      6923329.95
#Sta/Elev= 30
  3844.9  495.64  3899.8  493.84  3949.3  493.73  4097.8  488.27  4189.7  486.55
  4352.3  480.35  4387.7   480.5  4493.8  477.86    4515   478.4  4550.3  477.05
  4599.9  477.43  4606.9  476.68  4772.8  475.41  4790.8  474.68  4847.3  475.81
  4861.5  474.84  4889.8  475.47  4971.9  474.54  4988.9  472.82  4998.8  469.51
  5004.4   470.5  5007.1  468.11  5008.3  467.61    5015  468.11  5027.1  472.41
  5043.1  474.28  5055.1  475.18  5135.2  474.72  5248.4  476.35  5451.5  483.51
#Mann= 5 ,-1 , 0
  3844.9     .05       0  4772.8     .12       0  5007.1     .07       0
    5015     .12       0  5043.1     .05       0
Bank Sta=5007.1,5015
XS Rating Curve= 0 ,0
Exp/Cntr=0.3,0.1

Type RM Length L Ch R = 1 ,89544   ,379,379,379
BEGIN DESCRIPTION:
Mapping XS 6456c703
END DESCRIPTION:
XS GIS Cut Line= 3
      2683297.86      6924038.92      2682633.83      6923292.43
      2682004.49      6923110.14
#Sta/Elev= 30
  4025.6  487.09  4110.5  484.96  4188.2  484.06  4464.5   476.2  4626.5  473.39
  4663.2  472.31  4684.1  474.09  4712.5   473.2  4733.4  473.74  4804.5  472.97
  4974.3  474.25  5002.7   473.1  5006.5  471.84  5010.2  470.61  5016.9  470.01
  5018.4  468.54  5019.5  468.04  5026.3  468.54  5042.9  473.62  5048.1  474.15
  5064.1  473.55    5137  474.77  5371.2  479.55  5376.5  480.32  5438.4  480.59
  5501.3  482.64  5588.4  484.38  5605.4  484.03  5647.1  485.74  5679.9  485.52
#Mann= 5 ,-1 , 0
  4025.6     .05       0  4626.5     .12       0  5006.5     .05       0
  5018.4     .07       0  5026.3     .05       0
Bank Sta=5018.4,5026.3
XS Rating Curve= 0 ,0
Exp/Cntr=0.3,0.1

Type RM Length L Ch R = 1 ,89165   ,632,632,632
BEGIN DESCRIPTION:
Mapping XS 9491aa0b
END DESCRIPTION:
XS GIS Cut Line= 3
      2683401.16      6923908.71      2682852.58      6923089.31
      2682239.54      6922999.25
#Sta/Elev= 30
  4008.6  486.43  4046.4  486.44  4169.5  483.13  4205.5  483.53  4400.6  477.48
  4499.7  475.14  4535.8  475.31  4576.5  473.21  4637.8  473.61  4679.9     473
  4688.9  471.81  4724.9  472.64  4781.9  471.34    4875  473.43    4941  472.36
  4968.6  473.11  4983.1  472.72  4990.7   469.5  4994.7   469.5  4997.3  468.33
  4998.5  467.83  5005.3  468.33    5022  473.44  5061.2  473.11  5156.5  473.54
  5233.8  475.37  5446.1  477.82  5495.3  478.73  5587.6  482.73  5614.3  482.57
#Mann= 5 ,-1 , 0
  4008.6     .05       0  4576.5     .12       0  4997.3     .07       0
  5005.3     .12       0  5061.2     .05       0
Bank Sta=4997.3,5005.3
XS Rating Curve= 0 ,0
Exp/Cntr=0.3,0.1

Type RM Length L Ch R = 1 ,88533   ,887,887,887
BEGIN DESCRIPTION:
Mapping XS 2f29dd2b
END DESCRIPTION:
XS GIS Cut Line= 4
      2683550.47      6923620.51      2683321.33      6923103.19
      2683231.05      6923005.97      2682630.68      6922568.71
#Sta/Elev= 30
  4408.7   484.3  4509.1  481.03  4625.5  478.32  4654.3  476.44  4692.5  475.75
  4724.1  474.26  4863.7  472.04    4898  472.54  4933.1  471.04  4955.5  471.19
    4973   470.4  4993.8  471.52  5003.9  464.08  5005.1  463.58  5012.1  464.08
  5015.3  467.45  5022.2  470.81  5036.3  471.59  5078.8  471.04  5251.8  472.17
  5278.7  472.77    5400  471.69  5472.2  471.96  5686.7  476.43  5701.3  477.39
  5730.7  478.08  5736.9  477.69  5744.3  478.47  5757.7  478.39  5849.9   481.3
#Mann= 5 ,-1 , 0
  4408.7     .05       0  4863.7     .12       0  5003.9     .07       0
  5012.1     .12       0  5251.8     .05       0
Bank Sta=5003.9,5012.1
XS Rating Curve= 0 ,0
Exp/Cntr=0.3,0.1

Type RM Length L Ch R = 1 ,87646   ,382,382,382
BEGIN DESCRIPTION:
Mapping XS 9966cda9
END DESCRIPTION:
XS GIS Cut Line= 4
      2684291.18      6923209.62      2683622.77      6922623.68
      2683501.25      6922532.53      2682799.56      6922489.22
#Sta/Elev= 30
  4104.7  486.94  4270.8  482.88  4418.8  481.38  4507.7  479.54  4596.3   477.4
  4610.5  478.29  4624.8  477.99  4631.4  476.98  4751.9  474.94  4780.4  473.34
  4829.8  473.46  4880.1  470.65  4943.6  469.62  4950.3  468.09  4978.8  470.24
  4986.3  468.44  4987.7  461.38  4988.9  460.88    4996  461.38  5007.3  467.58
  5028.2  470.23  5092.7  469.85  5121.9  470.76  5145.5  469.74  5248.7  470.86
    5348  470.23  5576.3  472.73  5671.7  475.15    5812  480.46  5848.5  480.42
#Mann= 5 ,-1 , 0
  4104.7     .05       0  4507.7     .12       0  4987.7     .07       0
    4996     .12       0    5348     .05       0
Bank Sta=4987.7,4996
XS Rating Curve= 0 ,0
Exp/Cntr=0.3,0.1

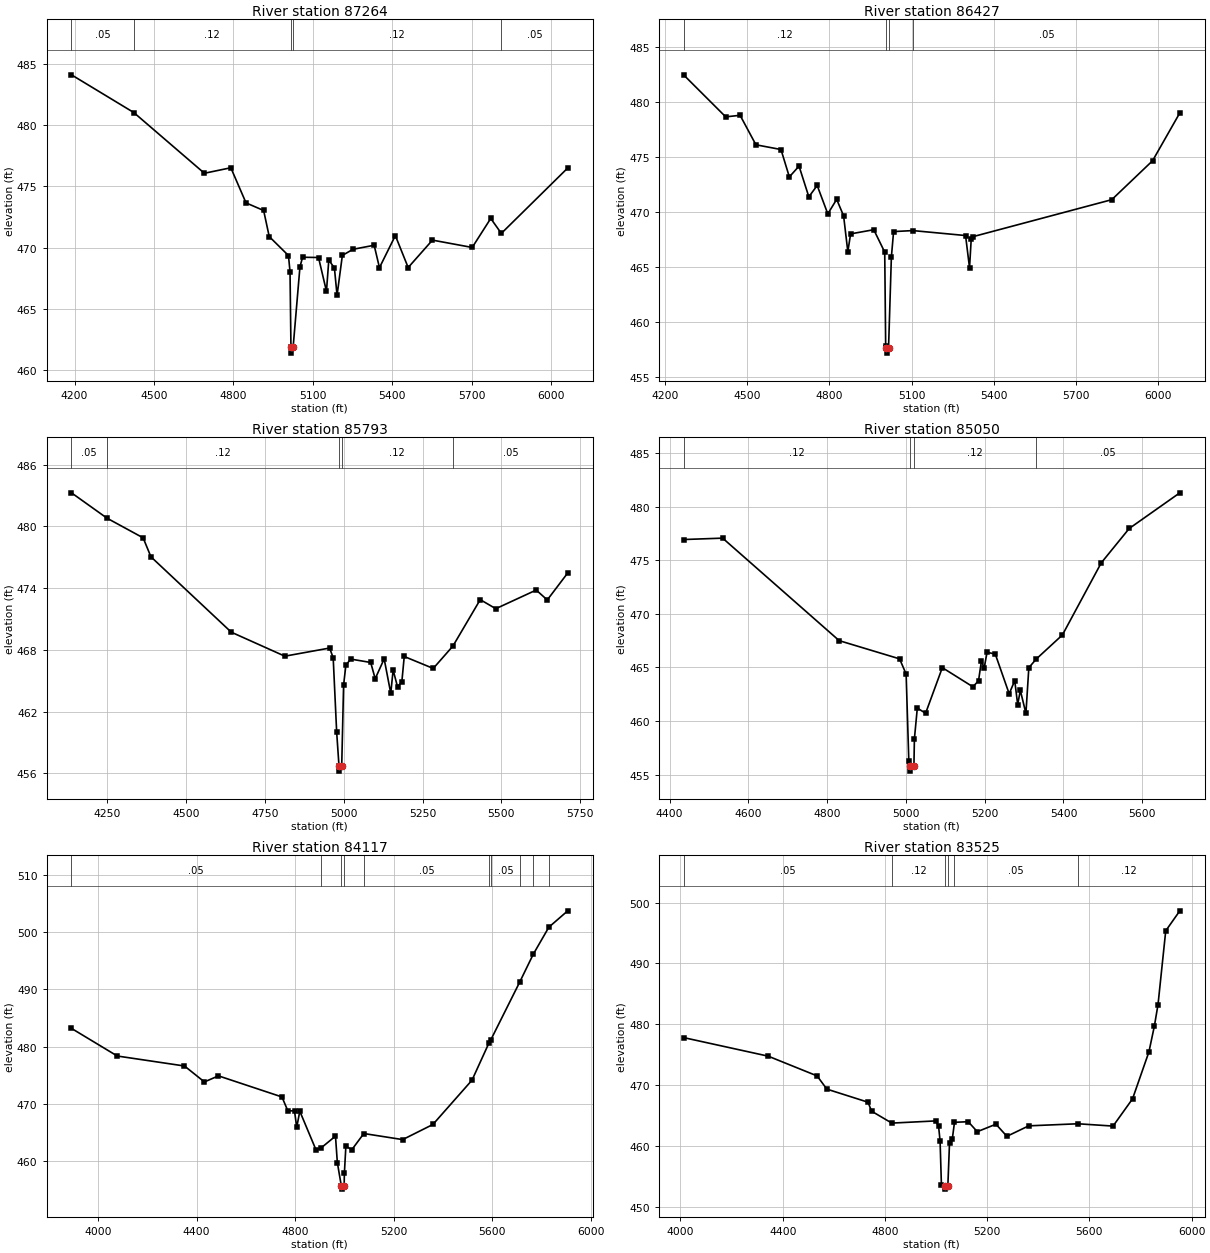
Type RM Length L Ch R = 1 ,87264   ,837,837,837
BEGIN DESCRIPTION:
Mapping XS 9a3227b9
END DESCRIPTION:
XS GIS Cut Line= 3
      2684347.61      6923062.06      2683892.74      6922360.66
      2682855.51      6922325.97
#Sta/Elev= 30
  4188.4  484.12  4423.7  481.04  4690.3  476.08  4790.1  476.53  4847.5  473.66
    4914  473.04  4935.1  470.91  5007.7  469.36  5013.6  468.04  5017.1  461.89
  5018.3  461.39  5025.4  461.89  5051.1  468.44  5061.1  469.22  5121.2   469.2
  5151.2  466.44    5160  468.99  5181.2  468.35  5191.2  466.11  5211.2  469.37
  5251.3  469.87  5331.3   470.2  5351.3  468.37  5411.3  470.99  5459.7  468.38
  5551.4  470.62  5701.5  470.02  5771.5  472.39  5811.5  471.17  6062.2  476.51
#Mann= 5 ,-1 , 0
  4188.4     .05       0  4423.7     .12       0  5017.1     .07       0
  5025.4     .12       0  5811.5     .05       0
Bank Sta=5017.1,5025.4
XS Rating Curve= 0 ,0
Exp/Cntr=0.3,0.1

Type RM Length L Ch R = 1 ,86427   ,634,634,634
BEGIN DESCRIPTION:
Mapping XS 6340fa5f
END DESCRIPTION:
XS GIS Cut Line= 3
       2684458.7      6922780.75      2684323.29      6922058.58
      2683656.65      6921211.38
#Sta/Elev= 30
  4267.3  482.44  4421.2  478.62  4473.8  478.76  4531.6  476.08  4623.1  475.65
  4653.7  473.16  4689.1  474.14  4724.9  471.35  4755.4  472.38  4794.2   469.8
  4826.6  471.12  4851.9  469.62  4867.3  466.36  4877.5  467.98  4962.1  468.36
  5002.1  466.32  5005.6  457.76  5007.7  457.64    5009  457.14  5016.1  457.64
  5026.4  465.87  5034.5  468.19  5104.9  468.28  5297.4  467.83  5311.9   464.9
  5318.2  467.56  5326.3  467.74  5831.5  471.09  5980.6  474.63  6080.1  478.98
#Mann= 4 ,-1 , 0
  4267.3     .12       0  5007.7     .07       0  5016.1     .12       0
  5104.9     .05       0
Bank Sta=5007.7,5016.1
XS Rating Curve= 0 ,0
Exp/Cntr=0.3,0.1

Type RM Length L Ch R = 1 ,85793   ,743,743,743
BEGIN DESCRIPTION:
Williams Creek 123.0
END DESCRIPTION:
XS GIS Cut Line= 4
      2685011.64      6922508.92      2684722.18      6921750.92
      2684651.11      6921718.17       2684197.9      6921207.66
#Sta/Elev= 30
  4137.8  483.25  4250.3  480.79  4364.8  478.88  4389.5  477.04  4644.1  469.72
  4813.8  467.39  4955.7  468.18    4967  467.23    4978  460.02  4985.4  456.73
  4986.6  456.23    4994  456.73    5000   464.6  5007.1  466.49    5022  467.11
  5085.8  466.78  5100.1   465.2  5128.5  467.13  5149.4  463.79  5156.9  466.05
  5170.8  464.42  5184.5  464.89  5192.1  467.36    5284   466.2  5346.5  468.38
  5432.9  472.88  5482.2     472  5610.2  473.81  5645.3  472.85  5710.1  475.47
#Mann= 5 ,-1 , 0
  4137.8     .05       0  4250.3     .12       0  4985.4     .07       0
    4994     .12       0  5346.5     .05       0
Bank Sta=4985.4,4994
XS Rating Curve= 0 ,0
Exp/Cntr=0.3,0.1

Type RM Length L Ch R = 1 ,85050   ,933,933,933
BEGIN DESCRIPTION:
Mapping XS ecce2a3e
END DESCRIPTION:
XS GIS Cut Line= 3
      2685406.33      6922004.73      2685216.23      6921478.71
      2684744.91      6920960.52
#Sta/Elev= 30
  4435.5  476.94  4534.7  477.07  4830.6   467.5  4983.9   465.8  5000.5  464.38
  5007.3   456.3  5009.2  455.82  5010.7  455.32  5020.3  455.82  5021.5  458.33
  5028.9  461.21  5049.9  460.72  5092.4  464.98  5170.1  463.19  5184.3  463.76
  5191.8  465.64  5198.5  464.93    5206  466.42  5226.9  466.24  5262.1  462.54
  5276.2  463.77  5283.7  461.53  5290.4  462.86  5304.6  460.71    5312  464.98
  5331.3   465.8  5397.2  468.03  5495.8  474.76  5566.8  477.97  5695.3   481.3
#Mann= 4 ,-1 , 0
  4435.5     .12       0  5009.2     .07       0  5020.3     .12       0
  5331.3     .05       0
Bank Sta=5009.2,5020.3
XS Rating Curve= 0 ,0
Exp/Cntr=0.3,0.1

Type RM Length L Ch R = 1 ,84117   ,592,592,592
BEGIN DESCRIPTION:
Mapping XS 09155f0f
END DESCRIPTION:
XS GIS Cut Line= 3
      2686256.14      6921868.44      2685646.79      6920967.43
      2684881.17       6920446.6
#Sta/Elev= 30
  3892.6  483.19  4078.5  478.37  4351.2  476.63    4432  473.85    4489  474.91
  4746.7  471.23  4770.6   468.8  4797.6  468.81  4806.6  465.93  4819.1  468.74
  4884.5  462.03  4903.3  462.26  4963.9   464.4  4971.4  459.79  4987.8  455.65
  4989.3  455.15    4999  455.65    5000  457.92  5006.1  462.68  5029.7     462
  5078.9  464.85  5236.5  463.79  5359.2  466.43  5517.9  474.16  5586.2   480.6
  5594.2  481.19    5712  491.32  5766.5  496.13  5829.8  500.85  5906.3   503.7
#Mann= 10 ,-1 , 0
  3892.6     .05       0  4903.3     .12       0  4987.8     .07       0
    4999     .12       0  5078.9     .05       0  5586.2     .12       0
  5594.2     .05       0    5712     .12       0  5766.5     .05       0
  5829.8     .12       0
Bank Sta=4987.8,4999
XS Rating Curve= 0 ,0
Exp/Cntr=0.3,0.1

Type RM Length L Ch R = 1 ,83525   ,795,795,795
BEGIN DESCRIPTION:
Mapping XS 53abc8c4
END DESCRIPTION:
XS GIS Cut Line= 3
       2686559.1      6921465.98      2686093.84      6920604.91
      2685192.84       6920265.3
#Sta/Elev= 30
  4012.2  477.83  4343.3  474.78  4534.6  471.54  4572.7  469.37  4733.9  467.22
  4747.7  465.75    4827  463.79  4999.3  464.15    5010  463.24  5015.8  460.86
  5021.1  453.56    5035  453.45  5036.6  452.95  5046.2  453.45  5052.7  460.51
  5063.4  461.11  5072.2  463.92  5125.9  464.02  5161.4  462.38  5234.4  463.61
  5277.2  461.62  5362.7  463.34  5555.2  463.68  5692.6   463.3  5768.8  467.77
  5832.9  475.48  5854.2  479.71  5868.5  483.25  5898.7  495.36  5953.8  498.64
#Mann= 6 ,-1 , 0
  4012.2     .05       0    4827     .12       0    5035     .07       0
  5046.2     .12       0  5072.2     .05       0  5555.2     .12       0
Bank Sta=5035,5046.2
XS Rating Curve= 0 ,0
Exp/Cntr=0.3,0.1