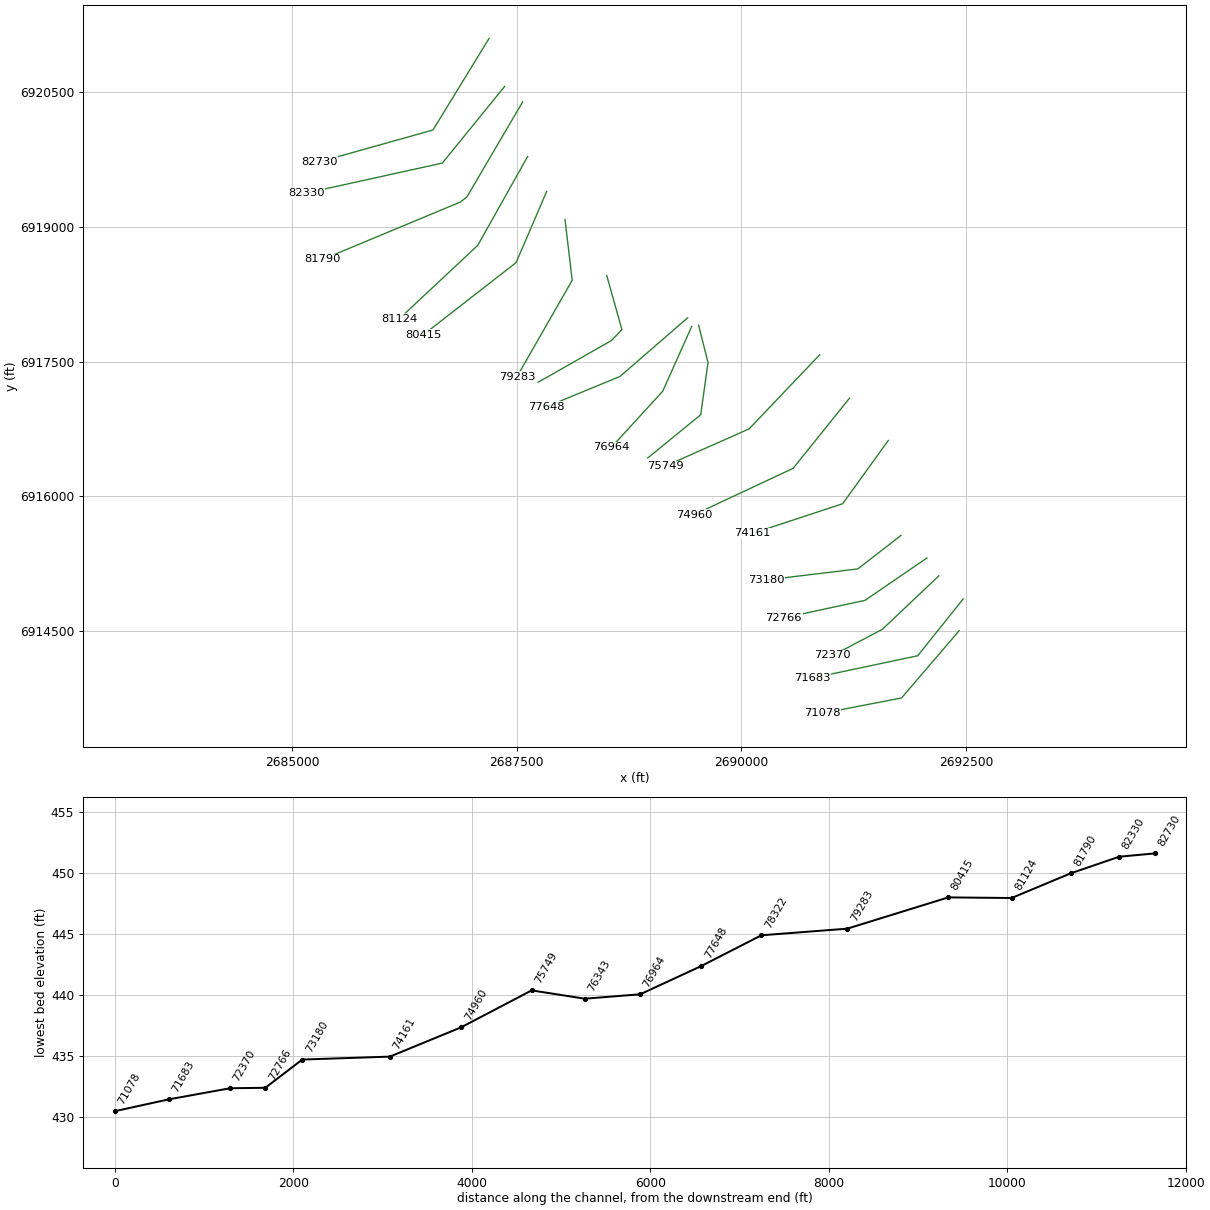
HEC-RAS study Williams Creek.prj: Williams Creek Base Level Engineering

--- Williams Creek.g01 (geometry) --- (continued)

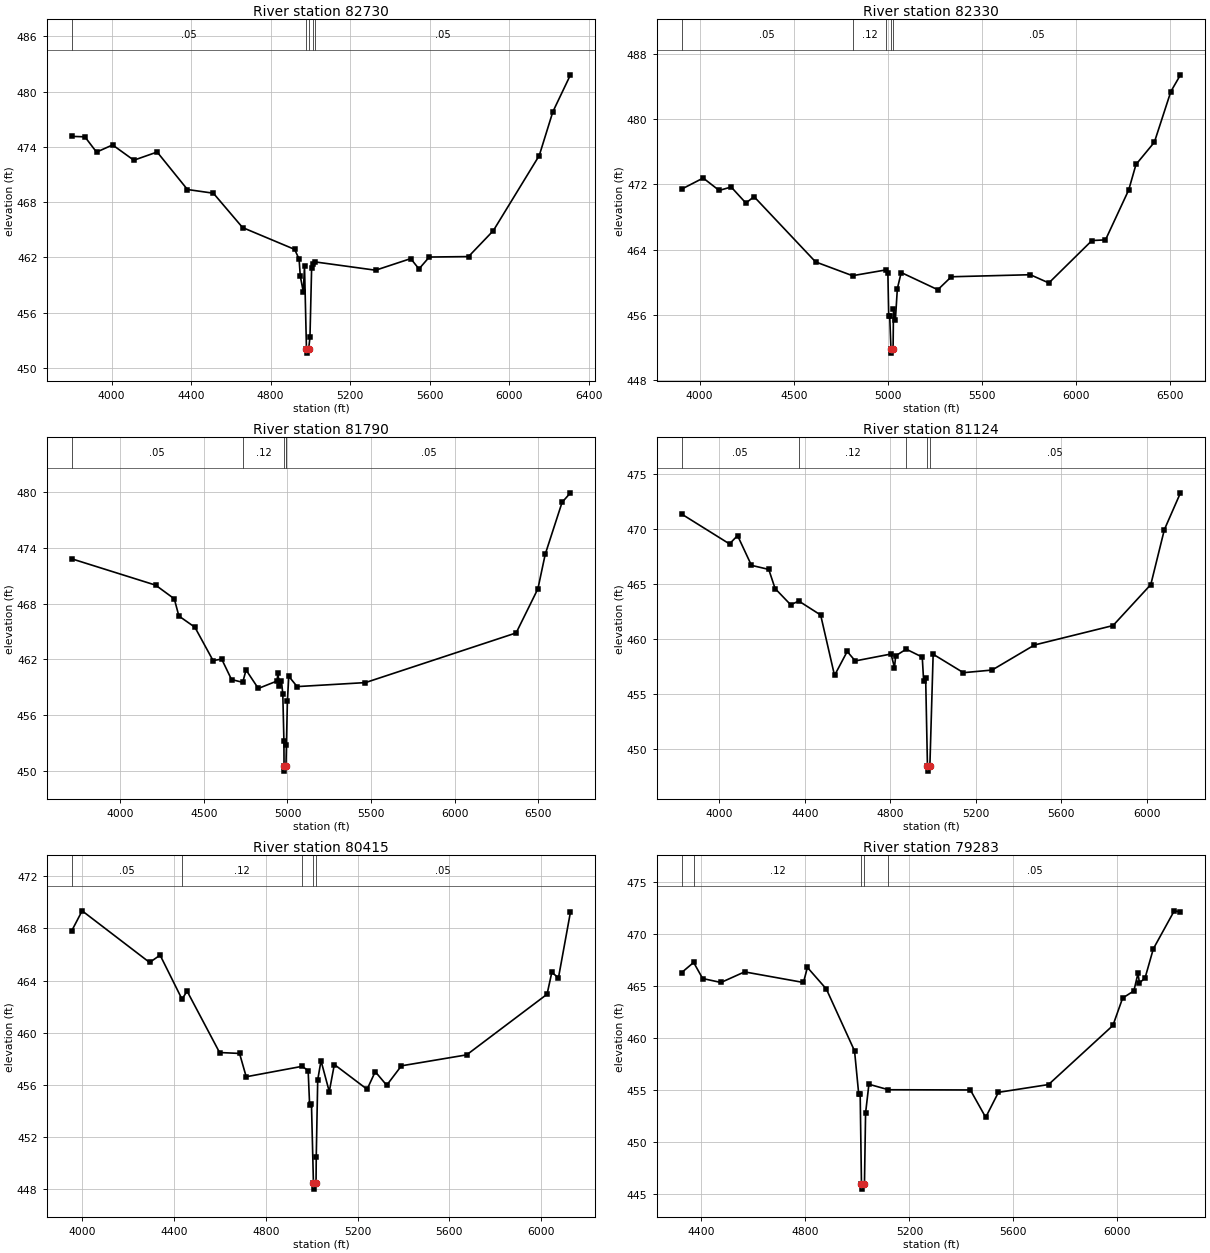
Type RM Length L Ch R = 1 ,82730   ,400,400,400
BEGIN DESCRIPTION:
Mapping XS b1ee4ec4
END DESCRIPTION:
XS GIS Cut Line= 3
      2687191.05      6921097.94      2686566.06      6920077.13
      2685302.18      6919722.97
#Sta/Elev= 30
  3798.6  475.13  3865.4  475.08    3924  473.42  4004.8   474.2  4111.6  472.54
  4228.9  473.43  4381.3  469.36  4511.7  468.96  4658.7  465.23  4920.7  462.86
    4943   461.8  4948.9  459.97  4964.3  458.23  4970.2  461.08    4980   452.1
  4981.5   451.6  4991.3   452.1  4997.6   453.3    5006  460.85  5010.7  461.28
    5024   461.5  5327.9   460.6  5504.5  461.86    5546  460.74  5597.9  462.03
  5795.3  462.08  5919.9  464.89  6151.1  473.05  6219.3  477.79  6308.1  481.81
#Mann= 5 ,-1 , 0
  3798.6     .05       0    4980     .03       0  4991.3     .05       0
  5010.7     .12       0    5024     .05       0
Bank Sta=4980,4991.3
XS Rating Curve= 0 ,0
Exp/Cntr=0.3,0.1

Type RM Length L Ch R = 1 ,82330   ,540,540,540
BEGIN DESCRIPTION:
Mapping XS e31c0b46
END DESCRIPTION:
XS GIS Cut Line= 3
      2687364.69      6920563.27      2686670.23      6919709.07
      2685156.95      6919375.88
#Sta/Elev= 30
  3904.3  471.43  4018.9  472.79  4103.7  471.27  4167.6  471.69  4245.9  469.72
    4289  470.51  4616.1  462.51  4812.2  460.82  4992.7  461.54  5000.1  461.21
  5004.6  455.86  5009.9  455.86  5016.5  451.83  5018.1  451.33  5027.8  451.83
    5030  456.71  5040.2  455.44  5050.5  459.24    5071  461.21  5265.5   459.1
  5337.2  460.69    5757  460.94  5855.4  459.93  6084.3  465.13  6156.3  465.21
  6279.7  471.33  6318.3  474.45    6416  477.18  6503.5  483.39  6554.7  485.44
#Mann= 5 ,-1 , 0
  3904.3     .05       0  4812.2     .12       0  4992.7     .05       0
  5016.5     .03       0  5027.8     .05       0
Bank Sta=5016.5,5027.8
XS Rating Curve= 0 ,0
Exp/Cntr=0.3,0.1

Type RM Length L Ch R = 1 ,81790   ,666,666,666
BEGIN DESCRIPTION:
Mapping XS 2c59c6d2
END DESCRIPTION:
XS GIS Cut Line= 4
      2687564.33       6920390.5      2686943.66      6919331.47
      2686869.88      6919275.05      2685336.39      6918636.01
#Sta/Elev= 30
  3709.9  472.84  4212.2     470  4323.6  468.53    4351  466.68  4446.8  465.47
  4555.5  461.88    4607  462.04  4665.7  459.84  4732.7  459.54  4752.5  460.87
  4825.9  458.88  4937.4  459.68  4943.6  460.59  4949.9  459.19  4964.4  459.65
  4972.2  458.28  4978.9   453.2  4979.6  450.48  4981.1  449.98  4990.9  450.48
  4993.9  452.78  4999.7  457.55    5008  460.19  5057.7  459.08  5466.1  459.51
    6367  464.86    6497  469.61  6540.7  473.32  6641.5  478.92  6691.6  479.94
#Mann= 5 ,-1 , 0
  3709.9     .05       0  4732.7     .12       0  4979.6     .03       0
  4990.9     .12       0  4993.9     .05       0
Bank Sta=4979.6,4990.9
XS Rating Curve= 0 ,0
Exp/Cntr=0.3,0.1

Type RM Length L Ch R = 1 ,81124   ,709,709,709
BEGIN DESCRIPTION:
Mapping XS b8647f51
END DESCRIPTION:
XS GIS Cut Line= 3
      2687620.17      6919782.57      2687064.61      6918792.99
       2686187.9      6917972.69
#Sta/Elev= 30
  3822.8  471.35    4047  468.63  4084.7  469.39  4149.7  466.68  4230.7  466.31
  4260.4  464.57  4333.4  463.09  4371.4  463.43  4473.7  462.16  4538.7  456.66
    4598  458.84  4635.7  457.98  4803.4  458.61  4819.3  457.37  4825.1  458.45
  4874.3  459.05  4949.4  458.33  4955.9  456.14  4965.3  456.46  4973.7  448.45
  4975.3  447.95  4985.1  448.45  5000.4  458.59  5142.1  456.91  5276.4  457.15
  5474.7  459.43  5842.6   461.2  6019.4  464.93  6082.9  469.93  6158.3  473.28
#Mann= 5 ,-1 , 0
  3822.8     .05       0  4371.4     .12       0  4874.3     .05       0
  4973.7     .03       0  4985.1     .05       0
Bank Sta=4973.7,4985.1
XS Rating Curve= 0 ,0
Exp/Cntr=0.3,0.1

Type RM Length L Ch R = 1 ,80415   ,1132,1132,1132
BEGIN DESCRIPTION:
Mapping XS beb715e6
END DESCRIPTION:
XS GIS Cut Line= 3
      2687831.96      6919393.13       2687491.7      6918601.49
      2686457.05      6917795.99
#Sta/Elev= 30
  3954.6   467.8  4000.5  469.35  4294.3  465.39  4340.1  465.95  4435.5  462.57
  4457.6  463.19  4599.1  458.48  4686.1  458.41  4715.1  456.62  4958.8  457.42
  4984.9  457.09  4991.3  454.47  4999.4   454.5  5007.9   448.5  5009.4     448
  5019.3   448.5  5020.2  450.48  5026.6  456.39    5041  457.85  5076.9  455.48
    5099  457.56  5241.7  455.66  5277.2  457.01    5327  455.97  5391.2  457.46
  5675.3   458.3  6025.5  462.95  6046.3  464.63  6075.2  464.21  6127.5  469.26
#Mann= 5 ,-1 , 0
  3954.6     .05       0  4435.5     .12       0  4958.8     .05       0
  5007.9     .03       0  5019.3     .05       0
Bank Sta=5007.9,5019.3
XS Rating Curve= 0 ,0
Exp/Cntr=0.3,0.1

Type RM Length L Ch R = 1 ,79283   ,961,961,961
BEGIN DESCRIPTION:
Mapping XS 78e5e70f
END DESCRIPTION:
XS GIS Cut Line= 3
      2688036.14      6919081.39        2688116.      6918404.27
      2687501.41      6917331.34
#Sta/Elev= 30
  4324.1  466.29  4370.3  467.27    4405  465.72  4475.5  465.34  4566.2  466.36
  4792.6  465.34  4807.8  466.79  4880.6  464.71  4989.1  458.75    5005  454.63
  5010.7  454.63  5015.7  445.94  5017.3  445.44  5027.2  445.94  5031.5  452.76
  5044.3  455.54  5119.5  455.01  5434.4  454.99  5493.4  452.35  5542.3  454.76
  5735.1  455.51  5982.6   461.2    6020  463.84  6063.2  464.53    6079  466.22
  6084.7  465.29  6106.3  465.78    6138  468.58  6218.5  472.24  6242.4  472.13
#Mann= 5 ,-1 , 0
  4324.1     .05       0  4370.3     .12       0  5015.7     .07       0
  5027.2     .12       0  5119.5     .05       0
Bank Sta=5015.7,5027.2
XS Rating Curve= 0 ,0
Exp/Cntr=0.3,0.1

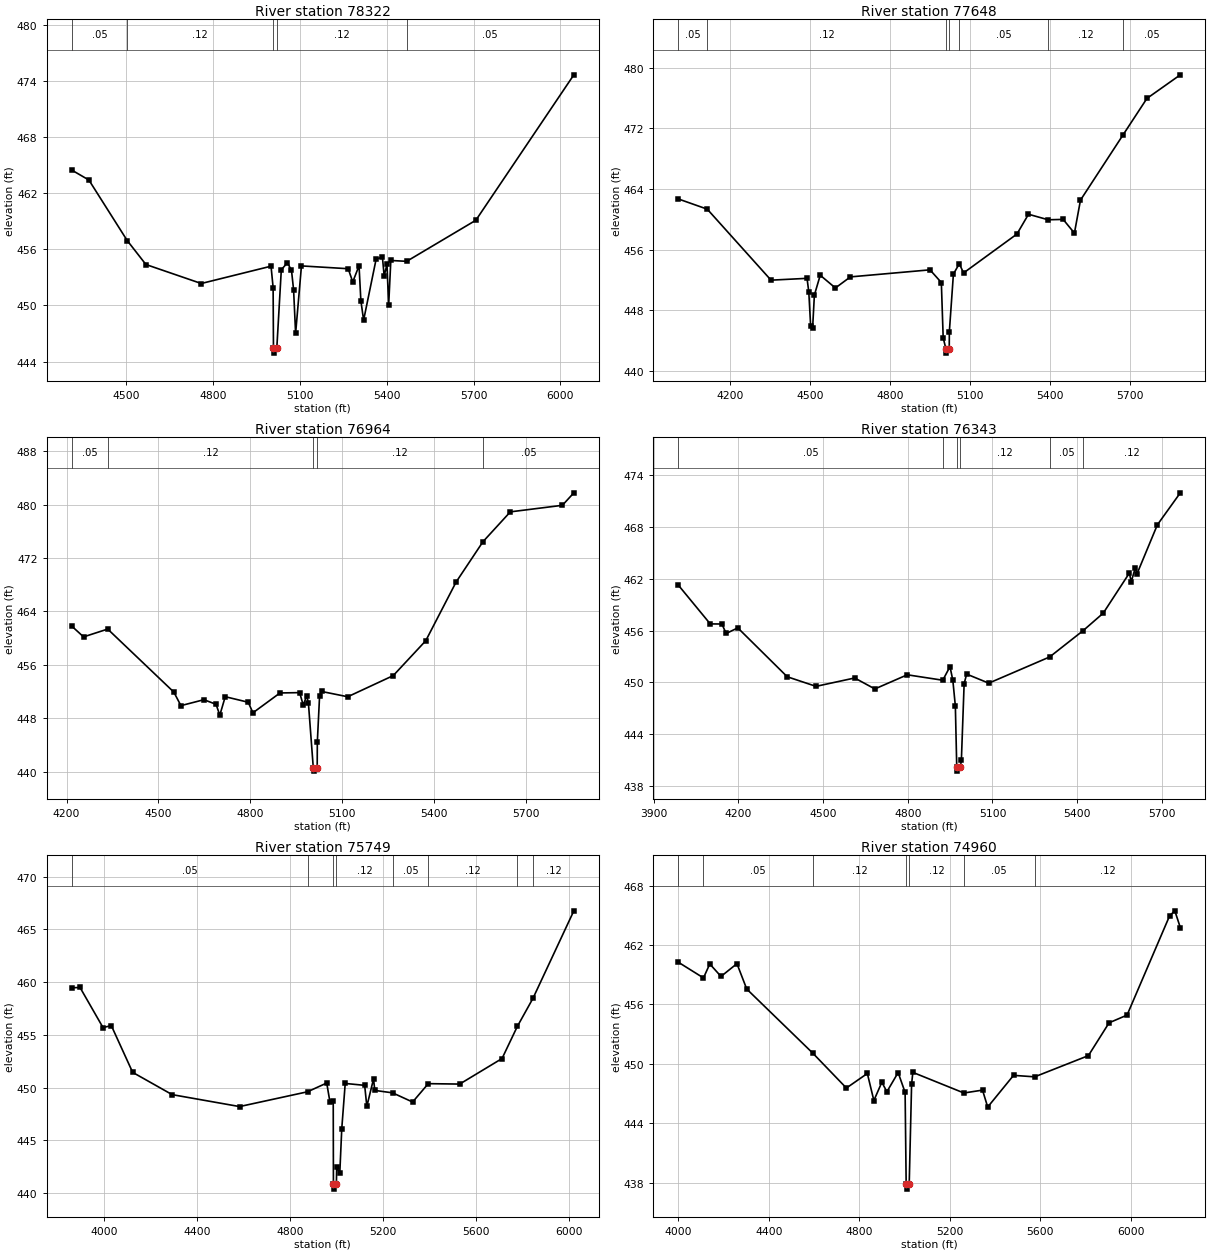
Type RM Length L Ch R = 1 ,78322   ,674,674,674
BEGIN DESCRIPTION:
Mapping XS 3c9f4ada
END DESCRIPTION:
XS GIS Cut Line= 4
       2688500.5       6918457.9      2688669.76      6917854.62
      2688552.58      6917733.09      2687736.58      6917268.67
#Sta/Elev= 30
  4311.9  464.46    4371   463.4  4503.4  456.93    4568  454.37  4759.2  452.34
  5000.2  454.19  5007.4  451.91  5008.6   445.4  5010.2   444.9  5020.1   445.4
  5035.7  453.81  5056.8  454.56  5070.9  453.74  5078.1  451.68  5085.1  447.01
  5105.3  454.22  5266.7  453.92  5282.5  452.51  5304.2  454.24  5310.5  450.51
    5320  448.42  5363.2  454.94  5384.9  455.17    5391  453.16  5400.7  454.38
  5406.5  449.99    5414   454.8  5468.8  454.71  5707.7   459.1  6046.2  474.64
#Mann= 5 ,-1 , 0
  4311.9     .05       0  4503.4     .12       0  5008.6     .07       0
  5020.1     .12       0  5468.8     .05       0
Bank Sta=5008.6,5020.1
XS Rating Curve= 0 ,0
Exp/Cntr=0.3,0.1

Type RM Length L Ch R = 1 ,77648   ,684,684,684
BEGIN DESCRIPTION:
Mapping XS 3cc4998f
END DESCRIPTION:
XS GIS Cut Line= 3
      2689400.98      6917985.98      2688648.06      6917333.79
      2687830.29      6916996.29
#Sta/Elev= 30
  4006.4  462.71  4115.1  461.36    4354     452  4488.9  452.24  4495.5  450.44
  4502.5   445.9  4509.8  445.69  4516.4  450.03  4538.3  452.65  4595.1  450.97
  4651.3  452.43  4949.5  453.36    4992  451.69  4998.9   444.4  5009.6  442.88
  5011.2  442.38  5021.6  442.88    5022   445.2  5037.2   452.8  5059.3  454.17
  5075.2  452.95  5275.2  458.08  5318.5  460.69  5392.2  459.96  5448.3  460.01
  5490.5   458.2  5513.2  462.55  5673.4  471.19  5762.2  475.96  5887.2  479.07
#Mann= 7 ,-1 , 0
  4006.4     .05       0  4115.1     .12       0  5009.6     .07       0
  5021.6     .12       0  5059.3     .05       0  5392.2     .12       0
  5673.4     .05       0
Bank Sta=5009.6,5021.6
XS Rating Curve= 0 ,0
Exp/Cntr=0.3,0.1

Type RM Length L Ch R = 1 ,76964   ,621,621,621
BEGIN DESCRIPTION:
Mapping XS 566019f9
END DESCRIPTION:
XS GIS Cut Line= 3
       2689446.8      6917890.95      2689123.18      6917167.99
      2688550.63      6916543.38
#Sta/Elev= 30
  4217.1  461.79  4255.6  460.18  4334.4  461.35  4550.3  451.91  4573.5  449.88
  4648.6  450.77  4688.2  450.08  4700.5  448.45  4718.2  451.22  4793.2  450.39
  4808.7  448.81    4897  451.78  4961.1  451.83    4973  449.95    4984  451.36
  4989.7  450.33  5005.7  440.57  5007.5  440.07  5018.5  440.57  5018.9  444.44
  5026.3  451.35  5033.1     452  5118.2  451.21  5266.8  454.38  5372.9   459.6
  5472.1   468.4  5559.8  474.44  5649.1  478.91    5819  479.89  5856.5  481.76
#Mann= 5 ,-1 , 0
  4217.1     .05       0  4334.4     .12       0  5005.7     .07       0
  5018.5     .12       0  5559.8     .05       0
Bank Sta=5005.7,5018.5
XS Rating Curve= 0 ,0
Exp/Cntr=0.3,0.1

Type RM Length L Ch R = 1 ,76343   ,594,594,594
BEGIN DESCRIPTION:
Mapping XS 684c9cf9
END DESCRIPTION:
XS GIS Cut Line= 4
      2689523.39      6917905.67      2689628.08      6917487.58
      2689546.57      6916906.85      2688956.88      6916425.55
#Sta/Elev= 30
  3986.8  461.29  4100.2  456.78  4141.4  456.77  4156.6  455.67  4197.8  456.32
    4373  450.65  4474.9  449.54  4611.9  450.51  4683.3  449.24  4798.1  450.88
  4923.9  450.25  4949.5  451.83  4959.6  450.23  4968.5  447.25  4973.4  440.21
  4975.2  439.71  4986.2  440.21  4989.9  441.04  4999.6  449.85  5008.5  450.96
  5086.8  449.91  5302.6  452.95  5421.1     456  5492.4  458.03    5585  462.68
  5591.5  461.66  5605.9  463.28  5612.3  462.61  5684.1  468.27  5765.4  471.98
#Mann= 6 ,-1 , 0
  3986.8     .05       0  4923.9     .12       0  4973.4     .07       0
  4986.2     .12       0  5302.6     .05       0  5421.1     .12       0
Bank Sta=4973.4,4986.2
XS Rating Curve= 0 ,0
Exp/Cntr=0.3,0.1

Type RM Length L Ch R = 1 ,75749   ,789,789,789
BEGIN DESCRIPTION:
Mapping XS d031a385
END DESCRIPTION:
XS GIS Cut Line= 3
      2690872.07      6917575.23      2690085.97       6916750.3
      2689153.75      6916335.85
#Sta/Elev= 30
  3860.5  459.46    3896  459.49    3995  455.69  4030.6  455.88  4122.4  451.45
  4292.3  449.34  4582.3  448.21  4874.5  449.61  4957.2  450.44  4971.4   448.6
  4985.2  448.72    4986  440.89  4987.8  440.39  4998.8  440.89    5000  442.44
  5013.5  441.95  5021.9  446.12  5036.7   450.4  5120.4  450.22  5129.7  448.23
  5158.5  450.82  5164.1  449.74  5240.4  449.51  5326.7  448.64    5394  450.38
  5529.1  450.34  5711.3  452.76  5777.1   455.8  5844.3  458.46  6020.2  466.75
#Mann= 8 ,-1 , 0
  3860.5     .05       0  4874.5     .12       0    4986     .07       0
  4998.8     .12       0  5240.4     .05       0    5394     .12       0
  5777.1     .05       0  5844.3     .12       0
Bank Sta=4986,4998.8
XS Rating Curve= 0 ,0
Exp/Cntr=0.3,0.1

Type RM Length L Ch R = 1 ,74960   ,799,799,799
BEGIN DESCRIPTION:
Williams Creek 104.0
END DESCRIPTION:
XS GIS Cut Line= 3
      2691201.95        6917090.        2690576.        6916311.
      2689472.77      6915793.99
#Sta/Elev= 30
  4000.3  460.27  4111.8  458.68  4139.6  460.09  4189.2  458.83  4259.6  460.12
  4302.8  457.56  4594.6  451.09  4743.1  447.57  4835.6  449.04  4864.4  446.31
  4899.6  448.15    4922   447.2  4971.6  449.13  5002.4  447.13  5007.1  437.87
    5009  437.37  5020.5  437.87  5031.1  447.98  5036.6  449.15  5262.1  447.07
  5344.4  447.36  5367.2  445.65  5481.4  448.85  5574.7   448.7    5812  450.84
  5903.3  454.15  5982.8  454.93    6171  464.96  6193.8  465.45    6218  463.76
#Mann= 7 ,-1 , 0
  4000.3     .12       0  4111.8     .05       0  4594.6     .12       0
  5007.1     .07       0  5020.5     .12       0  5262.1     .05       0
  5574.7     .12       0
Bank Sta=5007.1,5020.5
XS Rating Curve= 0 ,0
Exp/Cntr=0.3,0.1

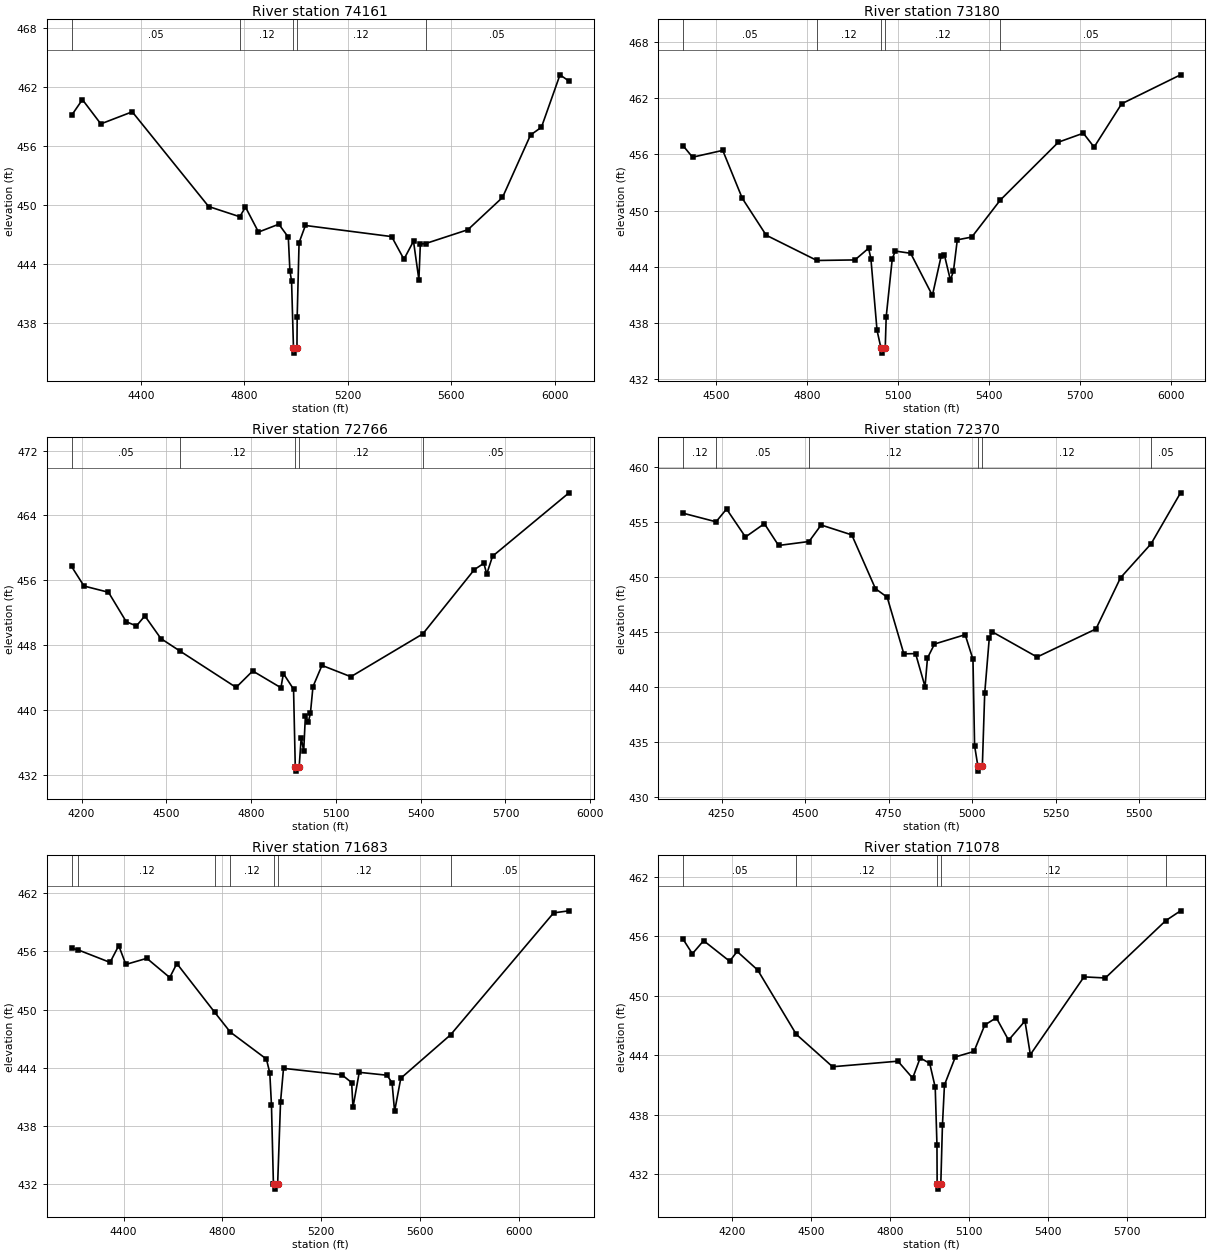
Type RM Length L Ch R = 1 ,74161   ,981,981,981
BEGIN DESCRIPTION:
Williams Creek 103.0
END DESCRIPTION:
XS GIS Cut Line= 3
       2691635.1       6916620.8      2691126.63      6915916.58
      2690124.72      6915586.11
#Sta/Elev= 30
  4131.4  459.14  4173.4  460.75  4244.6  458.28  4366.1  459.51  4661.5  449.88
  4781.9  448.84    4804  449.82  4854.3  447.28  4932.9  448.08  4969.6  446.76
  4975.7  443.37  4982.2  442.28  4989.6  435.47  4991.5  434.97    5003  435.47
  5003.9  438.68  5011.2   446.2  5035.6  447.95  5369.2  446.82  5416.7  444.52
  5453.7  446.35  5474.5  442.44  5480.2  446.07  5500.3  446.11    5664  447.52
  5797.8   450.8  5906.2  457.15  5948.4  457.94  6020.1  463.27    6055  462.63
#Mann= 5 ,-1 , 0
  4131.4     .05       0  4781.9     .12       0  4989.6     .07       0
    5003     .12       0  5500.3     .05       0
Bank Sta=4989.6,5003
XS Rating Curve= 0 ,0
Exp/Cntr=0.3,0.1

Type RM Length L Ch R = 1 ,73180   ,414,414,414
BEGIN DESCRIPTION:
Williams Creek 102.0
END DESCRIPTION:
XS GIS Cut Line= 3
      2691776.86      6915564.13      2691296.05      6915191.02
      2690273.37      6915067.58
#Sta/Elev= 30
  4391.4  456.94  4422.6  455.71  4522.1  456.44  4586.4  451.31  4665.1  447.36
  4832.4  444.65  4957.5  444.71  5002.5  445.96  5010.1  444.85  5030.3  437.17
  5043.6  435.23  5045.5  434.73  5057.3  435.23  5060.5  438.62  5080.6  444.86
  5090.7  445.66  5141.1  445.42  5212.7  440.91  5241.8  445.15  5251.9  445.28
    5272  442.55  5282.1  443.52  5294.7  446.86  5342.5  447.16  5436.6  451.13
  5627.8  457.32  5709.8  458.28  5745.4  456.79  5836.1  461.43  6030.1  464.53
#Mann= 5 ,-1 , 0
  4391.4     .05       0  4832.4     .12       0  5043.6     .07       0
  5057.3     .12       0  5436.6     .05       0
Bank Sta=5043.6,5057.3
XS Rating Curve= 0 ,0
Exp/Cntr=0.3,0.1

Type RM Length L Ch R = 1 ,72766   ,396,396,396
BEGIN DESCRIPTION:
Williams Creek 100.0
END DESCRIPTION:
XS GIS Cut Line= 3
      2692065.24      6915312.28      2691375.49      6914840.79
      2690471.46      6914645.89
#Sta/Elev= 30
  4164.5   457.7  4208.5  455.28  4295.2  454.51  4358.1  450.87    4394  450.35
  4423.9  451.59  4480.7  448.79  4549.9  447.21  4746.9  442.76  4805.6  444.79
  4905.4  442.72  4914.2  444.47  4950.1  442.54  4956.2  432.92  4958.1  432.42
  4969.9  432.92  4977.1  436.55    4986  434.91    4992  439.26  5002.3  438.49
  5009.7  439.54  5018.8  442.85  5050.6  445.48  5152.9  444.08  5407.5  449.37
  5589.9  457.31  5623.5  458.09  5633.7  456.76  5654.2  458.96  5924.8  466.79
#Mann= 5 ,-1 , 0
  4164.5     .05       0  4549.9     .12       0  4956.2     .07       0
  4969.9     .12       0  5407.5     .05       0
Bank Sta=4956.2,4969.9
XS Rating Curve= 0 ,0
Exp/Cntr=0.3,0.1

Type RM Length L Ch R = 1 ,72370   ,687,687,687
BEGIN DESCRIPTION:
Williams Creek 99.0
END DESCRIPTION:
XS GIS Cut Line= 3
      2692197.59      6915113.52       2691569.5      6914518.62
      2691017.04       6914228.1
#Sta/Elev= 30
  4134.9   455.8  4233.6  455.02  4265.1  456.18  4321.7  453.64  4378.3  454.85
  4420.8  452.87    4512  453.23  4548.2  454.73    4640  453.83  4710.8  448.95
    4746  448.17  4795.8  443.03    4831  443.05  4859.3  440.05  4866.6  442.65
  4887.6  443.92  4979.4  444.77  5002.8  442.53  5007.6   434.7  5017.2  432.88
  5019.1  432.38  5030.9  432.88  5037.9  439.44  5051.7  444.49  5060.4  445.03
  5194.7  442.74    5371  445.29  5444.6  449.94  5536.2  453.03  5624.2  457.65
#Mann= 6 ,-1 , 0
  4134.9     .12       0  4233.6     .05       0    4512     .12       0
  5017.2     .07       0  5030.9     .12       0  5536.2     .05       0
Bank Sta=5017.2,5030.9
XS Rating Curve= 0 ,0
Exp/Cntr=0.3,0.1

Type RM Length L Ch R = 1 ,71683   ,605,605,605
BEGIN DESCRIPTION:
Williams Creek 98.0
END DESCRIPTION:
XS GIS Cut Line= 3
      2692469.09       6914856.9      2691962.54      6914224.07
       2690785.1      6913974.97
#Sta/Elev= 30
  4189.4  456.32    4217  456.14  4345.3  454.86  4380.5  456.59  4409.3  454.65
  4494.2  455.28    4587   453.3  4615.8  454.74  4768.4  449.73  4832.2  447.67
  4978.3  444.89    4992  443.47  4998.8  440.18  5006.7  432.02    5010  431.97
    5012  431.47  5023.8  431.97  5035.6  440.47  5047.6  443.93  5284.2  443.26
  5323.5  442.46  5328.8   439.9  5354.2  443.52  5466.6  443.22  5487.1  442.44
  5497.3  439.49  5522.5  442.91    5724  447.39  6141.3  459.97  6203.5  460.18
#Mann= 7 ,-1 , 0
  4189.4     .05       0    4217     .12       0  4768.4     .05       0
  4832.2     .12       0    5010     .07       0  5023.8     .12       0
    5724     .05       0
Bank Sta=5010,5023.8
XS Rating Curve= 0 ,0
Exp/Cntr=0.3,0.1

Type RM Length L Ch R = 1 ,71078   ,345,345,345
BEGIN DESCRIPTION:
Williams Creek 97.0
END DESCRIPTION:
XS GIS Cut Line= 3
      2692423.94      6914502.71      2691782.49      6913754.28
      2690896.16       6913582.6
#Sta/Elev= 30
  4014.3   455.7  4049.5  454.23  4092.3  455.55  4191.1  453.48  4219.6  454.46
  4297.6  452.59    4444  446.11  4581.8  442.84  4829.9   443.4  4885.9  441.69
  4914.4  443.73  4950.6  443.18  4971.5  440.77  4978.1  434.96  4978.8     431
  4980.8   430.5  4992.7     431  4998.9  436.94  5006.6  441.01    5048  443.83
  5118.7  444.38  5159.4  447.04  5203.3  447.78  5249.9  445.52  5312.2  447.45
  5332.6  444.06  5536.3   451.9  5617.3  451.79  5846.6  457.57  5902.8  458.56
#Mann= 5 ,-1 , 0
  4014.3     .05       0    4444     .12       0  4978.8     .07       0
  4992.7     .12       0  5846.6     .05       0
Bank Sta=4978.8,4992.7
XS Rating Curve= 0 ,0
Exp/Cntr=0.3,0.1