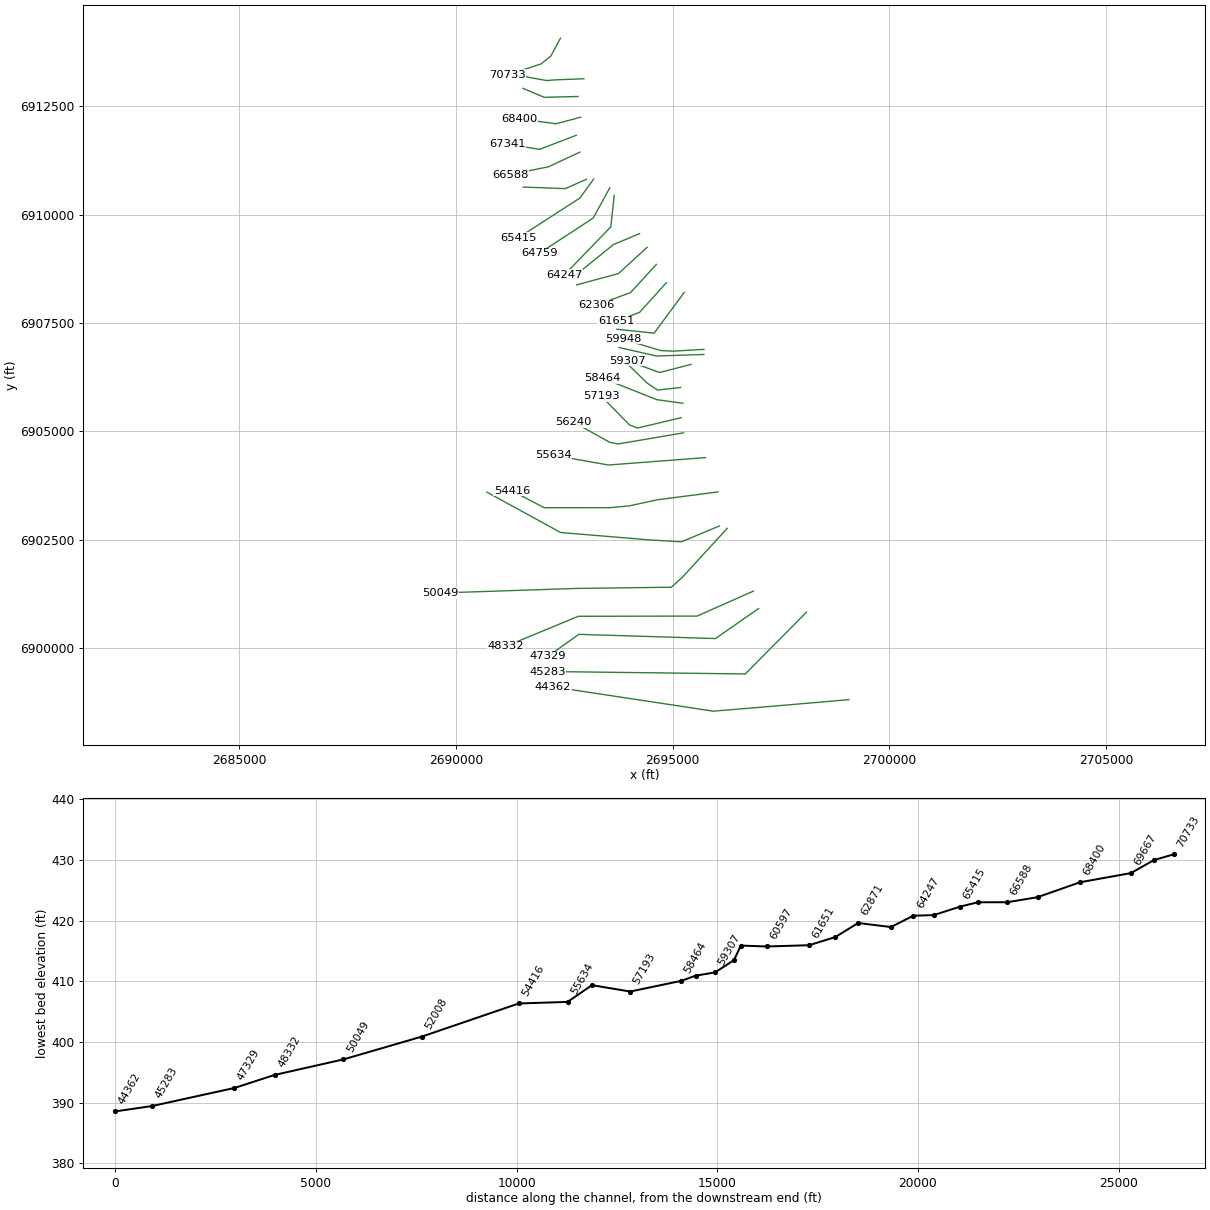
HEC-RAS study Williams Creek.prj: Williams Creek Base Level Engineering

--- Williams Creek.g01 (geometry) --- (continued)

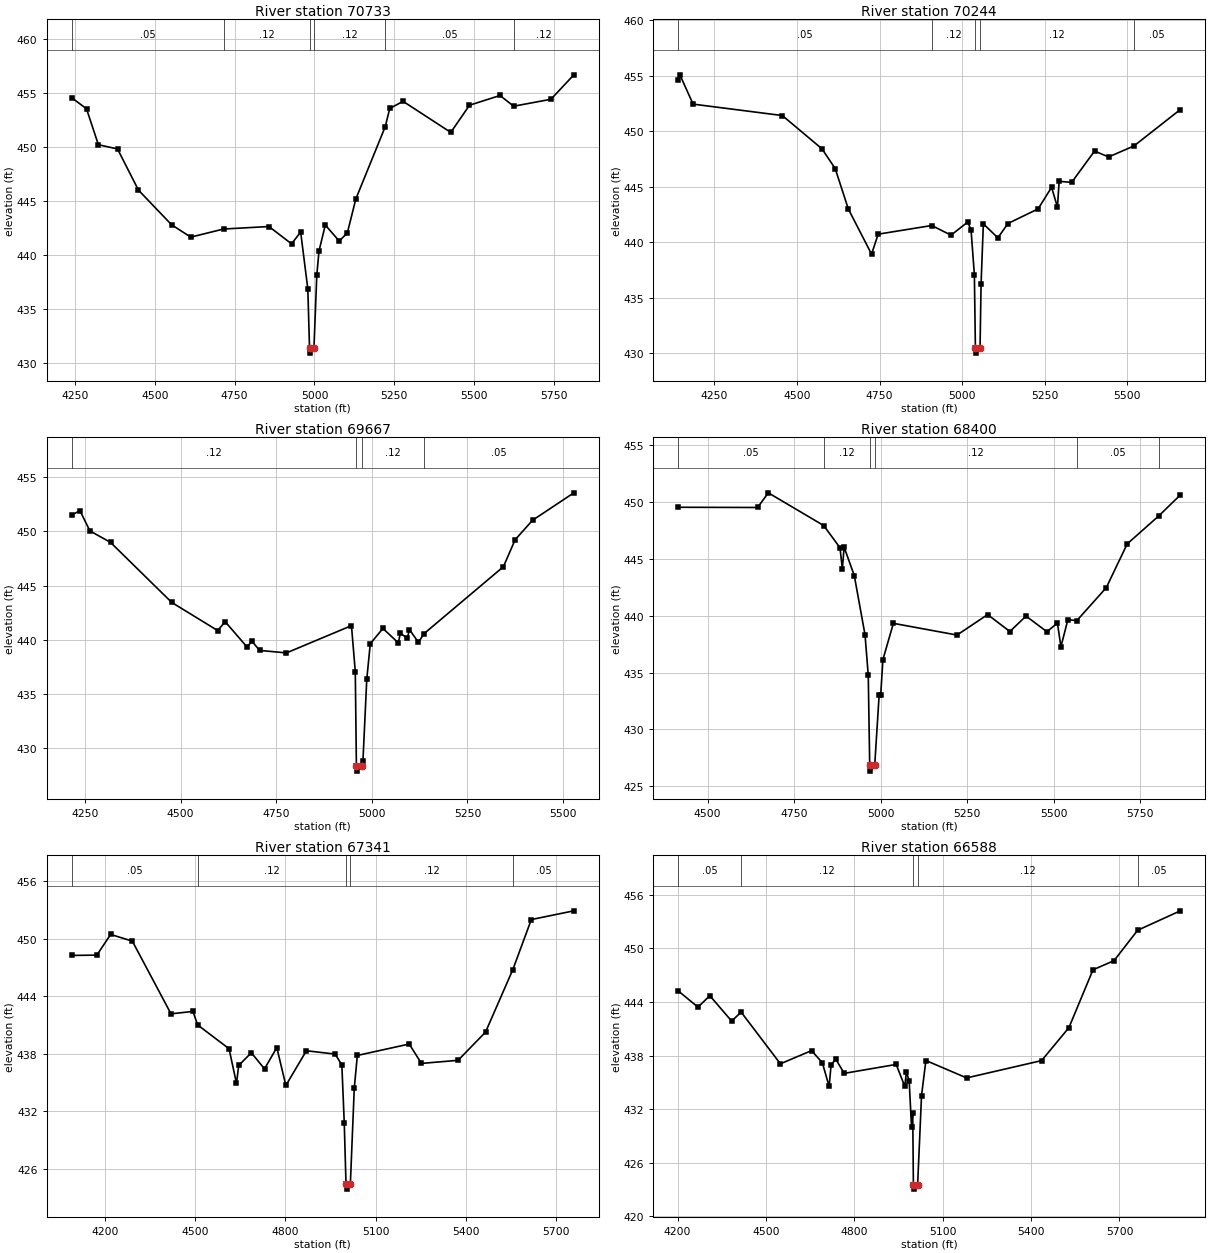
Type RM Length L Ch R = 1 ,70733   ,489,489,489
BEGIN DESCRIPTION:
Williams Creek 96.0
END DESCRIPTION:
XS GIS Cut Line= 4
      2692409.33      6914071.58      2692185.37      6913657.52
      2691962.46      6913478.71        2691188.      6913225.24
#Sta/Elev= 30
  4240.4  454.53  4286.5  453.51  4323.7  450.19  4383.6   449.8  4449.2  445.99
  4552.9  442.79  4612.9  441.65  4715.6   442.4  4857.6  442.63  4928.3  441.03
  4956.8  442.12  4979.2  436.86  4984.5  431.43  4986.5  430.93  4998.4  431.43
  5007.3  438.15  5014.2  440.37  5033.9  442.77  5077.4  441.29  5102.9  442.04
  5129.5  445.18  5221.5  451.86  5235.6  453.54  5277.3   454.2  5426.7  451.33
  5485.2  453.84  5580.7  454.74  5623.5  453.75    5740  454.39  5811.8  456.65
#Mann= 6 ,-1 , 0
  4240.4     .05       0  4715.6     .12       0  4984.5     .07       0
  4998.4     .12       0  5221.5     .05       0  5623.5     .12       0
Bank Sta=4984.5,4998.4
XS Rating Curve= 0 ,0
Exp/Cntr=0.3,0.1

Type RM Length L Ch R = 1 ,70244   ,577,577,577
BEGIN DESCRIPTION:
Williams Creek 95.0
END DESCRIPTION:
XS GIS Cut Line= 4
      2692950.97        6913136.      2692275.65      6913109.99
      2692092.34      6913094.31      2691442.33      6913211.55
#Sta/Elev= 30
  4140.2   454.6  4145.2  455.08  4185.2  452.44  4455.4  451.41  4575.5  448.41
  4615.5  446.63  4655.2  442.99  4725.6  438.92  4745.6  440.72  4907.8   441.5
  4966.2  440.63  5016.6  441.81  5026.8  441.12  5036.9  437.07    5040   430.5
    5042     430  5054.1   430.5  5057.2  436.24  5064.1  441.65  5108.1  440.39
  5138.5  441.68  5229.9     443  5270.6  444.94  5288.5  443.16  5293.6  445.48
  5331.6  445.39  5400.8  448.21  5443.4  447.68  5520.1  448.67  5660.5  451.95
#Mann= 5 ,-1 , 0
  4140.2     .05       0  4907.8     .12       0    5040     .07       0
  5054.1     .12       0  5520.1     .05       0
Bank Sta=5040,5054.1
XS Rating Curve= 0 ,0
Exp/Cntr=0.3,0.1

Type RM Length L Ch R = 1 ,69667   ,1267,1267,1267
BEGIN DESCRIPTION:
Williams Creek 94.0
END DESCRIPTION:
XS GIS Cut Line= 3
      2692817.27      6912727.18       2692032.7       6912708.1
      2691546.47      6912914.69
#Sta/Elev= 30
  4215.2  451.51  4236.5  451.93  4262.6  450.05  4316.5  448.99  4476.5  443.44
  4596.6  440.84  4616.6  441.65  4673.4  439.32  4686.6  439.84  4706.6     439
  4776.6  438.77  4946.7  441.29  4956.7  437.03  4959.6  428.34  4961.6  427.84
  4973.8  428.34  4976.7  428.77  4986.7  436.32  4995.9  439.62    5029  441.03
  5069.2   439.7  5074.6  440.59  5092.8  440.13  5098.3  440.93  5121.9  439.74
  5136.5  440.55  5344.1  446.74  5374.7  449.23  5420.2  451.03  5528.3  453.57
#Mann= 4 ,-1 , 0
  4215.2     .12       0  4959.6     .07       0  4973.8     .12       0
  5136.5     .05       0
Bank Sta=4959.6,4973.8
XS Rating Curve= 0 ,0
Exp/Cntr=0.3,0.1

Type RM Length L Ch R = 1 ,68400   ,1059,1059,1059
BEGIN DESCRIPTION:
Williams Creek 93.0
END DESCRIPTION:
XS GIS Cut Line= 3
      2692877.46      6912249.09      2692312.27      6912097.74
      2691453.88      6912210.02
#Sta/Elev= 30
  4414.9  449.54  4644.2  449.52  4675.2  450.81  4835.3  447.93  4882.3  445.98
  4889.1  444.12  4894.3  446.03  4923.7  443.52  4954.7  438.31    4964  434.75
  4968.2  426.83  4970.2  426.33  4982.6  426.83  4995.5  433.06    5000  433.06
  5006.3  436.14  5036.6  439.33  5220.5   438.3  5308.9   440.1  5373.3  438.61
  5419.8  439.97  5480.3  438.59  5510.6  439.36  5520.7  437.27  5540.8  439.65
  5566.7  439.57  5651.8  442.47  5712.3  446.32  5802.7  448.76  5865.7  450.62
#Mann= 6 ,-1 , 0
  4414.9     .05       0  4835.3     .12       0  4968.2     .07       0
  4982.6     .12       0  5566.7     .05       0  5802.7     .12       0
Bank Sta=4968.2,4982.6
XS Rating Curve= 0 ,0
Exp/Cntr=0.3,0.1

Type RM Length L Ch R = 1 ,67341   ,753,753,753
BEGIN DESCRIPTION:
Williams Creek 92.0
END DESCRIPTION:
XS GIS Cut Line= 3
      2692773.79       6911831.5      2691924.93       6911505.5
      2691176.63      6911631.86
#Sta/Elev= 30
  4090.7  448.24    4174  448.27  4219.9  450.43  4291.9  449.73  4420.4  442.15
  4493.3   442.4    4509  440.99  4613.3  438.51    4638  434.89  4645.4  436.77
  4687.3  438.09  4731.1  436.41    4772  438.63    4802  434.68  4870.3   438.3
    4966  437.95  4988.1  436.81    4996   430.8  5001.9  424.37  5003.9  423.87
  5016.3  424.37  5029.3  434.38  5039.5  437.81  5211.9     439  5252.5  436.98
  5374.2   437.3  5465.4  440.24  5556.3  446.77  5617.6  451.98  5758.9  452.89
#Mann= 5 ,-1 , 0
  4090.7     .05       0    4509     .12       0  5001.9     .07       0
  5016.3     .12       0  5556.3     .05       0
Bank Sta=5001.9,5016.3
XS Rating Curve= 0 ,0
Exp/Cntr=0.3,0.1

Type RM Length L Ch R = 1 ,66588   ,735,735,735
BEGIN DESCRIPTION:
Williams Creek 91.0
END DESCRIPTION:
XS GIS Cut Line= 3
      2692856.02      6911442.37       2692133.6      6911104.55
      2691245.66      6910922.08
#Sta/Elev= 30
  4202.5  445.25  4269.5  443.43  4309.7  444.71  4383.7  441.87  4416.1  442.87
  4549.2  437.08  4655.1  438.56  4691.7  437.19  4714.6  434.54  4721.4  436.99
  4737.4  437.59  4765.8  436.01  4942.2  437.01  4971.4  434.55  4976.9  436.16
  4986.3  435.16  4994.2  430.04  4998.3  431.58  5000.6  423.54  5002.6  423.04
    5015  423.54  5028.2  433.51    5043  437.45  5181.3   435.5  5435.7  437.44
  5528.4  441.13  5610.1  447.61  5681.6  448.64  5761.6  452.04  5906.5  454.22
#Mann= 5 ,-1 , 0
  4202.5     .05       0  4416.1     .12       0  5000.6     .07       0
    5015     .12       0  5761.6     .05       0
Bank Sta=5000.6,5015
XS Rating Curve= 0 ,0
Exp/Cntr=0.3,0.1

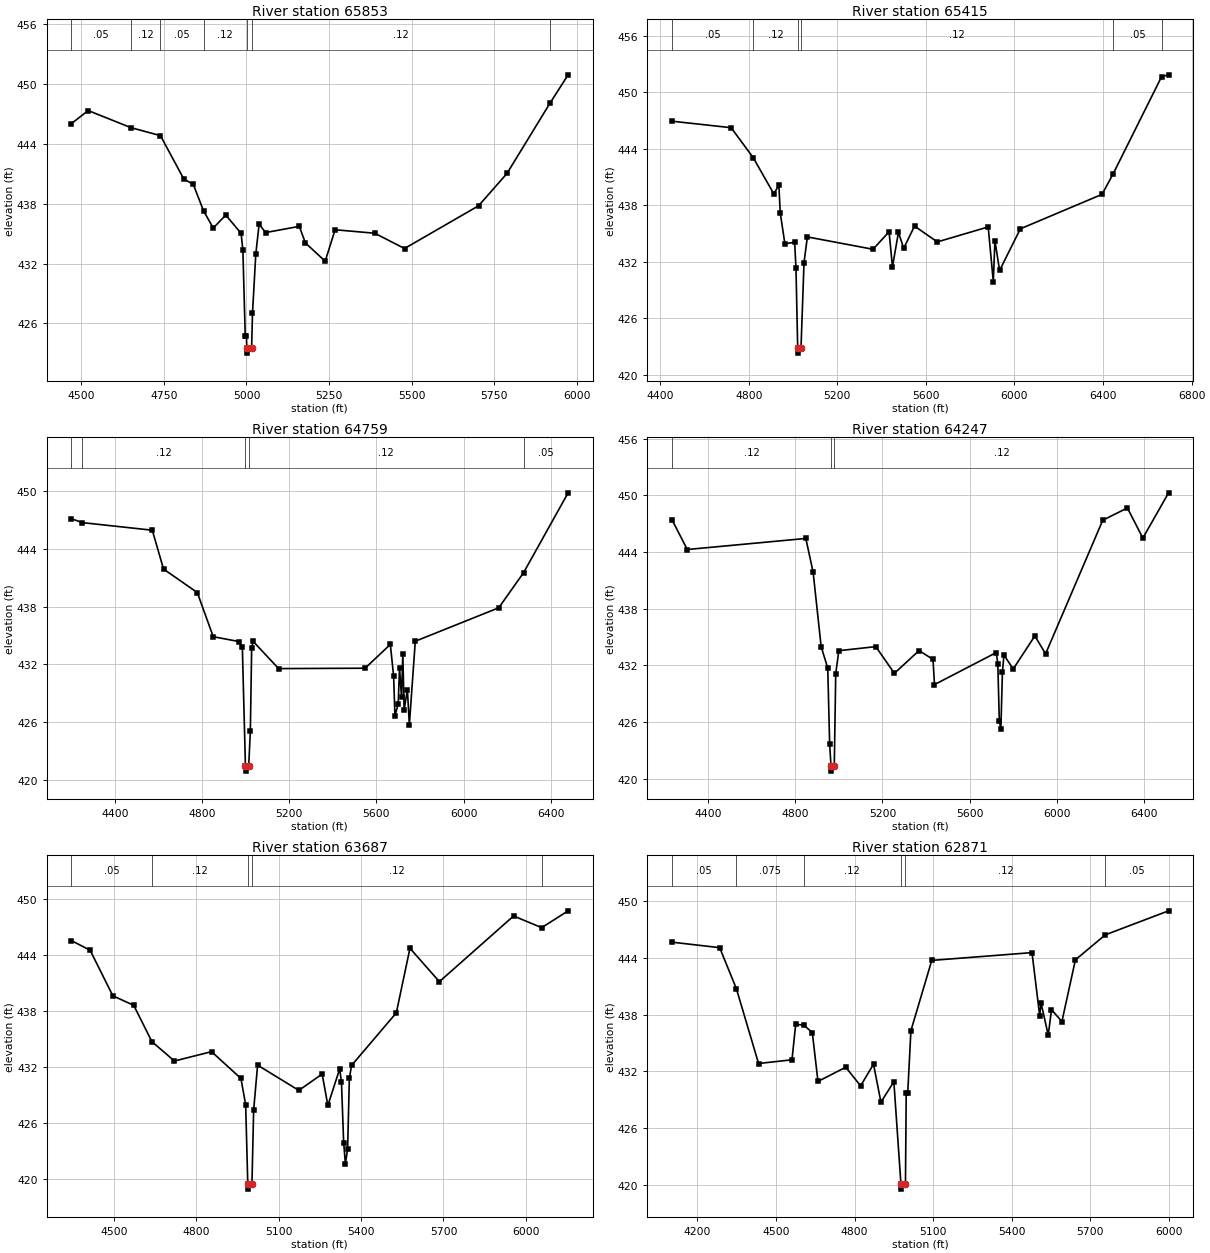
Type RM Length L Ch R = 1 ,65853   ,438,438,438
BEGIN DESCRIPTION:
Williams Creek 90.0
END DESCRIPTION:
XS GIS Cut Line= 3
      2693007.87      6910816.35      2692524.26      6910600.24
      2691551.02        6910636.
#Sta/Elev= 30
  4470.3  446.03  4520.9  447.33  4650.1  445.62  4739.6  444.82  4810.4  440.47
    4839  439.94    4870  437.29  4899.5  435.56  4937.4  436.86  4983.8  435.03
  4989.2  433.33  4996.3  424.77    5000  424.77  5000.9  423.53  5002.9  423.03
  5015.6  423.53  5018.3  427.03  5028.3  432.96  5038.3  435.94  5058.3  435.11
  5160.1  435.73  5178.4  434.07  5238.4  432.24  5268.4  435.39  5388.5  435.04
  5478.6  433.51  5702.7  437.79  5788.8  441.03  5919.6   448.1  5973.9  450.91
#Mann= 7 ,-1 , 0
  4470.3     .05       0  4650.1     .12       0  4739.6     .05       0
    4870     .12       0  5000.9     .07       0  5015.6     .12       0
  5919.6     .05       0
Bank Sta=5000.9,5015.6
XS Rating Curve= 0 ,0
Exp/Cntr=0.3,0.1

Type RM Length L Ch R = 1 ,65415   ,656,656,656
BEGIN DESCRIPTION:
Williams Creek 89.0
END DESCRIPTION:
XS GIS Cut Line= 3
      2693177.55       6910822.8      2692855.97      6910380.93
      2691430.97      6909461.63
#Sta/Elev= 30
  4453.5  446.93  4720.6  446.24  4820.7  443.05  4913.3  439.22  4936.2  440.14
  4942.4  437.21  4963.2  433.95  5007.5  434.06  5013.5   431.3  5021.2  422.82
  5023.2  422.32  5036.1  422.82  5049.7  431.93  5064.9  434.65  5361.3  433.34
  5433.8   435.2    5449  431.47  5476.1  435.13  5499.8  433.44  5548.7   435.8
  5651.6  434.12  5881.3  435.71  5904.4  429.91  5911.7  434.27  5932.8  431.09
  6026.5  435.51  6395.4  439.17  6445.6  441.35  6664.4  451.66  6695.8  451.85
#Mann= 6 ,-1 , 0
  4453.5     .05       0  4820.7     .12       0  5021.2     .07       0
  5036.1     .12       0  6445.6     .05       0  6664.4     .12       0
Bank Sta=5021.2,5036.1
XS Rating Curve= 0 ,0
Exp/Cntr=0.3,0.1

Type RM Length L Ch R = 1 ,64759   ,512,512,512
BEGIN DESCRIPTION:
Williams Creek 88.0
END DESCRIPTION:
XS GIS Cut Line= 3
      2693549.07      6910621.39      2693164.84       6909920.5
      2691925.97      6909110.98
#Sta/Elev= 30
  4200.7  447.11  4249.8  446.71  4571.5  445.92  4623.1  441.89  4778.1  439.45
  4851.2  434.87  4968.6  434.37  4984.8   433.8    4999  421.42    5001  420.92
  5013.9  421.42  5021.5  425.07  5027.5  433.67  5034.4  434.38  5151.2  431.56
  5548.1   431.6    5664  434.07  5679.1  430.78  5685.1  426.66  5700.2  427.89
  5706.1  431.65  5715.3  428.58  5721.3   433.1  5727.3  427.27  5742.3  429.38
  5751.2  425.72  5778.5   434.4  6161.6  437.87  6275.6  441.52  6479.9   449.8
#Mann= 5 ,-1 , 0
  4200.7     .05       0  4249.8     .12       0    4999     .07       0
  5013.9     .12       0  6275.6     .05       0
Bank Sta=4999,5013.9
XS Rating Curve= 0 ,0
Exp/Cntr=0.3,0.1

Type RM Length L Ch R = 1 ,64247   ,560,560,560
BEGIN DESCRIPTION:
Williams Creek 86.0
END DESCRIPTION:
XS GIS Cut Line= 3
      2693648.88      6910440.85      2693572.49      6909718.81
      2692495.24      6908605.13
#Sta/Elev= 30
  4235.9  447.43    4306  444.27  4849.2  445.44  4882.7  441.87  4919.5  433.98
  4949.7  431.72  4958.4  423.69  4964.7  421.31  4966.7  420.81  4979.6  421.31
  4986.3  431.14  5000.5  433.56    5170  433.99  5254.9  431.16  5368.1  433.57
  5431.9  432.64  5438.8  429.97  5721.8  433.36  5728.8   432.2  5735.9  426.07
  5742.9  425.29  5750.1  431.29    5757   433.1  5799.5  431.62  5898.5  435.12
  5947.9  433.23  6209.8  447.37  6322.7  448.67  6393.5  445.48  6511.4  450.27
#Mann= 3 ,-1 , 0
  4235.9     .12       0  4964.7     .07       0  4979.6     .12       0
Bank Sta=4964.7,4979.6
XS Rating Curve= 0 ,0
Exp/Cntr=0.3,0.1

Type RM Length L Ch R = 1 ,63687   ,816,816,816
BEGIN DESCRIPTION:
Williams Creek 84.0
END DESCRIPTION:
XS GIS Cut Line= 3
      2694234.78      6909561.68      2693630.65      6909308.22
      2692734.84      6908582.55
#Sta/Elev= 30
  4345.8   445.5  4413.6  444.48  4496.3  439.61  4572.4  438.59  4638.6  434.71
  4720.5  432.64  4855.6  433.64  4962.6  430.78  4979.9  427.97  4987.6  419.45
  4989.6  418.95  5002.7  419.45  5008.9  427.38  5023.3   432.2  5173.5   429.5
  5258.3  431.25  5279.1  427.89  5322.2   431.8  5328.7  430.35  5336.6  423.93
    5343  421.67    5351  423.25  5357.4  430.79  5365.4  432.17  5528.4  437.79
    5578  444.69  5685.1  441.12  5955.3  448.14  6057.6  446.89  6153.8  448.69
#Mann= 5 ,-1 , 0
  4345.8     .05       0  4638.6     .12       0  4987.6     .07       0
  5002.7     .12       0  6057.6     .05       0
Bank Sta=4987.6,5002.7
XS Rating Curve= 0 ,0
Exp/Cntr=0.3,0.1

Type RM Length L Ch R = 1 ,62871   ,565,565,565
BEGIN DESCRIPTION:
Williams Creek 83.0
END DESCRIPTION:
XS GIS Cut Line= 3
      2694409.39      6909245.31      2693747.34      6908639.63
      2692782.45      6908378.13
#Sta/Elev= 30
  4102.7  445.62  4284.9  445.04  4348.8  440.72  4433.5  432.84  4561.1  433.23
  4575.3  436.95  4605.3   436.9  4638.8   436.1  4660.4  430.95  4766.5  432.45
  4823.2  430.49  4872.6  432.76  4900.9  428.77  4950.3  430.92  4977.4  420.11
  4979.4  419.61  4994.6  420.11  4997.5  429.75  5003.3  429.75  5015.4  436.29
  5095.1   443.7    5478  444.52  5507.4  437.86  5512.6   439.2  5540.1  435.82
  5552.4  438.51  5592.2  437.26  5643.8  443.76    5758  446.39  5999.7  448.92
#Mann= 6 ,-1 , 0
  4102.7     .05       0  4348.8    .075       0  4605.3     .12       0
  4977.4     .07       0  4994.6     .12       0    5758     .05       0
Bank Sta=4977.4,4994.6
XS Rating Curve= 0 ,0
Exp/Cntr=0.3,0.1

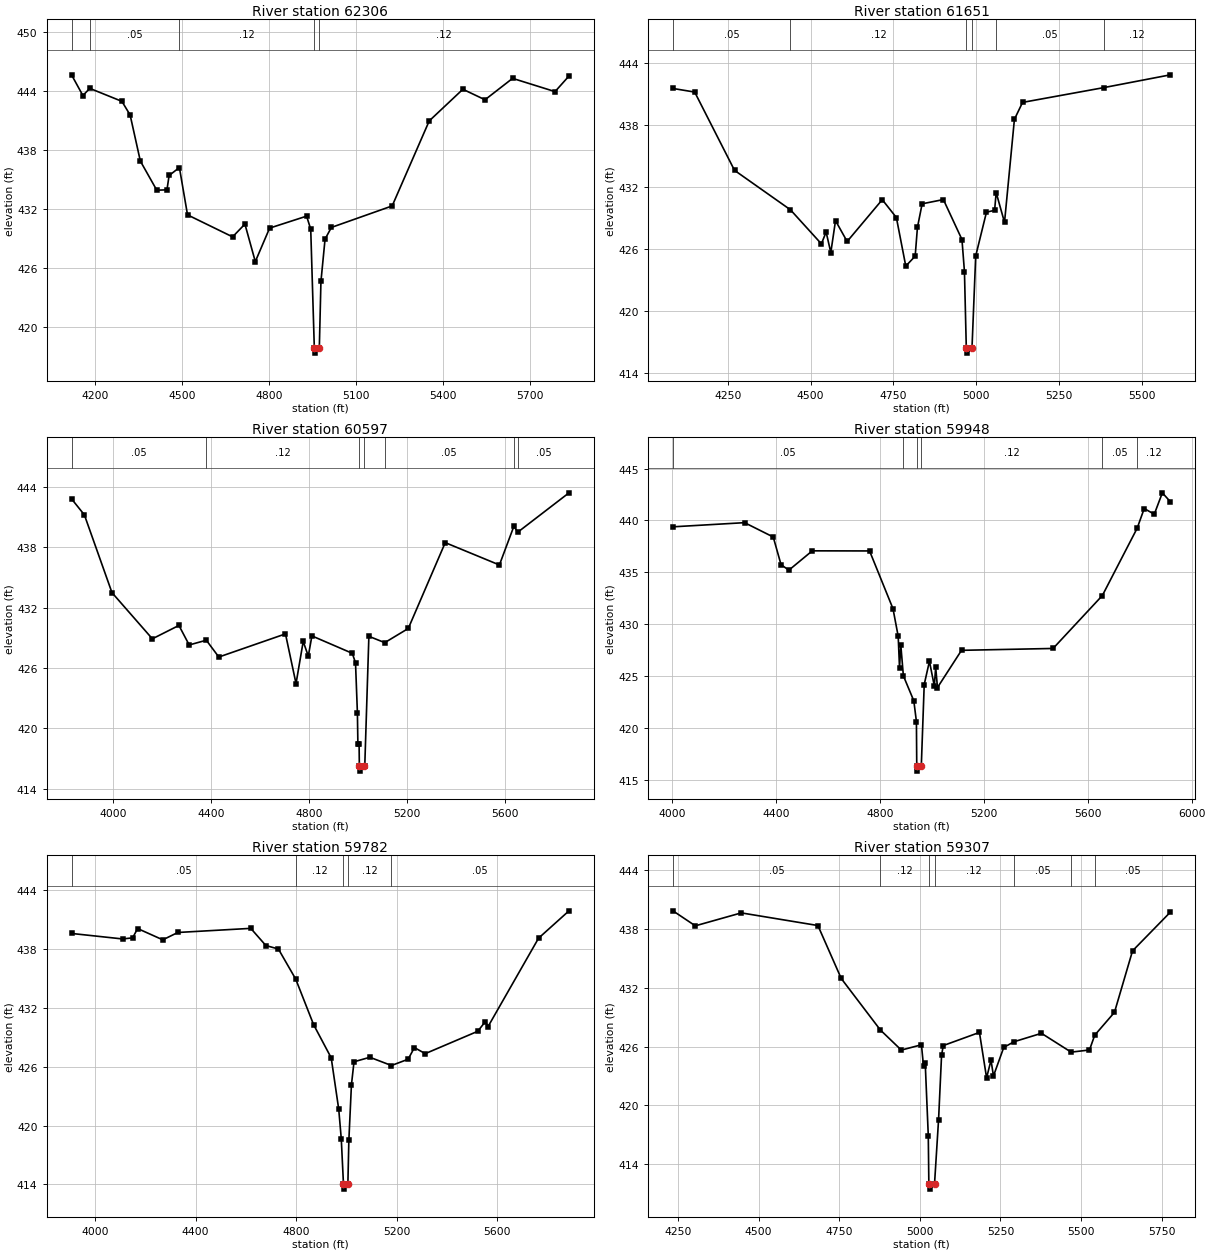
Type RM Length L Ch R = 1 ,62306   ,655,655,655
BEGIN DESCRIPTION:
Williams Creek 82.0
END DESCRIPTION:
XS GIS Cut Line= 3
      2694622.23      6908849.79      2694025.44      6908200.36
      2693244.59      6907909.68
#Sta/Elev= 30
    4118  445.64  4157.1  443.53  4180.9  444.26  4291.6  442.94    4320  441.55
  4355.2  436.86  4411.9  433.89    4447  433.93  4454.4  435.39  4489.9   436.2
  4517.9  431.38  4673.3  429.14  4715.8  430.44  4751.6  426.62  4800.9  430.03
  4928.5  431.25  4942.7  429.92  4955.1   417.8  4957.1   417.3  4972.3   417.8
  4977.9   424.6  4992.1  428.91  5013.9   430.1  5223.5  432.29  5351.3  440.95
  5467.3  444.17  5543.6   443.1  5638.7  445.28    5785  443.93  5833.2  445.52
#Mann= 5 ,-1 , 0
    4118     .12       0  4180.9     .05       0  4489.9     .12       0
  4955.1     .07       0  4972.3     .12       0
Bank Sta=4955.1,4972.3
XS Rating Curve= 0 ,0
Exp/Cntr=0.3,0.1

Type RM Length L Ch R = 1 ,61651   ,1054,1054,1054
BEGIN DESCRIPTION:
Williams Creek 81.0
END DESCRIPTION:
XS GIS Cut Line= 3
      2694851.89      6908428.21      2694239.56      6907747.62
      2693692.27      6907535.67
#Sta/Elev= 30
  4084.5  441.58  4150.2  441.23  4270.5  433.65  4439.4  429.83  4532.9  426.53
  4547.1  427.68  4561.3  425.69  4575.5  428.78  4610.6  426.76  4716.7  430.81
  4759.3  429.08  4787.7  424.38  4816.1  425.34  4822.9  428.12  4837.1  430.41
  4901.3  430.82  4957.4  426.95  4964.9  423.85  4970.5  416.45  4972.5  415.95
  4987.7  416.45  4998.9  425.36  5031.4   429.6    5056  429.78  5060.7   431.5
  5085.9  428.61  5115.8  438.59  5140.4  440.23  5385.5  441.66  5586.9   442.9
#Mann= 6 ,-1 , 0
  4084.5     .05       0  4439.4     .12       0  4970.5     .07       0
  4987.7     .12       0  5060.7     .05       0  5385.5     .12       0
Bank Sta=4970.5,4987.7
XS Rating Curve= 0 ,0
Exp/Cntr=0.3,0.1

Type RM Length L Ch R = 1 ,60597   ,649,649,649
BEGIN DESCRIPTION:
Williams Creek 80.0
END DESCRIPTION:
XS GIS Cut Line= 3
      2695265.49      6908203.65      2694570.66      6907263.19
      2693713.42      6907354.66
#Sta/Elev= 30
  3830.7   442.8  3883.1  441.21  3995.8  433.48  4160.7  428.89  4269.2  430.22
  4311.1  428.28  4381.1  428.75  4432.1  427.08  4704.3  429.38  4747.4  424.44
  4776.7  428.63  4797.5  427.17  4812.2  429.18  4977.1  427.45  4990.3  426.51
    4998  421.55    5000  418.45  5004.9  418.45    5006  416.24    5008  415.74
  5023.5  416.24  5028.1  416.25  5044.9  429.14  5109.7  428.51  5205.8  429.92
  5356.7  438.45  5577.9  436.23  5636.9  440.07    5653  439.49  5862.1   443.4
#Mann= 7 ,-1 , 0
  3830.7     .05       0  4381.1     .12       0    5006     .07       0
  5023.5     .12       0  5109.7     .05       0  5636.9     .12       0
    5653     .05       0
Bank Sta=5006,5023.5
XS Rating Curve= 0 ,0
Exp/Cntr=0.3,0.1

Type RM Length L Ch R = 1 ,59948   ,166,166,166
BEGIN DESCRIPTION:
Williams Creek 79.0
END DESCRIPTION:
XS GIS Cut Line= 5
      2695721.21      6906889.71       2695010.8      6906848.04
      2694727.18      6906862.15      2694085.02      6907053.77
      2693850.99        6907136.
#Sta/Elev= 30
  4004.4  439.39  4280.1  439.79  4390.3  438.41  4420.3  435.75  4450.4  435.22
  4540.5  437.08  4760.9  437.07    4851  431.51    4871  428.86  4876.1  425.82
  4881.1     428  4890.9  425.06  4931.1  422.65  4941.1  420.66  4942.4  416.39
  4944.4  415.89  4959.9  416.39  4971.1  424.22  4991.2  426.46    5010  424.07
  5015.2  425.89  5022.1  423.93  5114.6  427.51  5466.9  427.69  5656.4  432.78
  5790.4  439.26  5817.5  441.15  5856.2   440.6  5887.2  442.66  5918.2   441.8
#Mann= 6 ,-1 , 0
  4004.4     .05       0  4890.9     .12       0  4942.4     .07       0
  4959.9     .12       0  5656.4     .05       0  5790.4     .12       0
Bank Sta=4942.4,4959.9
XS Rating Curve= 0 ,0
Exp/Cntr=0.3,0.1

Type RM Length L Ch R = 1 ,59782   ,475,475,475
BEGIN DESCRIPTION:
Williams Creek 78.0
END DESCRIPTION:
XS GIS Cut Line= 3
      2695719.01      6906771.96       2694625.9      6906736.03
      2693761.55      6906932.56
#Sta/Elev= 30
  3906.3  439.61  4109.4  439.05  4149.4  439.16  4169.4  440.11  4269.5  438.96
  4329.5  439.71  4619.7  440.13  4679.7  438.38  4729.7  438.02  4798.6  434.95
  4869.8   430.3  4939.9  426.91  4969.9  421.65  4979.9  418.66  4988.7  414.01
  4990.7  413.51  5006.2  414.01  5010.1  418.48  5020.4  424.17  5030.7  426.51
  5093.7  426.97  5179.7  426.13    5246  426.77  5271.1  427.96  5314.1  427.34
  5522.9  429.62  5553.7  430.62  5563.9  430.09  5765.3  439.13  5886.4  441.92
#Mann= 5 ,-1 , 0
  3906.3     .05       0  4798.6     .12       0  4988.7     .07       0
  5006.2     .12       0  5179.7     .05       0
Bank Sta=4988.7,5006.2
XS Rating Curve= 0 ,0
Exp/Cntr=0.3,0.1

Type RM Length L Ch R = 1 ,59307   ,484,484,484
BEGIN DESCRIPTION:
Mapping XS 8bc3149e
END DESCRIPTION:
XS GIS Cut Line= 3
      2695421.09      6906542.69       2694698.9       6906355.2
      2693949.97      6906625.65
#Sta/Elev= 30
  4234.5  439.84  4303.9  438.31  4446.4  439.63    4684  438.34  4756.3  432.94
  4877.6  427.69  4942.6  425.64    5005  426.18  5011.4  424.01  5016.7  424.33
  5026.2  416.92    5028  411.96    5030  411.46  5045.5  411.96  5058.1  418.54
  5067.4  425.12  5072.7   426.1  5184.8  427.44    5207  422.81  5220.7  424.61
  5228.3     423  5260.2  425.91    5292  426.49  5377.1  427.35  5469.2  425.43
    5526  425.65  5542.3  427.16  5603.5  429.49  5659.5  435.76  5776.9  439.71
#Mann= 7 ,-1 , 0
  4234.5     .05       0  4877.6     .12       0    5028     .07       0
  5045.5     .12       0    5292     .05       0  5469.2     .12       0
  5542.3     .05       0
Bank Sta=5028,5045.5
XS Rating Curve= 0 ,0
Exp/Cntr=0.3,0.1

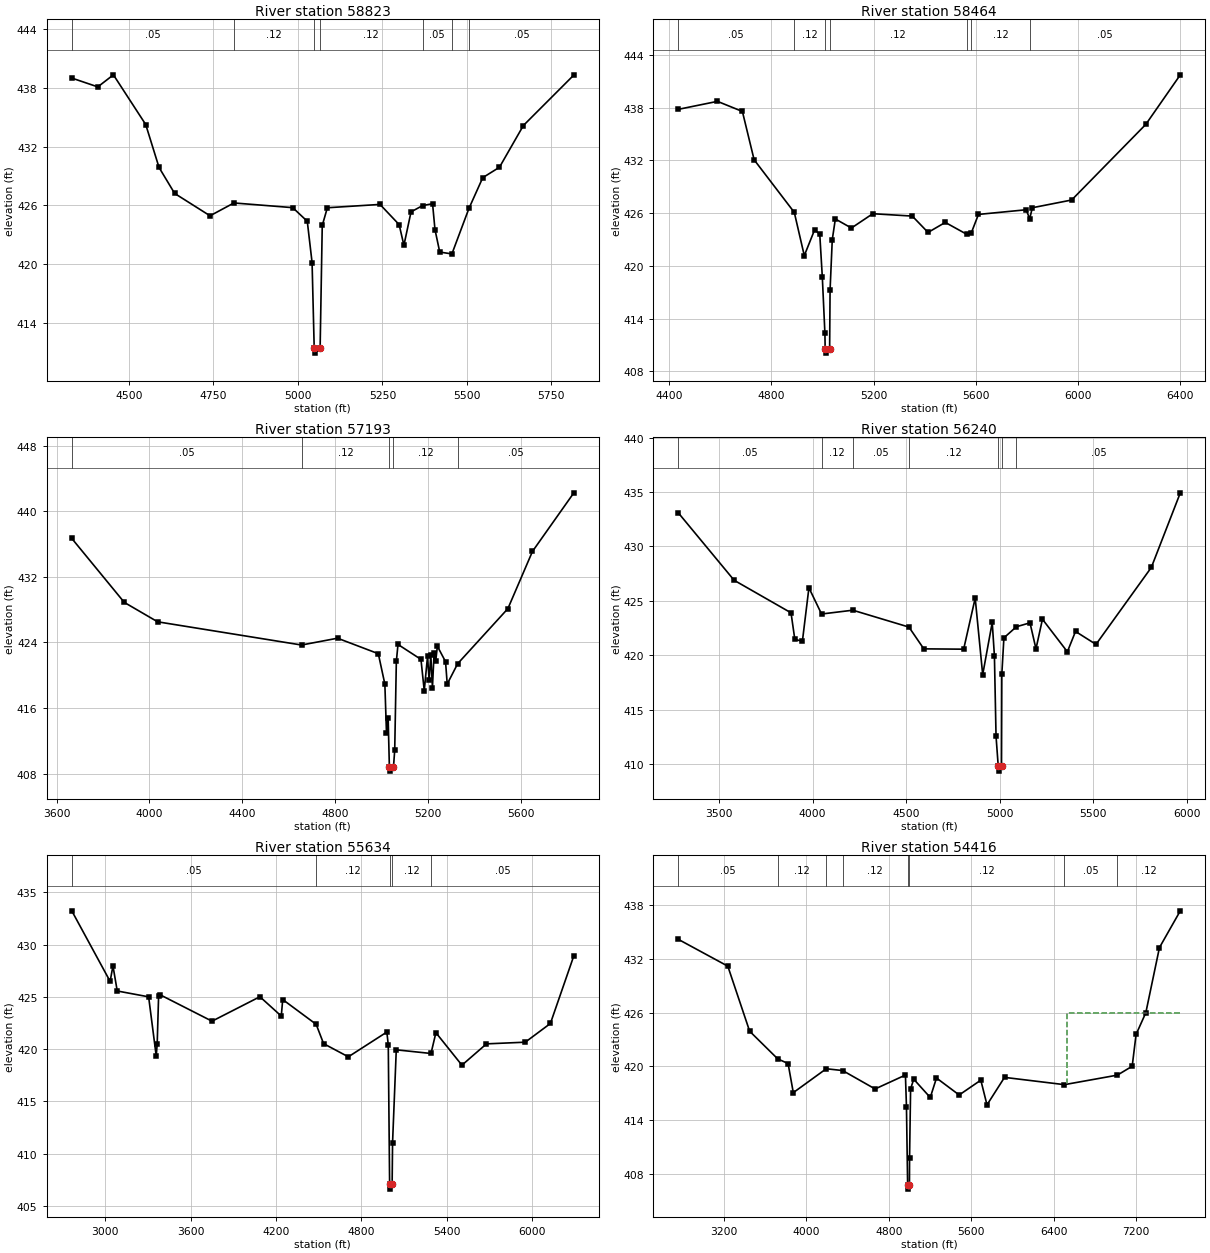
Type RM Length L Ch R = 1 ,58823   ,359,359,359
BEGIN DESCRIPTION:
Mapping XS 4235d23e
END DESCRIPTION:
XS GIS Cut Line= 4
      2695182.58      6906009.71      2694651.33      6905950.68
      2694415.22      6906106.93      2693936.08      6906572.18
#Sta/Elev= 30
    4331  438.99    4408  438.09  4454.2  439.32  4549.8  434.25  4589.2  429.87
  4635.4  427.22  4740.1  424.94  4810.8  426.25  4984.8  425.77  5027.8  424.38
    5042  420.17  5048.3  411.43  5050.3  410.93  5065.8  411.43  5072.1  423.95
  5087.2  425.76    5243   426.1  5299.6  424.04  5313.7  421.93  5334.8  425.34
  5368.9  425.98  5398.5  426.17  5405.6  423.54  5419.7  421.24  5455.7  421.05
  5506.1  425.69    5547  428.83  5596.4  429.89  5667.2  434.15  5816.5   439.3
#Mann= 7 ,-1 , 0
    4331     .05       0  4810.8     .12       0  5048.3     .07       0
  5065.8     .12       0  5368.9     .05       0  5455.7     .12       0
  5506.1     .05       0
Bank Sta=5048.3,5065.8
XS Rating Curve= 0 ,0
Exp/Cntr=0.3,0.1

Type RM Length L Ch R = 1 ,58464   ,1271,1271,1271
BEGIN DESCRIPTION:
Mapping XS a9ee7c46
END DESCRIPTION:
XS GIS Cut Line= 3
      2695234.68      6905645.13      2694633.97      6905728.46
      2693370.51      6906228.29
#Sta/Elev= 30
  4435.6  437.82  4589.1  438.73  4686.7  437.58  4732.6  432.08  4889.9  426.09
    4929  421.17  4969.3   424.1  4989.5  423.63  4999.6  418.71  5009.7  412.32
  5010.7  410.57  5012.7  410.07  5028.2  410.57  5029.9  417.25  5038.5  422.99
  5050.6  425.34  5113.4  424.31  5197.1  425.94  5351.7  425.67  5413.4  423.81
  5480.8  424.95  5564.8   423.6  5582.7  423.76  5610.7  425.86  5797.3  426.39
  5811.3  425.37  5821.6  426.62  5975.5   427.5  6265.8  436.11  6400.8  441.75
#Mann= 7 ,-1 , 0
  4435.6     .05       0  4889.9     .12       0  5010.7     .07       0
  5028.2     .12       0  5564.8     .05       0  5582.7     .12       0
  5811.3     .05       0
Bank Sta=5010.7,5028.2
XS Rating Curve= 0 ,0
Exp/Cntr=0.3,0.1

Type RM Length L Ch R = 1 ,57193   ,953,953,953
BEGIN DESCRIPTION:
Mapping XS ee0c6bc3
END DESCRIPTION:
XS GIS Cut Line= 4
      2695196.12      6905312.83      2694189.18      6905073.25
      2694001.68      6905146.17      2693352.34       6905809.4
#Sta/Elev= 30
  3665.4  436.69  3891.7  428.89  4035.5  426.52  4655.8  423.69  4811.2  424.52
  4986.9  422.63  5015.1  418.92  5022.1  412.97  5029.3  414.76  5034.6  408.81
  5036.6  408.31  5052.3  408.81  5057.6  410.88  5064.6  421.69  5071.7  423.76
  5170.7  421.94  5184.9  418.12    5199  422.29    5206  419.37  5213.2  422.47
  5220.2  418.48  5227.3   422.7  5234.3  421.73  5241.5  423.54  5276.7  421.66
  5283.9  418.93  5328.9  421.41  5545.5  428.13  5651.5  435.11  5829.8  442.25
#Mann= 5 ,-1 , 0
  3665.4     .05       0  4655.8     .12       0  5034.6     .07       0
  5052.3     .12       0  5328.9     .05       0
Bank Sta=5034.6,5052.3
XS Rating Curve= 0 ,0
Exp/Cntr=0.3,0.1

Type RM Length L Ch R = 1 ,56240   ,606,606,606
BEGIN DESCRIPTION:
Mapping XS 77786294
END DESCRIPTION:
XS GIS Cut Line= 4
      2695250.54      6904963.07      2693740.11      6904706.12
      2693545.66      6904744.32      2692712.35      6905209.59
#Sta/Elev= 30
  3281.2  433.09    3580  426.89  3884.3   423.9  3904.6  421.46  3945.1  421.29
    3980   426.2  4047.5  423.79  4214.8  424.14  4514.8  422.59  4594.3  420.59
  4807.4  420.56  4869.1  425.25  4909.2  418.22  4960.2  423.02  4971.9  419.93
  4980.6  412.55  4992.1  409.86  4994.1  409.36  5009.8  409.86  5011.5  418.27
  5022.6   421.6  5089.3  422.62  5162.1  422.98  5194.1  420.59  5228.7  423.31
    5362  420.32  5405.5  422.19    5515     421    5811  428.07  5965.9  434.92
#Mann= 7 ,-1 , 0
  3281.2     .05       0  4047.5     .12       0  4214.8     .05       0
  4514.8     .12       0  4992.1     .07       0  5009.8     .12       0
  5089.3     .05       0
Bank Sta=4992.1,5009.8
XS Rating Curve= 0 ,0
Exp/Cntr=0.3,0.1

Type RM Length L Ch R = 1 ,55634   ,1218,1218,1218
BEGIN DESCRIPTION:
Mapping XS 2935fa52
END DESCRIPTION:
XS GIS Cut Line= 3
      2695754.81      6904391.16       2693514.3      6904219.78
      2692251.26      6904445.48
#Sta/Elev= 30
  2763.7  433.23  3033.3  426.48  3053.3  427.96  3083.4  425.56  3304.1     425
  3357.5  419.34  3364.3   420.5  3374.3  425.11  3384.3   425.2  3749.8  422.67
  4086.4  425.01  4236.8  423.16  4246.8  424.74    4482  422.37  4534.3  420.52
  4708.2  419.26    4979  421.63    4989  420.41  4998.5   407.1  5000.5   406.6
  5016.2   407.1  5019.2  411.05  5045.3  419.93  5289.4  419.58  5323.9  421.57
  5506.8  418.46  5679.5   420.5  5952.2  420.66  6128.9  422.45  6293.8  428.93
#Mann= 5 ,-1 , 0
  2763.7     .05       0    4482     .12       0  4998.5     .07       0
  5016.2     .12       0  5289.4     .05       0
Bank Sta=4998.5,5016.2
XS Rating Curve= 0 ,0
Exp/Cntr=0.3,0.1

Type RM Length L Ch R = 1 ,54416   ,2408,2408,2408
BEGIN DESCRIPTION:
Mapping XS 290880cb
END DESCRIPTION:
XS GIS Cut Line= 6
      2696042.91      6903599.76      2694639.58      6903415.84
      2693997.59      6903276.76      2693544.68      6903234.54
      2692034.77      6903234.12      2691296.07      6903622.35
#Sta/Elev= 30
    2756  434.15    3237  431.16  3448.8  423.92  3721.2  420.84  3821.9  420.32
  3872.4  417.08  4192.3  419.74  4351.3  419.54  4666.1  417.49  4960.4  419.04
  4970.4  415.51  4981.7  406.84  4983.7  406.34  4999.4  406.84  5000.5  409.85
  5010.6  417.49  5040.7  418.58  5201.4  416.54  5261.7  418.71  5481.8  416.82
  5691.8  418.47  5751.8  415.72  5921.8  418.78  6502.8  417.97  7016.7  419.03
  7160.6  420.02  7198.3  423.56  7292.9  425.98  7425.1  433.23  7627.5  437.32
#Mann= 8 ,-1 , 0
    2756     .05       0  3721.2     .12       0  4192.3     .05       0
  4351.3     .12       0  4981.7     .07       0  4999.4     .12       0
  6502.8     .05       0  7016.7     .12       0
#XS Ineff= 2 , 0
       0                  6531.8       0     426
Permanent Ineff=
       F       F
Bank Sta=4981.7,4999.4
XS Rating Curve= 0 ,0
Exp/Cntr=0.3,0.1

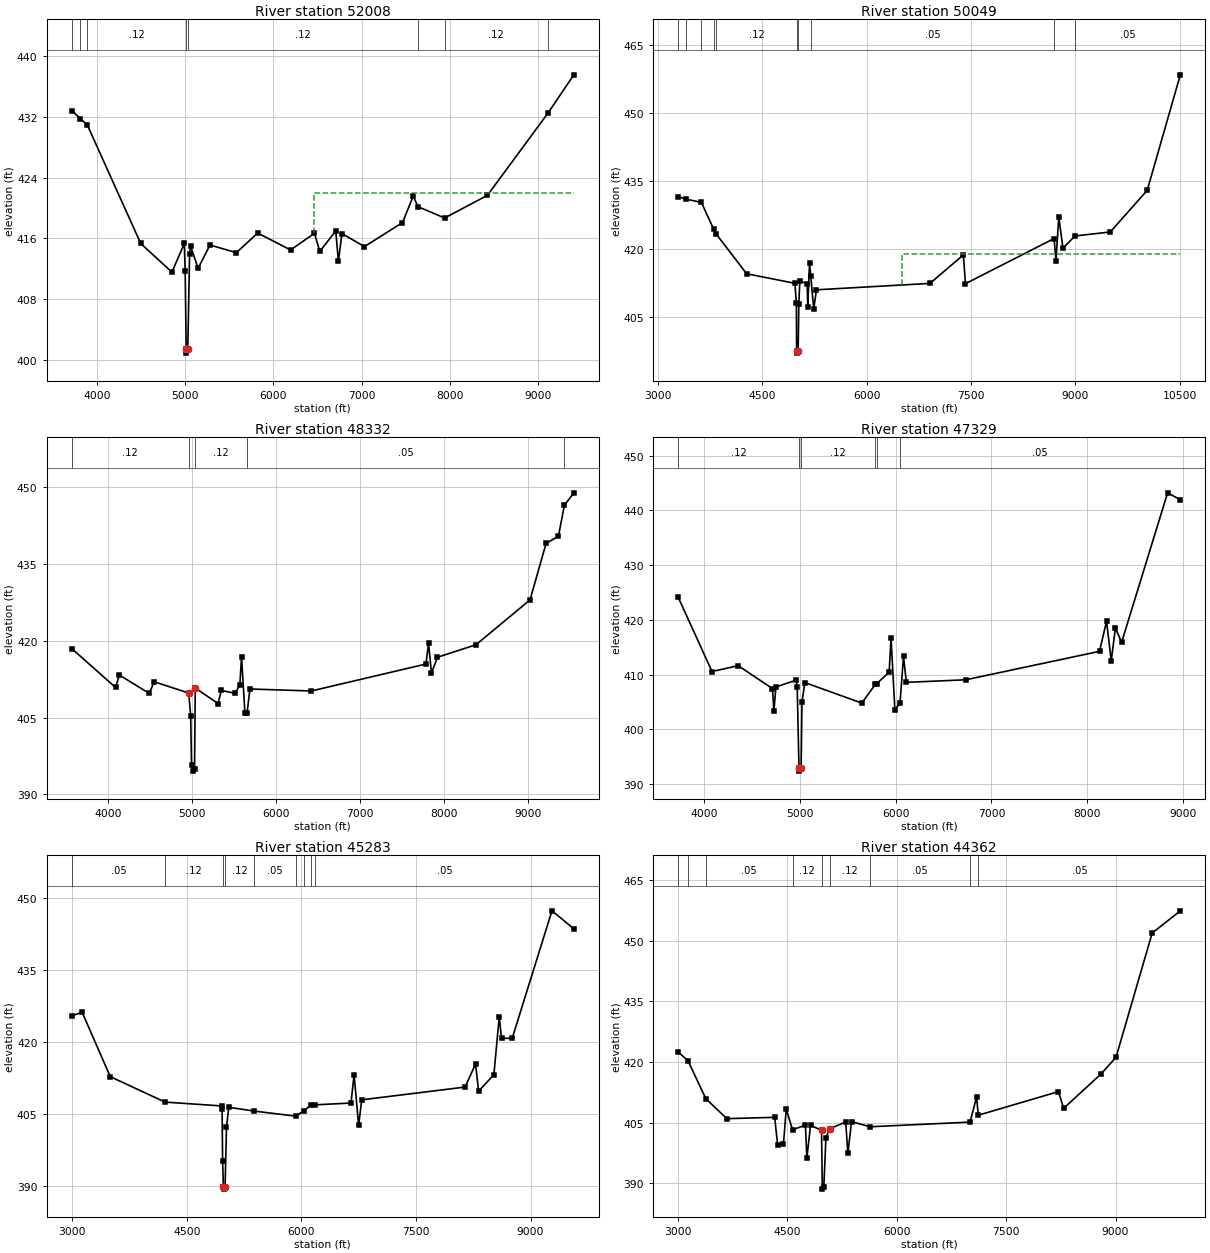
Type RM Length L Ch R = 1 ,52008   ,1959,1959,1959
BEGIN DESCRIPTION:
Mapping XS 9fe954b0
END DESCRIPTION:
XS GIS Cut Line= 5
      2696076.79      6902813.03      2695199.42      6902446.95
      2694447.71      6902492.42      2692414.71       6902661.6
      2690710.93      6903595.44
#Sta/Elev= 30
  3716.6  432.85  3813.6  431.81  3893.1  430.95  4497.6  415.34    4851  411.56
  4991.3  415.35  5001.3  411.65  5012.4  401.39  5014.4  400.89  5030.2  401.39
  5051.4  413.96  5061.4  415.02  5147.5  412.07  5281.8  415.14  5580.9  414.13
  5821.9  416.72  6194.7  414.49  6465.7  416.68  6525.9  414.29  6706.5     417
  6736.6  413.01  6776.7  416.64  7031.9  414.93  7462.5   418.1  7584.4  421.59
  7636.5   420.2  7939.6   418.7  8424.6  421.69    9108  432.49  9403.3  437.57
#Mann= 8 ,-1 , 0
  3716.6     .12       0  3813.6     .05       0  3893.1     .12       0
  5012.4     .07       0  5030.2     .12       0  7636.5     .05       0
  7939.6     .12       0    9108     .05       0
#XS Ineff= 2 , 0
       0                  6465.7       0     422
Permanent Ineff=
       F       F
Bank Sta=5012.4,5030.2
XS Rating Curve= 0 ,0
Exp/Cntr=0.3,0.1

Type RM Length L Ch R = 1 ,50049   ,1717,1717,1717
BEGIN DESCRIPTION:
Mapping XS b25e7f6f
END DESCRIPTION:
XS GIS Cut Line= 5
      2696257.17       6902758.2      2695226.77      6901633.65
      2694968.12      6901399.25      2692757.67      6901370.47
      2689630.75      6901266.01
#Sta/Elev= 30
  3293.1   431.6  3407.3  431.06  3626.1  430.34  3799.8  424.51  3842.3  423.29
  4275.9  414.62  4969.2  412.51  4990.8  408.07    4994  397.62  4996.2  397.12
  5015.9  397.62  5025.9  408.05  5040.1  412.98  5146.2  412.46  5153.7  407.33
  5179.5  416.91  5197.3  414.08  5239.5   406.9  5279.5  411.08  6909.7  412.49
  7389.7  418.77  7419.7  412.43    8693  422.38  8720.5  417.48  8760.5  427.21
  8820.5  420.22    8992  422.94  9500.9  423.83 10031.2  433.01 10506.7  458.47
#Mann= 10 ,-1 , 0
  3293.1     .12       0  3407.3     .05       0  3626.1     .12       0
  3799.8     .05       0  3842.3     .12       0    4994     .07       0
  5015.9     .12       0  5197.3     .05       0    8693     .12       0
    8992     .05       0
#XS Ineff= 2 , 0
       0                  6506.9       0     419
Permanent Ineff=
       F       F
Bank Sta=4994,5015.9
XS Rating Curve= 0 ,0
Exp/Cntr=0.3,0.1

Type RM Length L Ch R = 1 ,48332   ,1003,1003,1003
BEGIN DESCRIPTION:
Mapping XS dd3157c5
END DESCRIPTION:
XS GIS Cut Line= 4
      2696862.87      6901309.82      2695560.82      6900732.58
      2692822.39      6900728.36      2691151.01      6900036.01
#Sta/Elev= 30
  3568.5  418.46  4090.1  410.87  4133.9  413.31  4490.1  409.72  4549.6  411.98
  4959.7  409.79    4983  405.26  4992.7  395.67  5008.8  394.55  5028.6  395.05
  5037.6  410.78  5307.6  407.74  5347.6   410.3  5507.6  409.75  5567.6   411.3
  5587.6   416.9  5627.6  405.99  5653.5  405.86  5687.6  410.58  6417.6  410.19
  7781.4  415.45  7812.1   419.5  7846.8   413.7  7918.5  416.77  8376.7  419.22
  9019.2  427.97  9210.2     439  9356.9  440.38  9427.8  446.43  9540.3  448.86
#Mann= 5 ,-1 , 0
  3568.5     .12       0  4959.7     .07       0  5037.6     .12       0
  5653.5     .05       0  9427.8     .12       0
#XS Ineff= 2 , 0
       0                  5587.6       0   416.9
Permanent Ineff=
       F       F
Bank Sta=4959.7,5037.6
XS Rating Curve= 0 ,0
Exp/Cntr=0.3,0.1

Type RM Length L Ch R = 1 ,47329   ,2046,2046,2046
BEGIN DESCRIPTION:
Mapping XS 62c8a9e0
END DESCRIPTION:
XS GIS Cut Line= 4
      2696980.92      6900907.04      2695986.17      6900214.36
       2692831.5      6900311.34      2692119.69      6899801.14
#Sta/Elev= 30
  3728.1  424.12  4080.6  410.58  4354.7  411.64  4712.5  407.46  4727.3  403.34
  4748.2  407.76  4960.4  409.01  4970.5  407.82  4989.5   392.9  4991.7   392.4
  5011.5   392.9  5020.5  404.97  5050.5  408.56  5645.2  404.82  5786.3  408.22
  5801.5  408.37  5930.9  410.45  5950.9  416.64  5990.9  403.62  6044.4  404.81
    6081  413.35    6111   408.6  6731.3  409.07  8128.4  414.26  8201.6  419.76
  8250.8  412.56  8294.2  418.51  8359.2  415.91  8839.5  443.19  8972.2  441.93
#Mann= 6 ,-1 , 0
  3728.1     .12       0  4989.5     .07       0  5011.5     .12       0
  5786.3     .05       0  5801.5     .12       0  6044.4     .05       0
#XS Ineff= 2 , 0
       0                  5950.9       0  416.64
Permanent Ineff=
       F       F
Bank Sta=4989.5,5011.5
XS Rating Curve= 0 ,0
Exp/Cntr=0.3,0.1

Type RM Length L Ch R = 1 ,45283   ,921,921,921
BEGIN DESCRIPTION:
Mapping XS 29cdb6e0
END DESCRIPTION:
XS GIS Cut Line= 3
      2698086.32      6900823.04      2696674.15      6899397.19
       2692109.4      6899453.61
#Sta/Elev= 30
    2995  425.52    3131  426.24  3498.7  412.85  4215.9  407.55  4955.3  406.75
  4962.5  406.15  4969.5  395.34  4979.7  389.93  4981.9  389.43  5001.8  389.93
    5020  402.33    5050  406.47  5377.4  405.69  5933.3  404.61  6028.5  405.75
  6131.2  406.92    6178  406.98  6650.1  407.35  6690.1  413.21  6750.1  402.73
  6790.1  408.02  8143.7  410.68  8280.2  415.49  8320.2  409.82  8520.2  413.25
  8590.2  425.27  8620.2  420.82  8760.2  420.84  9280.3  447.37  9566.9  443.64
#Mann= 9 ,-1 , 0
    2995     .05       0  4215.9     .12       0  4979.7     .07       0
  5001.8     .12       0  5377.4     .05       0  5933.3     .12       0
  6028.5     .05       0  6131.2     .12       0    6178     .05       0
#XS Ineff= 2 , 0
       0                  6690.1       0  413.21
Permanent Ineff=
       F       F
Bank Sta=4979.7,5001.8
XS Rating Curve= 0 ,0
Exp/Cntr=0.3,0.1

Type RM Length L Ch R = 1 ,44362   ,649,649,649
BEGIN DESCRIPTION:
Mapping XS 287533c3
END DESCRIPTION:
XS GIS Cut Line= 4
       2699062.6      6898803.33      2697067.77      6898631.46
      2695937.56      6898537.71      2692234.91      6899099.29
#Sta/Elev= 30
  3006.2  422.49  3139.8   420.3  3384.8  410.91  3672.2  405.98  4327.7   406.3
  4367.8  399.58  4448.1  399.66  4486.4  408.33  4573.4   403.2  4749.2  404.41
  4769.3  396.23  4819.5  404.33    4970   403.1    4981  388.54  5001.5  389.04
  5030.3  401.24  5080.4  403.47  5301.2  405.15  5331.3  397.37  5381.5  405.25
  5635.3  403.97  7006.2  405.12  7094.8  411.33  7119.2  406.83  8217.5  412.67
  8288.3  408.53  8798.8     417  9006.5  421.18  9502.1  451.91  9887.5   457.4
#Mann= 9 ,-1 , 0
  3006.2     .05       0  3139.8    .075       0  3384.8     .05       0
  4573.4     .12       0    4970     .07       0  5080.4     .12       0
  5635.3     .05       0  7006.2     .12       0  7119.2     .05       0
Bank Sta=4970,5080.4
XS Rating Curve= 0 ,0
Exp/Cntr=0.3,0.1