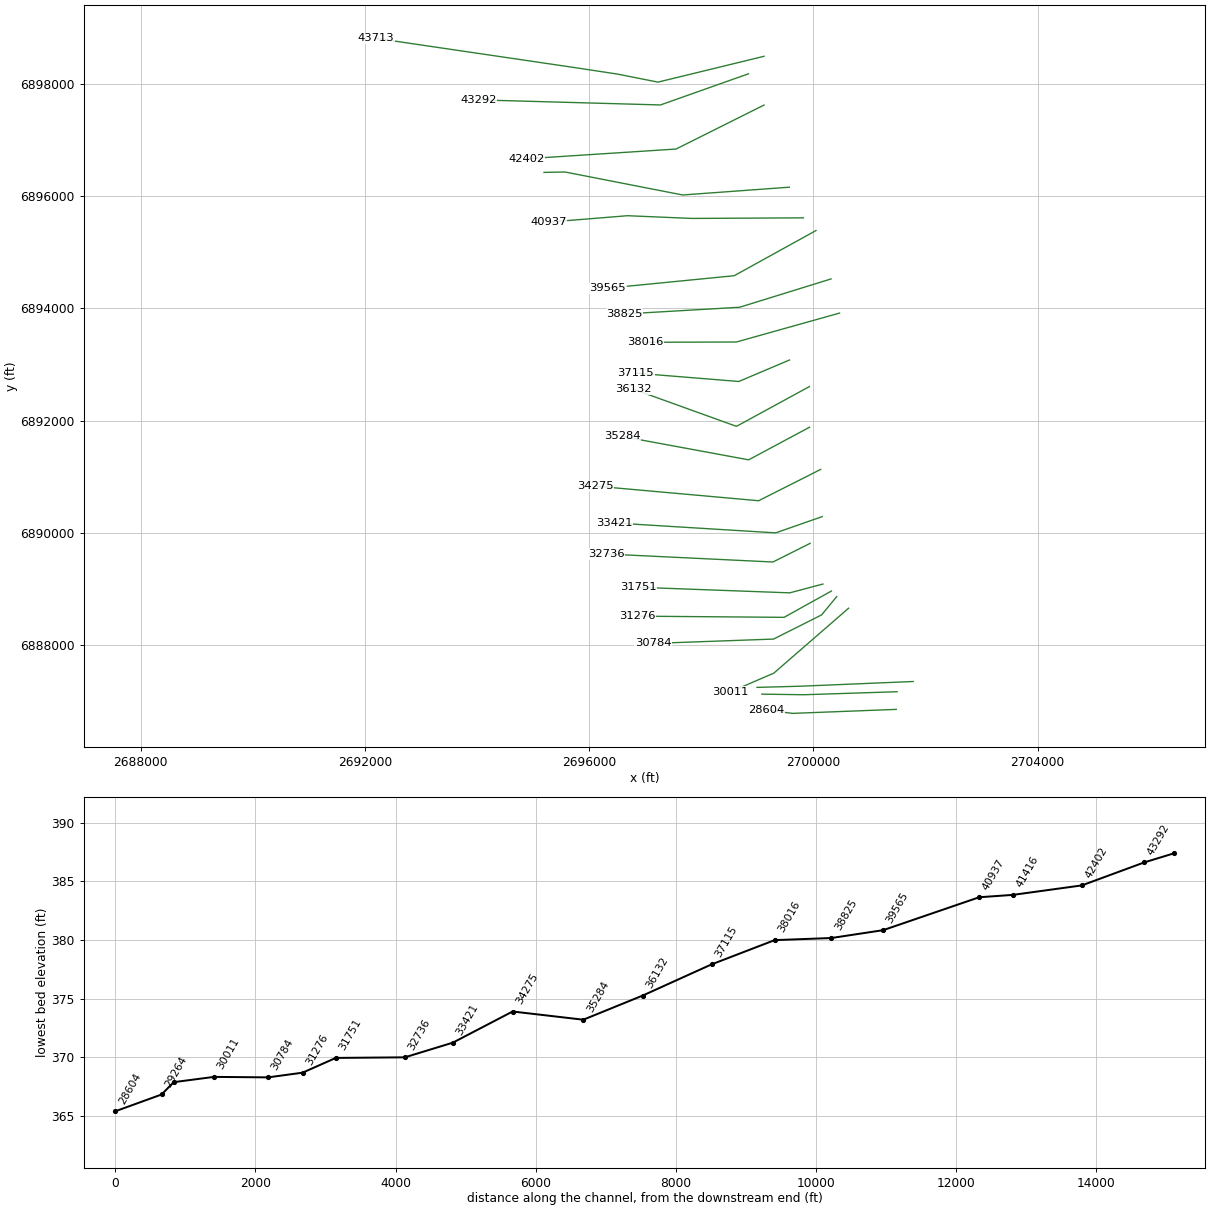
HEC-RAS study Williams Creek.prj: Williams Creek Base Level Engineering

--- Williams Creek.g01 (geometry) --- (continued)

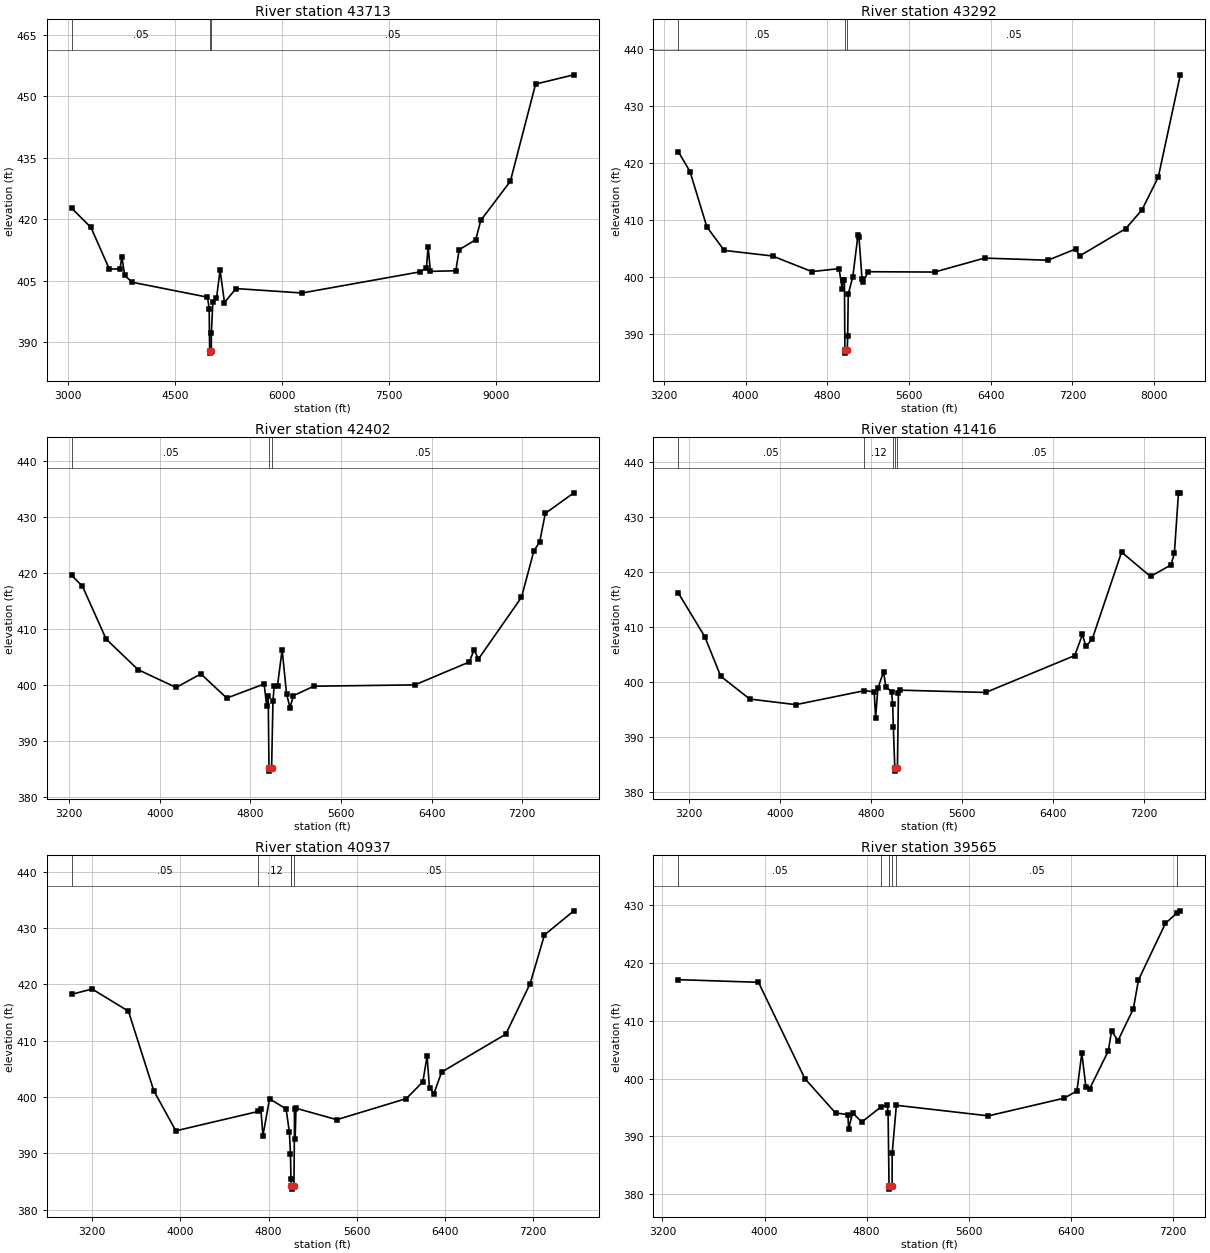
Type RM Length L Ch R = 1 ,43713   ,421,421,421
BEGIN DESCRIPTION:
Mapping XS cada5b70
END DESCRIPTION:
XS GIS Cut Line= 5
      2699117.66      6898496.47      2697226.09      6898036.04
      2696510.95      6898178.06      2695742.68      6898295.08
      2692195.41        6898817.
#Sta/Elev= 30
  3053.2   422.7  3322.5  418.02  3579.8  407.87  3730.4  407.92  3754.8   410.9
  3795.9  406.35  3897.3  404.68  4955.8  401.03  4979.5  398.26  4985.9  387.89
  4988.2  387.39    5009  387.89  5010.3  392.21  5030.7   399.8  5081.7  400.74
  5132.6  407.58  5193.8  399.73  5355.5  403.13  6280.3  402.05  7928.1  407.18
    8024  408.04  8049.4  413.37  8079.7  407.32  8437.3  407.47    8484  412.59
  8716.5  415.05  8787.2  419.75  9201.6  429.29  9555.4  452.98 10091.7  455.23
#Mann= 3 ,-1 , 0
  3053.2     .05       0  4985.9     .04       0    5009     .05       0
Bank Sta=4985.9,5009
XS Rating Curve= 0 ,0
Exp/Cntr=0.3,0.1

Type RM Length L Ch R = 1 ,43292   ,890,890,890
BEGIN DESCRIPTION:
Mapping XS 833513db
END DESCRIPTION:
XS GIS Cut Line= 3
      2698839.91      6898184.41      2697270.46      6897628.85
       2694020.7      6897719.12
#Sta/Elev= 30
    3341     422  3456.3  418.49    3621  408.79  3790.9  404.65    4264  403.67
  4649.7  400.93  4915.1  401.45    4947  397.89  4953.4  399.48  4968.2  399.45
  4972.7  387.12    4975  386.62  4995.8  387.12    5000  389.62  5005.6  396.97
  5050.4  400.05  5100.4  407.29  5110.4  407.03  5140.4  399.69  5150.4  399.08
  5200.4  400.91  5850.7  400.85  6339.8   403.3  6961.1  402.93  7231.2  404.89
  7271.2  403.68  7721.4  408.46  7881.5  411.76  8041.5  417.54  8256.9  435.47
#Mann= 3 ,-1 , 0
    3341     .05       0  4972.7     .04       0  4995.8     .05       0
Bank Sta=4972.7,4995.8
XS Rating Curve= 0 ,0
Exp/Cntr=0.3,0.1

Type RM Length L Ch R = 1 ,42402   ,986,986,986
BEGIN DESCRIPTION:
Mapping XS 33700115
END DESCRIPTION:
XS GIS Cut Line= 3
      2699117.65       6897627.1      2697548.24      6896842.39
      2694874.63      6896668.78
#Sta/Elev= 30
  3222.7  419.56  3317.1  417.63  3526.4   408.2    3809  402.75  4144.4  399.58
  4362.5     402  4591.7  397.69  4921.5   400.2  4943.8  396.34  4957.5  397.99
  4964.3  385.16  4966.6  384.66  4987.4  385.16  4999.6  397.17  5009.7  399.79
  5039.7  399.91  5080.4  406.33  5119.9  398.41    5150  395.98    5180  398.12
  5360.4  399.81  6252.3  400.04  6733.3  404.13    6776  406.31  6813.5  404.64
  7194.3  415.67  7304.5  423.99  7354.6  425.52  7404.7  430.64  7656.6   434.3
#Mann= 3 ,-1 , 0
  3222.7     .05       0  4964.3     .04       0  4987.4     .05       0
Bank Sta=4964.3,4987.4
XS Rating Curve= 0 ,0
Exp/Cntr=0.3,0.1

Type RM Length L Ch R = 1 ,41416   ,479,479,479
BEGIN DESCRIPTION:
Mapping XS 9aeebeb0
END DESCRIPTION:
XS GIS Cut Line= 4
      2699568.66      6896161.84      2697665.86      6896022.95
      2695568.64      6896432.67      2695193.64      6896425.73
#Sta/Elev= 30
  3102.9  416.28  3336.2  408.32  3476.6  401.12  3732.4  396.96  4138.3  395.94
  4739.2  398.47  4828.3  398.28  4840.2  393.49  4860.2  398.88  4910.4  401.95
  4930.4  399.16  4980.5  398.33  4990.6  395.98  4996.7   391.8  5009.2  384.35
  5011.5  383.85  5032.5  384.35  5041.2  398.07  5051.4  398.58  5809.7  398.16
  6593.2  404.87  6661.3  408.71  6691.2  406.53  6747.8   407.9  7005.6  423.68
  7260.3  419.26  7440.3  421.35  7470.3  423.45  7506.6  434.47  7522.7  434.45
#Mann= 5 ,-1 , 0
  3102.9     .05       0  4739.2     .12       0  4996.7     .05       0
  5009.2     .04       0  5032.5     .05       0
Bank Sta=5009.2,5032.5
XS Rating Curve= 0 ,0
Exp/Cntr=0.3,0.1

Type RM Length L Ch R = 1 ,40937   ,1372,1372,1372
BEGIN DESCRIPTION:
Mapping XS 9bb6dbd6
END DESCRIPTION:
XS GIS Cut Line= 4
      2699820.34      6895614.96      2697830.79      6895604.55
      2696683.22      6895653.16      2695270.54      6895538.62
#Sta/Elev= 30
  3013.6  418.24  3197.9  419.18  3527.9  415.24    3758   401.1    3958     394
  4707.1  397.45  4729.3  397.87    4748  393.14    4808  399.68    4958   397.9
    4988  393.79    4998   389.9  5002.4  385.36  5006.3  384.15  5008.6  383.65
  5029.6  384.15  5035.3  397.81  5040.3  392.55    5048  398.01  5418.3  395.98
  6048.9  399.72  6199.2   402.7  6237.3  407.25  6259.4  401.59  6299.5  400.62
  6369.7  404.44  6951.6  411.16  7172.3  420.13  7302.8  428.79  7569.1  433.06
#Mann= 5 ,-1 , 0
  3013.6     .05       0  4707.1     .12       0  5002.4     .05       0
  5006.3     .07       0  5029.6     .05       0
Bank Sta=5006.3,5029.6
XS Rating Curve= 0 ,0
Exp/Cntr=0.3,0.1

Type RM Length L Ch R = 1 ,39565   ,740,740,740
BEGIN DESCRIPTION:
Mapping XS 649c765d
END DESCRIPTION:
XS GIS Cut Line= 3
       2700044.3      6895388.38        2698586.      6894582.85
        2696330.      6894360.72
#Sta/Elev= 30
  3323.9  417.12  3952.6  416.66  4315.9  399.98  4555.8  394.03  4652.7  393.75
  4658.6  391.33  4690.5  394.05  4761.5  392.46  4910.5  395.05    4962   395.4
  4967.7  394.08  4975.2  381.34  4977.5  380.84  4998.9  381.34  4999.9  387.06
  5032.5  395.36  5753.6  393.53  6346.4  396.59  6446.9  397.83  6485.3  404.39
  6517.2  398.53  6547.4  398.26  6692.8  404.77  6718.2  408.25  6768.5  406.56
    6889  412.07  6929.2  417.08  7140.2  426.86  7231.5   428.7  7256.8  429.04
#Mann= 6 ,-1 , 0
  3323.9     .05       0  4910.5     .12       0  4975.2     .07       0
  4998.9     .12       0  5032.5     .05       0  7231.5     .12       0
Bank Sta=4975.2,4998.9
XS Rating Curve= 0 ,0
Exp/Cntr=0.3,0.1

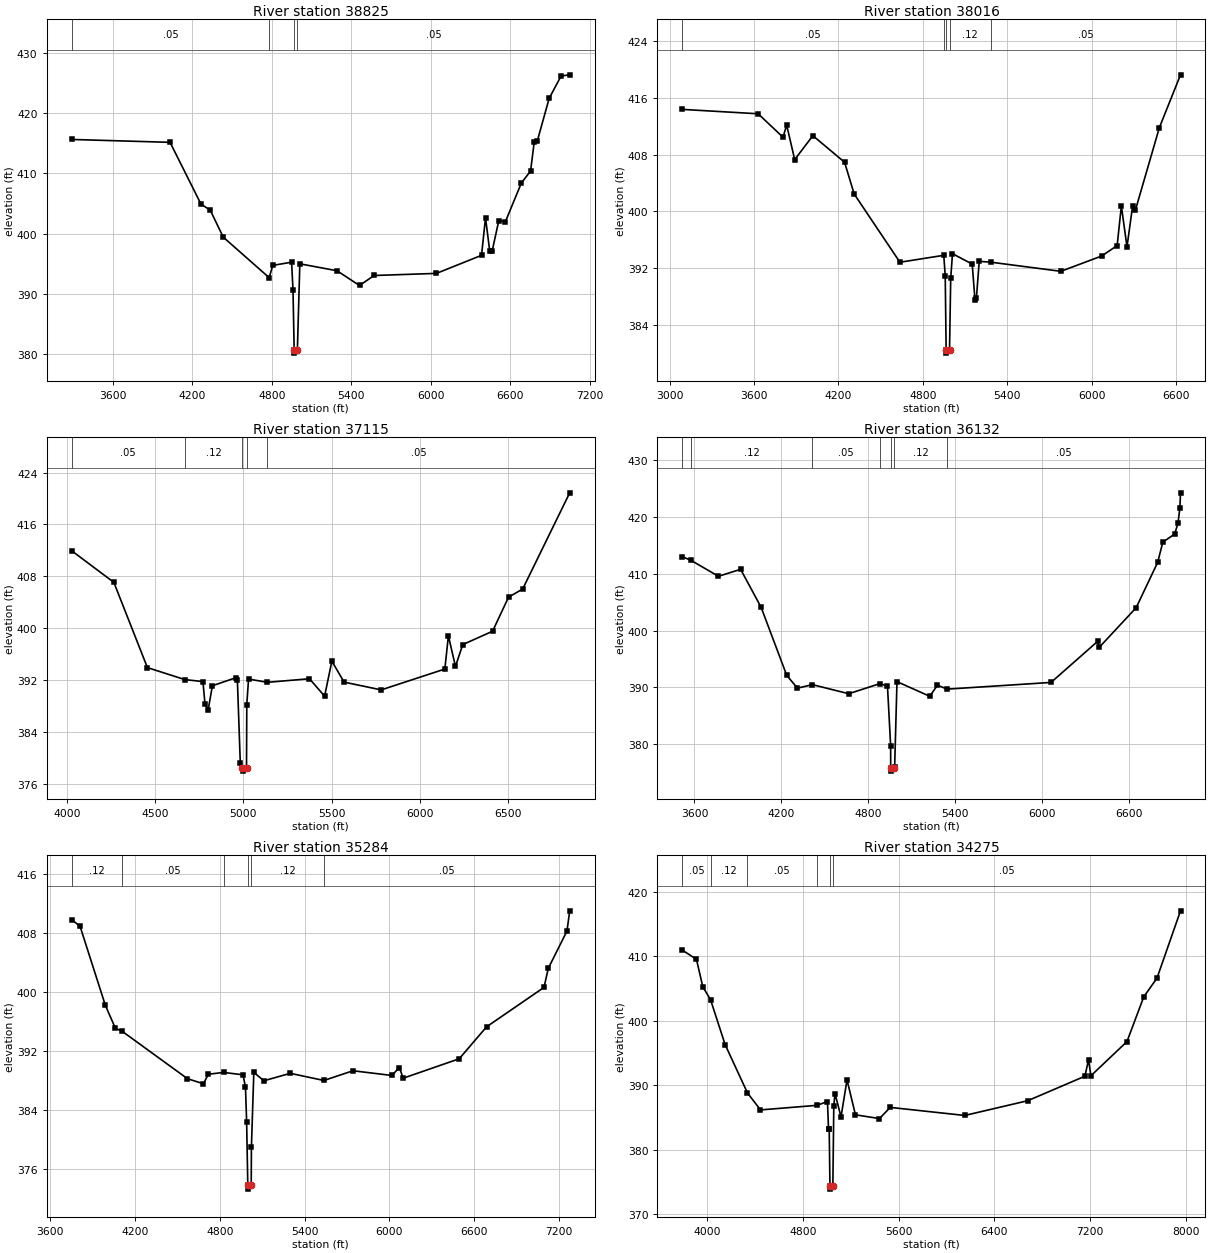
Type RM Length L Ch R = 1 ,38825   ,809,809,809
BEGIN DESCRIPTION:
Mapping XS ac62ac5a
END DESCRIPTION:
XS GIS Cut Line= 3
      2700313.46      6894525.56      2698683.22      6894020.35
      2696631.14      6893900.55
#Sta/Elev= 30
  3287.5  415.65  4031.3  415.17  4264.7  404.92  4335.1   403.9  4432.9  399.43
  4779.9   392.7  4807.2  394.74  4949.4  395.27  4959.9  390.66  4968.8  380.67
  4971.2  380.17  4992.9  380.67  5011.5     395    5292  393.85  5462.2   391.4
  5572.4  393.06  6043.2  393.41  6383.8  396.41  6413.9  402.65  6445.2  397.21
  6463.9   397.1    6514  402.15  6564.1  401.99  6684.3   408.4  6754.4  410.42
  6782.1  415.29  6804.5  415.35  6894.7  422.47  6984.8  426.19  7049.8  426.38
#Mann= 4 ,-1 , 0
  3287.5     .05       0  4779.9     .12       0  4968.8     .04       0
  4992.9     .05       0
Bank Sta=4968.8,4992.9
XS Rating Curve= 0 ,0
Exp/Cntr=0.3,0.1

Type RM Length L Ch R = 1 ,38016   ,901,901,901
BEGIN DESCRIPTION:
Mapping XS a448bb25
END DESCRIPTION:
XS GIS Cut Line= 3
      2700464.45      6893916.17      2698625.93      6893400.55
       2696995.7      6893395.35
#Sta/Elev= 30
  3091.1   414.4  3629.6  413.78  3806.1  410.47  3832.2  412.18  3889.2  407.31
  4018.3  410.69  4243.6  406.94  4311.8  402.46    4637  392.82  4948.5   393.8
  4958.9  390.89  4965.4  380.49  4967.8  379.99  4989.5  380.49  4997.9  390.56
  5010.5  394.03  5150.5  392.56  5170.5  387.46  5180.5  387.77  5200.5  392.95
  5282.8  392.83  5780.5  391.54  6070.5   393.7  6180.5  395.17  6210.5  400.77
  6250.5  394.99  6290.5  400.78  6310.5  400.19  6480.5  411.82  6630.8  419.28
#Mann= 5 ,-1 , 0
  3091.1     .05       0  4948.5     .12       0  4965.4     .07       0
  4989.5     .12       0  5282.8     .05       0
Bank Sta=4965.4,4989.5
XS Rating Curve= 0 ,0
Exp/Cntr=0.3,0.1

Type RM Length L Ch R = 1 ,37115   ,983,983,983
BEGIN DESCRIPTION:
Williams Creek 51.0
END DESCRIPTION:
XS GIS Cut Line= 3
      2699572.15      6893079.39       2698667.8      6892696.35
      2696830.05      6892845.35
#Sta/Elev= 30
  4025.1  411.95  4264.9  407.06  4455.3   393.9  4667.5  392.05  4770.3  391.74
    4782  388.27  4800.2  387.42  4823.9   391.1  4958.6  392.35  4965.7  391.98
  4982.3  379.15  4993.4  378.42  4995.8  377.92  5017.5  378.42  5019.1   388.2
  5029.1  392.13    5136  391.63  5374.7  392.18  5460.5  389.49  5501.7   394.9
  5570.9  391.66  5781.6  390.46  6142.7  393.68  6162.8  398.81  6202.9  394.08
  6244.2  397.45  6413.6  399.52  6503.9  404.77  6584.2  406.03    6851  420.88
#Mann= 5 ,-1 , 0
  4025.1     .05       0  4667.5     .12       0  4993.4     .07       0
  5017.5     .12       0    5136     .05       0
Bank Sta=4993.4,5017.5
XS Rating Curve= 0 ,0
Exp/Cntr=0.3,0.1

Type RM Length L Ch R = 1 ,36132   ,848,848,848
BEGIN DESCRIPTION:
Williams Creek 50.0
END DESCRIPTION:
XS GIS Cut Line= 3
      2699928.01      6892605.85      2698625.86      6891895.94
      2696789.15      6892558.34
#Sta/Elev= 30
  3516.9  413.02  3577.1  412.37  3765.7  409.57  3918.5   410.8    4060  404.11
  4236.7  392.12  4310.6  389.87  4413.6  390.49  4664.7  388.89  4880.1  390.68
  4931.5   390.2  4953.3  379.77  4953.6  375.76    4956  375.26  4977.8  375.76
  4980.9  375.96    4997  391.02  5223.1  388.44  5276.2  390.39  5342.9   389.7
  6059.5  390.88    6381  398.11  6392.4  397.07  6646.6  404.04  6794.7  412.01
  6830.7  415.59  6912.1  417.01  6934.6  418.87  6948.1  421.54  6952.5  424.27
#Mann= 7 ,-1 , 0
  3516.9     .05       0  3577.1     .12       0  4413.6     .05       0
  4880.1     .12       0  4953.6     .07       0  4977.8     .12       0
  5342.9     .05       0
Bank Sta=4953.6,4977.8
XS Rating Curve= 0 ,0
Exp/Cntr=0.3,0.1

Type RM Length L Ch R = 1 ,35284   ,1009,1009,1009
BEGIN DESCRIPTION:
Mapping XS f4827a94
END DESCRIPTION:
XS GIS Cut Line= 3
      2699929.06       6891880.3      2698843.98       6891298.7
      2696587.04      6891715.37
#Sta/Elev= 30
  3749.9  409.85  3810.1  408.92  3988.9  398.19  4060.4  395.05  4105.6  394.69
  4570.3  388.21  4683.7  387.52  4717.8  388.82  4826.6  389.06  4963.6  388.74
    4981  387.05  4989.1  382.35  4997.4   373.7  4999.8   373.2  5021.6   373.7
    5023  378.94    5040  389.07  5111.2  387.93    5298  388.94  5535.9  387.97
    5742  389.29    6017  388.65    6070  389.73  6097.6  388.28  6494.1  390.92
  6687.4  395.26  7094.1  400.62  7124.6  403.22  7256.8  408.29  7276.1  411.03
#Mann= 6 ,-1 , 0
  3749.9     .12       0  4105.6     .05       0  4826.6     .12       0
  4997.4     .07       0  5021.6     .12       0  5535.9     .05       0
Bank Sta=4997.4,5021.6
XS Rating Curve= 0 ,0
Exp/Cntr=0.3,0.1

Type RM Length L Ch R = 1 ,34275   ,854,854,854
BEGIN DESCRIPTION:
Williams Creek 49.0
END DESCRIPTION:
XS GIS Cut Line= 3
      2700128.38      6891127.75      2699021.38      6890569.17
      2696110.28      6890829.89
#Sta/Elev= 30
  3793.9  410.98  3911.5  409.56  3964.6  405.29  4029.3  403.29  4151.2  396.32
  4337.7  388.83  4446.7  386.19  4917.7   386.9  5006.3  387.48  5015.3  383.24
  5020.9  383.28  5027.1   374.4  5029.5   373.9  5051.4   374.4  5059.3  386.84
  5069.4  388.73  5119.6   385.1  5169.8  390.86    5240  385.43  5440.8  384.85
  5531.2  386.58  6153.7  385.33  6680.3  387.62  7157.7  391.42  7187.8  393.95
  7207.9  391.49  7509.1  396.79  7649.7  403.74  7760.1  406.64  7956.6  417.08
#Mann= 6 ,-1 , 0
  3793.9     .05       0  4029.3     .12       0  4337.7     .05       0
  4917.7     .12       0  5027.1     .07       0  5051.4     .05       0
Bank Sta=5027.1,5051.4
XS Rating Curve= 0 ,0
Exp/Cntr=0.3,0.1

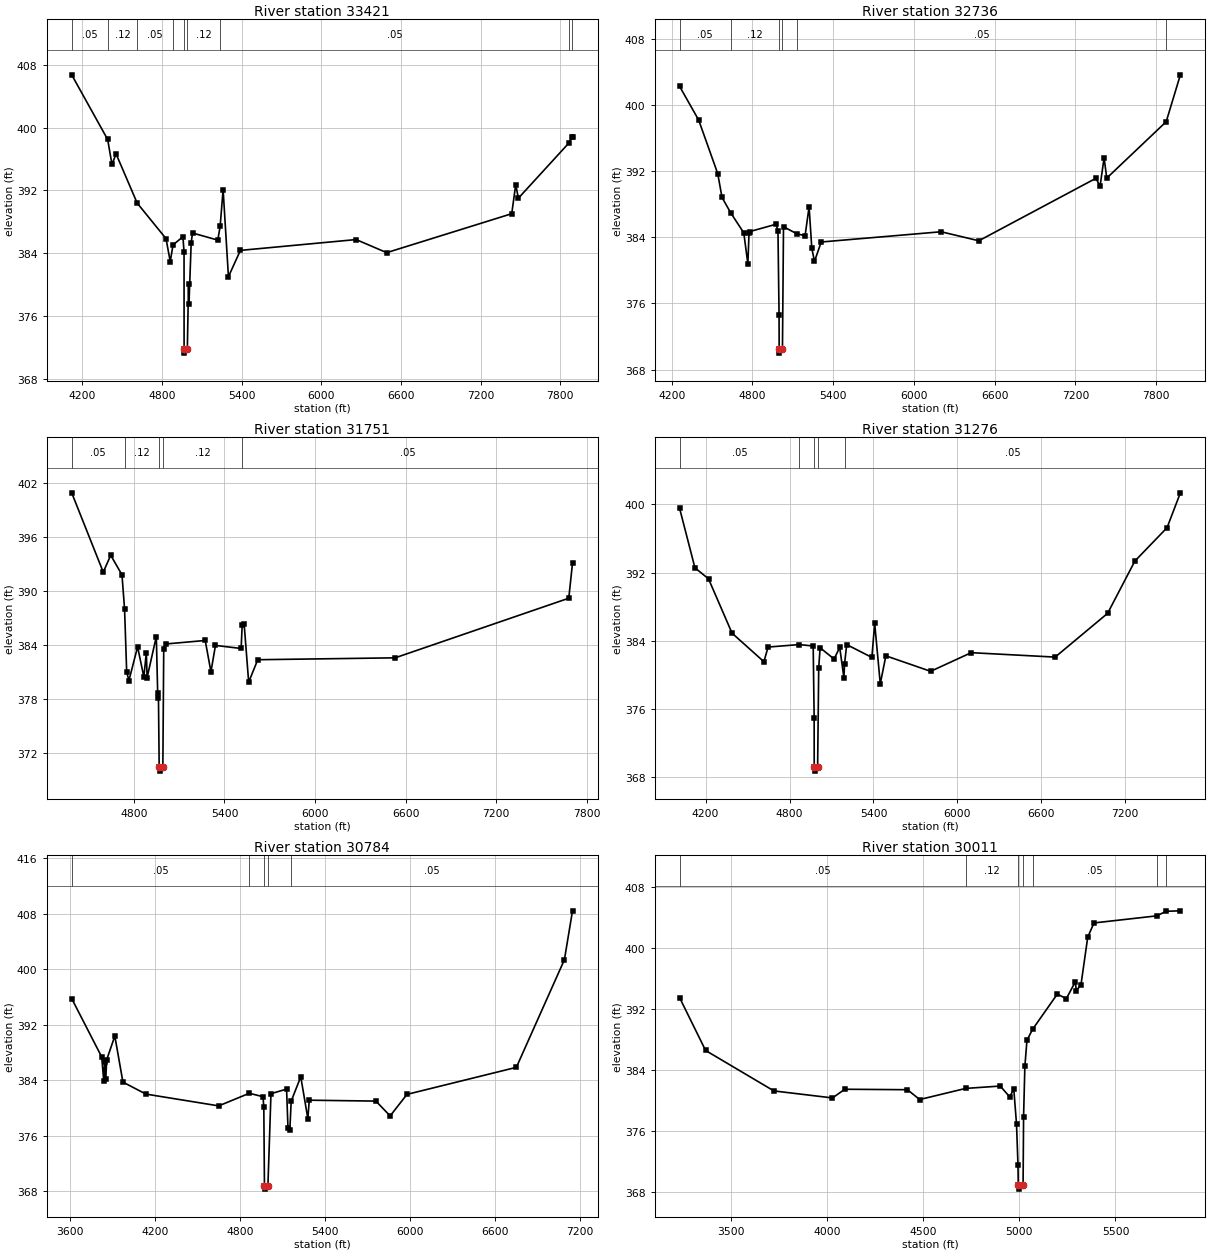
Type RM Length L Ch R = 1 ,33421   ,685,685,685
BEGIN DESCRIPTION:
Mapping XS 0e2fd6e5
END DESCRIPTION:
XS GIS Cut Line= 3
      2700156.77      6890286.18      2699325.91      6889995.91
      2696439.05      6890173.23
#Sta/Elev= 30
  4119.9  406.75  4390.8   398.5  4423.1  395.32  4454.2  396.66  4613.2  390.38
  4830.4  385.85  4862.2  382.92  4883.2  385.05  4957.5  386.09  4966.1  384.18
  4966.5  371.74    4969  371.24  4990.9  371.74  4999.9  380.03  5003.2  377.48
    5020  385.35    5030  386.57  5220.3  385.66    5238  387.41  5260.4   392.1
  5300.5  380.99  5390.6  384.35  6262.3  385.73  6492.7  384.06  7434.5  389.03
  7464.5  392.73  7484.6  391.01  7863.5  398.02  7886.3  398.77  7892.3  398.76
#Mann= 9 ,-1 , 0
  4119.9     .05       0  4390.8     .12       0  4613.2     .05       0
  4883.2     .12       0  4966.5     .07       0  4990.9     .12       0
    5238     .05       0  7863.5     .12       0  7886.3     .05       0
Bank Sta=4966.5,4990.9
XS Rating Curve= 0 ,0
Exp/Cntr=0.3,0.1

Type RM Length L Ch R = 1 ,32736   ,985,985,985
BEGIN DESCRIPTION:
Williams Creek 45.0
END DESCRIPTION:
XS GIS Cut Line= 3
      2699939.77      6889808.75      2699276.56      6889476.23
       2696299.6      6889619.46
#Sta/Elev= 30
  4258.1  402.26  4400.1  398.18    4542  391.69  4573.3  388.83    4637  386.99
  4735.3  384.54  4765.7  380.78  4774.4  384.56  4779.9  384.69  4975.4  385.58
  4989.4  384.78  4997.5  374.66  4998.4  370.49  5000.8  369.99  5022.8  370.49
  5030.6  385.27  5127.5  384.45  5190.8  384.17  5220.8  387.69  5240.8  382.69
  5260.9  381.09  5310.9  383.43  6201.9  384.67  6482.3  383.58  7353.3  391.14
  7383.3  390.16  7413.3   393.6  7433.4  391.16  7874.9  397.98  7980.4  403.65
#Mann= 6 ,-1 , 0
  4258.1     .05       0    4637     .12       0  4998.4     .07       0
  5022.8     .12       0  5127.5     .05       0  7874.9     .12       0
Bank Sta=4998.4,5022.8
XS Rating Curve= 0 ,0
Exp/Cntr=0.3,0.1

Type RM Length L Ch R = 1 ,31751   ,475,475,475
BEGIN DESCRIPTION:
Williams Creek 44.0
END DESCRIPTION:
XS GIS Cut Line= 3
      2700168.08      6889083.06      2699576.15      6888926.06
      2696871.19      6889025.77
#Sta/Elev= 30
  4387.6  400.89  4596.7  392.07  4646.2  393.95  4720.8  391.77    4738  387.95
  4751.9  380.99  4766.8  380.01  4824.3  383.77  4865.7  380.41  4882.2  383.12
  4887.4  380.34  4948.4  384.91  4957.4  378.61  4962.6  378.11  4967.3  370.44
  4969.7  369.94  4991.7  370.44  4997.5  383.53  5010.2  384.08  5272.5  384.47
  5310.4  380.99  5340.4  383.92  5510.5  383.58  5517.5  386.18  5530.5  386.29
  5560.5  379.83  5620.6  382.33  6531.2  382.54    7682  389.17  7706.8  393.07
#Mann= 5 ,-1 , 0
  4387.6     .05       0    4738     .12       0  4967.3     .07       0
  4991.7     .12       0  5517.5     .05       0
Bank Sta=4967.3,4991.7
XS Rating Curve= 0 ,0
Exp/Cntr=0.3,0.1

Type RM Length L Ch R = 1 ,31276   ,492,492,492
BEGIN DESCRIPTION:
Williams Creek 43.0
END DESCRIPTION:
XS GIS Cut Line= 3
       2700319.1      6888958.05      2699475.38      6888489.31
      2696860.94      6888510.14
#Sta/Elev= 30
  4014.2  399.55  4123.9  392.56  4221.1  391.26  4389.3  384.88  4616.9  381.53
  4646.9  383.25  4870.1  383.54  4969.3  383.37  4976.2  374.87  4976.6  369.18
    4979  368.68    5001  369.18  5008.8  380.83  5018.8  383.17  5118.8  381.84
  5158.8  383.21  5188.8  379.66  5193.7  381.29  5208.8  383.54  5388.8  382.03
  5408.8  386.03  5448.8  378.94  5488.8  382.22  5808.8   380.4  6098.8  382.59
  6698.8  382.07  7073.8  387.21  7268.8  393.35  7498.8  397.27  7593.9  401.36
#Mann= 5 ,-1 , 0
  4014.2     .05       0  4870.1     .12       0  4976.6     .07       0
    5001     .12       0  5193.7     .05       0
Bank Sta=4976.6,5001
XS Rating Curve= 0 ,0
Exp/Cntr=0.3,0.1

Type RM Length L Ch R = 1 ,30784   ,773,773,773
BEGIN DESCRIPTION:
Williams Creek 42.0
END DESCRIPTION:
XS GIS Cut Line= 4
      2700414.82      6888860.21      2700146.28      6888533.33
       2699286.6      6888101.45       2697140.2      6888024.06
#Sta/Elev= 30
  3614.9  395.77  3826.6  387.35  3840.9  383.91  3847.4  386.65  3855.3  384.18
  3861.7  386.94  3919.1  390.37  3976.2  383.72  4138.4  381.99  4651.9  380.29
    4868  382.11  4964.6  381.61  4970.1  380.07  4974.6  368.78  4977.1  368.28
  4999.1  368.78  5020.6  382.05  5130.7  382.71  5140.7  377.04  5153.5  376.74
  5163.2  380.97  5230.8  384.49  5280.8  378.45  5290.8  381.11  5761.1  380.98
  5861.2  378.84  5980.1  381.95  6751.7  385.85  7090.5  401.37  7147.8  408.43
#Mann= 5 ,-1 , 0
  3614.9     .05       0    4868     .12       0  4974.6     .07       0
  4999.1     .12       0  5163.2     .05       0
Bank Sta=4974.6,4999.1
XS Rating Curve= 0 ,0
Exp/Cntr=0.3,0.1

Type RM Length L Ch R = 1 ,30011   ,576,576,576
BEGIN DESCRIPTION:
Williams Creek 41.0
END DESCRIPTION:
XS GIS Cut Line= 3
      2700626.31      6888651.94      2699292.64      6887494.32
      2698523.98      6887162.05
#Sta/Elev= 30
    3234  393.46  3369.3  386.52  3724.4  381.21  4028.9  380.29  4092.9  381.43
  4418.6  381.37  4482.3  380.08  4721.3  381.54  4901.1  381.85  4950.4  380.42
  4971.3  381.49  4985.6  376.85  4993.2  371.53  4994.7  368.82  4997.2  368.32
  5019.7  368.82  5022.3  377.83    5029  384.44  5039.9  387.86  5069.2   389.3
  5197.6  393.92  5244.6  393.32  5290.5   395.5  5297.1  394.39  5320.6  395.13
  5355.9  401.41  5388.5  403.26  5714.8  404.19  5763.1  404.79  5837.4  404.85
#Mann= 7 ,-1 , 0
    3234     .05       0  4721.3     .12       0  4994.7     .07       0
  5019.7     .12       0  5069.2     .05       0  5714.8     .12       0
  5763.1     .05       0
Bank Sta=4994.7,5019.7
XS Rating Curve= 0 ,0
Exp/Cntr=0.3,0.1

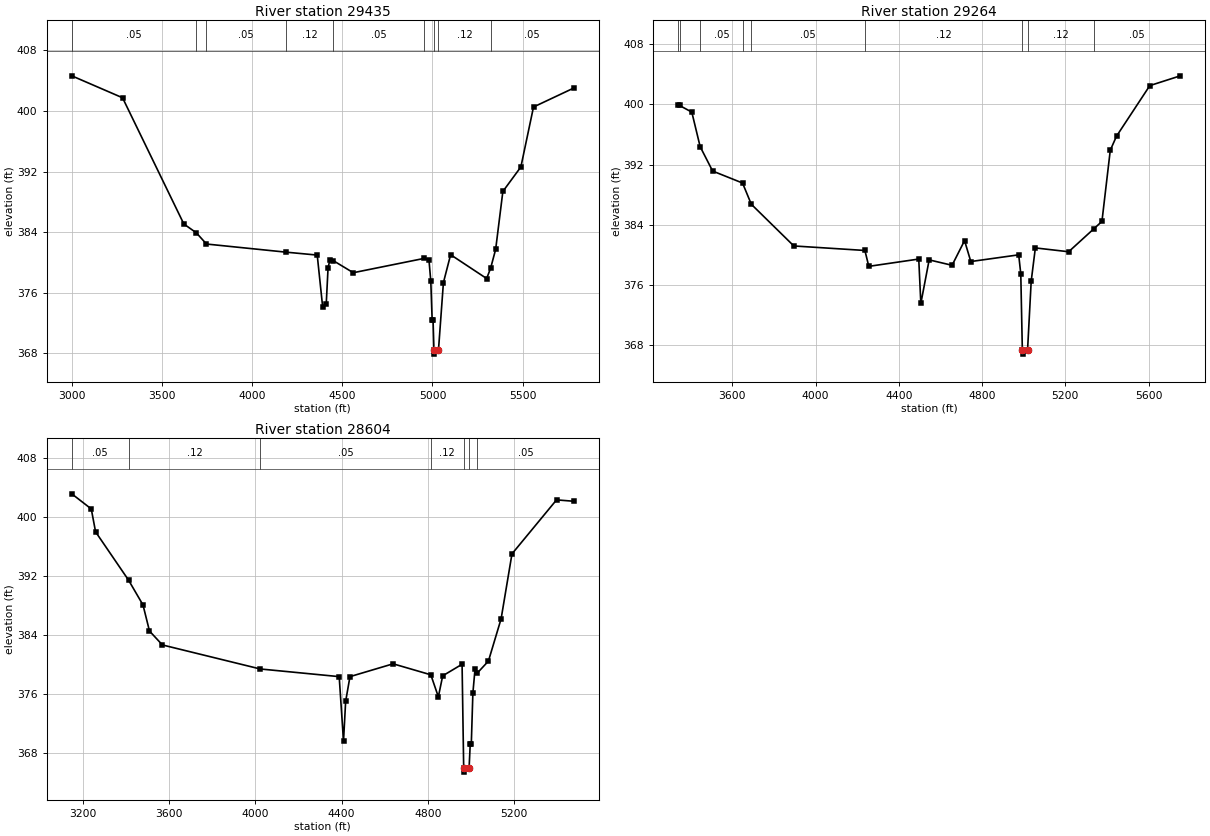
Type RM Length L Ch R = 1 ,29435   ,171,171,171
BEGIN DESCRIPTION:
Williams Creek 40.0
END DESCRIPTION:
XS GIS Cut Line= 3
      2701777.62      6887344.69        2699776.        6887261.
      2698992.05      6887239.66
#Sta/Elev= 30
  2997.3  404.65  3279.2  401.75  3619.5  385.07    3689   383.9  3745.3  382.42
  4185.2  381.35  4360.1  380.96  4390.1  374.15  4410.1  374.48  4420.2  379.24
  4430.2  380.33  4450.2  380.21  4560.3  378.63  4955.5  380.53  4980.6   380.3
  4990.7  377.48  4998.2  372.36  5003.2  372.36  5008.2  368.37  5010.7  367.87
  5033.2  368.37  5060.7  377.32  5100.7  381.01  5300.8  377.86  5323.1  379.25
  5350.8  381.72  5390.8  389.37  5490.8  392.61  5560.9  400.53  5784.9  403.04
#Mann= 9 ,-1 , 0
  2997.3     .05       0    3689     .12       0  3745.3     .05       0
  4185.2     .12       0  4450.2     .05       0  4955.5     .12       0
  5008.2     .07       0  5033.2     .12       0  5323.1     .05       0
Bank Sta=5008.2,5033.2
XS Rating Curve= 0 ,0
Exp/Cntr=0.3,0.1

Type RM Length L Ch R = 1 ,29264   ,660,660,660
BEGIN DESCRIPTION:
Williams Creek 39.0
END DESCRIPTION:
XS GIS Cut Line= 3
       2701491.2       6887162.4      2699831.77      6887108.68
      2699079.45      6887118.98
#Sta/Elev= 30
  3339.7  399.85    3346  399.85  3404.9  398.97    3445  394.38    3505  391.14
  3648.7  389.55  3690.8  386.73  3895.2  381.19  4236.7  380.59  4255.4  378.48
  4495.5  379.45  4505.5  373.55  4545.5  379.34  4655.6  378.62  4715.6   381.9
  4745.6  379.12  4975.8  380.01  4985.8  377.47  4993.3  367.32  4995.8  366.82
  5018.3  367.32  5035.8   376.5  5055.8  380.93  5215.8  380.42  5335.3  383.43
  5375.8  384.45  5415.8   393.9  5445.8  395.77  5605.8  402.49  5752.4  403.79
#Mann= 9 ,-1 , 0
  3339.7     .05       0    3346     .12       0    3445     .05       0
  3648.7     .12       0  3690.8     .05       0  4236.7     .12       0
  4993.3     .07       0  5018.3     .12       0  5335.3     .05       0
Bank Sta=4993.3,5018.3
XS Rating Curve= 0 ,0
Exp/Cntr=0.3,0.1

Type RM Length L Ch R = 1 ,28604   ,854,854,854
BEGIN DESCRIPTION:
Williams Creek 38.0
END DESCRIPTION:
XS GIS Cut Line= 3
       2701476.4       6886847.3      2699625.46      6886776.22
      2699151.01        6886836.
#Sta/Elev= 30
  3147.7  403.16  3238.2  401.11  3258.2     398  3411.4  391.44  3478.3  388.08
  3508.4  384.54  3568.4  382.65  4022.5  379.39    4389  378.35    4409  369.59
    4419     375    4439  378.35  4639.2  380.09  4814.3   378.6  4849.3  375.61
  4869.4  378.46  4959.4  380.03  4966.9  365.89  4969.4  365.39  4991.9  365.89
  4997.2  369.18  5002.2  369.18  5009.5   376.1  5019.6  379.41  5030.8  378.86
  5081.7  380.46  5140.6   386.2    5191  395.01  5397.9  402.34  5478.2  402.15
#Mann= 7 ,-1 , 0
  3147.7     .05       0  3411.4     .12       0  4022.5     .05       0
  4814.3     .12       0  4966.9     .07       0  4991.9     .12       0
  5030.8     .05       0
Bank Sta=4966.9,4991.9
XS Rating Curve= 0 ,0
Exp/Cntr=0.3,0.1