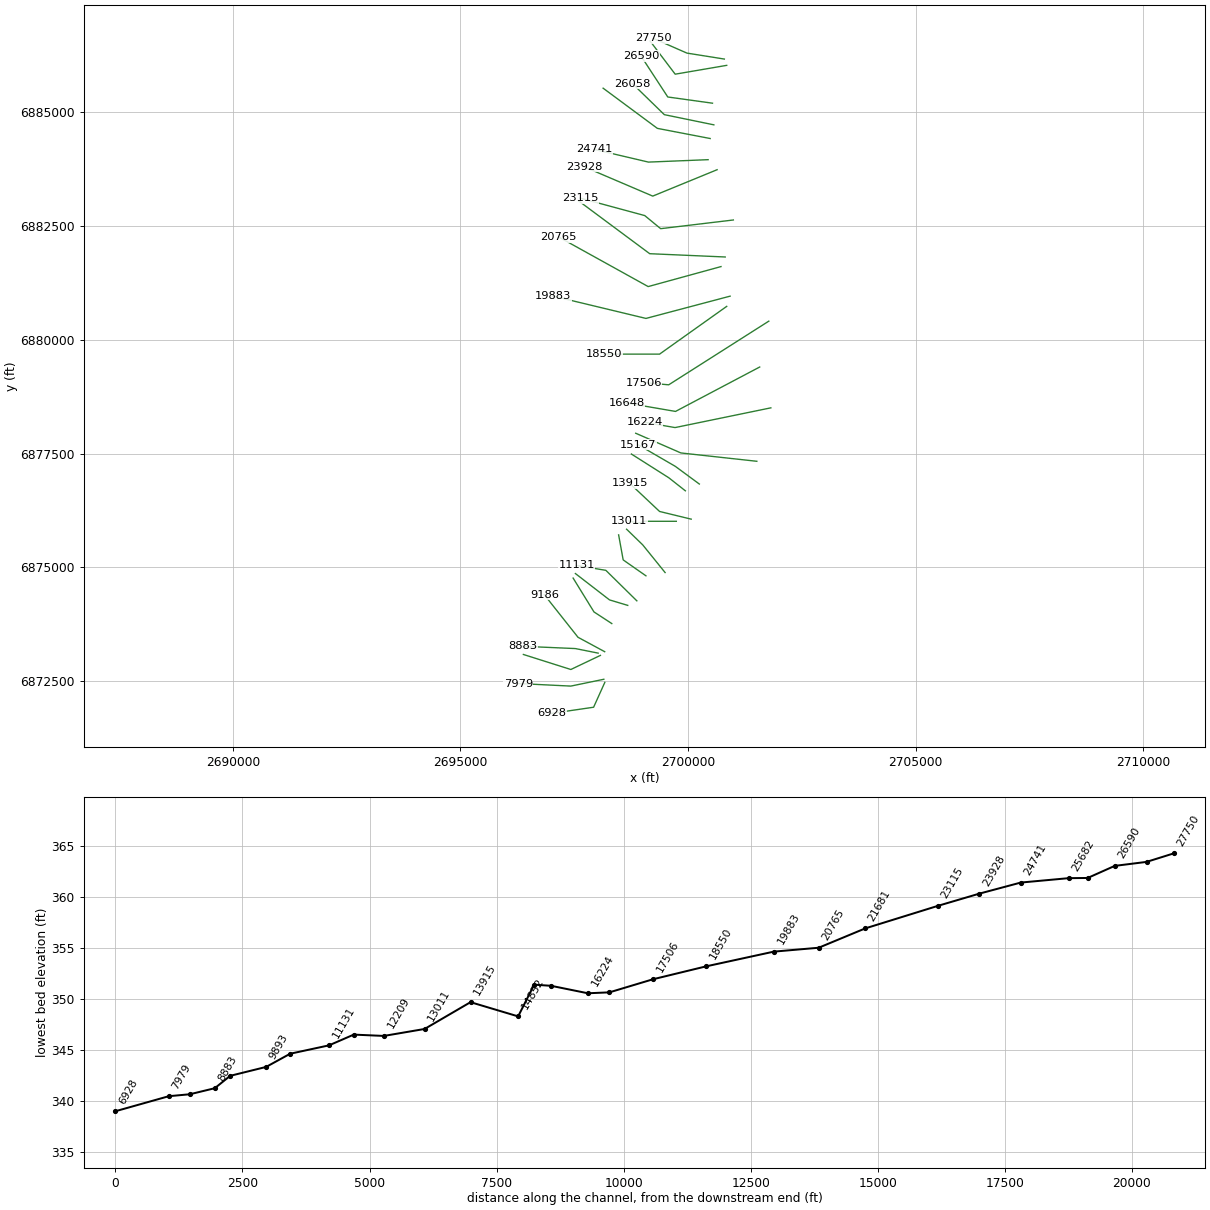
HEC-RAS study Williams Creek.prj: Williams Creek Base Level Engineering

--- Williams Creek.g01 (geometry) --- (continued)

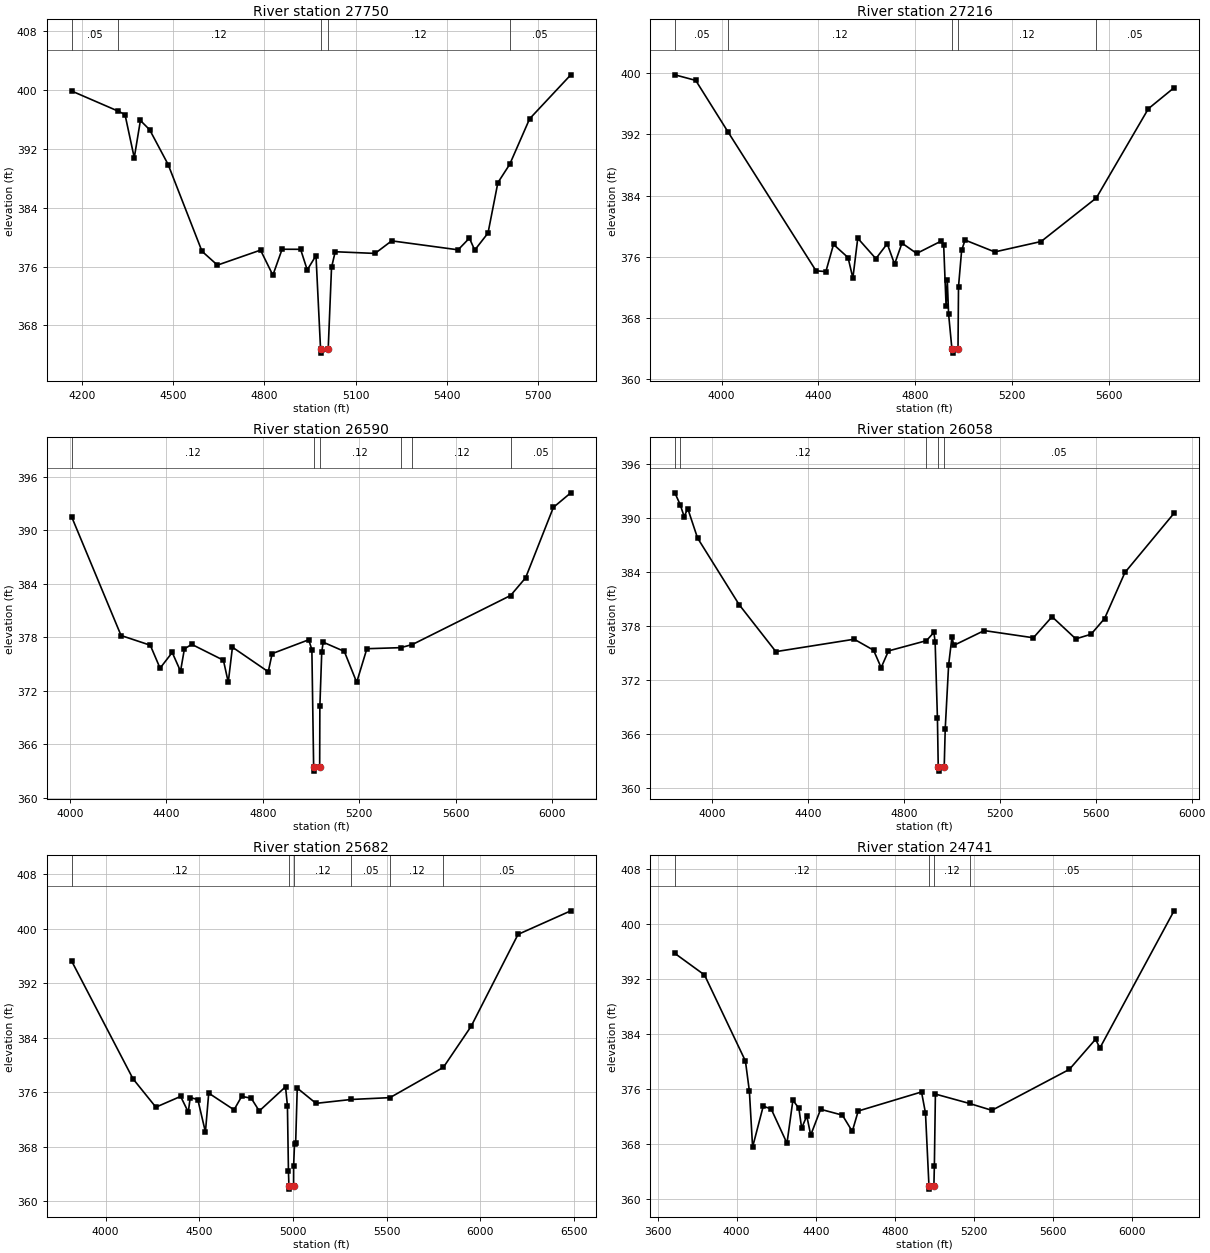
Type RM Length L Ch R = 1 ,27750   ,534,534,534
BEGIN DESCRIPTION:
Williams Creek 37.0
END DESCRIPTION:
XS GIS Cut Line= 3
       2700799.3      6886174.56      2699976.49      6886305.79
      2699236.84      6886630.28
#Sta/Elev= 30
  4166.8  399.88  4319.3  397.15  4342.3  396.67  4372.7   390.8  4392.9  395.87
  4423.3  394.61  4484.1  389.88  4595.4  378.08  4646.1   376.2  4787.8  378.24
  4828.4  374.83  4858.7  378.36  4919.5  378.35  4941.3  375.55  4970.1  377.49
  4985.2  364.73  4987.7  364.23  5010.2  364.73  5021.2  375.88  5033.3  378.02
  5164.3  377.79  5218.9   379.5  5437.3  378.28  5474.5  379.87  5491.9  378.24
  5535.6  380.56    5568  387.41    5607  389.91  5672.4   396.1  5807.7  402.08
#Mann= 5 ,-1 , 0
  4166.8     .05       0  4319.3     .12       0  4985.2     .07       0
  5010.2     .12       0    5607     .05       0
Bank Sta=4985.2,5010.2
XS Rating Curve= 0 ,0
Exp/Cntr=0.3,0.1

Type RM Length L Ch R = 1 ,27216   ,626,626,626
BEGIN DESCRIPTION:
Williams Creek 36.0
END DESCRIPTION:
XS GIS Cut Line= 3
        2700851.        6886036.      2699718.61      6885842.09
      2699167.42      6886571.22
#Sta/Elev= 30
  3807.1  399.78  3893.3  399.05  4026.2  392.34  4390.5  374.16  4431.1  374.06
  4462.7  377.61  4522.8  375.89  4542.7  373.21  4562.9  378.42  4637.8  375.75
  4684.7   377.7  4715.1  375.03  4745.6  377.78  4806.4  376.43  4907.9  378.05
    4918   377.5    4928  369.54    4933  372.91  4938.3  368.52  4952.2   363.9
  4954.7   363.4  4977.2   363.9  4979.3  372.09  4992.2  376.83  5006.4  378.18
  5129.1  376.63  5320.6  377.99    5549  383.69  5763.9  395.35    5870  398.09
#Mann= 5 ,-1 , 0
  3807.1     .05       0  4026.2     .12       0  4952.2     .07       0
  4977.2     .12       0    5549     .05       0
Bank Sta=4952.2,4977.2
XS Rating Curve= 0 ,0
Exp/Cntr=0.3,0.1

Type RM Length L Ch R = 1 ,26590   ,532,532,532
BEGIN DESCRIPTION:
Williams Creek 35.0
END DESCRIPTION:
XS GIS Cut Line= 3
      2700538.87      6885204.08       2699556.2      6885340.52
      2698967.76      6886241.36
#Sta/Elev= 30
  4007.9   391.5  4212.7   378.2  4333.9  377.11  4374.3  374.54  4424.7   376.3
  4459.1   374.2  4475.2   376.7  4505.5  377.21  4636.8  375.43  4656.9  372.96
  4674.2  376.89  4822.6  374.14  4838.7  376.17  4990.1  377.72  5003.3  376.62
  5010.6  363.51  5013.1  363.01  5035.6  363.51  5036.4  370.26  5044.2  376.35
  5050.2  377.45  5137.7  376.42    5189  372.96  5231.2  376.72  5371.8  376.84
  5419.7  377.19  5826.6  382.68  5888.8  384.66  6003.9  392.55    6076  394.18
#Mann= 6 ,-1 , 0
  4007.9     .12       0  5010.6     .07       0  5035.6     .12       0
  5371.8     .05       0  5419.7     .12       0  5826.6     .05       0
Bank Sta=5010.6,5035.6
XS Rating Curve= 0 ,0
Exp/Cntr=0.3,0.1

Type RM Length L Ch R = 1 ,26058   ,376,376,376
BEGIN DESCRIPTION:
Williams Creek 34.0
END DESCRIPTION:
XS GIS Cut Line= 3
      2700568.61      6884728.14      2699480.07       6884952.1
      2698784.72      6885629.22
#Sta/Elev= 30
  3844.6  392.76  3867.1  391.42  3883.3  390.12  3898.3  391.01  3939.1  387.74
  4112.7  380.33  4265.8  375.11  4592.6  376.49  4673.3  375.27  4704.9  373.33
  4735.5  375.19  4893.7  376.33    4925  377.25  4930.1  376.17  4939.7  367.69
    4943  362.33  4945.5  361.83    4968  362.33  4972.2  366.55  4986.4  373.65
  5000.5  376.79  5007.5   375.8  5134.8  377.45  5339.8  376.65  5417.7  378.99
  5516.7  376.53  5580.3  377.04  5636.9  378.79  5721.8  383.91  5926.5  390.49
#Mann= 5 ,-1 , 0
  3844.6     .05       0  3867.1     .12       0  4893.7     .05       0
    4943     .03       0    4968     .05       0
Bank Sta=4943,4968
XS Rating Curve= 0 ,0
Exp/Cntr=0.3,0.1

Type RM Length L Ch R = 1 ,25682   ,941,941,941
BEGIN DESCRIPTION:
Williams Creek 33.0
END DESCRIPTION:
XS GIS Cut Line= 3
      2700487.67      6884427.29      2699327.33      6884650.45
      2698135.21      6885534.08
#Sta/Elev= 30
  3818.4  395.29    4146  378.01  4268.2  373.84  4400.5  375.42  4441.3  373.12
  4451.8  375.25  4492.2  374.96  4532.9  370.19  4550.5   375.9  4685.7  373.45
  4726.4  375.42  4777.3  375.16  4820.4  373.28  4960.6  376.83  4970.8  374.06
  4976.2  364.49  4978.7  362.31  4981.2  361.81  5003.7  362.31  5003.9  365.23
  5008.6  368.38  5014.8  368.63  5023.2  376.64  5123.4   374.4  5311.5  374.97
  5518.5  375.24  5803.7  379.69  5951.8  385.71  6202.2   399.2  6483.9  402.66
#Mann= 6 ,-1 , 0
  3818.4     .12       0  4978.7     .07       0  5003.7     .12       0
  5311.5     .05       0  5518.5     .12       0  5803.7     .05       0
Bank Sta=4978.7,5003.7
XS Rating Curve= 0 ,0
Exp/Cntr=0.3,0.1

Type RM Length L Ch R = 1 ,24741   ,813,813,813
BEGIN DESCRIPTION:
Williams Creek 32.0
END DESCRIPTION:
XS GIS Cut Line= 3
      2700442.51      6883962.01      2699131.09      6883908.71
      2697951.03      6884185.99
#Sta/Elev= 30
  3687.5  395.75  3837.3  392.61  4044.3  380.06  4064.3  375.68  4080.6  367.51
  4134.4  373.47  4174.4  373.08  4254.5  368.07  4284.5  374.34  4314.5  373.18
  4328.8  370.26  4354.6  372.06  4374.6  369.26  4424.6  373.02  4534.7  372.17
  4584.8   369.8  4614.8  372.77    4935  375.55  4955.1  372.46  4972.6  361.88
  4975.1  361.38  4997.6  361.88    5000  364.79  5005.2  375.24  5177.7  373.87
  5290.9  372.87  5682.8  378.84  5815.2  383.23  5837.3  381.96  6212.2  401.96
#Mann= 4 ,-1 , 0
  3687.5     .12       0  4972.6     .07       0  4997.6     .12       0
  5177.7     .05       0
Bank Sta=4972.6,4997.6
XS Rating Curve= 0 ,0
Exp/Cntr=0.3,0.1

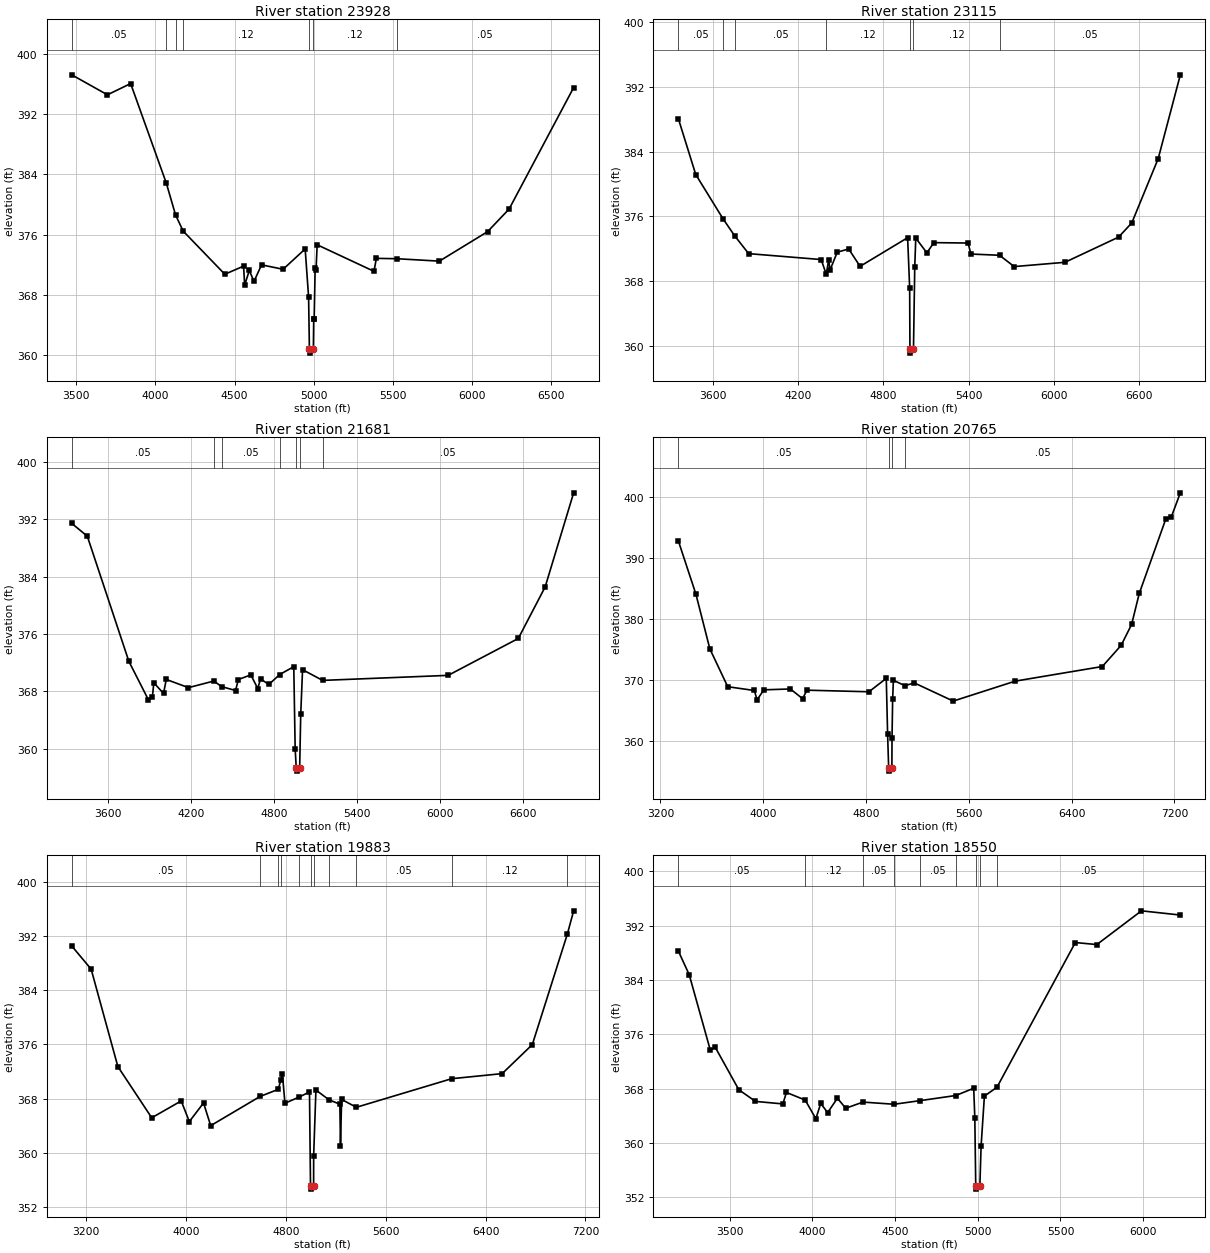
Type RM Length L Ch R = 1 ,23928   ,813,813,813
BEGIN DESCRIPTION:
Williams Creek 31.0
END DESCRIPTION:
XS GIS Cut Line= 3
      2700640.15      6883741.24      2699226.08      6883160.97
      2697716.04      6883806.18
#Sta/Elev= 30
  3471.5  397.21  3696.8  394.56  3843.5  396.05  4069.1  382.83  4127.2  378.63
  4175.1  376.49  4438.5  370.76  4556.9  371.84  4563.8  369.32  4593.2  371.27
  4622.6  369.81  4670.5  372.01  4806.6  371.42    4946  374.12  4967.7  367.74
  4972.8   360.8  4975.3   360.3  4997.8   360.8    5000  364.84  5002.8  364.84
  5009.2  371.61  5014.6  371.33  5021.8  374.67  5380.7  371.15  5395.8  372.87
  5525.9  372.82  5793.9   372.5  6098.4  376.41  6234.4  379.41  6642.1  395.52
#Mann= 7 ,-1 , 0
  3471.5     .05       0  4069.1     .12       0  4127.2     .05       0
  4175.1     .12       0  4972.8     .07       0  4997.8     .12       0
  5525.9     .05       0
Bank Sta=4972.8,4997.8
XS Rating Curve= 0 ,0
Exp/Cntr=0.3,0.1

Type RM Length L Ch R = 1 ,23115   ,1434,1434,1434
BEGIN DESCRIPTION:
Mapping XS 7435fd88
END DESCRIPTION:
XS GIS Cut Line= 4
      2700997.27      6882635.74      2699400.07      6882444.77
      2699049.38      6882732.97      2697625.73      6883118.39
#Sta/Elev= 30
    3355  388.04  3477.1  381.17  3669.5   375.7  3750.6  373.62  3849.8   371.4
    4361  370.67  4396.7  368.86  4413.8   370.6  4423.8  369.38  4474.2  371.58
  4554.8  371.98  4635.3  369.83  4970.4  373.37  4984.8  367.12  4986.6  359.61
  4989.1  359.11  5011.6  359.61  5020.6  369.74  5027.8  373.32    5106   371.5
  5155.5  372.76  5396.6  372.71  5416.4  371.35  5618.1   371.2  5721.4   369.8
  6079.2  370.33    6457  373.44  6550.2  375.19  6736.7  383.15  6892.4  393.49
#Mann= 7 ,-1 , 0
    3355     .05       0  3669.5     .12       0  3750.6     .05       0
  4396.7     .12       0  4986.6     .07       0  5011.6     .12       0
  5618.1     .05       0
Bank Sta=4986.6,5011.6
XS Rating Curve= 0 ,0
Exp/Cntr=0.3,0.1

Type RM Length L Ch R = 1 ,21681   ,916,916,916
BEGIN DESCRIPTION:
Williams Creek 30.0
END DESCRIPTION:
XS GIS Cut Line= 3
       2700818.1      6881821.97      2699158.98      6881894.47
      2697582.54      6883066.35
#Sta/Elev= 30
  3339.3  391.41  3451.5  389.63  3751.8  372.19  3893.4  366.82    3922  367.29
    3932  369.21    4002  367.72    4022  369.67  4182.2  368.53  4365.3  369.45
  4422.4  368.67  4522.5  368.13  4542.5  369.66  4632.6  370.31  4682.7  368.41
  4702.7  369.75  4762.8  368.97  4841.3  370.36  4942.9  371.45  4952.9  360.01
  4960.5   357.4    4963   356.9  4985.5   357.4    4993  364.79  5006.3  371.03
  5151.2  369.54  6057.6  370.24  6564.5  375.38  6758.5  382.56  6964.3  395.67
#Mann= 7 ,-1 , 0
  3339.3     .05       0  4365.3     .12       0  4422.4     .05       0
  4841.3     .12       0  4960.5     .07       0  4985.5     .12       0
  5151.2     .05       0
Bank Sta=4960.5,4985.5
XS Rating Curve= 0 ,0
Exp/Cntr=0.3,0.1

Type RM Length L Ch R = 1 ,20765   ,882,882,882
BEGIN DESCRIPTION:
Williams Creek 29.0
END DESCRIPTION:
XS GIS Cut Line= 3
      2700725.96      6881610.99      2699125.13      6881171.34
      2697160.56      6882260.52
#Sta/Elev= 30
  3339.9   392.8  3475.9  384.09  3584.4   375.1  3723.6  368.88    3931  368.26
  3951.7  366.71  4004.7  368.37    4211  368.51  4306.1  366.92  4340.5  368.31
  4822.8  368.05  4957.6  370.25    4968  361.04  4976.2  355.51  4978.7  355.01
  5001.2  355.51  5002.4  360.52  5007.2  366.87  5012.9  369.93  5103.2  369.05
  5175.4  369.51  5478.7  366.52  5961.7   369.8  6639.3   372.2  6785.8  375.68
  6867.1  379.11  6926.6   384.2  7132.7  396.41  7176.2  396.78  7246.3  400.74
#Mann= 4 ,-1 , 0
  3339.9     .05       0  4976.2     .07       0  5001.2     .05       0
  5103.2     .05       0
Bank Sta=4976.2,5001.2
XS Rating Curve= 0 ,0
Exp/Cntr=0.3,0.1

Type RM Length L Ch R = 1 ,19883   ,1333,1333,1333
BEGIN DESCRIPTION:
Williams Creek 28.0
END DESCRIPTION:
XS GIS Cut Line= 3
      2700926.02      6880961.01      2699076.82      6880471.07
      2697029.63      6880963.54
#Sta/Elev= 30
    3087  390.52  3242.2   387.1  3456.1  372.72  3727.3  365.16  3963.4  367.65
  4028.4   364.6  4142.2  367.35  4199.5     364  4594.9  368.31  4740.6  369.36
  4760.2  370.71  4773.3  371.69    4794  367.31    4904  368.19  4990.5  368.97
  4998.6  355.13  5001.1  354.63  5023.6  355.13  5023.8  359.51    5042  369.26
    5146  367.82  5233.6  367.17  5238.7  361.06  5247.7  367.87  5365.8  366.71
  6128.8  370.93  6533.4  371.68  6774.6  375.96  7054.4  392.23  7105.6  395.71
#Mann= 11 ,-1 , 0
    3087     .05       0  4594.9     .12       0  4740.6     .05       0
  4760.2     .12       0    4904      .1       0  4998.6     .07       0
  5023.6      .1       0    5146     .12       0  5365.8     .05       0
  6128.8     .12       0  7054.4     .05       0
Bank Sta=4998.6,5023.6
XS Rating Curve= 0 ,0
Exp/Cntr=0.3,0.1

Type RM Length L Ch R = 1 ,18550   ,1044,1044,1044
BEGIN DESCRIPTION:
Williams Creek 27.0
END DESCRIPTION:
XS GIS Cut Line= 3
        2700851.        6880736.      2699375.76      6879685.91
      2698150.96        6879686.
#Sta/Elev= 30
  3189.2  388.23  3254.4  384.77  3382.2  373.64  3411.8  374.08  3554.4  367.83
  3655.2  366.11  3821.2  365.74  3842.1  367.43  3955.8  366.31  4020.4  363.56
  4049.9  365.81  4091.7  364.46  4150.7  366.58  4201.2   365.1  4305.1  366.01
    4494  365.69    4650  366.22    4867  366.98  4975.2  368.05  4981.9  363.61
  4987.4  353.69  4989.9  353.19  5012.4  353.69  5019.8  359.54  5039.8  366.89
  5115.9   368.2  5589.8  389.51  5719.8  389.21  5989.8  394.18  6224.8  393.56
#Mann= 9 ,-1 , 0
  3189.2     .05       0  3955.8     .12       0  4305.1     .05       0
    4494     .12       0    4650     .05       0    4867      .1       0
  4987.4     .07       0  5012.4      .1       0  5115.9     .05       0
Bank Sta=4987.4,5012.4
XS Rating Curve= 0 ,0
Exp/Cntr=0.3,0.1

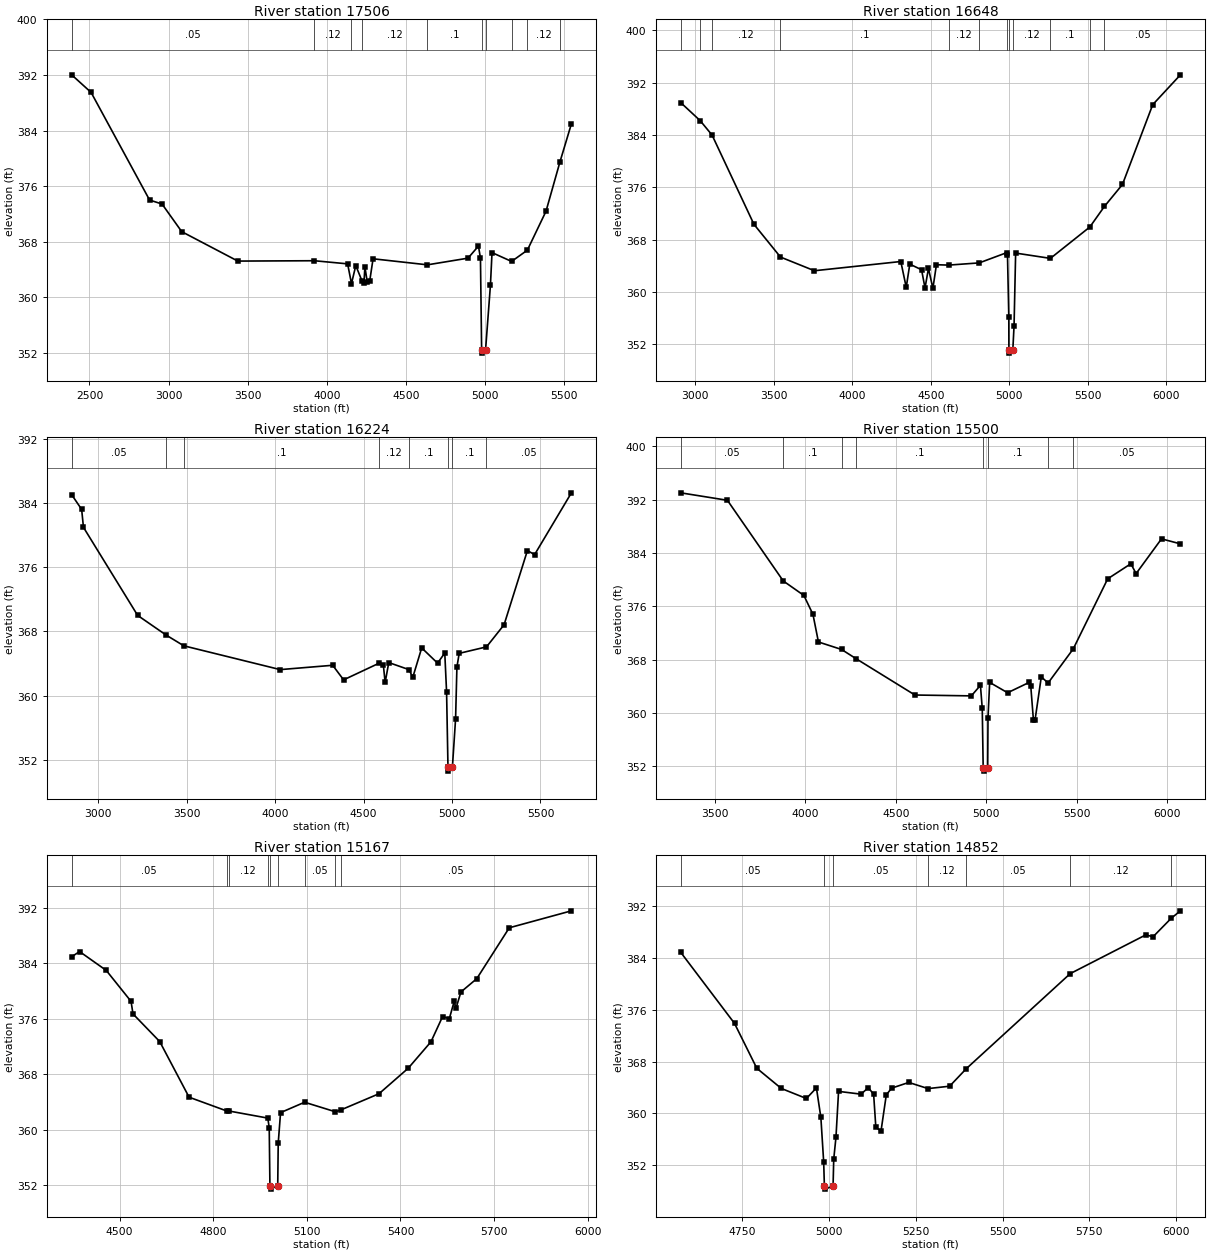
Type RM Length L Ch R = 1 ,17506   ,858,858,858
BEGIN DESCRIPTION:
Williams Creek 26.0
END DESCRIPTION:
XS GIS Cut Line= 3
        2701776.        6880411.        2699576.        6879011.
      2699026.05        6879061.
#Sta/Elev= 30
  2387.3  392.02  2510.1  389.49  2880.1  373.98  2958.8  373.41  3083.2  369.43
    3438  365.19  3921.8  365.24  4132.2  364.79  4156.6  361.95  4183.9  364.54
  4224.2  362.27  4235.5  362.04  4241.5  364.35  4256.7  362.12  4271.9  362.32
  4293.1  365.52  4636.9  364.65  4893.4  365.61  4959.4  367.35  4972.1  365.62
  4979.5  352.43    4982  351.93  5004.5  352.43  5035.1  361.69  5045.2  366.41
  5168.9  365.14  5268.6  366.76  5386.6  372.37  5474.9  379.49  5547.2  384.97
#Mann= 10 ,-1 , 0
  2387.3     .05       0  3921.8     .12       0  4156.6      .1       0
  4224.2     .12       0  4636.9      .1       0  4979.5     .07       0
  5004.5      .1       0  5168.9     .05       0  5268.6     .12       0
  5474.9     .05       0
Bank Sta=4979.5,5004.5
XS Rating Curve= 0 ,0
Exp/Cntr=0.3,0.1

Type RM Length L Ch R = 1 ,16648   ,424,424,424
BEGIN DESCRIPTION:
Williams Creek 24.0
END DESCRIPTION:
XS GIS Cut Line= 3
      2701575.82      6879402.49      2699726.03      6878426.02
      2698652.21      6878610.81
#Sta/Elev= 30
  2908.3  388.97  3032.1  386.21  3108.1     384  3374.7  370.35  3543.7  365.34
  3759.7  363.25  4309.6  364.66  4344.2  360.71  4366.8  364.26  4441.7   363.4
  4463.7  360.62  4485.7   363.6  4513.8  360.55  4536.4  364.17  4613.7  364.11
  4808.9  364.45  4983.3  366.01  4988.7   365.7  4997.2  356.11  4997.7  351.15
  5000.2  350.65  5022.7  351.15  5030.5  354.82  5040.6  365.95  5261.9  365.14
    5513  369.94  5605.9  373.09  5720.5  376.44  5913.3  388.65  6089.6  393.21
#Mann= 12 ,-1 , 0
  2908.3     .12       0  3032.1      .1       0  3108.1     .12       0
  3543.7      .1       0  4613.7     .12       0  4808.9      .1       0
  4983.3     .12       0  4997.7     .07       0  5022.7     .12       0
  5261.9      .1       0    5513     .12       0  5605.9     .05       0
Bank Sta=4997.7,5022.7
XS Rating Curve= 0 ,0
Exp/Cntr=0.3,0.1

Type RM Length L Ch R = 1 ,16224   ,724,724,724
BEGIN DESCRIPTION:
Williams Creek 23.0
END DESCRIPTION:
XS GIS Cut Line= 3
      2701821.35      6878504.77      2699715.89      6878070.86
      2699050.99        6878186.
#Sta/Elev= 30
  2850.3  385.09  2906.8  383.25    2917  381.01  3223.3  370.01  3383.9  367.56
  3484.4  366.21    4029  363.24  4325.7  363.78  4387.3  361.96  4587.8  364.04
  4611.9  363.81  4622.1  361.63  4642.5  364.12  4756.5  363.24  4778.4  362.28
  4828.7  365.95  4918.2  364.05  4959.1  365.31  4969.3  360.44  4977.2  351.06
  4979.7  350.56  5002.2  351.06  5020.2   357.1  5027.7  363.55  5040.5  365.27
  5194.9  366.08  5294.2  368.84  5426.1  378.11  5466.7   377.6  5674.8  385.32
#Mann= 8 ,-1 , 0
  2850.3     .05       0  3383.9     .12       0  3484.4      .1       0
  4587.8     .12       0  4756.5      .1       0  4977.2     .07       0
  5002.2      .1       0  5194.9     .05       0
Bank Sta=4977.2,5002.2
XS Rating Curve= 0 ,0
Exp/Cntr=0.3,0.1

Type RM Length L Ch R = 1 ,15500   ,333,333,333
BEGIN DESCRIPTION:
Mapping XS 2e4f2df7
END DESCRIPTION:
XS GIS Cut Line= 3
      2701512.72      6877329.55      2699843.85       6877512.9
       2698851.3      6877946.15
#Sta/Elev= 30
  3310.6  393.01  3568.9  391.89  3877.4   379.8  3991.4  377.63  4041.7  374.79
  4071.9  370.65  4199.6  369.53  4280.3  368.14  4605.1   362.7  4916.9  362.57
  4967.2  364.15  4977.3   360.7  4982.4  351.79  4984.9  351.29  5007.4  351.79
    5009   359.3  5018.3  364.59  5117.4  363.04  5238.1  364.61  5245.4  364.04
  5259.9  359.01  5268.8  358.91  5303.6  365.42  5341.2   364.5  5480.3  369.62
  5670.6  380.12  5798.6  382.38  5827.5   380.9  5967.9  386.11  6072.5  385.36
#Mann= 8 ,-1 , 0
  3310.6     .05       0  3877.4      .1       0  4199.6     .12       0
  4280.3      .1       0  4982.4     .07       0  5007.4      .1       0
  5341.2     .12       0  5480.3     .05       0
Bank Sta=4982.4,5007.4
XS Rating Curve= 0 ,0
Exp/Cntr=0.3,0.1

Type RM Length L Ch R = 1 ,15167   ,315,315,315
BEGIN DESCRIPTION:
Williams Creek 22.0
END DESCRIPTION:
XS GIS Cut Line= 3
      2700249.25      6876829.43       2699723.3      6877217.12
      2698903.81      6877693.12
#Sta/Elev= 30
  4346.6  384.96  4371.9  385.72  4457.5  382.99  4536.9  378.52  4543.1  376.71
  4628.7  372.72  4722.8  364.68  4844.1  362.68  4849.8  362.69    4975  361.66
  4979.6  360.26  4981.8   351.9  4984.3   351.4  5006.8   351.9  5008.4  358.05
  5015.9  362.45  5092.9  363.95  5191.8  362.57    5209  362.84  5331.3  365.18
  5424.8  368.86  5497.7  372.68    5535  376.33  5556.5  376.02  5572.2  378.52
    5578  377.55  5593.8  379.88  5644.5   381.8  5748.6  389.15  5947.7   391.6
#Mann= 9 ,-1 , 0
  4346.6     .05       0  4844.1      .1       0  4849.8     .12       0
    4975     .05       0  4981.8     .05       0  5006.8     .05       0
  5092.9     .05       0  5191.8     .12       0    5209     .05       0
Bank Sta=4981.8,5006.8
XS Rating Curve= 0 ,0
Exp/Cntr=0.3,0.1

Type RM Length L Ch R = 1 ,14852   ,937,937,937
BEGIN DESCRIPTION:
Williams Creek 21.0
END DESCRIPTION:
XS GIS Cut Line= 3
      2699942.62       6876680.1        2699579.      6876966.88
      2698756.25      6877489.12
#Sta/Elev= 30
  4574.2  384.89  4729.1   373.9  4793.2  366.97  4863.7  363.85  4935.9   362.3
  4964.7  363.94  4977.5  359.37  4985.6  352.48  4987.6   348.8  4990.1   348.3
  5012.6   348.8  5014.5  352.94  5020.9   356.3  5028.4   363.4  5092.9  362.97
  5114.1  363.98  5129.3  362.94  5135.6  357.86  5150.5  357.27  5165.7  362.86
    5181   363.9  5230.4  364.78  5285.8  363.83  5347.9   364.2  5395.7   366.9
  5694.8  381.59    5912  387.57  5933.2  387.29  5985.3  390.14  6011.8  391.29
#Mann= 7 ,-1 , 0
  4574.2     .05       0  4987.6     .03       0  5012.6     .05       0
  5285.8     .12       0  5395.7     .05       0  5694.8     .12       0
  5985.3     .05       0
Bank Sta=4987.6,5012.6
XS Rating Curve= 0 ,0
Exp/Cntr=0.3,0.1

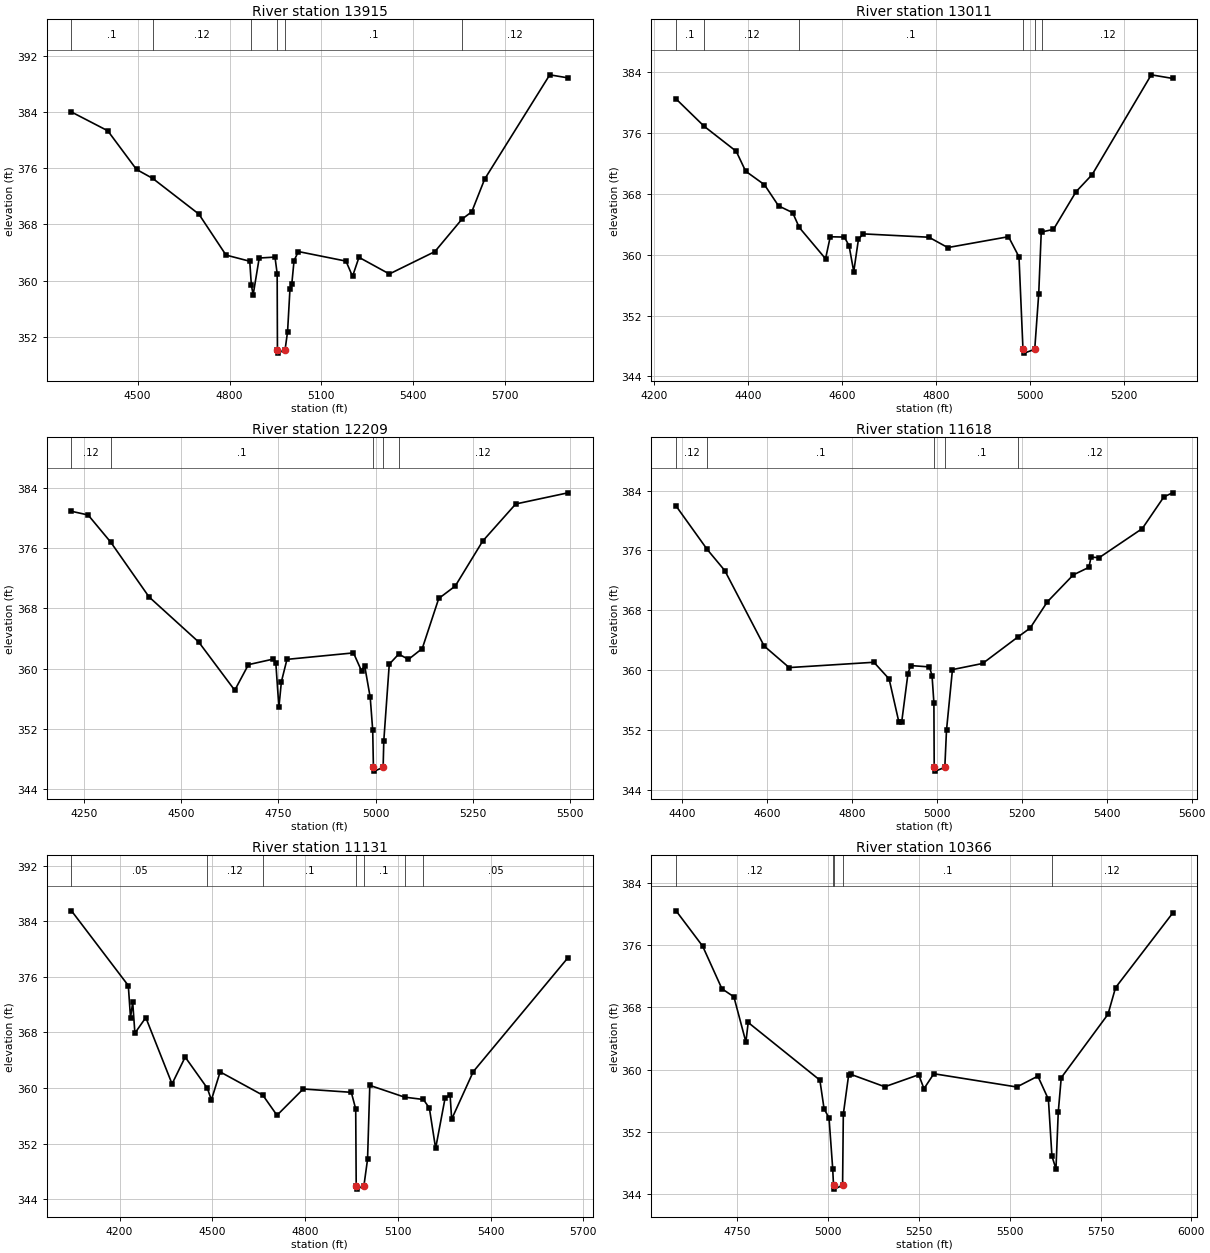
Type RM Length L Ch R = 1 ,13915   ,904,904,904
BEGIN DESCRIPTION:
Williams Creek 20.0
END DESCRIPTION:
XS GIS Cut Line= 3
      2700071.33      6876056.85      2699375.82      6876226.06
      2698717.56       6876846.4
#Sta/Elev= 30
  4284.2  383.99  4402.6  381.32  4496.4  375.82  4549.5  374.54  4699.9  369.47
  4788.5  363.64    4866  362.76  4871.2  359.41  4877.1  357.97  4896.9  363.22
  4948.4  363.35  4955.5  361.01  4956.4  350.19  4958.9  349.69  4981.4  350.19
  4989.5  352.76  4997.2  358.75  5003.3  359.53  5010.6  362.85  5024.7  364.14
  5180.1  362.78  5201.5  360.61  5222.5  363.32  5321.7  360.95  5470.2  364.13
  5558.7  368.75  5590.6  369.79  5632.8  374.45  5845.2  389.28  5904.5  388.85
#Mann= 6 ,-1 , 0
  4284.2      .1       0  4549.5     .12       0  4871.2      .1       0
  4956.4     .07       0  4981.4      .1       0  5558.7     .12       0
Bank Sta=4956.4,4981.4
XS Rating Curve= 0 ,0
Exp/Cntr=0.3,0.1

Type RM Length L Ch R = 1 ,13011   ,802,802,802
BEGIN DESCRIPTION:
Mapping XS 7e3e5f5f
END DESCRIPTION:
XS GIS Cut Line= 4
      2699744.04      6876009.97      2699046.15      6876009.97
      2698903.78      6875964.83      2698702.44      6876020.38
#Sta/Elev= 30
  4247.3  380.47    4307  376.88  4375.3  373.59  4395.3  370.98  4435.3   369.2
  4465.3  366.42  4495.3  365.53  4509.4  363.58  4565.3  359.47  4575.3  362.36
  4605.3  362.32  4615.3  361.19  4625.3  357.78  4635.3  362.03  4645.3  362.74
  4785.3   362.3  4825.3  360.94  4954.5  362.37  4976.8  359.72  4985.3  347.57
  4987.8  347.07  5010.3  347.57  5018.8  354.87  5024.3  363.17  5026.6  363.01
  5050.2  363.33  5098.2  368.28  5132.5  370.53  5258.2  383.64  5303.4  383.17
#Mann= 6 ,-1 , 0
  4247.3      .1       0    4307     .12       0  4509.4      .1       0
  4985.3     .07       0  5010.3      .1       0  5026.6     .12       0
Bank Sta=4985.3,5010.3
XS Rating Curve= 0 ,0
Exp/Cntr=0.3,0.1

Type RM Length L Ch R = 1 ,12209   ,591,591,591
BEGIN DESCRIPTION:
Williams Creek 19.0
END DESCRIPTION:
XS GIS Cut Line= 3
      2699497.55      6874882.35      2699005.79      6875491.15
      2698650.98      6875836.02
#Sta/Elev= 30
  4217.4  380.87  4260.2  380.38  4318.4  376.77  4416.9  369.51  4544.8  363.52
  4637.5  357.12  4672.7  360.52  4736.7  361.26  4743.1   360.8  4751.1  354.86
  4757.5  358.25  4771.9  361.22    4943  362.08  4963.8  359.68  4971.7  360.39
  4986.1  356.17  4992.5  351.81  4994.3  346.89  4996.8  346.39  5019.3  346.89
    5021   350.4  5035.1  360.58  5059.4  361.92  5084.5  361.22    5120  362.66
  5162.4   369.3  5204.9  370.95  5275.6  376.92  5360.5  381.84  5494.8  383.32
#Mann= 5 ,-1 , 0
  4217.4     .12       0  4318.4      .1       0  4994.3     .07       0
  5019.3      .1       0  5059.4     .12       0
Bank Sta=4994.3,5019.3
XS Rating Curve= 0 ,0
Exp/Cntr=0.3,0.1

Type RM Length L Ch R = 1 ,11618   ,487,487,487
BEGIN DESCRIPTION:
Williams Creek 18.0
END DESCRIPTION:
XS GIS Cut Line= 3
        2699076.        6874811.        2698576.        6875161.
      2698476.01      6875710.95
#Sta/Elev= 30
  4385.6  381.93  4458.9  376.13  4500.3  373.31  4593.1  363.23    4652  360.35
  4851.6  361.06  4887.4  358.83  4910.5  353.05    4917  353.06  4931.8  359.55
    4938  360.62  4982.4  360.44  4988.5  359.28  4992.9  355.64  4993.6  347.02
  4996.1  346.52  5018.6  347.02  5022.6     352  5036.6  360.08  5107.7   360.9
  5191.3  364.46  5219.5  365.62  5260.2  369.14  5321.2  372.73    5358  373.74
  5363.1   375.1  5382.2  375.03  5483.8  378.92  5534.6  383.15  5554.9  383.69
#Mann= 5 ,-1 , 0
  4385.6     .12       0  4458.9      .1       0  4993.6     .07       0
  5018.6      .1       0  5191.3     .12       0
Bank Sta=4993.6,5018.6
XS Rating Curve= 0 ,0
Exp/Cntr=0.3,0.1

Type RM Length L Ch R = 1 ,11131   ,765,765,765
BEGIN DESCRIPTION:
Williams Creek 17.0
END DESCRIPTION:
XS GIS Cut Line= 3
      2698876.01      6874260.99      2698195.35      6874931.43
      2697553.94      6875038.62
#Sta/Elev= 30
  4044.6  385.49  4228.4  374.74  4235.5  370.13  4242.6  372.33  4249.7   367.9
    4285  370.14  4369.9   360.6  4412.3  364.46    4484  359.98  4497.1  358.29
  4525.4  362.33  4663.7  358.97  4709.3  356.09  4794.2  359.87  4949.7  359.39
  4963.9  356.99  4965.5  345.97    4968  345.47  4990.5  345.97  5002.2  349.76
  5009.5  360.39  5121.8   358.7  5182.7  358.36  5202.1  357.14  5222.4  351.33
  5252.8  358.52  5269.2  358.97  5274.3  355.53  5344.1  362.36  5650.3  378.74
#Mann= 7 ,-1 , 0
  4044.6     .05       0    4484     .12       0  4663.7      .1       0
  4965.5     .07       0  4990.5      .1       0  5121.8     .12       0
  5182.7     .05       0
Bank Sta=4965.5,4990.5
XS Rating Curve= 0 ,0
Exp/Cntr=0.3,0.1

Type RM Length L Ch R = 1 ,10366   ,473,473,473
BEGIN DESCRIPTION:
Williams Creek 16.0
END DESCRIPTION:
XS GIS Cut Line= 3
      2698675.99        6874161.      2698275.96      6874281.19
      2697525.96      6874861.03
#Sta/Elev= 30
  4582.3  380.37  4655.4  375.84  4708.4  370.37  4741.4  369.33  4774.4  363.53
  4780.7  366.04  4977.9  358.64  4989.5  354.95  5003.1  353.79  5013.2  347.28
  5015.4  345.15  5017.9  344.65  5040.4  345.15  5042.4  354.26  5056.9  359.25
  5063.2  359.38  5156.5  357.79  5249.8  359.33  5264.3  357.54  5291.4  359.46
  5519.6  357.76  5577.6  359.15  5606.6  356.18  5616.3  348.89  5627.4  347.24
  5633.7  354.52  5641.9  358.95  5770.5  367.09  5791.3  370.51    5948  380.05
#Mann= 5 ,-1 , 0
  4582.3     .12       0  5013.2      .1       0  5015.4     .07       0
  5040.4      .1       0  5616.3     .12       0
Bank Sta=5015.4,5040.4
XS Rating Curve= 0 ,0
Exp/Cntr=0.3,0.1

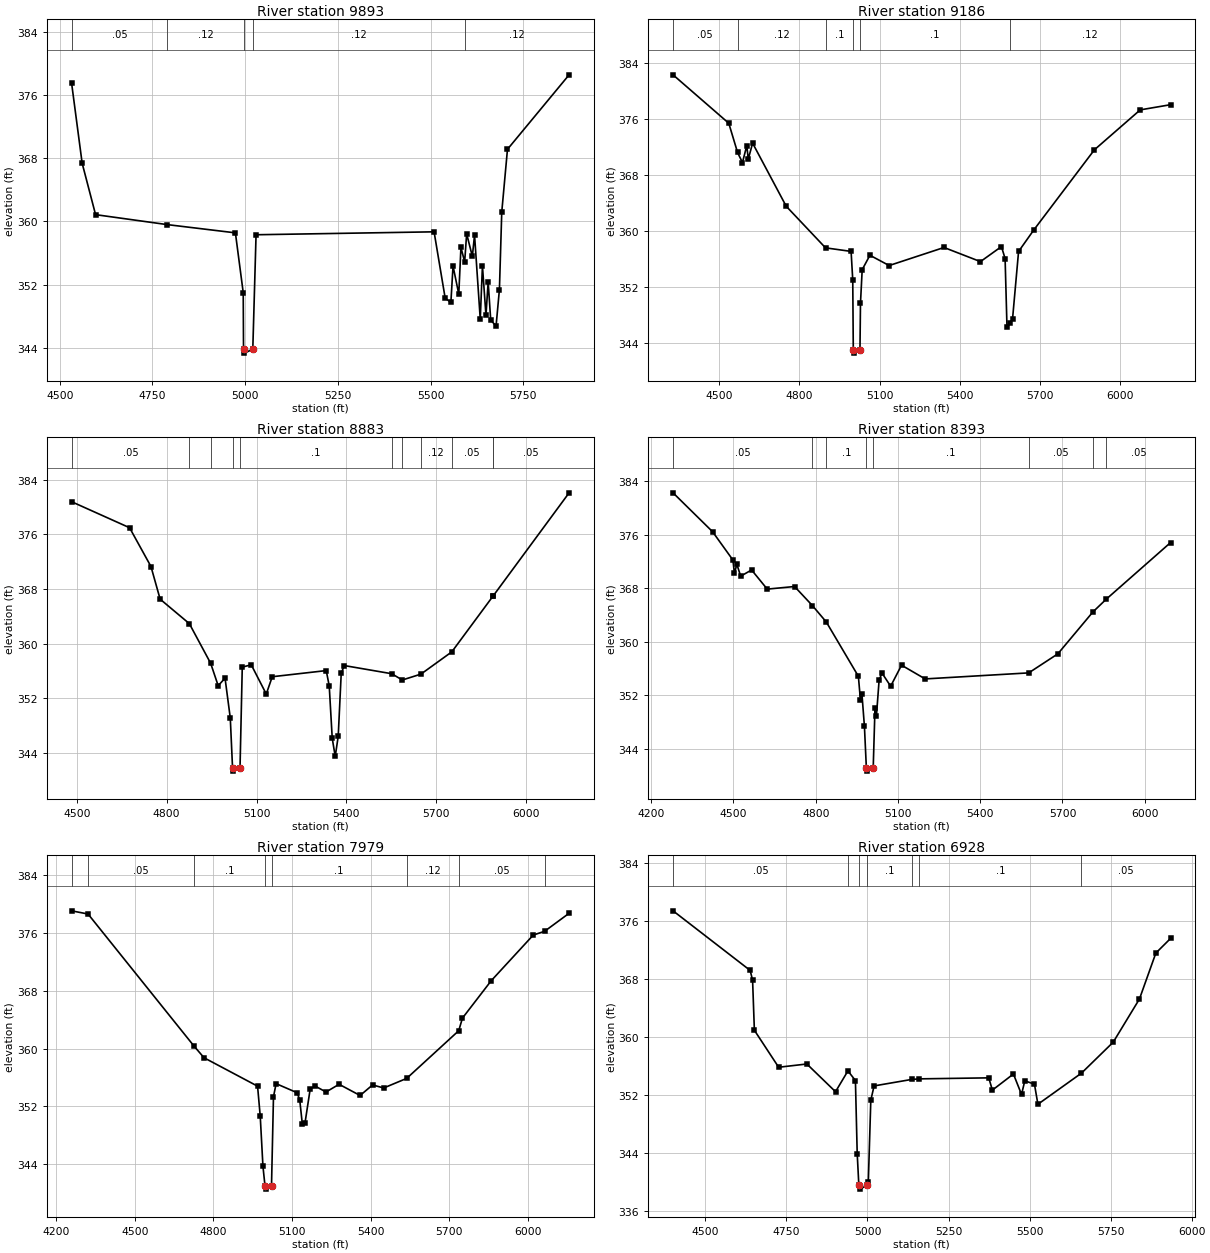
Type RM Length L Ch R = 1 ,9893    ,707,707,707
BEGIN DESCRIPTION:
Williams Creek 15.0
END DESCRIPTION:
XS GIS Cut Line= 3
      2698325.99        6873761.      2697934.15      6874017.08
      2697475.99      6874761.02
#Sta/Elev= 30
  4531.9  377.53  4560.5  367.36  4596.7  360.86  4790.2   359.6  4973.8  358.56
  4994.9     351  4995.7  343.86  4998.2  343.36  5020.7  343.86  5029.5  358.32
  5509.6  358.69  5539.5  350.31  5554.9  349.77  5560.7  354.37  5576.2  350.81
    5582  356.71  5592.1  354.89  5597.4  358.44  5612.8  355.59  5618.7  358.29
  5634.1  347.66    5640  354.38  5649.5  348.14  5655.4  352.37  5662.3  347.56
  5676.7  346.76  5685.8   351.4  5692.1  361.19  5707.5  369.12  5873.7  378.53
#Mann= 5 ,-1 , 0
  4531.9     .05       0  4790.2     .12       0  4995.7     .07       0
  5020.7     .12       0  5592.1     .12       0
Bank Sta=4995.7,5020.7
XS Rating Curve= 0 ,0
Exp/Cntr=0.3,0.1

Type RM Length L Ch R = 1 ,9186    ,303,303,303
BEGIN DESCRIPTION:
Williams Creek 14.0
END DESCRIPTION:
XS GIS Cut Line= 3
       2698169.4       6873142.5      2697583.47      6873459.34
      2696841.61      6874396.42
#Sta/Elev= 30
  4327.2  382.27  4535.7  375.35  4568.6  371.17  4586.9  369.73    4603  372.14
  4608.7  370.24  4624.9   372.5  4750.5  363.49  4897.6  357.54  4993.3  357.03
  4999.5  352.95  5001.5  342.99    5004  342.49  5026.5  342.99  5028.4  349.63
  5034.8  354.42  5063.7  356.48  5135.7  355.01  5340.9  357.59  5477.2  355.57
  5555.7  357.72  5569.4  356.01  5576.5  346.18  5588.2  346.79  5597.3  347.39
  5619.8  357.02  5675.9  360.05  5903.4  371.55  6074.9  377.26  6188.5     378
#Mann= 6 ,-1 , 0
  4327.2     .05       0  4568.6     .12       0  4897.6      .1       0
  5001.5     .07       0  5026.5      .1       0  5588.2     .12       0
Bank Sta=5001.5,5026.5
XS Rating Curve= 0 ,0
Exp/Cntr=0.3,0.1

Type RM Length L Ch R = 1 ,8883    ,490,490,490
BEGIN DESCRIPTION:
Williams Creek 13.0
END DESCRIPTION:
XS GIS Cut Line= 3
      2698025.95      6873111.01        2697526.        6873211.
      2696376.04        6873261.
#Sta/Elev= 30
  4482.5  380.81  4676.2  376.99  4747.6   371.3  4778.2  366.51  4875.7  362.92
  4946.9   357.1    4972  353.81  4994.9  354.92  5012.4  349.07  5019.9  341.78
  5022.4  341.28  5044.9  341.78  5052.4  356.54  5082.4  356.88  5132.5  352.59
  5152.5  355.13  5332.7  356.03  5342.7  353.78  5352.7   346.1  5362.7  343.43
  5372.7   346.4  5382.7  355.61  5392.7  356.77  5551.3  355.57  5586.6  354.65
  5648.7  355.51  5751.9  358.78  5888.6  366.91  5888.7  366.91  6143.4  382.11
#Mann= 11 ,-1 , 0
  4482.5     .05       0  4875.7     .12       0  4946.9      .1       0
  5019.9     .07       0  5044.9      .1       0  5551.3     .12       0
  5586.6      .1       0  5648.7     .12       0  5751.9     .05       0
  5888.6     .12       0  5888.7     .05       0
Bank Sta=5019.9,5044.9
XS Rating Curve= 0 ,0
Exp/Cntr=0.3,0.1

Type RM Length L Ch R = 1 ,8393    ,414,414,414
BEGIN DESCRIPTION:
Williams Creek 12.0
END DESCRIPTION:
XS GIS Cut Line= 3
      2698076.03      6873061.02      2697425.89      6872750.95
      2696382.77      6873081.39
#Sta/Elev= 30
  4279.7  382.22  4423.8  376.42  4498.1  372.19  4503.6  370.19  4512.4  371.57
  4526.3  369.78  4566.2  370.71  4623.2  367.85  4722.9  368.24  4787.8   365.4
  4838.7  362.94  4955.6  354.84  4963.1  351.32  4968.6  352.19  4977.7  347.35
  4984.7  341.19  4987.2  340.69  5009.7  341.19  5016.2  350.08  5021.4  348.92
  5031.3   354.3  5041.8  355.32  5073.3  353.36    5113   356.5  5199.2  354.45
  5576.8  355.35    5683  358.19  5810.8  364.44  5859.3  366.34  6094.2   374.8
#Mann= 8 ,-1 , 0
  4279.7     .05       0  4787.8     .12       0  4838.7      .1       0
  4984.7     .07       0  5009.7      .1       0  5576.8     .05       0
  5810.8     .12       0  5859.3     .05       0
Bank Sta=4984.7,5009.7
XS Rating Curve= 0 ,0
Exp/Cntr=0.3,0.1

Type RM Length L Ch R = 1 ,7979    ,1051,1051,1051
BEGIN DESCRIPTION:
Williams Creek 11.0
END DESCRIPTION:
XS GIS Cut Line= 3
      2698151.03      6872536.01      2697425.48        6872386.
      2696269.55      6872442.43
#Sta/Elev= 30
  4259.1   379.1    4322  378.66  4725.2  360.39  4764.6  358.72  4968.8  354.78
    4979   350.6  4989.3  343.67    4997     341  4999.5   340.5    5022     341
  5029.5  353.31  5039.5  355.13  5119.6  353.87  5129.6  352.89  5139.6   349.5
  5149.7  349.66  5169.7  354.42  5189.7  354.77  5229.8  353.97  5279.8  355.04
  5359.9  353.49  5407.6  354.95    5450  354.53  5537.8  355.86  5736.2  362.47
  5750.4  364.22  5860.5  369.42  6020.6  375.74  6063.8  376.26  6157.3  378.76
#Mann= 8 ,-1 , 0
  4259.1     .12       0    4322     .05       0  4725.2      .1       0
    4997     .07       0    5022      .1       0  5537.8     .12       0
  5736.2     .05       0  6063.8     .12       0
Bank Sta=4997,5022
XS Rating Curve= 0 ,0
Exp/Cntr=0.3,0.1

Type RM Length L Ch R = 1 ,6928    ,714,714,714
BEGIN DESCRIPTION:
Williams Creek 10.0
END DESCRIPTION:
XS GIS Cut Line= 3
      2698172.72      6872467.88      2697926.17       6871921.1
      2697000.98        6871786.
#Sta/Elev= 30
  4400.2  377.37  4638.1  369.16  4645.6  367.81  4651.1  360.92    4726  355.82
    4813  356.27  4901.4  352.45  4939.7  355.32  4962.8  353.99  4968.3  343.93
  4973.4  339.53  4975.9  339.03  4998.4  339.53  5002.6  340.07  5010.3  351.29
  5020.4  353.25  5136.1  354.14  5159.8  354.22  5374.1  354.36  5385.3  352.67
  5450.2  354.89  5475.2  352.07  5485.3  353.96  5515.1  353.48  5525.7  350.72
  5660.1  355.01  5758.1  359.28    5839  365.23  5889.5  371.55    5935  373.57
#Mann= 7 ,-1 , 0
  4400.2     .05       0  4939.7      .1       0  4973.4     .07       0
  4998.4      .1       0  5136.1     .12       0  5159.8      .1       0
  5660.1     .05       0
Bank Sta=4973.4,4998.4
XS Rating Curve= 0 ,0
Exp/Cntr=0.3,0.1