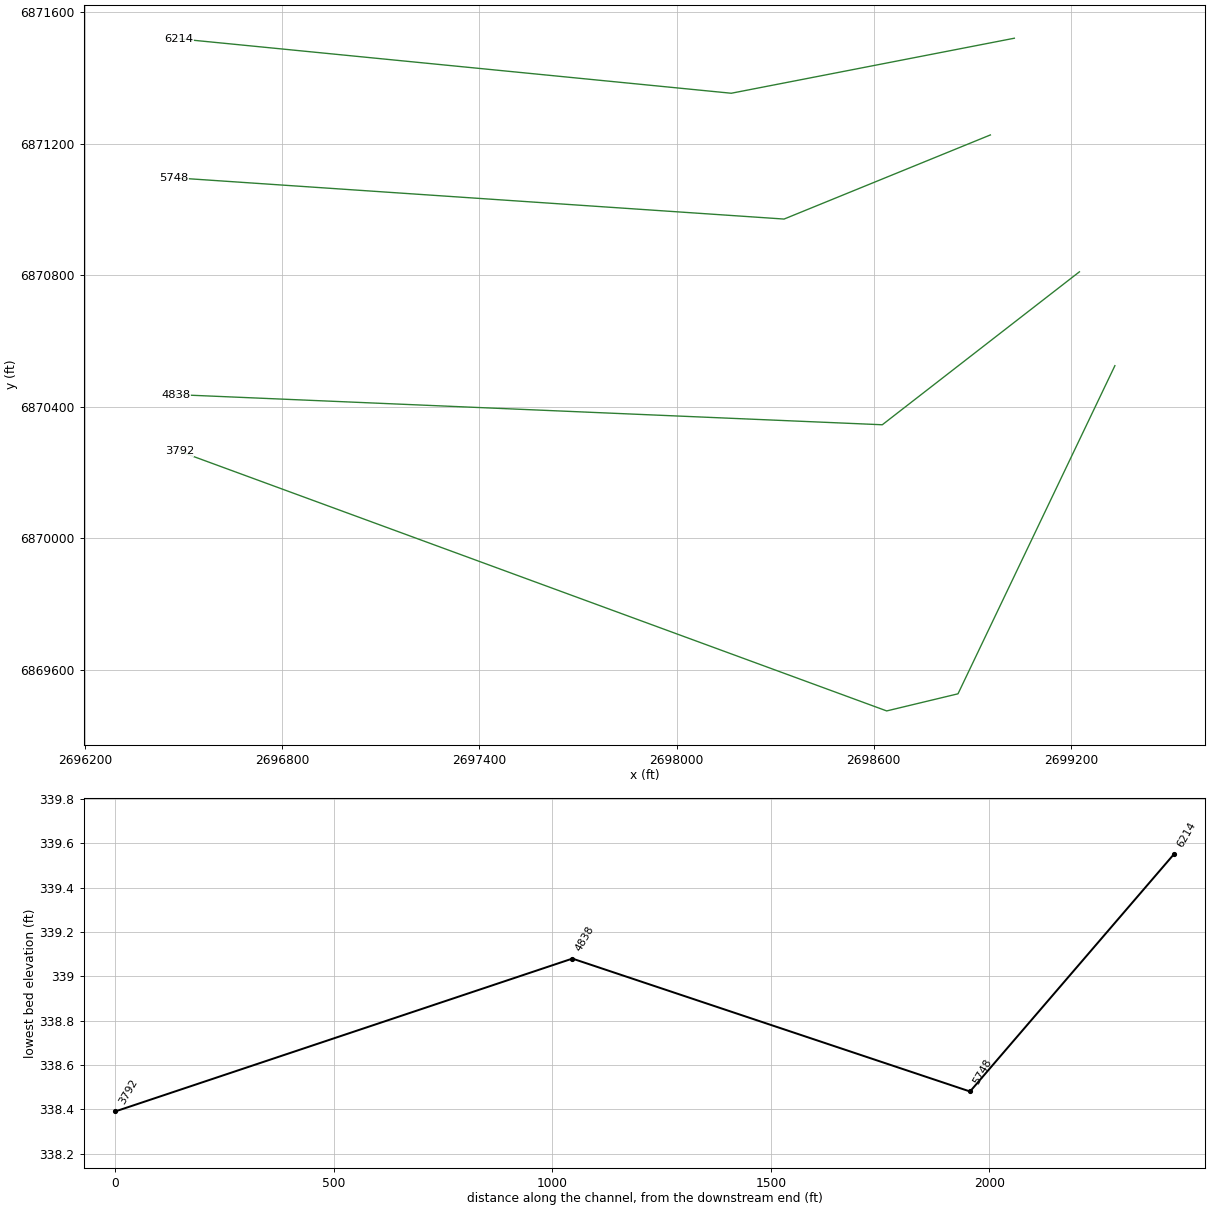
HEC-RAS study Williams Creek.prj: Williams Creek Base Level Engineering

--- Williams Creek.g01 (geometry) --- (continued)

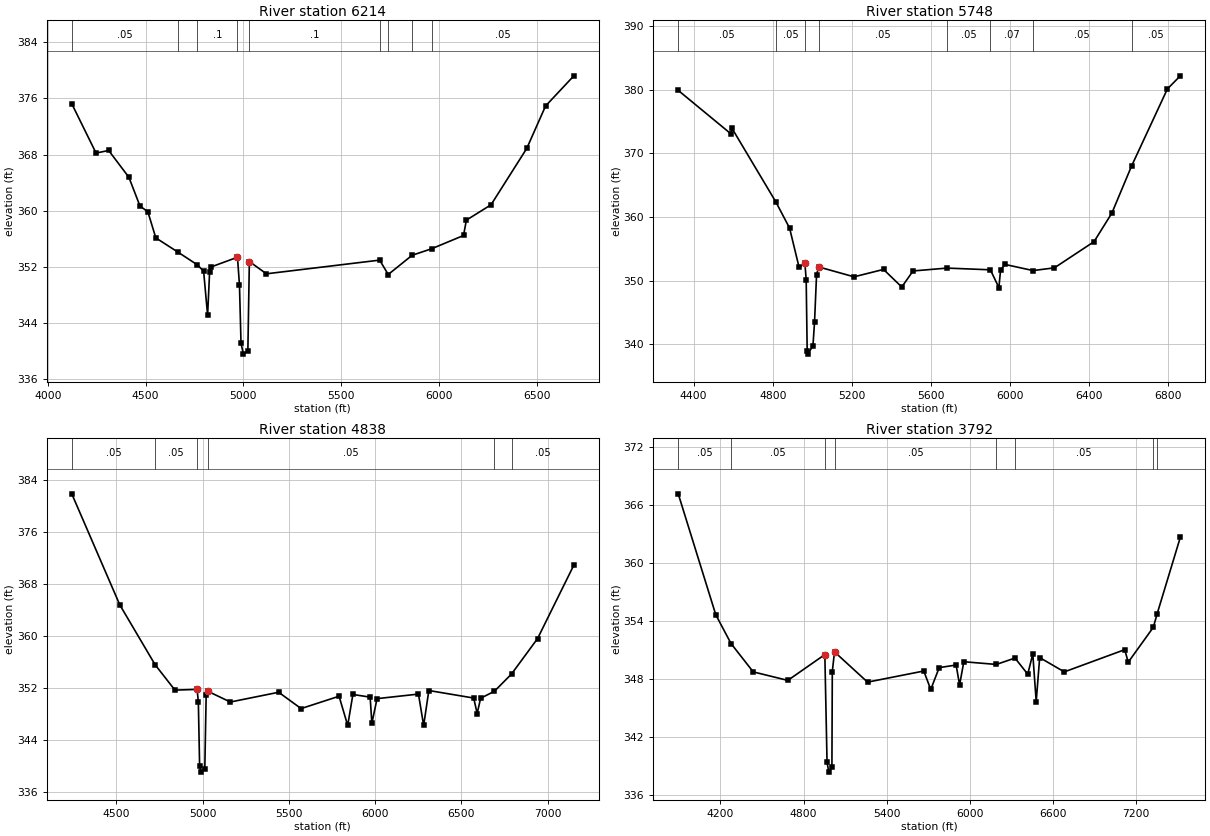
Type RM Length L Ch R = 1 ,6214    ,466,466,466
BEGIN DESCRIPTION:
Williams Creek 9.0
END DESCRIPTION:
XS GIS Cut Line= 3
      2699027.94      6871521.67      2698166.46      6871354.26
       2696484.5      6871519.93
#Sta/Elev= 30
  4122.4  375.24  4246.6  368.21  4311.1  368.58  4414.5  364.76  4471.2  360.66
  4511.5  359.84  4552.2  356.12  4664.3  354.11  4764.6  352.28  4796.7  351.37
  4817.1  345.08  4827.3  351.24    4833  351.96  4969.9  353.36  4980.1  349.37
    4988  341.07  5000.5  339.55    5023  340.05  5030.6  352.75  5117.9     351
    5697  352.95  5740.8   350.9    5863  353.64  5962.7  354.57  6125.9  356.46
  6140.5  358.65  6266.6  360.84  6449.2  368.87  6545.5  374.92  6690.1  379.22
#Mann= 9 ,-1 , 0
  4122.4     .05       0  4664.3     .12       0  4764.6      .1       0
  4969.9     .07       0  5030.6      .1       0    5697     .12       0
  5740.8      .1       0    5863     .12       0  5962.7     .05       0
Bank Sta=4969.9,5030.6
XS Rating Curve= 0 ,0
Exp/Cntr=0.3,0.1

Type RM Length L Ch R = 1 ,5748    ,910,910,910
BEGIN DESCRIPTION:
Williams Creek 8.0
END DESCRIPTION:
XS GIS Cut Line= 3
      2698955.01       6871227.4      2698327.16      6870971.48
      2696470.81      6871097.17
#Sta/Elev= 30
    4322  379.89  4588.1  373.08  4593.5  373.95  4816.3  362.34    4885  358.27
  4933.1   352.1  4962.5  352.72  4968.9  350.19    4974  338.98  4976.5  338.48
  5003.1  339.77  5011.2  343.52  5021.2  350.83  5031.2  352.18  5210.8  350.62
    5360  351.78  5452.2  349.02  5509.2  351.54  5680.9  351.99  5900.3  351.72
  5943.3  348.92  5951.7  351.67  5973.4  352.57  6115.9   351.6    6224  352.03
  6424.4  356.14  6514.6  360.63  6613.9     368  6795.3  380.12  6860.6  382.18
#Mann= 8 ,-1 , 0
    4322     .05       0  4816.3     .05       0  4962.5     .04       0
  5031.2     .05       0  5680.9     .05       0  5900.3     .07       0
  6115.9     .05       0  6613.9     .05       0
Bank Sta=4962.5,5031.2
XS Rating Curve= 0 ,0
Exp/Cntr=0.3,0.1

Type RM Length L Ch R = 1 ,4838    ,1046,1046,1046
BEGIN DESCRIPTION:
Williams Creek 7.0
END DESCRIPTION:
XS GIS Cut Line= 3
      2699225.97      6870810.98      2698626.11      6870345.64
      2696475.87      6870437.46
#Sta/Elev= 30
  4240.8  381.87  4519.2   364.8  4723.9   355.6  4839.1  351.69  4967.6   351.8
  4974.8  349.85  4982.1  340.06  4989.7  339.08  5012.2  339.58  5020.1  350.92
  5030.1  351.51  5160.3  349.86  5440.5  351.36  5570.6  348.85  5790.8  350.75
  5840.9  346.25  5870.9  351.02    5971  350.61    5981  346.59    6011  350.38
  6251.2  351.08  6281.3  346.25  6311.3  351.63  6571.5  350.47  6591.6  348.09
  6611.6  350.44  6691.5  351.51  6790.7  354.16  6941.9  359.62  7152.2  370.91
#Mann= 6 ,-1 , 0
  4240.8     .05       0  4723.9     .05       0  4967.6     .04       0
  5030.1     .05       0  6691.5     .05       0  6790.7     .05       0
Bank Sta=4967.6,5030.1
XS Rating Curve= 0 ,0
Exp/Cntr=0.3,0.1

Type RM Length L Ch R = 1 ,3792    ,0,0,0
BEGIN DESCRIPTION:
Mapping XS 54ea3a05
END DESCRIPTION:
XS GIS Cut Line= 4
      2699333.92      6870525.37      2698856.48      6869527.09
      2698639.46        6869475.      2696486.67      6870264.94
#Sta/Elev= 30
  3896.1  367.18    4167  354.67  4277.1  351.69  4437.2  348.76  4686.7  347.88
    4954  350.55  4969.8  339.44  4982.5  338.39    5005  338.89  5007.8  348.79
  5023.7  350.83  5262.3   347.7  5667.9  348.85  5718.2  346.94  5779.2   349.2
  5901.2  349.47  5926.3  347.41  5956.8  349.81  6191.4  349.53  6326.1  350.19
  6418.1  348.52  6454.5  350.62  6479.1  345.69  6504.2  350.24  6681.9  348.76
    7118  351.06  7143.1  349.76  7324.2  353.37  7351.2  354.74    7519  362.68
#Mann= 8 ,-1 , 0
  3896.1     .05       0  4277.1     .05       0    4954     .04       0
  5023.7     .05       0  6191.4     .05       0  6326.1     .05       0
  7324.2     .12       0  7351.2     .05       0
Bank Sta=4954,5023.7
XS Rating Curve= 0 ,0
Exp/Cntr=0.3,0.1

Chan Stop Cuts=-1
Use User Specified Reach Order=0
Composite Channel Slope=5