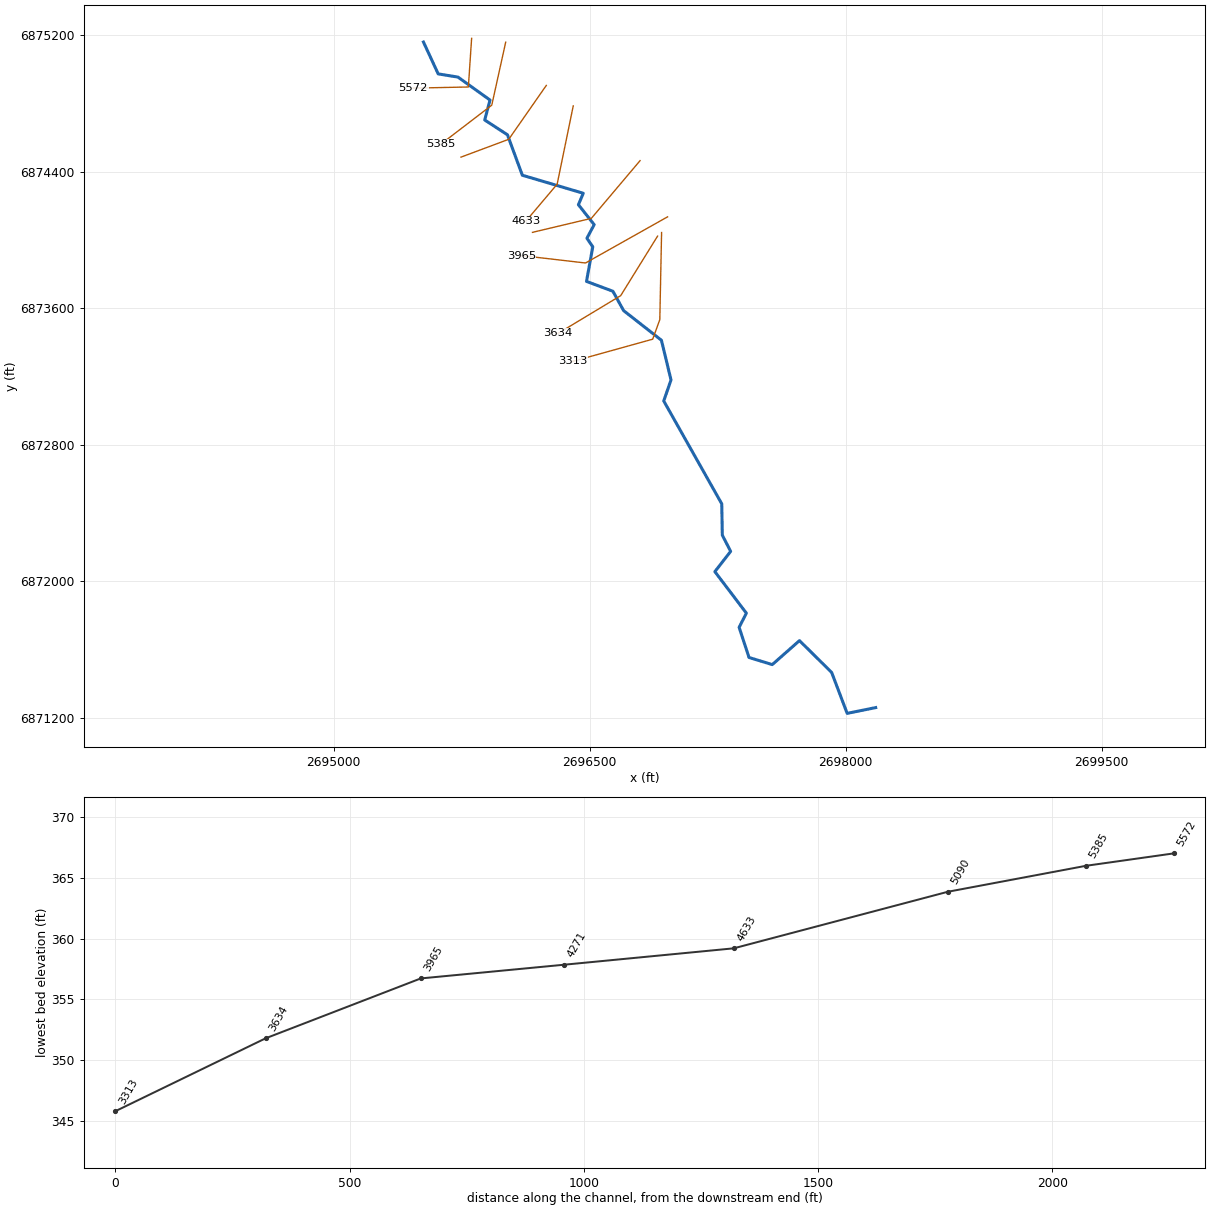
--- Williams T1.prj (project) ---

Proj Title=Williams T1 Base Level Engineering
Current Plan=p01
Default Exp/Contr=0.3,0.1
English Units
Geom File=g01
Flow File=f01
Plan File=p01
BEGIN DESCRIPTION:
Williams T1
END DESCRIPTION:

--- Williams T1.p01 (plan) ---

Plan Title=Multiple Run
Short Identifier=Multiple
Geom File=g01
Flow File=f01
Subcritical Flow
K Sum by GR= 0
Std Step Tol= 0.01
Critical Tol= 0.01
Num of Std Step Trials= 20
Max Error Tol= 0.3
Flow Tol Ratio= 0.001
Split Flow NTrial= 30
Split Flow Tol= 0.02
Split Flow Ratio= 0.02
Log Output Level= 0
Friction Slope Method= 1
Unsteady Friction Slope Method= 2
Unsteady Bridges Friction Slope Method= 1
Parabolic Critical Depth
Global Vel Dist=  1 , 1 , 1
Global Log Level= 0
CheckData=True
Encroach Param= -1, 0, 0, 0
BEGIN DESCRIPTION:
Multiple Run
END DESCRIPTION:

--- Williams T1.f01 (steady flow) ---

Flow Title=Multiple
Number of Profiles=7
Profile Names=10-year,25-year,50-year,1pct_min,100-year,1pct_plu,500-year
River Rch & RM= Williams T1,Reach-1,5572
     340     438     513     299     596    1189     803
Boundary for River Rch & Prof#=Williams T1,Reach-1,1
Up Type=0
Dn Type=3
Dn Slope=0.005
Boundary for River Rch & Prof#=Williams T1,Reach-1,2
Up Type=0
Dn Type=3
Dn Slope=0.005
Boundary for River Rch & Prof#=Williams T1,Reach-1,3
Up Type=0
Dn Type=3
Dn Slope=0.005
Boundary for River Rch & Prof#=Williams T1,Reach-1,4
Up Type=0
Dn Type=3
Dn Slope=0.005
Boundary for River Rch & Prof#=Williams T1,Reach-1,5
Up Type=0
Dn Type=3
Dn Slope=0.005
Boundary for River Rch & Prof#=Williams T1,Reach-1,6
Up Type=0
Dn Type=3
Dn Slope=0.005
Boundary for River Rch & Prof#=Williams T1,Reach-1,7
Up Type=0
Dn Type=3
Dn Slope=0.005

--- Williams T1.g01 (geometry) ---

Geom Title=Existing Conditions

River Reach=Williams T1,Reach-1
Reach XY= 30
      2695526.00      6875161.00      2695612.34      6874974.26
      2695728.42      6874955.46      2695915.93      6874820.99
      2695885.03      6874703.99      2696018.25      6874617.45
      2696105.45      6874380.44      2696462.52      6874274.75
      2696434.02      6874207.68      2696526.32      6874090.84
      2696483.83      6874010.92      2696518.21      6873961.10
      2696481.34      6873758.27      2696636.10      6873700.61
      2696698.86      6873587.17      2696920.53      6873413.45
      2696976.58      6873181.04      2696934.04      6873057.68
      2697273.93      6872455.14      2697277.24      6872271.50
      2697326.04      6872176.34      2697233.61      6872057.67
      2697418.17      6871814.40      2697375.79      6871731.21
      2697433.73      6871554.49      2697570.10      6871512.96
      2697729.33      6871653.41      2697917.86      6871467.06
      2698008.84      6871227.09      2698176.00      6871261.00

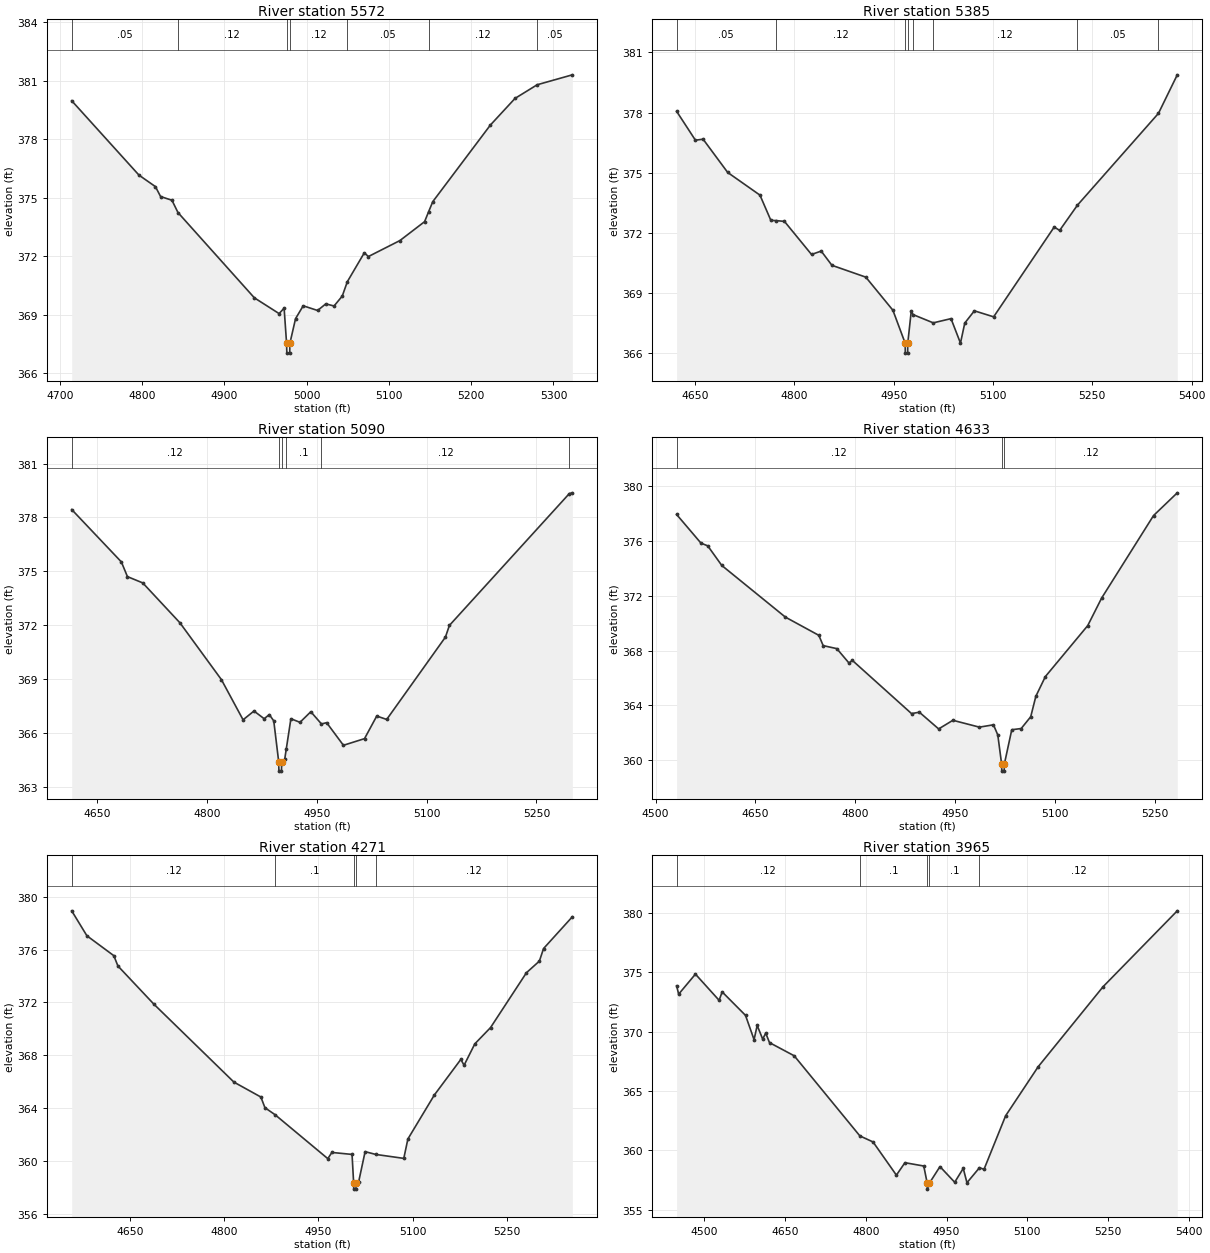
Type RM Length L Ch R = 1,5572,187,187,187
BEGIN DESCRIPTION:
Williams T1 7.0
END DESCRIPTION:
XS GIS Cut Line= 3
      2695808.29      6875182.60      2695789.24      6874897.44
      2695466.31      6874890.96
#Sta/Elev= 30
  4714.2  379.98  4796.0  376.16  4816.0  375.57  4822.3  375.06  4836.1  374.87
  4843.4  374.24  4936.3  369.86  4966.4  369.05  4972.5  369.33  4975.5  367.52
  4975.8  367.02  4979.3  367.02  4979.5  367.52  4986.4  368.79  4995.7  369.45
  5013.2  369.21  5023.2  369.55  5033.2  369.44  5043.2  369.95  5049.4  370.69
  5070.0  372.17  5075.0  371.98  5113.3  372.80  5143.3  373.77  5148.3  374.29
  5153.3  374.80  5223.3  378.73  5253.3  380.10  5280.2  380.80  5323.0  381.31
#Mann=7,-1,0
  4714.2    0.05       0  4843.4    0.12       0  4975.5    0.07       0
  4979.5    0.12       0  5049.4    0.05       0  5148.3    0.12       0
  5280.2    0.05       0
Bank Sta=4975.5,4979.5
Exp/Cntr=0.3,0.1

Type RM Length L Ch R = 1,5385,295,295,295
BEGIN DESCRIPTION:
Williams T1 6.0
END DESCRIPTION:
XS GIS Cut Line= 3
      2696007.94      6875160.03      2695926.36      6874790.94
      2695625.98      6874560.98
#Sta/Elev= 30
  4622.0  378.06  4650.4  376.62  4662.0  376.67  4699.2  375.01  4747.9  373.88
  4764.4  372.62  4772.1  372.61  4784.9  372.57  4825.8  370.92  4840.4  371.09
  4856.6  370.38  4907.8  369.79  4948.7  368.14  4967.2  366.50  4967.5  366.00
  4971.0  366.00  4971.2  366.50  4976.4  368.08  4979.3  367.92  5009.7  367.51
  5036.5  367.72  5050.8  366.50  5057.3  367.50  5071.8  368.11  5100.9  367.81
  5192.4  372.29  5200.6  372.12  5227.5  373.38  5349.9  377.96  5378.3  379.88
#Mann=8,-1,0
  4622.0    0.05       0  4772.1    0.12       0  4967.2    0.07       0
  4971.2    0.12       0  4979.3     0.1       0  5009.7    0.12       0
  5227.5    0.05       0  5349.9    0.12       0
Bank Sta=4967.2,4971.2
Exp/Cntr=0.3,0.1

Type RM Length L Ch R = 1,5090,457,457,457
BEGIN DESCRIPTION:
Williams T1 5.0
END DESCRIPTION:
XS GIS Cut Line= 3
      2696245.80      6874906.60      2696025.92      6874591.05
      2695745.81      6874486.45
#Sta/Elev= 30
  4615.4  378.44  4683.2  375.52  4691.5  374.70  4712.4  374.35  4763.1  372.13
  4819.8  368.96  4849.4  366.72  4864.3  367.21  4878.2  366.78  4885.2  367.01
  4891.3  366.66  4898.1  364.36  4898.3  363.86  4901.8  363.86  4902.1  364.36
  4906.2  364.51  4908.4  365.10  4914.7  366.78  4927.1  366.58  4941.9  367.17
  4956.4  366.49  4963.5  366.56  4986.4  365.30  5015.2  365.67  5031.9  366.93
  5045.5  366.74  5125.7  371.33  5131.1  371.98  5294.9  379.33  5299.0  379.37
#Mann=6,-1,0
  4615.4    0.12       0  4898.1    0.07       0  4902.1    0.12       0
  4908.4     0.1       0  4956.4    0.12       0  5294.9    0.05       0
Bank Sta=4898.1,4902.1
Exp/Cntr=0.3,0.1

Type RM Length L Ch R = 1,4633,362,362,362
BEGIN DESCRIPTION:
Williams T1 4.0
END DESCRIPTION:
XS GIS Cut Line= 3
      2696403.78      6874786.82      2696309.44      6874327.92
      2696125.99      6874110.99
#Sta/Elev= 30
  4531.5  377.93  4568.1  375.84  4578.3  375.64  4599.4  374.21  4695.0  370.44
  4745.3  369.11  4751.8  368.36  4772.3  368.14  4790.6  367.09  4795.7  367.28
  4884.6  363.40  4896.4  363.50  4925.4  362.28  4946.8  362.91  4986.6  362.41
  5007.8  362.58  5014.3  361.84  5020.1  359.70  5020.3  359.20  5023.8  359.20
  5024.1  359.70  5035.3  362.22  5049.5  362.31  5063.8  363.17  5071.5  364.66
  5085.8  366.10  5149.5  369.82  5170.4  371.83  5248.4  377.85  5284.1  379.51
#Mann=3,-1,0
  4531.5    0.12       0  5020.1    0.07       0  5024.1    0.12       0
Bank Sta=5020.1,5024.1
Exp/Cntr=0.3,0.1

Type RM Length L Ch R = 1,4271,306,306,306
BEGIN DESCRIPTION:
Williams T1 3.0
END DESCRIPTION:
XS GIS Cut Line= 3
      2696795.34      6874466.03      2696509.70      6874127.67
      2696164.91      6874045.73
#Sta/Elev= 30
  4557.2  378.94  4581.4  377.05  4624.3  375.54  4630.8  374.76  4688.0  371.87
  4815.5  365.96  4858.4  364.83  4864.9  364.02  4881.0  363.49  4965.0  360.16
  4971.5  360.63  5003.6  360.48  5006.1  358.35  5006.3  357.85  5009.8  357.85
  5010.1  358.35  5014.1  358.40  5024.4  360.69  5041.3  360.48  5086.0  360.18
  5092.5  361.65  5134.6  364.98  5176.8  367.68  5182.0  367.24  5199.1  368.86
  5224.1  370.09  5281.3  374.25  5301.9  375.13  5308.5  376.08  5354.4  378.49
#Mann=5,-1,0
  4557.2    0.12       0  4881.0     0.1       0  5006.1    0.07       0
  5010.1     0.1       0  5041.3    0.12       0
Bank Sta=5006.1,5010.1
Exp/Cntr=0.3,0.1

Type RM Length L Ch R = 1,3965,331,331,331
BEGIN DESCRIPTION:
Williams T1 2.0
END DESCRIPTION:
XS GIS Cut Line= 3
      2696956.52      6874136.60      2696475.53      6873866.17
      2696099.06      6873909.84
#Sta/Elev= 30
  4448.2  373.88  4452.0  373.17  4483.2  374.86  4527.2  372.65  4532.9  373.36
  4576.3  371.38  4592.2  369.33  4598.0  370.53  4608.2  369.38  4613.9  369.88
  4620.9  369.08  4666.8  367.97  4788.9  361.21  4813.4  360.70  4856.8  357.90
  4872.7  358.95  4907.7  358.67  4914.1  357.22  4914.3  356.72  4918.1  357.22
  4937.8  358.62  4965.2  357.30  4981.1  358.47  4988.0  357.26  5011.3  358.53
  5019.7  358.39  5059.9  362.91  5120.3  367.04  5241.1  373.80  5379.0  380.20
#Mann=5,-1,0
  4448.2    0.12       0  4788.9     0.1       0  4914.1    0.07       0
  4918.1     0.1       0  5011.3    0.12       0
Bank Sta=4914.1,4918.1
Exp/Cntr=0.3,0.1

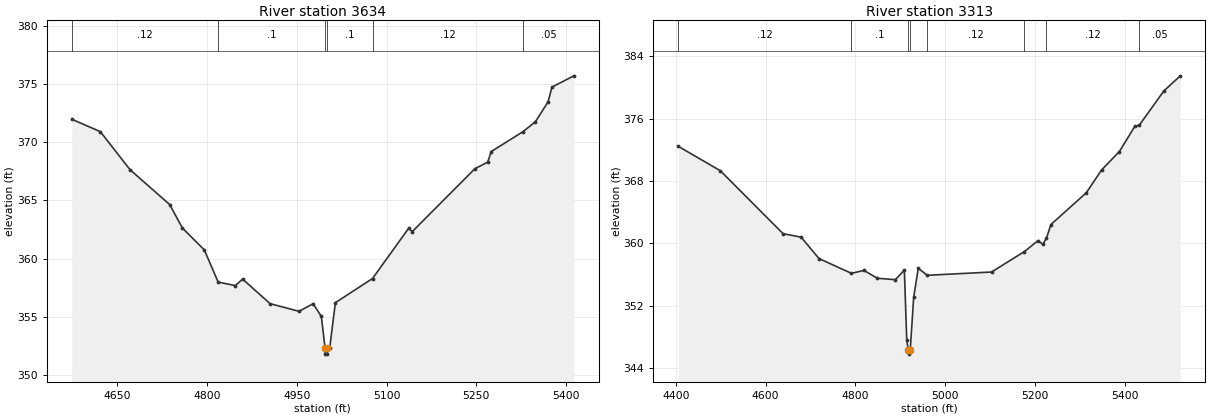
Type RM Length L Ch R = 1,3634,321,321,321
BEGIN DESCRIPTION:
Mapping XS 9d06185a
END DESCRIPTION:
XS GIS Cut Line= 3
      2696897.94      6874023.83      2696681.82      6873674.90
      2696314.62      6873453.54
#Sta/Elev= 30
  4573.8  371.98  4621.6  370.91  4671.2  367.64  4737.4  364.65  4758.7  362.63
  4795.3  360.75  4818.5  357.98  4847.3  357.68  4859.4  358.24  4905.2  356.13
  4953.6  355.47  4977.1  356.12  4991.0  355.03  4997.2  352.29  4997.4  351.79
  5000.9  351.79  5001.2  352.29  5005.0  352.35  5014.4  356.21  5076.5  358.29
  5137.0  362.61  5142.9  362.32  5247.7  367.73  5269.0  368.29  5274.9  369.20
  5327.7  370.90  5348.7  371.76  5370.0  373.48  5376.4  374.74  5413.0  375.71
#Mann=6,-1,0
  4573.8    0.12       0  4818.5     0.1       0  4997.2    0.07       0
  5001.2     0.1       0  5076.5    0.12       0  5327.7    0.05       0
Bank Sta=4997.2,5001.2
Exp/Cntr=0.3,0.1

Type RM Length L Ch R = 1,3313,0,0,0
BEGIN DESCRIPTION:
Mapping XS 0ff7c07c
END DESCRIPTION:
XS GIS Cut Line= 4
      2696921.40      6874044.66      2696910.98      6873534.28
      2696869.32      6873419.70      2696400.77      6873289.54
#Sta/Elev= 30
  4405.4  372.46  4499.1  369.33  4639.1  361.24  4679.1  360.80  4719.1  358.05
  4791.4  356.15  4819.1  356.53  4849.2  355.52  4889.2  355.34  4909.2  356.56
  4914.6  347.56  4918.3  346.28  4918.5  345.78  4922.3  346.28  4930.0  353.07
  4940.2  356.81  4960.0  355.90  5103.5  356.32  5176.8  358.95  5207.3  360.36
  5217.7  359.87  5225.9  360.67  5235.8  362.42  5314.7  366.50  5349.0  369.45
  5388.4  371.79  5422.7  375.02  5432.4  375.15  5487.5  379.57  5524.1  381.51
#Mann=8,-1,0
  4405.4    0.12       0  4791.4     0.1       0  4918.3    0.07       0
  4922.3     0.1       0  4960.0    0.12       0  5176.8    0.05       0
  5225.9    0.12       0  5432.4    0.05       0
Bank Sta=4918.3,4922.3
Exp/Cntr=0.3,0.1

Chan Stop Cuts=-1