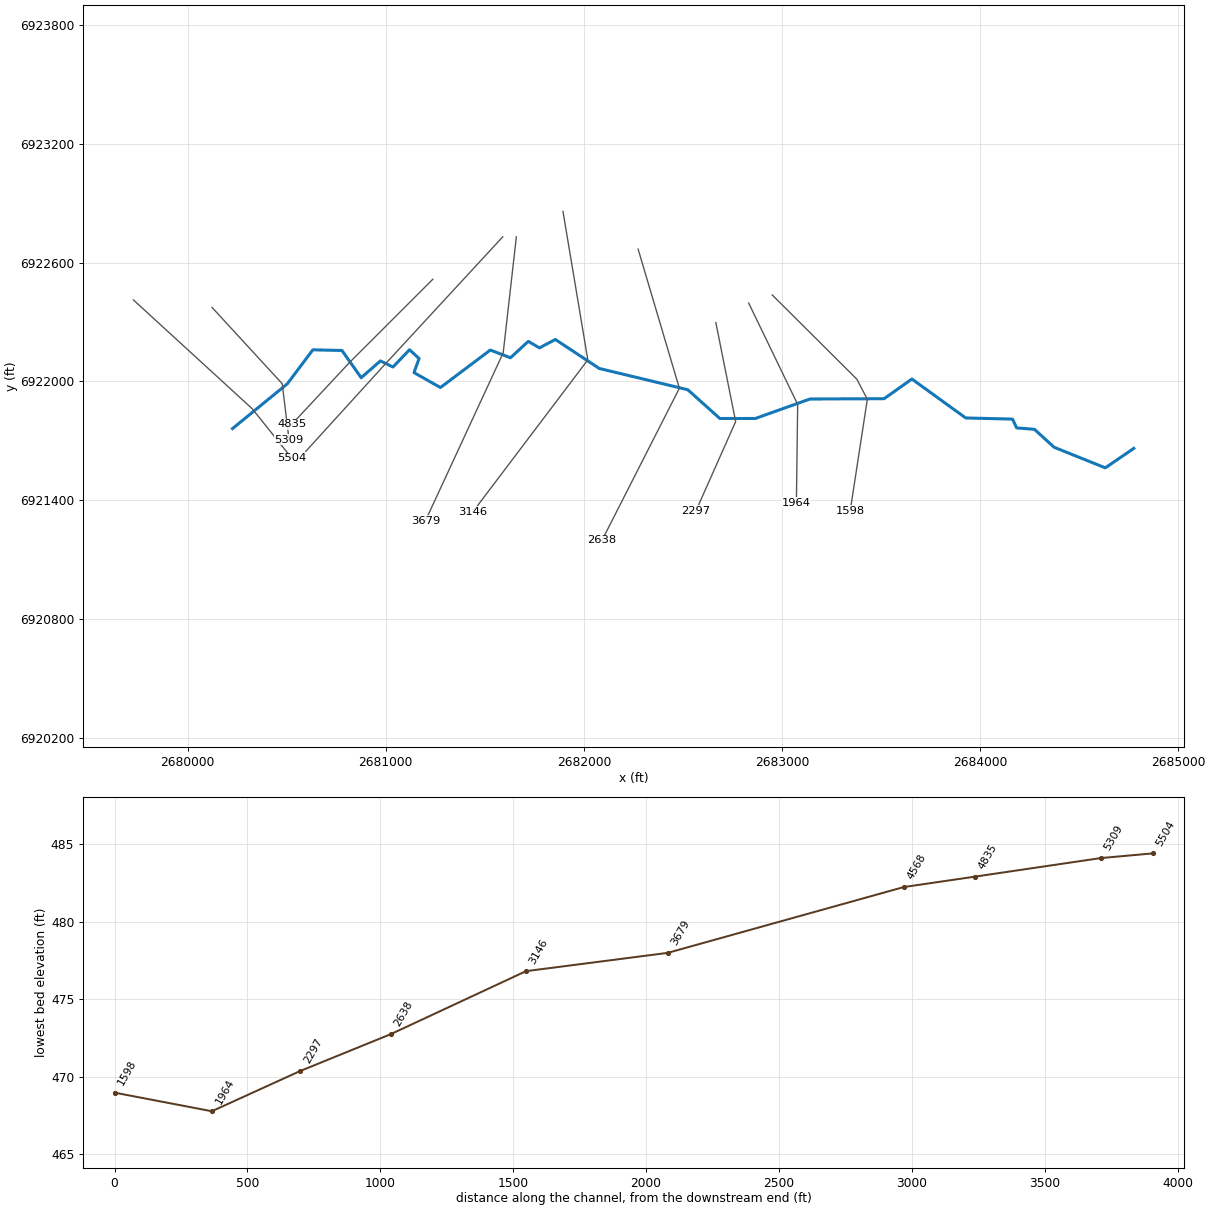
--- Williams T10.prj (project) ---

Proj Title=Williams T10 Base Level Engineering
Current Plan=p01
Default Exp/Contr=0.3,0.1
English Units
Geom File=g01
Flow File=f01
Plan File=p01
BEGIN DESCRIPTION:
Williams T10
END DESCRIPTION:

--- Williams T10.p01 (plan) ---

Plan Title=Multiple Run
Short Identifier=Multiple
Geom File=g01
Flow File=f01
Subcritical Flow
K Sum by GR= 0
Std Step Tol= 0.01
Critical Tol= 0.01
Num of Std Step Trials= 20
Max Error Tol= 0.3
Flow Tol Ratio= 0.001
Split Flow NTrial= 30
Split Flow Tol= 0.02
Split Flow Ratio= 0.02
Log Output Level= 0
Friction Slope Method= 1
Unsteady Friction Slope Method= 2
Unsteady Bridges Friction Slope Method= 1
Parabolic Critical Depth
Global Vel Dist=  1 , 1 , 1
Global Log Level= 0
CheckData=True
Encroach Param= -1, 0, 0, 0
BEGIN DESCRIPTION:
Multiple Run
END DESCRIPTION:

--- Williams T10.f01 (steady flow) ---

Flow Title=Multiple
Number of Profiles=7
Profile Names=10-year,25-year,50-year,1pct_min,100-year,1pct_plu,500-year
River Rch & RM= Williams T10,Reach-1,5504
     483     640     765     454     905    1806    1267
River Rch & RM= Williams T10,Reach-1,2638
     717     971    1178     709    1414    2821    2036
Boundary for River Rch & Prof#=Williams T10,Reach-1,1
Up Type=0
Dn Type=3
Dn Slope=0.005
Boundary for River Rch & Prof#=Williams T10,Reach-1,2
Up Type=0
Dn Type=3
Dn Slope=0.005
Boundary for River Rch & Prof#=Williams T10,Reach-1,3
Up Type=0
Dn Type=3
Dn Slope=0.005
Boundary for River Rch & Prof#=Williams T10,Reach-1,4
Up Type=0
Dn Type=3
Dn Slope=0.005
Boundary for River Rch & Prof#=Williams T10,Reach-1,5
Up Type=0
Dn Type=3
Dn Slope=0.005
Boundary for River Rch & Prof#=Williams T10,Reach-1,6
Up Type=0
Dn Type=3
Dn Slope=0.005
Boundary for River Rch & Prof#=Williams T10,Reach-1,7
Up Type=0
Dn Type=3
Dn Slope=0.005

--- Williams T10.g01 (geometry) ---

Geom Title=Existing Conditions

River Reach=Williams T10,Reach-1
Reach XY= 30
      2680226.00      6921761.00      2680502.88      6921987.27
      2680631.68      6922159.03      2680778.70      6922155.65
      2680875.79      6922018.01      2680972.67      6922102.96
      2681036.30      6922072.18      2681119.96      6922159.57
      2681168.06      6922114.66      2681142.24      6922043.96
      2681276.00      6921968.50      2681527.65      6922157.84
      2681629.41      6922118.85      2681719.33      6922201.67
      2681775.91      6922168.84      2681855.84      6922211.32
      2682077.58      6922064.83      2682524.50      6921957.39
      2682686.43      6921812.05      2682865.49      6921812.22
      2683141.22      6921910.48      2683515.56      6921912.06
      2683655.84      6922011.47      2683927.55      6921814.75
      2684164.03      6921809.04      2684184.50      6921764.56
      2684274.43      6921757.35      2684373.71      6921666.85
      2684632.13      6921562.77      2684776.00      6921661.00

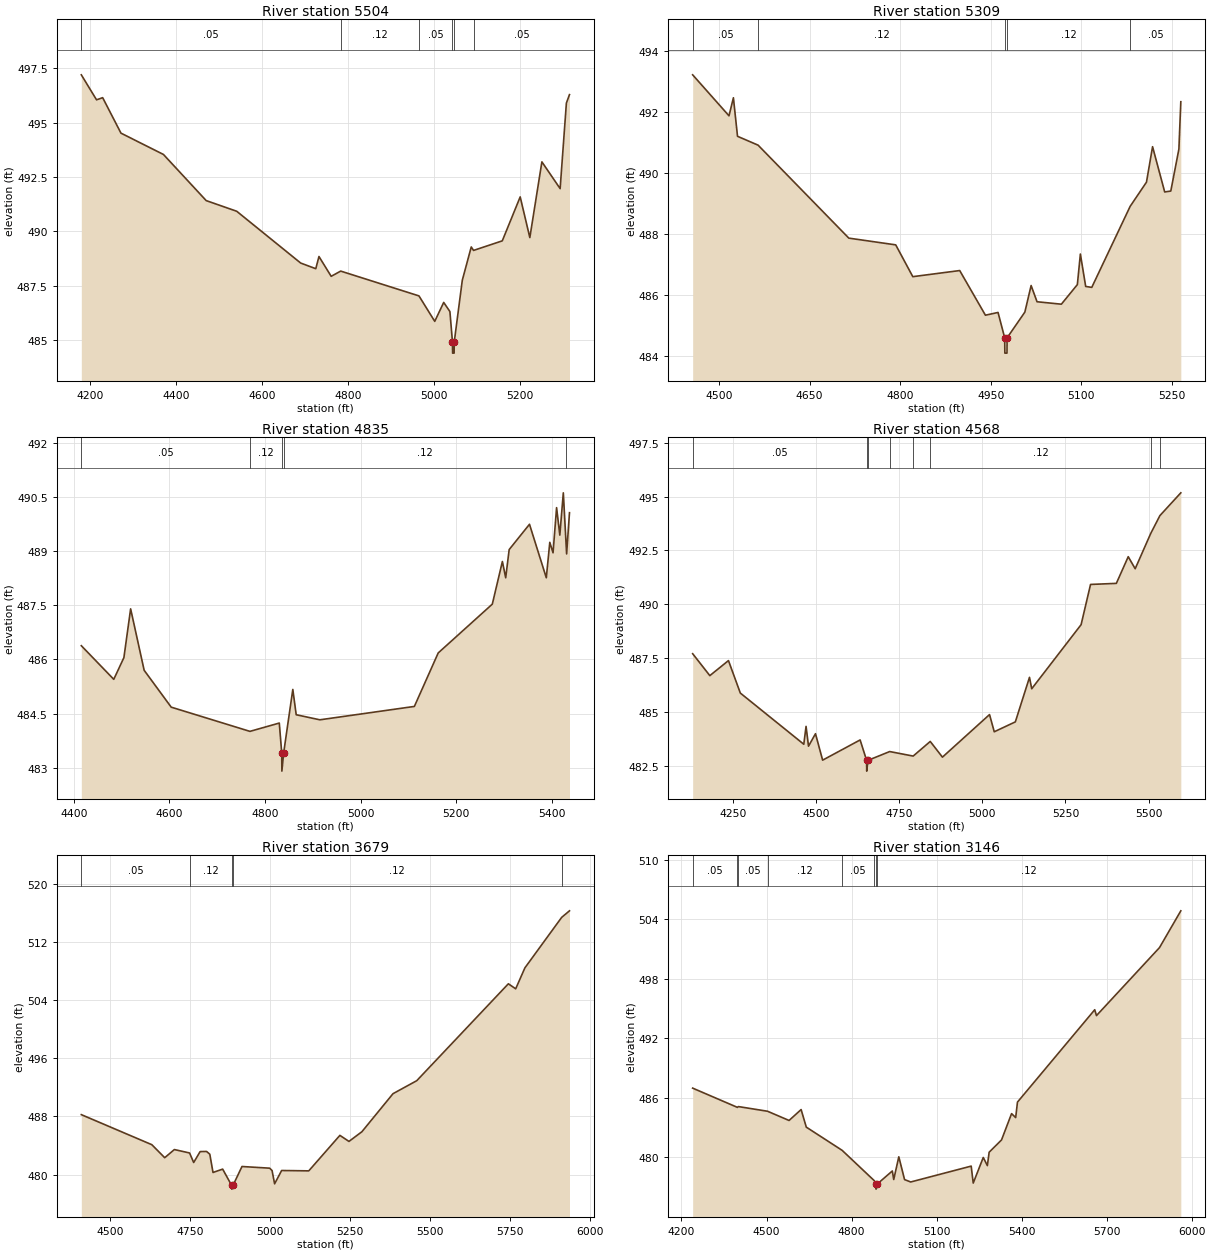
Type RM Length L Ch R = 1,5504,195,195,195
BEGIN DESCRIPTION:
Williams T10 6.0
END DESCRIPTION:
XS GIS Cut Line= 3
      2679726.03      6922410.97      2680326.00      6921861.00
      2680526.03      6921610.97
#Sta/Elev= 30
  4180.7  497.20  4216.1  496.05  4230.3  496.15  4272.8  494.52  4371.5  493.54
  4470.8  491.42  4541.7  490.93  4690.3  488.55  4725.4  488.29  4732.8  488.85
  4761.2  487.94  4783.3  488.18  4965.1  487.04  5001.8  485.87  5022.6  486.74
  5037.0  486.32  5043.0  484.91  5043.3  484.41  5046.8  484.41  5047.0  484.91
  5065.8  487.76  5086.6  489.29  5091.9  489.13  5158.7  489.57  5200.3  491.59
  5222.7  489.72  5250.7  493.20  5293.1  491.97  5307.6  495.90  5314.8  496.29
#Mann=6,-1,0
  4180.7    0.05       0  4783.3    0.12       0  4965.1    0.05       0
  5043.0    0.03       0  5047.0    0.05       0  5091.9    0.05       0
Bank Sta=5043,5047
Exp/Cntr=0.3,0.1

Type RM Length L Ch R = 1,5309,474,474,474
BEGIN DESCRIPTION:
Mapping XS 417dbfcb
END DESCRIPTION:
XS GIS Cut Line= 3
      2680122.91      6922373.14      2680477.05      6921987.75
      2680511.59      6921704.54
#Sta/Elev= 30
  4456.3  493.21  4516.5  491.87  4523.8  492.46  4530.6  491.20  4564.7  490.91
  4715.0  487.87  4792.7  487.65  4821.0  486.61  4898.7  486.81  4941.3  485.35
  4962.2  485.44  4973.2  484.61  4973.5  484.11  4977.0  484.11  4977.2  484.61
  5006.6  485.45  5017.0  486.32  5026.8  485.79  5067.1  485.71  5093.6  486.35
  5098.6  487.35  5107.4  486.29  5117.5  486.26  5181.1  488.91  5208.1  489.70
  5218.2  490.86  5238.3  489.38  5248.4  489.41  5261.8  490.78  5265.0  492.33
#Mann=5,-1,0
  4456.3    0.05       0  4564.7    0.12       0  4973.2    0.07       0
  4977.2    0.12       0  5181.1    0.05       0
Bank Sta=4973.2,4977.2
Exp/Cntr=0.3,0.1

Type RM Length L Ch R = 1,4835,267,267,267
BEGIN DESCRIPTION:
Mapping XS ac0033a0
END DESCRIPTION:
XS GIS Cut Line= 3
      2681237.45      6922515.52      2680813.85      6922091.92
      2680525.67      6921782.91
#Sta/Elev= 30
  4415.5  486.38  4483.4  485.45  4504.6  486.05  4518.7  487.40  4547.0  485.70
  4603.6  484.68  4768.4  484.01  4829.8  484.24  4834.9  483.41  4835.2  482.91
  4838.9  483.41  4858.1  485.17  4865.2  484.47  4914.7  484.33  5112.5  484.70
  5162.4  486.18  5275.6  487.53  5296.7  488.71  5303.6  488.26  5310.9  489.04
  5353.4  489.74  5388.6  488.26  5395.9  489.24  5402.7  488.95  5410.1  490.20
  5416.9  489.44  5424.2  490.61  5429.4  489.34  5431.1  488.92  5437.1  490.06
#Mann=5,-1,0
  4415.5    0.05       0  4768.4    0.12       0  4834.9    0.07       0
  4838.9    0.12       0  5429.4    0.05       0
Bank Sta=4834.9,4838.9
Exp/Cntr=0.3,0.1

Type RM Length L Ch R = 1,4568,889,889,889
BEGIN DESCRIPTION:
Mapping XS a28f92c6
END DESCRIPTION:
XS GIS Cut Line= 3
      2681590.10      6922729.59      2680987.25      6922076.29
      2680596.59      6921646.57
#Sta/Elev= 30
  4127.6  487.70  4179.3  486.68  4235.4  487.38  4271.1  485.87  4462.2  483.49
  4469.0  484.32  4476.4  483.40  4497.4  483.98  4518.9  482.75  4631.8  483.69
  4651.3  482.74  4651.6  482.24  4655.3  482.74  4720.8  483.15  4791.5  482.94
  4842.9  483.62  4879.6  482.89  5021.4  484.87  5035.6  484.07  5099.1  484.53
  5141.7  486.60  5148.4  486.07  5297.1  489.05  5325.5  490.92  5403.2  490.97
  5439.0  492.21  5459.9  491.65  5506.7  493.29  5534.3  494.12  5597.3  495.18
#Mann=8,-1,0
  4127.6    0.05       0  4651.3    0.07       0  4655.3    0.05       0
  4720.8    0.12       0  4791.5    0.05       0  4842.9    0.12       0
  5506.7    0.05       0  5534.3    0.12       0
Bank Sta=4651.3,4655.3
Exp/Cntr=0.3,0.1

Type RM Length L Ch R = 1,3679,533,533,533
BEGIN DESCRIPTION:
Williams T10 4.0
END DESCRIPTION:
XS GIS Cut Line= 3
      2681659.12      6922729.91      2681592.67      6922143.87
      2681199.87      6921294.61
#Sta/Elev= 30
  4410.2  488.23  4630.5  484.10  4670.8  482.31  4701.0  483.43  4748.5  482.96
  4761.3  481.65  4781.5  483.15  4801.6  483.17  4811.7  482.79  4821.7  480.28
  4851.9  480.74  4880.1  478.49  4880.4  477.99  4884.1  478.49  4912.3  481.10
  4998.9  480.87  5006.3  480.54  5014.2  478.72  5036.2  480.55  5121.0  480.50
  5218.2  485.38  5246.6  484.55  5287.0  485.88  5384.2  491.11  5458.5  492.90
  5744.7  506.22  5767.6  505.53  5796.4  508.41  5911.3  515.35  5935.7  516.25
#Mann=5,-1,0
  4410.2    0.05       0  4748.5    0.12       0  4880.1    0.07       0
  4884.1    0.12       0  5911.3    0.05       0
Bank Sta=4880.1,4884.1
Exp/Cntr=0.3,0.1

Type RM Length L Ch R = 1,3146,508,508,508
BEGIN DESCRIPTION:
Williams T10 3.0
END DESCRIPTION:
XS GIS Cut Line= 3
      2681894.36      6922858.44      2682019.87      6922108.26
      2681439.84      6921340.91
#Sta/Elev= 30
  4239.4  486.99  4397.3  485.05  4400.8  485.13  4503.5  484.66  4579.6  483.73
  4622.1  484.83  4640.3  483.06  4766.8  480.72  4880.3  477.66  4886.2  477.31
  4886.5  476.81  4890.2  477.31  4943.9  478.64  4948.9  477.78  4966.8  480.07
  4987.1  477.77  5008.8  477.53  5222.2  479.13  5229.4  477.42  5264.8  480.00
  5279.3  479.18  5285.6  480.53  5329.3  481.77  5364.7  484.42  5379.2  484.02
  5385.5  485.58  5658.1  494.89  5664.3  494.30  5886.6  501.15  5961.9  504.86
#Mann=8,-1,0
  4239.4    0.05       0  4397.3    0.12       0  4400.8    0.05       0
  4503.5    0.12       0  4766.8    0.05       0  4880.3    0.12       0
  4886.2    0.07       0  4890.2    0.12       0
Bank Sta=4886.2,4890.2
Exp/Cntr=0.3,0.1

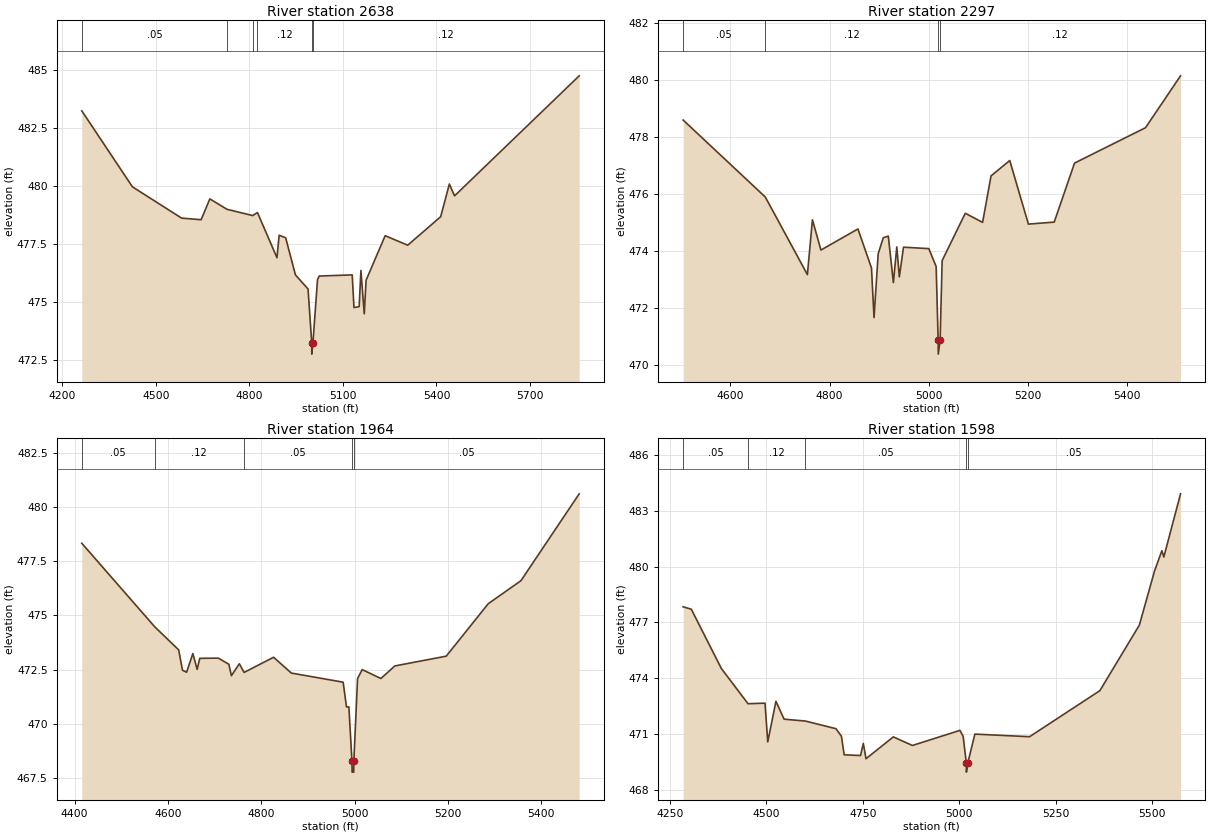
Type RM Length L Ch R = 1,2638,341,341,341
BEGIN DESCRIPTION:
Mapping XS ee705833
END DESCRIPTION:
XS GIS Cut Line= 3
      2682273.72      6922667.83      2682482.04      6921964.75
      2682091.43      6921196.55
#Sta/Elev= 30
  4262.6  483.25  4425.0  479.97  4582.6  478.62  4645.3  478.55  4673.3  479.45
  4728.2  479.00  4810.7  478.73  4825.9  478.86  4888.5  476.91  4895.5  477.88
  4916.4  477.77  4947.7  476.17  4988.2  475.56  4999.9  473.25  5000.2  472.75
  5003.9  473.25  5018.6  475.97  5024.2  476.12  5129.8  476.17  5135.4  474.76
  5152.1  474.80  5157.7  476.36  5168.4  474.49  5174.3  475.94  5235.5  477.86
  5307.8  477.45  5413.5  478.68  5441.3  480.09  5458.0  479.58  5857.7  484.76
#Mann=6,-1,0
  4262.6    0.05       0  4728.2    0.12       0  4810.7    0.05       0
  4825.9    0.12       0  4999.9    0.07       0  5003.9    0.12       0
Bank Sta=4999.9,5003.9
Exp/Cntr=0.3,0.1

Type RM Length L Ch R = 1,2297,333,333,333
BEGIN DESCRIPTION:
Williams T10 2.0
END DESCRIPTION:
XS GIS Cut Line= 3
      2682666.19      6922296.49      2682766.20      6921796.48
      2682566.18      6921346.44
#Sta/Elev= 30
  4504.7  478.58  4670.3  475.88  4755.1  473.16  4765.3  475.08  4782.4  474.02
  4857.0  474.76  4884.3  473.39  4889.4  471.65  4897.8  473.89  4908.0  474.45
  4918.2  474.51  4928.4  472.88  4935.3  474.13  4940.4  473.08  4948.8  474.12
  4999.8  474.07  5014.6  473.44  5018.6  470.87  5018.9  470.37  5022.6  470.87
  5026.7  473.65  5073.3  475.31  5108.2  474.99  5125.2  476.62  5162.9  477.16
  5200.5  474.93  5252.5  475.00  5293.5  477.07  5436.5  478.31  5507.1  480.13
#Mann=4,-1,0
  4504.7    0.05       0  4670.3    0.12       0  5018.6    0.07       0
  5022.6    0.12       0
Bank Sta=5018.6,5022.6
Exp/Cntr=0.3,0.1

Type RM Length L Ch R = 1,1964,366,366,366
BEGIN DESCRIPTION:
Mapping XS 0da4481f
END DESCRIPTION:
XS GIS Cut Line= 3
      2682831.87      6922395.29      2683079.26      6921883.15
      2683072.75      6921386.16
#Sta/Elev= 30
  4415.3  478.33  4571.4  474.48  4622.9  473.41  4631.1  472.47  4639.9  472.38
  4653.3  473.24  4662.5  472.51  4668.1  473.02  4707.7  473.03  4730.3  472.75
  4735.9  472.22  4752.9  472.77  4763.1  472.37  4826.3  473.07  4864.3  472.34
  4975.3  471.92  4982.5  470.78  4987.6  470.78  4994.2  468.27  4994.5  467.77
  4998.0  467.77  4998.2  468.27  5006.2  472.09  5016.2  472.50  5056.2  472.09
  5086.2  472.67  5196.2  473.12  5286.2  475.54  5356.2  476.60  5481.1  480.61
#Mann=5,-1,0
  4415.3    0.05       0  4571.4    0.12       0  4763.1    0.05       0
  4994.2    0.03       0  4998.2    0.05       0
Bank Sta=4994.2,4998.2
Exp/Cntr=0.3,0.1

Type RM Length L Ch R = 1,1598,0,0,0
BEGIN DESCRIPTION:
Mapping XS 61b2e923
END DESCRIPTION:
XS GIS Cut Line= 4
      2682950.99      6922436.01      2683378.30      6922010.28
      2683430.82      6921909.19      2683344.26      6921344.39
#Sta/Elev= 30
  4284.8  477.84  4306.0  477.71  4383.8  474.53  4452.9  472.64  4496.9  472.67
  4504.0  470.59  4525.2  472.77  4546.4  471.81  4601.5  471.71  4680.8  471.30
  4694.9  470.89  4702.0  469.90  4744.4  469.86  4751.5  470.51  4758.6  469.69
  4829.3  470.86  4878.8  470.40  5001.9  471.21  5010.2  470.89  5018.3  469.47
  5018.6  468.97  5022.3  469.47  5040.5  471.01  5182.2  470.87  5364.3  473.34
  5466.7  476.86  5505.9  479.76  5525.0  480.85  5530.0  480.51  5573.3  483.90
#Mann=5,-1,0
  4284.8    0.05       0  4452.9    0.12       0  4601.5    0.05       0
  5018.3    0.03       0  5022.3    0.05       0
Bank Sta=5018.3,5022.3
Exp/Cntr=0.3,0.1

Chan Stop Cuts=-1