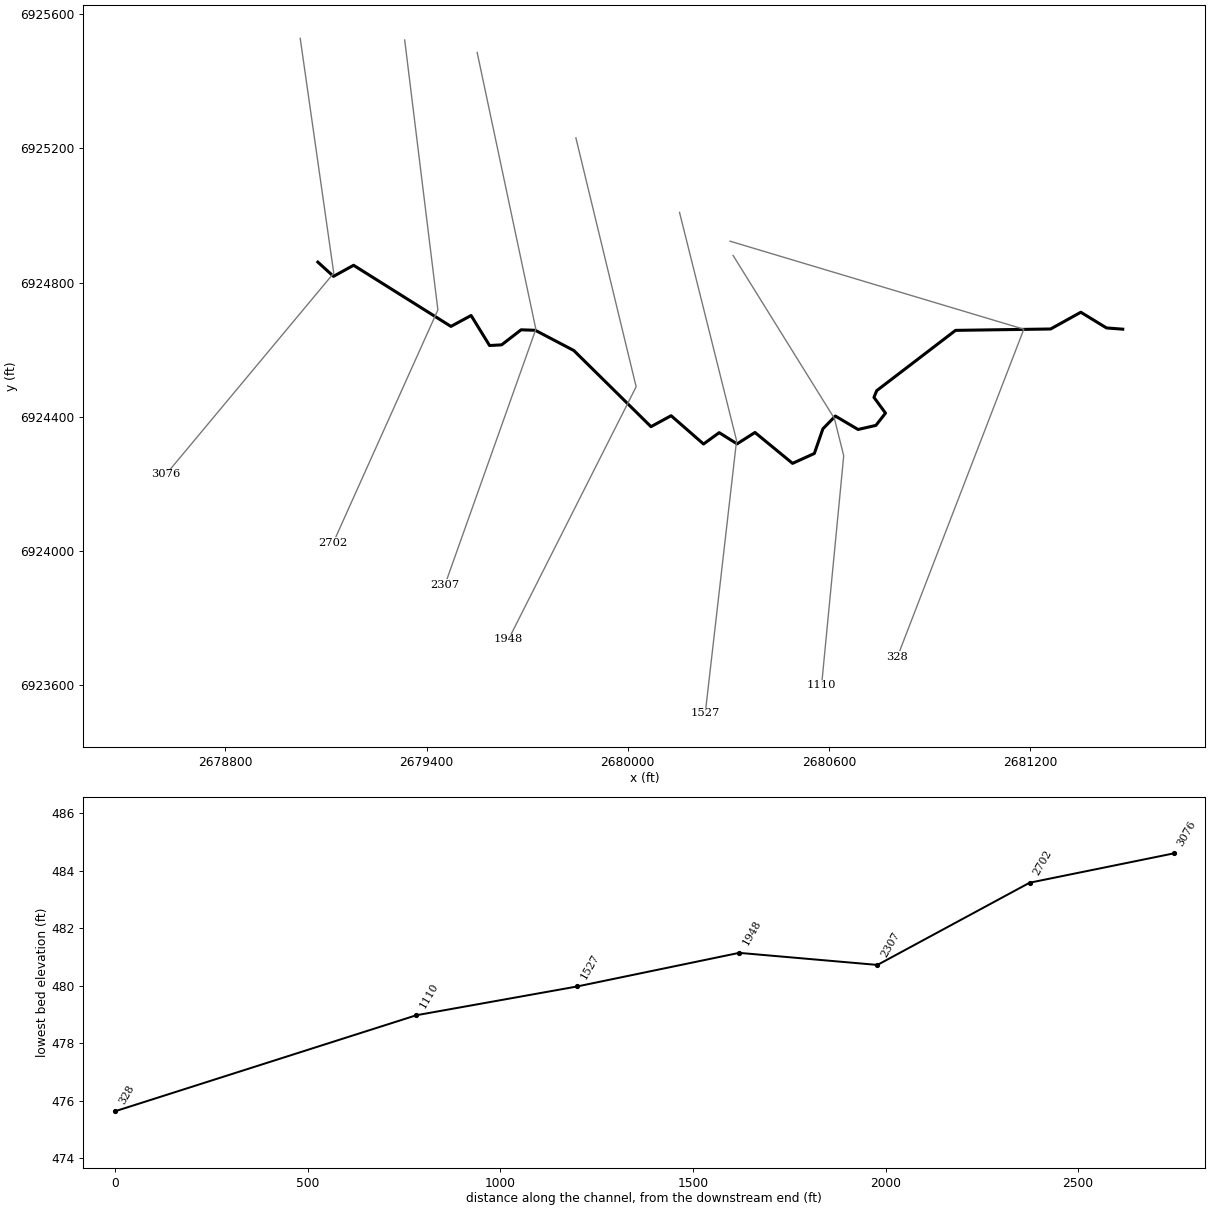
--- Williams T11.prj (project) ---

Proj Title=Williams T11 Base Level Engineering
Current Plan=p01
Default Exp/Contr=0.3,0.1
English Units
Geom File=g01
Flow File=f01
Plan File=p01
BEGIN DESCRIPTION:
Williams T11
END DESCRIPTION:

--- Williams T11.p01 (plan) ---

Plan Title=Multiple Run
Short Identifier=Multiple
Geom File=g01
Flow File=f01
Subcritical Flow
K Sum by GR= 0
Std Step Tol= 0.01
Critical Tol= 0.01
Num of Std Step Trials= 20
Max Error Tol= 0.3
Flow Tol Ratio= 0.001
Split Flow NTrial= 30
Split Flow Tol= 0.02
Split Flow Ratio= 0.02
Log Output Level= 0
Friction Slope Method= 1
Unsteady Friction Slope Method= 2
Unsteady Bridges Friction Slope Method= 1
Parabolic Critical Depth
Global Vel Dist=  1 , 1 , 1
Global Log Level= 0
CheckData=True
Encroach Param= -1, 0, 0, 0
BEGIN DESCRIPTION:
Multiple Run
END DESCRIPTION:

--- Williams T11.f01 (steady flow) ---

Flow Title=Multiple
Number of Profiles=7
Profile Names=10-year,25-year,50-year,1pct_min,100-year,1pct_plu,500-year
River Rch & RM= Williams T11,Reach-1,3076
     613     827    1000     601    1199    2391    1720
Boundary for River Rch & Prof#=Williams T11,Reach-1,1
Up Type=0
Dn Type=3
Dn Slope=0.005
Boundary for River Rch & Prof#=Williams T11,Reach-1,2
Up Type=0
Dn Type=3
Dn Slope=0.005
Boundary for River Rch & Prof#=Williams T11,Reach-1,3
Up Type=0
Dn Type=3
Dn Slope=0.005
Boundary for River Rch & Prof#=Williams T11,Reach-1,4
Up Type=0
Dn Type=3
Dn Slope=0.005
Boundary for River Rch & Prof#=Williams T11,Reach-1,5
Up Type=0
Dn Type=3
Dn Slope=0.005
Boundary for River Rch & Prof#=Williams T11,Reach-1,6
Up Type=0
Dn Type=3
Dn Slope=0.005
Boundary for River Rch & Prof#=Williams T11,Reach-1,7
Up Type=0
Dn Type=3
Dn Slope=0.005

--- Williams T11.g01 (geometry) ---

Geom Title=Existing Conditions

River Reach=Williams T11,Reach-1
Reach XY= 30
      2679076.00      6924861.00      2679122.66      6924818.51
      2679182.55      6924851.51      2679472.78      6924669.25
      2679532.93      6924701.77      2679588.01      6924612.22
      2679623.90      6924614.23      2679682.09      6924659.15
      2679724.27      6924657.66      2679839.21      6924597.38
      2680069.33      6924370.30      2680129.33      6924402.97
      2680226.00      6924318.56      2680272.67      6924352.44
      2680326.00      6924319.03      2680379.33      6924353.00
      2680491.42      6924260.88      2680556.37      6924290.33
      2680581.86      6924363.82      2680618.99      6924401.97
      2680686.73      6924361.89      2680740.00      6924374.14
      2680768.53      6924410.73      2680734.16      6924457.66
      2680742.38      6924477.70      2680977.47      6924657.45
      2681260.79      6924661.54      2681351.00      6924711.47
      2681427.49      6924664.69      2681476.00      6924661.00

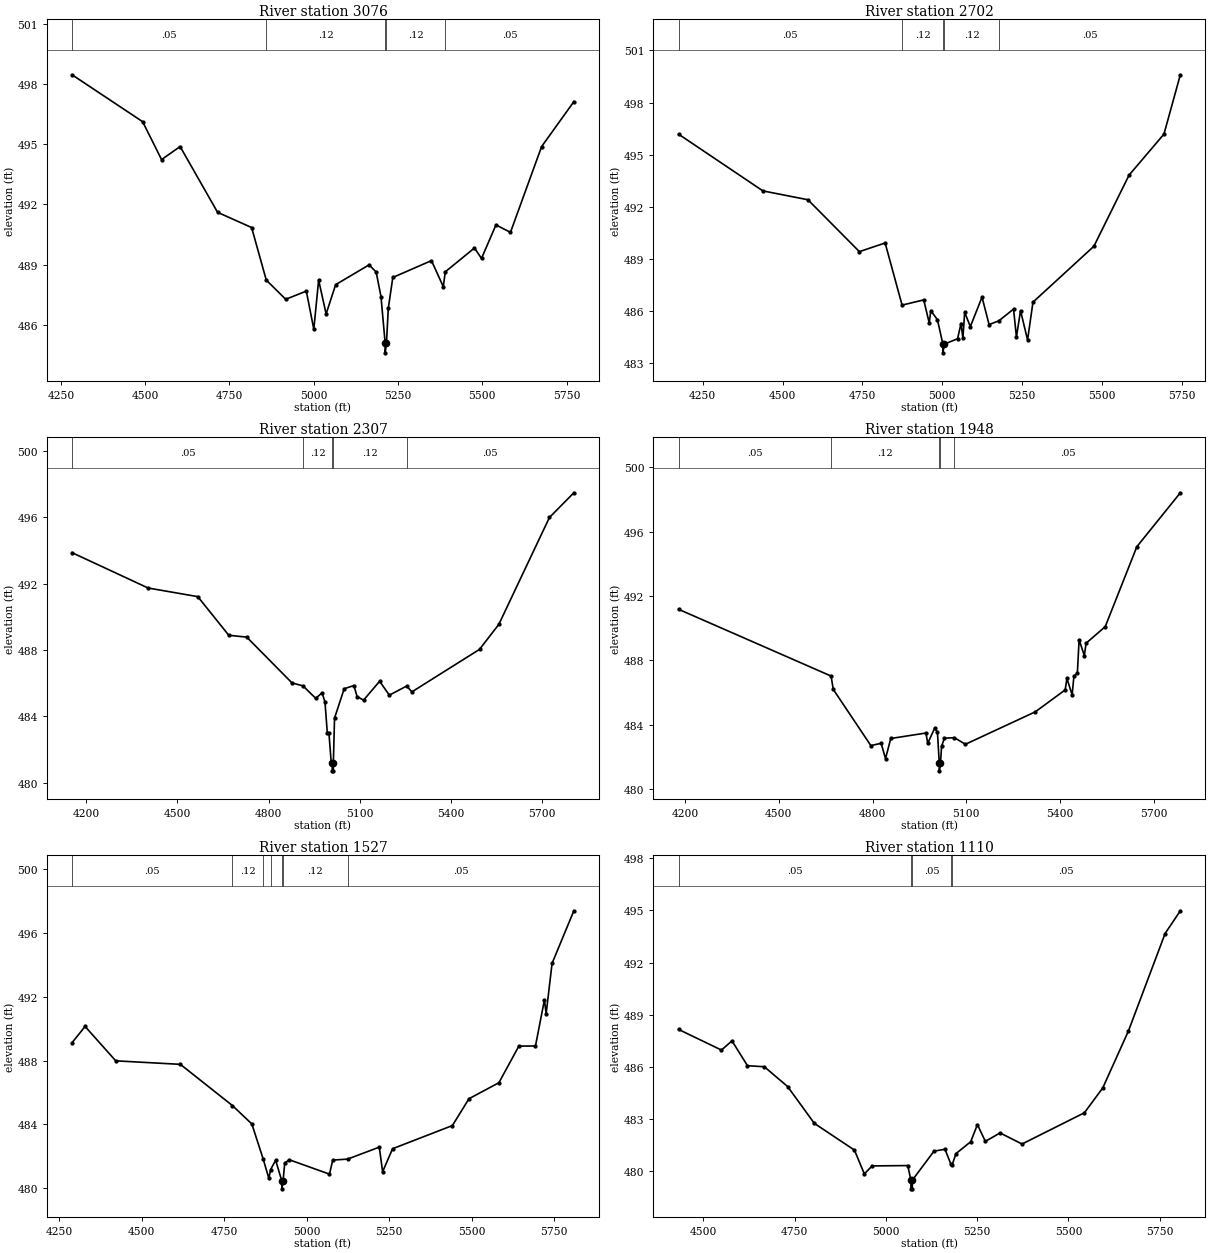
Type RM Length L Ch R = 1,3076,374,374,374
BEGIN DESCRIPTION:
Williams T11 3.0
END DESCRIPTION:
XS GIS Cut Line= 3
      2679023.40      6925528.19      2679123.40      6924828.19
      2678623.42      6924228.22
#Sta/Elev= 30
  4283.3  498.47  4492.6  496.13  4548.7  494.24  4603.7  494.89  4714.8  491.61
  4815.8  490.85  4859.2  488.23  4916.9  487.27  4978.0  487.68  5000.2  485.78
  5014.5  488.23  5036.7  486.54  5064.9  488.00  5164.2  488.99  5185.1  488.63
  5199.4  487.41  5211.7  485.10  5211.9  484.60  5215.7  485.10  5221.1  486.82
  5234.5  488.36  5349.1  489.20  5384.2  487.90  5390.1  488.64  5476.6  489.83
  5497.5  489.31  5540.4  490.98  5583.4  490.61  5675.8  494.89  5771.4  497.13
#Mann=5,-1,0
  4283.3    0.05       0  4859.2    0.12       0  5211.7    0.07       0
  5215.7    0.12       0  5390.1    0.05       0
Bank Sta=5211.7,5215.7
Exp/Cntr=0.3,0.1

Type RM Length L Ch R = 1,2702,395,395,395
BEGIN DESCRIPTION:
Mapping XS 8c511e6b
END DESCRIPTION:
XS GIS Cut Line= 3
      2679334.93      6925523.19      2679433.89      6924718.48
      2679122.04      6924024.61
#Sta/Elev= 30
  4174.3  496.18  4438.5  492.91  4579.5  492.40  4740.7  489.41  4821.3  489.91
  4874.4  486.33  4942.2  486.63  4959.4  485.30  4964.4  486.01  4985.1  485.49
  5002.2  484.08  5002.5  483.58  5006.2  484.08  5048.1  484.39  5059.0  485.27
  5064.9  484.43  5070.4  485.92  5088.1  485.09  5124.8  486.79  5146.8  485.21
  5177.1  485.42  5223.5  486.10  5232.5  484.49  5245.4  486.01  5267.4  484.32
  5284.3  486.50  5475.1  489.72  5585.3  493.82  5694.5  496.18  5745.8  499.60
#Mann=5,-1,0
  4174.3    0.05       0  4874.4    0.12       0  5002.2    0.07       0
  5006.2    0.12       0  5177.1    0.05       0
Bank Sta=5002.2,5006.2
Exp/Cntr=0.3,0.1

Type RM Length L Ch R = 1,2307,359,359,359
BEGIN DESCRIPTION:
Williams T11 2.0
END DESCRIPTION:
XS GIS Cut Line= 3
      2679550.99      6925486.05      2679726.00      6924661.00
      2679454.74      6923898.20
#Sta/Elev= 30
  4152.8  493.87  4403.3  491.74  4566.9  491.22  4669.1  488.89  4728.2  488.78
  4877.2  486.02  4913.6  485.84  4955.3  485.09  4976.5  485.42  4986.0  484.86
  4993.6  483.01  4998.9  483.01  5006.3  481.26  5009.6  481.22  5009.9  480.72
  5013.4  480.72  5013.6  481.22  5017.4  483.90  5049.3  485.67  5081.1  485.86
  5091.7  485.20  5113.0  484.98  5166.0  486.12  5197.9  485.28  5255.0  485.83
  5272.2  485.48  5495.0  488.04  5558.7  489.55  5725.3  495.99  5805.8  497.48
#Mann=5,-1,0
  4152.8    0.05       0  4913.6    0.12       0  5009.6    0.07       0
  5013.6    0.12       0  5255.0    0.05       0
Bank Sta=5009.6,5013.6
Exp/Cntr=0.3,0.1

Type RM Length L Ch R = 1,1948,421,421,421
BEGIN DESCRIPTION:
Mapping XS 44b9dbee
END DESCRIPTION:
XS GIS Cut Line= 3
      2679845.35      6925231.51      2680025.04      6924489.32
      2679644.84      6923736.73
#Sta/Elev= 30
  4178.7  491.18  4667.2  487.03  4674.2  486.20  4794.5  482.71  4827.4  482.85
  4841.5  481.90  4858.3  483.15  4971.0  483.49  4976.6  482.85  4998.9  483.79
  5007.7  483.56  5013.5  481.64  5013.8  481.14  5017.5  481.64  5021.1  482.67
  5030.1  483.17  5062.2  483.20  5097.3  482.79  5321.4  484.81  5416.8  486.17
  5422.4  486.88  5439.1  485.86  5444.7  487.02  5455.8  487.22  5461.4  489.29
  5478.1  488.30  5483.7  489.07  5545.0  490.10  5646.3  495.07  5785.5  498.42
#Mann=5,-1,0
  4178.7    0.05       0  4667.2    0.12       0  5013.5    0.07       0
  5017.5    0.12       0  5062.2    0.05       0
Bank Sta=5013.5,5017.5
Exp/Cntr=0.3,0.1

Type RM Length L Ch R = 1,1527,417,417,417
BEGIN DESCRIPTION:
Mapping XS 7665126b
END DESCRIPTION:
XS GIS Cut Line= 3
      2680154.37      6925009.32      2680324.52      6924328.73
      2680231.07      6923515.41
#Sta/Elev= 30
  4289.1  489.12  4328.6  490.13  4421.4  487.98  4617.2  487.76  4775.0  485.18
  4833.7  484.03  4868.2  481.83  4885.2  480.63  4890.7  481.18  4905.8  481.76
  4924.4  480.47  4924.7  479.97  4928.4  480.47  4933.3  481.58  4947.1  481.79
  5068.9  480.89  5078.9  481.77  5123.8  481.83  5219.9  482.58  5229.9  481.04
  5260.1  482.48  5441.3  483.93  5491.6  485.61  5582.2  486.61  5642.6  488.90
  5693.0  488.91  5720.2  491.80  5725.3  490.92  5743.3  494.08  5809.3  497.37
#Mann=7,-1,0
  4289.1    0.05       0  4775.0    0.12       0  4868.2    0.05       0
  4890.7    0.12       0  4924.4    0.07       0  4928.4    0.12       0
  5123.8    0.05       0
Bank Sta=4924.4,4928.4
Exp/Cntr=0.3,0.1

Type RM Length L Ch R = 1,1110,782,782,782
BEGIN DESCRIPTION:
Mapping XS 3957d310
END DESCRIPTION:
XS GIS Cut Line= 4
      2680314.09      6924880.83      2680616.18      6924394.70
      2680643.96      6924283.59      2680577.99      6923599.54
#Sta/Elev= 30
  4432.3  488.15  4549.8  486.96  4578.6  487.49  4621.1  486.06  4667.2  486.00
  4731.0  484.86  4804.2  482.74  4914.0  481.20  4941.1  479.83  4962.4  480.29
  5060.0  480.31  5068.6  479.47  5068.9  478.97  5072.4  478.97  5072.6  479.47
  5131.8  481.14  5162.0  481.25  5178.1  480.39  5181.9  480.37  5192.1  481.00
  5232.3  481.68  5250.8  482.67  5272.5  481.70  5312.7  482.19  5372.9  481.55
  5543.7  483.35  5594.0  484.78  5664.3  488.06  5764.7  493.67  5806.4  494.98
#Mann=5,-1,0
  4432.3    0.05       0  5068.6    0.03       0  5072.6    0.05       0
  5178.1    0.12       0  5181.9    0.05       0
Bank Sta=5068.6,5072.6
Exp/Cntr=0.3,0.1

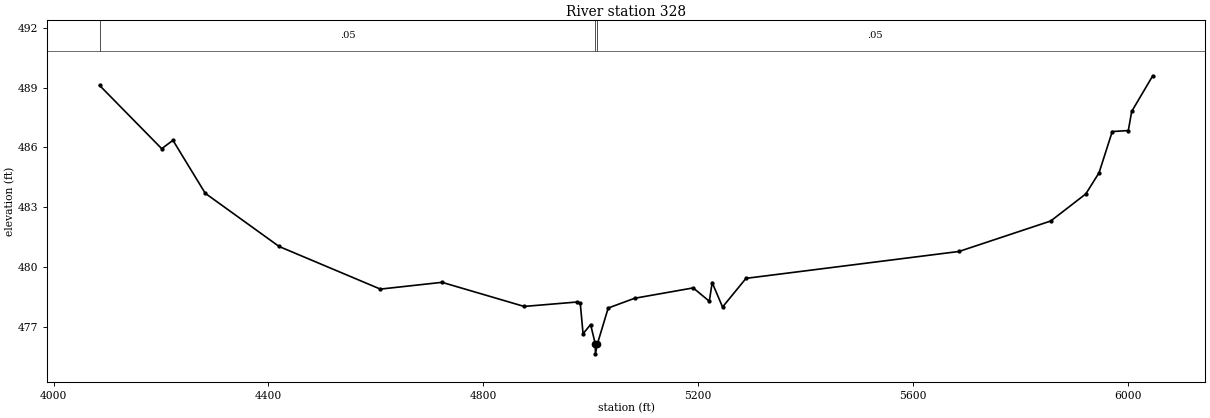
Type RM Length L Ch R = 1,328,0,0,0
BEGIN DESCRIPTION:
Williams T11 1.0
END DESCRIPTION:
XS GIS Cut Line= 3
      2680305.09      6924923.28      2681181.04      6924660.91
      2680804.29      6923684.47
#Sta/Elev= 30
  4085.6  489.11  4201.4  485.93  4222.3  486.35  4282.5  483.69  4420.0  481.02
  4608.5  478.88  4723.3  479.22  4876.2  478.01  4973.9  478.23  4980.7  478.17
  4985.9  476.64  5000.0  477.10  5008.6  476.13  5008.9  475.63  5012.6  476.13
  5032.7  477.93  5081.9  478.42  5191.0  478.94  5221.0  478.27  5226.3  479.21
  5245.6  477.98  5289.3  479.42  5685.9  480.77  5856.7  482.30  5922.0  483.66
  5946.6  484.72  5971.2  486.79  6001.1  486.84  6007.4  487.80  6046.6  489.59
#Mann=3,-1,0
  4085.6    0.05       0  5008.6    0.03       0  5012.6    0.05       0
Bank Sta=5008.6,5012.6
Exp/Cntr=0.3,0.1

Chan Stop Cuts=-1