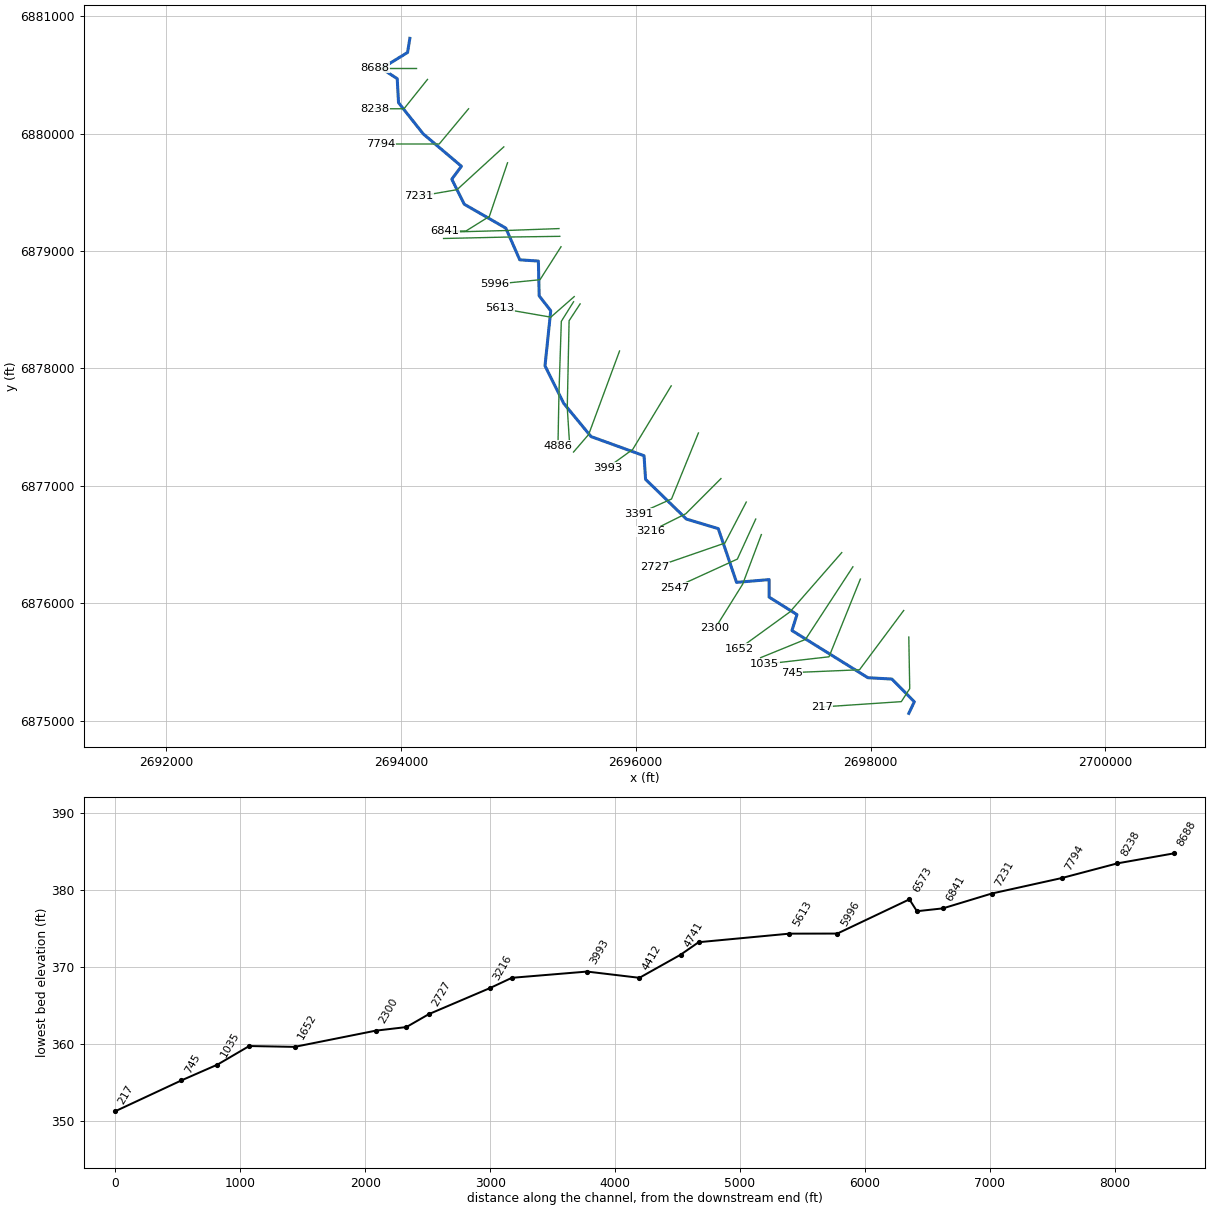
--- Williams T2.prj (project) ---

Proj Title=Williams T2 Base Level Engineering
Current Plan=p01
Default Exp/Contr=0.3,0.1
English Units
Geom File=g01
Flow File=f01
Plan File=p01
BEGIN DESCRIPTION:
Williams T2
END DESCRIPTION:

--- Williams T2.p01 (plan) ---

Plan Title=Multiple Run
Short Identifier=Multiple
Geom File=g01
Flow File=f01
Subcritical Flow
K Sum by GR= 0
Std Step Tol= 0.01
Critical Tol= 0.01
Num of Std Step Trials= 20
Max Error Tol= 0.3
Flow Tol Ratio= 0.001
Split Flow NTrial= 30
Split Flow Tol= 0.02
Split Flow Ratio= 0.02
Log Output Level= 0
Friction Slope Method= 1
Unsteady Friction Slope Method= 2
Unsteady Bridges Friction Slope Method= 1
Parabolic Critical Depth
Global Vel Dist=  1 , 1 , 1
Global Log Level= 0
CheckData=True
Encroach Param= -1, 0, 0, 0
BEGIN DESCRIPTION:
Multiple Run
END DESCRIPTION:

--- Williams T2.f01 (steady flow) ---

Flow Title=Multiple
Number of Profiles=7
Profile Names=10-year,25-year,50-year,1pct_min,100-year,1pct_plu,500-year
River Rch & RM= Williams T2,Reach-1,8688
     487     638     757     445     888    1772    1222
River Rch & RM= Williams T2,Reach-1,4886
     742     998    1205     721    1438    2870    2049
Boundary for River Rch & Prof#=Williams T2,Reach-1,1
Up Type=0
Dn Type=3
Dn Slope=0.005
Boundary for River Rch & Prof#=Williams T2,Reach-1,2
Up Type=0
Dn Type=3
Dn Slope=0.005
Boundary for River Rch & Prof#=Williams T2,Reach-1,3
Up Type=0
Dn Type=3
Dn Slope=0.005
Boundary for River Rch & Prof#=Williams T2,Reach-1,4
Up Type=0
Dn Type=3
Dn Slope=0.005
Boundary for River Rch & Prof#=Williams T2,Reach-1,5
Up Type=0
Dn Type=3
Dn Slope=0.005
Boundary for River Rch & Prof#=Williams T2,Reach-1,6
Up Type=0
Dn Type=3
Dn Slope=0.005
Boundary for River Rch & Prof#=Williams T2,Reach-1,7
Up Type=0
Dn Type=3
Dn Slope=0.005

--- Williams T2.g01 (geometry) ---

Geom Title=Existing Conditions

River Reach=Williams T2,Reach-1
Reach XY= 30
      2694076.00      6880811.00      2694056.40      6880690.79
      2693834.77      6880554.22      2693968.30      6880467.48
      2693979.54      6880262.46      2694189.49      6879997.44
      2694515.18      6879721.37      2694433.31      6879611.09
      2694539.61      6879397.76      2694893.08      6879194.58
      2695012.21      6878924.37      2695170.64      6878913.77
      2695177.67      6878617.05      2695276.06      6878491.01
      2695227.19      6878021.50      2695386.76      6877701.30
      2695619.50      6877418.73      2696070.82      6877255.56
      2696083.80      6877054.79      2696431.44      6876716.18
      2696703.16      6876634.58      2696858.86      6876177.03
      2697136.53      6876200.54      2697136.20      6876051.30
      2697373.37      6875902.54      2697330.78      6875766.61
      2697977.52      6875364.74      2698182.48      6875353.30
      2698373.02      6875159.66      2698326.00      6875061.00

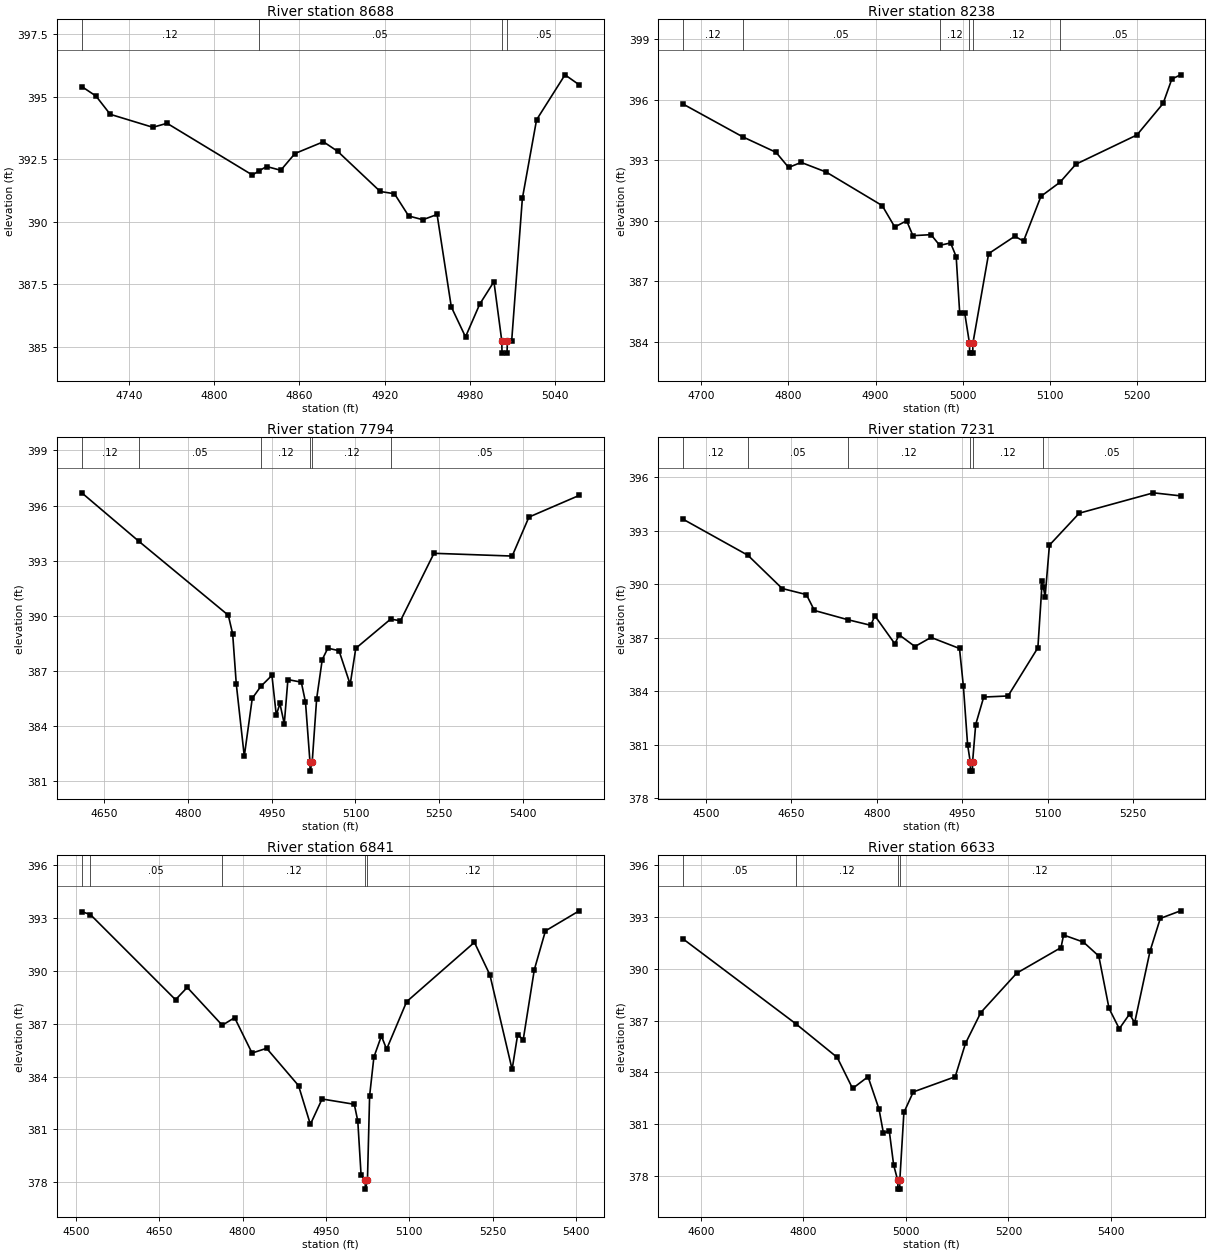
Type RM Length L Ch R = 1,8688,450,450,450
BEGIN DESCRIPTION:
Williams T2 19.0
END DESCRIPTION:
XS GIS Cut Line= 3
      2694125.99      6880561.00      2693826.00      6880561.00
      2693775.99      6880561.00
#Sta/Elev= 30
  4706.9  395.41  4716.9  395.03  4726.9  394.30  4756.9  393.78  4766.9  393.94
  4826.9  391.87  4831.5  392.03  4836.9  392.21  4846.9  392.06  4856.9  392.73
  4876.9  393.20  4886.9  392.82  4916.9  391.21  4926.9  391.12  4936.9  390.23
  4946.9  390.08  4956.9  390.29  4966.9  386.59  4976.9  385.39  4986.9  386.70
  4996.9  387.60  5002.4  385.24  5002.6  384.74  5006.1  384.74  5006.4  385.24
  5009.4  385.24  5016.9  390.93  5026.9  394.08  5046.9  395.88  5056.9  395.48
#Mann=4,-1,0
  4706.9    0.12       0  4831.5    0.05       0  5002.4    0.03       0
  5006.4    0.05       0
Bank Sta=5002.4,5006.4
Exp/Cntr=0.3,0.1

Type RM Length L Ch R = 1,8238,444,444,444
BEGIN DESCRIPTION:
Williams T2 18.0
END DESCRIPTION:
XS GIS Cut Line= 3
      2694226.03      6880461.04      2694026.00      6880211.00
      2693776.01      6880211.00
#Sta/Elev= 30
  4679.4  395.79  4747.6  394.17  4785.9  393.40  4800.3  392.65  4814.7  392.90
  4843.5  392.42  4907.6  390.76  4922.0  389.70  4935.6  390.01  4942.8  389.27
  4963.6  389.32  4973.5  388.79  4986.0  388.91  4992.4  388.23  4996.4  385.46
  5002.1  385.46  5007.6  383.95  5007.9  383.45  5011.4  383.45  5011.6  383.95
  5029.6  388.38  5059.6  389.24  5069.6  389.00  5089.6  391.22  5111.5  391.92
  5129.6  392.81  5199.6  394.26  5229.6  395.82  5239.6  397.03  5249.6  397.24
#Mann=6,-1,0
  4679.4    0.12       0  4747.6    0.05       0  4973.5    0.12       0
  5007.6    0.07       0  5011.6    0.12       0  5111.5    0.05       0
Bank Sta=5007.6,5011.6
Exp/Cntr=0.3,0.1

Type RM Length L Ch R = 1,7794,563,563,563
BEGIN DESCRIPTION:
Williams T2 17.0
END DESCRIPTION:
XS GIS Cut Line= 3
      2694575.98      6880210.98      2694326.00      6879911.00
      2693825.98      6879911.00
#Sta/Elev= 30
  4610.0  396.69  4712.3  394.05  4872.3  390.03  4880.1  389.02  4886.6  386.28
  4900.9  382.36  4915.2  385.51  4930.5  386.16  4950.4  386.76  4958.2  384.60
  4964.7  385.23  4972.5  384.12  4979.0  386.53  5003.0  386.39  5010.5  385.30
  5018.5  382.05  5018.7  381.55  5022.5  382.05  5030.5  385.50  5040.5  387.62
  5050.5  388.24  5070.5  388.10  5090.5  386.27  5100.5  388.23  5162.9  389.82
  5180.5  389.73  5240.5  393.40  5380.5  393.25  5410.5  395.37  5500.5  396.55
#Mann=6,-1,0
  4610.0    0.12       0  4712.3    0.05       0  4930.5    0.12       0
  5018.5    0.07       0  5022.5    0.12       0  5162.9    0.05       0
Bank Sta=5018.5,5022.5
Exp/Cntr=0.3,0.1

Type RM Length L Ch R = 1,7231,390,390,390
BEGIN DESCRIPTION:
Williams T2 16.0
END DESCRIPTION:
XS GIS Cut Line= 3
      2694876.02      6879886.35      2694477.60      6879521.70
      2694149.09      6879465.37
#Sta/Elev= 30
  4459.9  393.64  4573.7  391.62  4633.8  389.76  4676.3  389.42  4690.4  388.53
  4749.4  388.01  4789.2  387.70  4796.6  388.23  4831.7  386.66  4839.1  387.17
  4866.9  386.51  4895.2  387.02  4945.2  386.40  4952.0  384.28  4959.4  381.01
  4964.1  380.03  4964.4  379.53  4967.9  379.53  4968.1  380.03  4973.6  382.14
  4987.7  383.68  5030.4  383.74  5082.8  386.44  5090.4  390.17  5092.2  389.86
  5095.5  389.30  5103.1  392.19  5155.5  393.98  5285.7  395.12  5333.3  394.95
#Mann=6,-1,0
  4459.9    0.12       0  4573.7    0.05       0  4749.4    0.12       0
  4964.1    0.07       0  4968.1    0.12       0  5092.2    0.05       0
Bank Sta=4964.1,4968.1
Exp/Cntr=0.3,0.1

Type RM Length L Ch R = 1,6841,208,208,208
BEGIN DESCRIPTION:
Mapping XS f7c7a3f9
END DESCRIPTION:
XS GIS Cut Line= 4
      2694907.93      6879750.82      2694753.11      6879294.07
      2694554.52      6879170.13      2694375.20      6879168.70
#Sta/Elev= 30
  4510.3  393.37  4525.7  393.21  4679.1  388.37  4700.2  389.07  4763.2  386.92
  4785.5  387.35  4816.9  385.34  4843.1  385.61  4900.6  383.49  4921.9  381.29
  4943.0  382.73  5001.0  382.43  5007.3  381.48  5013.2  378.42  5020.7  378.11
  5020.9  377.61  5024.7  378.11  5028.6  382.91  5036.3  385.11  5049.8  386.31
  5059.2  385.56  5095.3  388.26  5217.3  391.63  5245.2  389.78  5285.2  384.41
  5295.2  386.39  5305.2  386.10  5325.2  390.08  5345.2  392.28  5406.0  393.42
#Mann=5,-1,0
  4510.3    0.12       0  4525.7    0.05       0  4763.2    0.12       0
  5020.7    0.07       0  5024.7    0.12       0
Bank Sta=5020.7,5024.7
Exp/Cntr=0.3,0.1

Type RM Length L Ch R = 1,6633,60,60,60
BEGIN DESCRIPTION:
Mapping XS c6c94126
END DESCRIPTION:
XS GIS Cut Line= 4
      2695346.42      6879190.49      2694968.13      6879176.81
      2694894.47      6879173.85      2694376.52      6879159.64
#Sta/Elev= 30
  4565.4  391.73  4784.7  386.83  4866.0  384.87  4896.0  383.07  4926.1  383.75
  4947.5  381.88  4956.1  380.49  4967.6  380.60  4976.1  378.64  4984.1  377.74
  4984.4  377.24  4987.9  377.24  4988.1  377.74  4996.1  381.68  5014.4  382.87
  5096.2  383.75  5116.2  385.68  5146.2  387.47  5216.2  389.75  5302.6  391.23
  5307.6  391.96  5346.3  391.55  5376.3  390.74  5396.3  387.71  5416.3  386.53
  5436.3  387.38  5446.3  386.88  5476.3  391.03  5496.3  392.92  5535.8  393.36
#Mann=4,-1,0
  4565.4    0.05       0  4784.7    0.12       0  4984.1    0.07       0
  4988.1    0.12       0
Bank Sta=4984.1,4988.1
Exp/Cntr=0.3,0.1

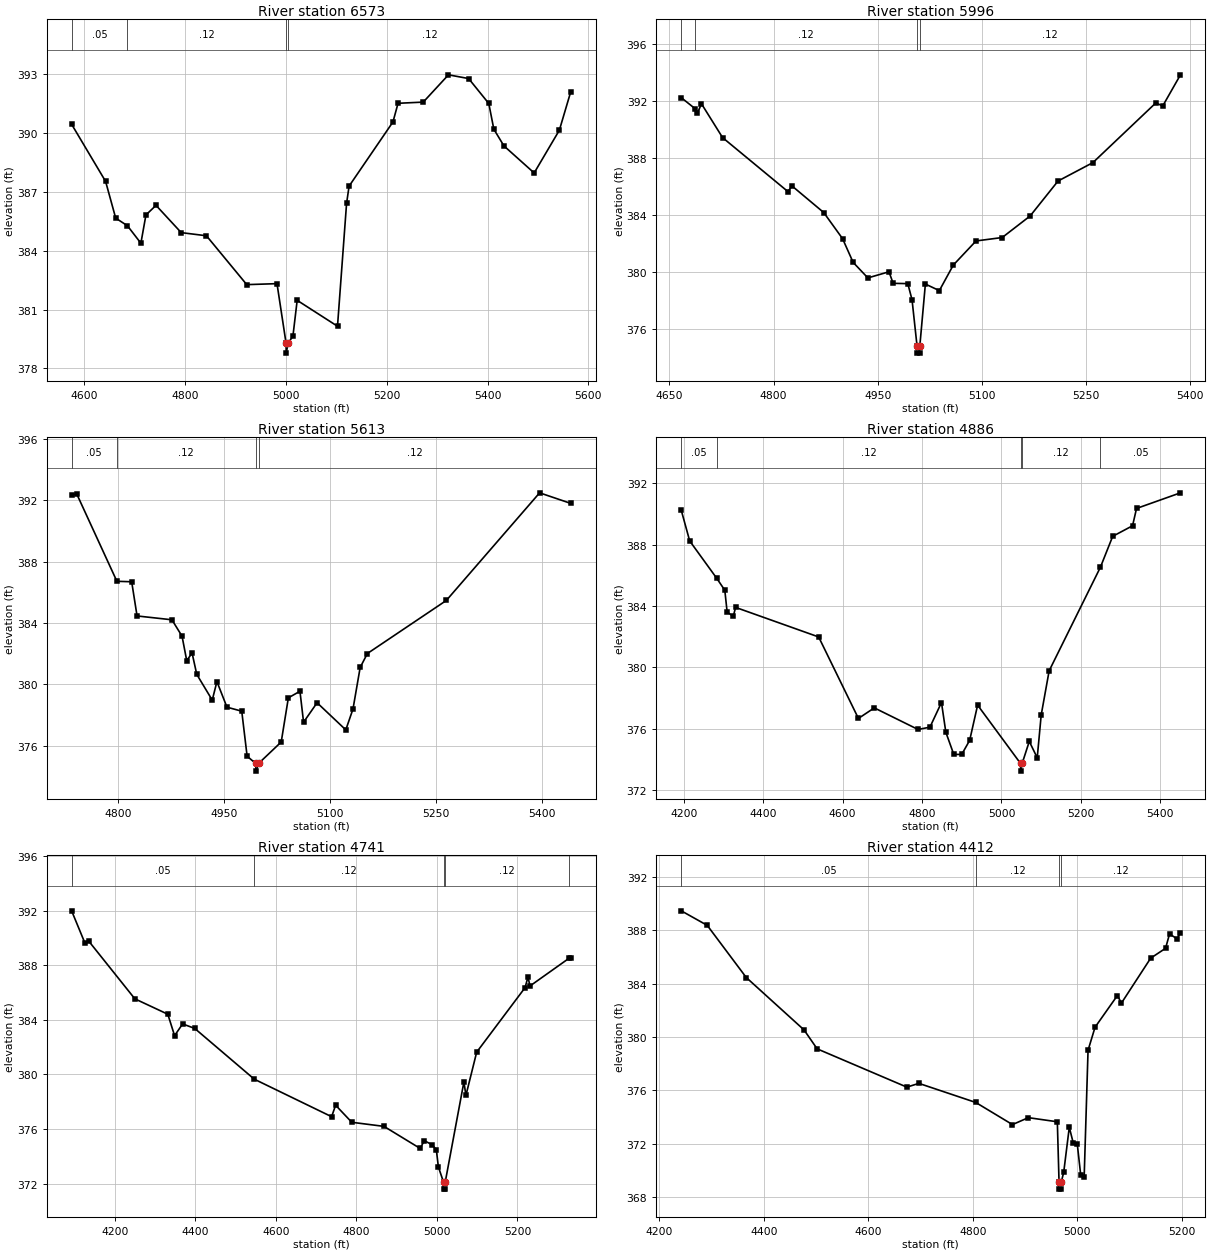
Type RM Length L Ch R = 1,6573,577,577,577
BEGIN DESCRIPTION:
Mapping XS 3d1cde1a
END DESCRIPTION:
XS GIS Cut Line= 3
      2695353.36      6879124.41      2694917.72      6879118.53
      2694363.34      6879106.09
#Sta/Elev= 30
  4575.0  390.44  4642.4  387.53  4662.4  385.66  4685.7  385.27  4712.4  384.38
  4722.4  385.82  4742.4  386.31  4792.4  384.92  4842.4  384.76  4922.4  382.27
  4982.4  382.32  5000.4  379.28  5000.6  378.78  5004.4  379.28  5014.0  379.65
  5022.4  381.47  5102.4  380.15  5120.4  386.41  5125.4  387.29  5212.4  390.56
  5222.5  391.51  5272.5  391.57  5322.5  392.96  5362.5  392.77  5402.5  391.50
  5412.5  390.19  5432.5  389.34  5492.5  387.96  5542.5  390.14  5565.2  392.11
#Mann=4,-1,0
  4575.0    0.05       0  4685.7    0.12       0  5000.4    0.07       0
  5004.4    0.12       0
Bank Sta=5000.4,5004.4
Exp/Cntr=0.3,0.1

Type RM Length L Ch R = 1,5996,383,383,383
BEGIN DESCRIPTION:
Williams T2 13.0
END DESCRIPTION:
XS GIS Cut Line= 3
      2695363.45      6879035.50      2695184.46      6878754.82
      2694800.66      6878716.59
#Sta/Elev= 30
  4667.1  392.24  4686.7  391.48  4690.2  391.14  4696.2  391.81  4726.6  389.44
  4820.6  385.66  4826.6  386.05  4872.2  384.19  4899.3  382.36  4914.5  380.70
  4935.7  379.61  4966.1  380.04  4972.1  379.23  4993.2  379.21  4999.3  378.08
  5006.5  374.84  5006.7  374.34  5010.2  374.34  5010.5  374.84  5018.5  379.18
  5038.6  378.72  5058.7  380.51  5091.4  382.20  5129.1  382.44  5169.3  383.95
  5209.5  386.40  5259.7  387.69  5350.2  391.87  5360.2  391.66  5385.7  393.84
#Mann=4,-1,0
  4667.1    0.05       0  4686.7    0.12       0  5006.5    0.07       0
  5010.5    0.12       0
Bank Sta=5006.5,5010.5
Exp/Cntr=0.3,0.1

Type RM Length L Ch R = 1,5613,727,727,727
BEGIN DESCRIPTION:
Williams T2 12.0
END DESCRIPTION:
XS GIS Cut Line= 3
      2695475.97      6878610.97      2695276.41      6878436.00
      2694842.58      6878511.21
#Sta/Elev= 30
  4734.6  392.32  4741.7  392.42  4798.6  386.71  4819.5  386.68  4827.1  384.45
  4876.4  384.20  4890.7  383.13  4897.3  381.54  4904.9  382.03  4911.5  380.64
  4933.4  378.96  4940.0  380.17  4954.2  378.50  4975.1  378.24  4982.7  375.30
  4994.9  374.83  4995.2  374.33  4998.9  374.83  5030.9  376.23  5041.0  379.11
  5057.4  379.54  5062.5  377.52  5081.6  378.79  5122.2  377.02  5132.4  378.39
  5142.5  381.09  5152.7  382.00  5264.3  385.46  5396.2  392.48  5440.3  391.79
#Mann=4,-1,0
  4734.6    0.05       0  4798.6    0.12       0  4994.9    0.07       0
  4998.9    0.12       0
Bank Sta=4994.9,4998.9
Exp/Cntr=0.3,0.1

Type RM Length L Ch R = 1,4886,145,145,145
BEGIN DESCRIPTION:
Williams T2 11.0
END DESCRIPTION:
XS GIS Cut Line= 4
      2695470.37      6878566.97      2695366.21      6878400.31
      2695346.17      6877791.07      2695337.56      6877340.45
#Sta/Elev= 30
  4193.9  390.25  4215.1  388.25  4282.9  385.82  4303.5  385.03  4309.4  383.60
  4324.8  383.33  4330.7  383.91  4539.8  381.98  4639.9  376.66  4679.9  377.35
  4790.0  375.94  4820.0  376.09  4849.0  377.70  4860.0  375.76  4880.0  374.31
  4900.0  374.31  4920.0  375.23  4940.0  377.53  5048.1  373.72  5048.3  373.22
  5052.1  373.72  5070.1  375.16  5090.1  374.09  5100.1  376.89  5120.1  379.77
  5249.3  386.54  5280.1  388.55  5330.1  389.24  5340.1  390.37  5450.7  391.39
#Mann=5,-1,0
  4193.9    0.05       0  4282.9    0.12       0  5048.1    0.07       0
  5052.1    0.12       0  5249.3    0.05       0
Bank Sta=5048.1,5052.1
Exp/Cntr=0.3,0.1

Type RM Length L Ch R = 1,4741,329,329,329
BEGIN DESCRIPTION:
Mapping XS c4a147fe
END DESCRIPTION:
XS GIS Cut Line= 4
      2695526.17      6878548.67      2695432.39      6878405.41
      2695416.77      6877665.82      2695437.61      6877337.66
#Sta/Elev= 30
  4092.7  391.99  4126.1  389.60  4135.2  389.77  4249.7  385.54  4331.6  384.41
  4348.4  382.84  4368.4  383.70  4398.4  383.37  4546.3  379.65  4738.4  376.90
  4748.4  377.74  4788.5  376.49  4868.5  376.19  4958.5  374.57  4968.5  375.15
  4988.5  374.83  4998.5  374.47  5003.6  373.22  5016.5  372.09  5016.8  371.59
  5020.3  371.59  5020.5  372.09  5067.0  379.45  5072.0  378.46  5098.7  381.63
  5218.9  386.36  5226.1  387.14  5231.1  386.48  5328.0  388.51  5332.5  388.50
#Mann=5,-1,0
  4092.7    0.05       0  4546.3    0.12       0  5016.5    0.07       0
  5020.5    0.12       0  5328.0    0.05       0
Bank Sta=5016.5,5020.5
Exp/Cntr=0.3,0.1

Type RM Length L Ch R = 1,4412,419,419,419
BEGIN DESCRIPTION:
Mapping XS f3b73927
END DESCRIPTION:
XS GIS Cut Line= 3
      2695862.09      6878147.63      2695599.06      6877436.66
      2695470.09      6877287.04
#Sta/Elev= 30
  4241.9  389.47  4291.6  388.38  4366.3  384.47  4476.9  380.54  4502.0  379.12
  4673.7  376.25  4696.8  376.53  4805.6  375.10  4875.9  373.44  4906.3  373.96
  4961.8  373.65  4965.1  369.10  4965.4  368.60  4968.9  368.60  4969.1  369.10
  4974.0  369.86  4984.7  373.24  4992.2  372.07  5000.0  371.97  5006.6  369.65
  5013.2  369.54  5020.6  379.01  5034.0  380.74  5076.8  383.12  5084.5  382.55
  5140.5  385.92  5169.0  386.66  5176.6  387.74  5190.9  387.37  5197.5  387.84
#Mann=4,-1,0
  4241.9    0.05       0  4805.6    0.12       0  4965.1    0.07       0
  4969.1    0.12       0
Bank Sta=4965.1,4969.1
Exp/Cntr=0.3,0.1

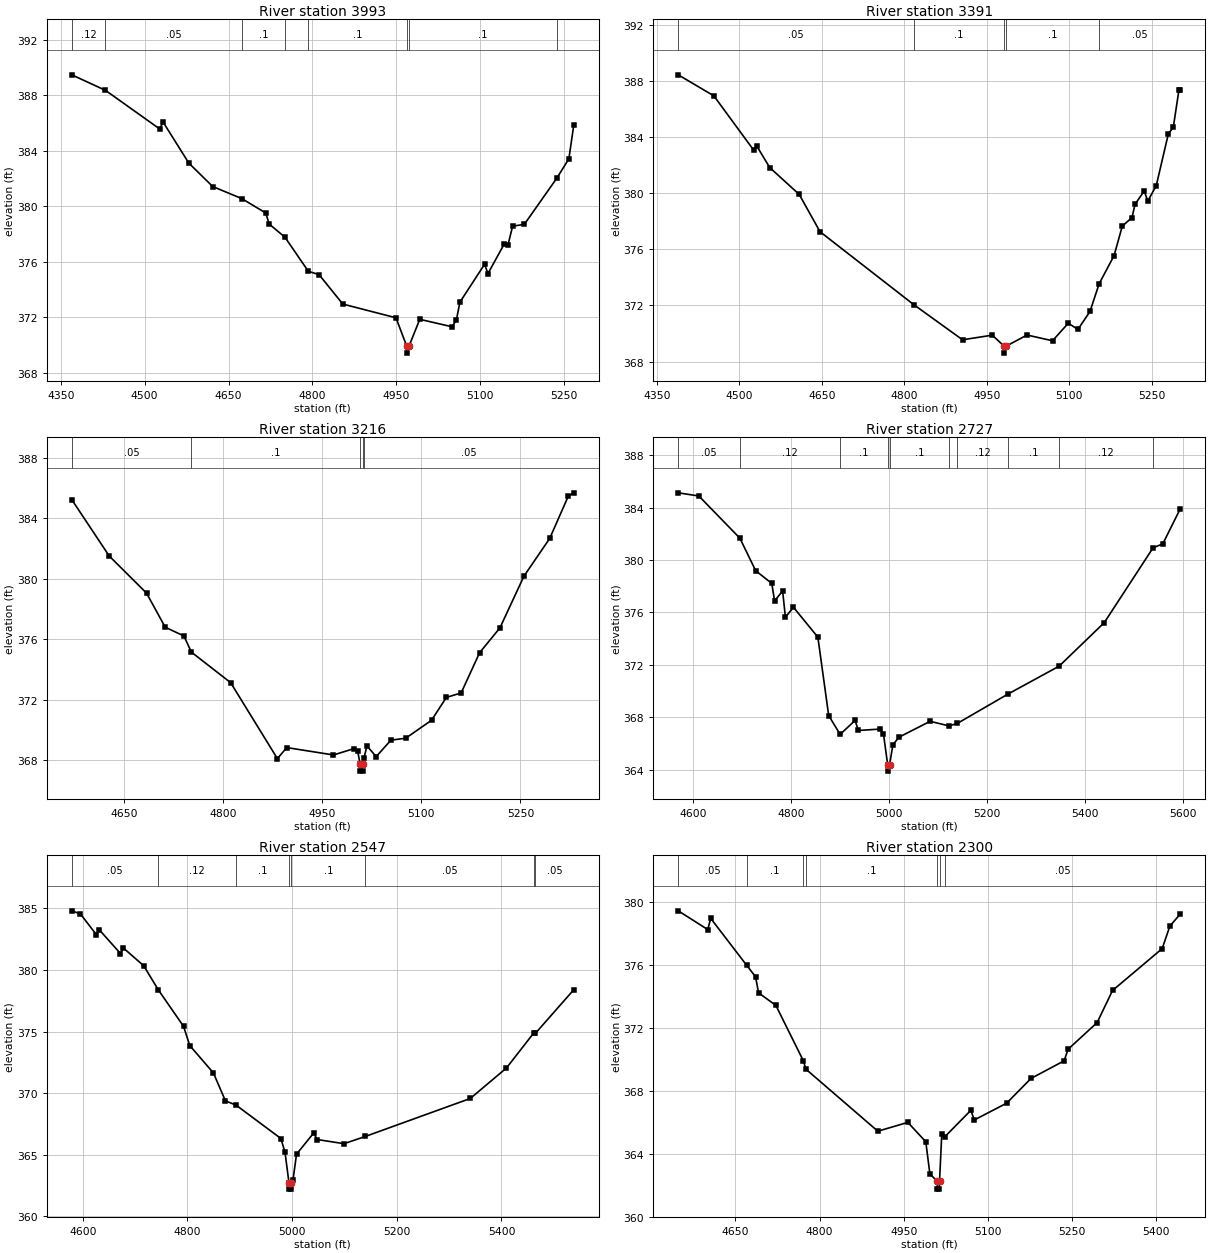
Type RM Length L Ch R = 1,3993,602,602,602
BEGIN DESCRIPTION:
Mapping XS f3c553f6
END DESCRIPTION:
XS GIS Cut Line= 3
      2696302.19      6877850.72      2695974.06      6877309.05
      2695759.46      6877153.92
#Sta/Elev= 30
  4369.6  389.49  4429.9  388.37  4526.7  385.59  4533.0  386.08  4579.0  383.12
  4621.7  381.43  4673.7  380.56  4716.7  379.52  4722.6  378.73  4751.0  377.77
  4792.8  375.31  4811.8  375.08  4854.4  372.95  4949.5  371.96  4968.8  369.91
  4969.1  369.41  4972.8  369.91  4992.1  371.85  5049.9  371.31  5057.7  371.82
  5063.8  373.08  5108.0  375.82  5114.1  375.15  5143.5  377.31  5149.7  377.19
  5158.2  378.57  5179.1  378.70  5237.0  382.02  5258.8  383.43  5267.7  385.90
#Mann=8,-1,0
  4369.6    0.12       0  4429.9    0.05       0  4673.7     0.1       0
  4751.0    0.05       0  4792.8     0.1       0  4968.8    0.07       0
  4972.8     0.1       0  5237.0    0.05       0
Bank Sta=4968.8,4972.8
Exp/Cntr=0.3,0.1

Type RM Length L Ch R = 1,3391,175,175,175
BEGIN DESCRIPTION:
Mapping XS 9dd3ccd8
END DESCRIPTION:
XS GIS Cut Line= 3
      2696533.97      6877449.71      2696304.79      6876887.18
      2696026.17      6876762.19
#Sta/Elev= 30
  4388.9  388.43  4453.7  386.93  4525.9  383.07  4531.3  383.38  4555.3  381.82
  4608.8  379.91  4646.7  377.25  4816.9  372.06  4905.8  369.55  4959.8  369.88
  4981.3  369.10  4981.6  368.60  4985.3  369.10  5023.0  369.89  5069.4  369.48
  5098.0  370.73  5115.6  370.29  5137.5  371.57  5154.2  373.55  5181.3  375.55
  5196.2  377.65  5213.9  378.26  5219.4  379.21  5236.1  380.15  5242.6  379.43
  5258.0  380.54  5280.0  384.23  5288.9  384.68  5299.1  387.32  5301.7  387.32
#Mann=5,-1,0
  4388.9    0.05       0  4816.9     0.1       0  4981.3    0.07       0
  4985.3     0.1       0  5154.2    0.05       0
Bank Sta=4981.3,4985.3
Exp/Cntr=0.3,0.1

Type RM Length L Ch R = 1,3216,489,489,489
BEGIN DESCRIPTION:
Williams T2 7.0
END DESCRIPTION:
XS GIS Cut Line= 3
      2696725.99      6877060.99      2696426.00      6876761.00
      2696125.96      6876610.98
#Sta/Elev= 30
  4571.1  385.25  4627.7  381.52  4684.2  379.06  4712.5  376.80  4740.8  376.22
  4752.1  375.15  4811.5  373.13  4882.2  368.10  4896.4  368.83  4967.1  368.34
  4998.1  368.76  5003.7  368.59  5007.3  367.77  5007.6  367.27  5011.1  367.27
  5011.3  367.77  5013.2  368.12  5017.7  368.94  5031.7  368.23  5054.0  369.32
  5076.4  369.45  5115.5  370.64  5137.9  372.15  5160.3  372.45  5188.2  375.11
  5219.0  376.76  5255.3  380.18  5294.4  382.69  5322.4  385.48  5330.8  385.70
#Mann=5,-1,0
  4571.1    0.05       0  4752.1     0.1       0  5007.3    0.07       0
  5011.3     0.1       0  5013.2    0.05       0
Bank Sta=5007.3,5011.3
Exp/Cntr=0.3,0.1

Type RM Length L Ch R = 1,2727,180,180,180
BEGIN DESCRIPTION:
Mapping XS 4edaf20f
END DESCRIPTION:
XS GIS Cut Line= 3
      2696941.60      6876860.91      2696759.29      6876511.49
      2696163.46      6876305.66
#Sta/Elev= 30
  4570.2  385.12  4612.2  384.88  4696.0  381.66  4728.2  379.18  4761.1  378.21
  4766.8  376.88  4783.2  377.63  4788.9  375.63  4805.3  376.39  4855.1  374.11
  4877.2  368.13  4900.6  366.69  4931.0  367.76  4937.8  366.99  4982.4  367.10
  4989.0  366.73  4997.5  364.39  4997.8  363.89  5001.5  364.39  5008.3  365.91
  5020.7  366.48  5084.2  367.69  5122.8  367.34  5139.7  367.53  5243.6  369.78
  5347.5  371.90  5439.6  375.22  5539.0  380.92  5559.0  381.23  5594.7  383.91
#Mann=10,-1,0
  4570.2    0.05       0  4696.0    0.12       0  4900.6     0.1       0
  4997.5    0.07       0  5001.5     0.1       0  5122.8    0.05       0
  5139.7    0.12       0  5243.6     0.1       0  5347.5    0.12       0
  5539.0    0.05       0
Bank Sta=4997.5,5001.5
Exp/Cntr=0.3,0.1

Type RM Length L Ch R = 1,2547,247,247,247
BEGIN DESCRIPTION:
Mapping XS 40360bd9
END DESCRIPTION:
XS GIS Cut Line= 3
      2697021.97      6876715.97      2696865.74      6876375.31
      2696334.05      6876132.25
#Sta/Elev= 30
  4578.9  384.81  4595.4  384.56  4626.0  382.87  4631.5  383.27  4672.0  381.34
  4677.5  381.79  4716.4  380.35  4744.0  378.41  4792.5  375.43  4804.4  373.87
  4849.5  371.65  4872.5  369.38  4892.9  369.03  4978.5  366.32  4986.4  365.19
  4994.0  362.71  4994.3  362.21  4997.8  362.21  4998.0  362.71  5001.5  362.92
  5008.4  365.05  5041.4  366.78  5047.5  366.24  5099.1  365.90  5140.0  366.49
  5340.3  369.57  5409.4  372.04  5461.3  374.87  5465.0  374.87  5538.3  378.41
#Mann=8,-1,0
  4578.9    0.05       0  4744.0    0.12       0  4892.9     0.1       0
  4994.0    0.07       0  4998.0     0.1       0  5140.0    0.05       0
  5461.3    0.12       0  5465.0    0.05       0
Bank Sta=4994,4998
Exp/Cntr=0.3,0.1

Type RM Length L Ch R = 1,2300,648,648,648
BEGIN DESCRIPTION:
Williams T2 5.0
END DESCRIPTION:
XS GIS Cut Line= 3
      2697070.05      6876583.92      2696910.52      6876161.01
      2696675.98      6875785.18
#Sta/Elev= 30
  4548.0  379.42  4600.6  378.23  4605.9  378.94  4670.0  375.96  4685.8  375.23
  4691.2  374.21  4722.1  373.41  4770.9  369.90  4775.6  369.36  4903.8  365.42
  4957.3  365.98  4989.3  364.75  4996.6  362.70  5009.8  362.24  5010.0  361.74
  5013.5  361.74  5013.8  362.24  5017.8  365.27  5023.6  365.08  5069.7  366.75
  5075.6  366.13  5133.4  367.20  5176.8  368.77  5235.8  369.89  5243.1  370.63
  5294.7  372.32  5322.2  374.36  5410.7  377.02  5424.4  378.45  5443.0  379.22
#Mann=7,-1,0
  4548.0    0.05       0  4670.0     0.1       0  4770.9    0.12       0
  4775.6     0.1       0  5009.8    0.07       0  5013.8     0.1       0
  5023.6    0.05       0
Bank Sta=5009.8,5013.8
Exp/Cntr=0.3,0.1

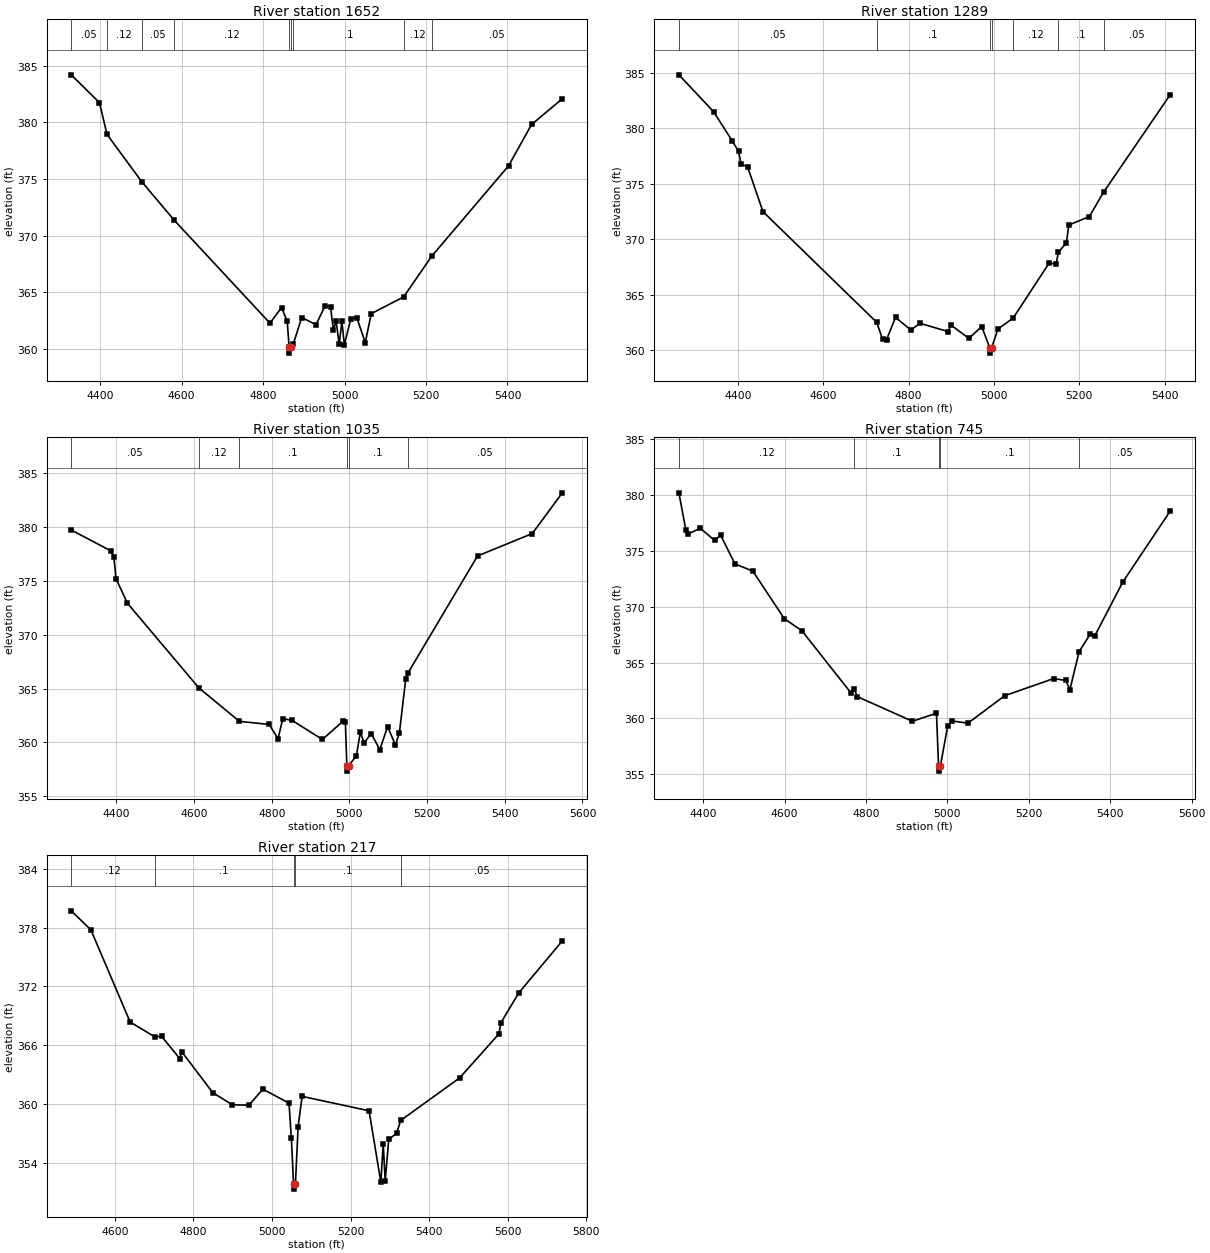
Type RM Length L Ch R = 1,1652,363,363,363
BEGIN DESCRIPTION:
Williams T2 3.0
END DESCRIPTION:
XS GIS Cut Line= 3
      2697754.80      6876430.31      2697313.23      6875925.08
      2696880.40      6875611.29
#Sta/Elev= 30
  4329.0  384.18  4398.3  381.73  4416.8  378.93  4502.0  374.76  4581.6  371.37
  4816.9  362.28  4845.4  363.66  4859.3  362.43  4864.0  360.14  4864.5  359.64
  4868.6  360.14  4874.4  360.47  4894.8  362.78  4929.9  362.15  4951.7  363.77
  4965.6  363.72  4972.6  361.66  4979.2  362.47  4986.8  360.44  4993.5  362.45
  4999.4  360.36  5015.3  362.65  5030.0  362.78  5050.8  360.57  5065.5  363.12
  5145.2  364.60  5213.6  368.17  5402.7  376.16  5459.1  379.80  5534.6  382.07
#Mann=9,-1,0
  4329.0    0.05       0  4416.8    0.12       0  4502.0    0.05       0
  4581.6    0.12       0  4864.0    0.07       0  4868.6    0.12       0
  4874.4     0.1       0  5145.2    0.12       0  5213.6    0.05       0
Bank Sta=4864,4868.6
Exp/Cntr=0.3,0.1

Type RM Length L Ch R = 1,1289,254,254,254
BEGIN DESCRIPTION:
Williams T2 2.0
END DESCRIPTION:
XS GIS Cut Line= 3
      2697849.85      6876309.37      2697446.02      6875691.07
      2697063.66      6875535.50
#Sta/Elev= 30
  4261.5  384.83  4343.2  381.49  4386.2  378.89  4401.3  377.94  4407.3  376.78
  4422.4  376.55  4458.6  372.50  4725.3  362.52  4739.1  360.99  4748.2  360.96
  4769.3  362.97  4805.5  361.83  4826.6  362.44  4892.6  361.69  4899.0  362.29
  4941.2  361.08  4971.4  362.14  4990.2  360.25  4990.7  359.75  4994.8  360.25
  5009.4  361.92  5045.2  362.91  5129.6  367.88  5145.9  367.76  5151.0  368.84
  5170.0  369.70  5175.4  371.29  5223.5  372.05  5256.9  374.24  5412.8  383.01
#Mann=7,-1,0
  4261.5    0.05       0  4725.3     0.1       0  4990.2    0.07       0
  4994.8     0.1       0  5045.2    0.12       0  5151.0     0.1       0
  5256.9    0.05       0
Bank Sta=4990.2,4994.8
Exp/Cntr=0.3,0.1

Type RM Length L Ch R = 1,1035,290,290,290
BEGIN DESCRIPTION:
Mapping XS e2029bd6
END DESCRIPTION:
XS GIS Cut Line= 3
      2697913.32      6876204.83      2697646.41      6875542.98
      2697099.14      6875480.25
#Sta/Elev= 30
  4283.7  379.72  4384.9  377.80  4393.6  377.21  4399.0  375.20  4428.5  372.92
  4611.7  365.09  4716.6  361.96  4793.6  361.67  4816.2  360.34  4828.5  362.22
  4852.7  362.04  4930.5  360.28  4984.2  362.00  4989.6  361.86  4993.4  357.84
  4993.9  357.34  4998.0  357.84  5017.9  358.75  5028.0  360.93  5038.0  359.96
  5055.9  360.83  5078.3  359.34  5098.4  361.48  5118.5  359.75  5128.6  360.87
  5145.1  365.92  5150.1  366.41  5329.9  377.31  5470.8  379.39  5548.2  383.17
#Mann=6,-1,0
  4283.7    0.05       0  4611.7    0.12       0  4716.6     0.1       0
  4993.4    0.07       0  4998.0     0.1       0  5150.1    0.05       0
Bank Sta=4993.4,4998
Exp/Cntr=0.3,0.1

Type RM Length L Ch R = 1,745,528,528,528
BEGIN DESCRIPTION:
Mapping XS 7702aafe
END DESCRIPTION:
XS GIS Cut Line= 3
      2698282.67      6875937.48      2697905.96      6875432.31
      2697330.24      6875408.03
#Sta/Elev= 30
  4340.4  380.22  4357.3  376.92  4363.6  376.53  4392.8  377.05  4428.2  375.95
  4442.8  376.43  4478.2  373.85  4522.1  373.20  4599.2  368.95  4643.0  367.84
  4763.9  362.25  4771.2  362.64  4778.5  361.96  4914.0  359.75  4973.1  360.47
  4978.2  355.78  4978.7  355.28  4982.9  355.78  5000.6  359.31  5010.6  359.78
  5050.6  359.58  5140.7  362.04  5260.8  363.57  5290.8  363.41  5300.8  362.57
  5323.6  366.00  5350.9  367.56  5361.8  367.39  5430.9  372.23  5546.8  378.56
#Mann=5,-1,0
  4340.4    0.12       0  4771.2     0.1       0  4978.2    0.07       0
  4982.9     0.1       0  5323.6    0.05       0
Bank Sta=4978.2,4982.9
Exp/Cntr=0.3,0.1

Type RM Length L Ch R = 1,217,0,0,0
BEGIN DESCRIPTION:
Williams T2 1.0
END DESCRIPTION:
XS GIS Cut Line= 4
      2698326.00      6875710.95      2698333.91      6875271.72
      2698262.30      6875161.04      2697585.26      6875115.47
#Sta/Elev= 30
  4489.0  379.71  4539.0  377.77  4639.0  368.35  4701.4  366.85  4719.0  366.89
  4765.3  364.62  4770.3  365.32  4849.0  361.15  4899.0  359.90  4941.1  359.86
  4976.8  361.50  5043.2  360.07  5049.2  356.49  5054.8  351.79  5055.3  351.29
  5059.5  351.79  5066.4  357.67  5076.5  360.76  5246.9  359.29  5276.9  352.00
  5283.0  355.91  5288.0  352.10  5297.0  356.36  5317.0  356.99  5327.3  358.30
  5477.4  362.65  5577.3  367.14  5582.3  368.27  5627.7  371.32  5738.7  376.64
#Mann=5,-1,0
  4489.0    0.12       0  4701.4     0.1       0  5054.8    0.07       0
  5059.5     0.1       0  5327.3    0.05       0
Bank Sta=5054.8,5059.5
Exp/Cntr=0.3,0.1

Chan Stop Cuts=-1