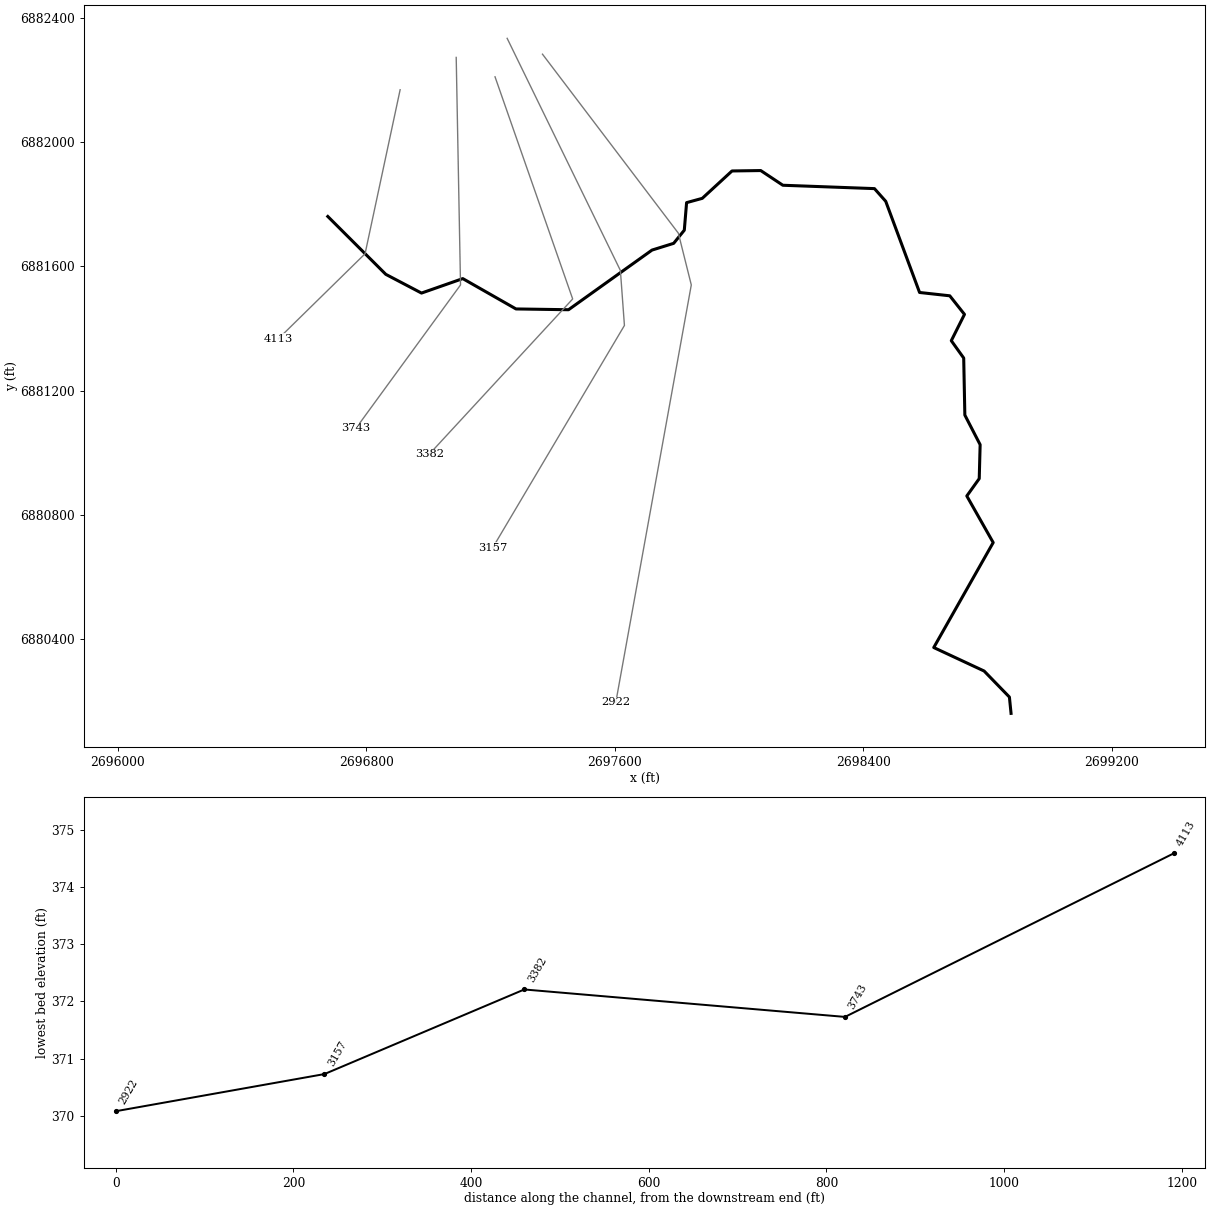
--- Williams T4.prj (project) ---

Proj Title=Williams T4 Base Level Engineering
Current Plan=p01
Default Exp/Contr=0.3,0.1
English Units
Geom File=g01
Flow File=f01
Plan File=p01
BEGIN DESCRIPTION:
Williams T4
END DESCRIPTION:

--- Williams T4.p01 (plan) ---

Plan Title=Multiple Run
Short Identifier=Multiple
Geom File=g01
Flow File=f01
Subcritical Flow
K Sum by GR= 0
Std Step Tol= 0.01
Critical Tol= 0.01
Num of Std Step Trials= 20
Max Error Tol= 0.3
Flow Tol Ratio= 0.001
Split Flow NTrial= 30
Split Flow Tol= 0.02
Split Flow Ratio= 0.02
Log Output Level= 0
Friction Slope Method= 1
Unsteady Friction Slope Method= 2
Unsteady Bridges Friction Slope Method= 1
Parabolic Critical Depth
Global Vel Dist=  1 , 1 , 1
Global Log Level= 0
CheckData=True
Encroach Param= -1, 0, 0, 0
BEGIN DESCRIPTION:
Multiple Run
END DESCRIPTION:

--- Williams T4.f01 (steady flow) ---

Flow Title=Multiple
Number of Profiles=7
Profile Names=10-year,25-year,50-year,1pct_min,100-year,1pct_plu,500-year
River Rch & RM= Williams T4,Reach-1,4113
     534     707     844     500     997    1990    1392
Boundary for River Rch & Prof#=Williams T4,Reach-1,1
Up Type=0
Dn Type=3
Dn Slope=0.005
Boundary for River Rch & Prof#=Williams T4,Reach-1,2
Up Type=0
Dn Type=3
Dn Slope=0.005
Boundary for River Rch & Prof#=Williams T4,Reach-1,3
Up Type=0
Dn Type=3
Dn Slope=0.005
Boundary for River Rch & Prof#=Williams T4,Reach-1,4
Up Type=0
Dn Type=3
Dn Slope=0.005
Boundary for River Rch & Prof#=Williams T4,Reach-1,5
Up Type=0
Dn Type=3
Dn Slope=0.005
Boundary for River Rch & Prof#=Williams T4,Reach-1,6
Up Type=0
Dn Type=3
Dn Slope=0.005
Boundary for River Rch & Prof#=Williams T4,Reach-1,7
Up Type=0
Dn Type=3
Dn Slope=0.005

--- Williams T4.g01 (geometry) ---

Geom Title=Existing Conditions

River Reach=Williams T4,Reach-1
Reach XY= 30
      2696676.00      6881761.00      2696862.78      6881574.62
      2696977.72      6881514.34      2697110.61      6881560.92
      2697281.93      6881463.24      2697451.12      6881460.71
      2697719.98      6881652.81      2697789.62      6881674.47
      2697823.89      6881716.80      2697831.26      6881805.53
      2697881.70      6881819.32      2697977.50      6881907.53
      2698070.02      6881908.84      2698141.22      6881861.52
      2698436.18      6881850.68      2698472.49      6881809.75
      2698581.45      6881516.25      2698678.69      6881505.55
      2698726.05      6881445.78      2698683.59      6881361.01
      2698723.54      6881305.14      2698727.22      6881121.51
      2698776.47      6881026.16      2698773.55      6880916.86
      2698733.53      6880860.99      2698818.50      6880711.00
      2698627.12      6880373.01      2698789.24      6880297.40
      2698870.70      6880213.54      2698876.00      6880161.00

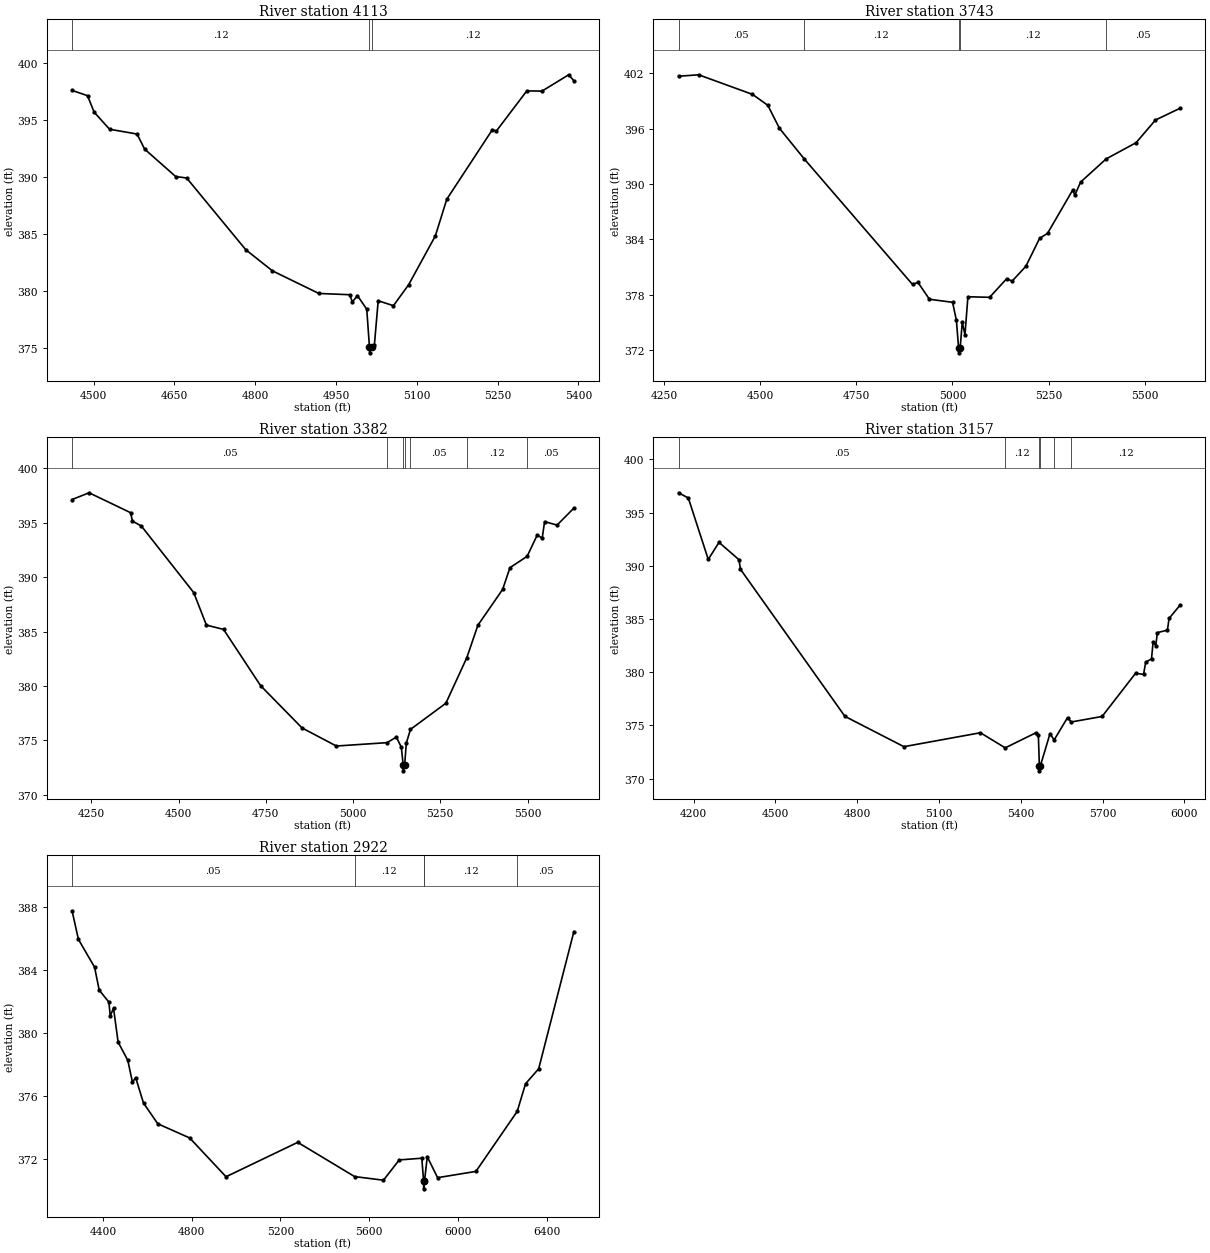
Type RM Length L Ch R = 1,4113,370,370,370
BEGIN DESCRIPTION:
Williams T4 4.0
END DESCRIPTION:
XS GIS Cut Line= 3
      2696908.90      6882169.02      2696795.98      6881640.96
      2696516.54      6881366.90
#Sta/Elev= 30
  4460.0  397.57  4488.7  397.11  4500.9  395.67  4529.6  394.17  4580.7  393.75
  4594.7  392.43  4652.3  390.03  4672.7  389.90  4782.4  383.62  4831.9  381.77
  4918.1  379.79  4975.2  379.68  4980.3  379.05  4989.7  379.60  5007.0  378.41
  5012.0  375.09  5012.3  374.59  5016.0  375.09  5021.2  375.31  5028.2  379.15
  5056.5  378.72  5084.8  380.56  5134.3  384.83  5155.5  388.04  5240.3  394.14
  5247.5  394.01  5304.1  397.53  5332.3  397.51  5381.8  398.94  5391.4  398.42
#Mann=3,-1,0
  4460.0    0.12       0  5012.0    0.07       0  5016.0    0.12       0
Bank Sta=5012,5016
Exp/Cntr=0.3,0.1

Type RM Length L Ch R = 1,3743,361,361,361
BEGIN DESCRIPTION:
Mapping XS 98a29ed3
END DESCRIPTION:
XS GIS Cut Line= 3
      2697089.45      6882273.13      2697103.34      6881540.51
      2696766.55      6881078.73
#Sta/Elev= 30
  4288.1  401.67  4340.2  401.83  4480.3  399.71  4520.3  398.52  4550.3  396.04
  4614.7  392.73  4896.3  379.13  4910.3  379.36  4940.3  377.53  5000.4  377.20
  5010.4  375.24  5016.1  372.23  5016.4  371.73  5020.1  372.23  5025.6  375.06
  5032.6  373.69  5040.3  377.80  5096.7  377.74  5140.7  379.74  5155.4  379.50
  5190.9  381.10  5226.5  384.11  5247.3  384.67  5312.2  389.32  5318.4  388.82
  5333.1  390.21  5399.5  392.72  5477.5  394.48  5527.7  396.93  5592.4  398.22
#Mann=5,-1,0
  4288.1    0.05       0  4614.7    0.12       0  5016.1    0.07       0
  5020.1    0.12       0  5399.5    0.05       0
Bank Sta=5016.1,5020.1
Exp/Cntr=0.3,0.1

Type RM Length L Ch R = 1,3382,225,225,225
BEGIN DESCRIPTION:
Mapping XS 020d68d8
END DESCRIPTION:
XS GIS Cut Line= 3
      2697214.44      6882210.70      2697464.45      6881495.37
      2697002.91      6880995.66
#Sta/Elev= 30
  4194.8  397.14  4243.6  397.76  4362.5  395.93  4367.8  395.16  4393.5  394.70
  4543.4  388.59  4579.8  385.60  4628.8  385.21  4735.0  380.04  4853.9  376.15
  4952.2  374.49  5097.3  374.80  5124.2  375.31  5138.4  374.38  5143.8  372.71
  5144.0  372.21  5147.8  372.71  5152.6  374.75  5164.6  376.02  5266.0  378.42
  5326.1  382.61  5357.8  385.59  5428.7  388.88  5449.7  390.88  5498.9  391.92
  5527.9  393.88  5542.1  393.59  5548.9  395.11  5584.6  394.79  5632.8  396.35
#Mann=7,-1,0
  4194.8    0.05       0  5097.3    0.12       0  5143.8    0.03       0
  5147.8    0.12       0  5164.6    0.05       0  5326.1    0.12       0
  5498.9    0.05       0
Bank Sta=5143.8,5147.8
Exp/Cntr=0.3,0.1

Type RM Length L Ch R = 1,3157,235,235,235
BEGIN DESCRIPTION:
Mapping XS d50bf1f6
END DESCRIPTION:
XS GIS Cut Line= 4
      2697253.50      6882334.57      2697618.10      6881587.13
      2697631.12      6881410.05      2697207.24      6880694.92
#Sta/Elev= 30
  4144.7  396.86  4180.6  396.37  4253.7  390.60  4293.2  392.20  4366.4  390.57
  4371.9  389.67  4755.0  375.85  4971.4  373.00  5251.9  374.31  5342.9  372.89
  5455.0  374.30  5464.4  374.14  5468.2  371.23  5468.4  370.73  5472.2  371.23
  5507.2  374.22  5522.3  373.63  5571.5  375.73  5584.9  375.32  5698.3  375.84
  5821.1  379.90  5850.3  379.79  5858.1  380.93  5879.5  381.26  5885.4  382.84
  5895.2  382.50  5901.0  383.72  5938.0  383.95  5943.8  385.05  5985.2  386.33
#Mann=6,-1,0
  4144.7    0.05       0  5342.9    0.12       0  5468.2    0.04       0
  5472.2    0.12       0  5522.3    0.05       0  5584.9    0.12       0
Bank Sta=5468.2,5472.2
Exp/Cntr=0.3,0.1

Type RM Length L Ch R = 1,2922,0,0,0
BEGIN DESCRIPTION:
Mapping XS 32dbf825
END DESCRIPTION:
XS GIS Cut Line= 4
      2697367.26      6882283.53      2697804.73      6881707.18
      2697846.40      6881540.51      2697603.35      6880196.79
#Sta/Elev= 30
  4261.3  387.78  4289.9  385.96  4362.7  384.19  4383.5  382.73  4427.1  381.97
  4433.4  381.08  4448.0  381.59  4468.8  379.42  4512.4  378.26  4533.3  376.87
  4547.8  377.16  4583.2  375.54  4647.6  374.22  4791.1  373.32  4955.0  370.85
  5278.1  373.04  5534.4  370.86  5664.3  370.63  5735.4  371.92  5837.0  372.03
  5845.2  370.58  5845.5  370.08  5849.2  370.58  5861.8  372.12  5908.2  370.79
  6080.9  371.19  6267.0  375.01  6304.5  376.77  6363.6  377.72  6522.2  386.45
#Mann=5,-1,0
  4261.3    0.05       0  5534.4    0.12       0  5845.2    0.03       0
  5849.2    0.12       0  6267.0    0.05       0
Bank Sta=5845.2,5849.2
Exp/Cntr=0.3,0.1

Chan Stop Cuts=-1