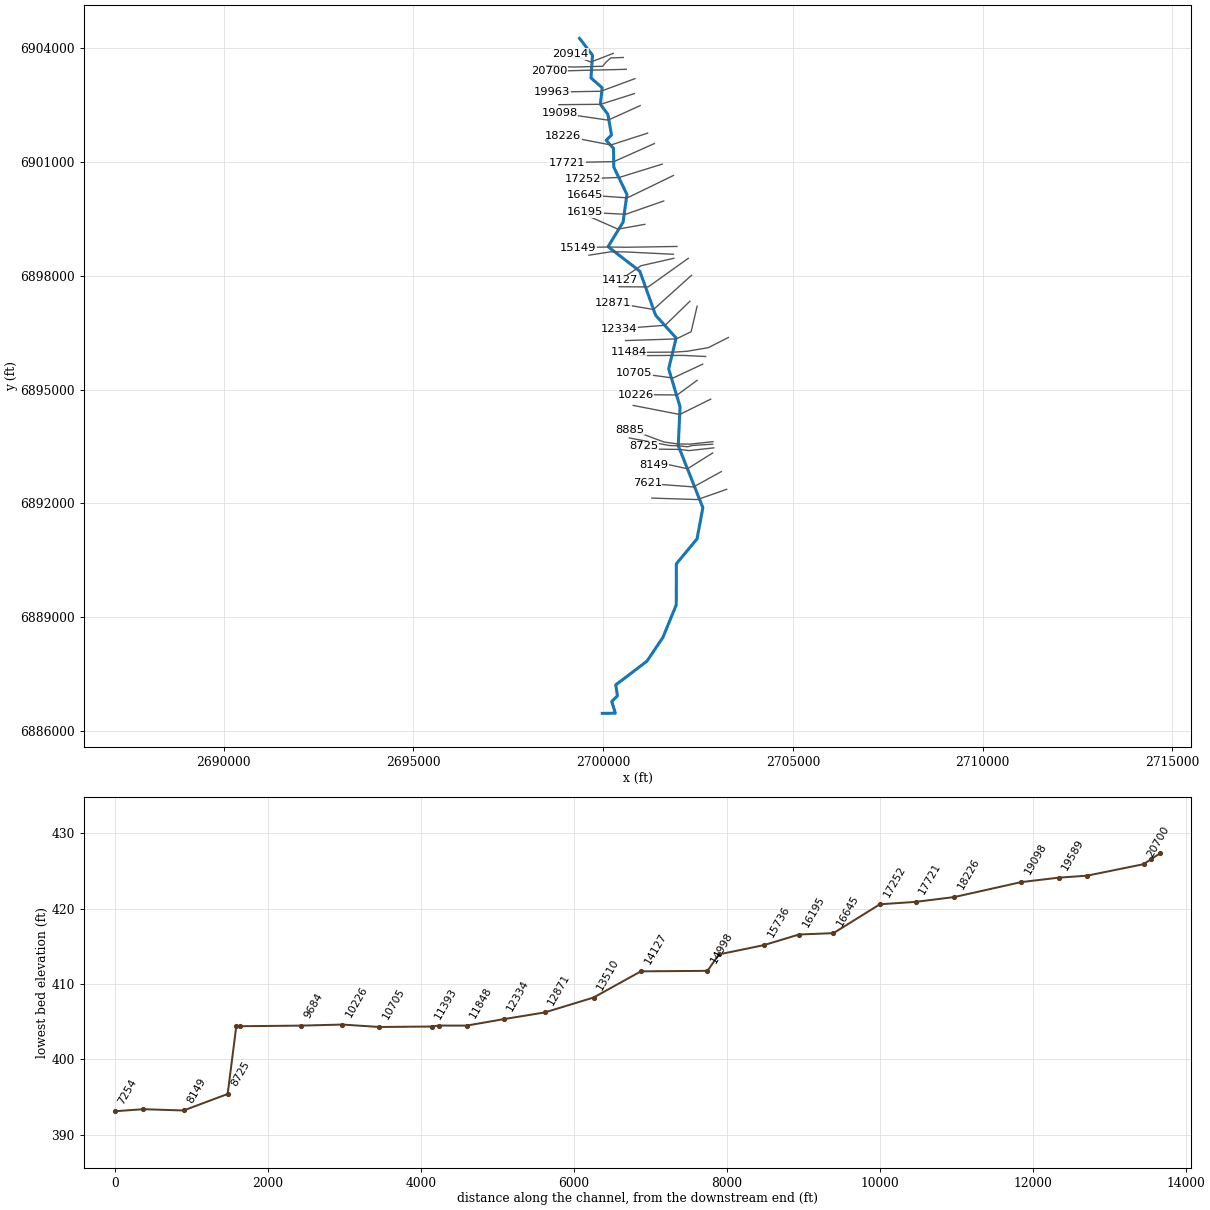
--- Williams T5.prj (project) ---

Proj Title=Williams T5 Base Level Engineering
Current Plan=p01
Default Exp/Contr=0.3,0.1
English Units
Geom File=g01
Flow File=f01
Plan File=p01
Y Axis Title=Elevation
X Axis Title(PF)=Main Channel Distance
X Axis Title(XS)=Station
BEGIN DESCRIPTION:
Williams T5
END DESCRIPTION:
DSS Export Rating Curves= 0
DSS Export Rating Curve Sorted= 0
DSS Export Volume Flow Curves= 0
DXF OffsetX= 0
DXF OffsetY= 0
DXF ScaleX= 1
DXF ScaleY= 10

--- Williams T5.p01 (plan) ---

Plan Title=Multiple Run
Short Identifier=Multiple
Geom File=g01
Flow File=f01
Subcritical Flow
K Sum by GR= 0
Std Step Tol= 0.01
Critical Tol= 0.01
Num of Std Step Trials= 20
Max Error Tol= 0.3
Flow Tol Ratio= 0.001
Split Flow NTrial= 30
Split Flow Tol= 0.02
Split Flow Ratio= 0.02
Log Output Level= 0
Friction Slope Method= 1
Unsteady Friction Slope Method= 2
Unsteady Bridges Friction Slope Method= 1
Parabolic Critical Depth
Global Vel Dist=  1 , 1 , 1
Global Log Level= 0
CheckData=True
Encroach Param= -1, 0, 0, 0
BEGIN DESCRIPTION:
Multiple Run
END DESCRIPTION:

--- Williams T5.f01 (steady flow) ---

Flow Title=Multiple
Number of Profiles=7
Profile Names=10-year,25-year,50-year,1pct_min,100-year,1pct_plu,500-year
River Rch & RM= Williams T5,Reach-1,20914
     755    1015    1225     732    1461    2915    2078
River Rch & RM= Williams T5,Reach-1,18226
     866    1171    1420     852    1699    3390    2434
River Rch & RM= Williams T5,Reach-1,14127
    1098    1500    1829    1103    2201    4392    3188
River Rch & RM= Williams T5,Reach-1,8725
    1176    1610    1966    1186    2366    4722    3432
River Rch & RM= Williams T5,Reach-1,3296
    1361    1882    2315    1407    2806    5599    4128
Boundary for River Rch & Prof#=Williams T5,Reach-1,1
Up Type=0
Dn Type=3
Dn Slope=0.005
Boundary for River Rch & Prof#=Williams T5,Reach-1,2
Up Type=0
Dn Type=3
Dn Slope=0.005
Boundary for River Rch & Prof#=Williams T5,Reach-1,3
Up Type=0
Dn Type=3
Dn Slope=0.005
Boundary for River Rch & Prof#=Williams T5,Reach-1,4
Up Type=0
Dn Type=3
Dn Slope=0.005
Boundary for River Rch & Prof#=Williams T5,Reach-1,5
Up Type=0
Dn Type=3
Dn Slope=0.005
Boundary for River Rch & Prof#=Williams T5,Reach-1,6
Up Type=0
Dn Type=3
Dn Slope=0.005
Boundary for River Rch & Prof#=Williams T5,Reach-1,7
Up Type=0
Dn Type=3
Dn Slope=0.005

--- Williams T5.g01 (geometry) ---

Geom Title=Existing Conditions
Program Version=4.10

River Reach=Williams T5     ,Reach-1
Reach XY= 30
        2699376.        6904261.      2699718.21      6903814.42
      2699677.98      6903216.67      2699972.93      6902959.57
      2699926.93      6902521.48      2700122.25      6902259.45
       2700218.8       6901710.7      2700077.12      6901573.09
      2700272.45      6901359.53      2700278.26      6900866.94
      2700625.49      6900145.79      2700522.39       6899412.5
      2700128.23      6898766.93      2700965.47      6898120.77
      2701381.52      6896958.57      2701922.26      6896359.47
      2701725.28      6895545.94      2702025.48      6894545.78
      2701977.22       6893521.5      2702626.21      6891886.09
      2702472.24      6891062.56      2701928.06      6890405.14
      2701924.78       6889321.5      2701572.38       6888462.5
      2701149.82      6887834.13      2700331.45      6887213.47
      2700374.83      6886923.01      2700225.21      6886776.08
      2700320.62      6886466.18        2699976.        6886461.

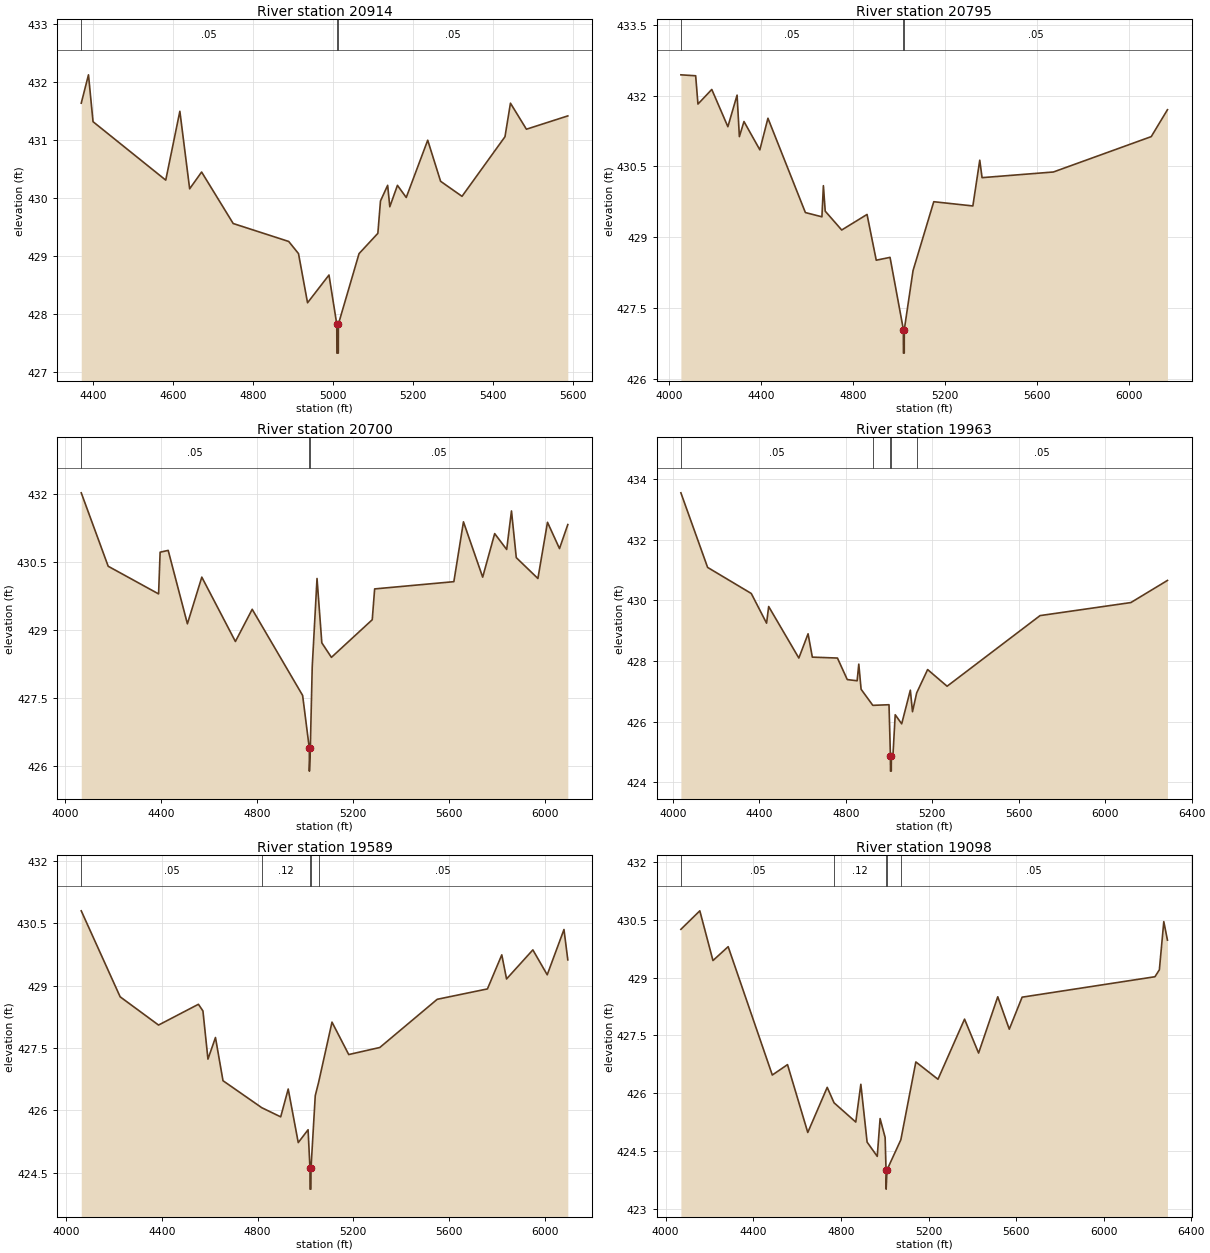
Type RM Length L Ch R = 1 ,20914   ,119,119,119
BEGIN DESCRIPTION:
Williams T5 28.0
END DESCRIPTION:
XS GIS Cut Line= 3
       2700263.5      6903864.26      2699675.98      6903636.01
      2699129.59      6903848.93
#Sta/Elev= 30
  4369.7  431.64  4387.8  432.13  4399.2  431.32    4581  430.31  4616.3   431.5
  4640.8  430.16  4670.7  430.45  4749.7  429.56  4888.5  429.25    4913  429.04
  4935.6  428.19  4989.2  428.67  5008.7  427.82    5009  427.32  5012.5  427.32
  5012.7  427.82  5064.4  429.04  5111.4  429.39    5118  429.95  5135.9  430.22
  5141.3  429.85  5160.4  430.22  5182.4  430.01  5236.1     431  5268.3  430.29
  5321.9  430.03  5429.3  431.06    5443  431.64  5482.9  431.19  5586.4  431.42
#Mann= 3 ,-1 , 0
  4369.7     .05       0  5008.7     .04       0  5012.7     .05       0
Bank Sta=5008.7,5012.7
XS Rating Curve= 0 ,0
Exp/Cntr=0.3,0.1

Type RM Length L Ch R = 1 ,20795   ,95,95,95
BEGIN DESCRIPTION:
Mapping XS f25879b9
END DESCRIPTION:
XS GIS Cut Line= 6
      2700530.19      6903756.19      2700200.29      6903745.34
      2700078.76      6903639.01      2699985.45      6903523.99
      2699236.75      6903504.46      2698510.37      6903528.31
#Sta/Elev= 30
  4050.6  432.44  4114.8  432.42  4124.8  431.82  4184.9  432.13  4254.9  431.34
  4294.9  432.01  4304.9  431.13  4324.9  431.45  4393.9  430.85  4429.1  431.52
  4591.9  429.52  4663.8  429.43  4670.2  430.09  4678.1  429.55  4749.8  429.15
    4860  429.48    4900  428.51    4960  428.57    5018  427.04  5018.2  426.54
  5021.7  426.54    5022  427.04    5060  428.29  5150.1  429.75  5320.1  429.66
  5350.1  430.63  5360.1  430.26  5670.3  430.38  6095.7  431.13  6166.2   431.7
#Mann= 3 ,-1 , 0
  4050.6     .05       0    5018     .03       0    5022     .05       0
Bank Sta=5018,5022
XS Rating Curve= 0 ,0
Exp/Cntr=0.3,0.1

Type RM Length L Ch R = 1 ,20700   ,737,737,737
BEGIN DESCRIPTION:
Mapping XS bc620d7e
END DESCRIPTION:
XS GIS Cut Line= 3
      2700608.24      6903443.69      2699677.29      6903421.99
      2698581.41      6903391.61
#Sta/Elev= 30
  4067.5  432.03  4179.8  430.41  4389.8   429.8  4396.2  430.72  4429.8  430.76
  4509.9  429.14  4569.9  430.17  4709.9  428.75  4779.9  429.46    4990  427.56
    5018  426.39  5018.2  425.89    5022  426.39    5030  428.19    5050  430.14
    5070  428.72    5110   428.4  5280.1  429.23  5290.1  429.91  5620.2  430.07
  5660.2  431.39  5740.3  430.17  5790.3  431.13  5840.3  430.78  5860.3  431.63
  5880.3   430.6  5970.4  430.14  6010.4  431.38  6060.4   430.8    6095  431.33
#Mann= 3 ,-1 , 0
  4067.5     .05       0    5018     .03       0    5022     .05       0
Bank Sta=5018,5022
XS Rating Curve= 0 ,0
Exp/Cntr=0.3,0.1

Type RM Length L Ch R = 1 ,19963   ,374,374,374
BEGIN DESCRIPTION:
Mapping XS 3d8f8196
END DESCRIPTION:
XS GIS Cut Line= 3
      2700837.71      6903198.63      2699938.36      6902865.28
      2698646.67      6902844.45
#Sta/Elev= 30
    4037  433.55  4160.6  431.09  4362.6  430.23  4433.4  429.25  4443.1   429.8
  4582.7   428.1  4625.4   428.9  4645.1  428.13  4761.3   428.1  4806.7  427.39
  4852.4  427.35    4860   427.9  4870.7  427.07  4924.9  426.54  4999.8  426.56
  5006.4  424.87  5006.7  424.37  5010.3  424.37  5010.6  424.87  5018.5  424.95
  5028.5  426.23  5058.5  425.93  5098.5  427.04  5108.5  426.33  5127.8  426.95
  5178.5  427.72  5268.5  427.17  5698.6   429.5  6118.6  429.93    6288  430.66
#Mann= 5 ,-1 , 0
    4037     .05       0  4924.9     .12       0  5006.4     .07       0
  5010.6     .12       0  5127.8     .05       0
Bank Sta=5006.4,5010.6
XS Rating Curve= 0 ,0
Exp/Cntr=0.3,0.1

Type RM Length L Ch R = 1 ,19589   ,491,491,491
BEGIN DESCRIPTION:
Mapping XS 9b0102d8
END DESCRIPTION:
XS GIS Cut Line= 3
      2700821.13      6902802.98      2699933.15      6902521.75
      2698829.95      6902511.34
#Sta/Elev= 30
  4062.3   430.8    4225  428.73  4385.6  428.05  4552.3  428.55  4571.2  428.39
  4592.2  427.23  4623.6  427.75  4655.1  426.71  4817.3  426.06  4896.4  425.84
  4927.8  426.51  4969.8  425.22  5010.9  425.53  5018.8   424.6  5019.1   424.1
  5022.7   424.1  5023.1   424.6  5040.9  426.35  5054.9  426.67  5110.9  428.12
  5180.9  427.34  5310.9  427.51  5550.9  428.67  5760.9  428.92  5820.9  429.74
  5840.9  429.16  5950.9  429.86  6010.9  429.26    6081  430.35    6097  429.62
#Mann= 5 ,-1 , 0
  4062.3     .05       0  4817.3     .12       0  5018.8     .07       0
  5023.1     .12       0  5054.9     .05       0
Bank Sta=5018.8,5023.1
XS Rating Curve= 0 ,0
Exp/Cntr=0.3,0.1

Type RM Length L Ch R = 1 ,19098   ,872,872,872
BEGIN DESCRIPTION:
Mapping XS bda4608f
END DESCRIPTION:
XS GIS Cut Line= 3
       2700974.8      6902486.09      2700128.46      6902104.15
       2698849.5      6902290.58
#Sta/Elev= 30
  4069.5  430.25  4155.9  430.73  4215.9  429.44  4285.3   429.8  4486.8  426.47
  4556.2  426.74  4648.7  424.98  4737.4  426.15  4768.6  425.75  4867.8  425.25
  4890.9  426.23  4919.5  424.73  4965.8  424.36  4978.8  425.34  5001.8  424.85
  5005.9  424.01  5006.4  423.51  5010.4  424.01  5073.5  424.79    5142  426.81
    5243  426.36  5364.3  427.92  5428.4  427.04  5515.9   428.5  5568.5  427.66
  5627.1  428.49  6233.4  429.02  6253.6   429.2  6273.8  430.45  6290.5  429.97
#Mann= 5 ,-1 , 0
  4069.5     .05       0  4768.6     .12       0  5005.9     .07       0
  5010.4     .12       0  5073.5     .05       0
Bank Sta=5005.9,5010.4
XS Rating Curve= 0 ,0
Exp/Cntr=0.3,0.1

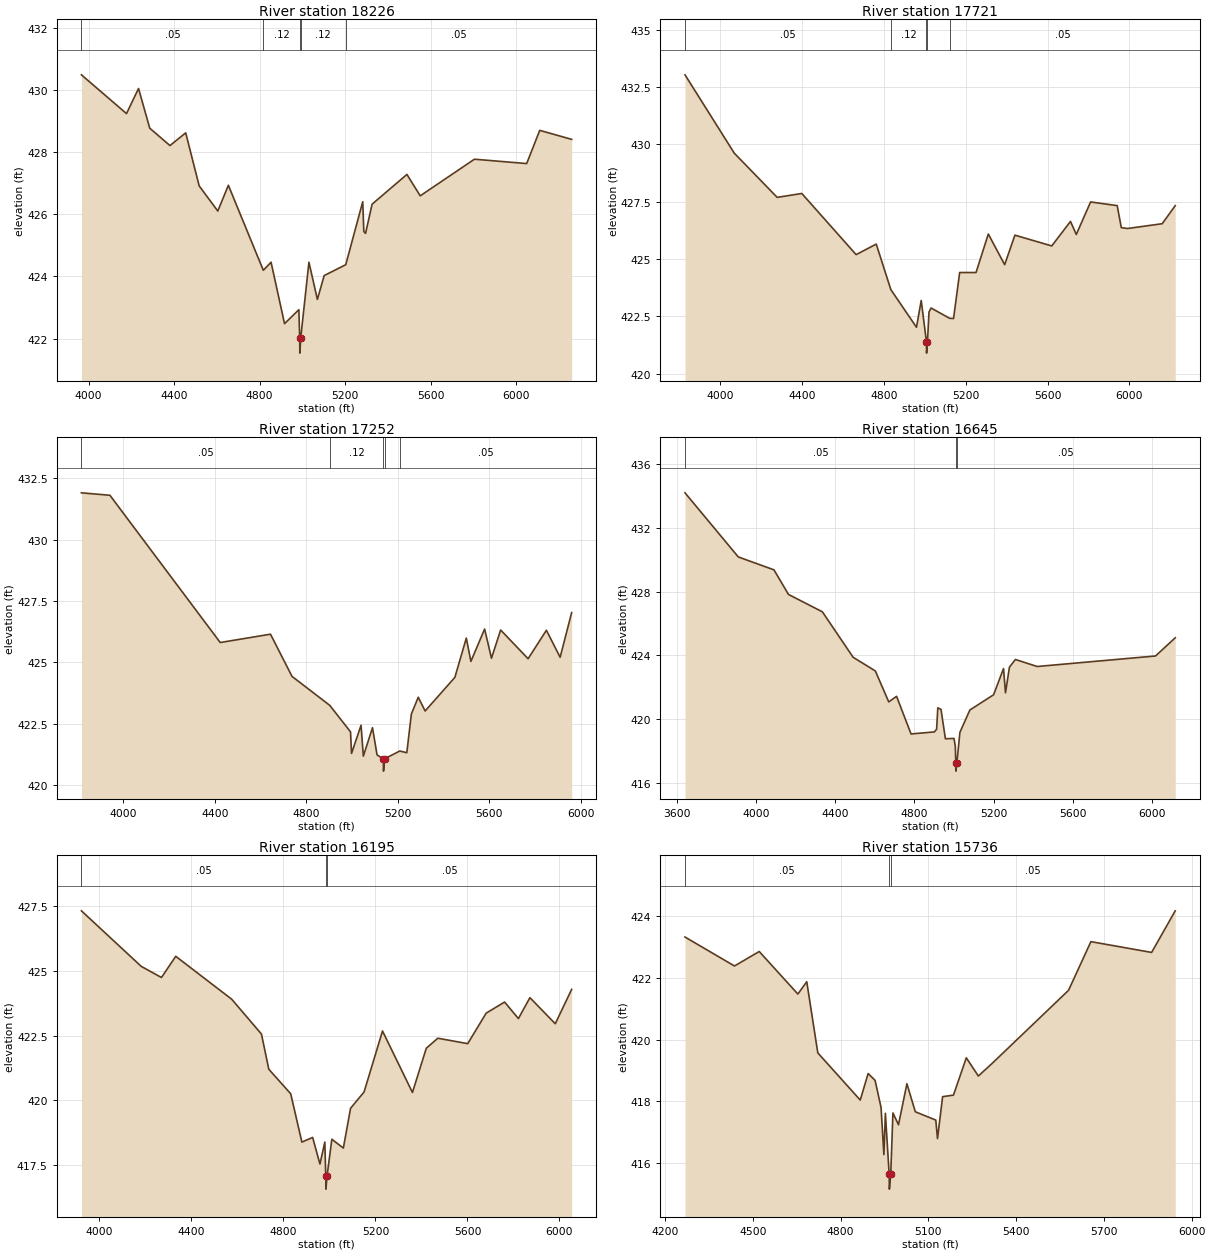
Type RM Length L Ch R = 1 ,18226   ,505,505,505
BEGIN DESCRIPTION:
Mapping XS 3ab04f9a
END DESCRIPTION:
XS GIS Cut Line= 3
      2701170.16      6901761.28      2700202.25      6901448.77
      2698949.47      6901691.52
#Sta/Elev= 30
  3966.8   430.5  4177.7  429.25  4233.9  430.06  4286.4  428.78    4381  428.22
  4454.6  428.63  4517.6  426.92  4604.7  426.11  4654.2  426.94  4817.6   424.2
  4853.9  424.46  4916.9  422.48  4983.9  422.93  4987.8  422.03  4988.4  421.53
  4992.8  422.03    5031  424.46  5070.6  423.26  5102.3  424.03  5203.3  424.38
  5282.7  426.41  5287.8  425.45  5295.9  425.39  5326.4  426.33  5489.4  427.29
  5551.6   426.6  5805.2  427.78  6049.6  427.64  6110.7  428.71    6260  428.42
#Mann= 5 ,-1 , 0
  3966.8     .05       0  4817.6     .12       0  4987.8     .07       0
  4992.8     .12       0  5203.3     .05       0
Bank Sta=4987.8,4992.8
XS Rating Curve= 0 ,0
Exp/Cntr=0.3,0.1

Type RM Length L Ch R = 1 ,17721   ,469,469,469
BEGIN DESCRIPTION:
Mapping XS a59db92b
END DESCRIPTION:
XS GIS Cut Line= 3
      2701347.53      6901485.82      2700281.53      6901010.11
       2699052.4      6900985.81
#Sta/Elev= 30
  3827.5  433.04  4068.5  429.62  4278.1  427.69  4398.6  427.86  4664.1  425.19
  4762.5  425.65    4834  423.66  4959.2  422.02  4982.4  423.19  5007.8  421.39
  5008.5  420.89  5012.9  421.39  5020.4  422.68  5030.4  422.86  5121.2  422.41
  5140.4   422.4  5170.4  424.41  5250.4  424.41  5310.4  426.09  5390.4  424.75
  5440.4  426.04  5620.5  425.57  5712.1  426.64  5740.5  426.07  5810.5  427.49
  5940.5  427.33  5960.5  426.37  5990.6  426.33  6160.6  426.54  6224.2  427.33
#Mann= 5 ,-1 , 0
  3827.5     .05       0    4834     .12       0  5007.8     .07       0
  5012.9     .12       0  5121.2     .05       0
Bank Sta=5007.8,5012.9
XS Rating Curve= 0 ,0
Exp/Cntr=0.3,0.1

Type RM Length L Ch R = 1 ,17252   ,607,607,607
BEGIN DESCRIPTION:
Mapping XS a3dd47e9
END DESCRIPTION:
XS GIS Cut Line= 3
      2701555.86      6900944.15      2700423.89      6900593.45
       2699465.6      6900555.26
#Sta/Elev= 30
  3816.9  431.91  3941.5  431.81    4424  425.81  4643.8  426.15    4738  424.43
    4903  423.25  4993.9  422.17  4998.2  421.29  5039.9  422.44  5049.9  421.18
  5089.9  422.34  5109.9  421.23  5137.4  421.07  5138.1  420.57  5142.5  421.07
  5209.3  421.39    5240  421.32    5260   422.9  5290.1  423.58  5320.1  423.02
  5450.2  424.39  5500.2  425.99  5520.3  425.04  5580.3  426.36  5610.3  425.17
  5650.4  426.32  5770.5  425.15  5850.5  426.31  5910.6  425.21    5961  427.03
#Mann= 5 ,-1 , 0
  3816.9     .05       0    4903     .12       0  5137.4     .07       0
  5142.5     .12       0  5209.3     .05       0
Bank Sta=5137.4,5142.5
XS Rating Curve= 0 ,0
Exp/Cntr=0.3,0.1

Type RM Length L Ch R = 1 ,16645   ,450,450,450
BEGIN DESCRIPTION:
Mapping XS 88107439
END DESCRIPTION:
XS GIS Cut Line= 3
      2701851.18      6900645.02      2700635.87      6900054.73
      2699509.24      6900132.73
#Sta/Elev= 30
  3639.1  434.19  3908.8  430.17  4089.3  429.36  4162.6  427.82  4334.1  426.73
  4489.8  423.88  4602.3  423.02    4670  421.08  4709.6  421.43  4782.8  419.07
  4901.2   419.2  4912.2  419.37  4918.2  420.71  4934.4  420.61  4956.7  418.77
  5000.1  418.79  5006.8   418.3  5009.2  417.24  5009.9  416.74  5014.5  417.24
  5030.1  419.17  5080.3  420.57  5200.6  421.53  5250.7  423.17  5260.7  421.65
  5280.7  423.26  5310.8  423.74  5421.1   423.3  6019.8  423.96  6119.5   425.1
#Mann= 3 ,-1 , 0
  3639.1     .05       0  5009.2     .04       0  5014.5     .05       0
Bank Sta=5009.2,5014.5
XS Rating Curve= 0 ,0
Exp/Cntr=0.3,0.1

Type RM Length L Ch R = 1 ,16195   ,459,459,459
BEGIN DESCRIPTION:
Mapping XS 46204338
END DESCRIPTION:
XS GIS Cut Line= 3
      2701595.07      6899972.27      2700588.13       6899620.7
      2699524.78      6899677.13
#Sta/Elev= 30
  3921.5  427.33  4181.6  425.18  4269.5  424.75  4331.6  425.57  4574.8  423.91
  4704.3  422.56  4736.1   421.2  4831.4  420.25    4880  418.38  4926.8  418.56
  4958.5  417.53  4979.7  418.38  4983.8  417.06  4984.6  416.56  4989.3  417.06
  5010.2  418.49  5060.3  418.15  5091.7  419.69  5150.4  420.32  5230.5  422.68
  5360.7   420.3  5420.8  422.01  5470.9   422.4    5601  422.19  5681.2  423.37
  5761.3   423.8  5821.4  423.16  5871.4  423.97  5981.6  422.96  6052.9  424.29
#Mann= 3 ,-1 , 0
  3921.5     .05       0  4983.8     .04       0  4989.3     .05       0
Bank Sta=4983.8,4989.3
XS Rating Curve= 0 ,0
Exp/Cntr=0.3,0.1

Type RM Length L Ch R = 1 ,15736   ,587,587,587
BEGIN DESCRIPTION:
Mapping XS 33b56278
END DESCRIPTION:
XS GIS Cut Line= 3
      2701095.89      6899355.94      2700388.47      6899230.08
      2699512.18      6899616.17
#Sta/Elev= 30
  4267.8  423.33    4437  422.39  4521.6  422.86  4653.7  421.48  4684.1  421.88
  4721.9  419.57    4867  418.04  4893.9   418.9  4917.7  418.68  4938.1   417.8
  4947.8  416.27  4952.9  417.61  4965.8  415.65  4966.6  415.15  4971.3  415.65
  4978.7  417.62  4997.8  417.24  5026.5  418.57  5055.3  417.66  5125.3  417.39
  5131.1  416.79  5148.6  418.15  5185.7   418.2  5229.6  419.41  5270.8  418.82
  5316.9  419.22  5579.1   421.6  5655.6  423.18  5863.2  422.83  5943.9  424.18
#Mann= 3 ,-1 , 0
  4267.8     .05       0  4965.8     .04       0  4971.3     .05       0
Bank Sta=4965.8,4971.3
XS Rating Curve= 0 ,0
Exp/Cntr=0.3,0.1

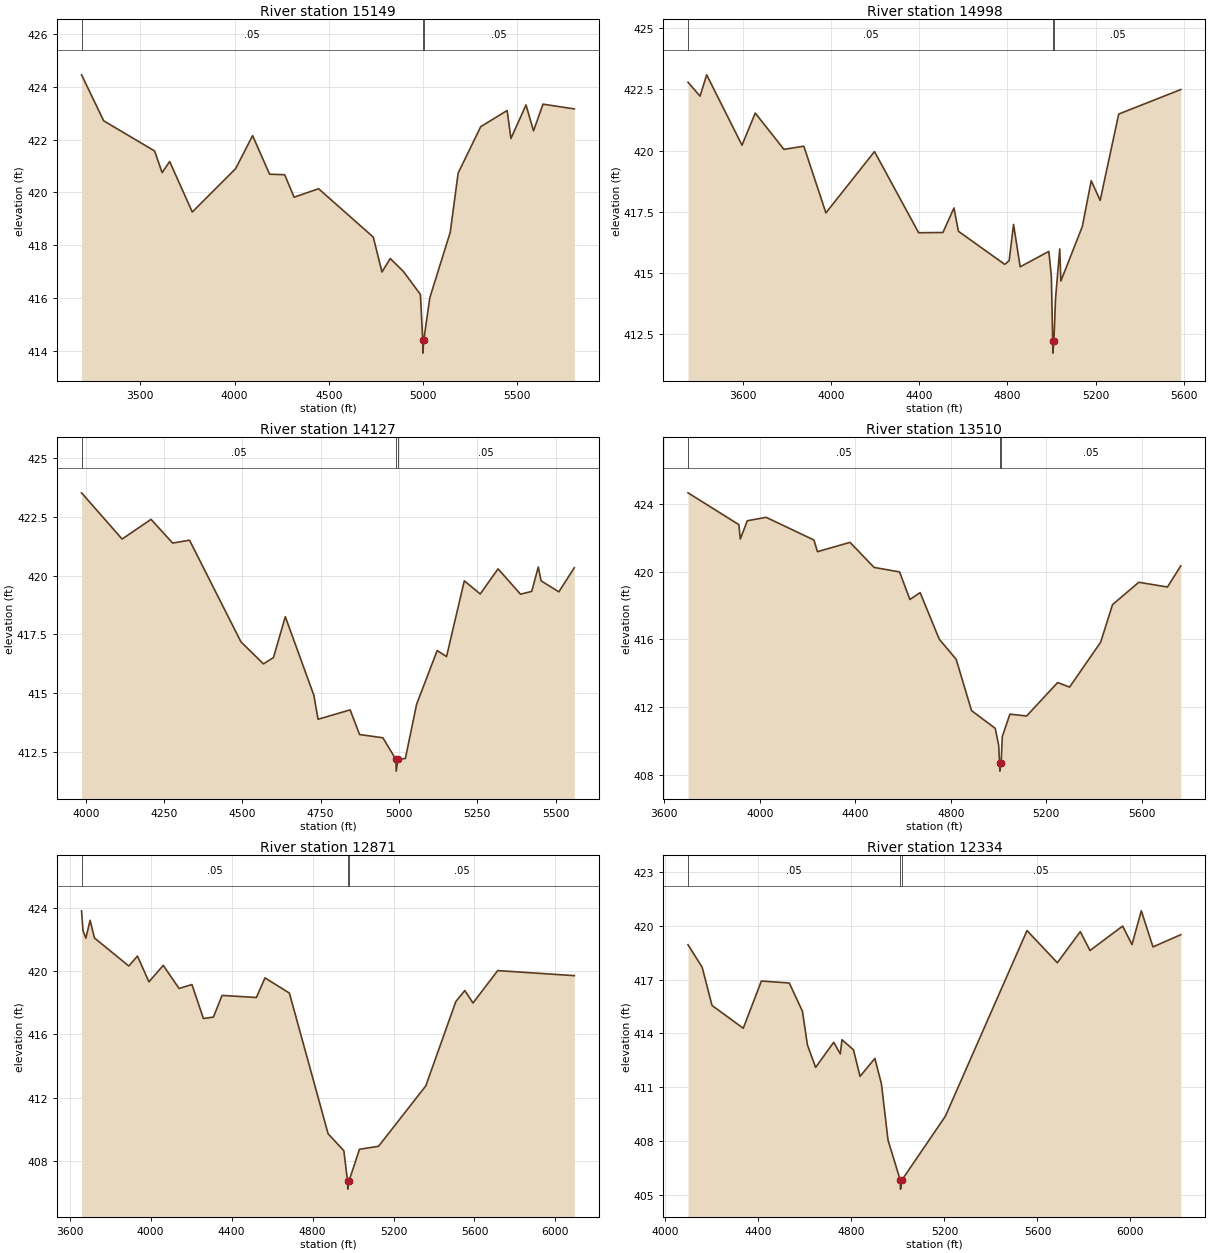
Type RM Length L Ch R = 1 ,15149   ,151,151,151
BEGIN DESCRIPTION:
Mapping XS 987624b9
END DESCRIPTION:
XS GIS Cut Line= 4
      2701943.34      6898773.05      2700609.97      6898752.21
       2700130.8      6898759.16      2699329.84      6898741.82
#Sta/Elev= 30
  3187.9  424.45  3305.3  422.71  3575.3  421.57  3615.3  420.75  3655.3  421.17
  3775.3  419.26  4005.3   420.9  4095.3  422.15  4185.4  420.69  4265.4  420.67
  4315.4  419.82  4445.4  420.14  4735.4  418.31  4781.5  416.99  4825.4   417.5
  4895.4  417.01  4985.4  416.14  4997.7  414.42  4998.6  413.92  5003.3  414.42
  5035.5  416.02  5143.6  418.49  5185.5  420.73  5305.5  422.49  5445.6   423.1
  5465.6  422.04  5545.6  423.31  5585.6  422.33  5635.6  423.34  5801.8  423.16
#Mann= 3 ,-1 , 0
  3187.9     .05       0  4997.7     .04       0  5003.3     .05       0
Bank Sta=4997.7,5003.3
XS Rating Curve= 0 ,0
Exp/Cntr=0.3,0.1

Type RM Length L Ch R = 1 ,14998   ,871,871,871
BEGIN DESCRIPTION:
Mapping XS 0323e099
END DESCRIPTION:
XS GIS Cut Line= 4
      2701850.47      6898566.97      2700569.17      6898629.47
      2700208.06      6898632.94      2699624.75      6898542.67
#Sta/Elev= 30
    3352  422.79  3406.5  422.22  3436.6  423.09  3596.8  420.22  3656.8  421.53
    3787  420.05  3877.1  420.18  3977.2  417.46  4197.5  419.96  4397.7  416.65
  4507.8  416.66  4557.9  417.66  4577.9  416.71    4788  415.36    4808  415.51
    4828  416.99    4858  415.26    4988  415.89  4999.5  414.87  5005.4  412.24
  5006.2  411.74    5011  412.24  5018.3  413.96  5037.4  415.99  5042.5  414.68
  5139.7   416.9  5180.2  418.77  5220.7  417.97  5304.8  421.49  5586.2  422.49
#Mann= 3 ,-1 , 0
    3352     .05       0  5005.4     .04       0    5011     .05       0
Bank Sta=5005.4,5011
XS Rating Curve= 0 ,0
Exp/Cntr=0.3,0.1

Type RM Length L Ch R = 1 ,14127   ,617,617,617
BEGIN DESCRIPTION:
Mapping XS 12afeeb1
END DESCRIPTION:
XS GIS Cut Line= 3
      2701862.25      6898461.08      2700992.44      6898263.15
      2700430.45      6897878.09
#Sta/Elev= 30
  3986.7  423.53  4116.2  421.56  4208.5   422.4  4277.6  421.39  4331.5  421.51
  4495.6  417.18  4567.4  416.24  4599.4  416.51  4637.3  418.25  4728.5   414.9
  4741.8  413.88  4844.3  414.28  4874.4  413.23  4948.9  413.09  4990.3  412.17
  4991.4  411.67  4996.8  412.17  5020.6  412.21  5056.5  414.52  5122.2  416.81
    5152  416.55  5208.8  419.78  5259.6  419.22  5316.5  420.29  5388.2  419.21
  5424.1  419.33    5445  420.37  5453.9  419.78  5510.7  419.31    5560  420.34
#Mann= 3 ,-1 , 0
  3986.7     .05       0  4990.3     .04       0  4996.8     .05       0
Bank Sta=4990.3,4996.8
XS Rating Curve= 0 ,0
Exp/Cntr=0.3,0.1

Type RM Length L Ch R = 1 ,13510   ,639,639,639
BEGIN DESCRIPTION:
Mapping XS cd89f18b
END DESCRIPTION:
XS GIS Cut Line= 3
       2702242.4      6898461.05      2701185.14      6897705.86
      2700420.23      6897711.06
#Sta/Elev= 30
  3699.2  424.66  3912.1  422.78  3918.2  421.93  3947.7  423.01  4026.6  423.21
  4226.7  421.87  4241.4  421.18  4377.8  421.73  4478.6  420.25  4585.5  419.98
  4628.7  418.35  4671.6  418.76  4751.4  416.01  4822.7  414.81  4886.8  411.78
  4986.2  410.73  5000.5  409.74  5004.3   408.7  5005.4   408.2  5010.9   408.7
  5015.8  410.25  5047.6  411.57  5117.6  411.46  5247.6  413.44  5297.6  413.17
  5427.6  415.82  5477.6  418.05  5587.6  419.37  5707.6  419.09  5763.4  420.34
#Mann= 3 ,-1 , 0
  3699.2     .05       0  5004.3     .04       0  5010.9     .05       0
Bank Sta=5004.3,5010.9
XS Rating Curve= 0 ,0
Exp/Cntr=0.3,0.1

Type RM Length L Ch R = 1 ,12871   ,537,537,537
BEGIN DESCRIPTION:
Williams T5 21.0
END DESCRIPTION:
XS GIS Cut Line= 3
      2702325.98      6898010.98        2701326.        6897111.
      2700252.89       6897294.4
#Sta/Elev= 30
  3659.1  423.82  3666.2  422.57  3680.4  422.09  3701.3  423.22    3723   422.1
  3892.6  420.33  3935.2  420.96    3992  419.33  4062.7  420.37  4140.8  418.91
  4204.3  419.16  4261.1  417.01  4310.4   417.1  4353.1  418.47  4522.7  418.34
  4565.3  419.58  4685.7  418.62    4877  409.72  4954.7  408.65  4973.1  406.72
  4974.2  406.22  4979.7  406.72    5032  408.74  5126.2  408.93  5359.5  412.75
  5507.8  418.08  5552.3  418.78  5592.8  417.99  5714.6  420.04  6093.1  419.72
#Mann= 3 ,-1 , 0
  3659.1     .05       0  4973.1     .04       0  4979.7     .05       0
Bank Sta=4973.1,4979.7
XS Rating Curve= 0 ,0
Exp/Cntr=0.3,0.1

Type RM Length L Ch R = 1 ,12334   ,486,486,486
BEGIN DESCRIPTION:
Mapping XS 2f1244f5
END DESCRIPTION:
XS GIS Cut Line= 3
      2702284.39      6897328.54      2701633.35      6896694.87
       2700426.8      6896603.72
#Sta/Elev= 30
  4097.7  418.94  4158.5  417.69  4200.9  415.56  4335.2  414.29  4413.1  416.92
  4533.2  416.81  4589.8  415.23  4611.1  413.36  4646.4  412.11  4724.1  413.51
  4752.4  412.86  4759.6  413.65    4809  413.09  4837.3  411.61    4901  412.61
  4929.3  411.19  4957.6  408.06  5010.2  405.83  5011.3  405.33  5016.9  405.83
  5204.1  409.39  5555.1  419.73  5685.5  417.94  5784.2  419.67  5825.9  418.62
  5966.3  419.98  6006.4  418.95  6046.5  420.83  6096.7  418.82  6216.2   419.5
#Mann= 3 ,-1 , 0
  4097.7     .05       0  5010.2     .04       0  5016.9     .05       0
Bank Sta=5010.2,5016.9
XS Rating Curve= 0 ,0
Exp/Cntr=0.3,0.1

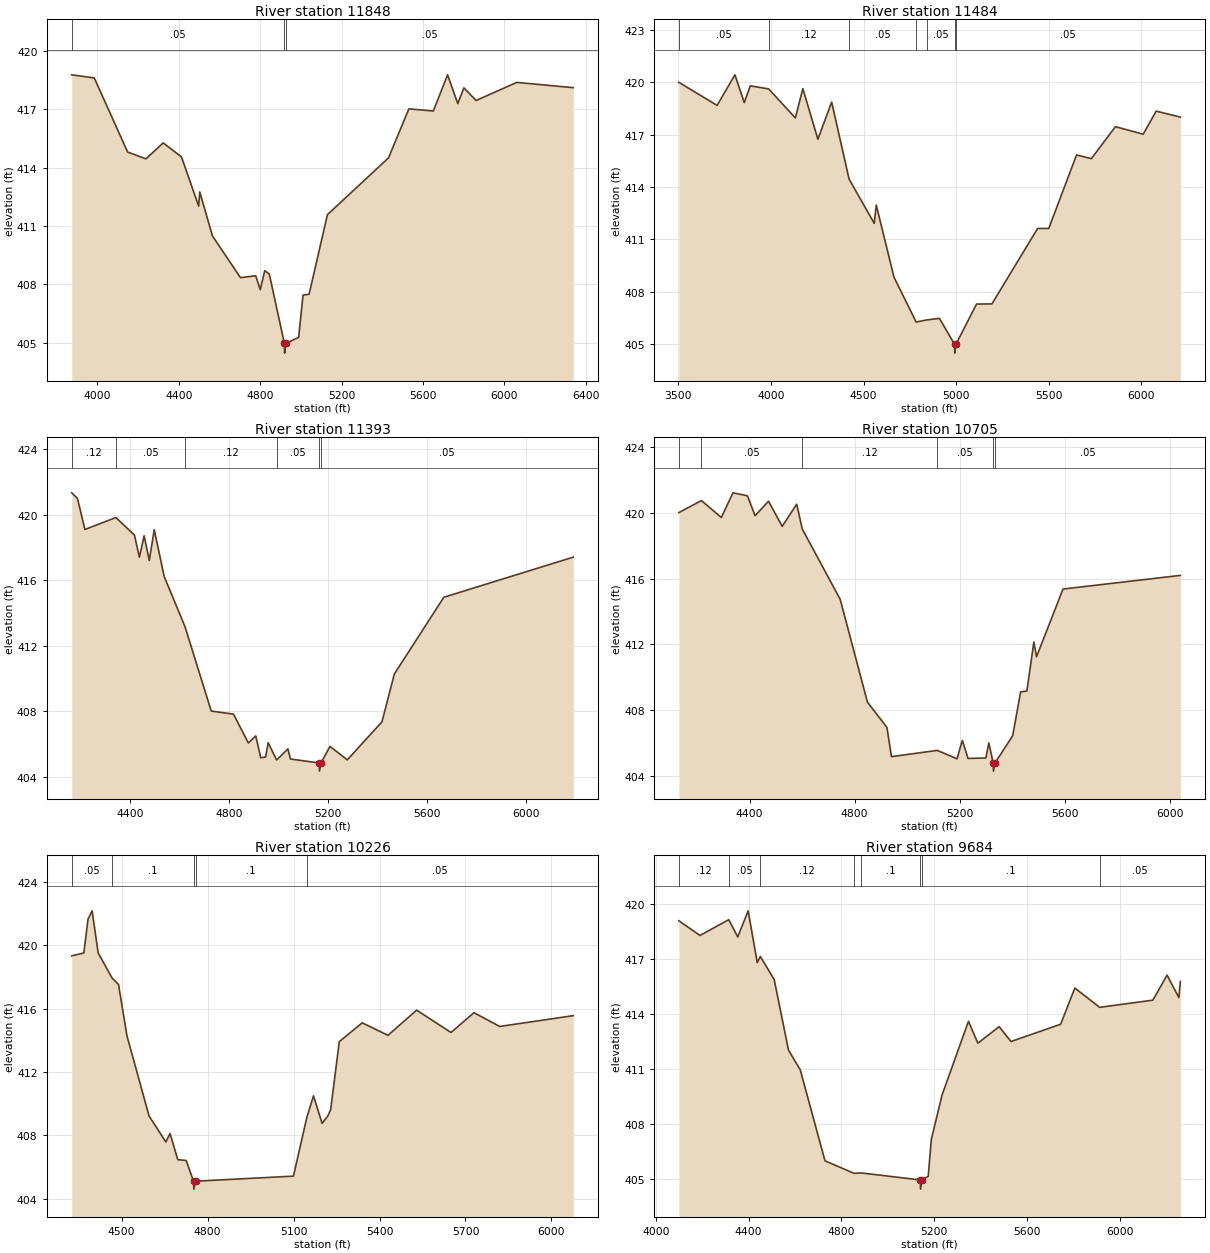
Type RM Length L Ch R = 1 ,11848   ,364,364,364
BEGIN DESCRIPTION:
Mapping XS cc6a4e35
END DESCRIPTION:
XS GIS Cut Line= 4
      2702475.35      6897198.29      2702316.36       6896524.4
      2701924.15      6896334.62      2700589.16      6896291.28
#Sta/Elev= 30
  3874.2  418.78  3984.9  418.62  4148.8  414.81  4238.9  414.46  4323.5  415.28
  4413.3  414.56  4497.9  412.03  4503.1  412.76  4565.8  410.49  4703.3  408.35
  4778.1  408.45  4800.3  407.73  4822.5  408.71  4844.7  408.54    4919  404.97
  4920.1  404.47  4925.9  404.97  4989.1  405.28  5010.5  407.45  5040.5   407.5
  5130.5  411.59  5430.7  414.51  5530.7  417.03  5650.8  416.92  5720.8  418.78
  5770.9   417.3  5800.9  418.11  5860.9  417.46    6061  418.39    6338  418.12
#Mann= 3 ,-1 , 0
  3874.2     .05       0    4919     .03       0  4925.9     .05       0
Bank Sta=4919,4925.9
XS Rating Curve= 0 ,0
Exp/Cntr=0.3,0.1

Type RM Length L Ch R = 1 ,11484   ,91,91,91
BEGIN DESCRIPTION:
Mapping XS f3d755f2
END DESCRIPTION:
XS GIS Cut Line= 5
      2703300.02      6896373.68       2702770.5      6896104.59
      2702210.61       6896009.1      2701880.75       6895987.4
       2700665.5      6895978.72
#Sta/Elev= 30
  3502.8  419.99  3709.2  418.67  3805.6  420.42  3855.8  418.83  3888.7  419.79
  3988.1  419.61  4131.8  417.95  4172.3  419.63  4253.5  416.73  4327.9  418.86
  4421.9  414.45  4557.8  411.91  4568.6  412.96  4664.5  408.83  4783.9  406.26
  4840.7  406.38  4909.9  406.47  4991.6  404.98  4992.7  404.48  4998.8  404.98
  5110.1  407.29  5193.2   407.3  5440.1  411.62  5500.1  411.62  5650.1  415.83
  5730.1  415.62  5860.1  417.45  6010.1  417.02  6080.1  418.34  6210.6     418
#Mann= 7 ,-1 , 0
  3502.8     .05       0  3988.1     .12       0  4421.9     .05       0
  4783.9     .12       0  4840.7     .05       0  4991.6     .03       0
  4998.8     .05       0
Bank Sta=4991.6,4998.8
XS Rating Curve= 0 ,0
Exp/Cntr=0.3,0.1

Type RM Length L Ch R = 1 ,11393   ,688,688,688
BEGIN DESCRIPTION:
Mapping XS c61bd962
END DESCRIPTION:
XS GIS Cut Line= 4
      2702699.09      6895871.12      2702128.79      6895899.76
      2701860.56      6895899.76      2700673.04      6895891.95
#Sta/Elev= 30
  4164.1  421.35  4187.2  421.01  4217.3  419.11  4342.6  419.84  4417.5  418.77
  4437.5  417.42  4456.7  418.73  4477.6  417.22  4497.6   419.1  4537.7  416.24
  4622.2  413.16  4727.9  408.02  4817.9  407.83  4877.9  406.07  4907.9   406.5
  4927.9  405.17  4947.9  405.21  4957.9  406.09  4992.3  405.03  5037.9  405.71
  5047.9  405.09  5164.3  404.85  5165.4  404.35  5171.5  404.85  5207.9  405.86
  5277.9  405.04  5417.9  407.36  5467.9  410.28  5667.9  414.97  6190.9  417.42
#Mann= 6 ,-1 , 0
  4164.1     .12       0  4342.6     .05       0  4622.2     .12       0
  4992.3     .05       0  5164.3     .03       0  5171.5     .05       0
Bank Sta=5164.3,5171.5
XS Rating Curve= 0 ,0
Exp/Cntr=0.3,0.1

Type RM Length L Ch R = 1 ,10705   ,479,479,479
BEGIN DESCRIPTION:
Mapping XS 7ce60165
END DESCRIPTION:
XS GIS Cut Line= 3
      2702622.61      6895669.34      2701841.35      6895304.75
      2700803.14      6895443.64
#Sta/Elev= 30
  4130.5  420.01  4216.4  420.74  4292.3  419.71  4336.4  421.21  4391.6  421.03
  4420.7  419.82  4471.9   420.7    4524  419.17  4579.2  420.52  4600.4  419.01
  4744.7  414.74  4848.7  408.48  4922.8  406.95  4940.1  405.17  5114.3  405.55
  5189.7  405.04  5209.9  406.16  5231.7  405.06  5299.7  405.09  5310.8  406.01
  5327.3  404.79  5328.4  404.29  5334.7  404.79  5401.6  406.44  5431.9  409.11
  5455.8  409.16  5482.3  412.14  5492.4  411.24  5593.3  415.36  6040.1  416.19
#Mann= 6 ,-1 , 0
  4130.5     .12       0  4216.4     .05       0  4600.4     .12       0
  5114.3     .05       0  5327.3     .03       0  5334.7     .05       0
Bank Sta=5327.3,5334.7
XS Rating Curve= 0 ,0
Exp/Cntr=0.3,0.1

Type RM Length L Ch R = 1 ,10226   ,542,542,542
BEGIN DESCRIPTION:
Mapping XS 67f960d1
END DESCRIPTION:
XS GIS Cut Line= 3
      2702473.27      6895242.24      2701948.99      6894856.84
      2700849.64      6894867.24
#Sta/Elev= 30
  4325.9  419.34  4368.1  419.52  4382.7  421.65    4397  422.18  4418.2  419.52
  4466.7  417.94  4489.2  417.53  4518.5   414.3  4595.7  409.23  4654.3  407.59
    4669  408.12    4696  406.47  4725.3  406.42  4750.9  405.11    4752  404.61
  4758.4  405.11  5099.6  405.43  5145.9   409.1  5169.6   410.5  5199.6  408.76
  5219.6  409.23  5229.6  409.63  5259.6  413.92  5339.6  415.11  5429.6  414.32
  5529.6  415.91  5649.6   414.5  5729.6  415.75  5819.6  414.88    6076  415.56
#Mann= 5 ,-1 , 0
  4325.9     .05       0  4466.7      .1       0  4750.9     .03       0
  4758.4      .1       0  5145.9     .05       0
Bank Sta=4750.9,4758.4
XS Rating Curve= 0 ,0
Exp/Cntr=0.3,0.1

Type RM Length L Ch R = 1 ,9684    ,799,799,799
BEGIN DESCRIPTION:
Mapping XS a2b28681
END DESCRIPTION:
XS GIS Cut Line= 3
      2702832.89      6894746.24      2702016.93       6894342.6
      2700789.82      6894581.08
#Sta/Elev= 30
  4099.8  419.07  4190.9  418.27  4314.7  419.13  4353.5  418.19  4398.3  419.61
  4437.6  416.79  4450.6  417.13  4510.5  415.87  4572.2  412.03  4622.7  410.96
  4729.3  406.01  4854.4  405.33  4885.7  405.35  5139.7  404.97  5140.9  404.47
  5147.3  404.97  5174.1  405.17  5187.3  407.17  5233.9   409.6  5347.4   413.6
    5388  412.41  5479.7  413.31  5530.6   412.5  5744.6  413.44  5805.7  415.41
  5912.4  414.36  6141.8  414.75    6203  416.11  6253.9  414.89  6260.2  415.77
#Mann= 8 ,-1 , 0
  4099.8     .12       0  4314.7     .05       0  4450.6     .12       0
  4854.4     .05       0  4885.7      .1       0  5139.7     .03       0
  5147.3      .1       0  5912.4     .05       0
Bank Sta=5139.7,5147.3
XS Rating Curve= 0 ,0
Exp/Cntr=0.3,0.1

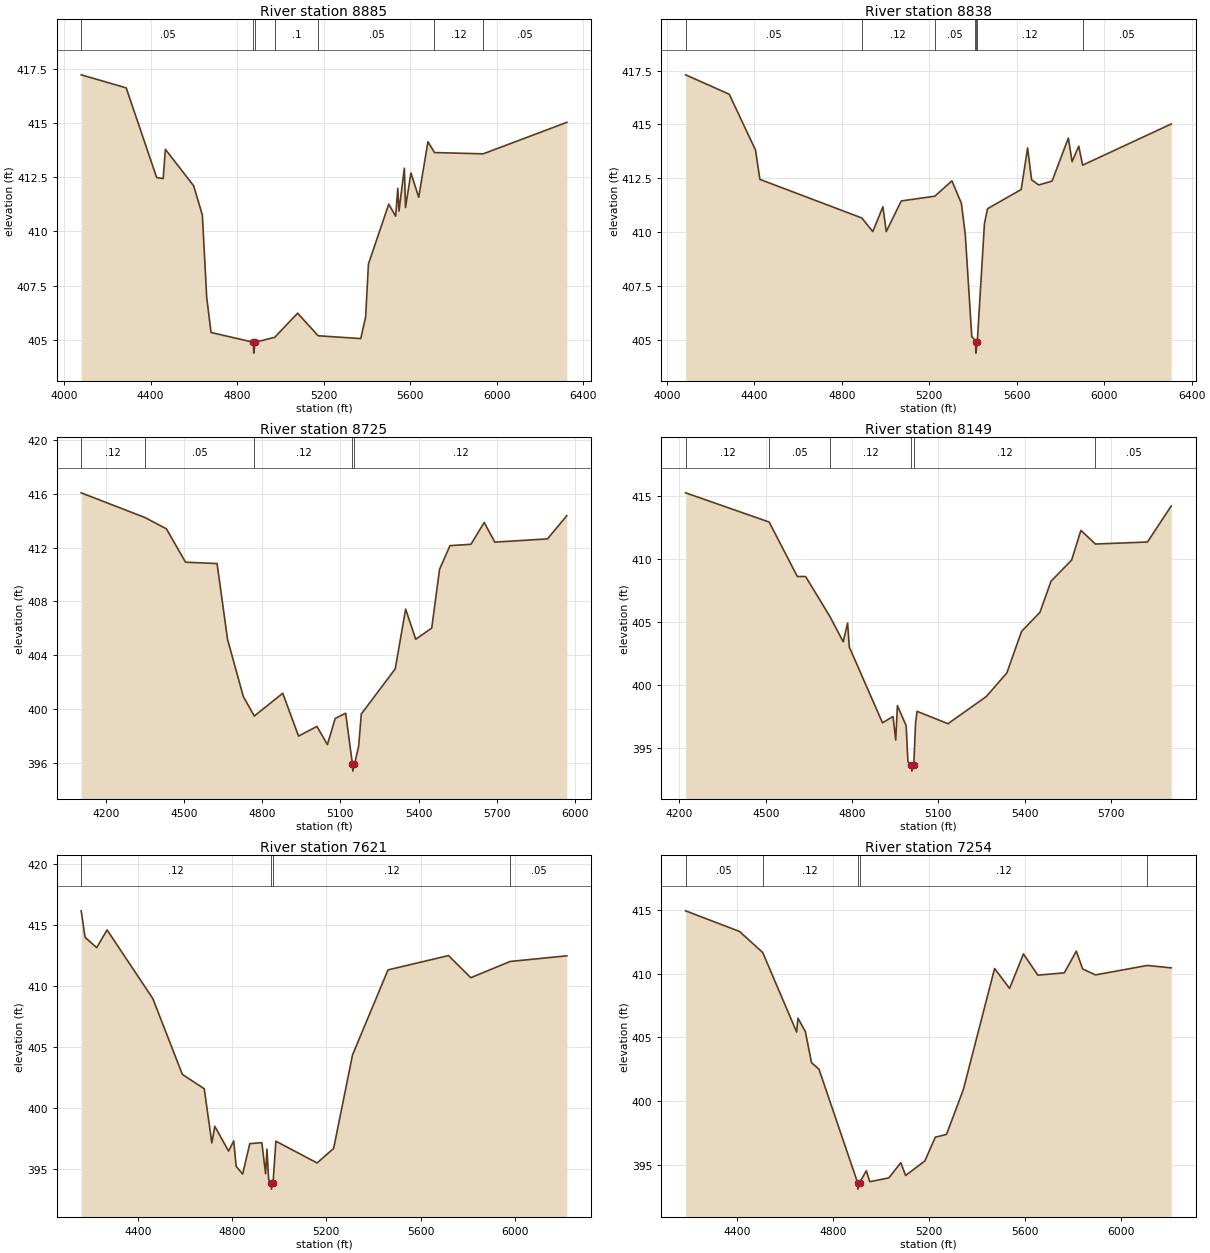
Type RM Length L Ch R = 1 ,8885    ,47,47,47
BEGIN DESCRIPTION:
Mapping XS 7165cbda
END DESCRIPTION:
XS GIS Cut Line= 5
      2702892.82      6893626.46      2702301.65      6893561.35
      2701978.74      6893563.96      2701603.74      6893616.04
      2700714.16      6893946.38
#Sta/Elev= 30
  4079.2  417.21  4287.3  416.61  4428.1  412.48  4458.3  412.43  4468.4  413.78
  4599.1   412.1  4639.4  410.75  4659.5  406.96  4679.6  405.34  4875.7  404.89
  4876.9  404.39  4883.4  404.89  4974.2  405.12  5079.9  406.23  5174.8  405.19
  5371.7  405.06  5394.4  406.06  5407.2  408.49  5501.1  411.25  5533.1   410.7
    5543  411.98  5548.4  410.93  5573.4  412.91  5578.7   411.1  5603.8  412.69
  5639.7  411.57  5682.4  414.13  5712.7  413.63  5937.8  413.57  6324.4  415.02
#Mann= 7 ,-1 , 0
  4079.2     .05       0  4875.7     .03       0  4883.4     .05       0
  4974.2      .1       0  5174.8     .05       0  5712.7     .12       0
  5937.8     .05       0
Bank Sta=4875.7,4883.4
XS Rating Curve= 0 ,0
Exp/Cntr=0.3,0.1

Type RM Length L Ch R = 1 ,8838    ,113,113,113
BEGIN DESCRIPTION:
Mapping XS 607d25d7
END DESCRIPTION:
XS GIS Cut Line= 6
      2702885.01      6893558.75      2702356.34       6893527.5
      2702223.53      6893491.04      2701978.74      6893517.08
      2701739.15      6893524.89      2700690.33      6893722.69
#Sta/Elev= 30
    4086   417.3  4285.4   416.4  4405.6  413.81  4425.6  412.45  4891.5  410.66
  4941.9  410.03  4988.2  411.18  5003.4  410.03  5072.2  411.45  5225.4  411.67
  5303.7  412.38    5347  411.34  5364.9  409.88  5394.6  405.15  5407.5  405.02
  5411.9  404.89  5413.1  404.39  5419.6  404.89  5452.4  410.39  5466.6  411.09
  5620.5  411.98  5649.8  413.91  5668.1  412.43  5700.6  412.19  5761.7  412.37
  5836.2  414.37  5853.2  413.27  5883.7  413.99  5901.4  413.11  6306.6  415.02
#Mann= 7 ,-1 , 0
    4086     .05       0  4891.5     .12       0  5225.4     .05       0
  5407.5     .12       0  5411.9     .05       0  5419.6     .12       0
  5901.4     .05       0
Bank Sta=5411.9,5419.6
XS Rating Curve= 0 ,0
Exp/Cntr=0.3,0.1

Type RM Length L Ch R = 1 ,8725    ,576,576,576
BEGIN DESCRIPTION:
Mapping XS e5cb3499
END DESCRIPTION:
XS GIS Cut Line= 5
      2702913.67       6893462.4      2702259.99      6893389.48
      2702025.61      6893420.73      2701444.88      6893428.54
       2701064.7      6893498.85
#Sta/Elev= 30
  4106.3  416.06  4350.3  414.23  4432.8  413.39  4506.4  410.91  4627.2  410.81
  4667.4  405.18  4727.8  400.94  4769.9  399.49    4879  401.18  4939.6     398
  5010.1  398.72  5050.1  397.37  5080.1  399.31  5120.1   399.7  5146.3   395.9
  5147.5   395.4    5154   395.9  5170.1  397.27  5180.1  399.64  5310.1  402.99
  5350.1  407.43  5388.8  405.19  5450.1  406.02  5480.1  410.38  5520.1  412.14
  5600.5  412.24  5651.3  413.86    5692   412.4  5893.8  412.64  5967.9  414.36
#Mann= 5 ,-1 , 0
  4106.3     .12       0  4350.3     .05       0  4769.9     .12       0
  5146.3     .05       0    5154     .12       0
Bank Sta=5146.3,5154
XS Rating Curve= 0 ,0
Exp/Cntr=0.3,0.1

Type RM Length L Ch R = 1 ,8149    ,528,528,528
BEGIN DESCRIPTION:
Mapping XS 62e9b763
END DESCRIPTION:
XS GIS Cut Line= 4
      2702884.55      6893327.84      2702223.09      6892911.18
      2701611.11      6893043.99      2701332.51      6893017.95
#Sta/Elev= 30
  4221.6  415.22  4511.9  412.91  4609.9   408.6  4638.6   408.6  4724.1   405.4
  4769.3  403.44  4784.6  404.92  4790.5  403.02  4905.9  397.03  4942.4  397.53
  4951.8  395.67  4957.7  398.39  4988.1   396.8  4994.2  393.97  5006.6  393.71
  5007.8  393.21  5014.6  393.71  5020.8  397.01    5026  397.94  5133.4  396.96
  5266.7  399.11  5338.1  400.98  5389.2  404.26  5453.1  405.77  5491.6  408.23
  5563.2   409.9  5595.4  412.25  5645.9  411.17  5826.7  411.33  5909.4  414.18
#Mann= 6 ,-1 , 0
  4221.6     .12       0  4511.9     .05       0  4724.1     .12       0
  5006.6     .05       0  5014.6     .12       0  5645.9     .05       0
Bank Sta=5006.6,5014.6
XS Rating Curve= 0 ,0
Exp/Cntr=0.3,0.1

Type RM Length L Ch R = 1 ,7621    ,367,367,367
BEGIN DESCRIPTION:
Mapping XS 0e4f84ed
END DESCRIPTION:
XS GIS Cut Line= 3
      2703112.09      6892835.84       2702380.3      6892432.18
      2701159.93      6892523.26
#Sta/Elev= 30
  4160.3  416.14  4176.8  413.97  4226.1  413.13    4270  414.58  4464.2  408.96
  4589.4  402.76  4682.2  401.59  4714.4  397.16  4726.9  398.52  4785.4  396.49
  4807.2  397.32  4817.5  395.25    4845  394.61  4875.3   397.1  4926.4  397.18
  4942.4  394.64  4948.1  396.66  4955.3  394.18  4965.9  393.88  4967.1  393.38
  4973.9  393.88    4986   397.3  5160.8  395.52    5231  396.71  5311.1  404.36
  5461.6  411.31  5718.3  412.48  5812.6  410.67    5980     412  6219.8  412.46
#Mann= 4 ,-1 , 0
  4160.3     .12       0  4965.9     .05       0  4973.9     .12       0
    5980     .05       0
Bank Sta=4965.9,4973.9
XS Rating Curve= 0 ,0
Exp/Cntr=0.3,0.1

Type RM Length L Ch R = 1 ,7254    ,631,631,631
BEGIN DESCRIPTION:
Mapping XS 09659a86
END DESCRIPTION:
XS GIS Cut Line= 3
      2703255.28      6892369.68      2702484.46      6892098.85
      2701281.31      6892137.91
#Sta/Elev= 30
  4186.3  414.92    4411   413.3  4507.2  411.65  4648.3  405.42  4653.6  406.51
  4684.5  405.46  4710.2  403.02  4741.2  402.51  4902.2  393.61  4903.4  393.11
  4910.3  393.61  4938.1  394.55  4952.8  393.69  5031.8  393.99  5081.8  395.18
  5101.8  394.18  5181.9  395.32  5225.3  397.18  5271.9   397.4    5342  400.91
    5472   410.4  5534.4  408.84  5592.1  411.54  5652.1  409.88  5762.2  410.06
  5812.2  411.76  5838.6  410.36  5892.2   409.9  6107.5  410.64  6207.1  410.45
#Mann= 5 ,-1 , 0
  4186.3     .05       0  4507.2     .12       0  4902.2     .05       0
  4910.3     .12       0  6107.5     .05       0
Bank Sta=4902.2,4910.3
XS Rating Curve= 0 ,0
Exp/Cntr=0.3,0.1