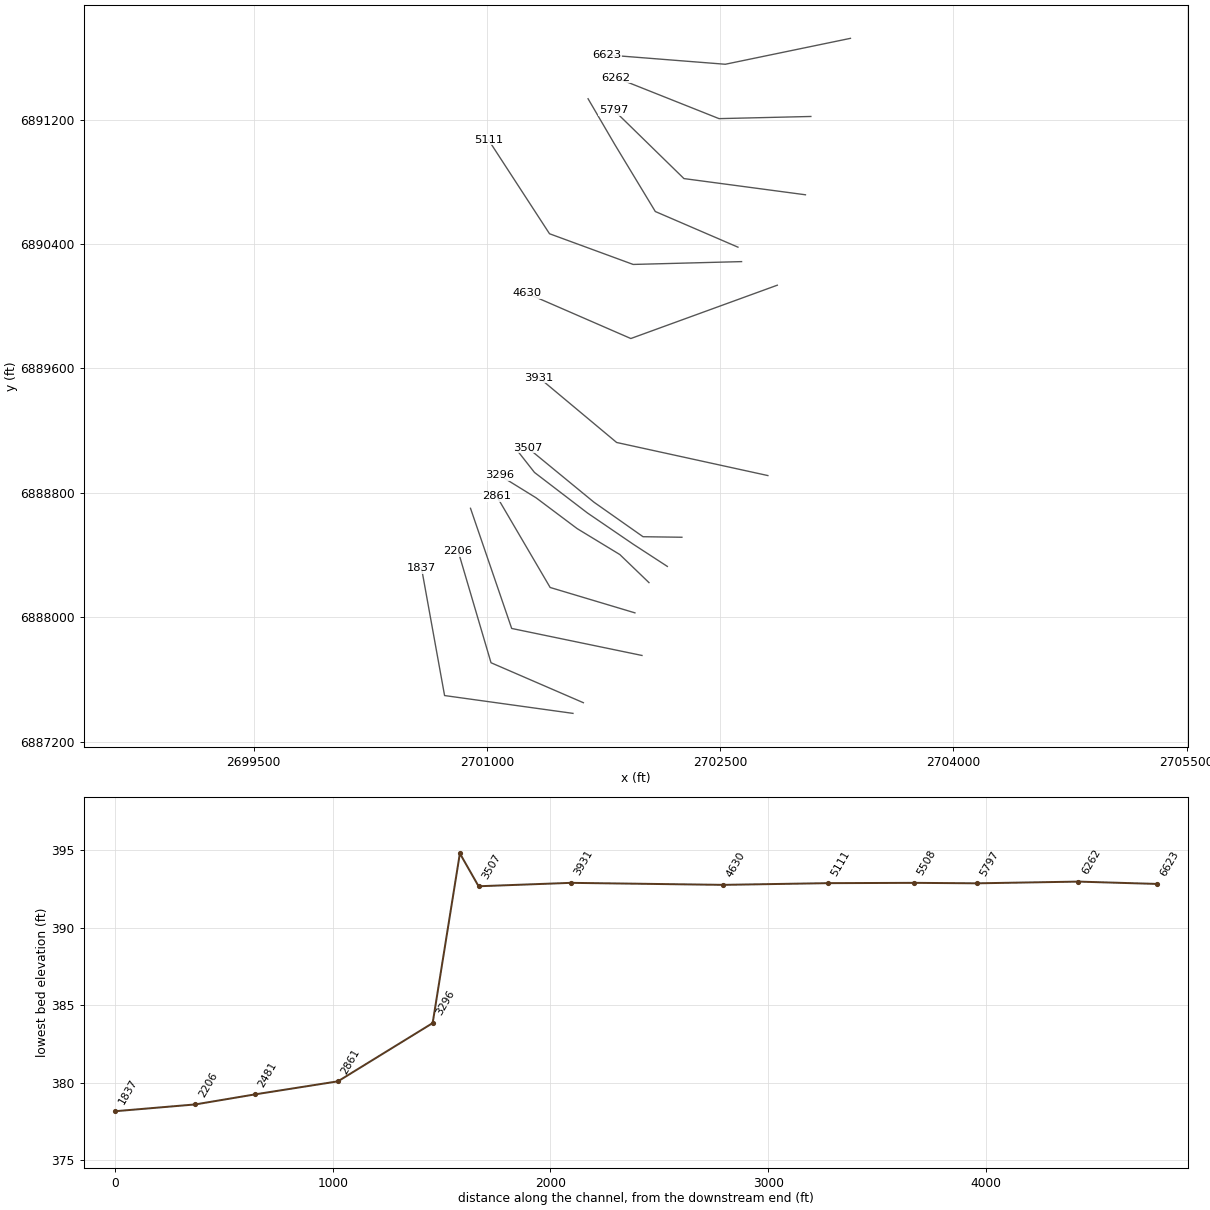
HEC-RAS study Williams T5.prj: Williams T5 Base Level Engineering

--- Williams T5.g01 (geometry) --- (continued)

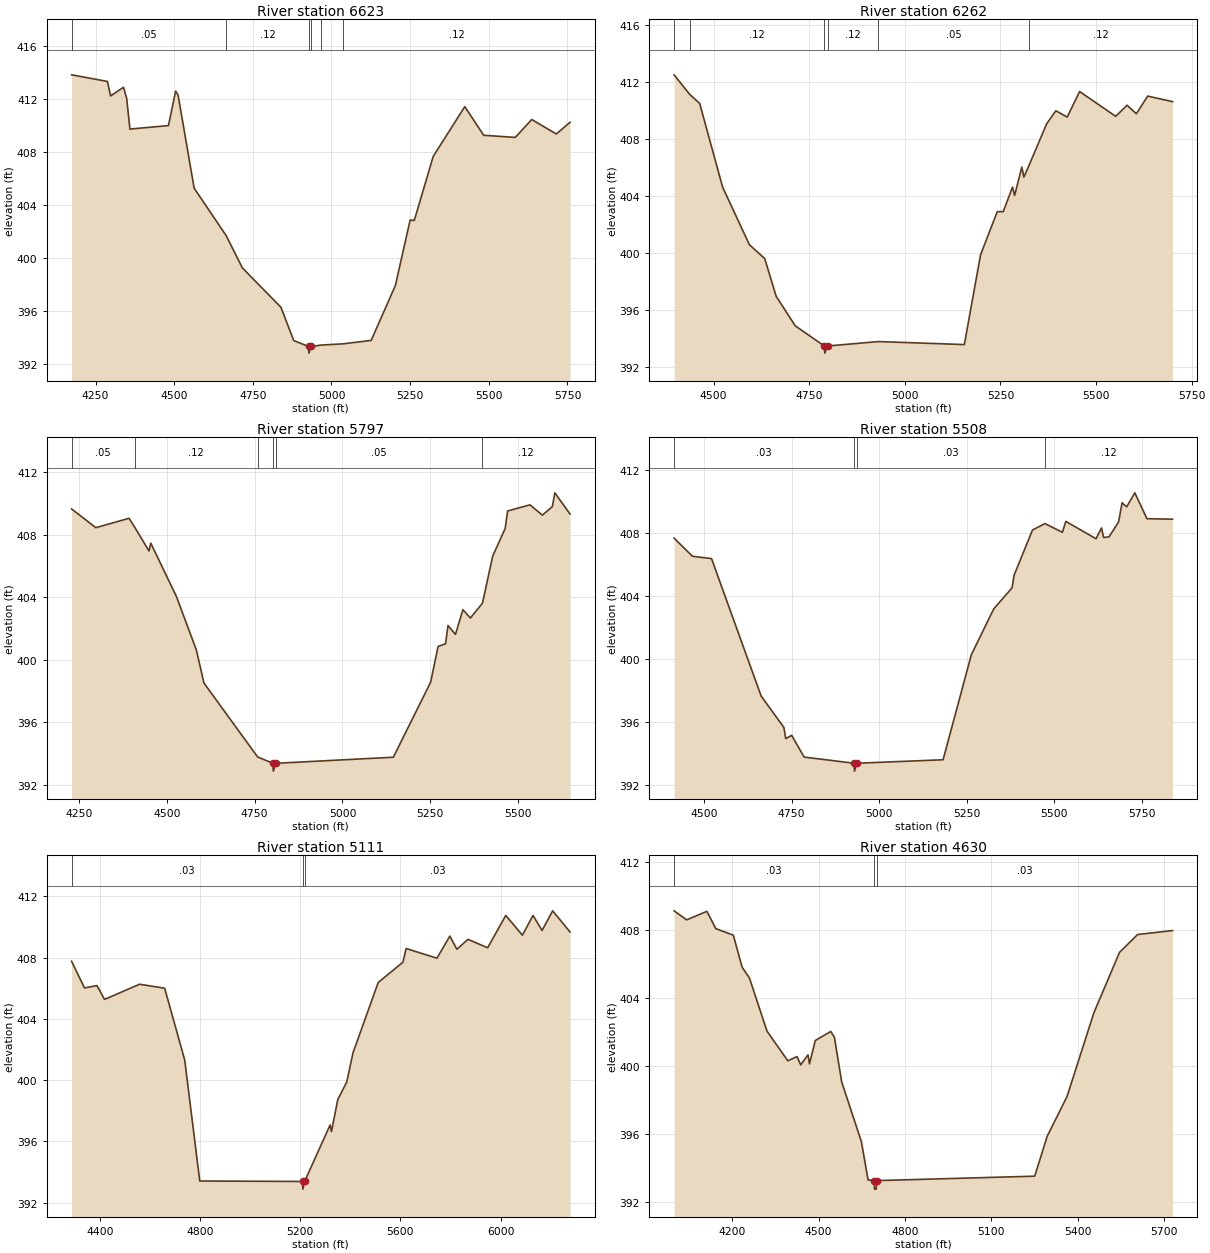
Type RM Length L Ch R = 1 ,6623    ,361,361,361
BEGIN DESCRIPTION:
Mapping XS 6b4ea7e5
END DESCRIPTION:
XS GIS Cut Line= 3
      2703337.54      6891722.55      2702532.86      6891555.88
      2701772.47      6891615.78
#Sta/Elev= 30
  4173.8  413.83  4287.7  413.33  4297.9  412.24  4338.8  412.89  4348.9  412.06
  4359.2  409.74  4481.7     410  4504.6   412.6  4512.4   412.3  4563.4  405.28
  4665.5  401.69  4716.6  399.27  4839.2   396.3    4880  393.79    4927  393.34
  4928.2  392.84  4935.2  393.34  4967.7  393.45  5036.7  393.54  5126.1   393.8
  5203.1  397.94    5250  402.88  5263.2  402.85  5323.4  407.68  5423.7  411.43
  5483.9  409.27  5584.2  409.11  5636.6  410.46  5714.6  409.37  5758.3  410.25
#Mann= 6 ,-1 , 0
  4173.8     .05       0  4665.5     .12       0    4927     .03       0
  4935.2     .12       0  4967.7     .05       0  5036.7     .12       0
Bank Sta=4927,4935.2
XS Rating Curve= 0 ,0
Exp/Cntr=0.3,0.1

Type RM Length L Ch R = 1 ,6262    ,465,465,465
BEGIN DESCRIPTION:
Mapping XS 266953e3
END DESCRIPTION:
XS GIS Cut Line= 3
      2703082.93      6891220.16      2702492.62      6891206.27
       2701830.2      6891469.85
#Sta/Elev= 30
  4396.6   412.5  4437.8  411.12  4463.5   410.5  4523.6  404.62  4593.6  400.59
  4633.6  399.62  4663.6  396.97  4713.6   394.9  4789.5  393.49  4790.7  392.99
  4797.8  393.49  4930.9   393.8  5155.6  393.59    5198  399.88  5241.7  402.91
  5257.3  402.91  5281.6  404.63    5287  404.04  5305.9  406.03  5311.3  405.33
  5324.3  406.12  5370.9  409.07  5394.9  409.98  5424.7  409.54    5457  411.33
  5551.4  409.59  5581.1  410.37  5605.4  409.77    5635  411.01    5700  410.62
#Mann= 6 ,-1 , 0
  4396.6     .05       0  4437.8     .12       0  4789.5     .03       0
  4797.8     .12       0  4930.9     .05       0  5324.3     .12       0
Bank Sta=4789.5,4797.8
XS Rating Curve= 0 ,0
Exp/Cntr=0.3,0.1

Type RM Length L Ch R = 1 ,5797    ,289,289,289
BEGIN DESCRIPTION:
Mapping XS 8d12d7c7
END DESCRIPTION:
XS GIS Cut Line= 3
      2703048.19      6890716.69      2702266.93      6890820.86
      2701815.55      6891261.82
#Sta/Elev= 30
  4228.7  409.66  4297.8  408.46  4392.3  409.06  4408.7  408.48  4449.1  406.97
  4454.2  407.47  4527.3  404.05    4584  400.63  4605.5  398.52  4758.3  393.79
  4801.8  393.38  4803.1  392.88  4810.1  393.38  5144.8  393.77    5251  398.57
  5272.2  400.86  5293.5  401.03  5300.4   402.2  5321.7  401.63  5342.9  403.21
  5364.2  402.68  5398.6  403.63  5427.7  406.64  5463.2  408.41  5470.2  409.53
  5533.9  409.92  5569.2  409.26  5597.5  409.81  5604.6  410.69  5647.9  409.33
#Mann= 6 ,-1 , 0
  4228.7     .05       0  4408.7     .12       0  4758.3     .05       0
  4801.8     .03       0  4810.1     .05       0  5398.6     .12       0
Bank Sta=4801.8,4810.1
XS Rating Curve= 0 ,0
Exp/Cntr=0.3,0.1

Type RM Length L Ch R = 1 ,5508    ,397,397,397
BEGIN DESCRIPTION:
Mapping XS 01fa5bd8
END DESCRIPTION:
XS GIS Cut Line= 4
      2702614.14      6890379.89       2702082.9      6890609.05
      2701822.49      6891039.61      2701650.57      6891334.05
#Sta/Elev= 30
  4414.8  407.68  4467.2  406.53  4521.7  406.38  4663.3  397.67  4728.2  395.68
  4733.6  394.97  4750.4  395.18  4786.1   393.8  4928.4  393.41  4929.7  392.91
  4936.8  393.41  5182.6  393.63  5263.1  400.28  5327.1  403.19  5379.5  404.53
  5385.3  405.33  5437.7  408.19  5473.1   408.6  5523.2  408.05  5532.9  408.74
  5619.1  407.64  5634.8  408.33  5640.6  407.72  5656.3  407.76  5683.6  408.71
  5693.5  409.92  5706.6  409.66  5729.8  410.55  5764.5  408.91  5837.5  408.88
#Mann= 4 ,-1 , 0
  4414.8     .03       0  4928.4     .03       0  4936.8     .03       0
  5473.1     .12       0
Bank Sta=4928.4,4936.8
XS Rating Curve= 0 ,0
Exp/Cntr=0.3,0.1

Type RM Length L Ch R = 1 ,5111    ,481,481,481
BEGIN DESCRIPTION:
Mapping XS fde754af
END DESCRIPTION:
XS GIS Cut Line= 4
      2702637.49      6890287.02      2701940.54      6890268.77
      2701402.65      6890466.19      2701010.14       6891069.6
#Sta/Elev= 30
  4287.3  407.76  4338.8  406.02  4388.8  406.17  4418.8  405.27  4558.9  406.26
  4658.9     406  4738.9  401.32    4799  393.42  5209.2  393.39  5210.5  392.89
  5217.7  393.39  5319.5  397.08  5324.8  396.64    5350  398.73  5385.8  399.88
  5410.9  401.79  5511.3  406.37  5610.2   407.7  5622.8  408.59    5746  407.96
  5797.4   409.4  5825.6  408.54  5869.8  409.19  5948.3  408.64  6020.7  410.75
  6087.2  409.46  6129.4  410.75  6165.7  409.77  6207.9  411.05  6277.3  409.67
#Mann= 3 ,-1 , 0
  4287.3     .03       0  5209.2     .03       0  5217.7     .03       0
Bank Sta=5209.2,5217.7
XS Rating Curve= 0 ,0
Exp/Cntr=0.3,0.1

Type RM Length L Ch R = 1 ,4630    ,699,699,699
BEGIN DESCRIPTION:
Mapping XS ce83cac0
END DESCRIPTION:
XS GIS Cut Line= 3
      2702867.26      6890135.38      2701925.44       6889792.5
      2701257.05      6890083.29
#Sta/Elev= 30
  3998.3  409.11  4042.2  408.58  4112.4  409.08    4143  408.07  4204.1  407.68
  4234.7   405.8    4260  405.17  4321.1  402.05  4393.4  400.31  4425.3  400.56
  4438.1  400.07  4463.4  400.66  4468.7  400.13  4488.6   401.5  4542.4  402.03
  4555.1   401.7  4580.4  399.07  4648.8  395.57  4672.1  393.32  4693.1  393.28
  4694.4  392.78  4700.4  392.78  4701.7  393.28  5250.8  393.54  5294.4  395.89
  5362.8   398.2  5456.6  403.14  5545.3  406.67  5608.1  407.72  5729.5  407.95
#Mann= 3 ,-1 , 0
  3998.3     .03       0  4693.1     .03       0  4701.7     .03       0
Bank Sta=4693.1,4701.7
XS Rating Curve= 0 ,0
Exp/Cntr=0.3,0.1

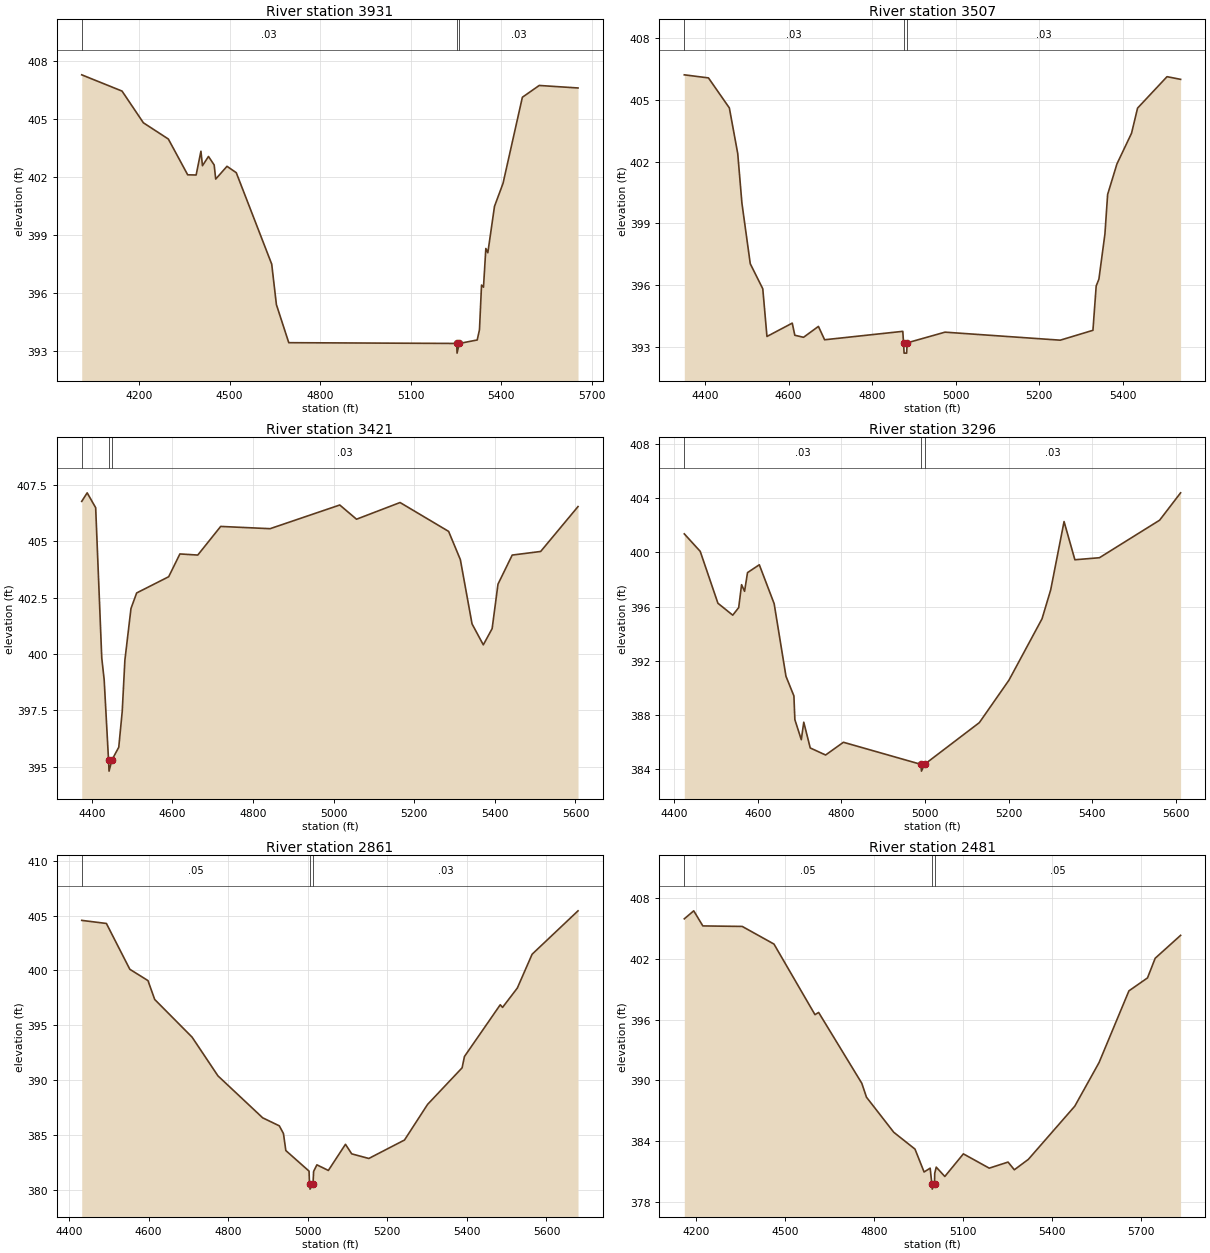
Type RM Length L Ch R = 1 ,3931    ,424,424,424
BEGIN DESCRIPTION:
Mapping XS f6dbc705
END DESCRIPTION:
XS GIS Cut Line= 3
      2702806.52      6888911.42      2701834.29       6889124.1
      2701335.16      6889540.76
#Sta/Elev= 30
  4009.8   407.3  4143.4  406.46  4214.2  404.82    4297  403.98  4361.1  402.13
  4389.1  402.12    4405  403.35  4410.1   402.6    4430  403.08  4448.9  402.64
    4454  401.91  4491.4  402.57  4522.2  402.24  4639.7  397.51  4655.2  395.42
  4696.2  393.45  5252.9  393.41  5254.2  392.91  5261.5  393.41    5321  393.59
  5328.5  394.12  5335.3  396.43  5341.8  396.32  5349.6  398.32  5356.2   398.1
  5378.3   400.5  5406.6  401.69  5470.7  406.14  5526.6  406.75  5655.2  406.62
#Mann= 3 ,-1 , 0
  4009.8     .03       0  5252.9     .03       0  5261.5     .03       0
Bank Sta=5252.9,5261.5
XS Rating Curve= 0 ,0
Exp/Cntr=0.3,0.1

Type RM Length L Ch R = 1 ,3507    ,86,86,86
BEGIN DESCRIPTION:
Mapping XS 70dd4976
END DESCRIPTION:
XS GIS Cut Line= 4
      2702253.94      6888514.76      2702003.94      6888518.23
      2701687.97      6888740.46      2701260.91      6889091.13
#Sta/Elev= 30
  4350.1  406.23    4408  406.08    4458  404.62  4478.1   402.4  4488.1  399.99
  4508.1  397.04  4538.1  395.82  4548.1   393.5  4608.7  394.15  4614.8  393.56
  4635.7  393.46  4671.4  393.99  4686.2  393.34  4873.5  393.75  4875.3  393.19
  4876.6  392.69  4882.7  392.69  4883.9  393.19  4974.6  393.71  5250.7  393.32
    5329   393.8  5336.8  395.96  5343.3  396.29  5357.7  398.48  5364.2  400.41
  5386.4  401.89  5421.5  403.39  5435.9  404.61  5506.5  406.14    5539  406.01
#Mann= 3 ,-1 , 0
  4350.1     .03       0  4875.3     .03       0  4883.9     .03       0
Bank Sta=4875.3,4883.9
XS Rating Curve= 0 ,0
Exp/Cntr=0.3,0.1

Type RM Length L Ch R = 1 ,3421    ,125,125,125
BEGIN DESCRIPTION:
Mapping XS 1ed43c1a
END DESCRIPTION:
XS GIS Cut Line= 5
       2702160.2      6888327.25      2701941.44      6888469.62
       2701646.3      6888671.01      2701306.02      6888931.43
      2701191.92      6889076.65
#Sta/Elev= 30
  4374.9  406.77  4388.4  407.15  4409.5  406.49  4424.6  399.83  4430.6  398.86
  4441.4  395.31  4442.7  394.81    4450  395.31  4466.8  395.87  4475.4  397.46
    4482  399.73  4497.1  402.02  4511.2  402.71  4590.7  403.43  4618.5  404.44
  4662.8  404.39  4719.7  405.66  4842.3  405.56  5015.2  406.61  5056.8  405.98
  5164.8  406.72  5285.3  405.44  5314.4  404.19  5343.4  401.34  5371.4  400.41
  5393.3  401.13  5407.8   403.1  5443.1  404.39  5513.7  404.55  5606.4  406.54
#Mann= 3 ,-1 , 0
  4374.9     .03       0  4441.4     .03       0    4450     .03       0
Bank Sta=4441.4,4450
XS Rating Curve= 0 ,0
Exp/Cntr=0.3,0.1

Type RM Length L Ch R = 1 ,3296    ,435,435,435
BEGIN DESCRIPTION:
Mapping XS f2c15e92
END DESCRIPTION:
XS GIS Cut Line= 5
      2702042.11      6888223.12      2701854.63      6888403.65
      2701580.33      6888570.32      2701316.44      6888768.23
      2701080.68      6888913.85
#Sta/Elev= 30
  4423.8  401.37  4461.9  400.08  4504.3  396.25  4539.8  395.37    4554  395.93
  4560.9  397.62  4568.1  397.13  4575.1  398.51  4603.4  399.09  4638.9  396.22
  4667.2  390.86  4686.2  389.41  4688.5  387.66  4703.9  386.18  4709.8  387.47
  4725.3  385.57  4762.1  385.05  4804.7  385.99  4990.3  384.36  4991.6  383.86
    4999  384.36  5130.2  387.44    5201  390.57  5280.2   395.1    5301  397.24
    5333  402.28  5358.9  399.46  5417.7  399.61  5561.8  402.38    5612   404.4
#Mann= 3 ,-1 , 0
  4423.8     .03       0  4990.3     .03       0    4999     .03       0
Bank Sta=4990.3,4999
XS Rating Curve= 0 ,0
Exp/Cntr=0.3,0.1

Type RM Length L Ch R = 1 ,2861    ,380,380,380
BEGIN DESCRIPTION:
Mapping XS 5f443862
END DESCRIPTION:
XS GIS Cut Line= 3
      2701951.83      6888028.66      2701406.72      6888191.85
      2701063.72      6888777.37
#Sta/Elev= 30
  4431.7  404.56  4493.7  404.28  4552.6  400.11  4598.2  399.08  4615.2  397.36
  4709.2  393.93  4774.1  390.41  4886.6  386.59  4928.4  385.86  4938.8  385.16
  4944.8  383.61  5003.1  381.74  5004.3   380.6  5005.6   380.1  5013.2   380.6
  5014.6  381.71  5022.9  382.31  5051.7   381.8  5094.7  384.18  5110.4  383.31
  5153.4  382.89  5243.1  384.57  5301.1  387.81  5387.9  391.14  5393.8  392.17
  5483.8  396.88  5489.6  396.64  5526.7   398.4  5563.9  401.48  5679.3  405.43
#Mann= 3 ,-1 , 0
  4431.7     .05       0  5004.3     .03       0  5013.2     .03       0
Bank Sta=5004.3,5013.2
XS Rating Curve= 0 ,0
Exp/Cntr=0.3,0.1

Type RM Length L Ch R = 1 ,2481    ,275,275,275
BEGIN DESCRIPTION:
Mapping XS 314df580
END DESCRIPTION:
XS GIS Cut Line= 3
      2701997.12      6887754.77      2701159.41      6887928.39
      2700894.65      6888700.97
#Sta/Elev= 30
  4161.3  405.94  4193.1  406.73  4223.7  405.24  4356.5  405.19  4463.4  403.45
  4601.6  396.48  4613.9   396.7  4759.3  389.71  4775.2  388.33  4867.1  384.87
  4938.6  383.21  4969.2  380.95  4989.7  381.33  4995.4  379.76  4996.7  379.26
  5004.3  379.76    5005  380.81  5010.1  381.43  5039.1  380.51  5101.6  382.74
  5188.7  381.33  5252.1  381.93  5273.3  381.17  5320.6   382.2    5477  387.45
  5558.7  391.75  5659.4  398.83    5722  400.11  5747.9  402.05  5833.5  404.31
#Mann= 3 ,-1 , 0
  4161.3     .05       0  4995.4     .04       0  5004.3     .05       0
Bank Sta=4995.4,5004.3
XS Rating Curve= 0 ,0
Exp/Cntr=0.3,0.1

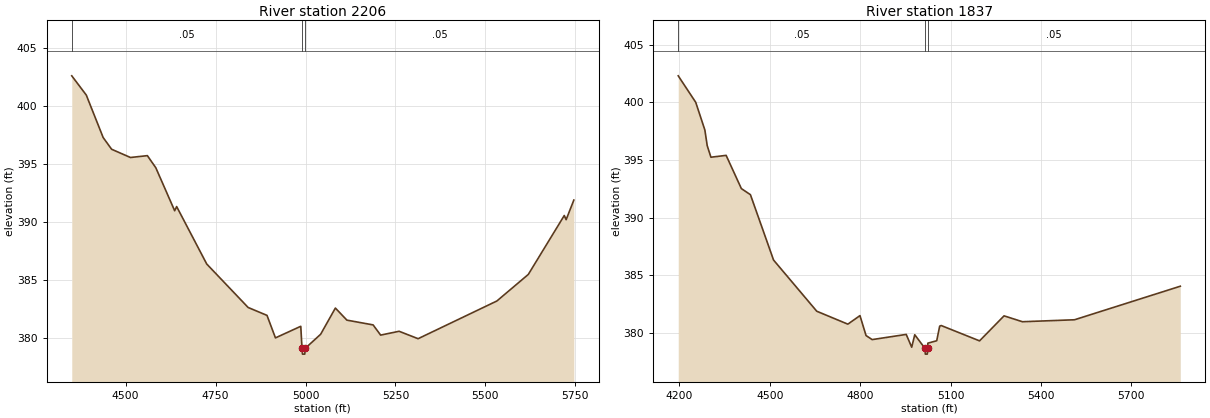
Type RM Length L Ch R = 1 ,2206    ,369,369,369
BEGIN DESCRIPTION:
Mapping XS 881b17b0
END DESCRIPTION:
XS GIS Cut Line= 3
      2701620.35      6887450.96      2701026.59       6887707.9
      2700814.89       6888426.3
#Sta/Elev= 30
  4350.1   402.6  4390.5  400.94  4437.4  397.28  4460.9  396.27  4513.3  395.56
  4560.3  395.72  4583.7  394.68  4636.2  390.97  4641.7  391.33  4725.3  386.38
  4840.5  382.63  4892.9  381.95  4916.4  380.01  4986.8  381.01  4990.2  379.11
  4991.5  378.61  4997.9  378.61  4999.2  379.11    5042  380.32    5083  382.58
    5115  381.54  5187.9  381.13  5208.8  380.25  5260.1  380.58    5313  379.94
    5532  383.19  5619.4  385.48  5719.4  390.56  5724.6   390.2    5746  391.89
#Mann= 3 ,-1 , 0
  4350.1     .05       0  4990.2     .03       0  4999.2     .05       0
Bank Sta=4990.2,4999.2
XS Rating Curve= 0 ,0
Exp/Cntr=0.3,0.1

Type RM Length L Ch R = 1 ,1837    ,0,0,0
BEGIN DESCRIPTION:
Mapping XS 7ea22e49
END DESCRIPTION:
XS GIS Cut Line= 3
      2701553.52      6887382.38      2700727.98      6887496.97
      2700579.67      6888316.61
#Sta/Elev= 30
  4196.2  402.31  4254.3  400.01  4284.6  397.61  4292.4  396.25  4304.7  395.25
  4355.2  395.41  4405.7  392.53  4435.8     392  4512.6  386.33    4656  381.89
  4759.1  380.77  4799.4  381.51  4819.6  379.78  4839.8  379.43  4952.9  379.88
  4971.1  378.77  4981.2  379.85  5015.1  378.67  5016.4  378.17  5022.8  378.17
  5024.1  378.67  5024.6  379.12  5054.1  379.33    5064   380.6  5069.1  380.65
  5196.3  379.32  5277.6  381.49  5338.6  380.98  5511.4  381.15  5862.6  384.06
#Mann= 3 ,-1 , 0
  4196.2     .05       0  5015.1     .03       0  5024.1     .05       0
Bank Sta=5015.1,5024.1
XS Rating Curve= 0 ,0
Exp/Cntr=0.3,0.1

Chan Stop Cuts=-1
Use User Specified Reach Order=0
Composite Channel Slope=5