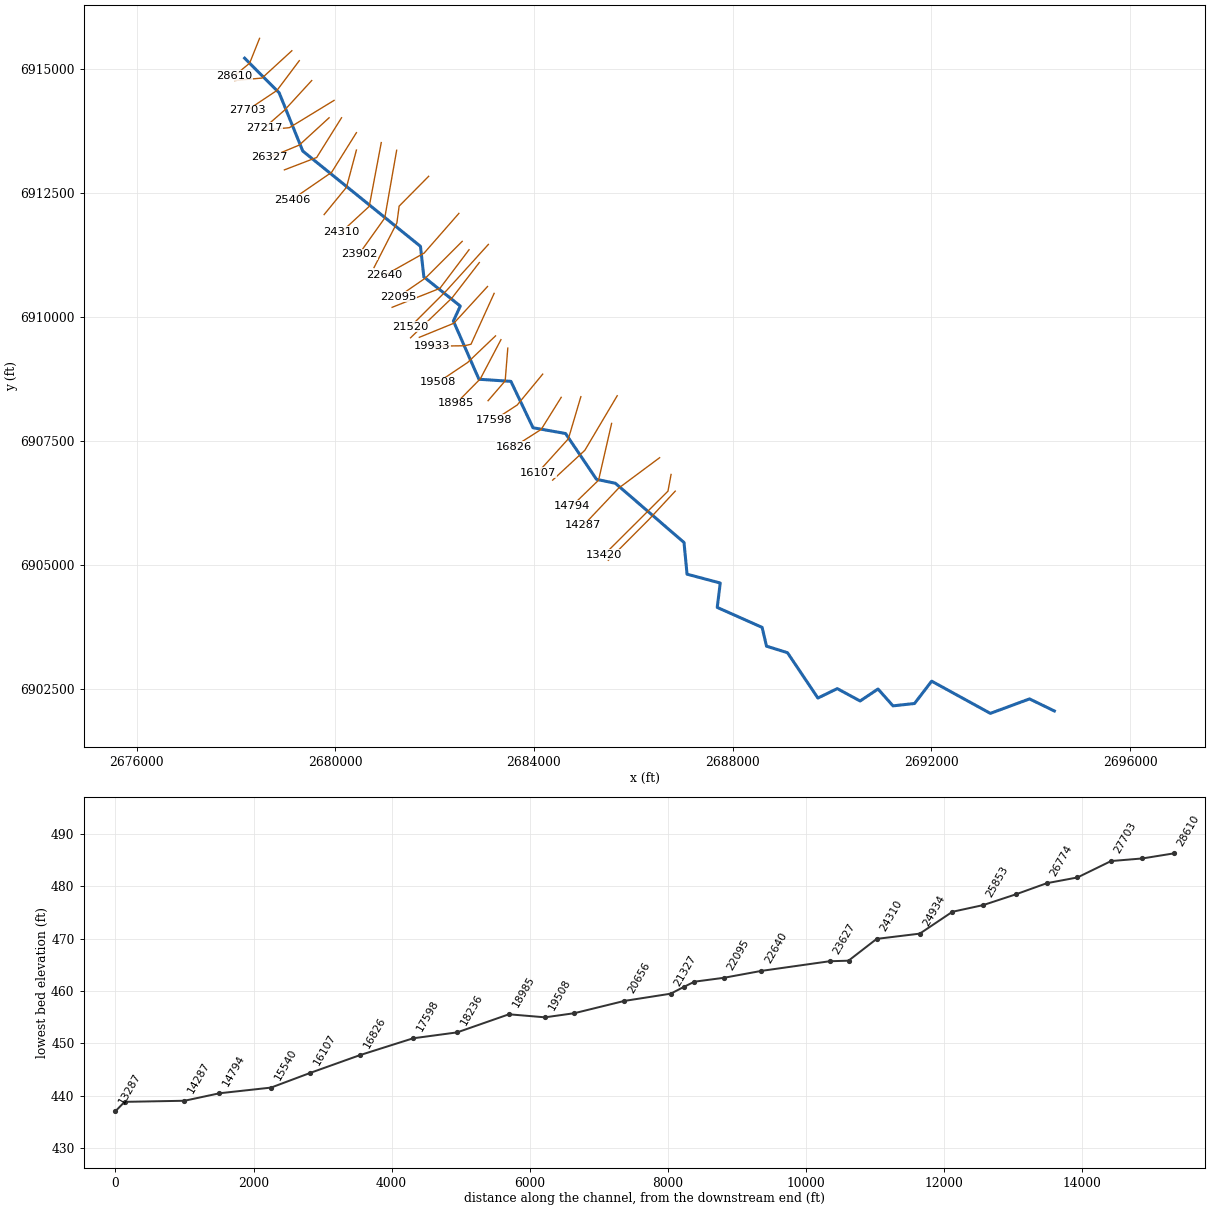
--- Williams T6.prj (project) ---

Proj Title=Williams T6 Base Level Engineering
Current Plan=p01
Default Exp/Contr=0.3,0.1
English Units
Geom File=g01
Flow File=f01
Plan File=p01
Y Axis Title=Elevation
X Axis Title(PF)=Main Channel Distance
X Axis Title(XS)=Station
BEGIN DESCRIPTION:
Williams T6
END DESCRIPTION:
DSS Export Rating Curves= 0
DSS Export Rating Curve Sorted= 0
DSS Export Volume Flow Curves= 0
DXF OffsetX= 0
DXF OffsetY= 0
DXF ScaleX= 1
DXF ScaleY= 10

--- Williams T6.p01 (plan) ---

Plan Title=Multiple Run
Short Identifier=Multiple
Geom File=g01
Flow File=f01
Subcritical Flow
K Sum by GR= 0
Std Step Tol= 0.01
Critical Tol= 0.01
Num of Std Step Trials= 20
Max Error Tol= 0.3
Flow Tol Ratio= 0.001
Split Flow NTrial= 30
Split Flow Tol= 0.02
Split Flow Ratio= 0.02
Log Output Level= 0
Friction Slope Method= 1
Unsteady Friction Slope Method= 2
Unsteady Bridges Friction Slope Method= 1
Parabolic Critical Depth
Global Vel Dist=  1 , 1 , 1
Global Log Level= 0
CheckData=True
Encroach Param= -1, 0, 0, 0
BEGIN DESCRIPTION:
Multiple Run
END DESCRIPTION:

--- Williams T6.f01 (steady flow) ---

Flow Title=Multiple
Number of Profiles=7
Profile Names=10-year,25-year,50-year,1pct_min,100-year,1pct_plu,500-year
River Rch & RM= Williams T6,Reach-1,28610
     441     582     694     411     820    1635    1143
River Rch & RM= Williams T6,Reach-1,27703
     675     914    1108     666    1329    2652    1913
River Rch & RM= Williams T6,Reach-1,25853
    1065    1475    1815    1106    2207    4403    3264
River Rch & RM= Williams T6,Reach-1,20656
    1283    1788    2210    1351    2696    5379    4014
River Rch & RM= Williams T6,Reach-1,15540
    1511    2119    2631    1614    3221    6427    4833
River Rch & RM= Williams T6,Reach-1,12302
    1724    2426    3019    1855    3702    7386    5573
River Rch & RM= Williams T6,Reach-1,5112
    2012    2843    3546    2184    4357    8694    6585
Boundary for River Rch & Prof#=Williams T6,Reach-1,1
Up Type=0
Dn Type=3
Dn Slope=0.005
Boundary for River Rch & Prof#=Williams T6,Reach-1,2
Up Type=0
Dn Type=3
Dn Slope=0.005
Boundary for River Rch & Prof#=Williams T6,Reach-1,3
Up Type=0
Dn Type=3
Dn Slope=0.005
Boundary for River Rch & Prof#=Williams T6,Reach-1,4
Up Type=0
Dn Type=3
Dn Slope=0.005
Boundary for River Rch & Prof#=Williams T6,Reach-1,5
Up Type=0
Dn Type=3
Dn Slope=0.005
Boundary for River Rch & Prof#=Williams T6,Reach-1,6
Up Type=0
Dn Type=3
Dn Slope=0.005
Boundary for River Rch & Prof#=Williams T6,Reach-1,7
Up Type=0
Dn Type=3
Dn Slope=0.005

--- Williams T6.g01 (geometry) ---

Geom Title=Existing Conditions
Program Version=4.10

River Reach=Williams T6     ,Reach-1
Reach XY= 30
        2678176.        6915211.      2678870.54      6914513.45
      2679345.76      6913340.87      2681715.24      6911420.73
      2681783.37      6910804.66      2682517.11      6910217.53
      2682377.97      6909916.65      2682892.43      6908743.38
      2683536.18      6908700.68      2683981.19      6907766.45
        2684636.      6907650.37      2685258.86      6906727.28
      2685639.68       6906647.5      2687020.37      6905455.35
      2687081.59      6904816.61      2687749.99       6904638.7
      2687689.17      6904147.26      2688592.68      6903744.78
      2688681.29      6903366.48      2689103.34      6903235.02
      2689715.88      6902321.34      2690105.94      6902511.52
      2690565.56      6902262.04       2690926.1      6902503.69
      2691227.17      6902164.13      2691660.73      6902211.37
      2692005.83      6902661.47      2693187.83      6902012.64
        2693976.       6902304.1        2694476.        6902061.

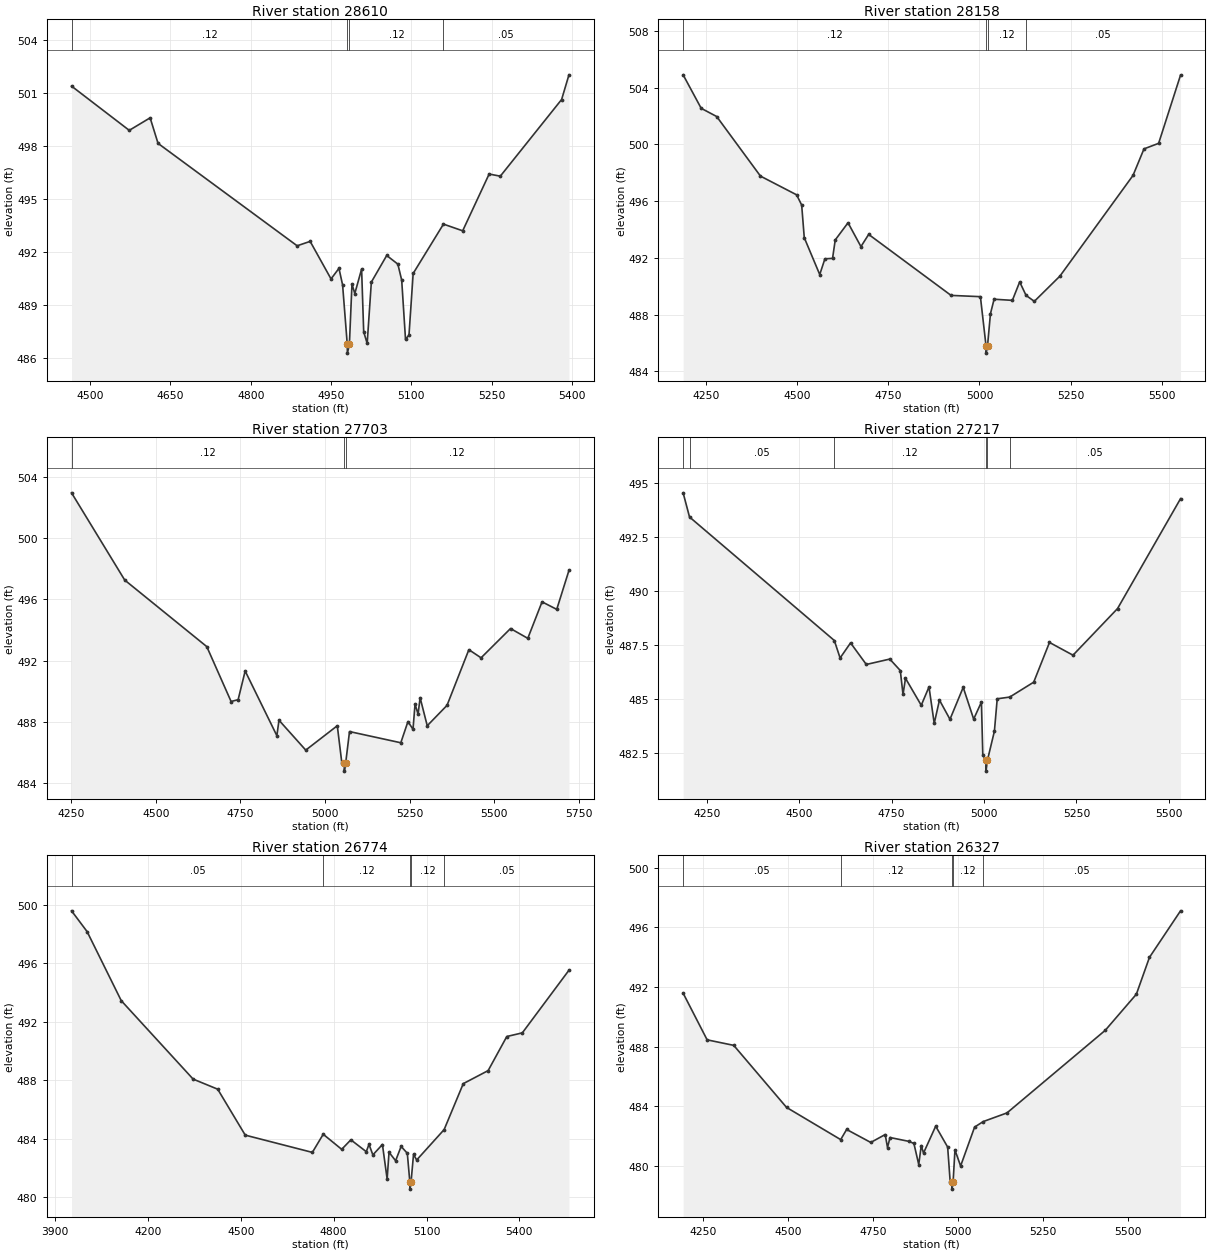
Type RM Length L Ch R = 1 ,28610   ,452,452,452
BEGIN DESCRIPTION:
Williams T6 49.0
END DESCRIPTION:
XS GIS Cut Line= 3
      2678476.02      6915611.04        2678276.        6915111.
      2677975.98      6914860.98
#Sta/Elev= 30
  4465.3   501.4  4573.1  498.89  4612.1   499.6  4626.9  498.15  4886.7  492.34
    4911  492.59    4950  490.46  4964.8  491.06  4971.6  490.12  4980.3  486.75
  4980.6  486.25  4984.3  486.75  4989.1  490.17  4994.4  489.63  5007.1  491.02
    5011  487.46  5017.5   486.8  5025.3  490.28    5054  491.79  5074.8   491.3
    5082  490.39  5089.1  487.04  5095.6  487.27  5103.4  490.77    5160  493.57
  5195.9  493.19  5245.3  496.41  5266.2  496.29  5380.7  500.64  5394.4  502.04
#Mann= 4 ,-1 , 0
  4465.3     .12       0  4980.3     .07       0  4984.3     .12       0
    5160     .05       0
Bank Sta=4980.3,4984.3
XS Rating Curve= 0 ,0
Exp/Cntr=0.3,0.1

Type RM Length L Ch R = 1 ,28158   ,455,455,455
BEGIN DESCRIPTION:
Williams T6 48.0
END DESCRIPTION:
XS GIS Cut Line= 3
      2679126.01      6915361.01        2678526.        6914811.
      2677976.02        6914761.
#Sta/Elev= 30
    4186  504.91  4235.6  502.55  4278.2  501.97  4398.4  497.77  4497.7  496.45
  4511.6  495.73  4518.7  493.43  4561.2  490.83  4575.4  491.94  4596.4  491.97
  4603.8  493.27  4638.9  494.48  4674.4   492.8  4695.6  493.66  4921.9  489.36
  5002.5  489.27    5018  485.79  5018.3  485.29    5022  485.79  5030.1  488.07
  5040.1  489.09  5090.3  489.01  5110.4  490.31  5127.9  489.36  5150.6  488.94
  5220.9  490.72  5421.7  497.82  5451.8  499.69    5492  500.08  5552.2  504.89
#Mann= 4 ,-1 , 0
    4186     .12       0    5018     .07       0    5022     .12       0
  5127.9     .05       0
Bank Sta=5018,5022
XS Rating Curve= 0 ,0
Exp/Cntr=0.3,0.1

Type RM Length L Ch R = 1 ,27703   ,486,486,486
BEGIN DESCRIPTION:
Williams T6 47.0
END DESCRIPTION:
XS GIS Cut Line= 3
      2679275.99      6915160.99        2678826.        6914561.
        2678226.        6914161.
#Sta/Elev= 30
  4250.3  502.94  4407.6  497.25  4650.3  492.91  4722.2  489.33    4743  489.45
  4763.8  491.32  4857.6   487.1  4863.8  488.11    4943  486.16  5036.3  487.75
  5049.9  485.29  5056.9  485.29  5057.1  484.79  5060.9  485.29  5072.4  487.37
  5224.1  486.64  5245.2  488.02  5260.2  487.52  5266.2  489.16  5275.2  488.51
  5281.2  489.58  5302.3  487.75  5360.8  489.08  5425.4  492.71  5461.5  492.18
  5548.6  494.09  5599.7  493.45  5641.8  495.83  5685.3  495.34  5721.4  497.88
#Mann= 3 ,-1 , 0
  4250.3     .12       0  5056.9     .07       0  5060.9     .12       0
Bank Sta=5056.9,5060.9
XS Rating Curve= 0 ,0
Exp/Cntr=0.3,0.1

Type RM Length L Ch R = 1 ,27217   ,443,443,443
BEGIN DESCRIPTION:
Williams T6 46.0
END DESCRIPTION:
XS GIS Cut Line= 3
      2679526.02      6914761.02        2678976.        6914161.
      2678575.99      6913810.99
#Sta/Elev= 30
    4186  494.55  4203.3  493.43    4595  487.71  4610.6   486.9  4638.9   487.6
  4681.5   486.6    4745  486.85  4773.4  486.32  4780.8  485.21  4787.5  485.96
  4830.1  484.71  4851.1  485.56  4865.2  483.87  4879.4  484.95  4907.8  484.06
  4943.6  485.54  4971.9  484.07  4992.9  484.86  4996.6  482.41  5005.1  482.16
  5005.3  481.66  5009.1  482.16    5028  483.51  5035.6  485.01  5069.4  485.09
  5134.3  485.78    5177  487.62  5240.6  487.03  5361.1  489.19  5531.5  494.28
#Mann= 6 ,-1 , 0
    4186     .12       0  4203.3     .05       0    4595     .12       0
  5005.1     .07       0  5009.1     .12       0  5069.4     .05       0
Bank Sta=5005.1,5009.1
XS Rating Curve= 0 ,0
Exp/Cntr=0.3,0.1

Type RM Length L Ch R = 1 ,26774   ,447,447,447
BEGIN DESCRIPTION:
Williams T6 45.0
END DESCRIPTION:
XS GIS Cut Line= 3
      2679975.97      6914360.98        2679076.        6913811.
      2678525.99        6913761.
#Sta/Elev= 30
  3953.1  499.59  4003.4  498.17  4113.7  493.45  4345.9  488.09  4425.3   487.4
  4514.3  484.26  4731.1  483.08  4766.2  484.32  4825.9  483.29  4855.5  483.94
  4905.3  483.13  4914.1  483.63  4926.6  482.91  4957.5  483.62  4972.7  481.26
  4978.8  483.09  5000.1  482.51  5017.9  483.49  5037.9  483.02    5046  481.07
  5046.2  480.57    5050  481.07    5058  482.95  5068.1  482.56  5156.9  484.64
  5218.7  487.78    5299  488.67  5359.3     491  5409.5  491.25  5560.1  495.53
#Mann= 5 ,-1 , 0
  3953.1     .05       0  4766.2     .12       0    5046     .07       0
    5050     .12       0  5156.9     .05       0
Bank Sta=5046,5050
XS Rating Curve= 0 ,0
Exp/Cntr=0.3,0.1

Type RM Length L Ch R = 1 ,26327   ,474,474,474
BEGIN DESCRIPTION:
Williams T6 44.0
END DESCRIPTION:
XS GIS Cut Line= 3
      2679875.98      6914010.98        2679276.        6913461.
      2678676.01      6913211.01
#Sta/Elev= 30
  4190.6  491.59  4261.2  488.46  4339.5  488.09  4494.9  483.93  4654.3  481.77
  4671.8  482.45  4742.8  481.58  4785.3  482.11  4792.1  481.24  4799.5  481.91
  4855.6  481.65  4869.8  481.51    4884   480.1  4891.4  481.37  4898.1  480.87
  4933.9  482.67  4969.1  481.27  4976.5  478.96  4981.2  478.95  4981.5  478.45
  4985.2  478.95  4990.6  481.08  5007.2     480  5048.4  482.61  5073.8  482.98
  5143.7  483.56    5433   489.1  5524.5  491.52    5563  493.99  5654.5  497.11
#Mann= 5 ,-1 , 0
  4190.6     .05       0  4654.3     .12       0  4981.2     .07       0
  4985.2     .12       0  5073.8     .05       0
Bank Sta=4981.2,4985.2
XS Rating Curve= 0 ,0
Exp/Cntr=0.3,0.1

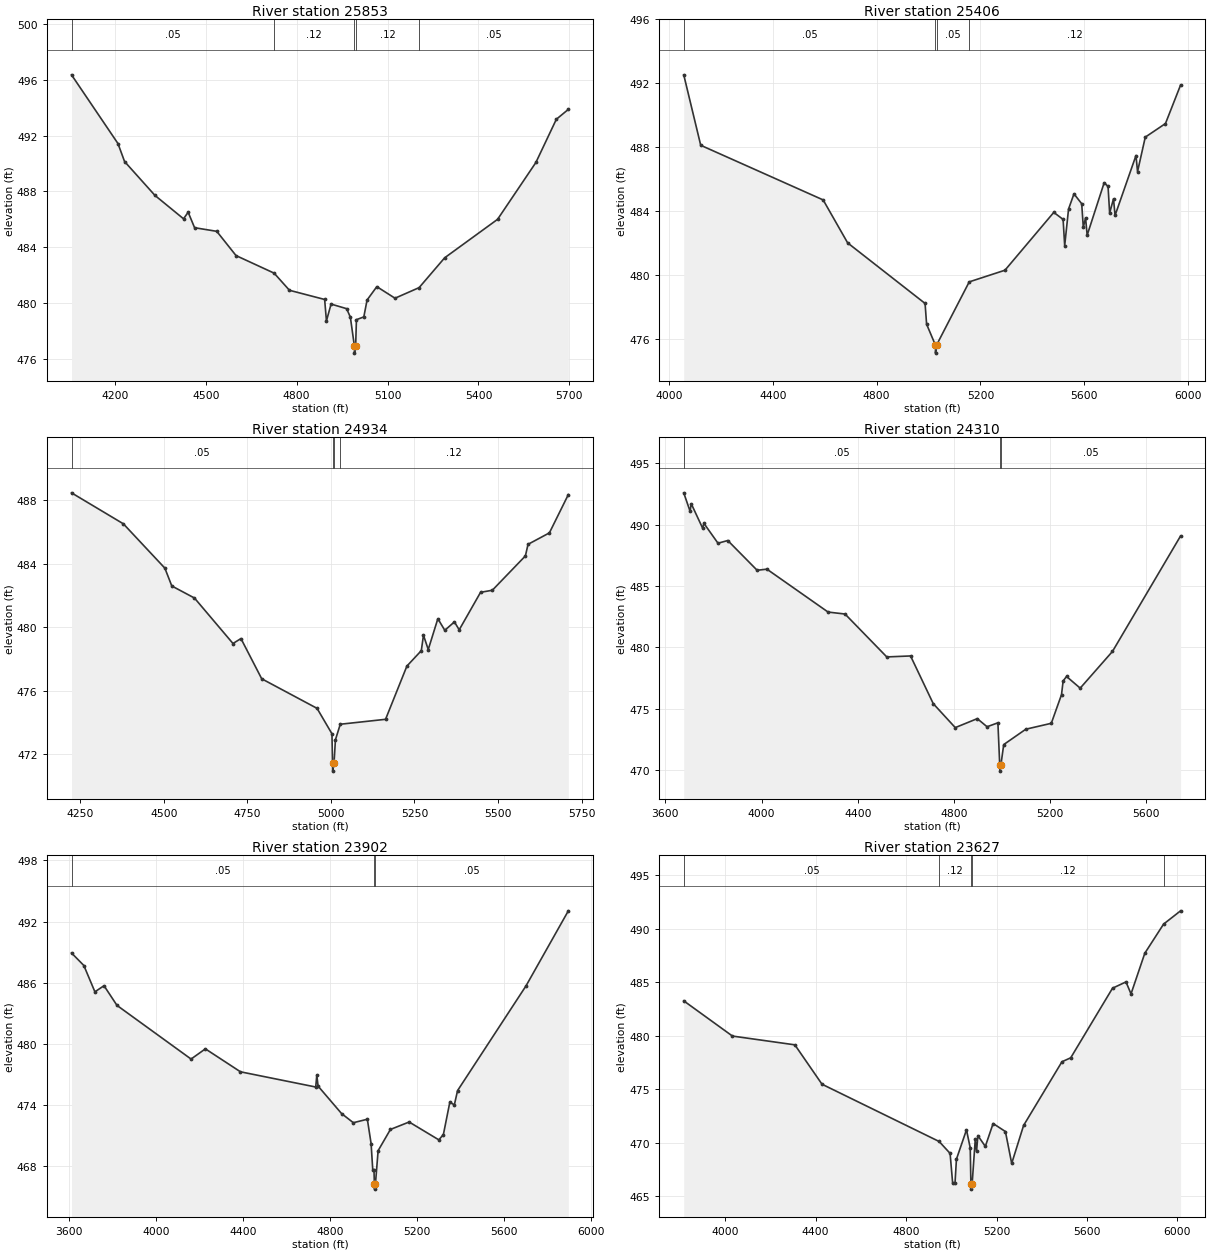
Type RM Length L Ch R = 1 ,25853   ,447,447,447
BEGIN DESCRIPTION:
Williams T6 43.0
END DESCRIPTION:
XS GIS Cut Line= 3
      2680125.99      6914010.99        2679626.        6913211.
        2678976.        6912961.
#Sta/Elev= 30
  4056.9  496.36  4210.2  491.43    4232  490.14  4332.2  487.71  4426.6  486.03
  4441.9   486.5  4463.1  485.39  4536.3  485.13  4599.9  483.39  4725.6  482.13
  4776.2   480.9  4892.4  480.24  4898.3   478.7  4913.6  479.91  4964.9  479.58
  4977.3  478.97  4990.6  476.89  4990.9  476.39  4994.7  476.89  4997.3  478.79
  5021.7  478.99  5032.4   480.2  5064.6  481.16  5124.6  480.33  5204.2  481.09
  5288.5  483.23  5463.1  485.99  5589.6  490.07  5657.1  493.17  5696.7  493.88
#Mann= 5 ,-1 , 0
  4056.9     .05       0  4725.6     .12       0  4990.6     .07       0
  4994.7     .12       0  5204.2     .05       0
Bank Sta=4990.6,4994.7
XS Rating Curve= 0 ,0
Exp/Cntr=0.3,0.1

Type RM Length L Ch R = 1 ,25406   ,472,472,472
BEGIN DESCRIPTION:
Williams T6 42.0
END DESCRIPTION:
XS GIS Cut Line= 3
      2680425.98      6913710.97        2679926.        6912911.
      2679125.99        6912361.
#Sta/Elev= 30
  4056.7  492.53  4122.1  488.12  4593.8   484.7  4688.2  482.01  4986.5  478.22
  4992.4  476.92  5026.4  475.61  5026.7  475.11  5030.6  475.61  5156.6  479.57
  5294.3   480.3  5482.4  483.92  5518.3  483.48  5524.4  481.84  5539.3  484.13
  5560.2  485.08    5590  484.46  5596.1  482.99  5604.9  483.57    5611  482.49
  5676.6  485.78  5691.5  485.54  5697.6  483.88  5712.5  484.77  5718.5  483.73
  5799.1  487.48  5805.1  486.47  5834.9  488.63  5912.7  489.48  5970.9  491.89
#Mann= 4 ,-1 , 0
  4056.7     .05       0  5026.4     .04       0  5030.6     .05       0
  5156.6     .12       0
Bank Sta=5026.4,5030.6
XS Rating Curve= 0 ,0
Exp/Cntr=0.3,0.1

Type RM Length L Ch R = 1 ,24934   ,624,624,624
BEGIN DESCRIPTION:
Williams T6 41.0
END DESCRIPTION:
XS GIS Cut Line= 3
      2680425.99      6913360.98        2680226.        6912611.
      2679776.01      6912061.02
#Sta/Elev= 30
  4223.6  488.45  4378.8   486.5    4503  483.71  4523.7  482.59  4591.6  481.83
  4706.8  478.97  4730.7  479.28  4792.8  476.75  4958.4  474.89    5003  473.29
  5004.7  471.44  5005.2  470.94  5009.2  471.44  5013.4  472.91  5027.9  473.89
  5163.4   474.2  5227.3  477.55  5270.4  478.52  5276.9  479.49  5291.2  478.59
  5319.9  480.53  5340.7   479.8  5369.5  480.33  5383.8  479.83  5447.7  482.19
  5482.9  482.32  5581.9  484.48  5589.8  485.21  5653.7  485.93  5710.4  488.34
#Mann= 4 ,-1 , 0
  4223.6     .05       0  5004.7     .04       0  5009.2     .05       0
  5027.9     .12       0
Bank Sta=5004.7,5009.2
XS Rating Curve= 0 ,0
Exp/Cntr=0.3,0.1

Type RM Length L Ch R = 1 ,24310   ,408,408,408
BEGIN DESCRIPTION:
Williams T6 40.0
END DESCRIPTION:
XS GIS Cut Line= 3
        2680926.      6913511.01      2680684.15      6912226.65
      2680126.02      6911711.02
#Sta/Elev= 30
  3676.3  492.58  3702.5  491.09  3707.6  491.69    3755   489.7  3760.1   490.1
  3818.8  488.48  3859.5   488.7  3981.6  486.28  4022.3  486.37  4276.7  482.88
  4347.3  482.72  4520.9  479.23  4619.8  479.31  4714.2  475.43  4805.8  473.48
  4897.4  474.21  4938.1  473.55  4983.2  473.87  4990.8  470.44  4991.4  469.94
  4995.6  470.44  5007.4   472.1  5099.3  473.35  5205.3  473.83  5247.8  476.16
  5254.6  477.28  5268.8  477.64  5325.5  476.69  5459.9  479.68  5743.1  489.07
#Mann= 3 ,-1 , 0
  3676.3     .05       0  4990.8     .03       0  4995.6     .05       0
Bank Sta=4990.8,4995.6
XS Rating Curve= 0 ,0
Exp/Cntr=0.3,0.1

Type RM Length L Ch R = 1 ,23902   ,275,275,275
BEGIN DESCRIPTION:
Williams T6 39.0
END DESCRIPTION:
XS GIS Cut Line= 3
      2681236.23      6913356.85      2680995.89      6911990.73
      2680475.99      6911260.99
#Sta/Elev= 30
  3612.9  488.93  3669.6   487.7  3720.4  485.12  3762.3  485.72  3821.9  483.79
  4162.3  478.53  4228.1  479.53  4389.4  477.28  4735.1  475.79  4740.2  476.96
  4745.9  475.88  4853.8  473.19    4908  472.29  4972.4  472.63  4989.6  470.25
  4997.3  467.65  5002.9  467.65  5004.7  466.28  5005.3  465.78  5009.5  466.28
  5021.9  469.55  5078.4  471.63  5164.5  472.36  5300.9  470.61  5321.8  471.13
  5351.4   474.3  5372.2  474.04    5387  475.44  5701.7  485.71    5896  493.06
#Mann= 3 ,-1 , 0
  3612.9     .05       0  5004.7     .04       0  5009.5     .05       0
Bank Sta=5004.7,5009.5
XS Rating Curve= 0 ,0
Exp/Cntr=0.3,0.1

Type RM Length L Ch R = 1 ,23627   ,987,987,987
BEGIN DESCRIPTION:
Williams T6 38.0
END DESCRIPTION:
XS GIS Cut Line= 4
      2681879.88      6912831.67      2681286.15      6912230.99
      2681241.01      6911894.18      2680780.09      6910993.14
#Sta/Elev= 30
  3817.1  483.26  4032.4  479.97  4308.3  479.15  4428.4  475.47  4946.3  470.12
  4994.6  469.01  5006.1   466.2  5016.3   466.2  5022.7  468.47  5067.1  471.21
  5083.7  469.52  5086.6  466.17  5087.4  465.67  5092.1  466.17  5105.9  470.31
  5111.6   469.2  5117.4  470.67  5150.4  469.66  5184.8   471.8  5239.2  471.05
    5267  468.07  5319.6  471.62  5489.2  477.57    5528  477.94  5712.7  484.44
  5772.3  485.03  5794.5  483.91  5855.5  487.71  5938.5  490.43  6013.6  491.67
#Mann= 5 ,-1 , 0
  3817.1     .05       0  4946.3     .12       0  5086.6     .07       0
  5092.1     .12       0  5938.5     .05       0
Bank Sta=5086.6,5092.1
XS Rating Curve= 0 ,0
Exp/Cntr=0.3,0.1

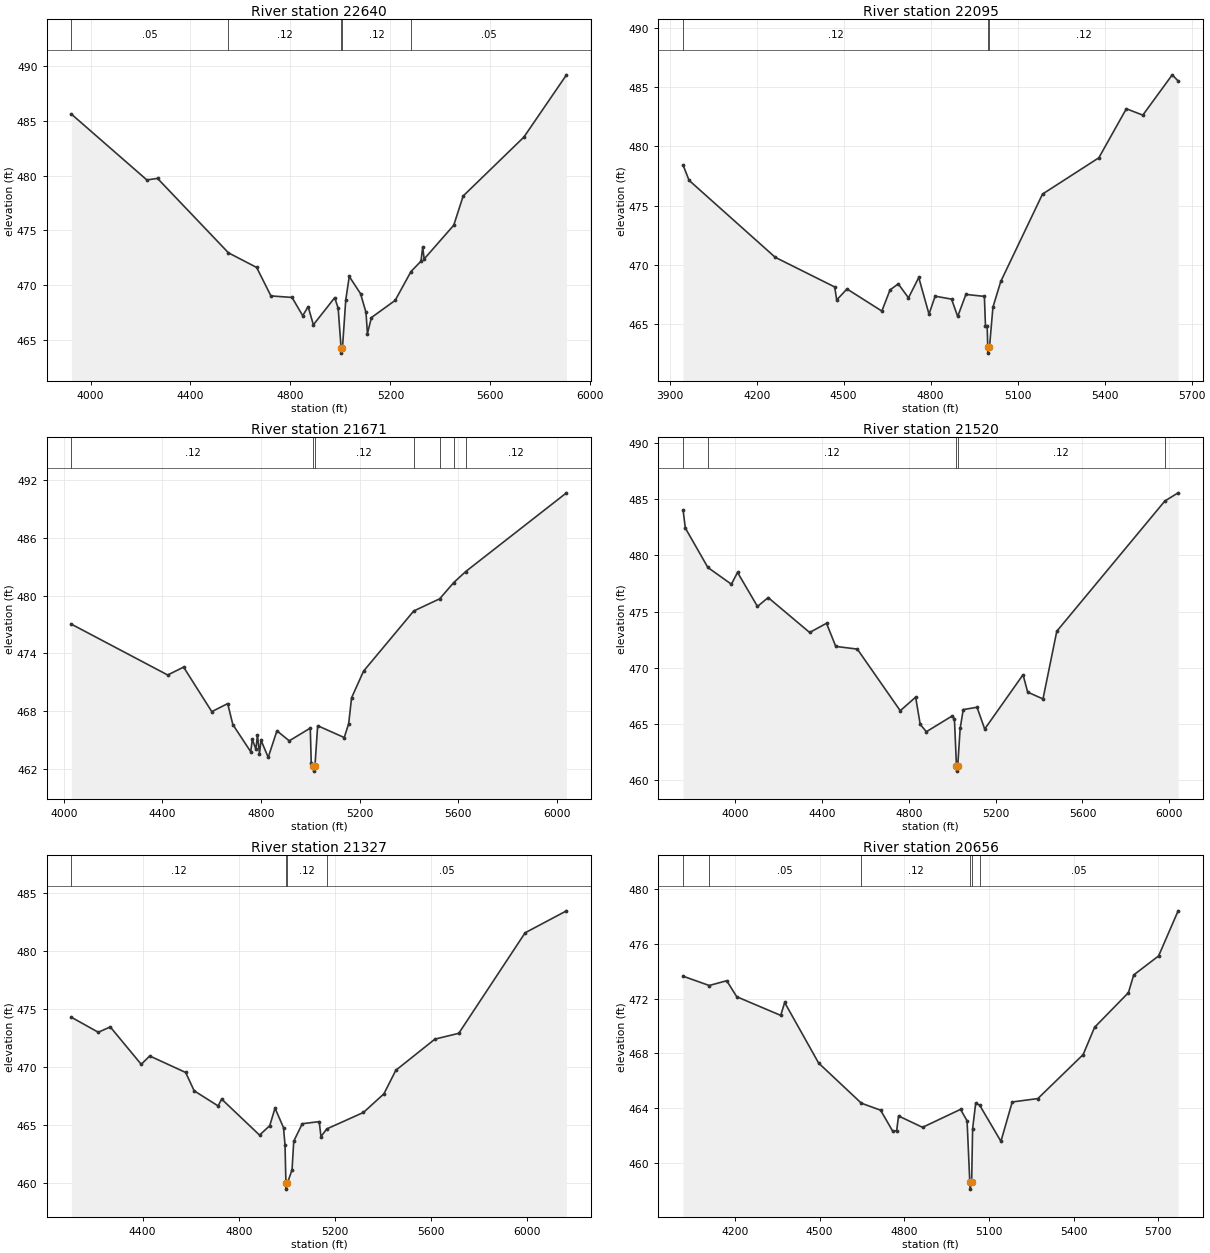
Type RM Length L Ch R = 1 ,22640   ,545,545,545
BEGIN DESCRIPTION:
Williams T6 36.0
END DESCRIPTION:
XS GIS Cut Line= 3
      2682488.47      6912084.58       2681788.5      6911284.61
      2680988.46      6910834.59
#Sta/Elev= 30
  3923.6  485.59  4225.4   479.6  4268.1  479.74  4552.1  472.96  4664.8  471.63
  4721.8  469.04  4806.3   468.9    4849  467.24  4870.8  468.06  4891.7  466.41
  4977.1  468.88  4990.9  467.92  5002.5  464.33  5003.4  463.83  5008.2  464.33
  5021.3  468.68  5035.3  470.81  5080.6  469.24  5102.3  467.53    5108  465.61
    5124  467.07  5218.9  468.63  5282.3  471.26  5322.2   472.2  5329.2   473.5
  5334.9   472.4  5453.5  475.48  5491.1  478.14    5734   483.5  5904.5  489.17
#Mann= 5 ,-1 , 0
  3923.6     .05       0  4552.1     .12       0  5002.5     .07       0
  5008.2     .12       0  5282.3     .05       0
Bank Sta=5002.5,5008.2
XS Rating Curve= 0 ,0
Exp/Cntr=0.3,0.1

Type RM Length L Ch R = 1 ,22095   ,424,424,424
BEGIN DESCRIPTION:
Mapping XS eca79213
END DESCRIPTION:
XS GIS Cut Line= 3
      2682555.15      6911521.29       2681815.6      6910781.74
      2681270.75      6910406.94
#Sta/Elev= 30
  3946.2  478.43    3967  477.13    4264  470.62  4469.1  468.11  4476.1  467.01
  4511.5  467.94  4631.7  466.07    4660  467.86  4688.3  468.37  4723.6  467.19
    4759  468.91  4794.3  465.81  4815.5  467.33  4872.1  467.08  4893.3  465.61
  4921.6  467.48  4985.3  467.31  4989.1  464.81  4994.9  464.81    4997  463.01
  4997.9  462.51  5002.9  463.01  5014.8   466.4  5041.9  468.58  5185.8  475.97
    5380  479.04  5474.8  483.19  5531.6  482.65  5633.1  486.06  5653.4  485.54
#Mann= 3 ,-1 , 0
  3946.2     .12       0    4997     .07       0  5002.9     .12       0
Bank Sta=4997,5002.9
XS Rating Curve= 0 ,0
Exp/Cntr=0.3,0.1

Type RM Length L Ch R = 1 ,21671   ,151,151,151
BEGIN DESCRIPTION:
Mapping XS 1d040ab9
END DESCRIPTION:
XS GIS Cut Line= 3
      2682693.03      6911352.16      2682106.26      6910574.42
      2681144.48      6910192.48
#Sta/Elev= 30
  4030.5  477.04  4421.2  471.76  4485.7  472.58  4600.2  467.95  4664.7  468.79
  4685.5  466.61  4758.3  463.78  4764.6  465.07  4779.2  464.04  4785.4  465.53
  4793.7   463.6    4800  464.98  4829.1   463.2  4864.5  465.96  4914.5  464.92
  4999.8  466.24  5003.8  462.57  5012.8  462.27  5013.8  461.77  5018.7  462.27
  5029.8  466.49  5137.7  465.26  5155.7  466.71  5167.4  469.39    5216  472.16
  5419.6  478.41  5525.1  479.68  5582.1  481.37  5630.6  482.51  6039.6  490.69
#Mann= 7 ,-1 , 0
  4030.5     .12       0  5012.8     .07       0  5018.7     .12       0
  5419.6     .05       0  5525.1     .12       0  5582.1     .05       0
  5630.6     .12       0
Bank Sta=5012.8,5018.7
XS Rating Curve= 0 ,0
Exp/Cntr=0.3,0.1

Type RM Length L Ch R = 1 ,21520   ,193,193,193
BEGIN DESCRIPTION:
Mapping XS c49c9397
END DESCRIPTION:
XS GIS Cut Line= 3
      2683082.18      6911459.41      2682241.89      6910532.32
      2681512.74      6909803.17
#Sta/Elev= 30
  3758.6  484.06  3769.2  482.44  3873.1  478.93  3981.4  477.44  4009.8  478.49
  4101.7  475.46    4151  476.25  4342.3  473.14    4420  473.96  4462.6   471.9
    4562  471.66    4760  466.17  4830.9  467.38  4851.9  464.96  4880.3   464.3
  5000.6  465.72  5009.8  465.41    5019  461.29    5020  460.79    5025  461.29
  5036.1  464.59  5050.3  466.27  5113.9  466.48  5149.3  464.54  5326.1  469.38
  5347.3  467.83    5418  467.22  5481.6  473.25  5979.7  484.85    6041  485.58
#Mann= 5 ,-1 , 0
  3758.6     .05       0  3873.1     .12       0    5019     .07       0
    5025     .12       0  5979.7     .05       0
Bank Sta=5019,5025
XS Rating Curve= 0 ,0
Exp/Cntr=0.3,0.1

Type RM Length L Ch R = 1 ,21327   ,671,671,671
BEGIN DESCRIPTION:
Williams T6 32.0
END DESCRIPTION:
XS GIS Cut Line= 3
      2682899.67      6911093.88      2682352.82      6910384.71
      2681515.35      6909578.35
#Sta/Elev= 30
  4104.2  474.27  4215.9  472.98  4265.7  473.44  4394.4  470.22  4429.7  470.94
  4579.2  469.52  4614.5  467.94  4714.1  466.64  4728.6  467.23  4886.3  464.13
  4928.6  464.94  4950.6  466.45  4985.9  464.77  4992.2  463.26  4995.9  459.98
  4996.9  459.48  5001.9  459.98  5021.4  461.15  5028.4   463.6  5063.9  465.11
  5134.4  465.29  5141.6     464  5165.7  464.66  5318.3  466.08  5403.2  467.68
  5452.9  469.71  5615.4  472.39  5714.5  472.89  5990.3  481.54  6162.3  483.43
#Mann= 4 ,-1 , 0
  4104.2     .12       0  4995.9     .07       0  5001.9     .12       0
  5165.7     .05       0
Bank Sta=4995.9,5001.9
XS Rating Curve= 0 ,0
Exp/Cntr=0.3,0.1

Type RM Length L Ch R = 1 ,20656   ,723,723,723
BEGIN DESCRIPTION:
Mapping XS 7bad50be
END DESCRIPTION:
XS GIS Cut Line= 3
      2683064.39      6910611.26      2682387.33      6909871.69
      2681692.02      6909587.84
#Sta/Elev= 30
  4016.2  473.64  4108.9  472.96  4170.9  473.31  4206.4  472.14  4362.1  470.78
  4376.2  471.72  4496.5   467.3  4647.9  464.37    4716  463.86  4758.6  462.34
  4772.8  462.36  4779.5  463.44  4864.6  462.61  4999.1  463.92  5022.3  463.09
    5032   458.6    5033   458.1  5038.5   458.6  5041.9   462.5  5052.7  464.36
  5066.7  464.23  5142.2  461.59  5182.3  464.46  5273.1  464.71  5433.5  467.92
    5474  469.91  5593.9  472.44  5612.5  473.73  5700.8  475.12  5769.9  478.41
#Mann= 6 ,-1 , 0
  4016.2     .12       0  4108.9     .05       0  4647.9     .12       0
    5032     .07       0  5038.5     .12       0  5066.7     .05       0
Bank Sta=5032,5038.5
XS Rating Curve= 0 ,0
Exp/Cntr=0.3,0.1

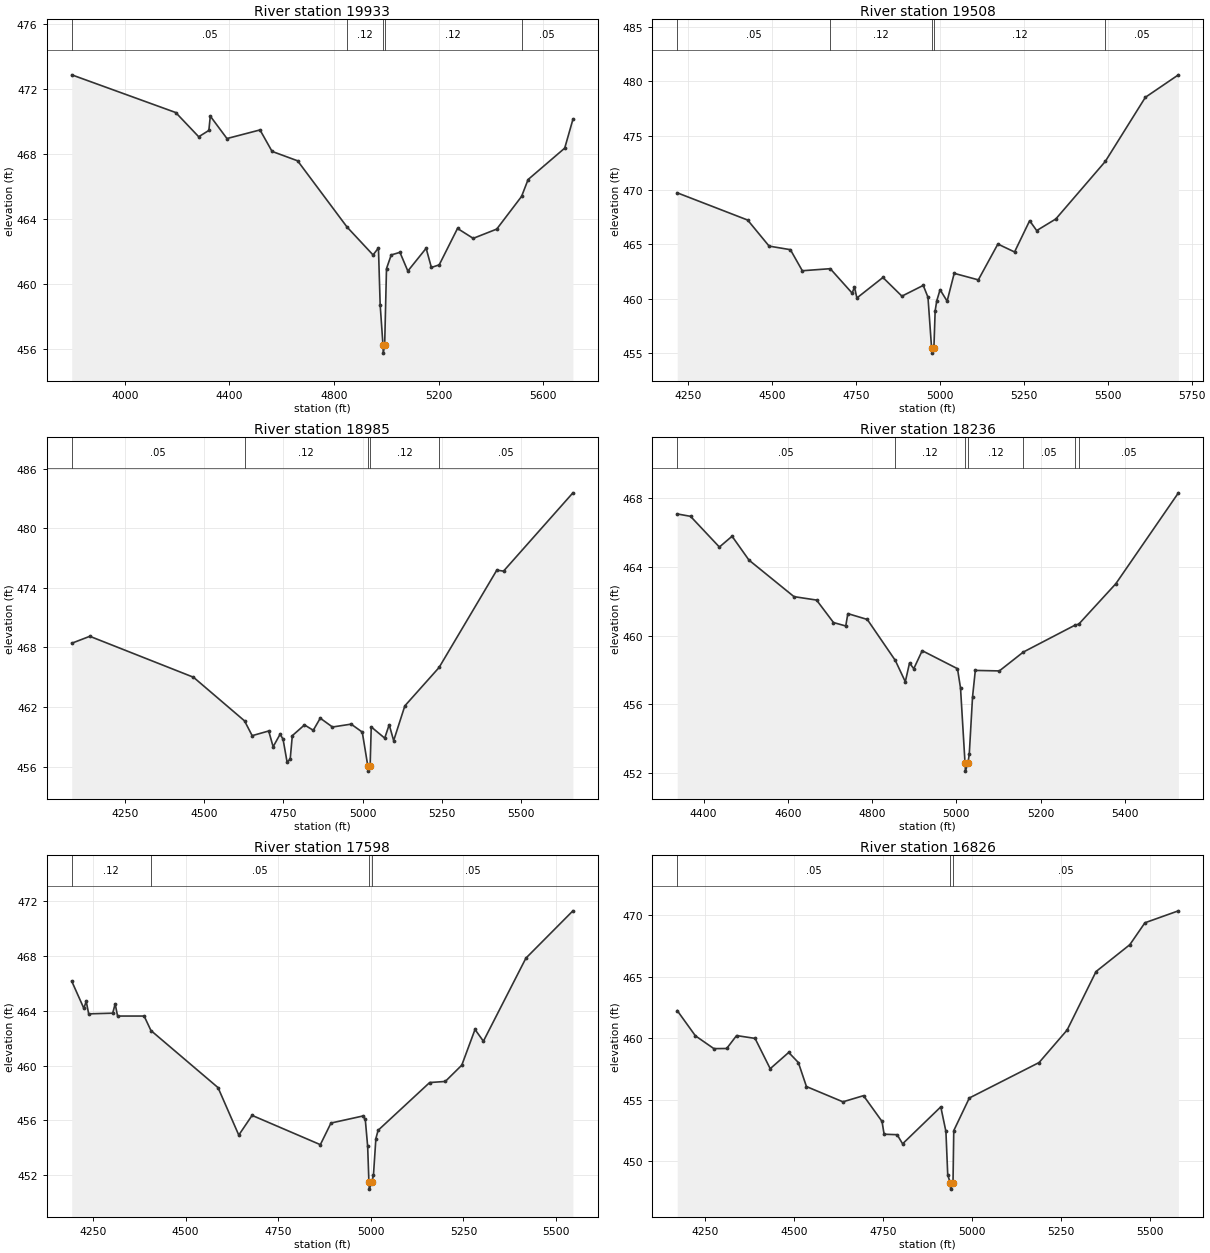
Type RM Length L Ch R = 1 ,19933   ,425,425,425
BEGIN DESCRIPTION:
Mapping XS e296cecc
END DESCRIPTION:
XS GIS Cut Line= 4
      2683198.08      6910473.23      2682732.81      6909448.95
      2682600.87       6909417.7      2681944.59      6909410.75
#Sta/Elev= 30
  3796.7  472.88  4194.5  470.56  4282.4  469.07  4321.2  469.46  4326.7  470.34
  4390.4  468.96  4516.8  469.49  4562.9  468.17  4660.7  467.59  4849.5  463.52
  4949.2   461.8  4969.8  462.23  4976.4  458.73  4987.1  456.26  4988.2  455.76
  4993.6  456.26  5000.6  460.96  5018.7   461.8    5052  461.96  5082.2  460.81
  5152.2  462.21  5172.2  461.03  5202.2  461.19  5272.2  463.43  5332.2  462.82
  5422.2  463.39  5517.2   465.4  5542.2  466.44  5682.2  468.37  5713.6  470.14
#Mann= 5 ,-1 , 0
  3796.7     .05       0  4849.5     .12       0  4987.1     .07       0
  4993.6     .12       0  5517.2     .05       0
Bank Sta=4987.1,4993.6
XS Rating Curve= 0 ,0
Exp/Cntr=0.3,0.1

Type RM Length L Ch R = 1 ,19508   ,523,523,523
BEGIN DESCRIPTION:
Mapping XS f9782e2b
END DESCRIPTION:
XS GIS Cut Line= 3
      2683226.74      6909617.35      2682664.24      6909080.89
      2682069.43      6908680.89
#Sta/Elev= 30
  4216.5  469.74  4426.5  467.23  4490.4  464.83  4553.9   464.5  4589.4  462.56
  4672.7  462.75  4737.9   460.5  4744.8  461.05  4752.1  460.05  4829.7  461.94
  4886.3  460.22  4949.9  461.21    4964  460.12  4974.7  455.47  4975.8  454.97
  4981.7  455.47  4985.4  458.86  4990.1  459.78  5000.1  460.81  5021.1  459.76
  5042.2  462.32  5114.1  461.72  5172.4  465.02  5222.1  464.29  5267.1  467.17
  5288.1  466.26  5345.1  467.33  5492.6  472.63  5612.1  478.54  5710.6  480.61
#Mann= 5 ,-1 , 0
  4216.5     .05       0  4672.7     .12       0  4974.7     .07       0
  4981.7     .12       0  5492.6     .05       0
Bank Sta=4974.7,4981.7
XS Rating Curve= 0 ,0
Exp/Cntr=0.3,0.1

Type RM Length L Ch R = 1 ,18985   ,749,749,749
BEGIN DESCRIPTION:
Mapping XS 74d34c94
END DESCRIPTION:
XS GIS Cut Line= 3
      2683335.43       6909540.7      2682920.42      6908752.26
      2682436.55      6908261.05
#Sta/Elev= 30
  4082.7  468.42  4139.8  469.12  4466.6     465  4627.6  460.61  4651.7  459.12
  4703.9  459.59  4717.8     458  4739.9  459.27  4749.1  458.76  4761.9  456.45
  4771.7  456.77  4778.3  459.12  4816.7   460.2  4844.4  459.66  4866.4  460.88
  4904.9  459.99  4963.8  460.28  4998.9  459.48  5016.5  456.05  5017.6  455.55
  5023.7  456.05  5027.2     460  5069.7  458.87  5083.8  460.22  5097.9  458.62
  5133.2  462.12  5241.1  465.98  5423.2  475.78  5444.4  475.68  5663.2  483.56
#Mann= 5 ,-1 , 0
  4082.7     .05       0  4627.6     .12       0  5016.5     .07       0
  5023.7     .12       0  5241.1     .05       0
Bank Sta=5016.5,5023.7
XS Rating Curve= 0 ,0
Exp/Cntr=0.3,0.1

Type RM Length L Ch R = 1 ,18236   ,638,638,638
BEGIN DESCRIPTION:
Williams T6 28.0
END DESCRIPTION:
XS GIS Cut Line= 3
      2683473.26      6909370.79      2683420.37       6908710.4
      2683075.98      6908310.97
#Sta/Elev= 30
  4337.5  467.09  4369.1  466.95  4437.6  465.16  4467.7  465.79  4507.8   464.4
  4614.7  462.27  4668.3  462.07  4708.5  460.76  4737.6  460.56  4742.6  461.28
  4788.7  460.94  4855.3  458.55    4879  457.31    4889   458.4  4899.1  458.07
  4919.1  459.12  5002.9  458.07  5010.1  456.94  5020.7   452.6  5021.8   452.1
    5028   452.6  5030.9  453.11  5038.6  456.42  5045.2  457.97  5102.2  457.94
  5159.2  459.04  5281.3   460.6  5290.9  460.67  5378.7  463.02  5527.4  468.32
#Mann= 7 ,-1 , 0
  4337.5     .05       0  4855.3     .12       0  5020.7     .07       0
    5028     .12       0  5159.2     .05       0  5281.3     .12       0
  5290.9     .05       0
Bank Sta=5020.7,5028
XS Rating Curve= 0 ,0
Exp/Cntr=0.3,0.1

Type RM Length L Ch R = 1 ,17598   ,772,772,772
BEGIN DESCRIPTION:
Williams T6 27.0
END DESCRIPTION:
XS GIS Cut Line= 3
      2684175.73      6908846.32      2683661.86      6908223.81
      2683204.38      6907927.05
#Sta/Elev= 30
  4192.8  466.17  4225.4  464.19  4231.9  464.69  4238.6  463.78  4303.4  463.83
    4310  464.51  4316.5  463.62  4388.2  463.62  4406.6  462.56  4587.6  458.39
  4643.6  454.92  4679.5  456.36  4863.7  454.22  4892.4   455.8  4977.7  456.31
  4984.9  456.09  4991.4  454.09  4994.8  451.47  4995.9  450.97  5002.4  451.47
    5007  451.98  5013.6  454.67  5019.6  455.27  5158.7  458.76  5200.9  458.84
  5245.4  460.03  5281.1  462.64  5303.7  461.78  5418.4  467.85  5545.3  471.31
#Mann= 4 ,-1 , 0
  4192.8     .12       0  4406.6     .05       0  4994.8     .04       0
  5002.4     .05       0
Bank Sta=4994.8,5002.4
XS Rating Curve= 0 ,0
Exp/Cntr=0.3,0.1

Type RM Length L Ch R = 1 ,16826   ,719,719,719
BEGIN DESCRIPTION:
Williams T6 25.0
END DESCRIPTION:
XS GIS Cut Line= 3
      2684548.32      6908378.73      2684145.51      6907732.86
      2683600.99        6907386.
#Sta/Elev= 30
  4172.3  462.25  4223.3   460.2  4275.2  459.16  4311.1  459.17  4338.9  460.22
  4390.8  459.99  4433.3  457.53  4485.2  458.85  4512.3  458.03    4535  456.08
  4637.4  454.84  4695.2  455.34  4747.1  453.25    4753  452.21  4789.6  452.17
  4804.9  451.43  4912.1  454.43  4926.5  452.43  4931.6   448.9  4938.7  448.25
  4939.8  447.75  4946.4  448.25  4948.5   452.5  4992.2  455.15    5188  458.03
  5266.7  460.67  5347.9  465.42  5442.7   467.6  5485.1  469.38  5579.1  470.35
#Mann= 3 ,-1 , 0
  4172.3     .05       0  4938.7     .04       0  4946.4     .05       0
Bank Sta=4938.7,4946.4
XS Rating Curve= 0 ,0
Exp/Cntr=0.3,0.1

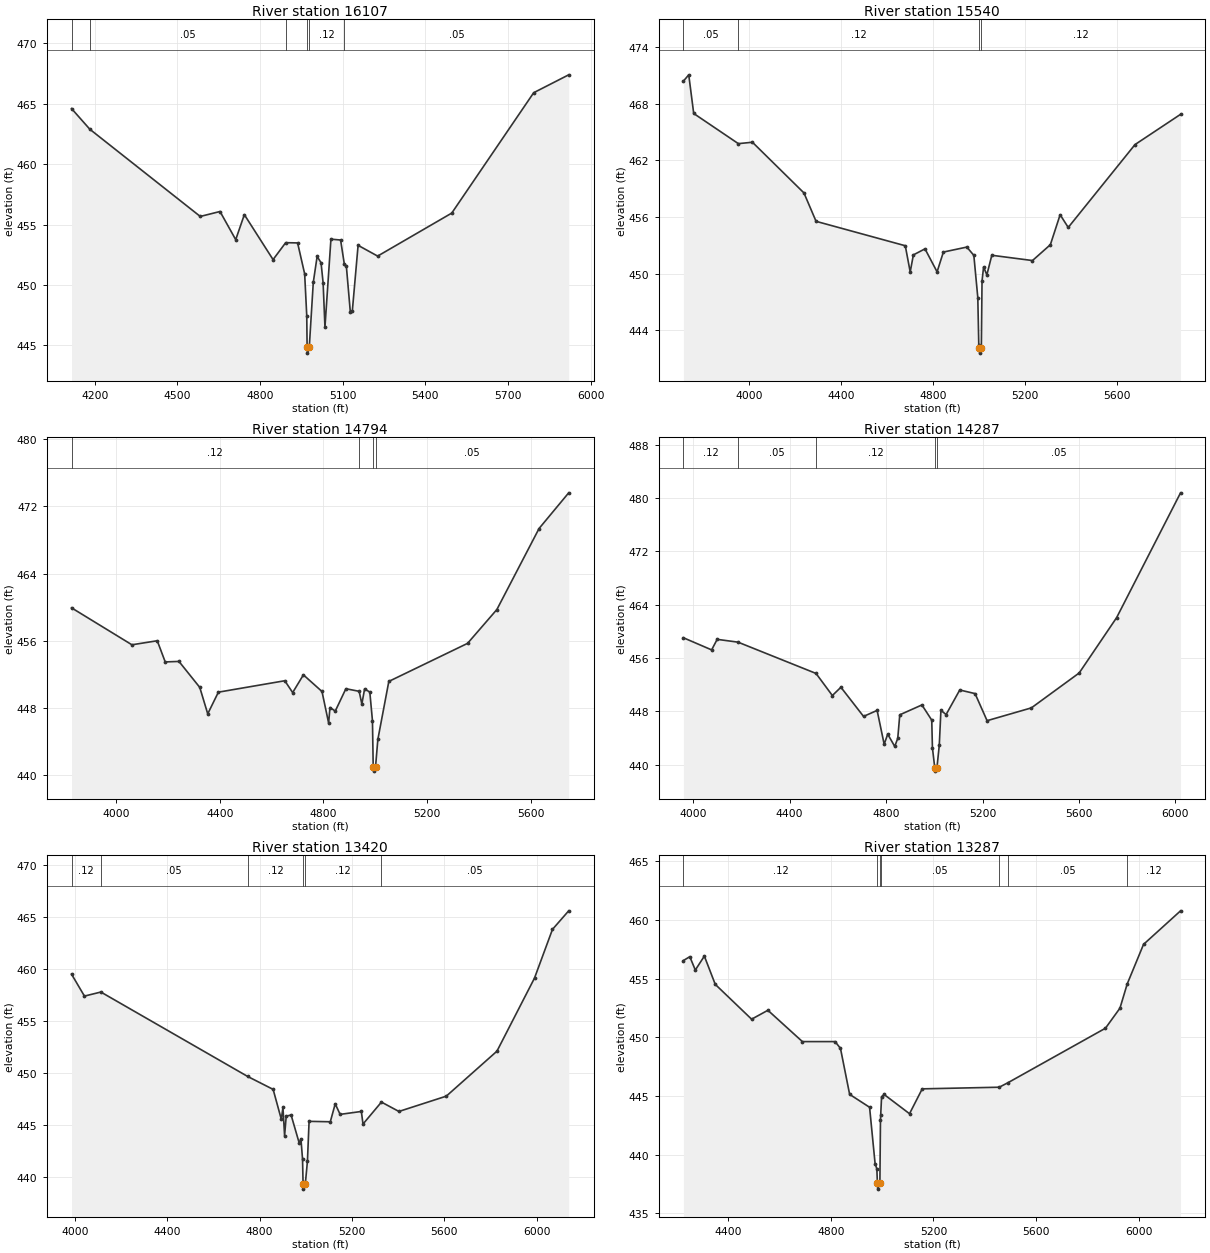
Type RM Length L Ch R = 1 ,16107   ,567,567,567
BEGIN DESCRIPTION:
Williams T6 24.0
END DESCRIPTION:
XS GIS Cut Line= 3
      2684944.13       6908392.6      2684693.03      6907544.49
      2684076.08      6906861.34
#Sta/Elev= 30
  4115.5   464.6  4181.8  462.89  4582.9  455.67  4654.6  456.08  4711.6  453.75
  4742.9  455.82  4847.2   452.1    4893   453.5  4936.3  453.48  4961.9  450.92
  4969.5  447.46  4970.8  444.86  4971.9  444.36  4978.7  444.86  4993.2  450.21
  5007.2  452.36  5021.4  451.84  5028.9  450.18  5035.6  446.51  5057.3  453.79
  5092.4  453.72  5105.7  451.76  5113.4  451.53  5127.6  447.79    5135  447.86
  5155.9  453.28  5226.9  452.39    5496  455.95  5793.4  465.91  5920.5  467.39
#Mann= 6 ,-1 , 0
  4115.5     .12       0  4181.8     .05       0    4893     .12       0
  4970.8     .07       0  4978.7     .12       0  5105.7     .05       0
Bank Sta=4970.8,4978.7
XS Rating Curve= 0 ,0
Exp/Cntr=0.3,0.1

Type RM Length L Ch R = 1 ,15540   ,746,746,746
BEGIN DESCRIPTION:
Williams T6 22.0
END DESCRIPTION:
XS GIS Cut Line= 3
      2685676.02      6908411.03      2685023.99      6907311.85
      2684376.01      6906711.01
#Sta/Elev= 30
  3715.5  470.41  3738.8  471.08  3760.4  466.98  3954.5  463.78  4015.7  463.93
  4239.8  458.55  4292.4  455.54  4680.3  452.95  4701.7  450.17  4715.5  451.98
    4766  452.62  4818.6  450.18  4845.9  452.28    4948  452.81  4978.4  451.93
  4995.6  447.46  4999.9   442.4  5002.3  442.06  5003.6  441.56    5011  442.06
    5014   449.2  5020.8   450.7    5035  449.86  5056.5  451.94  5233.4  451.38
  5311.1  453.06  5353.6  456.24  5388.8  454.89  5679.1  463.68  5877.2  466.89
#Mann= 4 ,-1 , 0
  3715.5     .05       0  3954.5     .12       0  5002.3     .07       0
    5011     .12       0
Bank Sta=5002.3,5011
XS Rating Curve= 0 ,0
Exp/Cntr=0.3,0.1

Type RM Length L Ch R = 1 ,14794   ,507,507,507
BEGIN DESCRIPTION:
Williams T6 20.0
END DESCRIPTION:
XS GIS Cut Line= 3
      2685563.04       6907853.7       2685300.8      6906710.69
      2684764.41      6906190.51
#Sta/Elev= 30
  3827.3  459.92  4060.5  455.52  4158.4     456  4189.1  453.48  4242.2  453.54
  4322.5  450.45  4353.3   447.3  4394.4  449.88  4650.9  451.24  4681.3  449.83
  4722.7  451.94  4794.5  449.96  4820.2   446.2  4825.3  448.05  4845.8  447.63
  4886.8  450.29  4938.1  449.98  4948.4  448.47  4959.1  450.27  4979.2  449.89
  4989.4  446.49  4992.3  440.98  4993.6  440.48  5001.3  440.98  5010.2  444.25
  5052.6  451.16  5356.7  455.69  5469.9  459.72  5632.7  469.36  5747.2  473.61
#Mann= 4 ,-1 , 0
  3827.3     .12       0  4938.1     .05       0  4992.3     .03       0
  5001.3     .05       0
Bank Sta=4992.3,5001.3
XS Rating Curve= 0 ,0
Exp/Cntr=0.3,0.1

Type RM Length L Ch R = 1 ,14287   ,867,867,867
BEGIN DESCRIPTION:
Mapping XS dfe7eef5
END DESCRIPTION:
XS GIS Cut Line= 3
      2686529.16      6907162.74      2685702.81      6906548.18
      2684994.51      6905798.22
#Sta/Elev= 30
  3959.6  459.04  4076.7  457.22  4099.7   458.8  4186.1  458.38  4509.6  453.69
  4577.3  450.38  4612.7  451.62  4706.6  447.25  4762.9  448.15  4792.1  443.08
  4806.8  444.59  4835.9  442.75  4848.4  443.96  4856.8  447.49  4948.6  448.97
  4989.4  446.69  4992.2  442.54  5001.9  439.55  5003.2  439.05  5010.9  439.55
  5020.6  442.92  5027.4  448.16  5048.9  447.53  5105.5  451.21    5169  450.67
  5218.8  446.61  5402.5  448.53  5600.7  453.76    5756  462.06    6021  480.76
#Mann= 5 ,-1 , 0
  3959.6     .12       0  4186.1     .05       0  4509.6     .12       0
  5001.9     .07       0  5010.9     .05       0
Bank Sta=5001.9,5010.9
XS Rating Curve= 0 ,0
Exp/Cntr=0.3,0.1

Type RM Length L Ch R = 1 ,13420   ,133,133,133
BEGIN DESCRIPTION:
Mapping XS aec9ebd5
END DESCRIPTION:
XS GIS Cut Line= 3
       2686760.1        6906826.       2686697.6      6906489.15
      2685416.35      6905211.38
#Sta/Elev= 30
  3985.8  459.49  4041.7  457.38  4112.8  457.77  4748.4  449.66  4858.5  448.42
  4893.9  445.55    4901  446.69  4908.1  443.96  4915.1  445.85  4936.3  445.96
  4971.7  443.24  4978.8  443.68  4985.8  441.73  4988.1  439.34  4989.5  438.84
  4997.8  439.34    5007  441.53  5014.1  445.35    5106  445.31  5127.2  447.03
  5148.5  446.02  5240.4   446.3  5247.5  445.09  5327.3   447.2    5403   446.3
  5608.1  447.77  5827.3  452.09  5989.9  459.11  6067.7  463.79  6137.9  465.57
#Mann= 6 ,-1 , 0
  3985.8     .12       0  4112.8     .05       0  4748.4     .12       0
  4988.1     .07       0  4997.8     .12       0  5327.3     .05       0
Bank Sta=4988.1,4997.8
XS Rating Curve= 0 ,0
Exp/Cntr=0.3,0.1

Type RM Length L Ch R = 1 ,13287   ,585,585,585
BEGIN DESCRIPTION:
Mapping XS 434aaa71
END DESCRIPTION:
XS GIS Cut Line= 3
      2686843.46      6906489.19      2686315.65      6905919.71
       2685496.2      6905096.78
#Sta/Elev= 30
  4225.3  456.54  4250.3  456.87  4271.8  455.73    4307  456.92  4349.5  454.51
  4491.2  451.54  4554.7   452.3  4689.1  449.63  4816.6  449.63  4837.6  449.05
  4873.3  445.13    4951  444.03  4972.5  439.23  4979.4  438.77  4981.5  437.55
  4982.9  437.05  4991.2  437.55  4993.5  442.97  4994.3  443.33  4997.8  444.93
  5007.7  445.12  5106.7  443.48  5156.2   445.6  5456.5  445.74  5491.7  446.14
  5870.4  450.77  5926.9  452.48  5955.1  454.54  6018.8  457.92  6163.1  460.78
#Mann= 7 ,-1 , 0
  4225.3     .12       0  4981.5     .04       0  4991.2     .12       0
  4994.3     .05       0  5456.5     .12       0  5491.7     .05       0
  5955.1     .12       0
Bank Sta=4981.5,4991.2
XS Rating Curve= 0 ,0
Exp/Cntr=0.3,0.1