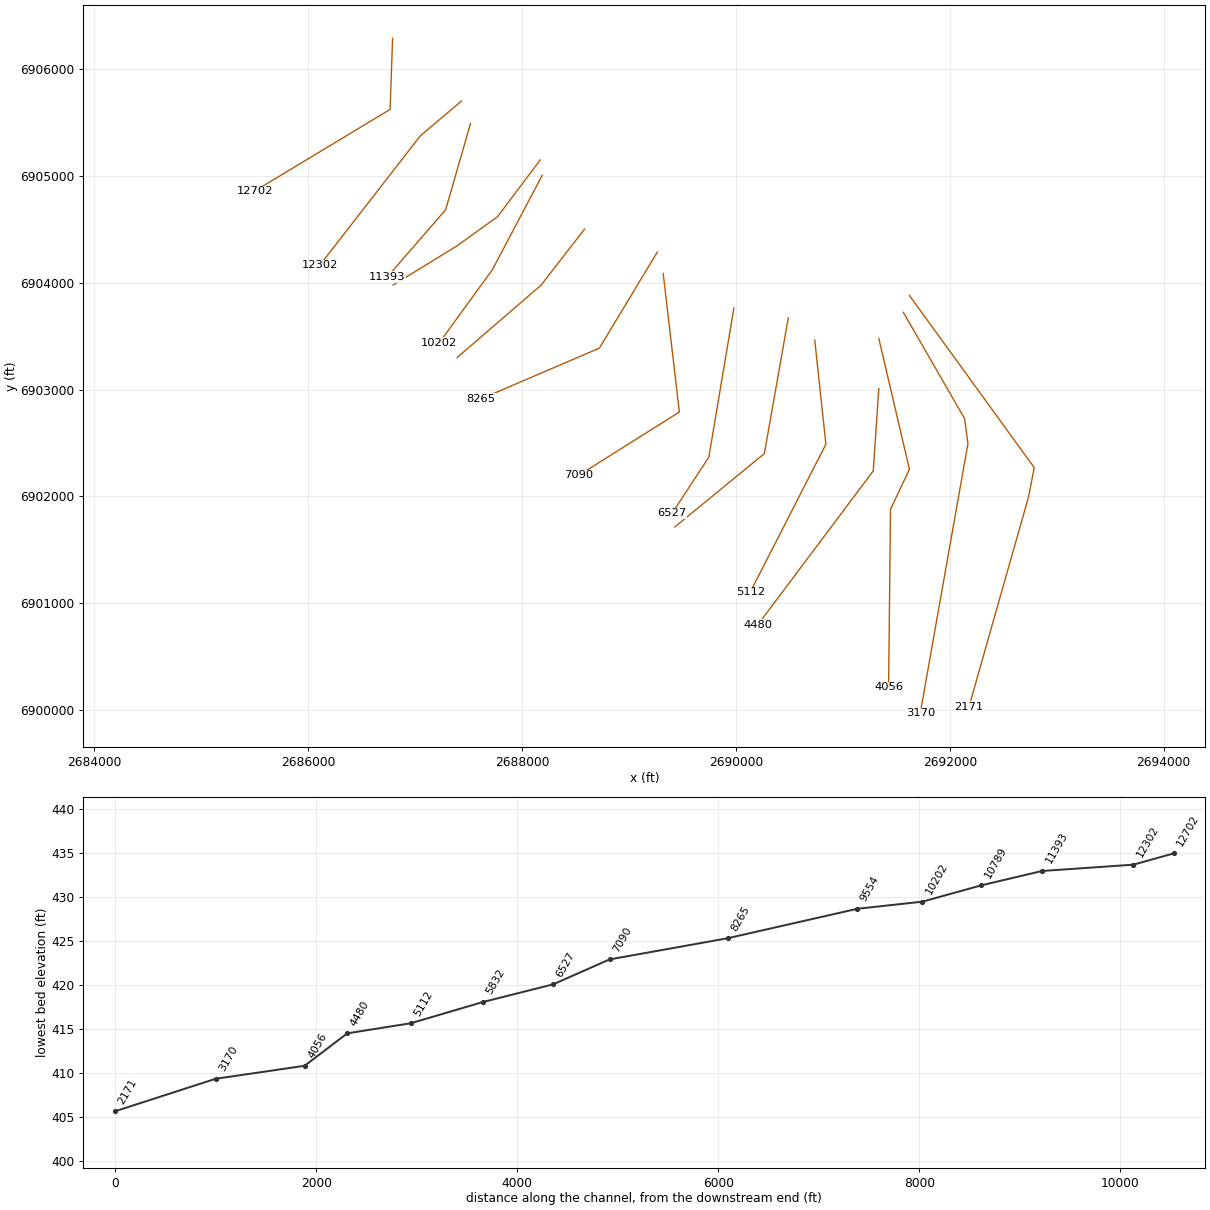
HEC-RAS study Williams T6.prj: Williams T6 Base Level Engineering

--- Williams T6.g01 (geometry) --- (continued)

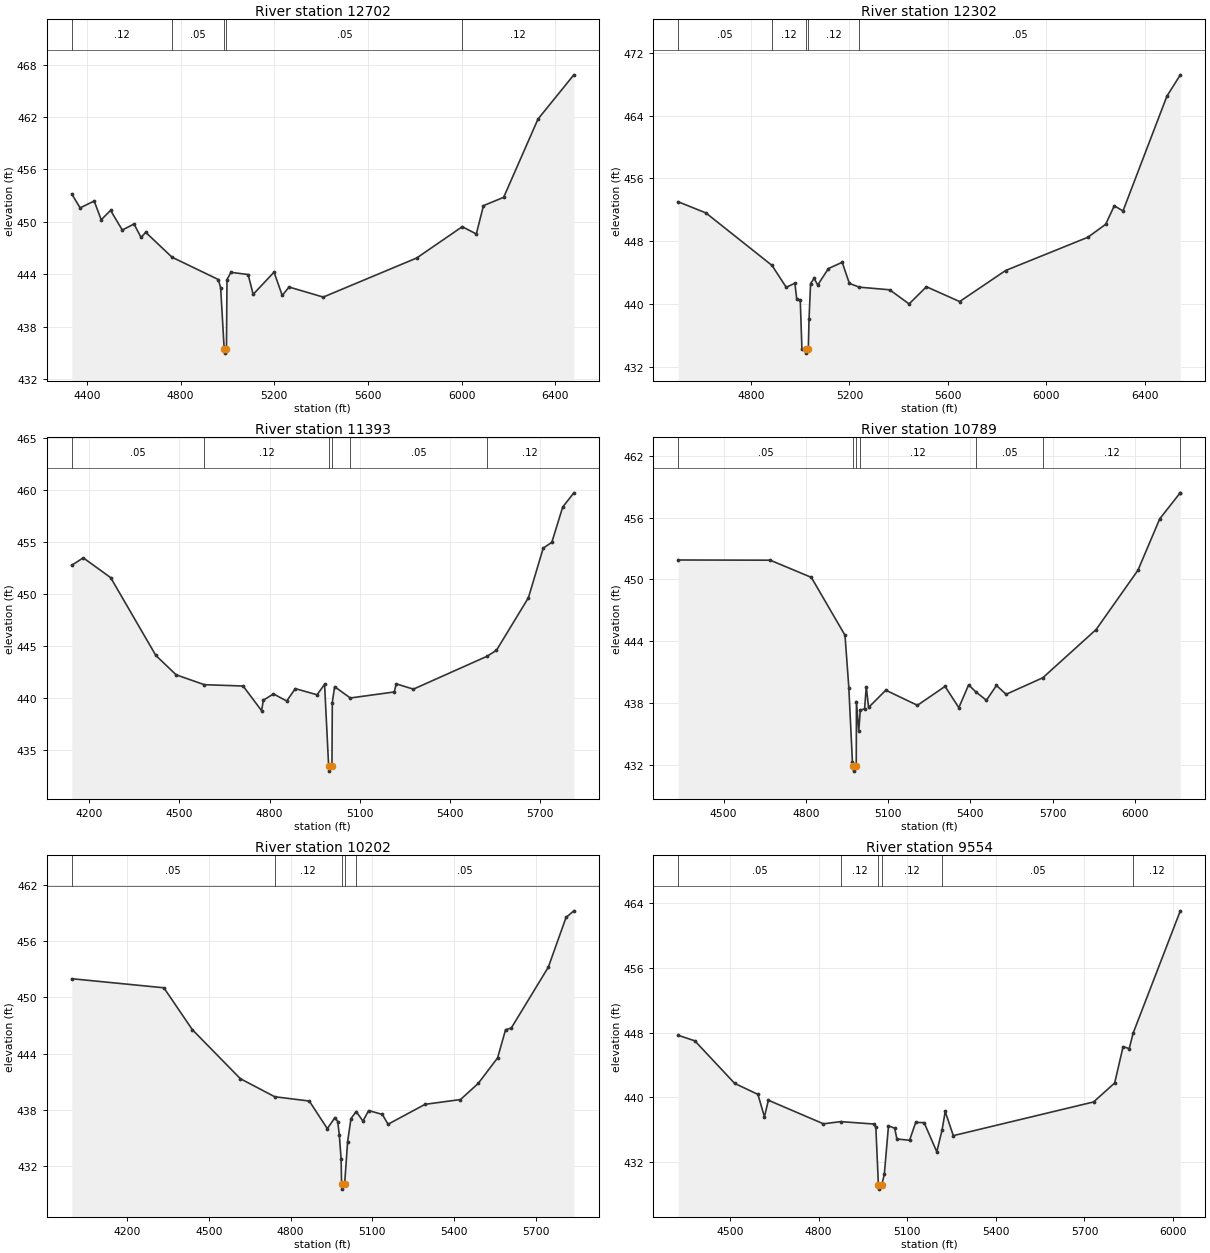
Type RM Length L Ch R = 1 ,12702   ,400,400,400
BEGIN DESCRIPTION:
Williams T6 15.0
END DESCRIPTION:
XS GIS Cut Line= 3
      2686789.26       6906286.7      2686766.33       6905621.8
      2685499.27      6904857.17
#Sta/Elev= 30
  4334.7   453.2  4370.4   451.6  4430.5  452.39  4460.5  450.24  4500.5  451.32
  4550.5  449.07  4600.6  449.76  4630.6  448.22  4650.6  448.81  4763.1  445.96
  4960.8  443.41  4970.8  442.47  4985.9  435.49  4987.3  434.99  4995.6  435.49
  4997.9   443.4  5014.6  444.23  5088.3  443.98  5109.7  441.71  5198.9  444.25
    5234  441.59    5263  442.55  5409.2   441.4  5808.4  445.87    6003  449.45
  6063.2  448.62  6093.8  451.86    6180  452.81  6326.7  461.76  6479.9  466.82
#Mann= 5 ,-1 , 0
  4334.7     .12       0  4763.1     .05       0  4985.9     .03       0
  4995.6     .05       0    6003     .12       0
Bank Sta=4985.9,4995.6
XS Rating Curve= 0 ,0
Exp/Cntr=0.3,0.1

Type RM Length L Ch R = 1 ,12302   ,909,909,909
BEGIN DESCRIPTION:
Mapping XS edb2d50b
END DESCRIPTION:
XS GIS Cut Line= 3
      2687434.19      6905700.75      2687048.81       6905374.4
      2686107.87      6904162.63
#Sta/Elev= 30
  4504.5  453.02  4616.8   451.6  4885.4   444.9  4943.1  442.11  4978.3  442.63
    4986  440.56  5000.1   440.5  5006.8  434.27  5022.2  434.21  5023.7  433.71
  5032.8  434.21  5035.7  438.02    5042  442.59  5056.5  443.25    5071   442.4
  5114.4   444.5  5170.5   445.3  5199.5  442.61  5239.5  442.13  5363.3  441.79
  5442.1  439.99  5512.6  442.18  5647.5  440.29    5834  444.25  6167.9  448.49
  6240.3  450.14  6275.6  452.51  6310.9  451.85  6489.2  466.49  6543.7  469.22
#Mann= 5 ,-1 , 0
  4504.5     .05       0  4885.4     .12       0  5022.2     .07       0
  5032.8     .12       0  5239.5     .05       0
Bank Sta=5022.2,5032.8
XS Rating Curve= 0 ,0
Exp/Cntr=0.3,0.1

Type RM Length L Ch R = 1 ,11393   ,604,604,604
BEGIN DESCRIPTION:
Mapping XS a724b782
END DESCRIPTION:
XS GIS Cut Line= 3
      2687517.56      6905487.81      2687285.79      6904683.13
      2686739.96      6904054.13
#Sta/Elev= 30
  4142.1  452.78  4180.4  453.49  4271.5  451.59  4421.8  444.11  4489.2  442.25
  4582.9   441.3  4712.1  441.17  4773.6   438.8  4779.4  439.81  4813.1  440.41
  4857.2  439.73  4885.6  440.92  4958.2  440.33  4983.1  441.34  4996.6  433.49
  4998.1  432.99  5007.6  433.49  5008.8  439.58  5016.4  441.11  5068.7  440.02
  5214.8   440.6  5221.5  441.38  5278.5  440.87  5522.8  444.02  5554.8   444.6
  5661.2  449.66  5710.5  454.43    5739  454.98  5775.2  458.37  5812.3  459.74
#Mann= 6 ,-1 , 0
  4142.1     .05       0  4582.9     .12       0  4996.6     .07       0
  5007.6     .12       0  5068.7     .05       0  5522.8     .12       0
Bank Sta=4996.6,5007.6
XS Rating Curve= 0 ,0
Exp/Cntr=0.3,0.1

Type RM Length L Ch R = 1 ,10789   ,587,587,587
BEGIN DESCRIPTION:
Mapping XS 8fc5b3ea
END DESCRIPTION:
XS GIS Cut Line= 4
      2688169.48      6905148.43      2687770.17      6904617.16
      2687388.22      6904342.86      2686794.46      6903978.27
#Sta/Elev= 30
  4334.3  451.89  4669.9  451.87  4819.8   450.2  4942.7  444.57  4956.6  439.49
  4969.8  432.23  4972.6  431.86  4974.1  431.36  4983.7  431.86  4984.4  438.13
  4992.7  435.22  4998.5  437.29  5014.1  437.42  5020.3  439.57  5028.7  437.55
  5091.5  439.23  5206.9  437.76  5307.6   439.6  5357.9  437.53  5393.5  439.74
  5420.6  439.05  5458.6  438.25  5495.2  439.69  5530.4  438.83  5664.4  440.44
  5858.8  445.13  6011.5   450.9  6090.8  455.89  6165.4  458.42  6165.9  458.42
#Mann= 7 ,-1 , 0
  4334.3     .05       0  4972.6     .07       0  4983.7     .05       0
  4998.5     .12       0  5420.6     .05       0  5664.4     .12       0
  6165.4     .05       0
Bank Sta=4972.6,4983.7
XS Rating Curve= 0 ,0
Exp/Cntr=0.3,0.1

Type RM Length L Ch R = 1 ,10202   ,648,648,648
BEGIN DESCRIPTION:
Mapping XS 39ca68af
END DESCRIPTION:
XS GIS Cut Line= 3
      2688188.58       6905005.2      2687723.29      6904123.24
      2687226.77      6903439.22
#Sta/Elev= 30
  3996.9     452  4334.9  451.03  4439.4  446.55  4615.5  441.31  4741.7  439.38
  4868.5  438.92  4934.6  435.97  4962.7  437.15  4972.9  436.73  4978.6  435.33
  4985.3  432.71    4987     430  4988.5   429.5  4998.1     430    5009  434.54
  5021.5  437.05  5040.6   437.8  5065.4  436.78  5086.3   437.9  5136.5  437.49
  5157.5  436.44  5293.5  438.57  5423.3  439.08  5488.3   440.8  5559.4  443.53
  5588.8  446.55  5609.6  446.72  5745.7  453.24  5810.6  458.55  5839.3  459.26
#Mann= 5 ,-1 , 0
  3996.9     .05       0  4741.7     .12       0    4987     .07       0
  4998.1     .12       0  5040.6     .05       0
Bank Sta=4987,4998.1
XS Rating Curve= 0 ,0
Exp/Cntr=0.3,0.1

Type RM Length L Ch R = 1 ,9554    ,1289,1289,1289
BEGIN DESCRIPTION:
Mapping XS 74b58611
END DESCRIPTION:
XS GIS Cut Line= 3
      2688584.38      6904501.68      2688178.15      6903977.41
      2687393.42      6903300.32
#Sta/Elev= 30
  4324.7  447.67  4380.8  446.99  4515.7  441.74  4594.5  440.38  4616.5  437.61
  4629.8  439.66  4816.3  436.75  4874.5  437.02  4987.9  436.72  4993.7   436.3
  5002.4  429.19  5003.9  428.69  5013.5  429.19  5022.3  430.51  5036.5   436.5
  5057.4  436.21    5065  434.88  5107.8  434.72  5128.7  436.93  5157.2  436.89
    5200   433.3  5217.7  435.95  5228.5  438.27  5255.9  435.29  5730.9  439.45
  5802.2  441.79  5830.7  446.27  5851.6  446.03  5864.3   447.9  6024.4  463.03
#Mann= 6 ,-1 , 0
  4324.7     .05       0  4874.5     .12       0  5002.4     .07       0
  5013.5     .12       0  5217.7     .05       0  5864.3     .12       0
Bank Sta=5002.4,5013.5
XS Rating Curve= 0 ,0
Exp/Cntr=0.3,0.1

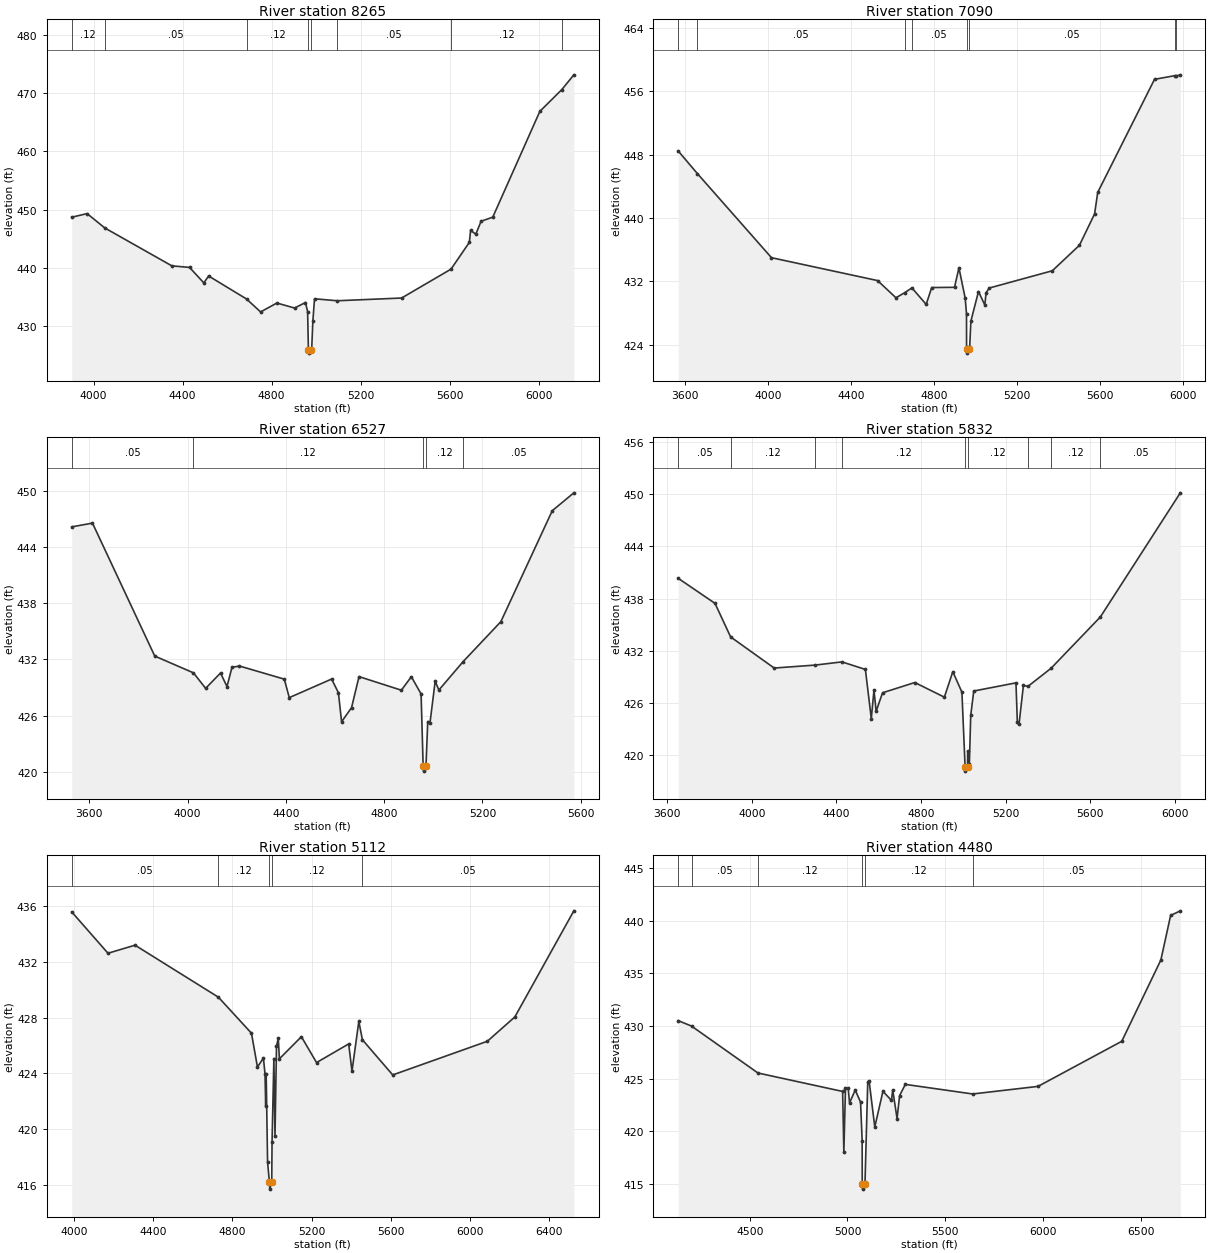
Type RM Length L Ch R = 1 ,8265    ,1175,1175,1175
BEGIN DESCRIPTION:
Mapping XS 2c1e5354
END DESCRIPTION:
XS GIS Cut Line= 3
      2689264.96      6904287.59      2688723.29      6903388.29
      2687615.65      6902912.59
#Sta/Elev= 30
  3902.2   448.7  3971.1  449.32  4050.7  446.85  4351.7  440.34  4431.3  440.07
  4495.4  437.41  4516.9   438.6  4687.4  434.64  4750.4  432.42  4823.5  433.95
  4903.2  433.09    4952  434.04  4961.6  432.48  4965.3  425.84  4966.8  425.34
  4976.5  425.84  4979.7  425.86  4985.2  430.86  4992.6  434.68  5094.6  434.34
  5383.8  434.81  5605.6  439.77  5688.2  444.38  5693.7  446.43  5717.2  445.79
  5740.8     448  5793.3  448.71  6004.8  466.89  6103.4  470.63  6157.5  473.17
#Mann= 8 ,-1 , 0
  3902.2     .12       0  4050.7     .05       0  4687.4     .12       0
  4965.3     .07       0  4976.5     .12       0  5094.6     .05       0
  5605.6     .12       0  6103.4     .05       0
Bank Sta=4965.3,4976.5
XS Rating Curve= 0 ,0
Exp/Cntr=0.3,0.1

Type RM Length L Ch R = 1 ,7090    ,563,563,563
BEGIN DESCRIPTION:
Mapping XS 0dc5c148
END DESCRIPTION:
XS GIS Cut Line= 3
      2689319.64      6904087.12      2689470.69       6902790.2
       2688529.5       6902197.4
#Sta/Elev= 30
  3567.7  448.45  3659.9   445.6  4016.8  434.98  4527.8  432.09  4616.3  429.92
  4658.9  430.57  4693.1  431.17  4761.8  429.08  4788.3  431.21  4898.3  431.24
  4919.5   433.7  4949.8  429.86    4956   427.9  4956.3  423.43  4957.8  422.93
  4967.6  423.43  4971.3   423.7  4977.2  426.98  5013.7  430.71  5044.3     429
  5050.2  430.56  5065.5  431.15  5369.3  433.33  5499.9  436.55  5572.9  440.51
    5588  443.23  5861.4   457.5  5960.1  457.97  5965.3  457.92  5985.7  458.07
#Mann= 8 ,-1 , 0
  3567.7     .12       0  3659.9     .05       0  4658.9     .12       0
  4693.1     .05       0  4956.3     .03       0  4967.6     .05       0
  5960.1     .12       0  5965.3     .05       0
Bank Sta=4956.3,4967.6
XS Rating Curve= 0 ,0
Exp/Cntr=0.3,0.1

Type RM Length L Ch R = 1 ,6527    ,695,695,695
BEGIN DESCRIPTION:
Mapping XS 78077221
END DESCRIPTION:
XS GIS Cut Line= 3
      2689981.11      6903764.17      2689746.73      6902368.32
      2689402.97      6901842.27
#Sta/Elev= 30
  3528.4  446.14  3612.7  446.54  3866.2  432.36  4023.9  430.57  4073.3  428.92
  4133.9  430.55  4160.3  429.11  4180.6  431.16    4211   431.3  4393.5   429.9
  4413.8  427.93  4586.2  429.91  4613.8  428.45  4626.7  425.35  4667.3  426.86
  4697.7  430.17  4870.1  428.72  4910.7  430.16  4950.4  428.32  4958.8  420.59
  4960.4  420.09  4970.2  420.59  4977.5  425.38  4986.6  425.23  5007.7  429.68
  5022.8  428.74  5121.9  431.78  5275.1  436.03  5484.3  447.86  5572.2  449.77
#Mann= 5 ,-1 , 0
  3528.4     .05       0  4023.9     .12       0  4958.8     .07       0
  4970.2     .12       0  5121.9     .05       0
Bank Sta=4958.8,4970.2
XS Rating Curve= 0 ,0
Exp/Cntr=0.3,0.1

Type RM Length L Ch R = 1 ,5832    ,720,720,720
BEGIN DESCRIPTION:
Mapping XS a4afd02c
END DESCRIPTION:
XS GIS Cut Line= 3
      2690489.79      6903672.19      2690265.83      6902401.31
      2689428.61      6901714.89
#Sta/Elev= 30
  3652.1  440.33  3825.9  437.44  3899.7  433.57  4105.6  429.98  4298.9  430.32
  4425.9  430.69  4536.7  429.82  4564.6  424.15  4577.3  427.44  4587.5     425
  4617.9  427.13  4770.3  428.31    4910  426.62  4949.9  429.56  4992.9   427.2
    5008  418.59  5009.6  418.09  5019.4  418.59  5020.2  420.38  5028.1  418.91
  5034.6  424.53  5048.9  427.33  5248.4  428.27  5254.9  423.76  5262.8  423.49
  5283.6  427.97  5305.3  427.87  5414.2  429.95  5647.5  435.88  6025.2  450.19
#Mann= 9 ,-1 , 0
  3652.1     .05       0  3899.7     .12       0  4298.9     .05       0
  4425.9     .12       0    5008     .07       0  5019.4     .12       0
  5305.3     .05       0  5414.2     .12       0  5647.5     .05       0
Bank Sta=5008,5019.4
XS Rating Curve= 0 ,0
Exp/Cntr=0.3,0.1

Type RM Length L Ch R = 1 ,5112    ,632,632,632
BEGIN DESCRIPTION:
Mapping XS 91028699
END DESCRIPTION:
XS GIS Cut Line= 3
      2690736.96      6903462.81      2690841.13      6902488.84
      2690133.44      6901104.68
#Sta/Elev= 30
  3989.3   435.6  4172.1  432.63  4308.6  433.21  4729.4  429.47  4896.3  426.88
  4926.4  424.45  4956.6  425.09  4964.6  423.97  4968.2  421.62  4970.6  423.97
  4977.6   417.6  4986.9  416.17  4988.6  415.67  4998.6  416.17  5000.1  419.03
  5009.4  425.06    5015  419.51  5022.6  425.93  5031.6  426.52  5037.2  425.04
  5148.3  426.63  5224.7  424.77    5387  426.11  5403.6  424.15  5438.1  427.73
  5456.2  426.41  5609.2  423.88  6086.7   426.3  6225.6  428.05  6523.4  435.68
#Mann= 5 ,-1 , 0
  3989.3     .05       0  4729.4     .12       0  4986.9     .07       0
  4998.6     .12       0  5456.2     .05       0
Bank Sta=4986.9,4998.6
XS Rating Curve= 0 ,0
Exp/Cntr=0.3,0.1

Type RM Length L Ch R = 1 ,4480    ,424,424,424
BEGIN DESCRIPTION:
Mapping XS 88834c12
END DESCRIPTION:
XS GIS Cut Line= 3
      2691335.92      6903009.68      2691283.84      6902238.84
       2690205.7      6900801.31
#Sta/Elev= 30
  4133.8  430.51  4202.1  429.99  4541.8  425.54  4975.1  423.79  4981.4  418.06
  4989.7  424.13  5003.7  424.08  5010.5  422.71  5039.7  423.92  5066.8  422.78
  5075.1  419.13  5075.5  415.02  5077.2  414.52  5087.2  415.02  5089.7  415.17
  5103.7  424.69  5110.5   424.8  5139.7  420.42  5181.4   423.8  5225.1  422.94
  5231.4  423.94  5253.7  421.22  5266.8   423.4    5296  424.46  5640.6  423.55
  5975.1  424.27  6403.7  428.55  6603.7  436.26  6653.7  440.49  6703.3  440.93
#Mann= 6 ,-1 , 0
  4133.8     .12       0  4202.1     .05       0  4541.8     .12       0
  5075.5     .07       0  5087.2     .12       0  5640.6     .05       0
Bank Sta=5075.5,5087.2
XS Rating Curve= 0 ,0
Exp/Cntr=0.3,0.1

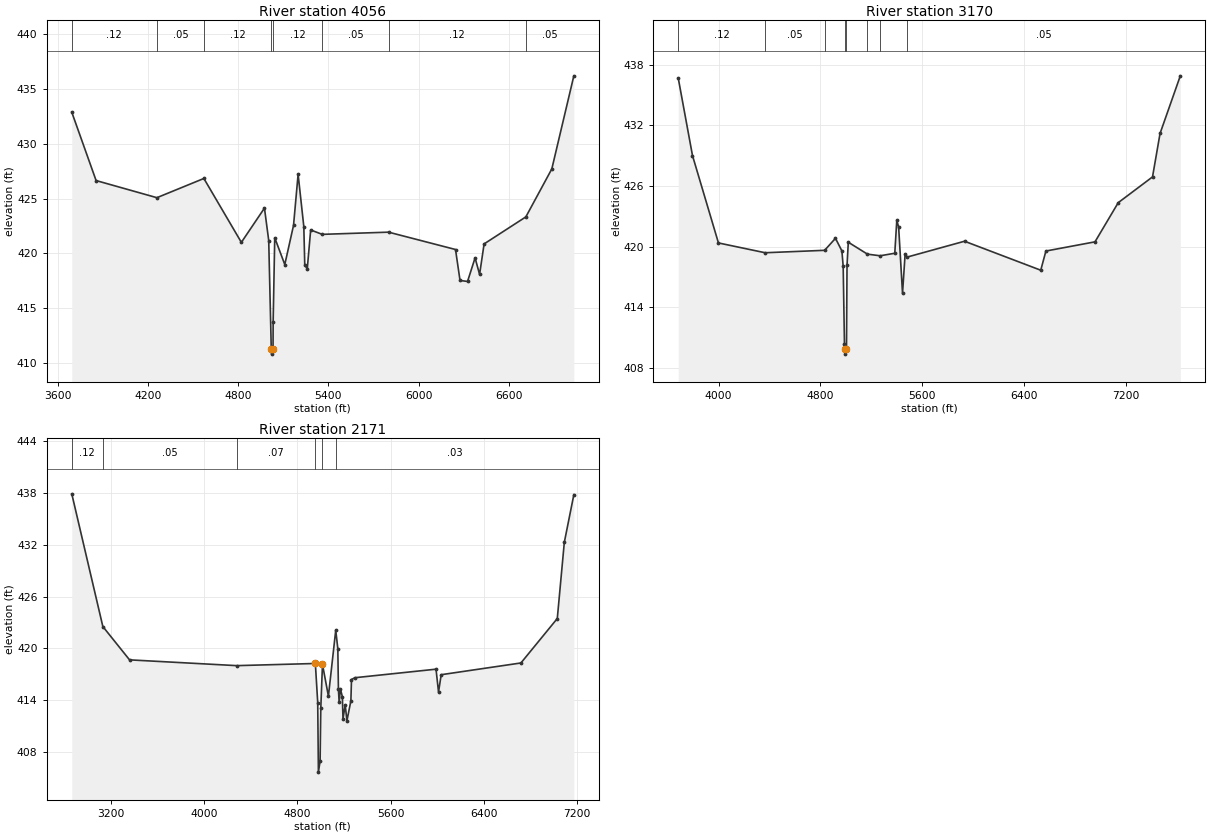
Type RM Length L Ch R = 1 ,4056    ,886,886,886
BEGIN DESCRIPTION:
Mapping XS ef019ae5
END DESCRIPTION:
XS GIS Cut Line= 4
      2691335.91      6903478.46      2691622.38      6902254.46
       2691445.3      6901879.46      2691427.27      6900214.65
#Sta/Elev= 30
  3694.4  432.87  3856.1  426.64  4260.1  425.08  4572.3  426.83  4821.5  421.01
    4975  424.13  5003.3  421.18  5020.2  411.33  5021.8  410.83    5032  411.33
  5032.7  413.73  5043.3  421.43  5110.1  418.99  5168.2  422.56  5198.6  427.21
  5236.5  422.45  5242.8  418.98  5259.3  418.58  5282.1  422.14  5358.8  421.74
  5799.7  421.94  6244.7  420.36  6274.7  417.54  6324.7  417.45  6374.7   419.6
  6404.7  418.09  6434.7  420.87  6712.1  423.33  6884.7   427.7  7031.1  436.18
#Mann= 8 ,-1 , 0
  3694.4     .12       0  4260.1     .05       0  4572.3     .12       0
  5020.2     .07       0    5032     .12       0  5358.8     .05       0
  5799.7     .12       0  6712.1     .05       0
Bank Sta=5020.2,5032
XS Rating Curve= 0 ,0
Exp/Cntr=0.3,0.1

Type RM Length L Ch R = 1 ,3170    ,999,999,999
BEGIN DESCRIPTION:
Mapping XS 9d13d2aa
END DESCRIPTION:
XS GIS Cut Line= 4
      2691565.11      6903723.17      2692138.01      6902728.42
      2692169.26      6902494.04        2691723.      6899970.58
#Sta/Elev= 30
  3683.2  436.69  3795.3  429.01  3999.3  420.36  4366.4  419.39  4834.1  419.63
  4919.3  420.82  4969.8  419.57  4979.9  418.04  4989.9   410.4  4994.1  409.85
  4995.7  409.35  5005.9  409.85  5010.1  418.13  5020.2  420.43  5170.8  419.25
  5270.6  419.09  5385.5  419.34  5401.4   422.6  5415.9  421.94  5446.4  415.37
  5466.7  419.23  5482.6  418.96  5933.9  420.53    6533  417.66  6573.6  419.56
  6959.5  420.47  7142.3  424.35  7411.7   426.9  7470.9   431.2  7630.2  436.91
#Mann= 8 ,-1 , 0
  3683.2     .12       0  4366.4     .05       0  4834.1     .07       0
  4994.1     .05       0  5005.9     .07       0  5170.8     .05       0
  5270.6     .12       0  5482.6     .05       0
Bank Sta=4994.1,5005.9
XS Rating Curve= 0 ,0
Exp/Cntr=0.3,0.1

Type RM Length L Ch R = 1 ,2171    ,0,0,0
BEGIN DESCRIPTION:
Mapping XS cd12c460
END DESCRIPTION:
XS GIS Cut Line= 4
      2691622.39      6903880.35      2692789.05      6902270.09
      2692736.96      6901999.25      2692179.56      6900034.36
#Sta/Elev= 30
  2864.8  437.91  3131.4  422.53  3360.4  418.67  4279.7     418  4954.2  418.25
  4974.5  413.72  4980.4  405.66  4994.9  406.94  5000.9  413.05  5015.3  418.15
  5066.2  414.46  5129.1  422.11  5146.9  419.97  5152.1  415.25  5158.4  413.73
  5168.8  415.32    5186  414.39  5191.2  411.85  5210.4  413.43  5225.1  411.62
    5259  413.92  5264.2  416.39  5292.9   416.6  5989.3  417.59  6010.8  414.94
  6033.6  416.95  6717.6  418.31  7029.5  423.46  7089.8  432.29  7171.5  437.81
#Mann= 6 ,-1 , 0
  2864.8     .12       0  3131.4     .05       0  4279.7     .07       0
  4954.2     .05       0  5015.3     .07       0  5129.1     .03       0
Bank Sta=4954.2,5015.3
XS Rating Curve= 0 ,0
Exp/Cntr=0.3,0.1

Chan Stop Cuts=-1
Use User Specified Reach Order=0
Composite Channel Slope=5