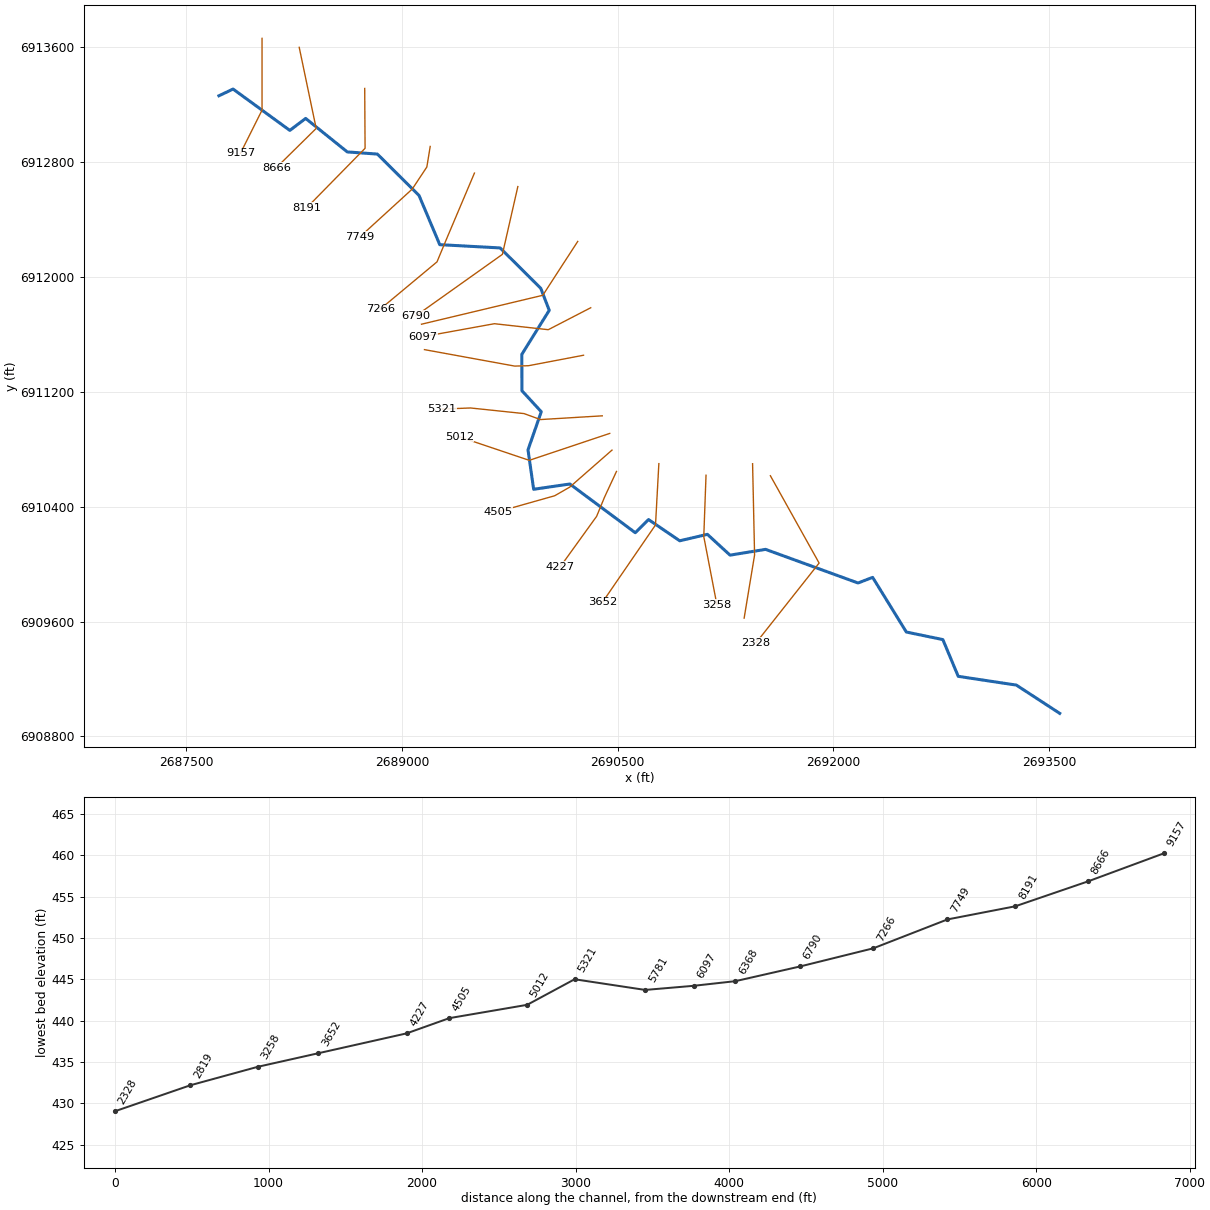
--- Williams T7.prj (project) ---

Proj Title=Williams T7 Base Level Engineering
Current Plan=p01
Default Exp/Contr=0.3,0.1
English Units
Geom File=g01
Flow File=f01
Plan File=p01
BEGIN DESCRIPTION:
Williams T7
END DESCRIPTION:

--- Williams T7.p01 (plan) ---

Plan Title=Multiple Run
Short Identifier=Multiple
Geom File=g01
Flow File=f01
Subcritical Flow
K Sum by GR= 0
Std Step Tol= 0.01
Critical Tol= 0.01
Num of Std Step Trials= 20
Max Error Tol= 0.3
Flow Tol Ratio= 0.001
Split Flow NTrial= 30
Split Flow Tol= 0.02
Split Flow Ratio= 0.02
Log Output Level= 0
Friction Slope Method= 1
Unsteady Friction Slope Method= 2
Unsteady Bridges Friction Slope Method= 1
Parabolic Critical Depth
Global Vel Dist=  1 , 1 , 1
Global Log Level= 0
CheckData=True
Encroach Param= -1, 0, 0, 0
BEGIN DESCRIPTION:
Multiple Run
END DESCRIPTION:

--- Williams T7.f01 (steady flow) ---

Flow Title=Multiple
Number of Profiles=7
Profile Names=10-year,25-year,50-year,1pct_min,100-year,1pct_plu,500-year
River Rch & RM= Williams T7,Reach-1,9157
     532     708     848     505    1008    2011    1420
River Rch & RM= Williams T7,Reach-1,7749
     708     957    1160     697    1391    2776    2001
River Rch & RM= Williams T7,Reach-1,4505
     892    1221    1491     902    1800    3591    2623
Boundary for River Rch & Prof#=Williams T7,Reach-1,1
Up Type=0
Dn Type=3
Dn Slope=0.005
Boundary for River Rch & Prof#=Williams T7,Reach-1,2
Up Type=0
Dn Type=3
Dn Slope=0.005
Boundary for River Rch & Prof#=Williams T7,Reach-1,3
Up Type=0
Dn Type=3
Dn Slope=0.005
Boundary for River Rch & Prof#=Williams T7,Reach-1,4
Up Type=0
Dn Type=3
Dn Slope=0.005
Boundary for River Rch & Prof#=Williams T7,Reach-1,5
Up Type=0
Dn Type=3
Dn Slope=0.005
Boundary for River Rch & Prof#=Williams T7,Reach-1,6
Up Type=0
Dn Type=3
Dn Slope=0.005
Boundary for River Rch & Prof#=Williams T7,Reach-1,7
Up Type=0
Dn Type=3
Dn Slope=0.005

--- Williams T7.g01 (geometry) ---

Geom Title=Existing Conditions

River Reach=Williams T7,Reach-1
Reach XY= 30
      2687726.00      6913261.00      2687824.42      6913307.92
      2688219.34      6913019.99      2688329.33      6913103.36
      2688619.25      6912870.14      2688828.30      6912855.17
      2689118.14      6912567.17      2689262.43      6912224.47
      2689682.67      6912201.71      2689965.24      6911920.68
      2690024.21      6911767.11      2689833.53      6911461.01
      2689834.03      6911207.65      2689968.74      6911061.30
      2689876.52      6910795.78      2689915.84      6910521.28
      2690167.65      6910558.00      2690622.96      6910218.82
      2690714.92      6910310.45      2690932.04      6910162.63
      2691124.50      6910207.54      2691282.05      6910062.66
      2691529.31      6910102.93      2692172.60      6909868.84
      2692274.35      6909907.84      2692508.86      6909527.27
      2692762.80      6909474.74      2692869.81      6909218.85
      2693274.35      6909157.83      2693576.00      6908961.00

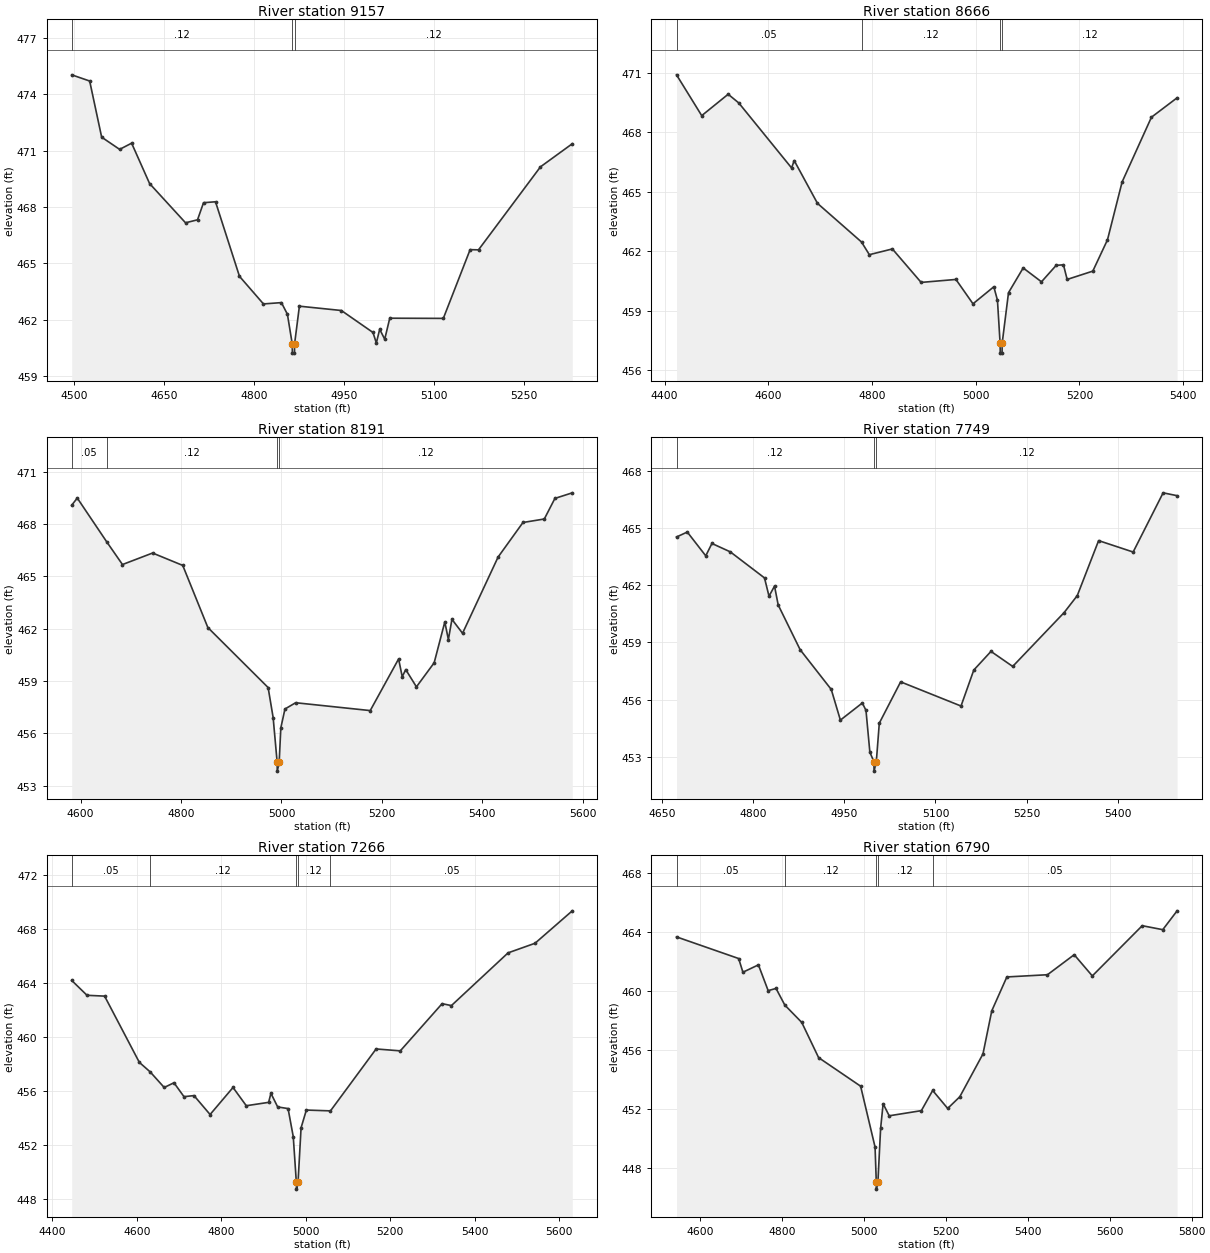
Type RM Length L Ch R = 1,9157,491,491,491
BEGIN DESCRIPTION:
Williams T7 10.0
END DESCRIPTION:
XS GIS Cut Line= 3
      2688026.00      6913661.03      2688026.00      6913161.00
      2687876.02      6912861.04
#Sta/Elev= 30
  4495.4  475.04  4525.4  474.71  4545.4  471.72  4575.4  471.07  4595.4  471.40
  4625.4  469.25  4685.4  467.16  4705.4  467.32  4715.4  468.23  4735.4  468.28
  4775.4  464.31  4815.4  462.84  4845.4  462.91  4855.4  462.29  4863.4  460.72
  4863.7  460.22  4867.2  460.22  4867.4  460.72  4875.4  462.72  4945.4  462.49
  4998.2  461.32  5003.8  460.76  5009.4  461.49  5017.8  460.96  5026.2  462.08
  5115.6  462.07  5160.3  465.73  5174.3  465.72  5277.7  470.14  5330.8  471.37
#Mann=3,-1,0
  4495.4    0.12       0  4863.4    0.07       0  4867.4    0.12       0
Bank Sta=4863.4,4867.4
Exp/Cntr=0.3,0.1

Type RM Length L Ch R = 1,8666,475,475,475
BEGIN DESCRIPTION:
Williams T7 9.0
END DESCRIPTION:
XS GIS Cut Line= 3
      2688284.62      6913598.53      2688402.67      6913033.63
      2688126.02      6912761.02
#Sta/Elev= 30
  4422.9  470.90  4471.5  468.84  4522.5  469.92  4543.0  469.48  4644.8  466.20
  4649.9  466.57  4694.8  464.41  4779.7  462.46  4794.8  461.82  4839.2  462.11
  4894.7  460.42  4961.8  460.57  4994.7  459.34  5034.9  460.20  5041.9  459.52
  5047.0  457.35  5047.3  456.85  5050.8  456.85  5051.0  457.35  5063.2  459.90
  5091.5  461.15  5126.8  460.45  5155.1  461.28  5169.2  461.31  5176.3  460.57
  5225.8  460.99  5254.1  462.57  5282.3  465.49  5338.9  468.76  5388.4  469.74
#Mann=4,-1,0
  4422.9    0.05       0  4779.7    0.12       0  5047.0    0.07       0
  5051.0    0.12       0
Bank Sta=5047,5051
Exp/Cntr=0.3,0.1

Type RM Length L Ch R = 1,8191,442,442,442
BEGIN DESCRIPTION:
Mapping XS 87e4d5bf
END DESCRIPTION:
XS GIS Cut Line= 3
      2688740.34      6913312.07      2688742.94      6912895.45
      2688336.70      6912481.39
#Sta/Elev= 30
  4582.3  469.07  4593.4  469.48  4651.6  466.99  4683.4  465.67  4743.4  466.33
  4803.4  465.62  4853.4  462.06  4973.4  458.62  4983.4  456.90  4991.4  454.33
  4991.6  453.83  4995.4  454.33  4998.7  456.31  5006.9  457.39  5028.2  457.75
  5176.7  457.30  5233.2  460.26  5240.4  459.24  5247.4  459.65  5268.7  458.66
  5304.0  460.04  5325.2  462.38  5332.3  461.37  5339.4  462.53  5360.5  461.73
  5431.3  466.10  5480.8  468.08  5523.3  468.28  5544.4  469.46  5579.0  469.78
#Mann=4,-1,0
  4582.3    0.05       0  4651.6    0.12       0  4991.4    0.07       0
  4995.4    0.12       0
Bank Sta=4991.4,4995.4
Exp/Cntr=0.3,0.1

Type RM Length L Ch R = 1,7749,483,483,483
BEGIN DESCRIPTION:
Mapping XS d37e6426
END DESCRIPTION:
XS GIS Cut Line= 4
      2689196.06      6912908.42      2689172.63      6912765.24
      2689071.07      6912611.59      2688706.46      6912278.23
#Sta/Elev= 30
  4674.1  464.54  4691.8  464.80  4722.2  463.55  4732.3  464.20  4762.5  463.76
  4818.8  462.39  4826.2  461.43  4835.3  461.96  4841.3  460.97  4877.4  458.62
  4928.6  456.53  4943.6  454.92  4979.7  455.82  4985.7  455.43  4992.1  453.23
  4998.7  452.74  4999.0  452.24  5002.7  452.74  5007.6  454.76  5042.7  456.93
  5142.0  455.66  5163.0  457.55  5191.3  458.53  5227.0  457.74  5311.6  460.57
  5333.2  461.46  5368.3  464.35  5425.1  463.75  5474.4  466.86  5497.4  466.71
#Mann=3,-1,0
  4674.1    0.12       0  4998.7    0.07       0  5002.7    0.12       0
Bank Sta=4998.7,5002.7
Exp/Cntr=0.3,0.1

Type RM Length L Ch R = 1,7266,476,476,476
BEGIN DESCRIPTION:
Mapping XS 6e457702
END DESCRIPTION:
XS GIS Cut Line= 4
      2689503.72      6912722.74      2689312.73      6912271.31
      2689243.29      6912104.65      2688848.21      6911775.41
#Sta/Elev= 30
  4445.8  464.19  4482.1  463.09  4523.7  463.03  4605.9  458.13  4631.7  457.42
  4664.8  456.27  4687.9  456.62  4711.6  455.59  4735.3  455.67  4773.4  454.27
  4827.7  456.27  4859.1  454.92  4912.0  455.17  4917.4  455.84  4933.4  454.83
  4958.0  454.71  4970.3  452.63  4977.6  449.25  4977.9  448.75  4981.6  449.25
  4988.8  453.29  5001.3  454.60  5058.4  454.54  5166.4  459.12  5223.7  458.98
  5322.6  462.47  5344.7  462.33  5478.8  466.23  5542.6  466.94  5630.8  469.34
#Mann=5,-1,0
  4445.8    0.05       0  4631.7    0.12       0  4977.6    0.07       0
  4981.6    0.12       0  5058.4    0.05       0
Bank Sta=4977.6,4981.6
Exp/Cntr=0.3,0.1

Type RM Length L Ch R = 1,6790,422,422,422
BEGIN DESCRIPTION:
Mapping XS 22671db1
END DESCRIPTION:
XS GIS Cut Line= 3
      2689805.80      6912628.99      2689698.15      6912156.73
      2689097.47      6911729.65
#Sta/Elev= 30
  4543.2  463.69  4694.8  462.22  4705.2  461.29  4743.0  461.79  4766.8  460.04
  4786.0  460.19  4807.4  459.06  4848.8  457.88  4889.9  455.49  4992.4  453.55
  5027.6  449.42  5030.6  447.06  5030.8  446.56  5034.6  447.06  5041.2  450.69
  5047.3  452.36  5062.1  451.54  5140.6  451.89  5168.2  453.26  5204.8  452.04
  5234.3  452.83  5290.9  455.74  5312.4  458.67  5349.2  460.97  5448.3  461.12
  5513.5  462.48  5557.7  461.04  5679.5  464.45  5729.6  464.18  5764.6  465.46
#Mann=5,-1,0
  4543.2    0.05       0  4807.4    0.12       0  5030.6    0.07       0
  5034.6    0.12       0  5168.2    0.05       0
Bank Sta=5030.6,5034.6
Exp/Cntr=0.3,0.1

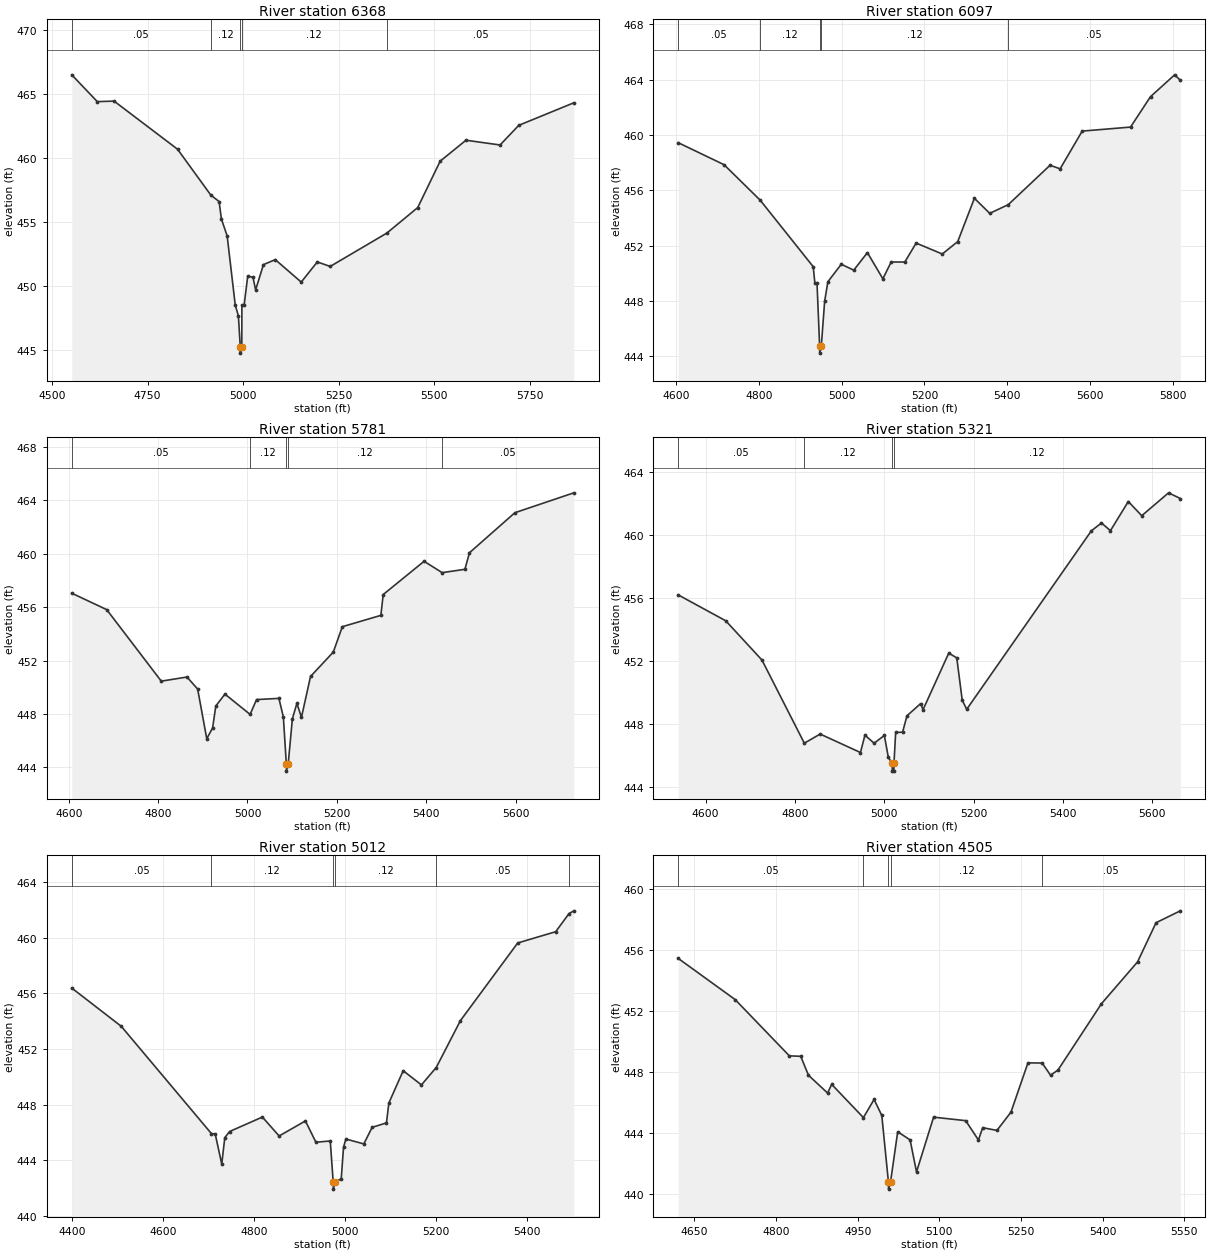
Type RM Length L Ch R = 1,6368,271,271,271
BEGIN DESCRIPTION:
Mapping XS 10c2b79a
END DESCRIPTION:
XS GIS Cut Line= 3
      2690222.47      6912247.04      2689979.40      6911872.01
      2689135.61      6911670.61
#Sta/Elev= 30
  4551.4  466.48  4618.2  464.39  4662.2  464.43  4828.3  460.68  4915.5  457.10
  4937.1  456.60  4943.1  455.24  4958.2  453.92  4979.3  448.54  4987.6  447.68
  4992.5  445.28  4992.7  444.78  4996.5  445.28  4996.8  448.51  5002.6  448.51
  5012.1  450.80  5025.9  450.68  5032.7  449.71  5053.2  451.68  5084.1  452.07
  5152.1  450.32  5194.2  451.89  5228.0  451.54  5376.3  454.14  5457.1  456.13
  5515.9  459.75  5583.4  461.38  5672.7  461.01  5721.5  462.54  5865.8  464.30
#Mann=5,-1,0
  4551.4    0.05       0  4915.5    0.12       0  4992.5    0.07       0
  4996.5    0.12       0  5376.3    0.05       0
Bank Sta=4992.5,4996.5
Exp/Cntr=0.3,0.1

Type RM Length L Ch R = 1,6097,316,316,316
BEGIN DESCRIPTION:
Mapping XS 8ab552a4
END DESCRIPTION:
XS GIS Cut Line= 4
      2690312.72      6911785.20      2690017.59      6911632.42
      2689642.59      6911674.09      2689146.07      6911583.81
#Sta/Elev= 30
  4604.4  459.44  4715.2  457.85  4802.7  455.28  4930.9  450.47  4934.8  449.30
  4940.0  449.30  4946.4  444.72  4946.6  444.22  4950.4  444.72  4958.5  447.97
  4966.3  449.38  4998.7  450.65  5028.9  450.22  5061.9  451.49  5099.3  449.60
  5119.4  450.81  5152.4  450.81  5179.8  452.18  5243.0  451.39  5280.4  452.29
  5320.7  455.42  5357.8  454.33  5402.6  454.96  5503.7  457.81  5528.0  457.55
  5581.4  460.28  5698.3  460.57  5746.6  462.77  5805.0  464.35  5818.7  463.96
#Mann=5,-1,0
  4604.4    0.05       0  4802.7    0.12       0  4946.4    0.07       0
  4950.4    0.12       0  5402.6    0.05       0
Bank Sta=4946.4,4950.4
Exp/Cntr=0.3,0.1

Type RM Length L Ch R = 1,5781,460,460,460
BEGIN DESCRIPTION:
Mapping XS 15709069
END DESCRIPTION:
XS GIS Cut Line= 4
      2690262.82      6911454.55      2689880.03      6911381.64
      2689783.67      6911379.04      2689156.11      6911493.62
#Sta/Elev= 30
  4606.6  457.05  4684.8  455.82  4807.0  450.46  4864.5  450.77  4888.4  449.87
  4908.8  446.15  4921.8  446.95  4929.1  448.60  4949.5  449.49  5005.8  447.97
  5020.3  449.08  5070.3  449.17  5080.3  447.78  5087.0  444.22  5087.2  443.72
  5091.0  444.22  5100.5  447.64  5110.6  448.80  5120.8  447.75  5141.1  450.81
  5192.1  452.64  5212.3  454.54  5298.6  455.39  5303.8  456.95  5395.3  459.44
  5435.8  458.59  5486.7  458.84  5496.9  460.08  5598.6  463.08  5730.6  464.57
#Mann=5,-1,0
  4606.6    0.05       0  5005.8    0.12       0  5087.0    0.03       0
  5091.0    0.12       0  5435.8    0.05       0
Bank Sta=5087,5091
Exp/Cntr=0.3,0.1

Type RM Length L Ch R = 1,5321,309,309,309
BEGIN DESCRIPTION:
Mapping XS f0cbd057
END DESCRIPTION:
XS GIS Cut Line= 5
      2690393.01      6911032.68      2689963.36      6911006.64
      2689848.78      6911048.31      2689476.38      6911087.37
      2689279.74      6911079.61
#Sta/Elev= 30
  4538.8  456.18  4645.1  454.54  4726.2  452.05  4821.0  446.78  4856.4  447.36
  4946.6  446.19  4956.6  447.29  4977.1  446.78  5000.1  447.27  5009.0  445.88
  5017.6  445.51  5017.9  445.01  5021.4  445.01  5021.6  445.51  5025.4  447.46
  5040.9  447.48  5050.7  448.52  5081.3  449.29  5086.6  448.90  5144.2  452.49
  5162.1  452.19  5174.4  449.50  5184.4  448.93  5463.3  460.24  5486.0  460.74
  5506.0  460.25  5546.0  462.10  5576.1  461.20  5636.1  462.65  5662.4  462.29
#Mann=4,-1,0
  4538.8    0.05       0  4821.0    0.12       0  5017.6    0.07       0
  5021.6    0.12       0
Bank Sta=5017.6,5021.6
Exp/Cntr=0.3,0.1

Type RM Length L Ch R = 1,5012,507,507,507
BEGIN DESCRIPTION:
Mapping XS 0e7f739c
END DESCRIPTION:
XS GIS Cut Line= 3
      2690445.16      6910910.30      2689885.24      6910722.79
      2689398.22      6910886.86
#Sta/Elev= 30
  4399.6  456.37  4508.5  453.62  4706.8  445.91  4715.1  445.89  4729.5  443.72
  4736.2  445.62  4746.7  446.06  4818.9  447.10  4855.7  445.74  4913.6  446.82
  4936.6  445.29  4968.2  445.38  4974.7  442.42  4975.0  441.92  4978.7  442.42
  4992.3  442.66  4997.4  444.93  5002.6  445.52  5042.0  445.17  5060.3  446.36
  5091.8  446.68  5097.1  448.11  5128.6  450.43  5168.7  449.41  5201.3  450.66
  5254.5  454.03  5380.5  459.61  5464.1  460.42  5493.3  461.72  5504.0  461.92
#Mann=6,-1,0
  4399.6    0.05       0  4706.8    0.12       0  4974.7    0.07       0
  4978.7    0.12       0  5201.3    0.05       0  5493.3    0.12       0
Bank Sta=4974.7,4978.7
Exp/Cntr=0.3,0.1

Type RM Length L Ch R = 1,4505,278,278,278
BEGIN DESCRIPTION:
Mapping XS 7524196d
END DESCRIPTION:
XS GIS Cut Line= 4
      2690460.75      6910793.96      2690166.49      6910536.16
      2690062.32      6910476.26      2689666.53      6910364.29
#Sta/Elev= 30
  4620.3  455.44  4724.9  452.74  4824.5  449.05  4845.4  449.02  4859.6  447.78
  4894.8  446.61  4902.3  447.18  4960.6  445.00  4980.2  446.19  4994.4  445.14
  5006.5  440.81  5006.8  440.31  5010.6  440.81  5023.6  444.07  5046.4  443.54
  5058.2  441.44  5089.6  445.03  5148.6  444.80  5172.0  443.53  5179.8  444.34
  5206.0  444.16  5231.8  445.36  5263.0  448.59  5289.1  448.58  5304.5  447.78
  5318.2  448.12  5398.1  452.47  5464.4  455.21  5498.4  457.78  5543.0  458.56
#Mann=5,-1,0
  4620.3    0.05       0  4960.6    0.12       0  5006.5    0.07       0
  5010.6    0.12       0  5289.1    0.05       0
Bank Sta=5006.5,5010.6
Exp/Cntr=0.3,0.1

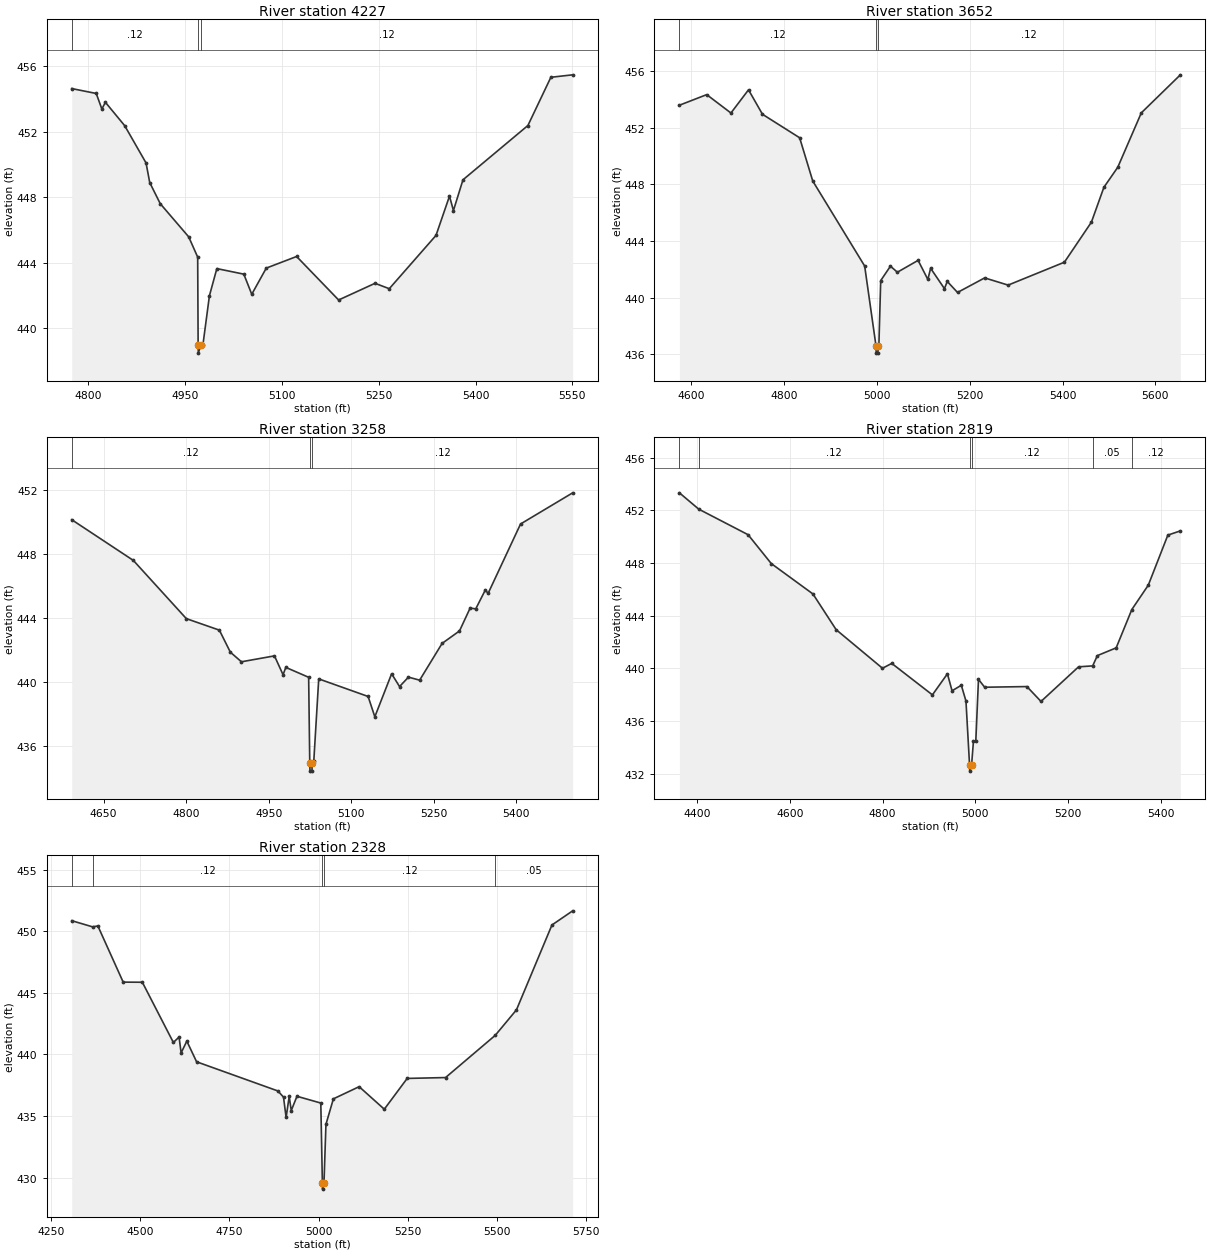
Type RM Length L Ch R = 1,4227,575,575,575
BEGIN DESCRIPTION:
Mapping XS 239e54b1
END DESCRIPTION:
XS GIS Cut Line= 4
      2690491.99      6910645.49      2690408.67      6910465.84
      2690353.99      6910333.03      2690099.89      6909980.40
#Sta/Elev= 30
  4774.2  454.65  4812.2  454.35  4820.9  453.40  4826.4  453.81  4856.3  452.38
  4889.4  450.10  4895.1  448.90  4911.4  447.61  4955.5  445.58  4969.4  444.34
  4970.1  438.97  4970.4  438.47  4974.2  438.97  4977.5  438.97  4987.6  441.98
  4999.1  443.64  5040.9  443.30  5053.2  442.07  5075.7  443.67  5122.7  444.38
  5187.8  441.72  5244.2  442.74  5266.3  442.41  5338.7  445.67  5359.6  448.07
  5365.7  447.19  5380.5  449.07  5481.1  452.39  5516.7  455.34  5550.5  455.49
#Mann=3,-1,0
  4774.2    0.12       0  4970.1    0.07       0  4974.2    0.12       0
Bank Sta=4970.1,4974.2
Exp/Cntr=0.3,0.1

Type RM Length L Ch R = 1,3652,394,394,394
BEGIN DESCRIPTION:
Mapping XS 3db889ae
END DESCRIPTION:
XS GIS Cut Line= 3
      2690786.93      6910699.82      2690763.49      6910272.70
      2690394.53      6909734.85
#Sta/Elev= 30
  4574.1  453.60  4633.0  454.35  4685.2  453.05  4723.1  454.69  4753.2  452.96
  4833.3  451.30  4861.6  448.24  4973.5  442.23  4998.0  436.57  4998.4  436.07
  5002.0  436.07  5002.4  436.57  5004.1  436.57  5008.1  441.20  5029.1  442.22
  5044.0  441.79  5088.7  442.63  5109.7  441.28  5115.7  442.07  5145.5  440.63
  5151.6  441.14  5173.7  440.36  5232.2  441.39  5282.8  440.88  5404.1  442.50
  5462.3  445.33  5489.3  447.80  5519.1  449.21  5569.9  453.06  5654.1  455.75
#Mann=3,-1,0
  4574.1    0.12       0  4998.0    0.07       0  5002.4    0.12       0
Bank Sta=4998,5002.4
Exp/Cntr=0.3,0.1

Type RM Length L Ch R = 1,3258,439,439,439
BEGIN DESCRIPTION:
Mapping XS b3549b81
END DESCRIPTION:
XS GIS Cut Line= 3
      2691115.05      6910619.05      2691099.43      6910191.97
      2691190.57      6909718.02
#Sta/Elev= 30
  4592.2  450.16  4704.2  447.61  4800.4  443.97  4860.4  443.25  4880.4  441.87
  4900.5  441.27  4960.5  441.64  4976.1  440.46  4981.1  440.92  5022.6  440.30
  5024.6  434.93  5025.0  434.43  5028.6  434.43  5029.0  434.93  5031.9  435.04
  5040.9  440.20  5130.6  439.10  5142.8  437.83  5173.3  440.52  5187.7  439.72
  5203.9  440.31  5224.2  440.12  5265.0  442.42  5296.6  443.20  5315.9  444.63
  5326.1  444.58  5343.5  445.76  5348.6  445.55  5407.5  449.89  5502.2  451.84
#Mann=3,-1,0
  4592.2    0.12       0  5024.6    0.07       0  5029.0    0.12       0
Bank Sta=5024.6,5029
Exp/Cntr=0.3,0.1

Type RM Length L Ch R = 1,2819,491,491,491
BEGIN DESCRIPTION:
Mapping XS f9c32d8f
END DESCRIPTION:
XS GIS Cut Line= 3
      2691439.01      6910699.12      2691452.90      6910063.67
      2691380.26      6909624.34
#Sta/Elev= 30
  4361.5  453.33  4403.3  452.09  4509.7  450.15  4559.7  447.96  4649.7  445.65
  4699.7  442.94  4799.7  440.01  4819.7  440.38  4907.4  437.99  4939.8  439.59
  4949.8  438.30  4969.8  438.72  4979.8  437.52  4987.5  432.70  4988.0  432.20
  4992.0  432.70  4995.9  434.45  5001.0  434.45  5006.8  439.17  5020.1  438.57
  5111.3  438.62  5141.7  437.49  5222.8  440.12  5253.2  440.19  5263.3  440.97
  5303.9  441.56  5337.7  444.47  5373.2  446.32  5415.4  450.12  5442.4  450.44
#Mann=6,-1,0
  4361.5    0.05       0  4403.3    0.12       0  4987.5    0.07       0
  4992.0    0.12       0  5253.2    0.05       0  5337.7    0.12       0
Bank Sta=4987.5,4992
Exp/Cntr=0.3,0.1

Type RM Length L Ch R = 1,2328,0,0,0
BEGIN DESCRIPTION:
Mapping XS 46faad4b
END DESCRIPTION:
XS GIS Cut Line= 3
      2691562.84      6910615.65      2691901.86      6910007.58
      2691463.29      6909452.53
#Sta/Elev= 30
  4308.0  450.86  4366.3  450.36  4381.3  450.43  4452.2  445.87  4505.9  445.86
  4592.8  440.97  4608.8  441.41  4614.5  440.12  4630.5  441.08  4657.9  439.40
  4885.8  437.03  4901.4  436.53  4908.7  434.88  4917.3  436.59  4923.1  435.44
  4939.1  436.60  5005.9  436.05  5010.3  429.56  5010.8  429.06  5014.8  429.56
  5020.3  434.32  5041.1  436.39  5113.3  437.38  5183.8  435.55  5247.9  438.05
  5355.4  438.12  5494.7  441.55  5554.1  443.62  5653.5  450.51  5711.6  451.66
#Mann=5,-1,0
  4308.0    0.05       0  4366.3    0.12       0  5010.3    0.07       0
  5014.8    0.12       0  5494.7    0.05       0
Bank Sta=5010.3,5014.8
Exp/Cntr=0.3,0.1

Chan Stop Cuts=-1