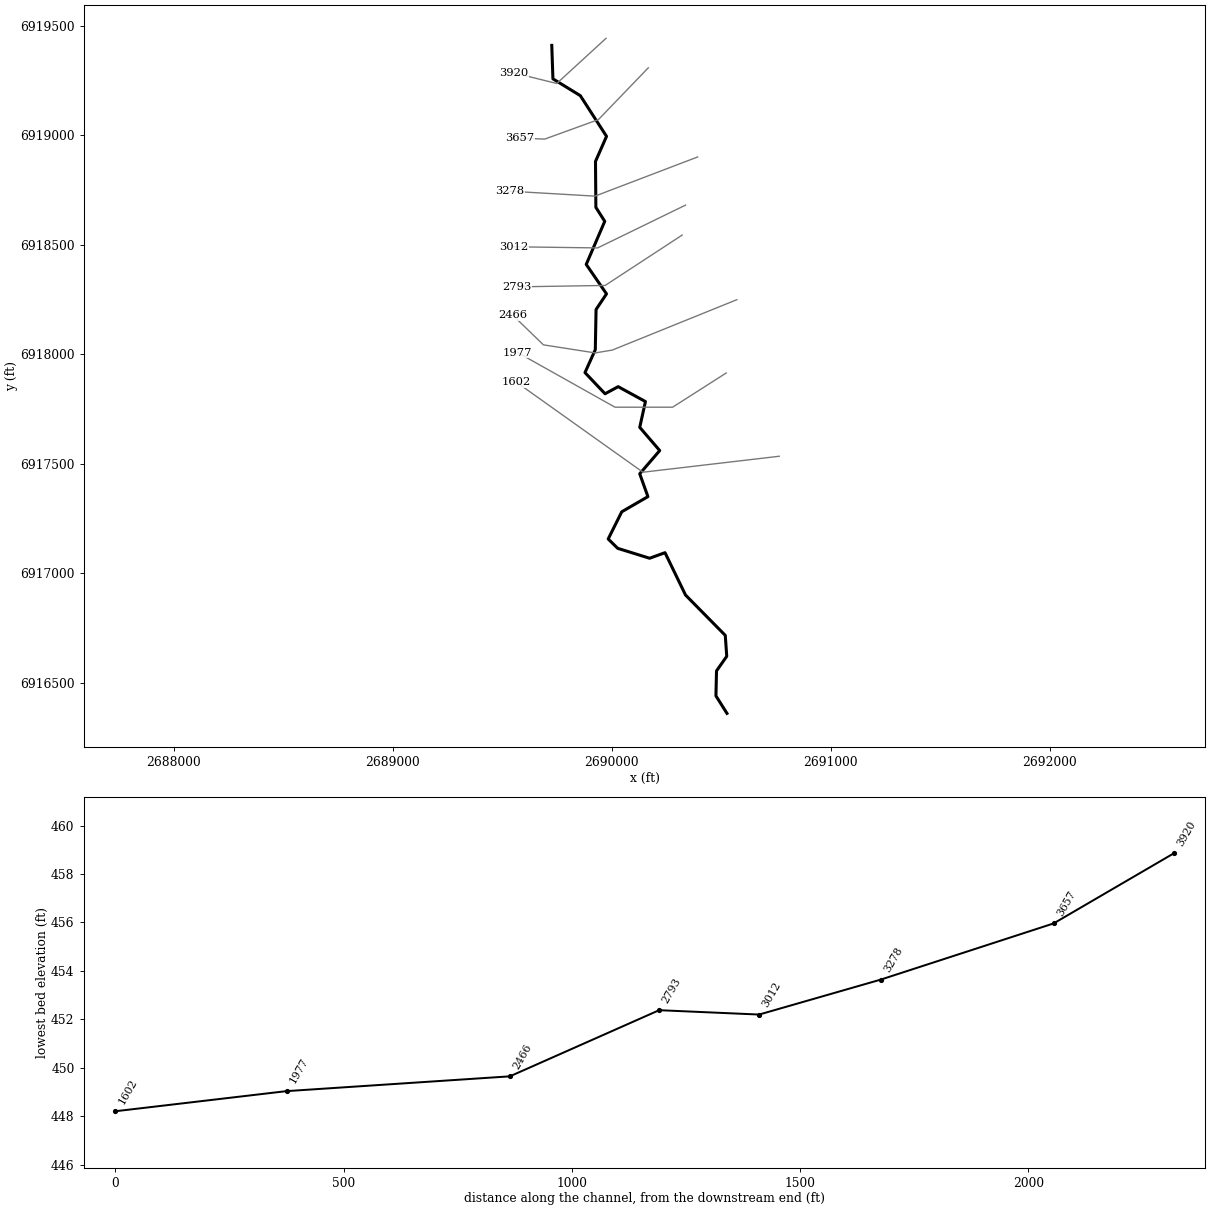
--- Williams T8.prj (project) ---

Proj Title=Williams T8 Base Level Engineering
Current Plan=p01
Default Exp/Contr=0.3,0.1
English Units
Geom File=g01
Flow File=f01
Plan File=p01
Y Axis Title=Elevation
X Axis Title(PF)=Main Channel Distance
X Axis Title(XS)=Station
BEGIN DESCRIPTION:
Williams T8
END DESCRIPTION:
DSS Export Rating Curves= 0
DSS Export Rating Curve Sorted= 0
DSS Export Volume Flow Curves= 0
DXF OffsetX= 0
DXF OffsetY= 0
DXF ScaleX= 1
DXF ScaleY= 10

--- Williams T8.p01 (plan) ---

Plan Title=Multiple Run
Short Identifier=Multiple
Geom File=g01
Flow File=f01
Subcritical Flow
K Sum by GR= 0
Std Step Tol= 0.01
Critical Tol= 0.01
Num of Std Step Trials= 20
Max Error Tol= 0.3
Flow Tol Ratio= 0.001
Split Flow NTrial= 30
Split Flow Tol= 0.02
Split Flow Ratio= 0.02
Log Output Level= 0
Friction Slope Method= 1
Unsteady Friction Slope Method= 2
Unsteady Bridges Friction Slope Method= 1
Parabolic Critical Depth
Global Vel Dist=  1 , 1 , 1
Global Log Level= 0
CheckData=True
Encroach Param= -1, 0, 0, 0
BEGIN DESCRIPTION:
Multiple Run
END DESCRIPTION:

--- Williams T8.f01 (steady flow) ---

Flow Title=Multiple
Program Version=4.10
Number of Profiles= 7
Profile Names=10-year,25-year,50-year,1pct_min,100-year,1pct_plu,500-year
River Rch & RM=Williams T8,Reach-1         ,3920
     647     875    1060     638    1274    2542    1836
Boundary for River Rch & Prof#=Williams T8,Reach-1         , 1
Up Type= 0
Dn Type= 3
Dn Slope=0.00173
Boundary for River Rch & Prof#=Williams T8,Reach-1         , 2
Up Type= 0
Dn Type= 3
Dn Slope=0.00173
Boundary for River Rch & Prof#=Williams T8,Reach-1         , 3
Up Type= 0
Dn Type= 3
Dn Slope=0.00173
Boundary for River Rch & Prof#=Williams T8,Reach-1         , 4
Up Type= 0
Dn Type= 3
Dn Slope=0.00173
Boundary for River Rch & Prof#=Williams T8,Reach-1         , 5
Up Type= 0
Dn Type= 3
Dn Slope=0.00173
Boundary for River Rch & Prof#=Williams T8,Reach-1         , 6
Up Type= 0
Dn Type= 3
Dn Slope=0.00173
Boundary for River Rch & Prof#=Williams T8,Reach-1         , 7
Up Type= 0
Dn Type= 3
Dn Slope=0.00173
DSS Import GetInterval= 0
DSS Import GetPeak= 0
DSS Import FillOption= 0

--- Williams T8.g01 (geometry) ---

Geom Title=Existing Conditions
Program Version=4.10

River Reach=Williams T8     ,Reach-1
Reach XY= 30
        2689726.        6919411.      2689731.33      6919258.28
      2689856.36      6919181.47      2689976.04      6918995.66
      2689925.65      6918881.15      2689927.38      6918671.44
      2689967.92       6918607.7      2689883.33       6918410.9
      2689975.96      6918276.42      2689928.29      6918205.07
      2689924.76       6918021.5      2689877.62      6917917.01
      2689969.31      6917820.29      2690029.23      6917852.75
       2690153.7      6917784.74      2690127.68      6917667.05
       2690218.9        6917561.      2690127.68      6917454.95
      2690165.02      6917350.63      2690045.62      6917281.47
      2689983.65      6917157.31      2690027.02       6917114.6
      2690172.79      6917069.29      2690243.05      6917094.77
      2690336.76      6916901.32      2690518.24      6916717.17
       2690524.9      6916621.55      2690478.25      6916555.06
       2690475.6      6916440.87        2690526.        6916361.

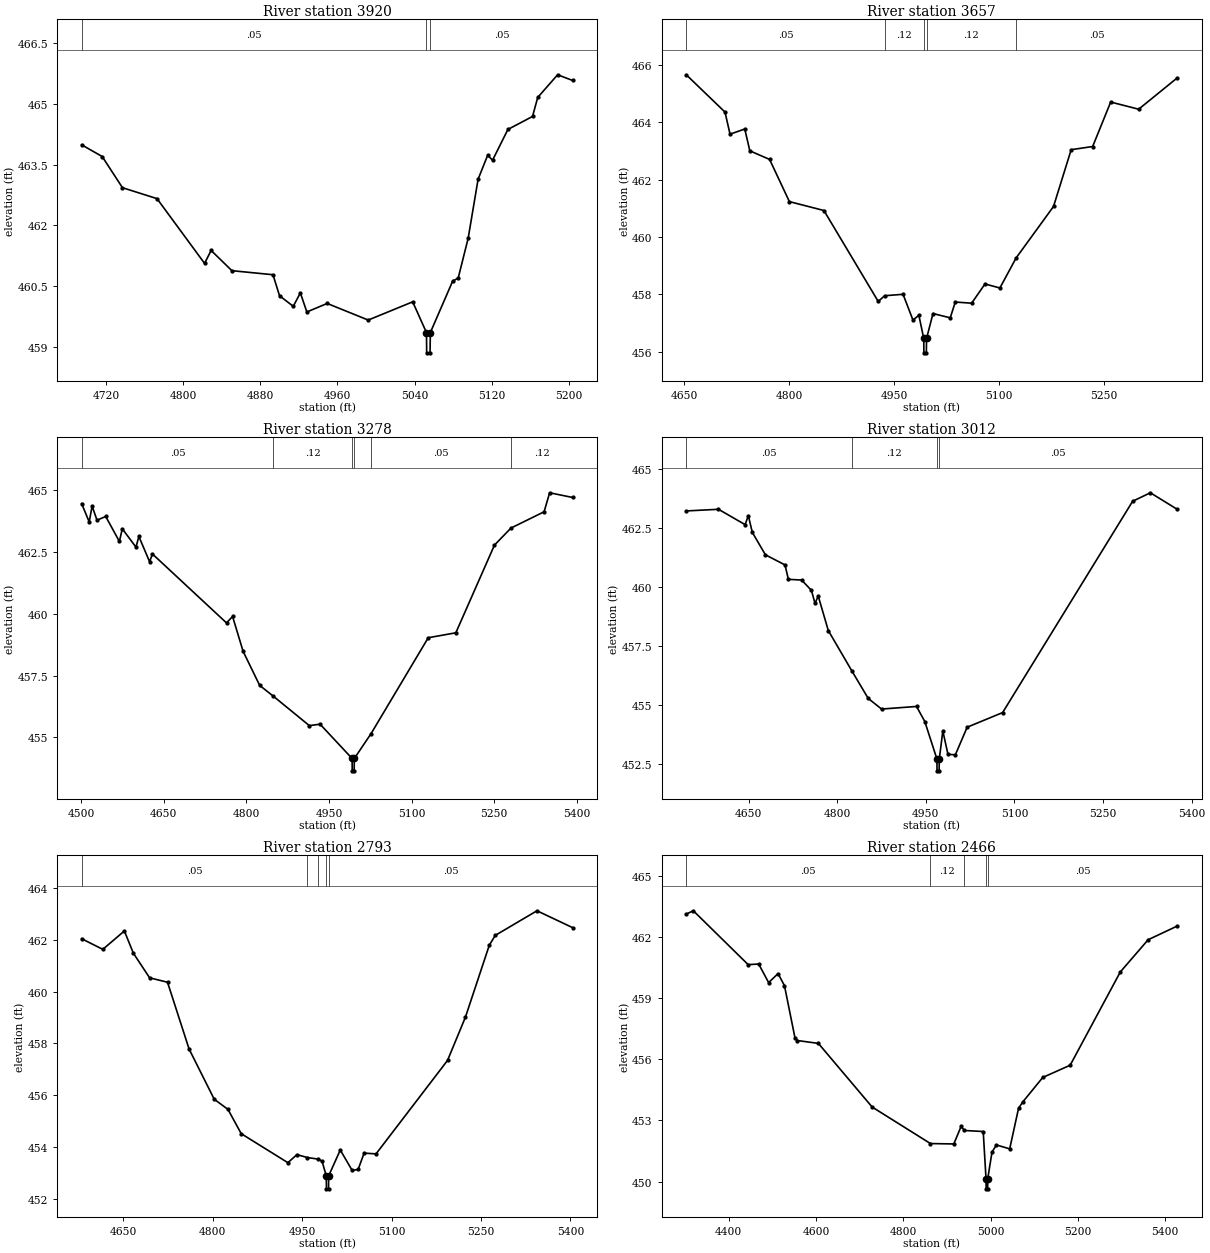
Type RM Length L Ch R = 1 ,3920    ,263,263,263
BEGIN DESCRIPTION:
Williams T8 5.0
END DESCRIPTION:
XS GIS Cut Line= 3
      2689973.66      6919443.21      2689748.71       6919237.1
      2689550.97      6919286.01
#Sta/Elev= 30
  4694.9  463.99  4716.2   463.7  4737.2  462.93    4773  462.66  4822.3  461.06
  4829.1  461.38  4850.6  460.88  4893.2  460.78    4900  460.26  4914.2     460
  4921.6  460.33  4928.3  459.86  4949.4  460.07  4991.9  459.66    5038  460.11
  5052.3  459.35  5052.5  458.85    5056  458.85  5056.3  459.35  5079.4  460.62
  5085.2   460.7  5095.5  461.68  5105.8  463.14  5115.7  463.73  5120.8  463.61
  5136.7  464.37  5162.2  464.69  5167.6  465.16  5188.2  465.72  5203.7  465.58
#Mann= 3 ,-1 , 0
  4694.9     .05       0  5052.3     .03       0  5056.3     .05       0
Bank Sta=5052.3,5056.3
XS Rating Curve= 0 ,0
Exp/Cntr=0.3,0.1

Type RM Length L Ch R = 1 ,3657    ,379,379,379
BEGIN DESCRIPTION:
Mapping XS a183958d
END DESCRIPTION:
XS GIS Cut Line= 4
      2690166.82      6919308.68      2689938.93      6919072.11
      2689693.71      6918983.14      2689580.93      6918987.47
#Sta/Elev= 30
  4652.7  465.65  4708.1  464.35  4715.3  463.58  4736.4  463.76  4743.6     463
  4771.9   462.7  4800.2  461.23  4849.6  460.92  4927.3  457.75  4936.4  457.95
  4962.8     458    4977   457.1  4985.4  457.27  4992.4  456.46  4992.6  455.96
  4996.1  455.96  4996.4  456.46  5005.6  457.33  5030.3  457.18  5037.5  457.73
  5060.9  457.69    5080  458.36  5101.3  458.22  5124.6  459.27    5178  461.06
  5203.3  463.04    5234  463.15  5259.8   464.7  5299.8  464.45  5354.9  465.54
#Mann= 5 ,-1 , 0
  4652.7     .05       0  4936.4     .12       0  4992.4     .07       0
  4996.4     .12       0  5124.6     .05       0
Bank Sta=4992.4,4996.4
XS Rating Curve= 0 ,0
Exp/Cntr=0.3,0.1

Type RM Length L Ch R = 1 ,3278    ,266,266,266
BEGIN DESCRIPTION:
Mapping XS 40a4d29d
END DESCRIPTION:
XS GIS Cut Line= 3
      2690392.03      6918901.53      2689923.31      6918722.72
      2689534.44      6918745.29
#Sta/Elev= 30
  4500.9  464.46  4514.6  463.72  4519.9  464.36  4528.8  463.79  4544.6  463.94
  4569.4  462.93  4574.7  463.44  4599.5   462.7  4604.8  463.13  4624.2  462.11
  4629.5  462.42  4763.9  459.63  4774.9  459.89    4794  458.48  4824.1   457.1
    4849  456.66  4914.3  455.47  4933.7  455.53  4991.9  454.14  4992.1  453.64
  4995.6  453.64  4995.9  454.14  5026.4  455.15  5130.1  459.03  5180.2  459.23
  5250.3  462.78  5280.2  463.47  5340.4  464.13  5350.5   464.9  5392.1  464.71
#Mann= 6 ,-1 , 0
  4500.9     .05       0    4849     .12       0  4991.9     .07       0
  4995.9     .12       0  5026.4     .05       0  5280.2     .12       0
Bank Sta=4991.9,4995.9
XS Rating Curve= 0 ,0
Exp/Cntr=0.3,0.1

Type RM Length L Ch R = 1 ,3012    ,219,219,219
BEGIN DESCRIPTION:
Mapping XS c7c9b805
END DESCRIPTION:
XS GIS Cut Line= 3
      2690336.49      6918681.57      2689935.46      6918486.26
      2689550.56      6918491.46
#Sta/Elev= 30
  4544.4  463.22  4598.9  463.29    4644  462.64  4649.5  463.02  4656.2  462.31
  4678.4  461.36  4711.6  460.93  4717.2  460.32  4739.7  460.29  4756.3  459.85
  4762.3   459.3  4767.8  459.61  4784.8  458.15  4824.4  456.45  4852.4  455.27
    4875  454.82  4934.2  454.93  4948.2  454.29  4968.7   452.7  4968.9   452.2
  4972.4   452.2  4972.7   452.7  4978.7  453.89  4987.4   452.9  4999.9  452.88
  5019.9  454.05  5079.9  454.67    5300  463.63    5330  463.99  5375.4  463.29
#Mann= 4 ,-1 , 0
  4544.4     .05       0  4824.4     .12       0  4968.7     .05       0
  4972.7     .05       0
Bank Sta=4968.7,4972.7
XS Rating Curve= 0 ,0
Exp/Cntr=0.3,0.1

Type RM Length L Ch R = 1 ,2793    ,327,327,327
BEGIN DESCRIPTION:
Mapping XS a6b9734a
END DESCRIPTION:
XS GIS Cut Line= 3
      2690321.45      6918544.99      2689969.89      6918314.96
      2689566.27      6918308.45
#Sta/Elev= 30
  4579.8  462.04  4615.3  461.63  4651.5  462.34  4666.6  461.48  4693.9  460.53
  4723.9  460.36  4760.1  457.78  4802.3  455.84  4825.3  455.45  4847.6  454.51
  4925.9  453.39    4941   453.7  4958.6  453.59  4976.1  453.53  4983.2  453.45
  4990.3  452.88  4990.6  452.38  4994.1  452.38  4994.3  452.88  5013.8  453.88
  5033.8  453.09  5043.8  453.13  5053.8  453.76  5073.8  453.73  5193.8  457.34
  5223.8  459.01  5263.9  461.79  5273.9  462.17  5343.9  463.12  5403.6  462.47
#Mann= 5 ,-1 , 0
  4579.8     .05       0  4958.6     .12       0  4976.1     .05       0
  4990.3     .05       0  4994.3     .05       0
Bank Sta=4990.3,4994.3
XS Rating Curve= 0 ,0
Exp/Cntr=0.3,0.1

Type RM Length L Ch R = 1 ,2466    ,489,489,489
BEGIN DESCRIPTION:
Mapping XS b73e1a38
END DESCRIPTION:
XS GIS Cut Line= 5
        2690571.      6918249.85      2690002.44      6918019.83
      2689924.32       6918006.8      2689687.77       6918043.7
      2689548.89      6918178.24
#Sta/Elev= 30
  4302.6  463.12  4318.8  463.28  4444.5  460.64  4468.6  460.67  4491.4  459.76
    4513   460.2  4527.7  459.61  4551.8  457.05  4557.2  456.92  4605.4  456.78
  4728.7  453.66  4862.3  451.87  4915.9  451.85  4932.6  452.71  4940.2  452.51
  4983.3  452.46  4989.7  450.15    4990  449.65  4993.5  449.65  4993.7  450.15
  5003.5  451.46  5013.7   451.8    5044  451.61  5064.3   453.6  5074.4  453.92
  5119.8  455.11  5182.6  455.71  5297.5  460.28  5361.3  461.86  5427.9  462.53
#Mann= 5 ,-1 , 0
  4302.6     .05       0  4862.3     .12       0  4940.2     .05       0
  4989.7     .05       0  4993.7     .05       0
Bank Sta=4989.7,4993.7
XS Rating Curve= 0 ,0
Exp/Cntr=0.3,0.1

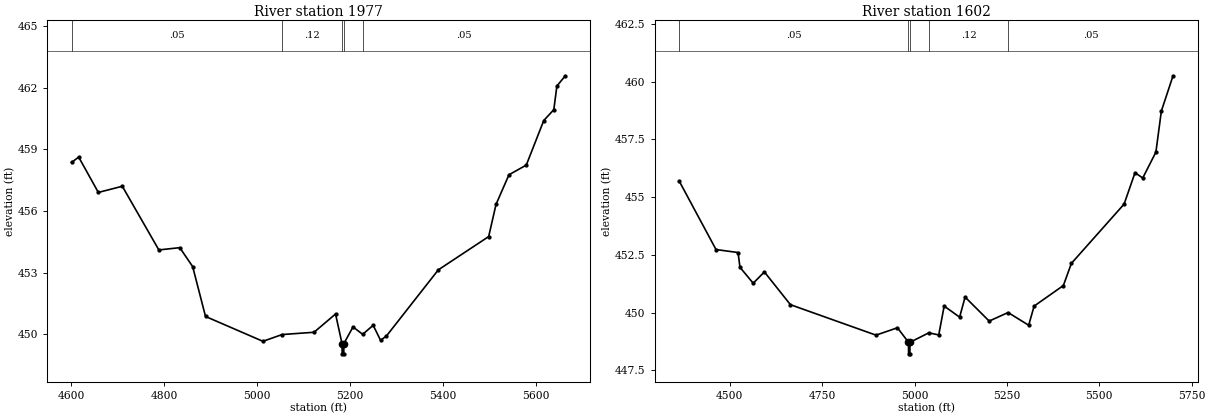
Type RM Length L Ch R = 1 ,1977    ,375,375,375
BEGIN DESCRIPTION:
Mapping XS 37ef0620
END DESCRIPTION:
XS GIS Cut Line= 4
      2690522.53      6917915.21      2690277.75      6917758.97
      2690014.73      6917758.97       2689570.2      6918008.53
#Sta/Elev= 30
  4600.2  458.36  4615.6  458.62  4657.9   456.9  4709.5   457.2  4788.2   454.1
  4833.3  454.21    4861  453.29  4888.7  450.86  5012.3  449.65  5053.7  449.98
  5122.3  450.09  5168.7  450.98  5182.6  449.54  5182.9  449.04  5186.4  449.04
  5186.6  449.54  5206.3  450.35  5227.1  449.99  5249.7  450.43  5265.6   449.7
  5278.3  449.91    5390  453.13  5498.4  454.75  5514.3  456.32  5542.1  457.76
  5579.4  458.23    5617   460.4  5638.7  460.93  5645.3  462.08  5663.4  462.58
#Mann= 5 ,-1 , 0
  4600.2     .05       0  5053.7     .12       0  5182.6     .05       0
  5186.6     .12       0  5227.1     .05       0
Bank Sta=5182.6,5186.6
XS Rating Curve= 0 ,0
Exp/Cntr=0.3,0.1

Type RM Length L Ch R = 1 ,1602    ,0,0,0
BEGIN DESCRIPTION:
Mapping XS 74e19233
END DESCRIPTION:
XS GIS Cut Line= 3
      2690764.77      6917535.02      2690142.33       6917462.1
       2689564.2      6917873.56
#Sta/Elev= 30
  4363.3  455.69  4462.7  452.73  4522.4   452.6  4527.5  451.96  4563.4  451.27
  4593.6  451.76  4664.1  450.34  4895.7  449.02  4953.8  449.34  4983.6  448.71
  4983.9  448.21  4987.4  448.21  4987.6  448.71  5038.6  449.12  5065.5  449.03
  5080.2  450.28    5122   449.8  5136.8  450.67    5202  449.63  5253.2     450
  5308.9  449.45  5323.7  450.28  5402.8  451.17  5424.5  452.13  5567.2   454.7
  5596.7  456.06  5617.6  455.83  5653.2  456.95    5668  458.73  5699.6  460.26
#Mann= 5 ,-1 , 0
  4363.3     .05       0  4983.6     .05       0  4987.6     .05       0
  5038.6     .12       0  5253.2     .05       0
Bank Sta=4983.6,4987.6
XS Rating Curve= 0 ,0
Exp/Cntr=0.3,0.1

Chan Stop Cuts=-1
Use User Specified Reach Order=0
Composite Channel Slope=5