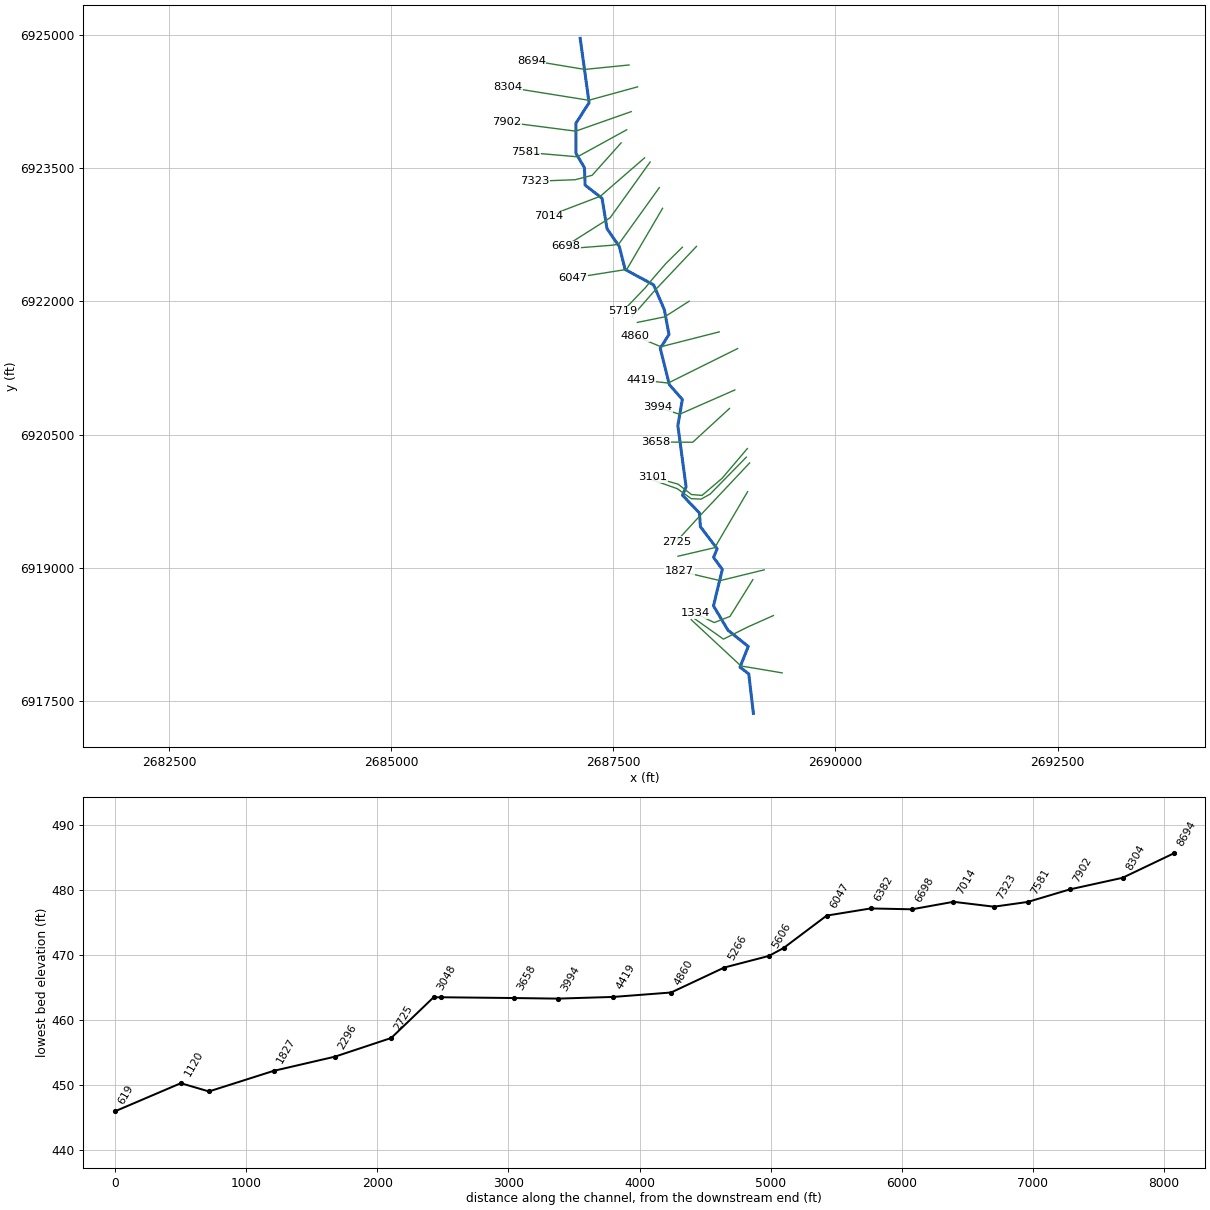
--- Williams T9.prj (project) ---

Proj Title=Williams T9 Base Level Engineering
Current Plan=p01
Default Exp/Contr=0.3,0.1
English Units
Geom File=g01
Flow File=f01
Plan File=p01
Y Axis Title=Elevation
X Axis Title(PF)=Main Channel Distance
X Axis Title(XS)=Station
BEGIN DESCRIPTION:
Williams T9
END DESCRIPTION:
DSS Export Rating Curves= 0
DSS Export Rating Curve Sorted= 0
DSS Export Volume Flow Curves= 0
DXF OffsetX= 0
DXF OffsetY= 0
DXF ScaleX= 1
DXF ScaleY= 10

--- Williams T9.p01 (plan) ---

Plan Title=Multiple Run
Short Identifier=Multiple
Geom File=g01
Flow File=f01
Subcritical Flow
K Sum by GR= 0
Std Step Tol= 0.01
Critical Tol= 0.01
Num of Std Step Trials= 20
Max Error Tol= 0.3
Flow Tol Ratio= 0.001
Split Flow NTrial= 30
Split Flow Tol= 0.02
Split Flow Ratio= 0.02
Log Output Level= 0
Friction Slope Method= 1
Unsteady Friction Slope Method= 2
Unsteady Bridges Friction Slope Method= 1
Parabolic Critical Depth
Global Vel Dist=  1 , 1 , 1
Global Log Level= 0
CheckData=True
Encroach Param= -1, 0, 0, 0
BEGIN DESCRIPTION:
Multiple Run
END DESCRIPTION:

--- Williams T9.f01 (steady flow) ---

Flow Title=Multiple
Number of Profiles=7
Profile Names=10-year,25-year,50-year,1pct_min,100-year,1pct_plu,500-year
River Rch & RM= Williams T9,Reach-1,8694
     528     702     842     501    1001    1996    1411
River Rch & RM= Williams T9,Reach-1,7014
     627     842    1015     607    1211    2416    1723
River Rch & RM= Williams T9,Reach-1,2725
     684     923    1118     671    1339    2671    1919
Boundary for River Rch & Prof#=Williams T9,Reach-1,1
Up Type=0
Dn Type=3
Dn Slope=0.005
Boundary for River Rch & Prof#=Williams T9,Reach-1,2
Up Type=0
Dn Type=3
Dn Slope=0.005
Boundary for River Rch & Prof#=Williams T9,Reach-1,3
Up Type=0
Dn Type=3
Dn Slope=0.005
Boundary for River Rch & Prof#=Williams T9,Reach-1,4
Up Type=0
Dn Type=3
Dn Slope=0.005
Boundary for River Rch & Prof#=Williams T9,Reach-1,5
Up Type=0
Dn Type=3
Dn Slope=0.005
Boundary for River Rch & Prof#=Williams T9,Reach-1,6
Up Type=0
Dn Type=3
Dn Slope=0.005
Boundary for River Rch & Prof#=Williams T9,Reach-1,7
Up Type=0
Dn Type=3
Dn Slope=0.005

--- Williams T9.g01 (geometry) ---

Geom Title=Existing Conditions
Program Version=4.10

River Reach=Williams T9     ,Reach-1
Reach XY= 30
        2687126.        6924961.      2687226.21      6924235.91
      2687078.06      6924005.14      2687077.84      6923667.12
      2687173.76      6923505.07      2687181.45      6923308.53
      2687372.48      6923159.72      2687428.15       6922816.9
      2687566.42      6922617.55      2687631.83      6922358.69
      2687953.19      6922184.95      2688073.73      6921905.06
      2688125.79       6921626.1      2688027.06      6921471.66
      2688129.54      6921062.47      2688276.05      6920895.66
      2688225.55      6920600.81      2688318.41      6919910.99
      2688277.66      6919817.05      2688468.18      6919617.19
      2688479.76      6919462.56      2688667.95      6919214.34
      2688627.67      6919117.05      2688726.13      6918981.47
      2688626.75      6918571.68      2688789.62      6918297.76
      2689018.02      6918114.35      2688925.63      6917881.38
      2689023.99      6917805.32        2689076.        6917361.

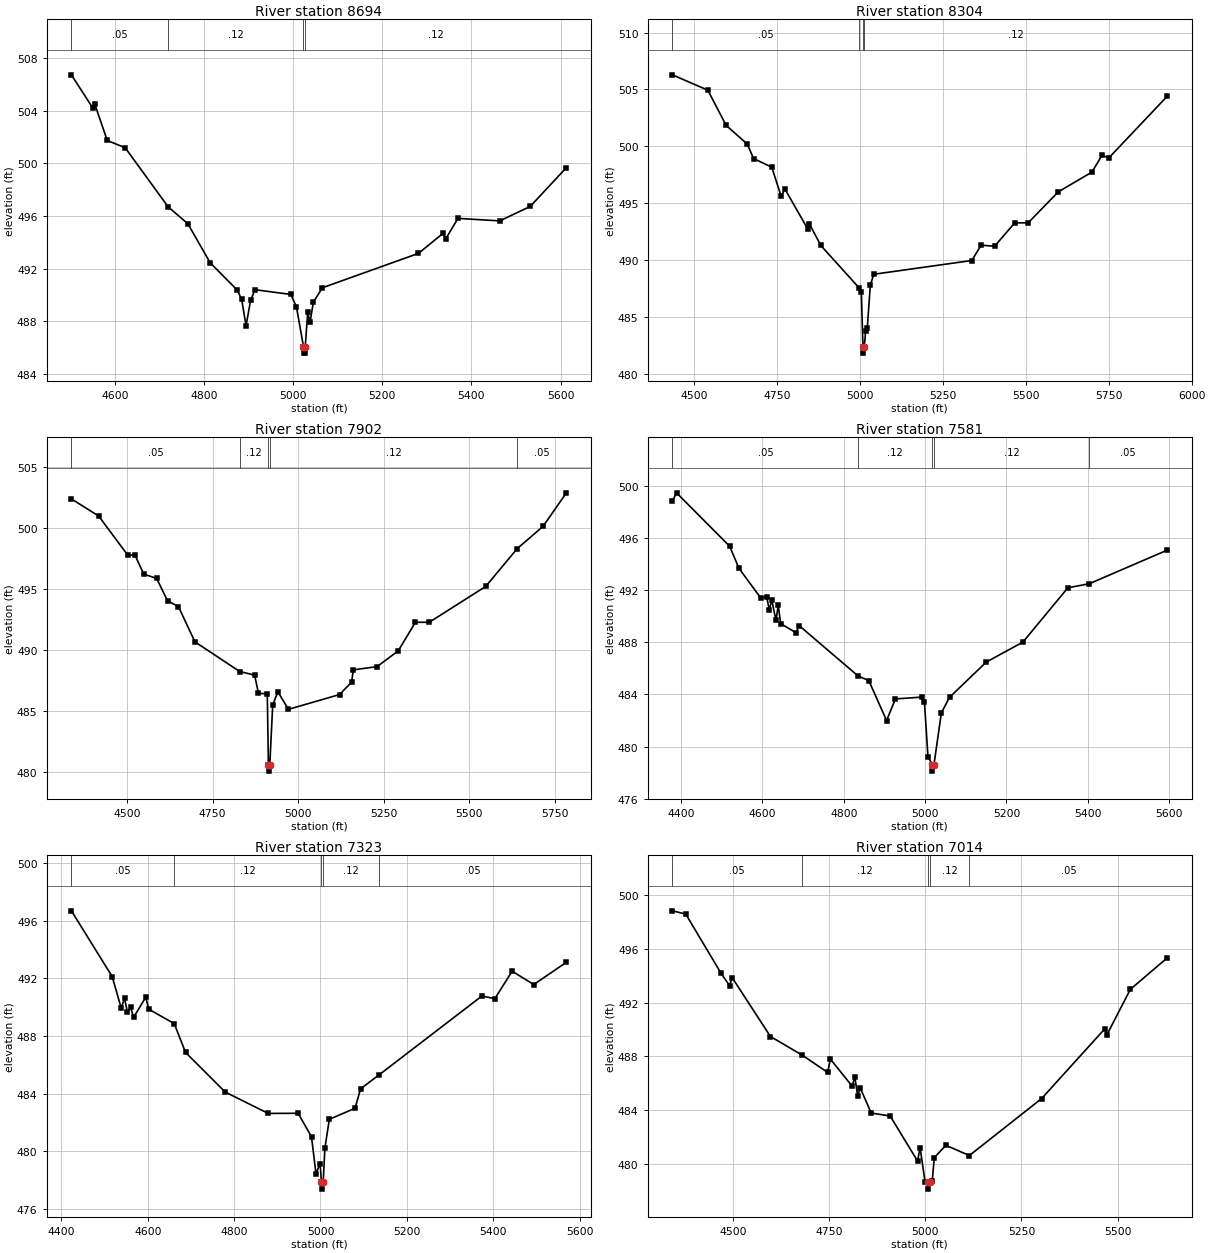
Type RM Length L Ch R = 1 ,8694    ,390,390,390
BEGIN DESCRIPTION:
Williams T9 12.0
END DESCRIPTION:
XS GIS Cut Line= 3
      2687675.96        6924661.        2687176.        6924611.
      2686576.03      6924710.99
#Sta/Elev= 30
  4502.4  506.72  4550.1  504.21  4555.1  504.47  4582.8  501.73    4623  501.18
  4719.4  496.69  4763.7   495.4  4813.9  492.43  4874.2  490.37  4884.3  489.67
  4894.3  487.65  4904.4  489.57  4914.4  490.39  4994.8  490.03  5007.4  489.08
  5023.1  486.07  5023.4  485.57  5026.9  485.57  5027.1  486.07  5032.7   488.7
  5037.8   487.9  5045.4  489.46  5065.7  490.54  5281.1  493.15  5336.9  494.69
  5341.9  494.23  5369.8  495.81  5463.6  495.62    5532  496.72  5613.1  499.67
#Mann= 4 ,-1 , 0
  4502.4     .05       0  4719.4     .12       0  5023.1     .07       0
  5027.1     .12       0
Bank Sta=5023.1,5027.1
XS Rating Curve= 0 ,0
Exp/Cntr=0.3,0.1

Type RM Length L Ch R = 1 ,8304    ,402,402,402
BEGIN DESCRIPTION:
Mapping XS cf7fb767
END DESCRIPTION:
XS GIS Cut Line= 3
      2687772.32      6924414.84      2687222.83      6924263.79
      2686311.39      6924409.62
#Sta/Elev= 30
  4433.8  506.28  4540.7  504.93  4595.9  501.84  4659.6  500.19  4678.9  498.92
  4733.6  498.16  4761.9   495.6  4773.2  496.24    4842  492.74  4847.2  493.17
  4881.6  491.28  4996.2  487.58  5003.7  487.23  5008.6  482.32  5008.8  481.82
  5012.6  482.32  5016.6  483.77  5021.7  484.05  5030.8  487.77    5041  488.75
  5336.9  489.96    5365  491.31  5405.5  491.21  5466.3  493.27  5506.8  493.27
    5598     496  5699.2  497.73  5729.6  499.21  5749.9  498.97  5926.7  504.41
#Mann= 4 ,-1 , 0
  4433.8     .05       0  4996.2     .12       0  5008.6     .07       0
  5012.6     .12       0
Bank Sta=5008.6,5012.6
XS Rating Curve= 0 ,0
Exp/Cntr=0.3,0.1

Type RM Length L Ch R = 1 ,7902    ,321,321,321
BEGIN DESCRIPTION:
Williams T9 10.0
END DESCRIPTION:
XS GIS Cut Line= 3
      2687700.97      6924135.99      2687075.84      6923916.01
       2686298.4      6924016.39
#Sta/Elev= 30
  4337.3  502.37  4416.8  500.97  4501.6  497.77  4523.1  497.76  4548.7   496.2
  4586.4  495.85  4618.2  494.01    4650  493.54  4698.2  490.65  4829.1  488.21
  4872.6  487.92    4884  486.43  4909.7  486.37    4913  480.54  4913.3  480.04
    4917  480.54  4925.6  485.47  4940.7  486.54  4971.6  485.11  5120.8  486.32
  5156.1  487.34  5161.2  488.35  5230.4  488.61  5292.2   489.9  5342.7  492.25
    5383  492.25    5548  495.19  5640.4   498.3  5715.7  500.12  5783.9  502.87
#Mann= 5 ,-1 , 0
  4337.3     .05       0  4829.1     .12       0    4913     .07       0
    4917     .12       0  5640.4     .05       0
Bank Sta=4913,4917
XS Rating Curve= 0 ,0
Exp/Cntr=0.3,0.1

Type RM Length L Ch R = 1 ,7581    ,258,258,258
BEGIN DESCRIPTION:
Mapping XS 1de0d930
END DESCRIPTION:
XS GIS Cut Line= 3
      2687649.36      6923931.27      2687095.95      6923627.43
      2686512.21      6923677.35
#Sta/Elev= 30
  4378.4  498.85  4388.6   499.5  4519.4  495.39  4541.9  493.71  4595.2  491.44
  4610.4  491.48    4617  490.48  4622.7  491.29  4633.1  489.69  4638.8  490.86
  4644.6  489.45  4682.4  488.75  4690.3  489.29  4835.6  485.41  4861.4  485.07
  4905.1     482  4926.9  483.66  4992.3   483.8  4998.3  483.39  5006.9  479.22
  5017.7  478.61    5018  478.11  5021.7  478.61  5039.8  482.58  5059.9  483.78
  5150.2  486.49  5240.5  488.03  5350.9   492.2  5403.4  492.51  5595.6   495.1
#Mann= 5 ,-1 , 0
  4378.4     .05       0  4835.6     .12       0  5017.7     .07       0
  5021.7     .12       0  5403.4     .05       0
Bank Sta=5017.7,5021.7
XS Rating Curve= 0 ,0
Exp/Cntr=0.3,0.1

Type RM Length L Ch R = 1 ,7323    ,309,309,309
BEGIN DESCRIPTION:
Mapping XS 3be16e52
END DESCRIPTION:
XS GIS Cut Line= 4
      2687586.38      6923783.66      2687260.88       6923419.1
      2687069.91      6923369.19      2686610.45      6923351.85
#Sta/Elev= 30
  4423.4  496.68  4517.8  492.12  4538.8  489.92  4546.3  490.64    4553  489.65
  4560.5  489.99  4567.2  489.29  4595.6  490.69  4602.3  489.86  4661.4  488.86
  4687.6  486.86  4779.5  484.11    4879  482.63  4948.2  482.64  4979.2  481.01
  4989.5  478.46  4999.1  479.15  5002.3  477.88  5002.5  477.38  5006.3  477.88
  5010.2  480.22  5020.5  482.22    5080  482.99  5092.9  484.34  5135.9  485.31
  5373.6  490.77  5403.6  490.59  5443.7  492.49  5493.7  491.57  5569.3  493.11
#Mann= 5 ,-1 , 0
  4423.4     .05       0  4661.4     .12       0  5002.3     .07       0
  5006.3     .12       0  5135.9     .05       0
Bank Sta=5002.3,5006.3
XS Rating Curve= 0 ,0
Exp/Cntr=0.3,0.1

Type RM Length L Ch R = 1 ,7014    ,316,316,316
BEGIN DESCRIPTION:
Mapping XS 0ec7f5a9
END DESCRIPTION:
XS GIS Cut Line= 3
      2687851.17      6923615.43      2687352.89      6923183.13
      2686766.05      6922959.16
#Sta/Elev= 30
  4341.8  498.83  4376.6  498.59  4468.7  494.17  4490.6  493.27  4497.2  493.87
    4597  489.48  4678.9  488.11  4745.8  486.81  4752.7  487.81  4809.7  485.78
  4816.3   486.5  4823.9  485.08  4830.6  485.65  4859.1  483.79  4908.4  483.57
  4979.7  480.22  4986.3  481.22  4999.3  478.65  5006.8  478.63  5007.1  478.13
  5010.8  478.63  5017.8   478.7  5023.2  480.47  5053.3  481.39  5114.5  480.63
  5302.6  484.87    5467  490.06  5472.3  489.61  5533.3  492.99  5629.6  495.34
#Mann= 5 ,-1 , 0
  4341.8     .05       0  4678.9     .12       0  5006.8     .07       0
  5010.8     .12       0  5114.5     .05       0
Bank Sta=5006.8,5010.8
XS Rating Curve= 0 ,0
Exp/Cntr=0.3,0.1

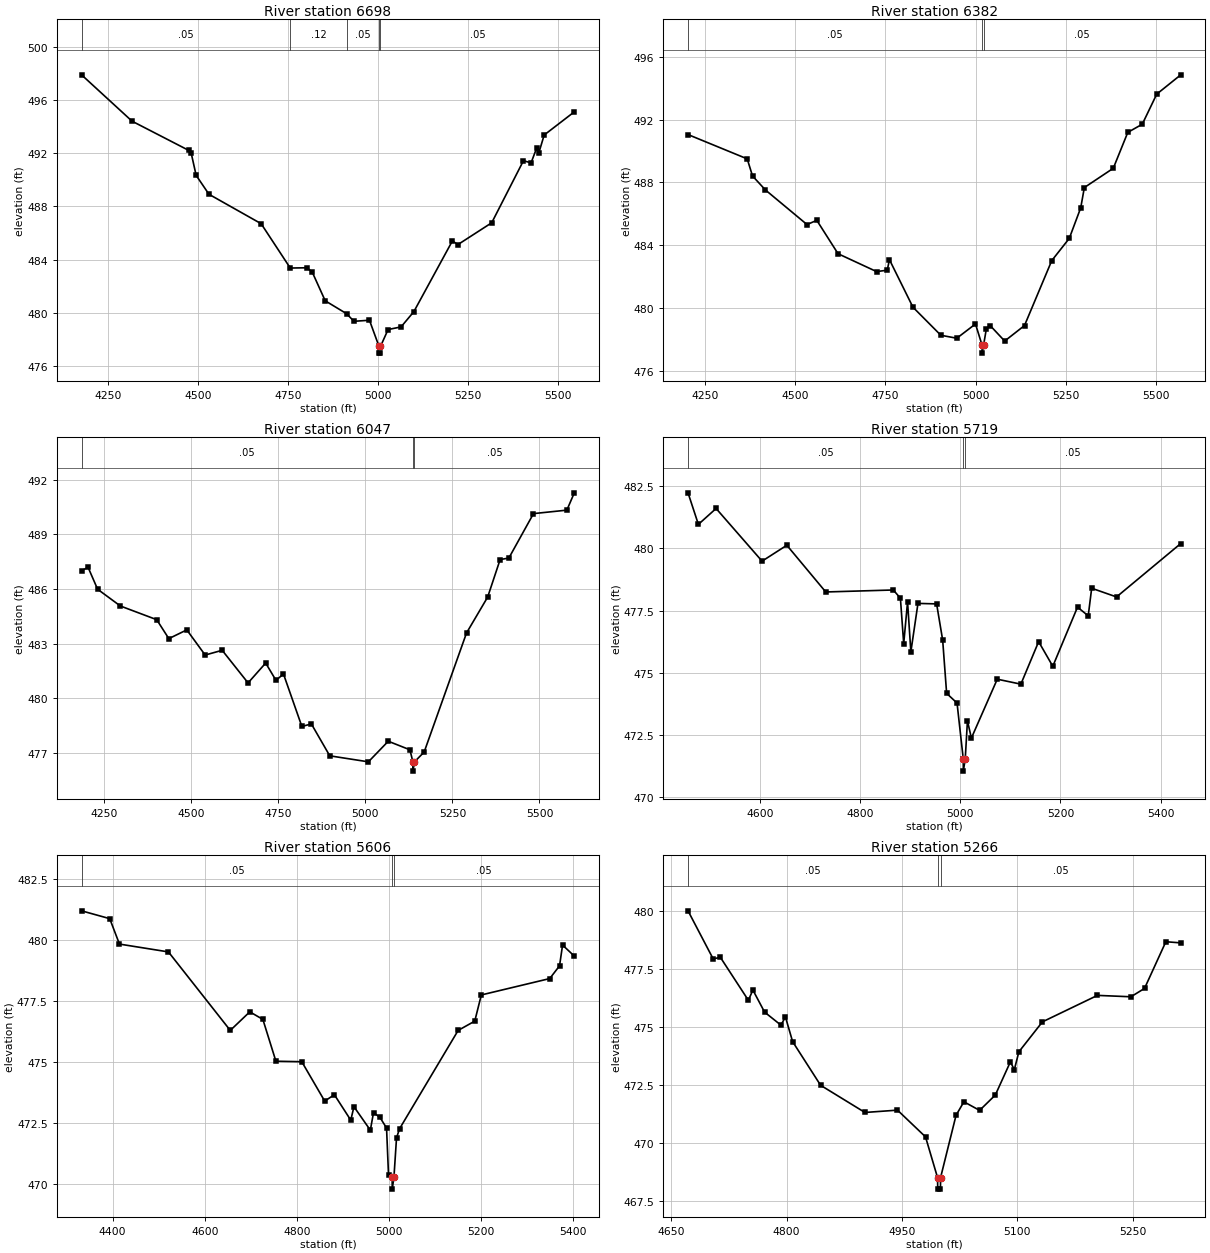
Type RM Length L Ch R = 1 ,6698    ,316,316,316
BEGIN DESCRIPTION:
Mapping XS deb326df
END DESCRIPTION:
XS GIS Cut Line= 3
      2687913.67      6923568.57      2687464.01      6922941.82
      2686959.92      6922621.35
#Sta/Elev= 30
  4176.2  497.88  4316.4   494.4  4473.6  492.21  4480.9  491.98  4494.5  490.33
  4530.1  488.91    4675   486.7  4755.9  483.37  4802.7  483.39  4817.4  483.04
    4853  480.91  4912.4  479.94  4932.8  479.37  4975.9  479.45  5002.5  477.48
  5002.7  476.98  5006.2  476.98  5006.5  477.48  5027.6  478.75  5063.7  478.95
  5099.3   480.1  5206.3  485.41  5221.5  485.13  5315.5  486.77  5403.6  491.43
  5424.8  491.27    5440  492.36  5445.9  491.98  5461.2  493.36  5544.9   495.1
#Mann= 5 ,-1 , 0
  4176.2     .05       0  4755.9     .12       0  4912.4     .05       0
  5002.5     .03       0  5006.5     .05       0
Bank Sta=5002.5,5006.5
XS Rating Curve= 0 ,0
Exp/Cntr=0.3,0.1

Type RM Length L Ch R = 1 ,6382    ,335,335,335
BEGIN DESCRIPTION:
Mapping XS 7b43fcae
END DESCRIPTION:
XS GIS Cut Line= 4
      2688016.51      6923279.47      2687559.93      6922644.07
      2687487.01      6922631.92      2686979.62      6922592.09
#Sta/Elev= 30
  4203.4  491.05  4367.4   489.5  4382.1  488.41  4417.7  487.52  4533.1  485.31
  4560.2  485.58  4619.1  483.45  4725.9  482.31  4755.4   482.4  4761.5  483.07
  4826.6  480.04  4903.9  478.25  4948.1  478.06  4999.9  478.97  5018.2  477.61
  5018.5  477.11  5022.2  477.61  5030.1  478.67  5040.5  478.87  5080.8  477.88
  5135.7  478.87  5211.2  483.01  5259.8  484.43  5291.5  486.38  5301.5  487.67
  5381.7   488.9  5421.9  491.19    5462  491.71  5502.1  493.63  5568.7  494.86
#Mann= 3 ,-1 , 0
  4203.4     .05       0  5018.2     .03       0  5022.2     .05       0
Bank Sta=5018.2,5022.2
XS Rating Curve= 0 ,0
Exp/Cntr=0.3,0.1

Type RM Length L Ch R = 1 ,6047    ,328,328,328
BEGIN DESCRIPTION:
Mapping XS 47049735
END DESCRIPTION:
XS GIS Cut Line= 3
       2688053.5      6923047.19      2687650.72       6922359.7
       2687040.3      6922262.58
#Sta/Elev= 30
  4185.2  487.01    4204  487.19  4231.3  485.99  4296.7  485.07    4401  484.32
  4435.8  483.28  4487.4  483.76  4540.1  482.38    4589  482.64  4663.3  480.85
  4713.9  481.94  4743.5  480.99    4765  481.34  4817.8  478.46  4845.1   478.6
  4897.9  476.85  5008.8  476.52  5065.9  477.65  5128.1  477.18  5136.7  476.51
  5136.9  476.01  5140.7  476.51    5169  477.06  5290.6  483.59  5351.3  485.56
  5387.1  487.62  5412.1   487.7  5482.9  490.14  5578.7  490.33  5600.1  491.28
#Mann= 3 ,-1 , 0
  4185.2     .05       0  5136.7     .04       0  5140.7     .05       0
Bank Sta=5136.7,5140.7
XS Rating Curve= 0 ,0
Exp/Cntr=0.3,0.1

Type RM Length L Ch R = 1 ,5719    ,113,113,113
BEGIN DESCRIPTION:
Mapping XS 54f1a191
END DESCRIPTION:
XS GIS Cut Line= 5
      2688276.72      6922609.54      2688087.94      6922422.92
       2687938.2      6922249.31      2687860.07      6922153.82
      2687606.18      6921889.09
#Sta/Elev= 30
  4455.6  482.24  4476.3  480.97  4511.7  481.61  4603.6  479.49  4653.1  480.13
  4730.9  478.25  4865.9  478.33  4880.1     478  4886.7  476.17  4894.4  477.85
    4901  475.84  4915.2  477.79  4952.5  477.77  4964.6  476.31  4972.5  474.17
  4993.3  473.78  5005.7  471.54  5005.9  471.04  5009.7  471.54  5014.1  473.06
    5022  472.37  5073.7  474.74  5120.9  474.54  5156.4  476.25  5184.7  475.26
  5234.1  477.64  5255.5  477.29  5262.4   478.4  5312.1  478.05  5440.5   480.2
#Mann= 3 ,-1 , 0
  4455.6     .05       0  5005.7     .03       0  5009.7     .05       0
Bank Sta=5005.7,5009.7
XS Rating Curve= 0 ,0
Exp/Cntr=0.3,0.1

Type RM Length L Ch R = 1 ,5606    ,340,340,340
BEGIN DESCRIPTION:
Mapping XS dd72d975
END DESCRIPTION:
XS GIS Cut Line= 3
      2688435.19      6922618.26      2687975.09      6922132.12
      2687710.66      6921830.85
#Sta/Elev= 30
  4332.5  481.19  4393.7  480.87  4414.8  479.83  4521.2  479.51  4655.5   476.3
  4697.9  477.06  4726.3  476.75  4754.6  475.04  4810.8  475.02  4860.6  473.41
  4881.6  473.67  4917.2  472.63  4924.1  473.18  4959.7  472.22  4966.6  472.94
  4980.7  472.74  4994.9  472.31  4999.2  470.39    5007  470.31  5007.3  469.81
    5011  470.31  5016.6  471.91  5023.2  472.28  5150.4   476.3  5186.5  476.68
  5200.7  477.75  5349.3  478.42  5370.6  478.94  5377.2  479.79  5402.7  479.34
#Mann= 3 ,-1 , 0
  4332.5     .05       0    5007     .03       0    5011     .05       0
Bank Sta=5007,5011
XS Rating Curve= 0 ,0
Exp/Cntr=0.3,0.1

Type RM Length L Ch R = 1 ,5266    ,406,406,406
BEGIN DESCRIPTION:
Mapping XS a680a75f
END DESCRIPTION:
XS GIS Cut Line= 3
      2688352.54      6922001.04      2688076.94      6921825.26
      2687769.87      6921762.55
#Sta/Elev= 30
    4672  480.01  4704.7  477.94    4714  478.01  4750.4  476.16  4756.3   476.6
  4771.5  475.65  4792.7  475.09  4798.6  475.44  4807.9  474.38  4844.3   472.5
  4901.9  471.33  4944.2  471.43  4980.6  470.28  4996.2  468.53  4996.5  468.03
    5000  468.03  5000.2  468.53  5020.3  471.21  5030.5  471.79  5050.9  471.42
  5071.3  472.08  5090.9  473.51    5096  473.17  5101.9  473.94  5132.5  475.23
    5204  476.37  5247.5  476.31  5265.2  476.67  5292.9  478.68  5312.3  478.63
#Mann= 3 ,-1 , 0
    4672     .05       0  4996.2     .04       0  5000.2     .05       0
Bank Sta=4996.2,5000.2
XS Rating Curve= 0 ,0
Exp/Cntr=0.3,0.1

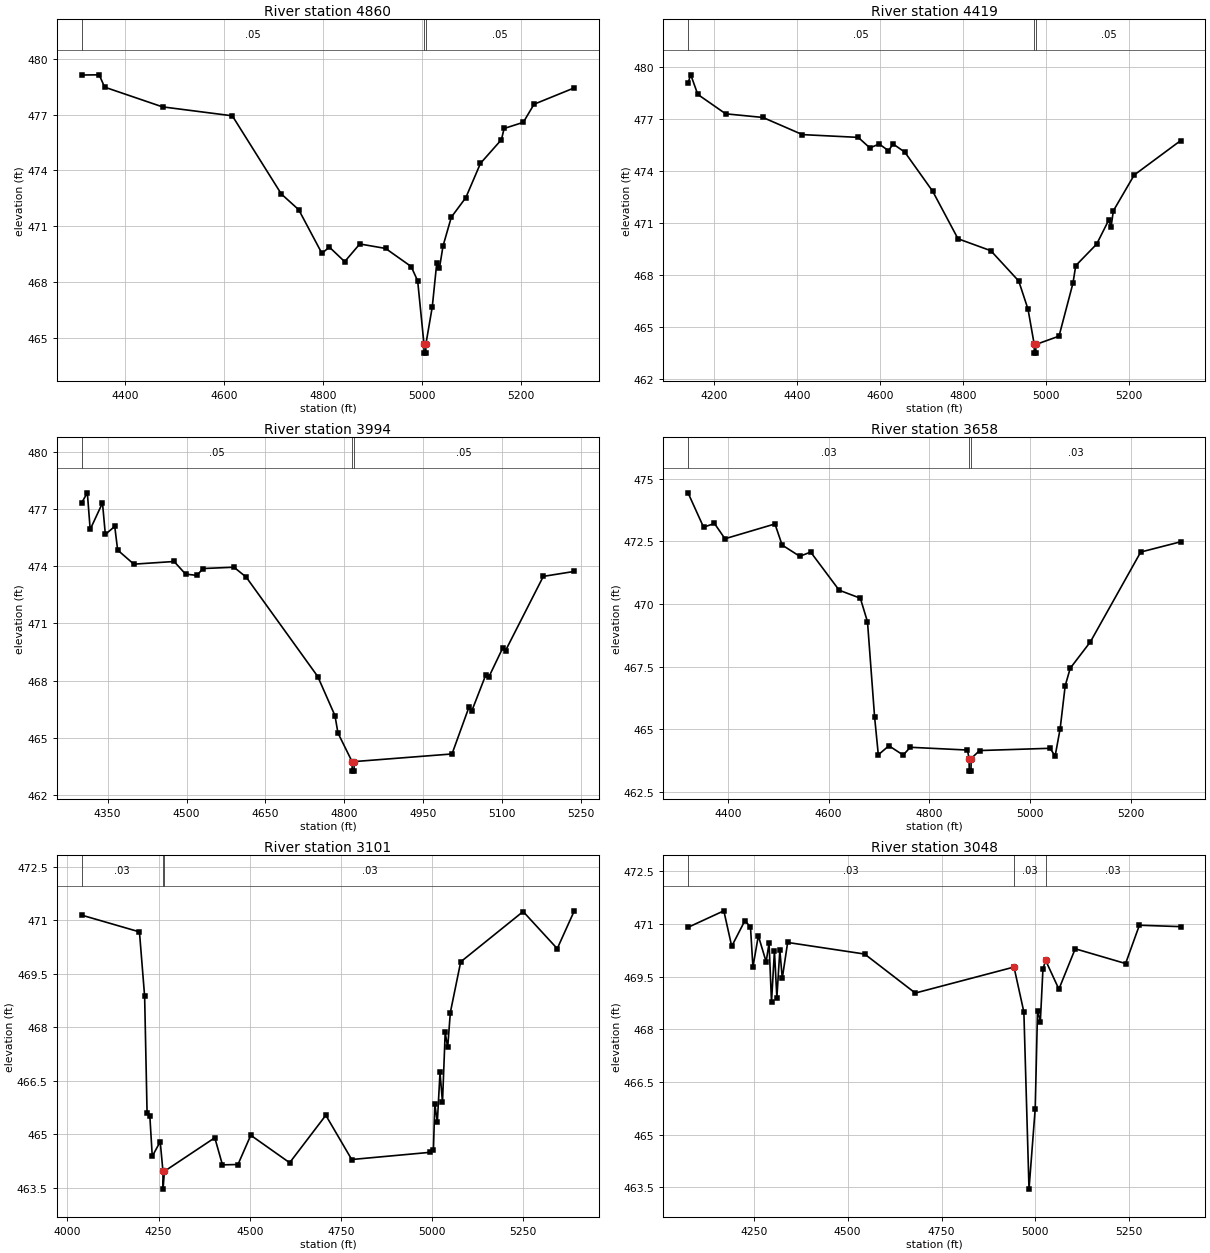
Type RM Length L Ch R = 1 ,4860    ,441,441,441
BEGIN DESCRIPTION:
Mapping XS 53e072c8
END DESCRIPTION:
XS GIS Cut Line= 3
      2688691.05      6921655.98      2688035.71      6921488.89
      2687740.74      6921610.35
#Sta/Elev= 30
  4312.4  479.12  4348.1  479.13  4358.9  478.47  4475.9  477.41  4616.9  476.93
    4716  472.73    4751  471.89  4797.8  469.55    4813  469.88  4843.9   469.1
  4874.4  470.05  4926.5  469.81  4978.1  468.84  4991.3  468.07    5004  464.69
  5004.2  464.19  5007.7  464.19    5008  464.69  5020.8  466.67  5029.9  469.04
  5035.3  468.75  5042.5  469.94  5059.3  471.49  5088.6  472.54  5118.2  474.38
  5160.5  475.65  5165.9  476.25  5204.7  476.58  5226.3  477.55  5307.7  478.43
#Mann= 3 ,-1 , 0
  4312.4     .05       0    5004     .04       0    5008     .05       0
Bank Sta=5004,5008
XS Rating Curve= 0 ,0
Exp/Cntr=0.3,0.1

Type RM Length L Ch R = 1 ,4419    ,425,425,425
BEGIN DESCRIPTION:
Mapping XS 1361a297
END DESCRIPTION:
XS GIS Cut Line= 3
      2688898.26      6921468.29      2688117.05      6921080.29
      2687804.54      6921114.15
#Sta/Elev= 30
  4137.5   479.1  4144.1  479.57    4161  478.44  4228.2  477.32  4317.8  477.11
    4413  476.12  4547.4  475.96  4575.5  475.35  4597.8  475.58  4620.2  475.19
  4631.3  475.58  4659.5  475.11  4726.7  472.85  4787.6  470.11  4866.7  469.42
  4933.9  467.67  4956.3  466.04  4971.2  464.01  4971.4  463.51  4974.9  463.51
  4975.2  464.01  5030.9  464.49  5064.4  467.54  5071.2  468.56  5121.5   469.8
  5151.1  471.21  5156.1  470.76  5161.7  471.72    5212  473.79  5324.1  475.78
#Mann= 3 ,-1 , 0
  4137.5     .05       0  4971.2     .04       0  4975.2     .05       0
Bank Sta=4971.2,4975.2
XS Rating Curve= 0 ,0
Exp/Cntr=0.3,0.1

Type RM Length L Ch R = 1 ,3994    ,336,336,336
BEGIN DESCRIPTION:
Mapping XS e0aab7a0
END DESCRIPTION:
XS GIS Cut Line= 3
      2688867.03      6921002.16      2688244.66      6920728.73
      2687999.91      6920806.84
#Sta/Elev= 30
  4300.4  477.31  4311.4  477.84  4316.8  475.92  4340.2  477.31  4345.6  475.66
  4363.5  476.08    4369  474.84  4399.8   474.1  4476.3  474.24  4498.1  473.58
    4520  473.51  4530.9  473.87  4590.1  473.94  4613.4  473.42  4749.4  468.21
  4782.1  466.16  4787.8  465.25  4814.6  463.75  4814.9  463.25  4818.4  463.25
  4818.6  463.75  5004.6  464.15  5036.8   466.6    5042  466.39  5068.9   468.3
  5074.2  468.16  5101.1  469.71  5106.4  469.57  5178.2  473.46  5237.1  473.72
#Mann= 3 ,-1 , 0
  4300.4     .05       0  4814.6     .04       0  4818.6     .05       0
Bank Sta=4814.6,4818.6
XS Rating Curve= 0 ,0
Exp/Cntr=0.3,0.1

Type RM Length L Ch R = 1 ,3658    ,557,557,557
BEGIN DESCRIPTION:
Mapping XS 76417644
END DESCRIPTION:
XS GIS Cut Line= 3
      2688807.13      6920793.81      2688393.09      6920413.63
      2687976.41      6920416.23
#Sta/Elev= 30
  4320.9  474.43  4351.8  473.06  4373.4  473.21  4394.3   472.6  4493.6  473.19
  4507.8  472.35  4542.9   471.9  4564.5  472.07  4621.1  470.55  4663.2  470.23
  4677.4  469.29  4691.5   465.5  4698.9  463.99  4719.9  464.35  4748.3  463.98
  4762.4  464.29  4875.9  464.18  4879.2  463.84  4879.5  463.34    4883  463.34
  4883.2  463.84  4900.1  464.16  5040.1  464.25  5050.1  463.94  5060.1  465.03
  5070.1  466.74  5080.1  467.44  5120.1  468.49  5220.1  472.07  5299.7  472.48
#Mann= 3 ,-1 , 0
  4320.9     .03       0  4879.2     .03       0  4883.2     .03       0
Bank Sta=4879.2,4883.2
XS Rating Curve= 0 ,0
Exp/Cntr=0.3,0.1

Type RM Length L Ch R = 1 ,3101    ,53,53,53
BEGIN DESCRIPTION:
Mapping XS ea880954
END DESCRIPTION:
XS GIS Cut Line= 6
      2689008.24      6920342.55       2688723.5      6920007.46
      2688497.81      6919814.75      2688378.02      6919825.17
      2688228.71      6919941.49      2687940.92      6920022.58
#Sta/Elev= 30
  4039.1  471.14  4197.8  470.67    4212  468.86  4218.7  465.59  4226.2  465.52
  4232.9  464.38  4254.7  464.79  4262.2  463.96  4262.5  463.46  4266.2  463.96
  4404.3   464.9  4425.3  464.14  4467.8  464.15  4502.9  464.97  4609.5   464.2
  4708.6  465.53  4779.6  464.29    4993  464.49  5003.5  464.56  5007.4  465.85
  5014.2  465.33  5021.6  466.73  5028.4  465.89  5035.8  467.85  5042.6  467.43
  5049.9  468.41  5078.3  469.83  5249.4  471.24  5342.9   470.2  5389.7  471.26
#Mann= 3 ,-1 , 0
  4039.1     .03       0  4262.2     .03       0  4266.2     .03       0
Bank Sta=4262.2,4266.2
XS Rating Curve= 0 ,0
Exp/Cntr=0.3,0.1

Type RM Length L Ch R = 1 ,3048    ,323,323,323
BEGIN DESCRIPTION:
Mapping XS c848053f
END DESCRIPTION:
XS GIS Cut Line= 6
      2688996.08      6920245.32      2688589.82      6919830.38
      2688487.39      6919773.09      2688376.28       6919778.3
       2688218.3      6919891.14      2687930.74      6919992.86
#Sta/Elev= 30
  4074.7   470.9  4170.1  471.37  4191.1  470.36  4226.2  471.09  4241.1  470.91
  4247.6  469.77    4262  470.66  4282.8  469.92  4290.6  470.45  4297.1  468.77
  4304.9  470.23  4311.4   468.9  4319.3  470.25  4325.8  469.45  4340.1  470.47
  4545.2  470.14  4680.1  469.03  4943.1  469.77  4969.4  468.49  4983.1  463.45
  4999.6  465.74  5005.8  468.53  5013.3  468.22  5020.2  469.71  5027.3  469.96
  5062.7  469.14  5106.2  470.29  5240.4  469.87  5277.1  470.96  5387.4  470.92
#Mann= 3 ,-1 , 0
  4074.7     .03       0  4943.1     .03       0  5027.3     .03       0
Bank Sta=4943.1,5027.3
XS Rating Curve= 0 ,0
Exp/Cntr=0.3,0.1

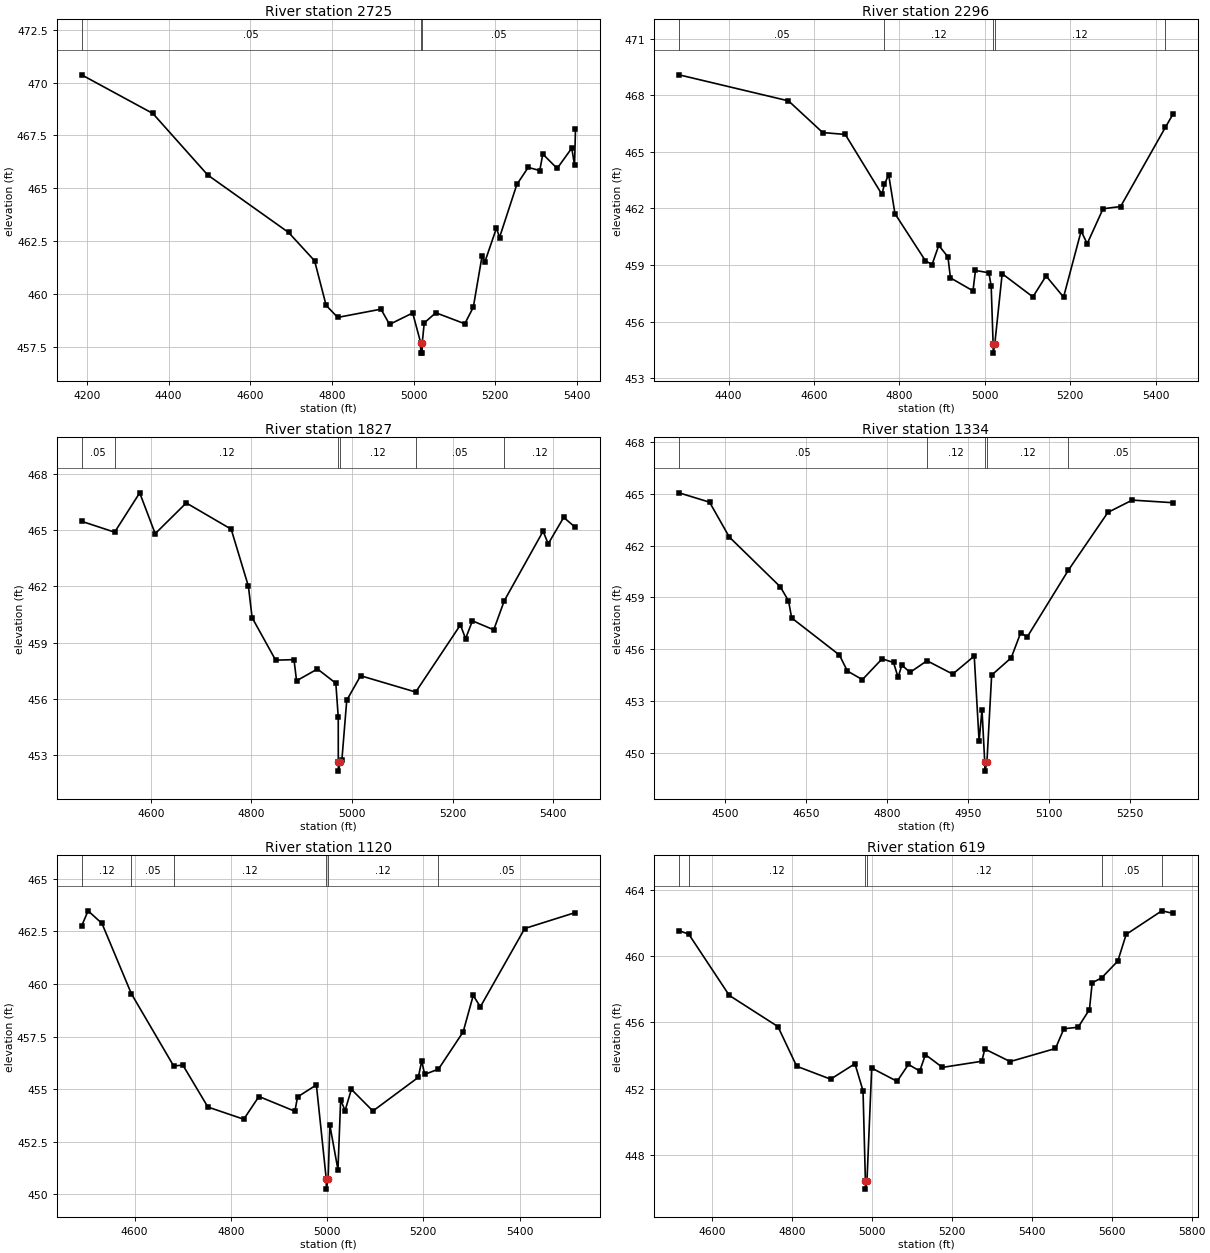
Type RM Length L Ch R = 1 ,2725    ,429,429,429
BEGIN DESCRIPTION:
Mapping XS 466cd657
END DESCRIPTION:
XS GIS Cut Line= 3
       2689033.4      6920180.21       2688472.2      6919583.85
      2688208.41      6919295.37
#Sta/Elev= 30
  4186.9  470.37  4361.5  468.54  4495.8  465.63  4693.9  462.91  4757.6  461.57
  4785.9  459.46  4814.2  458.89  4920.2  459.28  4941.3  458.56  4997.9   459.1
  5017.4   457.7  5017.7   457.2  5021.2   457.2  5021.4   457.7  5026.2  458.63
  5054.6  459.11  5125.5  458.59  5146.4  459.37    5168  461.81  5174.8  461.52
  5203.2  463.12  5210.6  462.67  5253.1  465.18  5280.9  465.99  5309.2  465.84
  5316.7  466.62  5351.8  465.94  5387.6   466.9  5394.4   466.1  5396.7  467.79
#Mann= 3 ,-1 , 0
  4186.9     .05       0  5017.4     .03       0  5021.4     .05       0
Bank Sta=5017.4,5021.4
XS Rating Curve= 0 ,0
Exp/Cntr=0.3,0.1

Type RM Length L Ch R = 1 ,2296    ,469,469,469
BEGIN DESCRIPTION:
Mapping XS f9b6457c
END DESCRIPTION:
XS GIS Cut Line= 3
      2689010.64      6919856.78      2688640.87       6919226.6
      2688226.78      6919130.24
#Sta/Elev= 30
  4284.2  469.08  4540.3   467.7  4620.4  466.02  4673.2  465.92  4759.1  462.74
  4764.7  463.28  4774.8  463.78  4789.5  461.72  4860.7  459.23  4876.3  459.02
    4892  460.04  4913.5  459.43  4919.3  458.32  4972.1  457.63  4977.9  458.71
  5009.3  458.59  5014.7  457.88  5019.2  454.83  5019.5  454.33  5023.2  454.83
  5040.4  458.54  5112.3  457.31  5143.1  458.42  5184.1   457.3  5225.2   460.8
  5239.4  460.13  5276.5  461.98  5317.6   462.1  5422.2  466.29    5440  466.99
#Mann= 5 ,-1 , 0
  4284.2     .05       0  4764.7     .12       0  5019.2     .07       0
  5023.2     .12       0  5422.2     .05       0
Bank Sta=5019.2,5023.2
XS Rating Curve= 0 ,0
Exp/Cntr=0.3,0.1

Type RM Length L Ch R = 1 ,1827    ,493,493,493
BEGIN DESCRIPTION:
Mapping XS 61c2ce0d
END DESCRIPTION:
XS GIS Cut Line= 3
      2689198.14      6918977.12      2688701.63       6918855.6
      2688243.27      6918963.24
#Sta/Elev= 30
  4462.4  465.47  4528.1  464.89  4577.9  466.99  4608.7  464.81  4670.5  466.45
  4759.8  465.05  4794.1     462  4801.4  460.33  4848.2  458.06  4884.7  458.09
  4889.8  456.96  4931.4  457.59  4967.9  456.83  4972.7  455.02  4972.8  452.64
    4973  452.14  4976.8  452.64  4979.9  452.73  4989.6  455.92  5017.2  457.23
  5126.7  456.36  5215.6  459.94  5225.9  459.21  5239.5  460.16  5281.9  459.68
  5302.8  461.23    5380  464.94  5390.2  464.27    5421  465.68  5444.4  465.14
#Mann= 6 ,-1 , 0
  4462.4     .05       0  4528.1     .12       0  4972.8     .07       0
  4976.8     .12       0  5126.7     .05       0  5302.8     .12       0
Bank Sta=4972.8,4976.8
XS Rating Curve= 0 ,0
Exp/Cntr=0.3,0.1

Type RM Length L Ch R = 1 ,1334    ,214,214,214
BEGIN DESCRIPTION:
Mapping XS 953f455a
END DESCRIPTION:
XS GIS Cut Line= 4
       2689069.7      6918866.04      2688812.74      6918452.82
      2688635.66      6918383.37      2688420.35      6918487.55
#Sta/Elev= 30
  4414.1  465.04  4470.7   464.5  4507.3  462.49  4601.8  459.62  4617.1  458.81
    4623  457.82  4711.6  455.68  4726.2  454.76  4754.1  454.26  4790.7  455.46
  4811.9  455.25  4820.4  454.39  4827.3   455.1  4842.6  454.68    4874  455.35
  4921.7  454.58  4961.6  455.62  4970.6  450.71    4976  452.53  4981.1  449.48
  4981.4  448.98  4985.1  449.48  4993.9  454.52  5030.2  455.52  5047.6  456.95
    5060  456.73  5136.3  460.58  5209.5  463.91  5254.6  464.62  5330.1  464.47
#Mann= 5 ,-1 , 0
  4414.1     .05       0    4874     .12       0  4981.1     .07       0
  4985.1     .12       0  5136.3     .05       0
Bank Sta=4981.1,4985.1
XS Rating Curve= 0 ,0
Exp/Cntr=0.3,0.1

Type RM Length L Ch R = 1 ,1120    ,501,501,501
BEGIN DESCRIPTION:
Mapping XS 0eb720f8
END DESCRIPTION:
XS GIS Cut Line= 4
      2689301.46      6918462.37        2689015.      6918334.76
      2688738.96      6918196.74      2688409.59      6918430.15
#Sta/Elev= 30
  4490.1  462.75  4503.6  463.47  4532.4  462.87  4593.5  459.53  4681.3   456.1
  4700.5  456.14  4752.4  454.15  4826.9  453.57  4858.5  454.65  4933.1  453.95
  4938.7  454.63  4977.8   455.2  4998.2  450.75  4998.5  450.25  5002.2  450.75
  5005.8  453.29  5022.6  451.17  5028.2  454.49  5037.4  453.98  5050.5  454.99
  5095.2  453.96  5189.5  455.56  5196.6  456.34  5202.7   455.7  5231.4  455.95
  5282.7  457.72  5303.6  459.45  5318.4  458.91  5410.6  462.63    5516  463.39
#Mann= 6 ,-1 , 0
  4490.1     .12       0  4593.5     .05       0  4681.3     .12       0
  4998.2     .07       0  5002.2     .12       0  5231.4     .05       0
Bank Sta=4998.2,5002.2
XS Rating Curve= 0 ,0
Exp/Cntr=0.3,0.1

Type RM Length L Ch R = 1 ,619     ,0,0,0
BEGIN DESCRIPTION:
Mapping XS 0a3e5de7
END DESCRIPTION:
XS GIS Cut Line= 3
      2689399.96      6917816.97      2688935.57      6917895.09
      2688375.68      6918415.92
#Sta/Elev= 30
  4517.5  461.52  4541.6  461.32  4643.2  457.62  4764.9  455.74  4811.8  453.35
  4896.7  452.57  4957.6   453.5  4977.8  451.87  4983.7  446.44  4983.9  445.94
  4987.7  446.44  4999.5  453.24    5063  452.44  5091.4  453.46  5119.7  453.06
  5133.9  454.05  5176.4  453.28  5275.1  453.65  5282.4  454.39  5345.9  453.63
  5459.3  454.42  5480.3  455.61    5516   455.7  5544.3  456.77  5551.1  458.38
  5574.9  458.68  5615.2  459.69  5636.2   461.3  5725.3  462.72  5753.1  462.57
#Mann= 6 ,-1 , 0
  4517.5     .05       0  4541.6     .12       0  4983.7     .07       0
  4987.7     .12       0  5574.9     .05       0  5725.3     .12       0
Bank Sta=4983.7,4987.7
XS Rating Curve= 0 ,0
Exp/Cntr=0.3,0.1

Chan Stop Cuts=-1
Use User Specified Reach Order=0
Composite Channel Slope=5