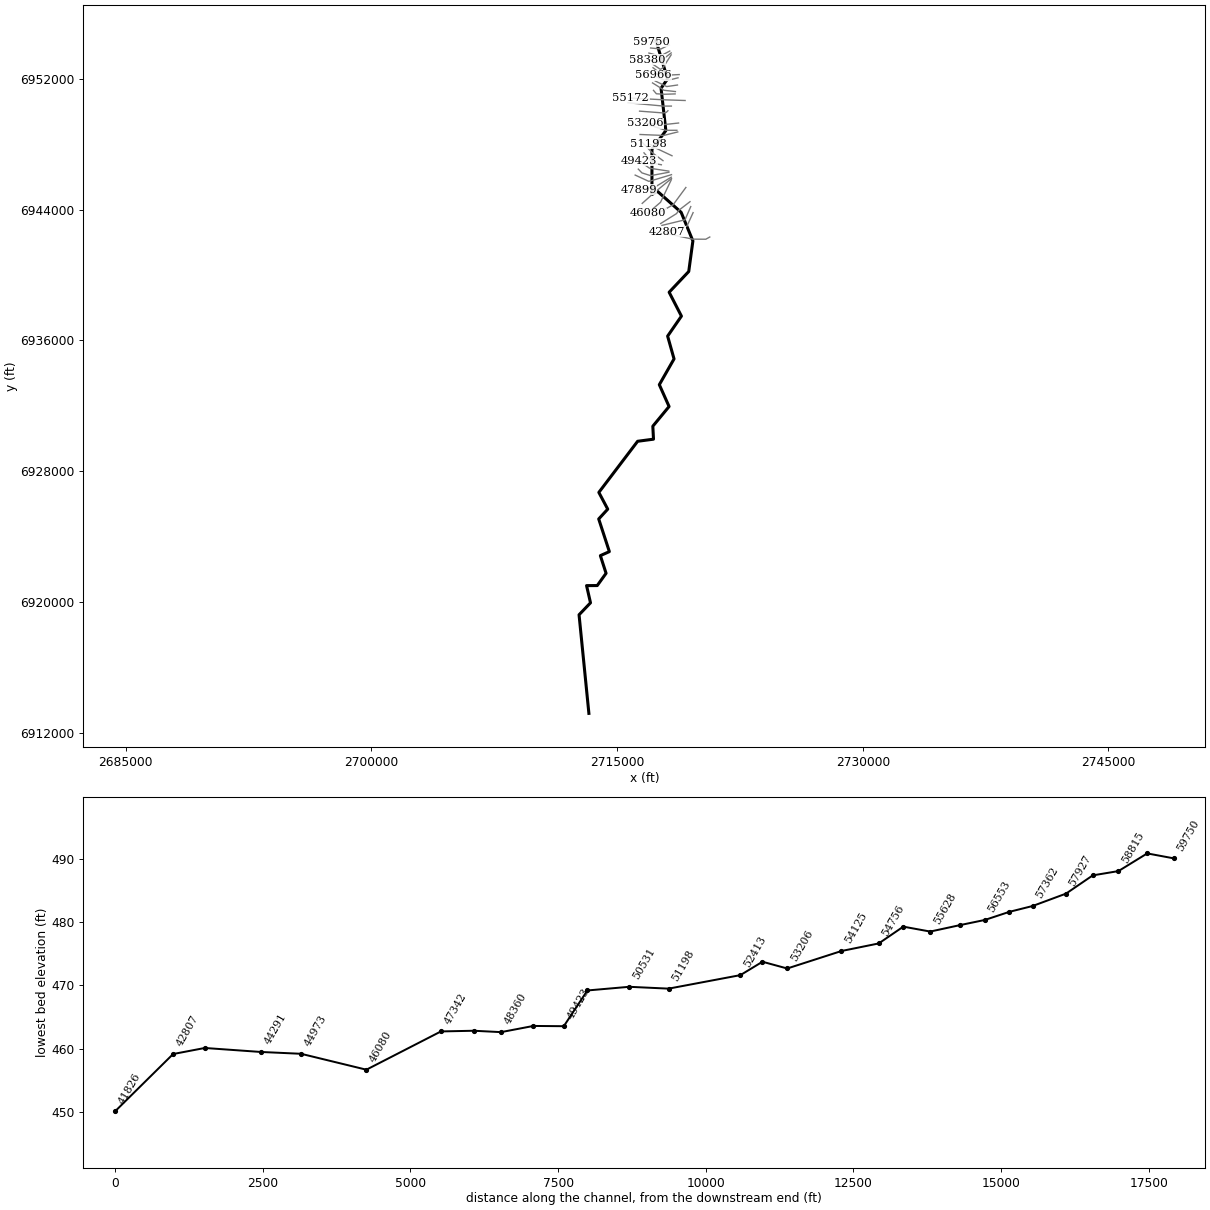
--- Wolf Creek.prj (project) ---

Proj Title=Wolf Creek Base Level Engineering
Current Plan=p01
Default Exp/Contr=0.3,0.1
English Units
Geom File=g01
Flow File=f01
Plan File=p01
Y Axis Title=Elevation
X Axis Title(PF)=Main Channel Distance
X Axis Title(XS)=Station
BEGIN DESCRIPTION:
Wolf Creek
END DESCRIPTION:
DSS Export Rating Curves= 0
DSS Export Rating Curve Sorted= 0
DSS Export Volume Flow Curves= 0
DXF OffsetX= 0
DXF OffsetY= 0
DXF ScaleX= 1
DXF ScaleY= 10

--- Wolf Creek.p01 (plan) ---

Plan Title=Multiple Run
Short Identifier=Multiple
Geom File=g01
Flow File=f01
Subcritical Flow
K Sum by GR= 0
Std Step Tol= 0.01
Critical Tol= 0.01
Num of Std Step Trials= 20
Max Error Tol= 0.3
Flow Tol Ratio= 0.001
Split Flow NTrial= 30
Split Flow Tol= 0.02
Split Flow Ratio= 0.02
Log Output Level= 0
Friction Slope Method= 1
Unsteady Friction Slope Method= 2
Unsteady Bridges Friction Slope Method= 1
Parabolic Critical Depth
Global Vel Dist=  1 , 1 , 1
Global Log Level= 0
CheckData=True
Encroach Param= -1, 0, 0, 0
BEGIN DESCRIPTION:
Multiple Run
END DESCRIPTION:

--- Wolf Creek.f01 (steady flow) ---

Flow Title=Multiple
Program Version=4.10
Number of Profiles= 7
Profile Names=10-year,25-year,50-year,1pct_min,100-year,1pct_plu,500-year
River Rch & RM=Wolf Creek,Reach-1         ,59750
     364     471     555     325     648    1293     882
River Rch & RM=Wolf Creek,Reach-1         ,57362
     558     741     886     527    1051    2097    1474
River Rch & RM=Wolf Creek,Reach-1         ,55172
    1052    1445    1769    1073    2141    4271    3133
River Rch & RM=Wolf Creek,Reach-1         ,53206
    1069    1465    1793    1086    2166    4323    3163
River Rch & RM=Wolf Creek,Reach-1         ,52413
    1193    1646    2022    1229    2452    4892    3604
River Rch & RM=Wolf Creek,Reach-1         ,47899
    1327    1834    2254    1369    2732    5451    4017
River Rch & RM=Wolf Creek,Reach-1         ,41826
    2130    3000    3736    2297    4584    9146    6901
River Rch & RM=Wolf Creek,Reach-1         ,40141
    2265    3182    3955    2424    4837    9651    7240
River Rch & RM=Wolf Creek,Reach-1         ,35093
    3004    4269    5347    3301    6587   13143   10002
River Rch & RM=Wolf Creek,Reach-1         ,15790
    3345    4765    5976    3694    7371   14706   11215
River Rch & RM=Wolf Creek,Reach-1         ,4877
    3358    4777    5987    3697    7376   14718   11202
Boundary for River Rch & Prof#=Wolf Creek,Reach-1         , 1
Up Type= 0
Dn Type= 3
Dn Slope=0.00121
Boundary for River Rch & Prof#=Wolf Creek,Reach-1         , 2
Up Type= 0
Dn Type= 3
Dn Slope=0.00121
Boundary for River Rch & Prof#=Wolf Creek,Reach-1         , 3
Up Type= 0
Dn Type= 3
Dn Slope=0.00121
Boundary for River Rch & Prof#=Wolf Creek,Reach-1         , 4
Up Type= 0
Dn Type= 3
Dn Slope=0.00121
Boundary for River Rch & Prof#=Wolf Creek,Reach-1         , 5
Up Type= 0
Dn Type= 3
Dn Slope=0.00121
Boundary for River Rch & Prof#=Wolf Creek,Reach-1         , 6
Up Type= 0
Dn Type= 3
Dn Slope=0.00121
Boundary for River Rch & Prof#=Wolf Creek,Reach-1         , 7
Up Type= 0
Dn Type= 3
Dn Slope=0.00121
DSS Import GetInterval= 0
DSS Import GetPeak= 0
DSS Import FillOption= 0

--- Wolf Creek.g01 (geometry) ---

Geom Title=Existing Conditions
Program Version=4.10

River Reach=Wolf Creek      ,Reach-1
Reach XY= 30
        2717376.        6954311.      2718076.39      6951981.13
      2717683.18      6951411.34      2717975.07      6948821.48
      2717126.02      6947690.81      2717126.93      6944921.14
      2717467.52      6945108.42      2718909.72      6943828.32
      2719626.39      6942081.12      2719372.87      6940212.62
      2718176.23      6938945.78      2718926.48      6937485.97
       2718083.6      6936264.33      2718475.07      6934871.48
      2717576.51      6933295.79      2718172.26      6931962.56
      2717179.67      6930759.41      2717220.62      6929966.18
      2716252.61      6929838.36      2713883.53      6926714.17
      2714426.21      6925690.94      2713875.59      6925090.86
      2714525.99      6923095.58      2713976.55      6922850.26
      2714324.95      6921771.09      2713786.03      6921021.95
      2713133.74      6921017.55      2713374.05      6919966.89
      2712675.29      6919236.29        2713276.        6913211.

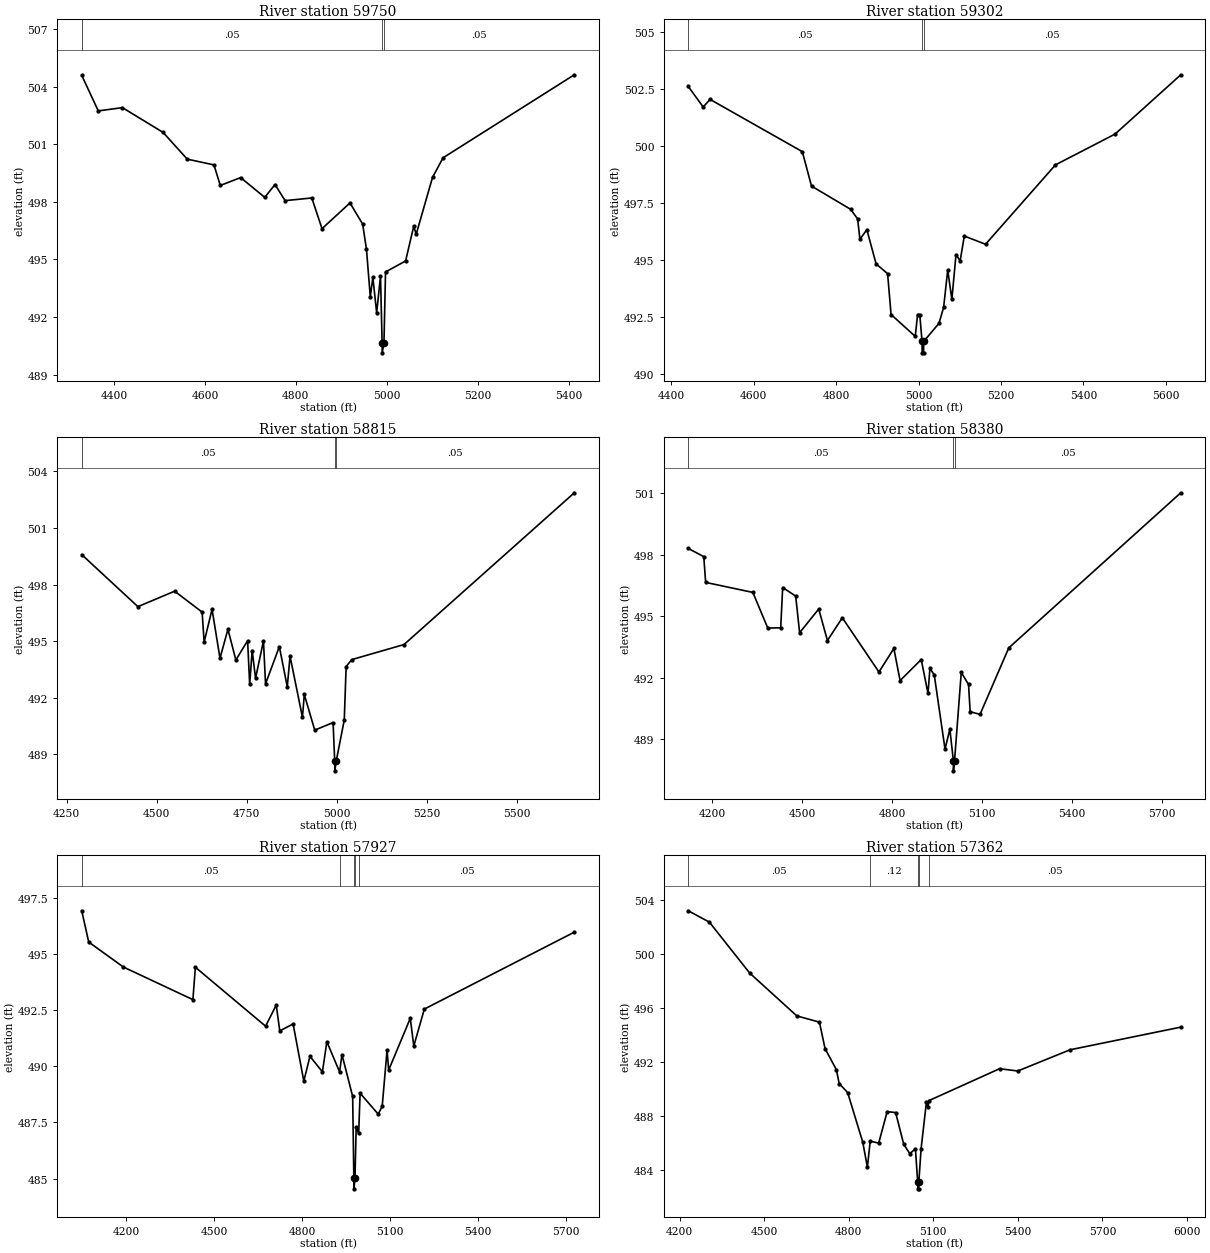
Type RM Length L Ch R = 1 ,59750   ,448,448,448
BEGIN DESCRIPTION:
Wolf Creek 59.0
END DESCRIPTION:
XS GIS Cut Line= 3
      2718076.01      6954461.01        2717476.        6954161.
      2717076.05      6954260.99
#Sta/Elev= 30
  4329.2  504.58  4365.6  502.73  4418.7   502.9  4508.1  501.61  4561.2  500.22
  4619.9  499.92  4633.9  498.85  4678.6  499.26  4731.7  498.23  4754.1   498.9
  4776.4  498.06  4835.1   498.2  4857.5   496.6    4919  497.94  4946.9  496.84
  4955.3  495.52  4963.7  493.06  4969.3  494.07  4977.7  492.22  4986.1  494.14
  4989.7  490.64  4989.9  490.14  4993.7  490.64  4997.2  494.35  5041.3  494.92
  5059.3  496.74  5064.5   496.3  5100.5  499.27  5123.7  500.29  5412.3  504.61
#Mann= 3 ,-1 , 0
  4329.2     .05       0  4989.7     .04       0  4993.7     .05       0
Bank Sta=4989.7,4993.7
XS Rating Curve= 0 ,0
Exp/Cntr=0.3,0.1

Type RM Length L Ch R = 1 ,59302   ,487,487,487
BEGIN DESCRIPTION:
Wolf Creek 58.0
END DESCRIPTION:
XS GIS Cut Line= 3
      2718175.97      6954060.99        2717676.        6953811.
      2717043.44       6953871.2
#Sta/Elev= 30
  4441.5   502.6  4477.8   501.7  4494.6  502.03  4718.2  499.74  4740.5  498.23
  4835.6  497.21  4852.3  496.79  4857.9   495.9  4874.7  496.32  4897.1  494.82
    4925  494.39  4933.4   492.6  4992.1  491.64  4997.7   492.6    5003   492.6
  5008.5  491.42  5008.8  490.92  5012.3  490.92  5012.5  491.42  5049.5  492.21
  5060.8  492.91  5070.8  494.55  5080.8  493.26  5090.9  495.23  5100.9  494.95
    5111  496.04  5162.5  495.68    5332  499.16  5476.5  500.51  5635.9  503.11
#Mann= 3 ,-1 , 0
  4441.5     .05       0  5008.5     .04       0  5012.5     .05       0
Bank Sta=5008.5,5012.5
XS Rating Curve= 0 ,0
Exp/Cntr=0.3,0.1

Type RM Length L Ch R = 1 ,58815   ,435,435,435
BEGIN DESCRIPTION:
Mapping XS 96b306a8
END DESCRIPTION:
XS GIS Cut Line= 4
      2718213.62       6953683.7      2717703.21      6953412.87
      2717578.21      6953388.56       2716940.2      6953561.93
#Sta/Elev= 30
  4292.2  499.59    4448  496.83  4549.9  497.65  4626.1  496.54  4631.7  494.95
  4653.7  496.69  4675.7  494.09  4697.7  495.63  4719.7     494  4752.3  495.02
    4758  492.72    4765   494.5  4774.3  493.03  4796.3  495.01    4802  492.73
  4840.3  494.71  4862.3  492.58    4870   494.2  4904.4  490.96  4909.5  492.17
  4938.5  490.28  4989.4  490.68  4993.9  488.62  4994.2  488.12  4997.9  488.62
  5020.4  490.82  5025.6  493.65  5041.1  494.02  5186.2  494.82  5658.5  502.87
#Mann= 3 ,-1 , 0
  4292.2     .05       0  4993.9     .04       0  4997.9     .05       0
Bank Sta=4993.9,4997.9
XS Rating Curve= 0 ,0
Exp/Cntr=0.3,0.1

Type RM Length L Ch R = 1 ,58380   ,453,453,453
BEGIN DESCRIPTION:
Mapping XS e98f452b
END DESCRIPTION:
XS GIS Cut Line= 4
      2718300.41       6953569.1      2717626.82      6953048.28
      2717512.23      6953003.15      2716860.26       6953159.2
#Sta/Elev= 30
    4119  498.31    4171  497.91  4177.3  496.65  4334.9  496.16  4384.7  494.42
  4427.9  494.43  4434.5   496.4    4478  495.98  4491.1  494.19  4554.9  495.35
  4583.9  493.81  4633.7  494.92    4756  492.27  4805.8  493.42  4826.6  491.85
  4897.2  492.88  4919.9  491.22  4926.2  492.45  4940.7  492.13  4976.7   488.5
  4992.8  489.48  5004.5  487.94  5004.7  487.44  5008.5  487.94  5030.9  492.25
  5055.2  491.66  5060.6  490.33  5093.6   490.2  5189.6  493.45    5764  501.03
#Mann= 3 ,-1 , 0
    4119     .05       0  5004.5     .04       0  5008.5     .05       0
Bank Sta=5004.5,5008.5
XS Rating Curve= 0 ,0
Exp/Cntr=0.3,0.1

Type RM Length L Ch R = 1 ,57927   ,565,565,565
BEGIN DESCRIPTION:
Mapping XS ef3ad36f
END DESCRIPTION:
XS GIS Cut Line= 4
      2718300.41      6953451.04      2717790.01      6952648.98
      2717637.23      6952569.12      2717175.42      6952881.63
#Sta/Elev= 30
    4048  496.91  4071.8  495.52  4190.1  494.41  4427.3  492.96  4435.7   494.4
  4675.3  491.78  4711.7  492.72  4723.7  491.57  4769.2  491.88  4805.7  489.34
  4826.8  490.44  4869.2  489.75  4884.4  491.09  4927.7  489.75    4936  490.51
  4972.4  488.66  4976.4  485.05  4976.6  484.55  4980.4  485.05  4984.4  487.28
  4992.9  487.02  4997.8   488.8  5059.6  487.87  5073.2  488.22  5089.7  490.71
  5095.3  489.83    5169  492.13    5181   490.9  5216.9  492.54  5728.7  495.96
#Mann= 5 ,-1 , 0
    4048     .05       0  4927.7     .12       0  4976.4     .04       0
  4980.4     .12       0  4992.9     .05       0
Bank Sta=4976.4,4980.4
XS Rating Curve= 0 ,0
Exp/Cntr=0.3,0.1

Type RM Length L Ch R = 1 ,57362   ,396,396,396
BEGIN DESCRIPTION:
Mapping XS f58bd24a
END DESCRIPTION:
XS GIS Cut Line= 4
      2718790.96      6952246.72      2718023.63      6952208.53
      2717763.22      6952232.83      2717191.24      6952666.15
#Sta/Elev= 30
  4230.5  503.19  4305.6  502.35  4448.4  498.58  4615.9   495.4    4696  494.94
  4716.1  492.97  4756.1  491.42  4766.1  490.39  4796.2  489.72  4849.8  486.04
  4866.2  484.19  4876.1  486.12  4906.3  485.98  4936.3  488.31  4966.4  488.24
  4995.1  485.89  5016.5   485.2  5036.6  485.55  5044.6  483.09  5044.9  482.59
  5048.4  482.59  5048.6  483.09  5056.7  485.57  5075.5     489  5080.5  488.62
  5084.9  489.13  5335.1  491.49  5399.6  491.32  5584.8  492.89  5977.9  494.57
#Mann= 5 ,-1 , 0
  4230.5     .05       0  4876.1     .12       0  5044.6     .07       0
  5048.6     .12       0  5084.9     .05       0
Bank Sta=5044.6,5048.6
XS Rating Curve= 0 ,0
Exp/Cntr=0.3,0.1

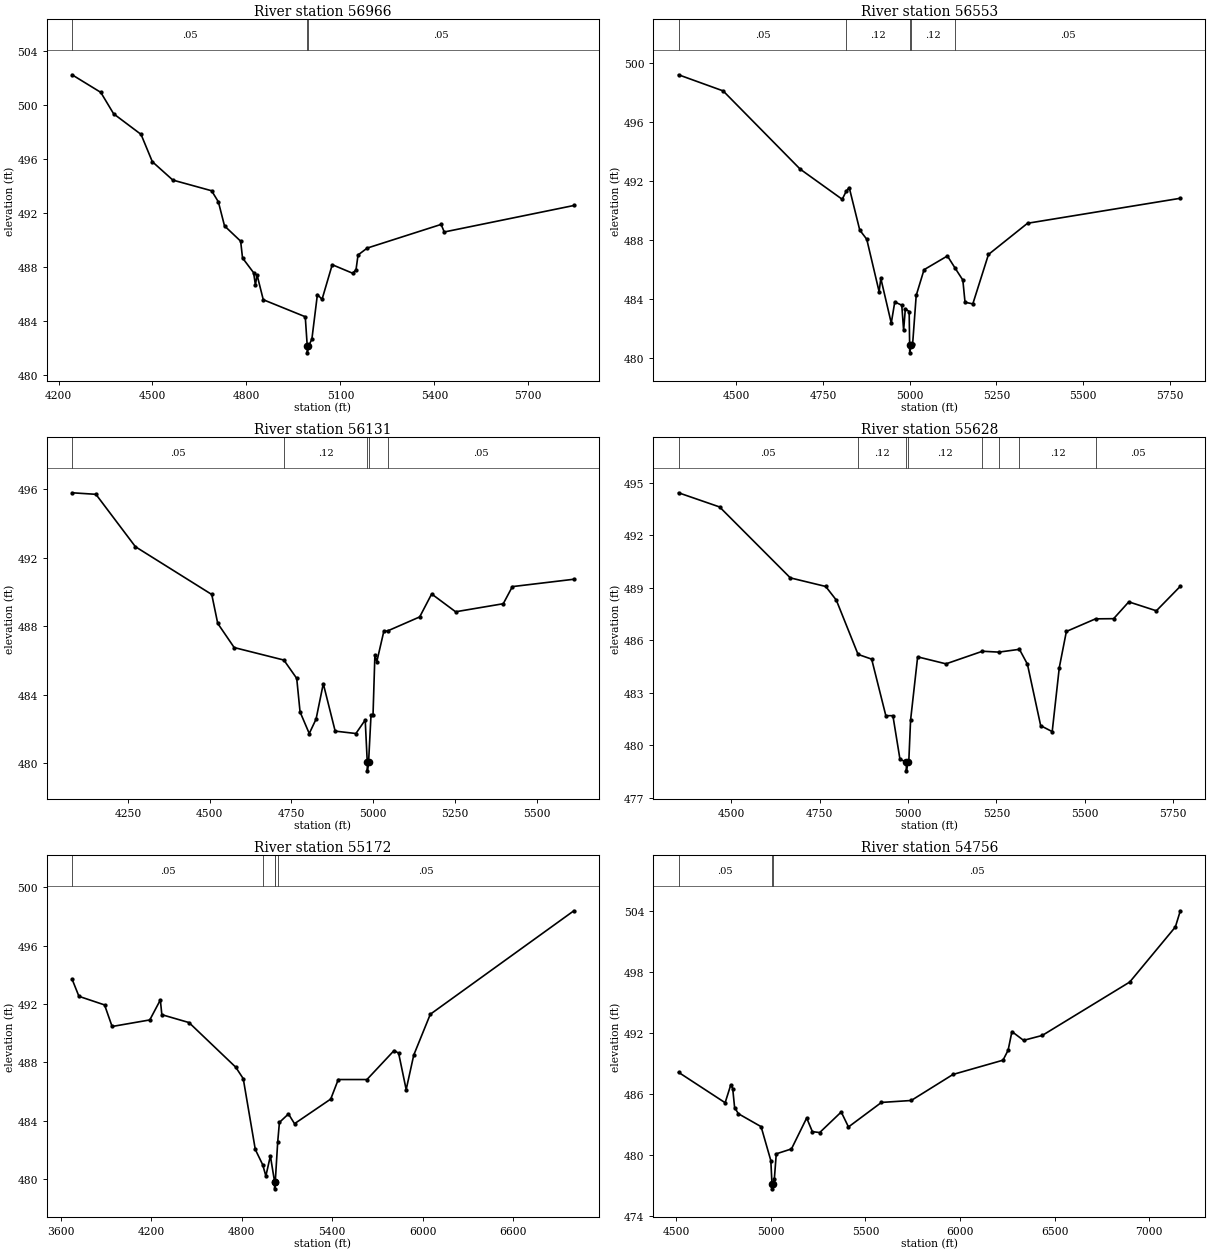
Type RM Length L Ch R = 1 ,56966   ,413,413,413
BEGIN DESCRIPTION:
Mapping XS 56633ec7
END DESCRIPTION:
XS GIS Cut Line= 3
      2718718.03      6952048.79      2717985.44      6951864.78
      2717204.23      6952191.15
#Sta/Elev= 30
  4243.3  502.23  4334.9  500.93  4376.1  499.34  4463.5  497.82  4499.5   495.8
    4565  494.44  4688.8  493.65  4710.4  492.83    4730  491.05  4781.5  489.92
  4787.5  488.68  4822.8  487.59  4828.7  486.68  4833.8  487.43  4853.7  485.59
  4987.8  484.33  4994.1  482.16  4994.4  481.66  4998.1  482.16  5008.9  482.67
  5026.5  485.97  5041.4  485.62  5073.9  488.18  5138.9  487.55  5149.8   487.8
  5156.3   488.9  5185.6  489.41  5421.5  491.16  5431.5   490.6  5845.3  492.56
#Mann= 3 ,-1 , 0
  4243.3     .05       0  4994.1     .04       0  4998.1     .05       0
Bank Sta=4994.1,4998.1
XS Rating Curve= 0 ,0
Exp/Cntr=0.3,0.1

Type RM Length L Ch R = 1 ,56553   ,422,422,422
BEGIN DESCRIPTION:
Mapping XS 59d6ef4b
END DESCRIPTION:
XS GIS Cut Line= 3
      2718683.31      6951607.83      2718027.11      6951514.08
      2717322.23      6951857.84
#Sta/Elev= 30
  4333.3  499.18  4461.9  498.09  4684.1   492.8  4805.4  490.76  4816.9  491.31
  4825.6  491.55  4855.9  488.68  4876.1  488.06  4911.7  484.52  4916.7  485.41
  4946.8  482.39  4956.9  483.82  4977.1   483.6  4982.4  481.91  4987.4  483.36
  4998.4  483.17  4999.8  480.88    5000  480.38  5003.8  480.88  5008.5  481.01
  5018.7  484.26  5041.3     486  5108.7  486.93  5131.1   486.1  5153.2   485.3
  5159.5   483.8    5182  483.69  5227.1  487.03  5339.7  489.14  5780.4  490.83
#Mann= 5 ,-1 , 0
  4333.3     .05       0  4816.9     .12       0  4999.8     .07       0
  5003.8     .12       0  5131.1     .05       0
Bank Sta=4999.8,5003.8
XS Rating Curve= 0 ,0
Exp/Cntr=0.3,0.1

Type RM Length L Ch R = 1 ,56131   ,503,503,503
BEGIN DESCRIPTION:
Mapping XS c9ee77b6
END DESCRIPTION:
XS GIS Cut Line= 4
       2718558.4      6951208.52      2717850.02      6951288.39
      2717686.83      6951409.92       2717162.8      6951736.13
#Sta/Elev= 30
  4079.5   495.8  4152.4  495.71  4273.1  492.65  4506.4  489.86  4524.7  488.17
    4575  486.76  4726.8  486.03  4766.1  484.96  4776.3     483  4804.4  481.74
  4825.2  482.58  4847.3  484.65  4883.6  481.88    4947  481.74  4975.4  482.53
  4981.7  480.06    4982  479.56  4985.7  480.06  4993.2  482.83  4999.3  482.83
    5005  486.32  5010.9  485.94  5032.2   487.7  5044.9  487.74  5141.9  488.55
  5178.5  489.89  5251.7  488.85  5397.3  489.32  5425.2  490.32  5613.1  490.75
#Mann= 5 ,-1 , 0
  4079.5     .05       0  4726.8     .12       0  4981.7     .07       0
  4985.7     .12       0  5044.9     .05       0
Bank Sta=4981.7,4985.7
XS Rating Curve= 0 ,0
Exp/Cntr=0.3,0.1

Type RM Length L Ch R = 1 ,55628   ,456,456,456
BEGIN DESCRIPTION:
Mapping XS 8d39adae
END DESCRIPTION:
XS GIS Cut Line= 4
      2718542.12      6951065.12      2717891.11      6951043.42
      2717396.37      6951073.21      2717220.61       6951281.7
#Sta/Elev= 30
  4350.6  494.42  4466.8  493.61  4666.9  489.56    4767  489.07    4797  488.29
  4858.5  485.19    4897  484.92  4937.1  481.69  4957.1  481.69  4977.1   479.2
    4995  479.04  4995.3  478.54    4999  479.04    5002  479.04  5007.1  481.43
  5027.1  485.05  5107.3  484.65  5210.5  485.37  5256.8  485.32  5315.1  485.48
  5337.7  484.63  5375.2  481.12  5407.8  480.78  5427.9  484.44  5447.9   486.5
  5530.4  487.22  5581.6  487.23  5624.5  488.19  5702.5  487.68  5770.3  489.08
#Mann= 8 ,-1 , 0
  4350.6     .05       0  4858.5     .12       0    4995     .07       0
    4999     .12       0  5210.5      .1       0  5256.8     .05       0
  5315.1     .12       0  5530.4     .05       0
Bank Sta=4995,4999
XS Rating Curve= 0 ,0
Exp/Cntr=0.3,0.1

Type RM Length L Ch R = 1 ,55172   ,416,416,416
BEGIN DESCRIPTION:
Wolf Creek 48.0
END DESCRIPTION:
XS GIS Cut Line= 3
      2719151.56      6950662.22      2717825.48      6950705.78
      2715824.56      6950813.24
#Sta/Elev= 30
  3673.2  493.71  3718.8  492.53  3888.9  491.94  3938.9  490.46    4189  490.91
  4259.1  492.28  4269.1  491.27  4449.2  490.73  4759.3  487.67  4809.4  486.88
  4889.4  482.02  4938.7  480.97  4959.5   480.2  4989.5  481.58  5017.1  479.82
  5017.7  479.32    5022  479.82  5037.9  482.51  5049.5  483.88  5109.6  484.46
  5149.7  483.79    5390  485.48  5440.1  486.82  5630.4  486.82  5810.6  488.81
  5840.7  488.63  5890.8  486.13  5941.1   488.5    6051   491.3  7003.8   498.4
#Mann= 5 ,-1 , 0
  3673.2     .05       0  4938.7     .12       0  5017.1     .07       0
    5022     .12       0  5037.9     .05       0
Bank Sta=5017.1,5022
XS Rating Curve= 0 ,0
Exp/Cntr=0.3,0.1

Type RM Length L Ch R = 1 ,54756   ,631,631,631
BEGIN DESCRIPTION:
Wolf Creek 47.0
END DESCRIPTION:
XS GIS Cut Line= 3
      2718312.34      6950321.49      2717824.64      6950321.52
      2715669.91      6950523.78
#Sta/Elev= 30
  4512.3  488.11  4758.6  485.12  4788.6  486.89  4798.6  486.51  4808.6  484.65
  4828.6  484.04  4948.6  482.77    5000  479.44  5006.1  477.16  5006.8  476.66
  5011.3  477.16  5018.7  477.63  5028.8   480.1  5109.1  480.58  5189.5  483.62
  5219.6  482.28  5258.3  482.19  5372.1  484.21  5410.4  482.74  5584.6  485.15
  5741.9  485.34  5962.9   487.9    6227   489.3  6254.1  490.28  6274.2  492.11
  6335.7  491.25  6434.4  491.73  6896.9  496.98    7138  502.39  7164.2  503.98
#Mann= 3 ,-1 , 0
  4512.3     .05       0  5006.1     .04       0  5011.3     .05       0
Bank Sta=5006.1,5011.3
XS Rating Curve= 0 ,0
Exp/Cntr=0.3,0.1

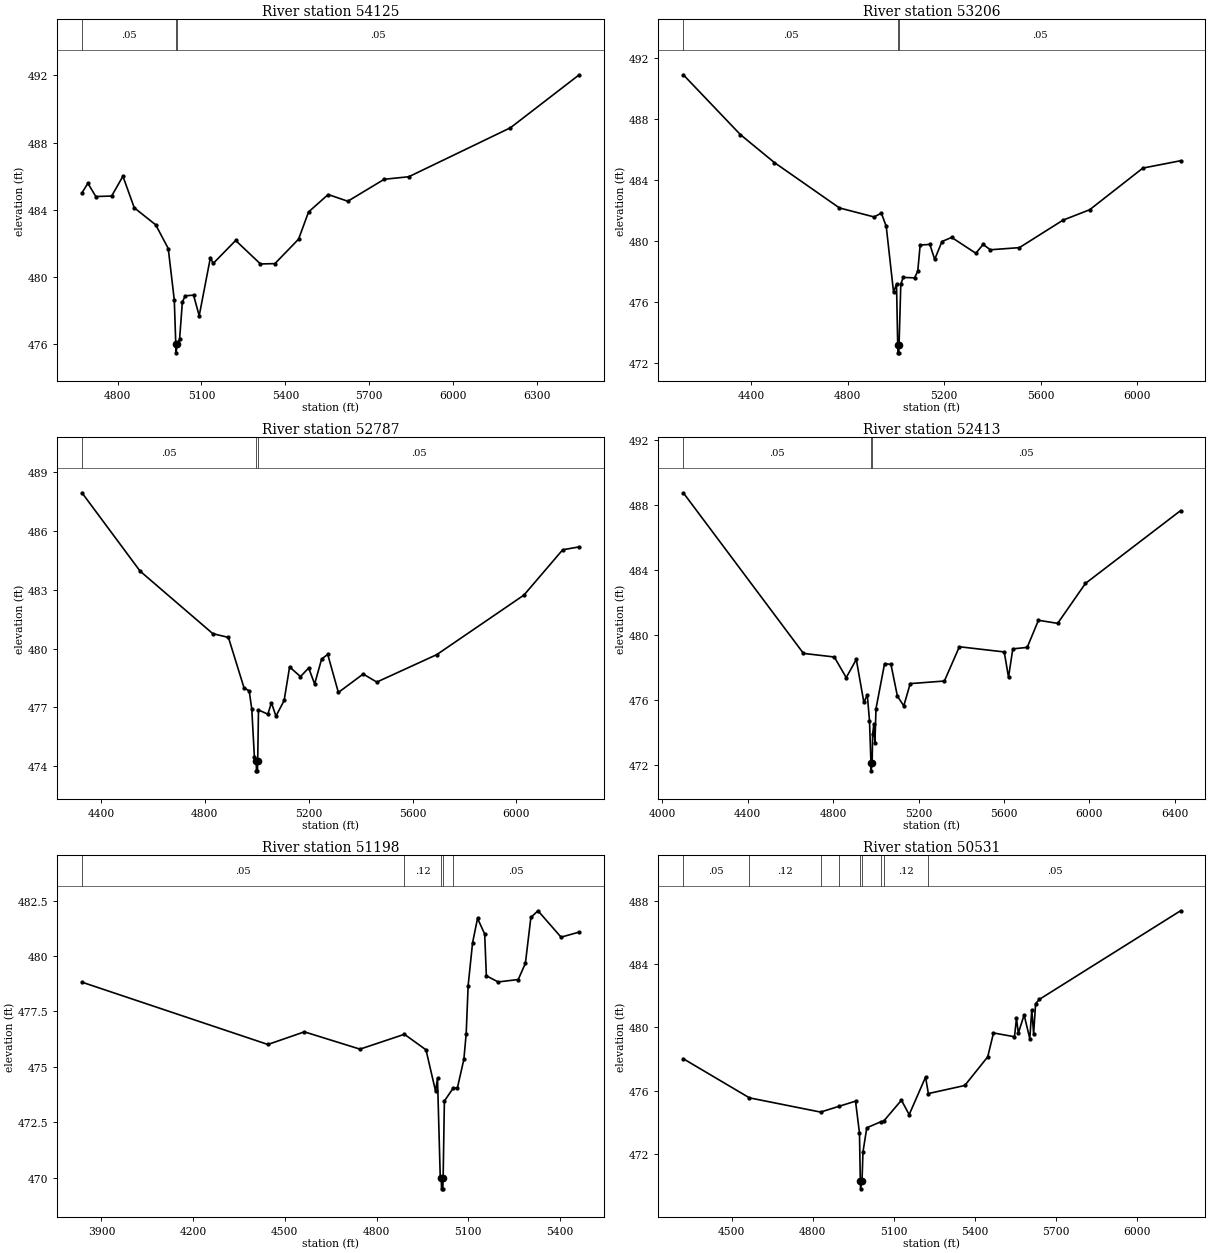
Type RM Length L Ch R = 1 ,54125   ,919,919,919
BEGIN DESCRIPTION:
Mapping XS df7f6603
END DESCRIPTION:
XS GIS Cut Line= 4
      2718100.99      6950035.99        2718001.        6949936.
      2717802.57      6949903.38      2716370.68      6950011.85
#Sta/Elev= 30
  4672.6     485  4693.8  485.57  4722.1  484.78  4778.7  484.81  4819.1  485.99
  4859.6  484.11  4936.5  483.09  4981.2  481.68  5002.8  478.61  5008.2  475.96
  5008.9  475.46  5013.5  475.96  5021.7  476.26  5031.7  478.49  5041.8  478.86
  5071.8   478.9  5091.9  477.67    5132  481.14    5142  480.79  5222.3  482.16
    5311  480.76  5362.7  480.78  5447.4  482.24    5483  483.86  5553.2   484.9
  5623.4   484.5  5753.8  485.81  5841.6  485.96  6205.1  488.88  6451.1  492.04
#Mann= 3 ,-1 , 0
  4672.6     .05       0  5008.2     .04       0  5013.5     .05       0
Bank Sta=5008.2,5013.5
XS Rating Curve= 0 ,0
Exp/Cntr=0.3,0.1

Type RM Length L Ch R = 1 ,53206   ,419,419,419
BEGIN DESCRIPTION:
Mapping XS 119c44b0
END DESCRIPTION:
XS GIS Cut Line= 3
      2718750.97        6949286.      2717876.41      6949191.03
      2716700.46      6949265.35
#Sta/Elev= 30
  4120.3   490.9  4356.7  486.98  4497.5  485.15  4766.4  482.18  4909.9  481.59
  4940.1  481.84  4960.2  480.97  4990.4  476.67  5002.7  477.19  5007.7  473.19
  5008.5  472.69  5012.4  472.69  5013.2  473.19  5020.5  477.19  5030.5  477.63
  5077.2   477.6  5090.6  478.03  5100.6  479.75  5140.7  479.79  5160.7  478.81
  5190.8  479.98  5230.9  480.25  5331.1  479.21  5361.1  479.79    5391  479.44
  5511.4  479.58  5691.8  481.38    5802  482.06  6022.4  484.79  6178.3  485.27
#Mann= 3 ,-1 , 0
  4120.3     .05       0  5007.7     .04       0  5013.2     .05       0
Bank Sta=5007.7,5013.2
XS Rating Curve= 0 ,0
Exp/Cntr=0.3,0.1

Type RM Length L Ch R = 1 ,52787   ,374,374,374
BEGIN DESCRIPTION:
Mapping XS 8e9e5941
END DESCRIPTION:
XS GIS Cut Line= 3
      2718649.99      6948841.57      2717969.41      6948841.57
      2716793.24      6949216.28
#Sta/Elev= 30
  4326.7  487.95  4550.7  483.95  4830.7  480.76  4890.7  480.57  4950.7     478
  4970.7  477.84  4980.7  476.91  4990.7  474.48  4997.9  474.26  4998.7  473.76
  5002.6  473.76  5003.5  474.26  5006.5  476.87  5042.3  476.65  5056.5  477.23
  5073.8  476.55  5105.3  477.35  5126.3  479.06  5168.3  478.57  5199.8  479.01
  5222.8  478.19  5249.7  479.47  5273.2   479.7  5314.2  477.76  5409.7   478.7
  5462.2  478.29  5693.1  479.69  6028.9  482.73    6178  485.04  6241.7  485.19
#Mann= 3 ,-1 , 0
  4326.7     .05       0  4997.9     .04       0  5003.5     .05       0
Bank Sta=4997.9,5003.5
XS Rating Curve= 0 ,0
Exp/Cntr=0.3,0.1

Type RM Length L Ch R = 1 ,52413   ,1215,1215,1215
BEGIN DESCRIPTION:
Mapping XS 3ea2eca1
END DESCRIPTION:
XS GIS Cut Line= 3
      2718702.01      6948740.87      2717840.94       6948525.6
      2716400.98        6948586.
#Sta/Elev= 30
    4098  488.76  4660.8  478.87  4805.1  478.65    4861  477.38  4908.2   478.5
  4943.5  475.86  4959.7  476.31    4970  474.73  4976.8  472.14  4977.6  471.64
  4982.4  472.14  4984.7  473.89  4990.4   474.5  4995.3  473.34  5000.5  475.47
  5040.6  478.24  5070.6  478.19  5100.6  476.24  5130.6  475.64  5160.7  477.01
  5320.8  477.17  5390.9  479.28  5601.1  478.96  5621.1   477.4  5641.1  479.15
  5708.6  479.24  5761.2  480.91  5851.3  480.72  5981.4  483.18  6426.8  487.66
#Mann= 3 ,-1 , 0
    4098     .05       0  4976.8     .04       0  4982.4     .05       0
Bank Sta=4976.8,4982.4
XS Rating Curve= 0 ,0
Exp/Cntr=0.3,0.1

Type RM Length L Ch R = 1 ,51198   ,667,667,667
BEGIN DESCRIPTION:
Mapping XS 924224ee
END DESCRIPTION:
XS GIS Cut Line= 4
        2718351.        6947286.      2717299.47      6947784.01
      2717221.43      6947882.79      2716913.18      6948018.27
#Sta/Elev= 30
  3836.5  478.82  4444.5  476.01  4563.8  476.58  4745.7   475.8    4891  476.47
  4961.5  475.77  4992.8  473.91  4999.2  474.48  5008.1  470.05  5011.4     470
  5012.4   469.5  5016.6   469.5  5017.6     470  5021.7  473.46  5050.4  474.04
  5064.2  474.05  5085.4  475.34    5093   476.5  5099.4  478.67  5113.8  480.59
  5130.1   481.7  5153.5  480.99  5158.9  479.11  5197.4  478.83  5263.2  478.94
  5286.6  479.67  5304.5  481.74  5327.8  482.04  5403.3  480.85  5462.6  481.08
#Mann= 5 ,-1 , 0
  3836.5     .05       0    4891     .12       0  5011.4     .07       0
  5017.6     .12       0  5050.4     .05       0
Bank Sta=5011.4,5017.6
XS Rating Curve= 0 ,0
Exp/Cntr=0.3,0.1

Type RM Length L Ch R = 1 ,50531   ,709,709,709
BEGIN DESCRIPTION:
Mapping XS 89e7422c
END DESCRIPTION:
XS GIS Cut Line= 4
      2717800.97      6946986.02      2717248.06      6947393.65
      2717086.26        6947526.       2716436.4      6948209.65
#Sta/Elev= 30
  4320.8  478.01  4565.3  475.54  4828.6  474.64  4897.6  475.01  4957.8  475.33
  4972.4  473.32  4975.5  470.29  4976.5  469.79  4981.8  470.29  4985.4  472.13
  4999.5  473.65  5050.4  474.02  5061.9  474.07  5127.6  475.39  5156.3  474.48
  5216.8  476.85  5227.2  475.81  5361.8  476.32  5446.7  478.13  5468.1  479.64
  5545.8   479.4  5553.1  480.56    5560  479.63  5581.4  480.78  5602.4  479.28
  5609.7  481.11  5616.6  479.59  5623.8  481.49  5637.6  481.76    6160  487.36
#Mann= 9 ,-1 , 0
  4320.8     .05       0  4565.3     .12       0  4828.6     .05       0
  4897.6     .12       0  4975.5     .07       0  4981.8     .12       0
  5050.4     .05       0  5061.9     .12       0  5227.2     .05       0
Bank Sta=4975.5,4981.8
XS Rating Curve= 0 ,0
Exp/Cntr=0.3,0.1

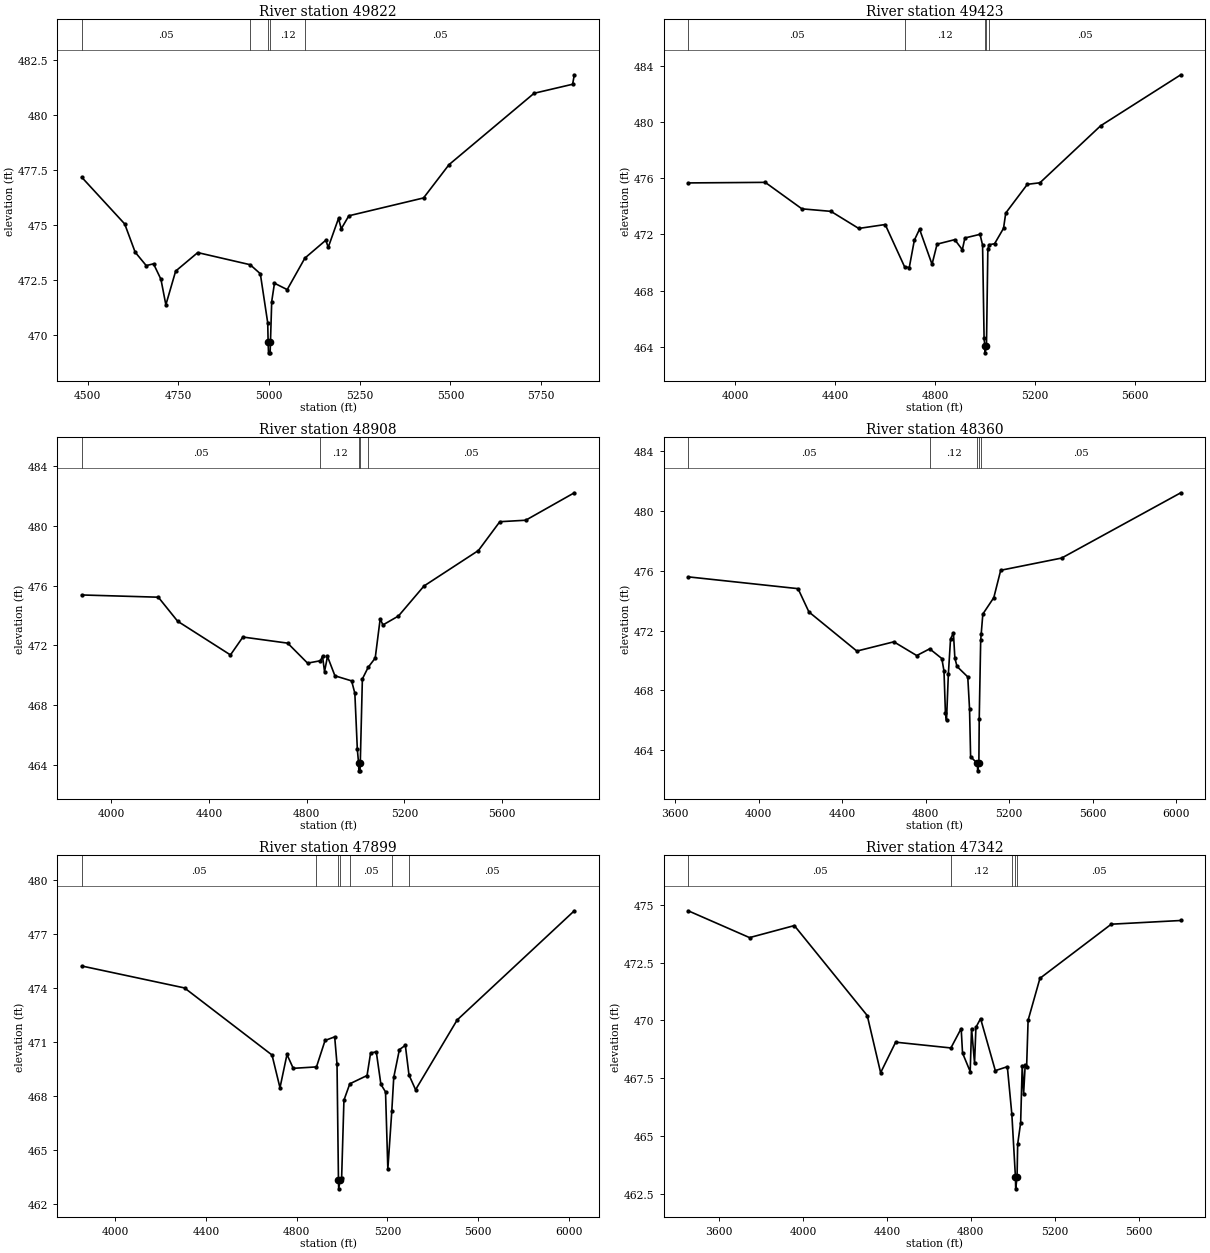
Type RM Length L Ch R = 1 ,49822   ,399,399,399
BEGIN DESCRIPTION:
Mapping XS 7cd58de0
END DESCRIPTION:
XS GIS Cut Line= 3
      2717701.04      6946735.99      2717195.97      6946825.08
      2716640.72      6947462.75
#Sta/Elev= 30
  4483.3  477.18  4601.8  475.06  4630.6  473.78  4661.1  473.17  4681.3  473.25
  4701.7  472.55  4715.3  471.39  4742.3  472.92  4803.2  473.76  4947.7  473.21
  4975.8   472.8  4996.2  470.57  4997.3  469.71  4998.4  469.21  5002.8  469.21
  5003.8  469.71  5007.2  471.54  5014.8  472.37  5049.9  472.08  5098.7  473.51
  5156.3  474.32  5163.1     474  5191.4  475.31    5199  474.84  5219.9  475.43
  5425.9  476.24  5496.1  477.75  5730.7  480.99    5837   481.4  5841.7  481.83
#Mann= 5 ,-1 , 0
  4483.3     .05       0  4947.7     .12       0  4997.3     .07       0
  5003.8     .12       0  5098.7     .05       0
Bank Sta=4997.3,5003.8
XS Rating Curve= 0 ,0
Exp/Cntr=0.3,0.1

Type RM Length L Ch R = 1 ,49423   ,515,515,515
BEGIN DESCRIPTION:
Mapping XS c8264cec
END DESCRIPTION:
XS GIS Cut Line= 3
       2718150.8      6946347.65      2716978.96       6946525.6
      2716332.22      6946972.67
#Sta/Elev= 30
    3811  475.68  4119.3  475.72  4266.1  473.83  4382.3  473.65  4493.5  472.43
  4599.5  472.71  4677.1  469.69  4695.8  469.64  4716.1  471.59  4736.9  472.38
  4786.9  469.87  4807.1  471.31  4877.9  471.63  4908.2  470.91  4918.4  471.75
    4979  472.01  4989.2  471.24  4995.2  464.63  4998.1  464.05  4999.2  463.55
  5004.8  464.05  5010.3  470.95  5015.8  471.27  5037.3  471.34  5073.1  472.44
  5081.9  473.53  5168.4  475.58  5218.7  475.69  5461.8  479.76  5782.5   483.4
#Mann= 5 ,-1 , 0
    3811     .05       0  4677.1     .12       0  4998.1     .07       0
  5004.8     .12       0  5015.8     .05       0
Bank Sta=4998.1,5004.8
XS Rating Curve= 0 ,0
Exp/Cntr=0.3,0.1

Type RM Length L Ch R = 1 ,48908   ,548,548,548
BEGIN DESCRIPTION:
Mapping XS 0687df95
END DESCRIPTION:
XS GIS Cut Line= 4
      2718163.85       6946278.2      2717044.06      6946069.87
      2716514.55      6946239.14      2716293.23      6946469.14
#Sta/Elev= 30
  3880.3  475.38  4193.4  475.23  4272.4  473.62  4488.4  471.36  4539.3  472.56
  4722.4  472.15  4803.7  470.81  4856.1  470.97  4864.8  471.27  4873.1  470.24
  4885.1  471.26  4915.6  469.96  4983.8  469.62    4997  468.79  5007.2  465.03
  5012.4  464.09  5013.4  463.59  5018.1  463.59  5019.2  464.09  5027.8  469.75
  5051.5  470.53  5080.3  471.15  5100.6  473.78  5111.8  473.37  5175.4  473.97
  5279.7  475.98  5502.3  478.36  5589.7  480.29  5695.7  480.39  5894.4  482.23
#Mann= 5 ,-1 , 0
  3880.3     .05       0  4856.1     .12       0  5012.4     .07       0
  5019.2     .12       0  5051.5     .05       0
Bank Sta=5012.4,5019.2
XS Rating Curve= 0 ,0
Exp/Cntr=0.3,0.1

Type RM Length L Ch R = 1 ,48360   ,461,461,461
BEGIN DESCRIPTION:
Mapping XS b37a4ab9
END DESCRIPTION:
XS GIS Cut Line= 4
      2718320.12      6946130.64      2717104.83      6945766.05
      2716931.22      6945722.65      2716102.23      6946104.59
#Sta/Elev= 30
  3661.8   475.6  4188.1  474.81  4240.3  473.25    4470  470.63  4647.3  471.25
  4756.9  470.33    4819  470.78  4877.2  470.13  4887.6  469.29  4894.4  466.48
  4899.6  465.99  4908.5  469.08  4918.9  471.43  4932.7  471.86  4939.7  470.16
    4950   469.6  5001.5   468.9    5010  466.76  5015.1  463.55  5047.8  463.11
  5048.9  462.61  5054.7  463.11  5056.4  466.06  5063.4  471.35    5066  471.79
  5073.7  473.11  5126.3  474.21  5159.3  476.04  5451.6  476.86  6022.3  481.23
#Mann= 5 ,-1 , 0
  3661.8     .05       0    4819     .12       0  5047.8     .07       0
  5054.7     .12       0    5066     .05       0
Bank Sta=5047.8,5054.7
XS Rating Curve= 0 ,0
Exp/Cntr=0.3,0.1

Type RM Length L Ch R = 1 ,47899   ,557,557,557
BEGIN DESCRIPTION:
Mapping XS d66fff02
END DESCRIPTION:
XS GIS Cut Line= 3
      2718303.59      6945976.98      2717374.79      6945412.75
      2716309.07      6945200.47
#Sta/Elev= 30
  3851.7  475.22  4305.2     474  4691.3  470.27  4726.4  468.45  4757.3   470.3
  4784.9  469.53  4887.5  469.61  4925.3  471.08  4967.8  471.28  4978.1  469.75
  4984.4  463.33  4985.5  462.83    4992  463.33  4998.4  463.42  5008.6  467.76
  5034.5  468.67  5110.6  469.13  5126.2  470.38  5151.3  470.45  5171.7  468.64
  5192.1  468.22  5202.3  463.93  5219.7  467.14  5228.4  469.03  5253.3  470.57
  5279.5  470.81  5295.6  469.16  5324.7  468.34  5508.2  472.22  6025.1  478.29
#Mann= 7 ,-1 , 0
  3851.7     .05       0  4887.5     .12       0  4984.4     .07       0
    4992     .12       0  5034.5     .05       0  5219.7     .12       0
  5295.6     .05       0
Bank Sta=4984.4,4992
XS Rating Curve= 0 ,0
Exp/Cntr=0.3,0.1

Type RM Length L Ch R = 1 ,47342   ,1262,1262,1262
BEGIN DESCRIPTION:
Mapping XS b1ef6d16
END DESCRIPTION:
XS GIS Cut Line= 3
        2718321.      6945898.89      2717144.76       6944922.3
      2716533.11      6944375.72
#Sta/Elev= 30
  3452.2  474.74  3744.8  473.58  3958.4   474.1  4306.1  470.21  4369.9  467.74
  4441.5  469.06    4705  468.81    4754  469.65  4760.5  468.59    4797  467.79
  4803.5  469.65  4817.8  468.15  4824.3   469.7  4846.5  470.08  4916.8  467.83
  4974.1     468  4995.7  465.94  5012.8  463.22    5014  462.72  5020.5  463.22
  5023.4  464.65  5037.6  465.58  5045.1  468.05  5051.8  466.83  5059.3  468.08
    5066  467.97  5073.2  470.01  5129.6  471.82  5469.8  474.16  5801.3  474.32
#Mann= 5 ,-1 , 0
  3452.2     .05       0    4705     .12       0  4995.7     .05       0
  5012.8     .04       0  5020.5     .05       0
Bank Sta=5012.8,5020.5
XS Rating Curve= 0 ,0
Exp/Cntr=0.3,0.1

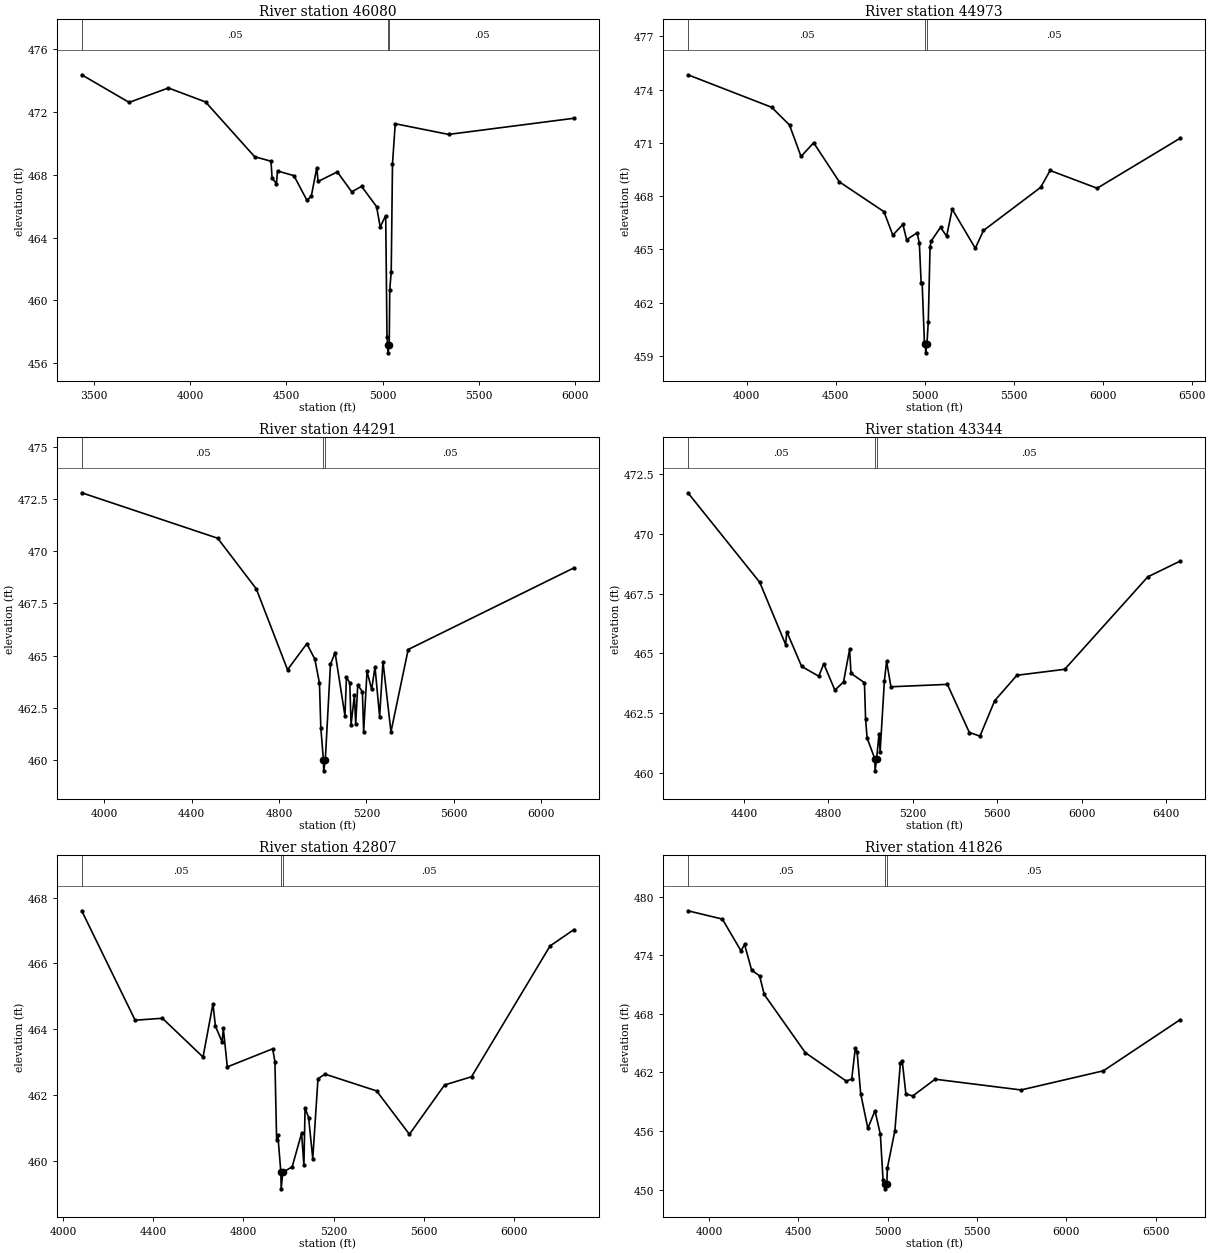
Type RM Length L Ch R = 1 ,46080   ,1107,1107,1107
BEGIN DESCRIPTION:
Mapping XS fdbcc9bb
END DESCRIPTION:
XS GIS Cut Line= 3
      2718307.96      6945816.41      2717648.23      6944440.53
      2716867.01      6943772.15
#Sta/Elev= 30
  3438.7  474.38  3684.6  472.62  3888.3  473.54  4080.8  472.65  4335.6  469.16
  4420.6  468.87  4426.2  467.79  4448.8  467.45  4454.4  468.25  4539.5  467.95
  4607.4  466.37  4630.1  466.67  4658.3  468.47  4664.6  467.58  4764.4  468.19
  4839.5  466.92  4890.4  467.27  4968.1  465.98  4987.1  464.68  5015.6  465.41
  5022.2  457.68    5026  457.16  5027.2  456.66  5033.9  457.16  5036.5  460.67
  5044.2  461.83  5050.8  468.71    5065  471.26  5341.6  470.58  5992.7  471.61
#Mann= 3 ,-1 , 0
  3438.7     .05       0    5026     .04       0  5033.9     .05       0
Bank Sta=5026,5033.9
XS Rating Curve= 0 ,0
Exp/Cntr=0.3,0.1

Type RM Length L Ch R = 1 ,44973   ,682,682,682
BEGIN DESCRIPTION:
Mapping XS f5d0d0c5
END DESCRIPTION:
XS GIS Cut Line= 3
      2719197.72      6945347.67       2718420.8      6944292.96
      2717153.41       6943576.8
#Sta/Elev= 30
  3670.5  474.84  4140.8  473.01  4241.1  472.01  4305.8  470.24  4376.8  471.01
    4521  468.81  4771.7  467.13  4821.4  465.81  4878.1  466.41    4899  465.55
  4957.6  465.94  4970.5  465.36  4980.5  463.14  4986.1  463.14  4998.9  459.77
  5004.8  459.68    5006  459.18  5013.1  459.68  5020.6  460.92  5030.7  465.15
  5036.5  465.47  5089.4  466.25  5123.8  465.75  5154.9  467.27  5284.8  465.07
  5330.6  466.07  5652.2   468.5    5705  469.45  5969.2  468.45  6436.2  471.27
#Mann= 3 ,-1 , 0
  3670.5     .05       0  5004.8     .05       0  5013.1     .05       0
Bank Sta=5004.8,5013.1
XS Rating Curve= 0 ,0
Exp/Cntr=0.3,0.1

Type RM Length L Ch R = 1 ,44291   ,947,947,947
BEGIN DESCRIPTION:
Mapping XS b77d0997
END DESCRIPTION:
XS GIS Cut Line= 4
      2719449.43      6944479.58      2718750.66       6943941.4
      2718633.47      6943754.77      2717656.95      6943142.81
#Sta/Elev= 30
  3896.1  472.81  4518.7  470.63  4695.6   468.2  4838.7  464.32    4927  465.57
  4963.6  464.83  4984.8  463.68  4991.1  461.54  5003.1  459.97  5004.3  459.47
  5011.5  459.97  5035.3  464.58  5056.5  465.14  5101.7   462.1  5108.4  463.95
  5123.7   463.7  5129.6  461.68  5144.9  463.09  5150.8  461.72  5160.2  463.59
  5181.4  463.27  5187.3  461.35  5202.7  464.24  5223.9  463.38  5239.2  464.45
  5260.4  462.07  5275.7  464.71  5312.3  461.34  5391.2  465.29  6150.9  469.21
#Mann= 3 ,-1 , 0
  3896.1     .05       0  5003.1     .04       0  5011.5     .05       0
Bank Sta=5003.1,5011.5
XS Rating Curve= 0 ,0
Exp/Cntr=0.3,0.1

Type RM Length L Ch R = 1 ,43344   ,537,537,537
BEGIN DESCRIPTION:
Mapping XS c01eef4e
END DESCRIPTION:
XS GIS Cut Line= 3
      2719496.32      6944179.24      2719144.76      6943371.95
      2717734.14      6943029.07
#Sta/Elev= 30
  4134.2  471.71  4474.5  467.97  4597.1  465.37  4602.5  465.91  4672.8  464.46
    4754  464.05  4777.5  464.57  4830.3  463.47  4871.2  463.81  4900.1  465.17
  4906.7  464.17  4970.3  463.78  4975.8  462.25    4983  461.47  5019.5   460.6
  5020.8   460.1  5027.9   460.6  5039.5  461.65  5044.7   460.9  5064.9  463.86
  5075.2  464.67  5095.8  463.61  5363.3  463.71  5467.3   461.7  5517.7  461.55
  5587.4  463.03  5692.6  464.09  5919.1  464.34  6312.6   468.2  6466.4  468.86
#Mann= 3 ,-1 , 0
  4134.2     .05       0  5019.5     .04       0  5027.9     .05       0
Bank Sta=5019.5,5027.9
XS Rating Curve= 0 ,0
Exp/Cntr=0.3,0.1

Type RM Length L Ch R = 1 ,42807   ,981,981,981
BEGIN DESCRIPTION:
Mapping XS 162acbf7
END DESCRIPTION:
XS GIS Cut Line= 3
      2719639.55      6943810.33      2719266.29      6942990.01
      2718033.61      6942642.78
#Sta/Elev= 30
  4083.1   467.6  4319.8  464.27  4440.6  464.33  4620.7  463.15  4664.7  464.77
  4675.6  464.09  4705.2  463.61  4710.7  464.02  4728.3  462.85  4929.3   463.4
  4939.3  463.01  4946.8  460.64  4952.3  460.77  4965.7  459.64  4966.9  459.14
  4974.1  459.64  5015.8  459.81  5057.4  460.83  5067.7  459.86  5072.9   461.6
  5088.5  461.31    5107  460.06  5130.1  462.49  5161.3  462.63  5389.8  462.12
  5535.3   460.8  5691.1   462.3  5810.6  462.55  6158.6  466.53    6265  467.03
#Mann= 3 ,-1 , 0
  4083.1     .05       0  4965.7     .04       0  4974.1     .05       0
Bank Sta=4965.7,4974.1
XS Rating Curve= 0 ,0
Exp/Cntr=0.3,0.1

Type RM Length L Ch R = 1 ,41826   ,699,699,699
BEGIN DESCRIPTION:
Mapping XS 436ca8de
END DESCRIPTION:
XS GIS Cut Line= 4
      2720657.54      6942320.98      2720414.73      6942185.28
      2719600.49       6942190.1      2717975.45      6942544.27
#Sta/Elev= 30
  3882.5  478.54  4075.2  477.69  4179.4  474.44  4199.4  475.09  4239.4  472.45
  4283.6  471.88  4309.4  469.98  4539.4  464.02  4769.4   461.1  4799.4  461.33
  4819.4  464.51  4829.4  464.09  4849.4  459.83  4889.4  456.28  4929.4  458.07
  4959.4  455.67  4974.7  450.94  4983.7  450.58  4985.4  450.08  4995.7  450.58
  4998.7   452.2  5040.9  456.05  5071.6  462.96  5081.9   463.2  5102.3  459.79
  5140.8  459.59  5266.1   461.3  5747.1   460.2  6207.7  462.16  6638.1   467.4
#Mann= 3 ,-1 , 0
  3882.5     .05       0  4983.7     .04       0  4995.7     .05       0
Bank Sta=4983.7,4995.7
XS Rating Curve= 0 ,0
Exp/Cntr=0.3,0.1