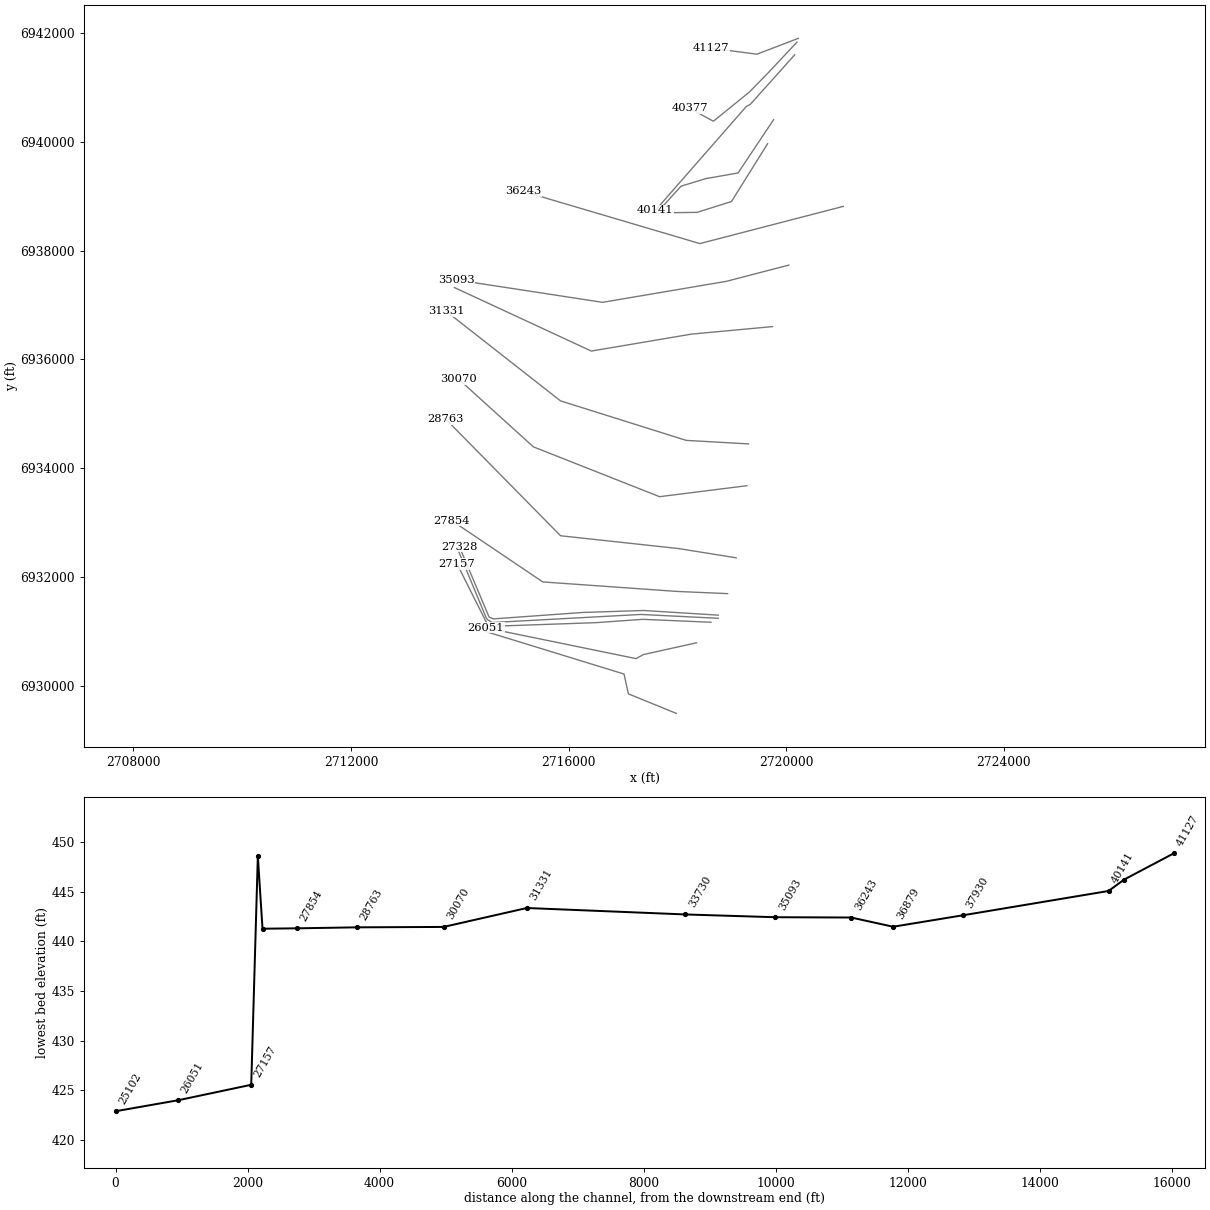
HEC-RAS study Wolf Creek.prj: Wolf Creek Base Level Engineering

--- Wolf Creek.g01 (geometry) --- (continued)

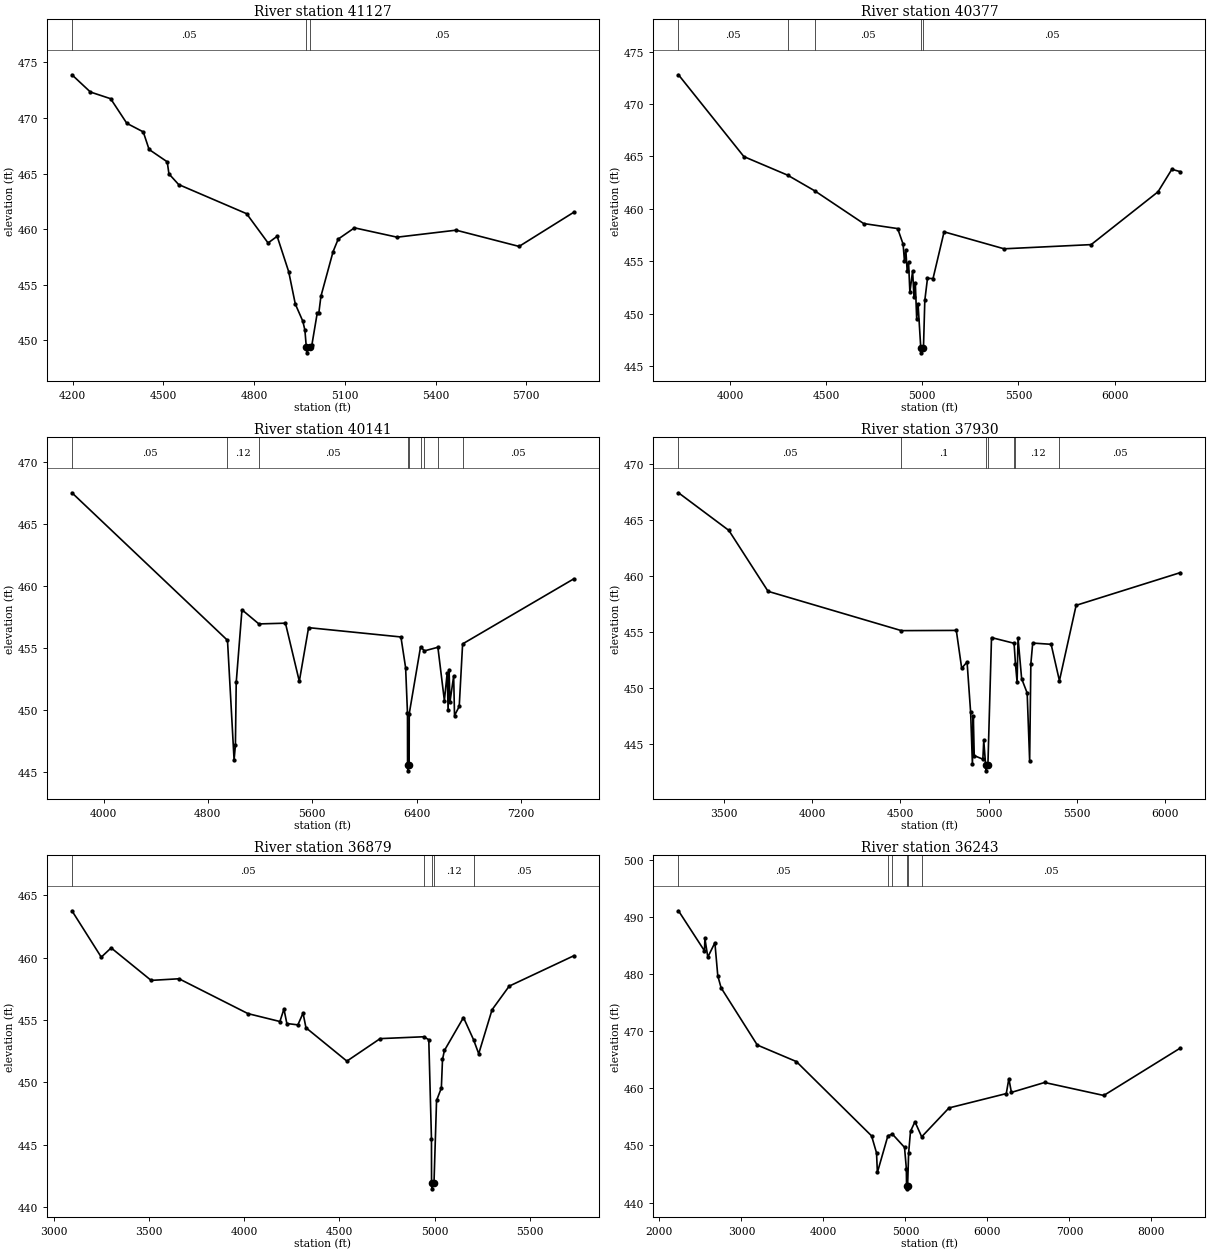
Type RM Length L Ch R = 1 ,41127   ,750,750,750
BEGIN DESCRIPTION:
Mapping XS d9cb04f7
END DESCRIPTION:
XS GIS Cut Line= 3
      2720225.48      6941908.84      2719465.07      6941617.18
       2718626.5      6941726.56
#Sta/Elev= 30
  4197.3  473.87  4258.4  472.32  4325.3  471.72  4378.8  469.51  4433.2  468.74
  4452.5  467.16  4512.5  466.05  4518.1  464.97  4550.2  464.01  4775.1  461.39
  4846.1  458.76  4876.1  459.36  4914.3  456.18  4936.2  453.27  4960.9  451.74
  4967.9  450.93  4972.6  449.39  4974.2  448.89  4984.6  449.39  4990.9  449.58
  5008.5  452.43  5013.8  452.43  5020.9  453.97  5061.2  457.99  5078.1  459.11
  5131.8  460.12    5273  459.28  5468.1  459.91  5676.4  458.45  5857.4  461.52
#Mann= 3 ,-1 , 0
  4197.3     .05       0  4972.6     .05       0  4984.6     .05       0
Bank Sta=4972.6,4984.6
XS Rating Curve= 0 ,0
Exp/Cntr=0.3,0.1

Type RM Length L Ch R = 1 ,40377   ,236,236,236
BEGIN DESCRIPTION:
Mapping XS 5c304ce0
END DESCRIPTION:
XS GIS Cut Line= 5
      2720200.28      6941837.63       2719670.8      6941273.43
      2719323.58      6940917.53      2718663.85      6940383.67
      2718234.15      6940618.06
#Sta/Elev= 30
  3732.3  472.79  4072.4  464.98  4299.6  463.21  4440.1  461.72    4695  458.59
  4871.9  458.11  4900.2  456.62  4907.2     455  4914.3  456.05  4921.3  454.07
  4928.5  454.91  4935.4  452.03  4949.6  454.07  4956.6  451.61  4963.7   452.9
  4970.7  449.52  4977.9  450.92  4991.9  446.75  4993.6  446.25    5004  446.75
  5006.1  446.76    5013  451.26  5026.9  453.36  5055.7  453.34  5113.2   457.8
  5425.1  456.18  5877.8  456.58  6225.4  461.62  6297.4  463.77  6341.4  463.54
#Mann= 5 ,-1 , 0
  3732.3     .05       0  4299.6    .075       0  4440.1     .05       0
  4991.9     .05       0    5004     .05       0
Bank Sta=4991.9,5004
XS Rating Curve= 0 ,0
Exp/Cntr=0.3,0.1

Type RM Length L Ch R = 1 ,40141   ,2211,2211,2211
BEGIN DESCRIPTION:
Mapping XS edf0b735
END DESCRIPTION:
XS GIS Cut Line= 4
      2720158.62      6941604.71      2719342.67      6940693.28
      2719268.89      6940654.22      2717595.74      6938741.14
#Sta/Elev= 30
  3757.8  467.49  4950.6  455.61  5001.1  445.98  5011.3  447.17  5017.5  452.22
  5061.5  458.07  5191.2  456.93    5395  456.99  5501.3  452.31  5572.4  456.63
  6280.5  455.88  6316.6  453.39  6330.8  449.73  6331.4   445.6  6333.1   445.1
  6343.5   445.6  6344.2   449.7  6431.1  455.09  6460.7  454.76  6563.9  455.05
  6613.7  450.76  6635.5  453.01  6642.1     450  6649.7  453.25  6656.4  450.64
  6684.9  452.73  6691.5  449.55  6727.6  450.29  6753.5  455.32  7606.1  460.56
#Mann= 9 ,-1 , 0
  3757.8     .05       0  4950.6     .12       0  5191.2     .05       0
  6331.4     .07       0  6343.5     .05       0  6431.1     .12       0
  6460.7     .05       0  6563.9     .12       0  6753.5     .05       0
Bank Sta=6331.4,6343.5
XS Rating Curve= 0 ,0
Exp/Cntr=0.3,0.1

Type RM Length L Ch R = 1 ,37930   ,1051,1051,1051
BEGIN DESCRIPTION:
Mapping XS 9e7cd570
END DESCRIPTION:
XS GIS Cut Line= 5
      2719771.04      6940411.12      2719118.25      6939431.94
      2718527.98      6939327.77      2718069.64      6939188.88
      2717673.83      6938751.41
#Sta/Elev= 30
  3241.3  467.47  3526.9  464.11  3749.2  458.67  4505.1  455.16  4816.4  455.18
  4846.9   451.8  4877.4  452.36  4897.7  447.85  4907.7  443.24  4912.8  447.55
    4918     444  4966.9  443.68    4972  445.35  4982.7  443.14  4984.5  442.64
  4995.5  443.14    5016  454.54  5143.9  454.03  5151.8  452.17  5161.1  450.55
  5166.3  454.51  5186.8  450.87  5218.1  449.59  5232.2  443.52    5239  452.19
  5249.5  454.05    5354  453.94    5401  450.69  5495.7  457.42  6086.4  460.34
#Mann= 7 ,-1 , 0
  3241.3     .05       0  4505.1      .1       0  4982.7     .07       0
  4995.5      .1       0  5143.9      .1       0  5151.8     .12       0
    5401     .05       0
Bank Sta=4982.7,4995.5
XS Rating Curve= 0 ,0
Exp/Cntr=0.3,0.1

Type RM Length L Ch R = 1 ,36879   ,636,636,636
BEGIN DESCRIPTION:
Mapping XS 9a813fde
END DESCRIPTION:
XS GIS Cut Line= 4
       2719660.8      6939969.28      2718996.73      6938905.89
      2718363.04      6938706.24       2717646.9      6938697.56
#Sta/Elev= 30
  3096.4  463.74  3250.3  460.03  3302.2  460.77  3512.1  458.17  3658.4   458.3
  4020.5  455.51    4188  454.88  4209.2  455.88  4224.5  454.72  4282.3  454.61
  4309.5  455.55  4324.8  454.38  4539.6  451.71  4714.2  453.51  4944.1  453.66
  4969.5  453.42  4983.6  445.47    4984  441.99  4985.8  441.49  4996.9  441.99
  5010.3  448.56  5035.5  449.56  5041.5  451.84  5051.5  452.56  5151.6   455.2
  5204.3  453.43  5231.6   452.3  5301.6  455.82  5391.6  457.71  5730.7  460.14
#Mann= 5 ,-1 , 0
  3096.4     .05       0  4944.1     .12       0    4984     .07       0
  4996.9     .12       0  5204.3     .05       0
Bank Sta=4984,4996.9
XS Rating Curve= 0 ,0
Exp/Cntr=0.3,0.1

Type RM Length L Ch R = 1 ,36243   ,1150,1150,1150
BEGIN DESCRIPTION:
Mapping XS d82d0a5d
END DESCRIPTION:
XS GIS Cut Line= 3
       2721053.7      6938816.78       2718415.7      6938132.01
      2715160.81      6939094.34
#Sta/Elev= 30
  2232.7  491.05  2549.8  484.04    2555  486.21  2590.4  482.94  2676.7  485.46
  2712.1  479.67  2752.6  477.57  3193.7  467.57  3670.1  464.68  4587.5  451.68
  4647.9   448.7  4658.2  445.28  4786.4   451.7  4841.4  451.99  4989.1  449.67
  5011.3  445.97  5013.9  442.92  5015.8  442.42  5026.8  442.92  5039.4  448.74
  5062.1  452.48  5116.4  454.15  5198.4  451.52  5531.3  456.57    6230  459.08
  6261.3  461.68  6292.6  459.29  6697.3  461.02  7418.8  458.75  8352.3  467.04
#Mann= 6 ,-1 , 0
  2232.7     .05       0  4786.4     .12       0  4841.4      .1       0
  5013.9     .07       0  5026.8      .1       0  5198.4     .05       0
Bank Sta=5013.9,5026.8
XS Rating Curve= 0 ,0
Exp/Cntr=0.3,0.1

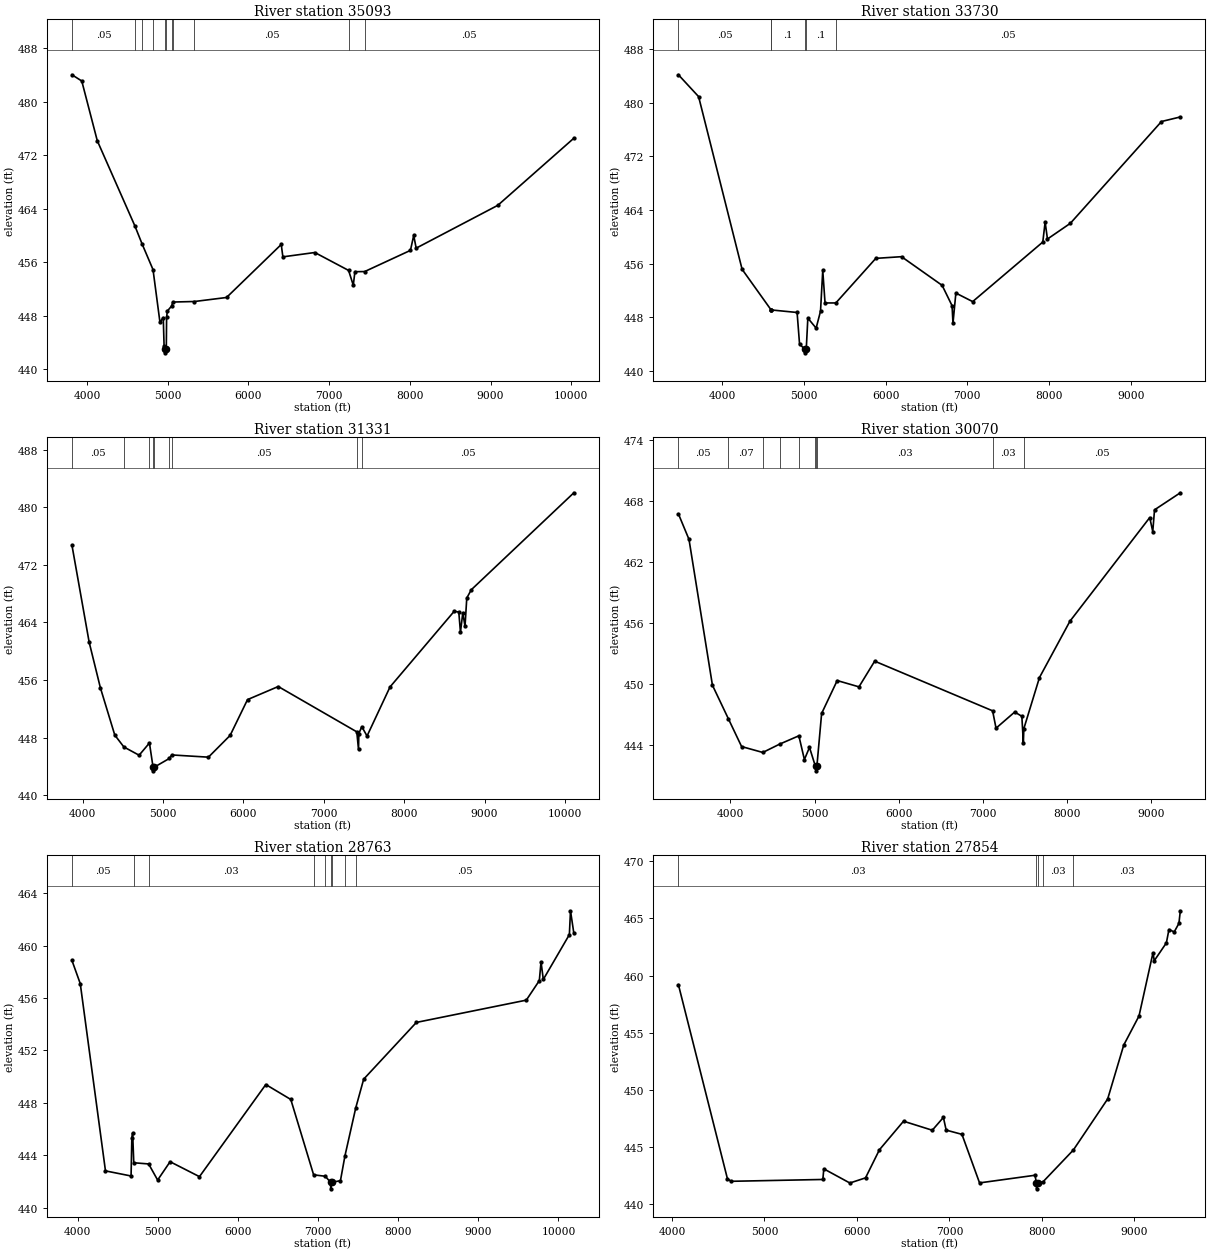
Type RM Length L Ch R = 1 ,35093   ,1363,1363,1363
BEGIN DESCRIPTION:
Mapping XS d5504016
END DESCRIPTION:
XS GIS Cut Line= 4
      2720050.97      6937735.99      2718903.24      6937437.55
      2716626.47      6937050.76      2713934.93      6937464.24
#Sta/Elev= 30
  3814.1  484.05  3935.7  483.12    4128  474.18  4594.5  461.42  4683.2  458.74
  4818.5   454.9  4904.2  447.05  4945.5  447.72  4955.8  443.41    4970  442.95
  4971.8  442.45    4983  442.95  4986.8  447.74    4996   448.7  5050.3  449.48
  5062.6  450.05    5332  450.13  5729.2  450.73  6407.1  458.66  6427.4  456.81
    6823  457.46  7241.6  454.78  7299.7  452.56    7320  454.59  7440.9  454.61
    8008  457.78  8048.4  460.01  8078.8  458.11  9090.5  464.52 10032.5  474.56
#Mann= 11 ,-1 , 0
  3814.1     .05       0  4594.5     .12       0  4683.2     .05       0
  4818.5     .12       0    4970     .07       0    4983     .12       0
  5050.3      .1       0  5062.6     .12       0    5332     .05       0
  7241.6     .12       0  7440.9     .05       0
Bank Sta=4970,4983
XS Rating Curve= 0 ,0
Exp/Cntr=0.3,0.1

Type RM Length L Ch R = 1 ,33730   ,2399,2399,2399
BEGIN DESCRIPTION:
Mapping XS e024aefd
END DESCRIPTION:
XS GIS Cut Line= 4
      2719751.83      6936604.45      2718261.02      6936465.92
      2716419.35      6936154.31      2713901.55      6937322.79
#Sta/Elev= 30
  3465.6  484.14  3712.5  480.89  4244.8  455.17  4599.1  449.13  4600.3  449.12
  4600.8  449.12  4917.7  448.74  4947.8  444.01  5016.4  443.23  5018.3  442.73
  5029.5  443.23  5049.1   447.9  5150.5  446.41  5204.2  448.93  5231.6  455.01
  5259.5  450.16  5391.8  450.16  5880.7   456.8  6195.1  457.05  6692.1  452.78
  6813.8  449.75  6824.8  447.12  6860.2  451.63  7065.9  450.36  7923.8  459.23
  7952.3   462.2  7980.9  459.68    8261  462.02    9376  477.18  9606.4  477.86
#Mann= 7 ,-1 , 0
  3465.6     .05       0  4599.1     .12       0  4600.3     .05       0
  4600.8      .1       0  5016.4     .05       0  5029.5      .1       0
  5391.8     .05       0
Bank Sta=5016.4,5029.5
XS Rating Curve= 0 ,0
Exp/Cntr=0.3,0.1

Type RM Length L Ch R = 1 ,31331   ,1261,1261,1261
BEGIN DESCRIPTION:
Mapping XS c9a8fe61
END DESCRIPTION:
XS GIS Cut Line= 4
      2719309.85      6934445.91      2718165.77      6934510.27
      2715852.93      6935237.56      2713751.01      6936885.99
#Sta/Elev= 30
  3868.4  474.74  4082.6  461.25  4221.9  454.93  4401.1  448.35  4513.9   446.7
  4703.6  445.55  4832.1  447.25  4877.2  443.88  4879.1  443.38  4890.4  443.88
  5079.7   445.1  5109.8  445.59  5565.6  445.28  5835.2   448.3  6051.8  453.28
    6434   455.1  7410.6   448.8    7432  446.36  7436.2  448.57  7472.8  449.52
  7538.2  448.22  7823.8  455.04  8621.2  465.55    8679  465.46  8699.8  462.65
  8728.7  465.33  8756.6  463.48  8778.4   467.4  8834.5  468.55   10110  482.03
#Mann= 9 ,-1 , 0
  3868.4     .05       0  4513.9     .12       0  4832.1     .07       0
  4877.2     .03       0  4890.4     .07       0  5079.7     .12       0
  5109.8     .05       0  7410.6     .12       0  7472.8     .05       0
Bank Sta=4877.2,4890.4
XS Rating Curve= 0 ,0
Exp/Cntr=0.3,0.1

Type RM Length L Ch R = 1 ,30070   ,1307,1307,1307
BEGIN DESCRIPTION:
Mapping XS be1dae2e
END DESCRIPTION:
XS GIS Cut Line= 4
      2719280.76       6933676.5      2717674.17      6933474.71
      2715355.02        6934391.      2713984.27      6935632.03
#Sta/Elev= 30
  3381.9  466.77  3507.6  464.26    3786   449.9  3974.6  446.61  4132.5  443.86
  4384.3  443.28  4584.3   444.1  4812.7  444.92  4878.3  442.58  4938.8  443.78
  5004.8  442.03    5014  441.97  5015.9  441.47  5027.3  441.97    5083  447.12
    5268  450.36  5526.5  449.74  5713.2  452.27  7113.9  447.38  7154.8  445.67
  7376.5  447.26  7461.4  446.84  7479.3  444.23  7485.2  445.63  7670.8  450.66
  8032.4   456.2  8980.6  466.41  9016.4  465.03  9037.4  467.17  9343.8  468.85
#Mann= 10 ,-1 , 0
  3381.9     .05       0  3974.6     .07       0  4384.3     .05       0
  4584.3     .03       0  4812.7     .03       0  5004.8     .03       0
    5014     .03       0  5027.3     .03       0  7113.9     .03       0
  7485.2     .05       0
Bank Sta=5014,5027.3
XS Rating Curve= 0 ,0
Exp/Cntr=0.3,0.1

Type RM Length L Ch R = 1 ,28763   ,909,909,909
BEGIN DESCRIPTION:
Mapping XS bd3db624
END DESCRIPTION:
XS GIS Cut Line= 4
       2719083.8      6932349.56      2718025.17      6932519.81
       2715853.9      6932755.44      2713744.86      6934899.16
#Sta/Elev= 30
  3928.6  458.86  4032.4  457.09  4346.9   442.8  4666.4  442.41  4675.9  445.31
    4686  445.69  4700.2  443.42  4885.6  443.33  4997.9   442.1  5153.4   443.5
  5519.8  442.36  6347.9  449.39  6659.7  448.25  6944.6   442.5  7089.8  442.39
    7156  441.93  7157.9  441.43  7169.3  441.93  7279.2  442.05  7335.9  443.96
  7470.7  447.62  7569.2   449.8  8226.8  454.13  9598.6  455.83  9761.2  457.32
  9782.5  458.75  9810.8  457.41 10136.1  460.83 10150.2  462.65 10192.1  460.93
#Mann= 9 ,-1 , 0
  3928.6     .05       0  4700.2     .03       0  4885.6     .03       0
  6944.6     .03       0  7089.8     .03       0    7156     .03       0
  7169.3     .03       0  7335.9     .03       0  7470.7     .05       0
Bank Sta=7156,7169.3
XS Rating Curve= 0 ,0
Exp/Cntr=0.3,0.1

Type RM Length L Ch R = 1 ,27854   ,526,526,526
BEGIN DESCRIPTION:
Mapping XS 6a069225
END DESCRIPTION:
XS GIS Cut Line= 4
      2718925.57      6931690.58      2717992.92      6931731.28
      2715526.09      6931905.96      2713850.97      6933036.02
#Sta/Elev= 30
  4069.7   459.2  4599.8  442.21  4639.8  441.99  5631.5  442.15  5641.8  443.08
  5923.5  441.84  6092.9  442.29  6243.3  444.75  6503.9  447.25  6814.7  446.46
    6935  447.58  6965.1  446.47  7135.5   446.1    7326  441.85    7926  442.52
  7940.3  441.83  7942.2  441.33  7953.7  441.83    8014  441.96  8340.3  444.73
  8711.4   449.2  8885.3  453.92  9050.2  456.46  9201.3  461.99  9215.1   461.3
  9346.1  462.86    9374  464.03  9430.9  463.82  9481.9  464.57  9496.9  465.67
#Mann= 5 ,-1 , 0
  4069.7     .03       0  7940.3     .03       0  7953.7     .03       0
    8014     .03       0  8340.3     .03       0
Bank Sta=7940.3,7953.7
XS Rating Curve= 0 ,0
Exp/Cntr=0.3,0.1

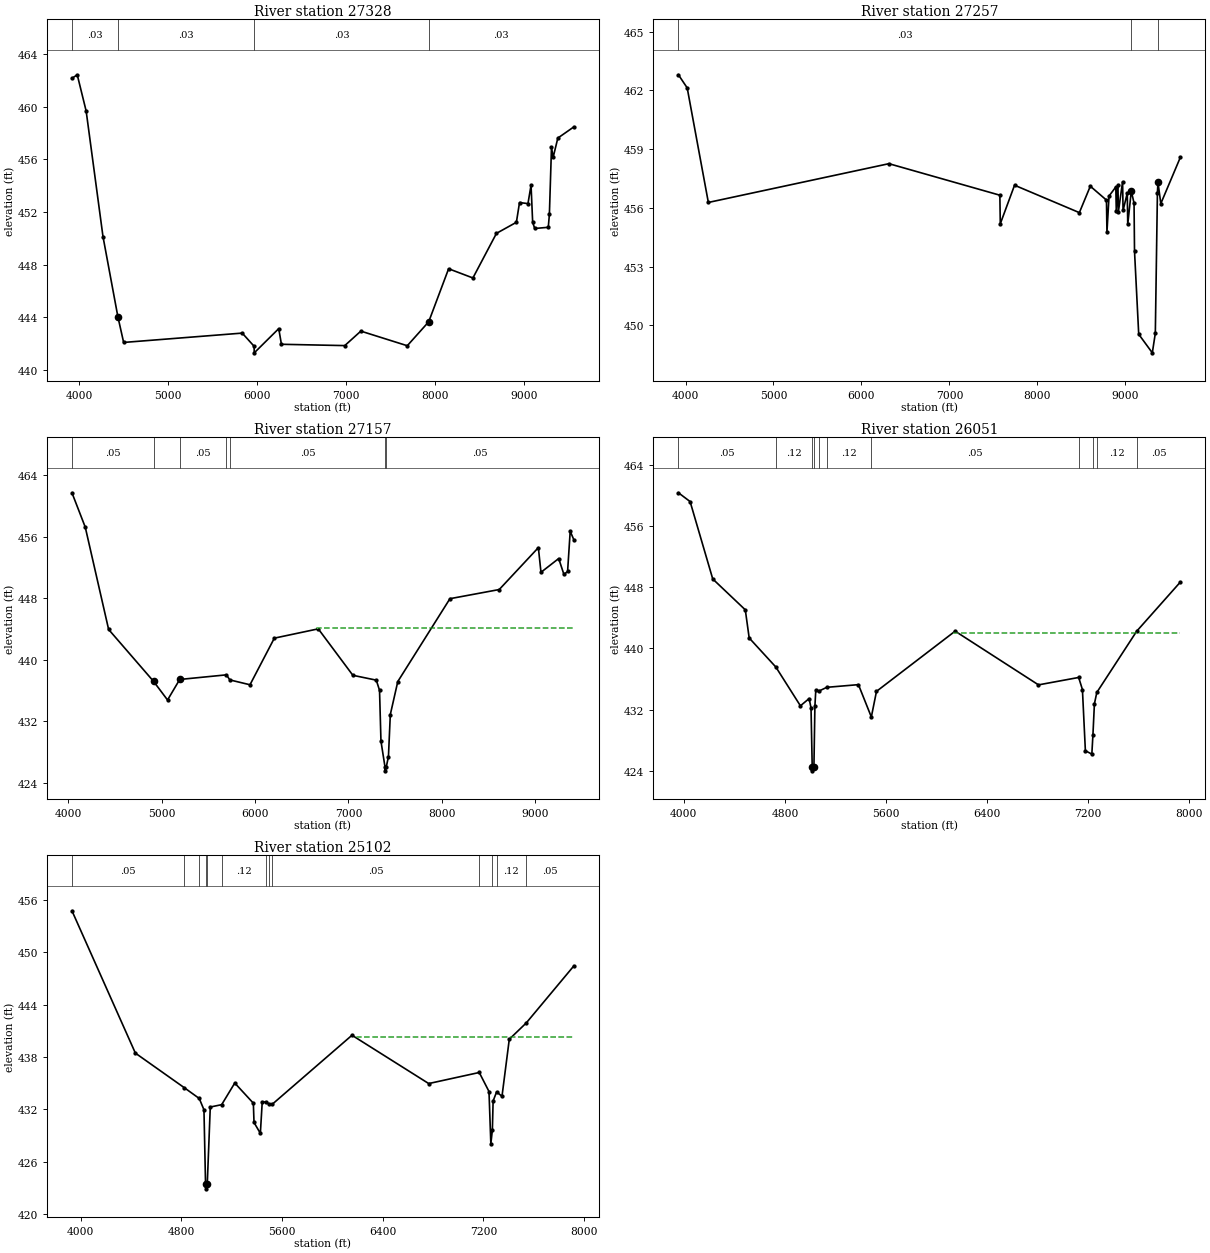
Type RM Length L Ch R = 1 ,27328   ,71,71,71
BEGIN DESCRIPTION:
Mapping XS 48a87320
END DESCRIPTION:
XS GIS Cut Line= 6
       2718755.4      6931294.52       2717381.1      6931380.41
      2716262.73      6931344.13      2714616.64      6931225.71
      2714538.92      6931260.71      2713992.66      6932555.61
#Sta/Elev= 30
  3918.5  462.15    3978  462.42  4078.2  459.66    4267  450.13  4434.2  444.04
    4499  442.08  5830.9  442.79  5964.2  441.79  5966.1  441.29  6241.1  443.13
  6271.1  441.94  6982.7  441.84  7163.2  442.94  7684.6  441.83  7925.3  443.65
    8149  447.68  8421.7  446.98  8686.3  450.37  8910.1  451.21  8945.2  452.71
  9040.1  452.63  9074.7  454.03  9092.9   451.2  9116.4  450.74  9268.3  450.83
  9280.7  451.81  9304.4  456.91  9322.6  456.14  9375.5  457.61  9555.5  458.46
#Mann= 4 ,-1 , 0
  3918.5     .03       0  4434.2     .03       0  5964.2     .03       0
  7925.3     .03       0
Bank Sta=4434.2,7925.3
XS Rating Curve= 0 ,0
Exp/Cntr=0.3,0.1

Type RM Length L Ch R = 1 ,27257   ,100,100,100
BEGIN DESCRIPTION:
Mapping XS 544482ac
END DESCRIPTION:
XS GIS Cut Line= 6
      2718755.68      6931236.69      2717329.41      6931307.51
      2714595.47      6931158.77      2714506.93      6931213.46
       2714483.5      6931252.52      2713951.01      6932535.97
#Sta/Elev= 30
  3919.1   462.8    4019  462.13  4259.4  456.28  6312.5  458.26  7573.8  456.65
  7578.8  455.19  7740.9  457.16  8477.8  455.76  8602.2  457.11    8786   456.4
  8791.4  454.76  8815.3  456.61  8892.3  457.07  8897.7  455.85  8916.2  457.18
  8921.6  455.81  8969.3  457.34  8974.7  455.87  9022.5  456.76  9027.9  455.16
  9068.2  456.86  9099.5  456.25  9104.9  453.79  9152.7  449.55  9307.3   448.6
  9341.5   449.6  9365.3  456.77  9371.3  457.33  9403.8  456.22  9625.7  458.58
#Mann= 3 ,-1 , 0
  3919.1     .03       0  9068.2     .03       0  9371.3     .03       0
Bank Sta=9068.2,9371.3
XS Rating Curve= 0 ,0
Exp/Cntr=0.3,0.1

Type RM Length L Ch R = 1 ,27157   ,1106,1106,1106
BEGIN DESCRIPTION:
Mapping XS 5c296057
END DESCRIPTION:
XS GIS Cut Line= 6
      2718618.43      6931163.89      2717363.14       6931217.9
      2716509.04      6931156.56      2714556.41      6931088.46
      2714509.54      6931122.31      2713950.99      6932236.02
#Sta/Elev= 30
  4040.2  461.69  4182.7  457.22  4432.8  443.92  4913.1  437.18  5063.3  434.75
  5193.7  437.42  5693.5  438.02  5730.2  437.36  5945.7  436.73  6206.3  442.79
  6676.5     444  7046.9  437.96  7297.4  437.33  7332.2  436.01  7347.5   429.4
  7390.8  426.04  7392.7  425.54  7404.3  426.04  7427.6   427.4  7447.6  432.86
  7527.6  437.15  8085.7  447.92  8613.3  449.11  9032.2  454.56  9060.1  451.35
  9249.8  453.14  9305.9  451.07    9345  451.46  9372.9  456.69    9412  455.58
#Mann= 7 ,-1 , 0
  4040.2     .05       0  4913.1     .04       0  5193.7     .05       0
  5693.5     .12       0  5730.2     .05       0  7390.8     .04       0
  7404.3     .05       0
#XS Ineff= 2 , 0
       0                  6666.5       0  444.05
Permanent Ineff=
       F       F
Bank Sta=4913.1,5193.7
XS Rating Curve= 0 ,0
Exp/Cntr=0.3,0.1

Type RM Length L Ch R = 1 ,26051   ,949,949,949
BEGIN DESCRIPTION:
Mapping XS 4ab04016
END DESCRIPTION:
XS GIS Cut Line= 4
      2718352.85      6930785.72      2717376.31      6930568.71
      2717241.76      6930494.93      2714479.74      6931061.26
#Sta/Elev= 30
  3957.1  460.37  4049.6  459.22  4228.9  449.09  4486.6  445.05  4517.3  441.37
  4728.6  437.56  4922.9  432.49    4992  433.44  5006.9  432.21  5016.3  424.48
  5018.2  423.98  5029.8  424.48  5037.6  432.44  5044.8  434.58  5069.4  434.42
  5131.6  434.91  5382.2  435.26  5484.3  431.03  5525.1  434.38  6147.8  442.26
  6807.6  435.23  7125.7   436.2  7155.4  434.62  7178.8  426.61  7229.9  426.17
  7238.7  428.72  7250.3  432.75  7269.4  434.24  7584.9  442.25  7930.4  448.68
#Mann= 11 ,-1 , 0
  3957.1     .05       0  4728.6     .12       0  5016.3     .07       0
  5029.8     .12       0  5069.4      .1       0  5131.6     .12       0
  5484.3     .05       0  7125.7     .12       0  7238.7      .1       0
  7269.4     .12       0  7584.9     .05       0
#XS Ineff= 2 , 0
       0                  6127.4       0  442.04
Permanent Ineff=
       F       F
Bank Sta=5016.3,5029.8
XS Rating Curve= 0 ,0
Exp/Cntr=0.3,0.1

Type RM Length L Ch R = 1 ,25102   ,1114,1114,1114
BEGIN DESCRIPTION:
Mapping XS 4e8ddb43
END DESCRIPTION:
XS GIS Cut Line= 4
      2717981.38       6929487.1      2717101.14      6929846.49
      2717020.89       6930211.1      2714475.77      6930993.89
#Sta/Elev= 30
    3932  454.75  4435.9  438.43  4824.9  434.46  4943.3  433.23  4980.6  431.93
  4993.3  423.37  4995.2  422.87  5006.8  423.37  5030.8  432.25  5121.3  432.52
  5225.3     435    5373  432.69  5378.2  430.48  5428.6  429.23  5443.6  432.85
  5475.4  432.81  5497.6  432.59  5522.6  432.56  6156.5  440.48    6766  434.94
  7167.4  436.21  7244.8  434.03  7259.5  428.03  7271.7  429.62  7277.5  432.94
  7305.2  433.98  7348.1  433.48    7406  440.02  7540.8  441.89  7918.9  448.43
#Mann= 13 ,-1 , 0
    3932     .05       0  4824.9     .12       0  4943.3      .1       0
  4993.3     .07       0  5006.8      .1       0  5121.3     .12       0
  5475.4      .1       0  5497.6     .12       0  5522.6     .05       0
  7167.4     .12       0  7271.7      .1       0  7305.2     .12       0
  7540.8     .05       0
#XS Ineff= 2 , 0
       0                  6194.4       0   440.3
Permanent Ineff=
       F       F
Bank Sta=4993.3,5006.8
XS Rating Curve= 0 ,0
Exp/Cntr=0.3,0.1