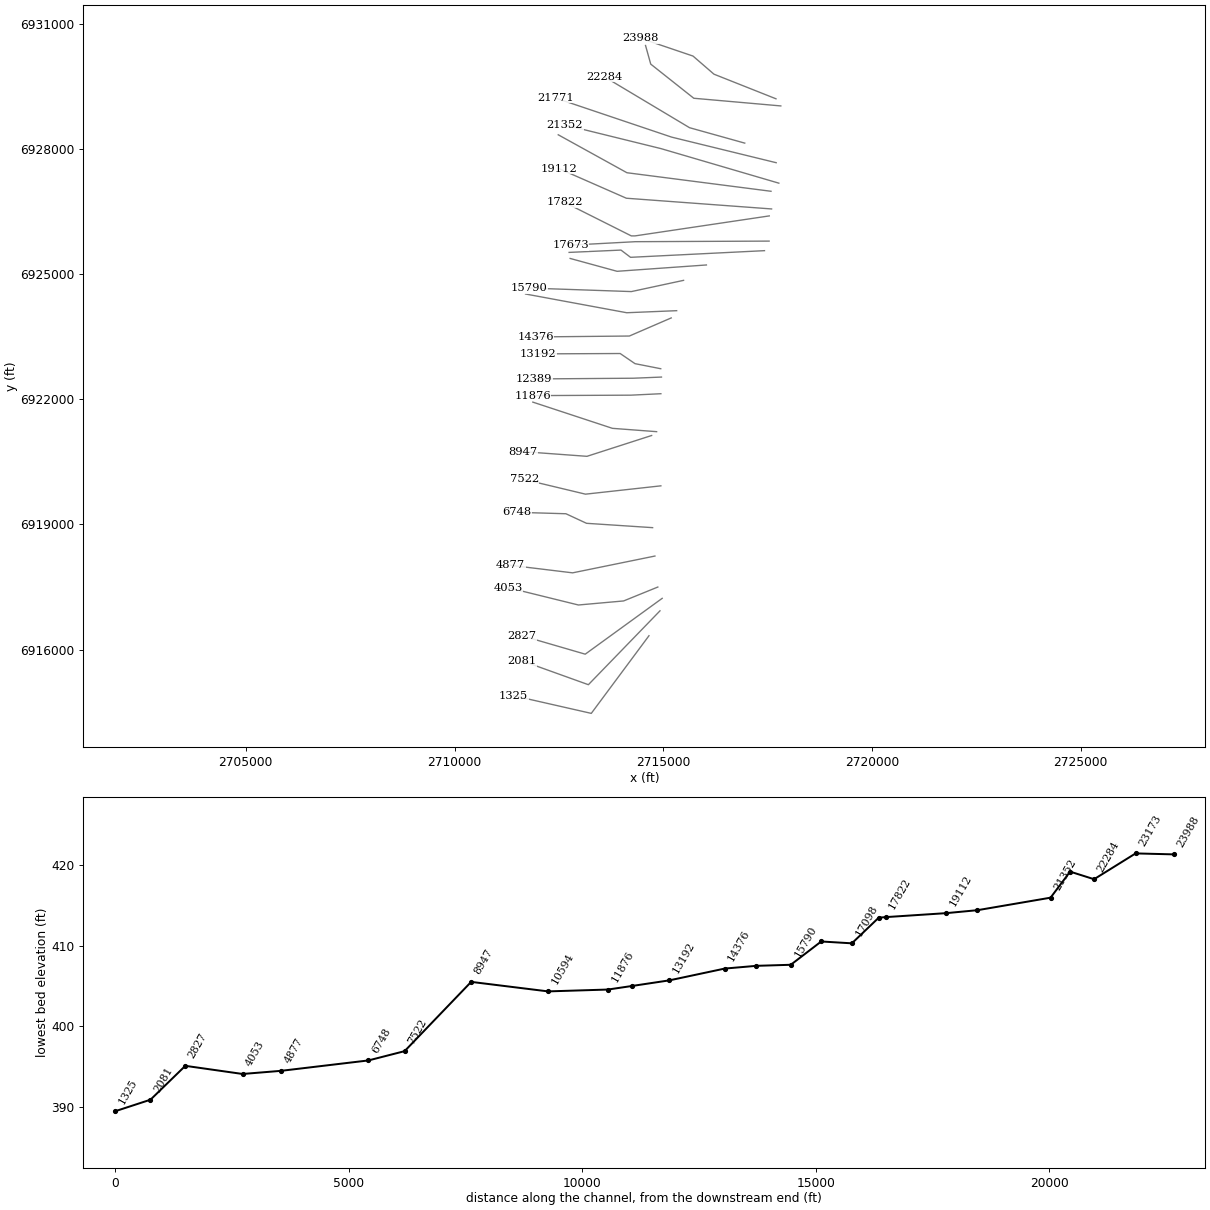
HEC-RAS study Wolf Creek.prj: Wolf Creek Base Level Engineering

--- Wolf Creek.g01 (geometry) --- (continued)

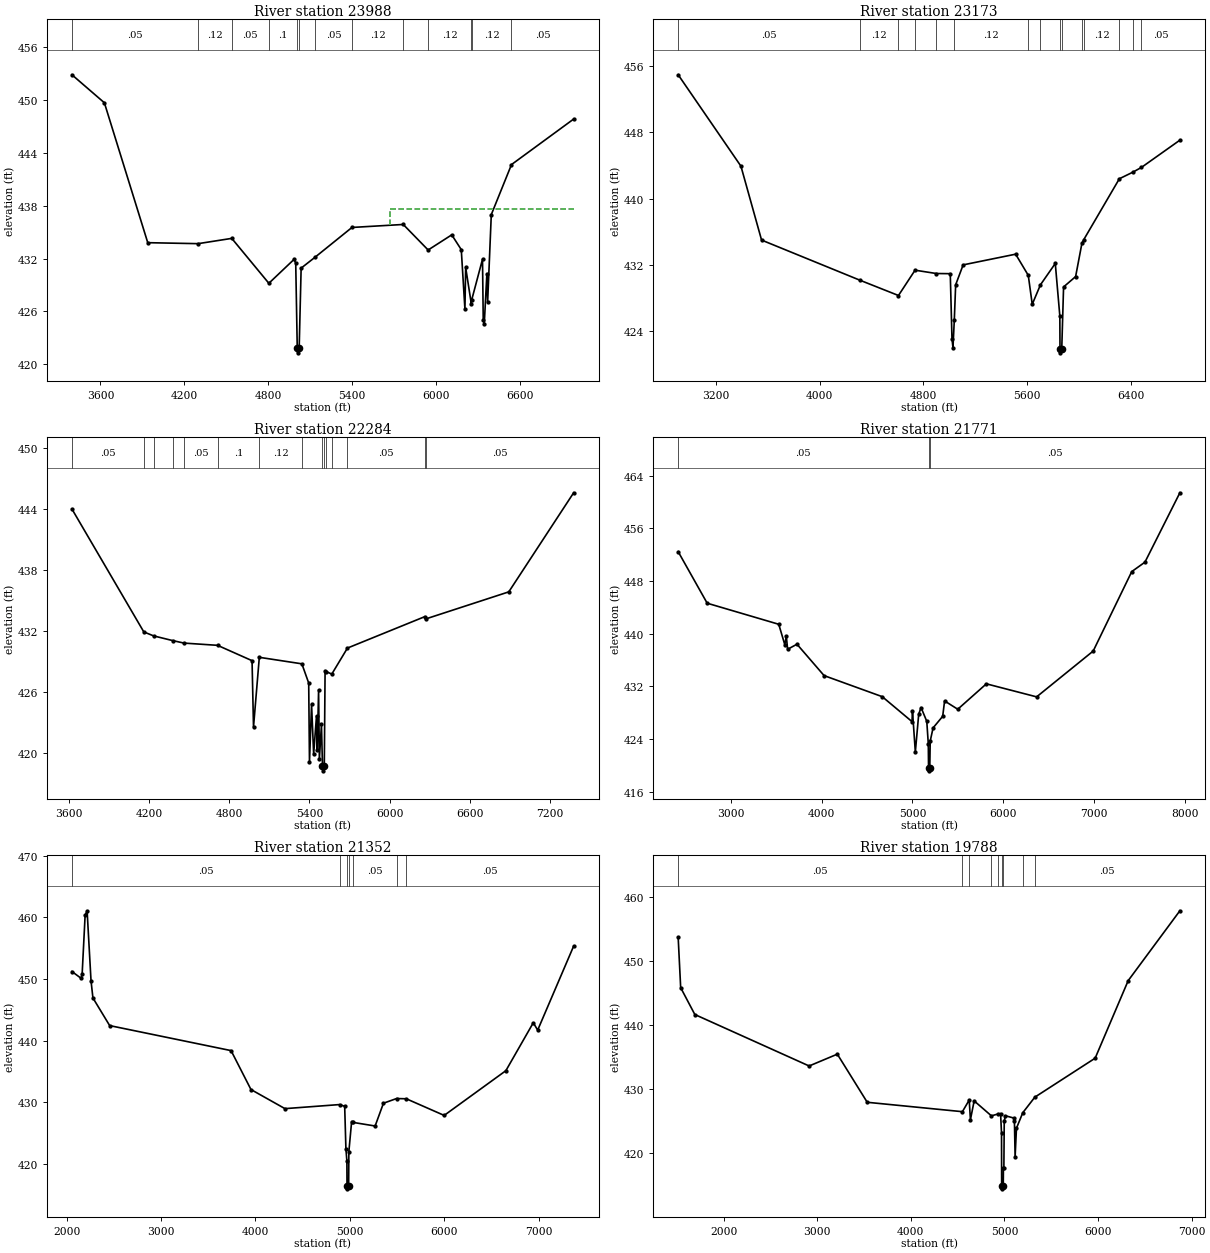
Type RM Length L Ch R = 1 ,23988   ,815,815,815
BEGIN DESCRIPTION:
Mapping XS 14c960e3
END DESCRIPTION:
XS GIS Cut Line= 4
      2717701.41      6929204.78      2716215.29      6929795.06
      2715713.41      6930229.34      2714461.26      6930654.16
#Sta/Elev= 30
  3396.7  452.88  3628.5   449.7  3938.5  433.81  4298.3   433.7  4538.8   434.3
  4803.8   429.2  4984.2  431.92  4995.8  431.48  5006.8   421.8  5008.7   421.3
  5020.4   421.8  5034.5  430.92  5133.2  432.15  5397.7  435.54  5764.1  435.88
    5942  432.98  6110.7   434.7  6178.8  433.02  6204.9  426.26  6210.2     431
  6250.2   426.9  6252.3  427.25  6330.5  431.93  6335.8     425  6343.1   424.6
  6361.9   430.3  6367.2  427.07  6393.3     437  6537.6  442.68  6981.7  447.85
#Mann= 13 ,-1 , 0
  3396.7     .05       0  4298.3     .12       0  4538.8     .05       0
  4803.8      .1       0  5006.8     .07       0  5020.4      .1       0
  5133.2     .05       0  5397.7     .12       0  5764.1     .05       0
    5942     .12       0  6250.2      .1       0  6252.3     .12       0
  6537.6     .05       0
#XS Ineff= 2 , 0
       0                  5667.3       0  437.64
Permanent Ineff=
       F       F
Bank Sta=5006.8,5020.4
XS Rating Curve= 0 ,0
Exp/Cntr=0.3,0.1

Type RM Length L Ch R = 1 ,23173   ,889,889,889
BEGIN DESCRIPTION:
Mapping XS 0e50cf96
END DESCRIPTION:
XS GIS Cut Line= 4
      2717817.33      6929033.77      2715732.32      6929217.67
        2714701.        6930036.      2714576.39      6930482.59
#Sta/Elev= 30
  2906.9  454.93  3391.3  443.92  3550.7  435.01  4308.8  430.18  4607.6  428.33
  4735.7  431.38  4900.1  430.98  5007.5  430.96  5020.8  423.13  5028.4  422.05
  5038.8  425.41  5049.2  429.62  5106.9  432.02  5512.2  433.31  5609.8  430.76
  5640.4  427.27  5703.8  429.62  5818.3  432.19  5853.5  425.85  5854.7  421.92
  5856.7  421.42  5868.3  421.92  5882.3  429.36  5975.3  430.61  6023.9  434.62
  6038.5  435.07    6313   442.4  6415.5  443.18  6483.9  443.77  6780.2  447.05
#Mann= 15 ,-1 , 0
  2906.9     .05       0  4308.8     .12       0  4607.6      .1       0
  4735.7     .12       0  4900.1      .1       0  5038.8     .12       0
  5609.8      .1       0  5703.8     .12       0  5854.7     .07       0
  5868.3     .12       0  6023.9      .1       0  6038.5     .12       0
    6313     .05       0  6415.5     .12       0  6483.9     .05       0
Bank Sta=5854.7,5868.3
XS Rating Curve= 0 ,0
Exp/Cntr=0.3,0.1

Type RM Length L Ch R = 1 ,22284   ,513,513,513
BEGIN DESCRIPTION:
Mapping XS 5c917040
END DESCRIPTION:
XS GIS Cut Line= 3
      2716953.18      6928142.27      2715630.22      6928512.07
      2713590.66      6929732.33
#Sta/Elev= 30
  3624.3  443.98  4161.5  431.89  4234.5   431.5  4376.1  431.04  4462.1  430.79
  4712.8  430.57  4970.7  429.06  4981.6  422.53    5025  429.39  5343.1  428.75
  5394.2  426.86    5400  419.08  5415.6  424.75  5431.2  419.86  5452.6  423.63
  5458.4   420.3  5468.1  426.19    5474  419.36  5489.5  422.78  5497.1  418.72
  5499.1  418.22  5510.8  418.72  5516.7  428.08  5526.4  427.98  5566.8  427.74
  5683.8   430.3  6263.5   433.4  6269.8  433.17  6889.9  435.83  7374.7  445.58
#Mann= 15 ,-1 , 0
  3624.3     .05       0  4161.5     .12       0  4234.5     .05       0
  4376.1     .12       0  4462.1     .05       0  4712.8      .1       0
    5025     .12       0  5343.1      .1       0  5497.1     .07       0
  5510.8      .1       0  5526.4     .12       0  5566.8      .1       0
  5683.8     .05       0  6263.5     .12       0  6269.8     .05       0
Bank Sta=5497.1,5510.8
XS Rating Curve= 0 ,0
Exp/Cntr=0.3,0.1

Type RM Length L Ch R = 1 ,21771   ,419,419,419
BEGIN DESCRIPTION:
Wolf Creek 14.0
END DESCRIPTION:
XS GIS Cut Line= 3
      2717706.17      6927672.66        2715201.        6928286.
      2712411.77      6929226.23
#Sta/Elev= 30
  2420.9  452.46  2740.2  444.63    3528  441.43  3594.7  438.32  3611.3  439.61
  3625.6  437.63  3728.6   438.4  4027.1  433.63  4667.1  430.43  4994.9  426.64
  5000.1  428.25  5031.5  422.02  5068.6  427.76  5094.5  428.78  5157.5  426.68
  5174.2  423.25  5176.8  419.66  5178.8  419.16  5190.5  419.66  5195.3  423.68
  5226.9  425.69  5332.5  427.44  5353.6  429.78  5498.5  428.52  5813.3  432.38
  6366.7   430.4  6989.3  437.36  7413.6  449.43  7559.1  450.87  7943.5  461.41
#Mann= 3 ,-1 , 0
  2420.9     .05       0  5176.8     .05       0  5190.5     .05       0
Bank Sta=5176.8,5190.5
XS Rating Curve= 0 ,0
Exp/Cntr=0.3,0.1

Type RM Length L Ch R = 1 ,21352   ,1564,1564,1564
BEGIN DESCRIPTION:
Mapping XS bf4f0dd5
END DESCRIPTION:
XS GIS Cut Line= 3
      2717769.94      6927182.22      2714946.24      6928010.57
      2712644.97      6928578.04
#Sta/Elev= 30
  2057.3  451.21  2155.2   450.1  2165.6  450.86  2196.9  460.32  2217.9  461.07
  2259.4  449.71  2279.5  446.92  2456.9  442.43  3742.4  438.37  3953.2  432.05
  4313.2  428.95  4891.2  429.61  4945.6  429.33  4958.6  422.45    4969  420.42
  4970.3  416.43  4972.3  415.93  4987.6  416.43  4989.8  421.96  5019.2  426.86
  5032.5  426.72    5268  426.13  5356.2  429.83  5495.5  430.59  5598.1  430.55
  5999.3  427.85  6652.5  435.11  6942.8  442.89  6989.5   441.7  7370.2  455.33
#Mann= 7 ,-1 , 0
  2057.3     .05       0  4891.2      .1       0  4970.3     .07       0
  4987.6      .1       0  5032.5     .05       0  5495.5     .12       0
  5598.1     .05       0
Bank Sta=4970.3,4987.6
XS Rating Curve= 0 ,0
Exp/Cntr=0.3,0.1

Type RM Length L Ch R = 1 ,19788   ,676,676,676
BEGIN DESCRIPTION:
Mapping XS 3700a874
END DESCRIPTION:
XS GIS Cut Line= 3
       2717582.5      6926987.76      2714131.09      6927432.21
      2712485.28      6928341.92
#Sta/Elev= 30
    1514   453.7  1540.7  445.85    1692  441.65  2913.3   433.6  3214.4  435.45
    3534  427.92  4550.8  426.45  4623.5  428.27  4636.6   425.2  4676.4  428.14
  4860.7   425.8  4931.1  426.09  4958.7  426.15  4968.8  423.08  4970.2  414.88
  4972.2  414.38  4987.5  414.88  4988.9  417.68  4993.9  417.68  4997.9  425.01
  5011.1  425.81    5101  425.45  5106.7  425.04    5114  419.38  5128.4  423.86
  5195.6  426.28  5324.5  428.72  5969.3  434.82  6322.1  446.95  6874.4  457.88
#Mann= 9 ,-1 , 0
    1514     .05       0  4550.8     .12       0  4623.5      .1       0
  4860.7     .12       0  4931.1      .1       0  4970.2     .07       0
  4987.5      .1       0  5195.6     .12       0  5324.5     .05       0
Bank Sta=4970.2,4987.5
XS Rating Curve= 0 ,0
Exp/Cntr=0.3,0.1

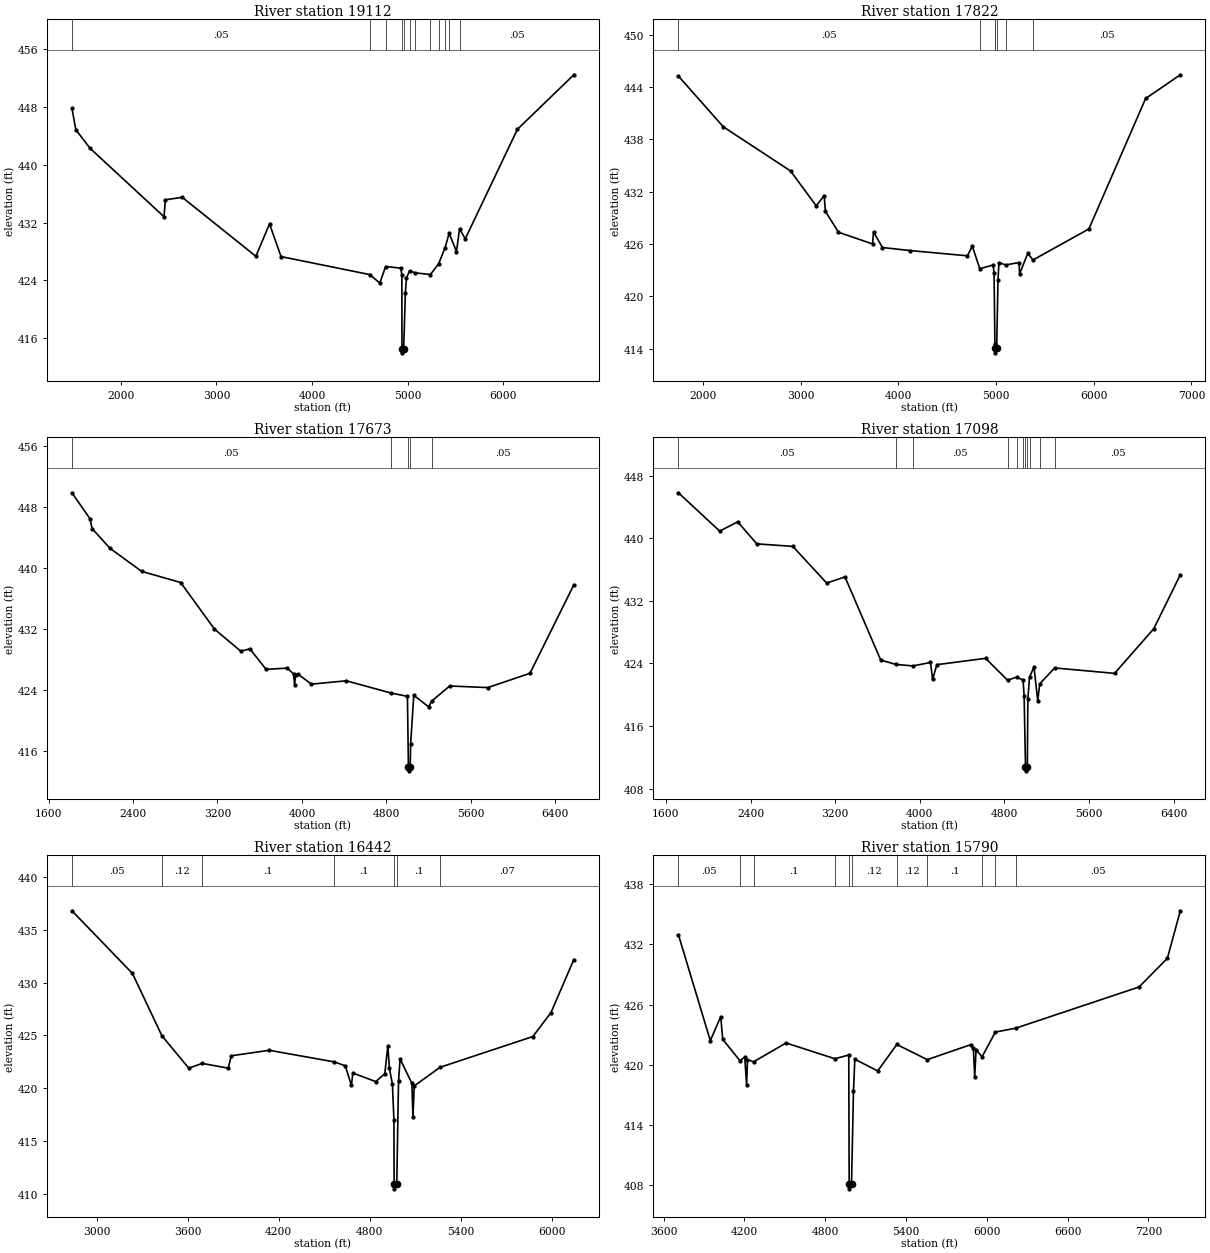
Type RM Length L Ch R = 1 ,19112   ,1290,1290,1290
BEGIN DESCRIPTION:
Mapping XS d17548e9
END DESCRIPTION:
XS GIS Cut Line= 3
      2717596.38      6926564.15       2714117.2       6926821.1
      2712506.09      6927529.43
#Sta/Elev= 30
  1488.7  447.77  1529.2  444.81  1679.6  442.23  2451.7   432.8  2465.5  435.14
  2642.2  435.48    3412  427.34    3555  431.81    3675   427.3  4604.4  424.81
  4707.8  423.64  4768.9  425.93  4928.4   425.7  4938.5  424.77  4939.8  414.51
  4941.8  414.01  4957.1  414.51  4975.5  422.28  4986.8  424.38  5020.8  425.33
  5075.5  425.06  5237.4  424.82  5323.9  426.33  5390.3  428.52  5433.2  430.51
  5509.9     428  5542.5  431.14  5601.3  429.74  6147.5  444.88  6737.3   452.4
#Mann= 12 ,-1 , 0
  1488.7     .05       0  4604.4     .12       0  4768.9      .1       0
  4939.8     .07       0  4957.1      .1       0  5020.8     .12       0
  5075.5      .1       0  5237.4     .12       0  5323.9      .1       0
  5390.3     .12       0  5433.2      .1       0  5542.5     .05       0
Bank Sta=4939.8,4957.1
XS Rating Curve= 0 ,0
Exp/Cntr=0.3,0.1

Type RM Length L Ch R = 1 ,17822   ,149,149,149
BEGIN DESCRIPTION:
Mapping XS f8225400
END DESCRIPTION:
XS GIS Cut Line= 4
      2717540.76      6926397.48      2714325.53      6925918.32
      2714235.25      6925918.32      2712631.07      6926723.88
#Sta/Elev= 30
  1749.8  445.26  2209.6  439.44  2897.1  434.38    3160  430.38  3240.8  431.56
  3254.2  429.75  3387.8  427.35  3736.3  426.01  3746.4  427.38  3837.4   425.6
  4120.5  425.25  4706.9  424.65  4757.4  425.75  4833.7  423.17  4969.7  423.59
  4979.8  422.71  4988.6  414.49  4989.1  414.02  4991.1  413.52  5006.5  414.02
  5020.1  421.89  5030.1  423.87  5099.7   423.6  5235.4  423.88  5241.3  422.58
    5325  424.93  5378.1  424.17  5950.4  427.73    6531  442.69  6885.9  445.41
#Mann= 7 ,-1 , 0
  1749.8     .05       0  4833.7     .12       0  4988.6      .1       0
  4989.1     .07       0  5006.5      .1       0  5099.7      .1       0
  5378.1     .05       0
Bank Sta=4989.1,5006.5
XS Rating Curve= 0 ,0
Exp/Cntr=0.3,0.1

Type RM Length L Ch R = 1 ,17673   ,575,575,575
BEGIN DESCRIPTION:
Mapping XS b520d289
END DESCRIPTION:
XS GIS Cut Line= 3
       2717536.9      6925793.32      2714335.51      6925779.43
      2712780.46      6925696.13
#Sta/Elev= 30
    1820  449.89  1990.9  446.49  2010.9   445.2  2180.9  442.61  2480.9  439.59
  2850.9  438.13  3170.9  432.03  3420.9  429.13  3506.8  429.44  3660.9  426.75
  3860.9  426.91  3920.9  426.16  3930.9  424.74  3940.9     426  3960.9  426.14
  4090.9  424.81  4420.9  425.25  4841.6  423.66  5000.9  423.21    5010  413.95
    5012  413.45  5027.4  413.95  5030.9  416.94    5061  423.34  5201.2  421.85
  5231.7   422.6  5401.5  424.57    5762  424.36  6162.6  426.23  6578.7  437.83
#Mann= 5 ,-1 , 0
    1820     .05       0  4841.6     .12       0    5010     .07       0
  5027.4     .12       0  5231.7     .05       0
Bank Sta=5010,5027.4
XS Rating Curve= 0 ,0
Exp/Cntr=0.3,0.1

Type RM Length L Ch R = 1 ,17098   ,656,656,656
BEGIN DESCRIPTION:
Mapping XS 00208ceb
END DESCRIPTION:
XS GIS Cut Line= 4
      2717425.78      6925564.15      2714217.46      6925404.43
      2713988.29      6925578.04      2712745.23      6925522.49
#Sta/Elev= 30
  1718.3  445.81  2108.6  440.91  2278.8   442.1    2459  439.28  2799.4  438.96
  3119.8  434.27  3292.6  435.06  3630.4  424.43  3774.9  423.87  3935.4  423.68
    4101  424.12    4121  421.96  4161.1  423.84  4621.7  424.65  4829.1  421.86
  4914.8  422.24  4975.9  421.88  4985.9  419.89    4999  410.77    5001  410.27
  5016.4  410.77  5021.3  419.43    5037  422.26  5079.5  423.53  5114.8  419.21
  5133.1  421.39  5274.4  423.42    5841  422.73  6211.4  428.43  6462.4  435.33
#Mann= 11 ,-1 , 0
  1718.3     .05       0  3774.9     .12       0  3935.4     .05       0
  4829.1     .12       0  4914.8      .1       0  4975.9     .12       0
    4999     .07       0  5016.4     .12       0    5037      .1       0
  5133.1     .12       0  5274.4     .05       0
Bank Sta=4999,5016.4
XS Rating Curve= 0 ,0
Exp/Cntr=0.3,0.1

Type RM Length L Ch R = 1 ,16442   ,652,652,652
BEGIN DESCRIPTION:
Mapping XS 888f308a
END DESCRIPTION:
XS GIS Cut Line= 3
      2716034.35      6925221.28      2713894.54      6925069.36
      2712770.69      6925377.44
#Sta/Elev= 30
  2835.9  436.79  3235.2  430.86  3428.9  424.98  3606.2  421.91  3694.8  422.36
  3866.8  421.91  3886.9  423.08  4137.5   423.6  4567.1   422.5  4638.8  422.13
  4678.9  420.28  4688.9  421.45  4839.3  420.64  4899.4  421.38  4919.5  424.04
  4929.5   421.9  4949.6  420.41  4959.6     417  4960.9     411  4962.9   410.5
  4978.3     411  4989.9  420.65  5000.3  422.78  5078.1  420.47  5085.1  417.29
  5093.6  420.23  5263.6  421.99  5876.3   424.9  5995.7  427.17  6146.4  432.18
#Mann= 7 ,-1 , 0
  2835.9     .05       0  3428.9     .12       0  3694.8      .1       0
  4567.1      .1       0  4960.9     .07       0  4978.3      .1       0
  5263.6     .07       0
Bank Sta=4960.9,4978.3
XS Rating Curve= 0 ,0
Exp/Cntr=0.3,0.1

Type RM Length L Ch R = 1 ,15790   ,735,735,735
BEGIN DESCRIPTION:
Mapping XS 9724708a
END DESCRIPTION:
XS GIS Cut Line= 3
      2715487.46      6924852.36      2714237.42      6924583.25
      2711789.96      6924667.72
#Sta/Elev= 30
    3710  432.96  3946.8   422.4  4024.4  424.79  4038.8  422.53  4165.9  420.41
  4202.5  420.74  4216.6  417.99    4223  420.51  4267.7  420.28  4509.4  422.16
  4872.3  420.59  4975.2  420.96  4978.2  408.11  4980.2  407.61  4995.6  408.11
  5010.1  417.35  5020.1  420.54  5190.2  419.37  5331.9  422.01  5558.1   420.5
  5880.6  421.99  5900.6  421.63  5910.7  418.78  5920.7  421.51  5964.8  420.77
  6063.9  423.25  6215.7  423.64  7131.4  427.75  7341.5  430.61  7437.6  435.35
#Mann= 11 ,-1 , 0
    3710     .05       0  4165.9     .12       0  4267.7      .1       0
  4872.3     .12       0  4978.2     .07       0  4995.6     .12       0
  5331.9     .12       0  5558.1      .1       0  5964.8     .05       0
  6063.9     .12       0  6215.7     .05       0
#XS Ineff= 2 , 0
       0  4024.4  424.79               0
Permanent Ineff=
       F       F
Bank Sta=4978.2,4995.6
XS Rating Curve= 0 ,0
Exp/Cntr=0.3,0.1

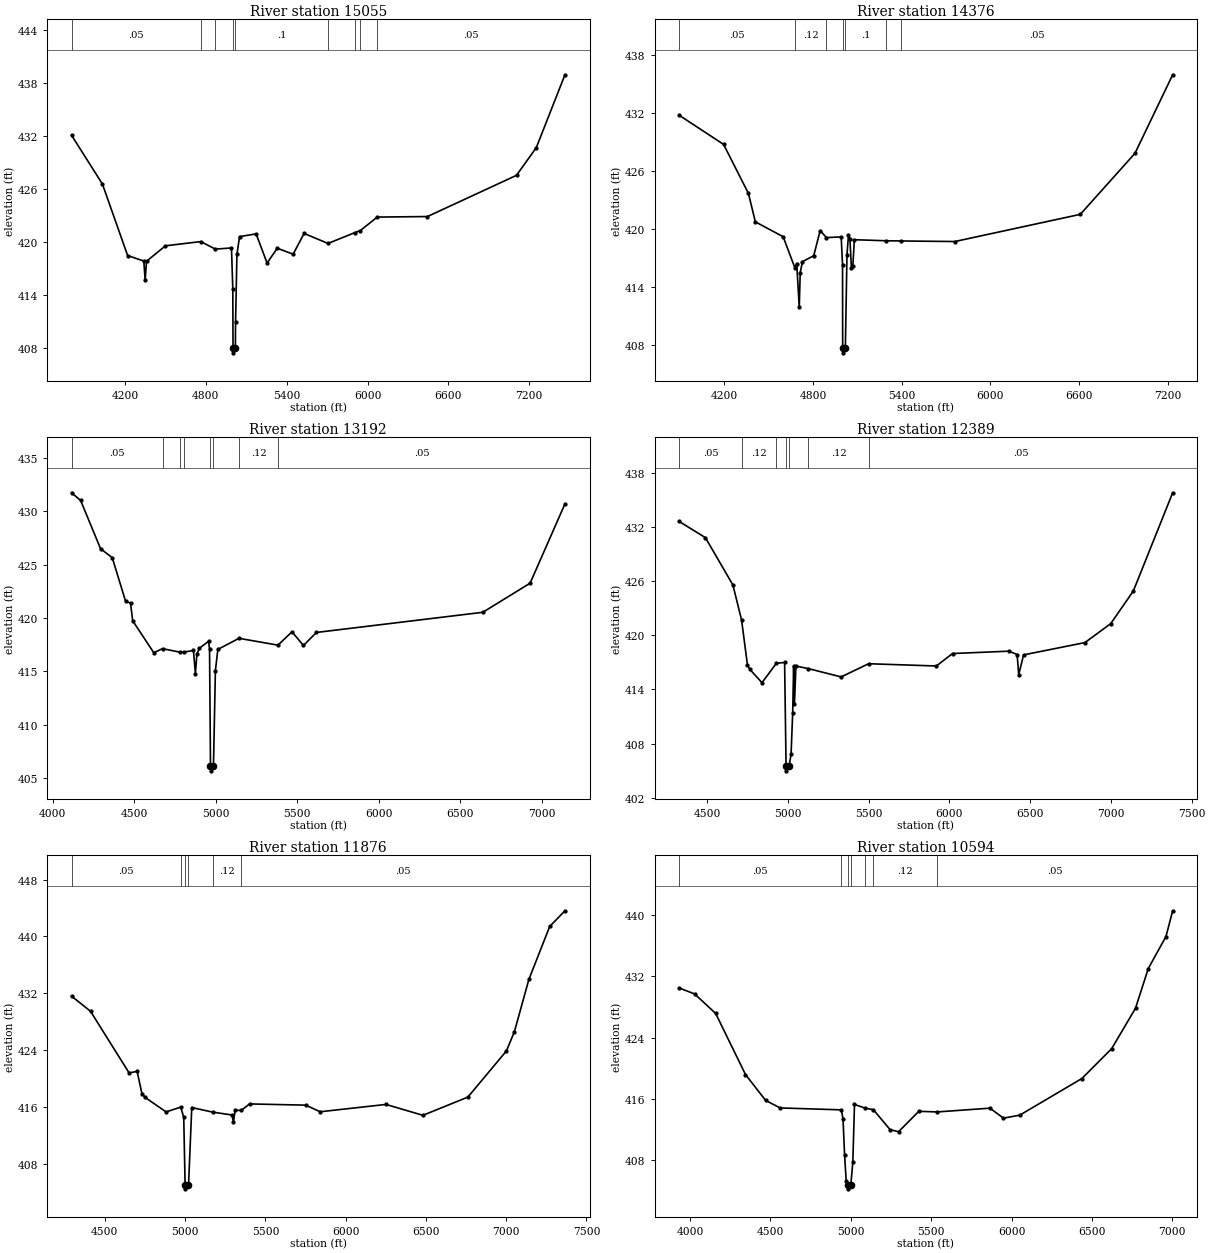
Type RM Length L Ch R = 1 ,15055   ,679,679,679
BEGIN DESCRIPTION:
Mapping XS 56bf8575
END DESCRIPTION:
XS GIS Cut Line= 3
      2715321.97      6924125.35      2714126.09      6924076.09
      2711702.49      6924524.85
#Sta/Elev= 30
  3803.1  432.08  4032.3  426.57  4219.4  418.48  4339.5  417.86  4349.5  415.69
  4359.5  417.83  4499.7  419.58  4762.2  420.06  4870.3  419.21  4990.1  419.34
    5000  414.66  5001.6  407.98  5003.6  407.48    5019  407.98  5020.4  410.99
  5030.6  418.63  5050.1  420.62    5173  420.93  5254.3  417.63  5329.8  419.31
  5447.6  418.63  5528.9  420.98  5706.7  419.85  5907.1  421.08  5946.6  421.31
  6071.9  422.83  6444.2  422.89  7105.3  427.55  7252.1  430.68  7464.8  438.92
#Mann= 9 ,-1 , 0
  3803.1     .05       0  4762.2     .12       0  4870.3      .1       0
  5001.6     .07       0    5019      .1       0  5706.7     .12       0
  5907.1     .05       0  5946.6     .12       0  6071.9     .05       0
Bank Sta=5001.6,5019
XS Rating Curve= 0 ,0
Exp/Cntr=0.3,0.1

Type RM Length L Ch R = 1 ,14376   ,1184,1184,1184
BEGIN DESCRIPTION:
Mapping XS c732881b
END DESCRIPTION:
XS GIS Cut Line= 3
       2715191.7      6923951.73      2714189.14      6923517.71
      2711940.92      6923496.01
#Sta/Elev= 30
  3893.9  431.77  4194.3  428.75  4362.3  423.67  4409.3  420.72  4597.5  419.18
  4676.7  415.96  4689.4  416.39  4706.5  411.85  4712.9  415.46  4728.3   416.6
  4804.5  417.21  4848.1  419.82  4890.2  419.09  4990.4  419.16  4999.5  416.28
  5000.4  407.64  5002.4  407.14  5018.6  407.64  5029.5  417.28  5039.5  419.33
  5049.5  418.98  5059.5  415.96  5069.5  416.19  5079.5  418.87  5293.2  418.76
  5392.2  418.74  5759.5  418.68  6609.6   421.5  6979.6  427.83  7234.7  435.97
#Mann= 7 ,-1 , 0
  3893.9     .05       0  4676.7     .12       0  4890.2      .1       0
  5000.4     .07       0  5018.6      .1       0  5293.2     .12       0
  5392.2     .05       0
Bank Sta=5000.4,5018.6
XS Rating Curve= 0 ,0
Exp/Cntr=0.3,0.1

Type RM Length L Ch R = 1 ,13192   ,803,803,803
BEGIN DESCRIPTION:
Mapping XS 44b27b7a
END DESCRIPTION:
XS GIS Cut Line= 4
      2714940.85      6922733.86      2714324.55      6922855.39
      2713968.65      6923098.44      2712002.52      6923089.76
#Sta/Elev= 30
  4116.2  431.74  4172.1  431.02  4294.4  426.49  4365.8  425.66  4447.3  421.59
  4477.9   421.4  4491.1  419.75  4620.6  416.75  4674.2  417.13  4781.9   416.8
  4804.4  416.81  4863.6  416.96  4875.8   414.8  4884.6   416.6  4899.5  417.16
  4956.4  417.82  4962.4  417.11  4968.2  406.18  4970.2  405.68  4986.6  406.18
  4998.3  415.07  5013.3  417.06    5143   418.1  5381.8  417.46    5468  418.71
    5538  417.43    5618  418.65    6638  420.54    6928  423.27  7141.5   430.7
#Mann= 8 ,-1 , 0
  4116.2     .05       0  4674.2     .12       0  4781.9      .1       0
  4804.4     .12       0  4968.2     .07       0  4986.6     .12       0
    5143     .12       0  5381.8     .05       0
Bank Sta=4968.2,4986.6
XS Rating Curve= 0 ,0
Exp/Cntr=0.3,0.1

Type RM Length L Ch R = 1 ,12389   ,513,513,513
BEGIN DESCRIPTION:
Mapping XS facc75ba
END DESCRIPTION:
XS GIS Cut Line= 3
      2714958.09      6922534.03      2714284.45      6922506.26
      2711902.53      6922488.89
#Sta/Elev= 30
  4326.2  432.59  4488.4   430.8  4658.6  425.56  4712.3  421.68  4748.6  416.71
  4763.8  416.21  4838.7  414.74  4927.8  416.89  4978.8  416.98  4987.9  405.48
  4989.9  404.98  5006.3  405.48  5018.9  406.82  5028.9  411.42  5034.7  416.55
  5039.7  412.36  5048.9  416.58    5126   416.3  5328.9  415.38  5499.1  416.84
  5918.9  416.59  6018.9  417.97  6368.9  418.23  6418.9  417.86  6428.9  415.64
  6458.9  417.82  6838.9  419.18  6998.9  421.28  7138.9   424.9  7382.4  435.77
#Mann= 7 ,-1 , 0
  4326.2     .05       0  4712.3     .12       0  4927.8      .1       0
  4987.9     .07       0  5006.3      .1       0    5126     .12       0
  5499.1     .05       0
Bank Sta=4987.9,5006.3
XS Rating Curve= 0 ,0
Exp/Cntr=0.3,0.1

Type RM Length L Ch R = 1 ,11876   ,1282,1282,1282
BEGIN DESCRIPTION:
Mapping XS 71aa6aee
END DESCRIPTION:
XS GIS Cut Line= 3
      2714944.18      6922134.73      2714225.42      6922100.01
      2711871.24      6922089.59
#Sta/Elev= 30
  4292.3  431.62  4410.6  429.49  4650.9  420.83    4701  421.04    4731   417.9
    4751  417.38  4881.2  415.35  4972.4  416.02  4991.3  414.61  4999.9  405.04
  5001.9  404.54  5018.4  405.04  5021.3  405.07  5041.3  415.96  5173.6  415.31
  5291.3  414.92  5301.3  413.96  5311.3  415.59  5349.8  415.56  5401.3  416.47
  5751.3   416.3  5841.3  415.37  6251.3   416.4  6481.3  414.87  6761.3  417.43
  7001.3  423.91  7051.3  426.62  7141.3  433.96  7271.3  441.41  7366.1  443.61
#Mann= 6 ,-1 , 0
  4292.3     .05       0  4972.4      .1       0  4999.9     .07       0
  5018.4      .1       0  5173.6     .12       0  5349.8     .05       0
Bank Sta=4999.9,5018.4
XS Rating Curve= 0 ,0
Exp/Cntr=0.3,0.1

Type RM Length L Ch R = 1 ,10594   ,1647,1647,1647
BEGIN DESCRIPTION:
Mapping XS 11b31d9c
END DESCRIPTION:
XS GIS Cut Line= 3
      2714841.72      6921225.01      2713782.71      6921304.87
      2711876.45      6921933.34
#Sta/Elev= 30
  3933.1  430.45  4029.1  429.67  4159.5  427.14  4345.1  419.19  4470.3  415.82
  4560.6  414.84  4941.5  414.59  4951.7  413.42  4961.7  408.66  4971.8  405.28
  4981.7  404.81  4983.7  404.31  5000.2  404.81  5012.7  407.75  5023.2  415.29
  5087.4  414.83  5140.6  414.61  5244.4  412.02    5297  411.74  5423.4   414.4
    5538  414.32  5865.9  414.81  5949.8  413.51  6051.3   413.9  6437.7  418.67
    6623  422.56  6771.1  427.81  6850.6  432.98  6960.7  437.15  7002.3   440.5
#Mann= 7 ,-1 , 0
  3933.1     .05       0  4941.5     .12       0  4981.7     .07       0
  5000.2     .12       0  5087.4      .1       0  5140.6     .12       0
    5538     .05       0
Bank Sta=4981.7,5000.2
XS Rating Curve= 0 ,0
Exp/Cntr=0.3,0.1

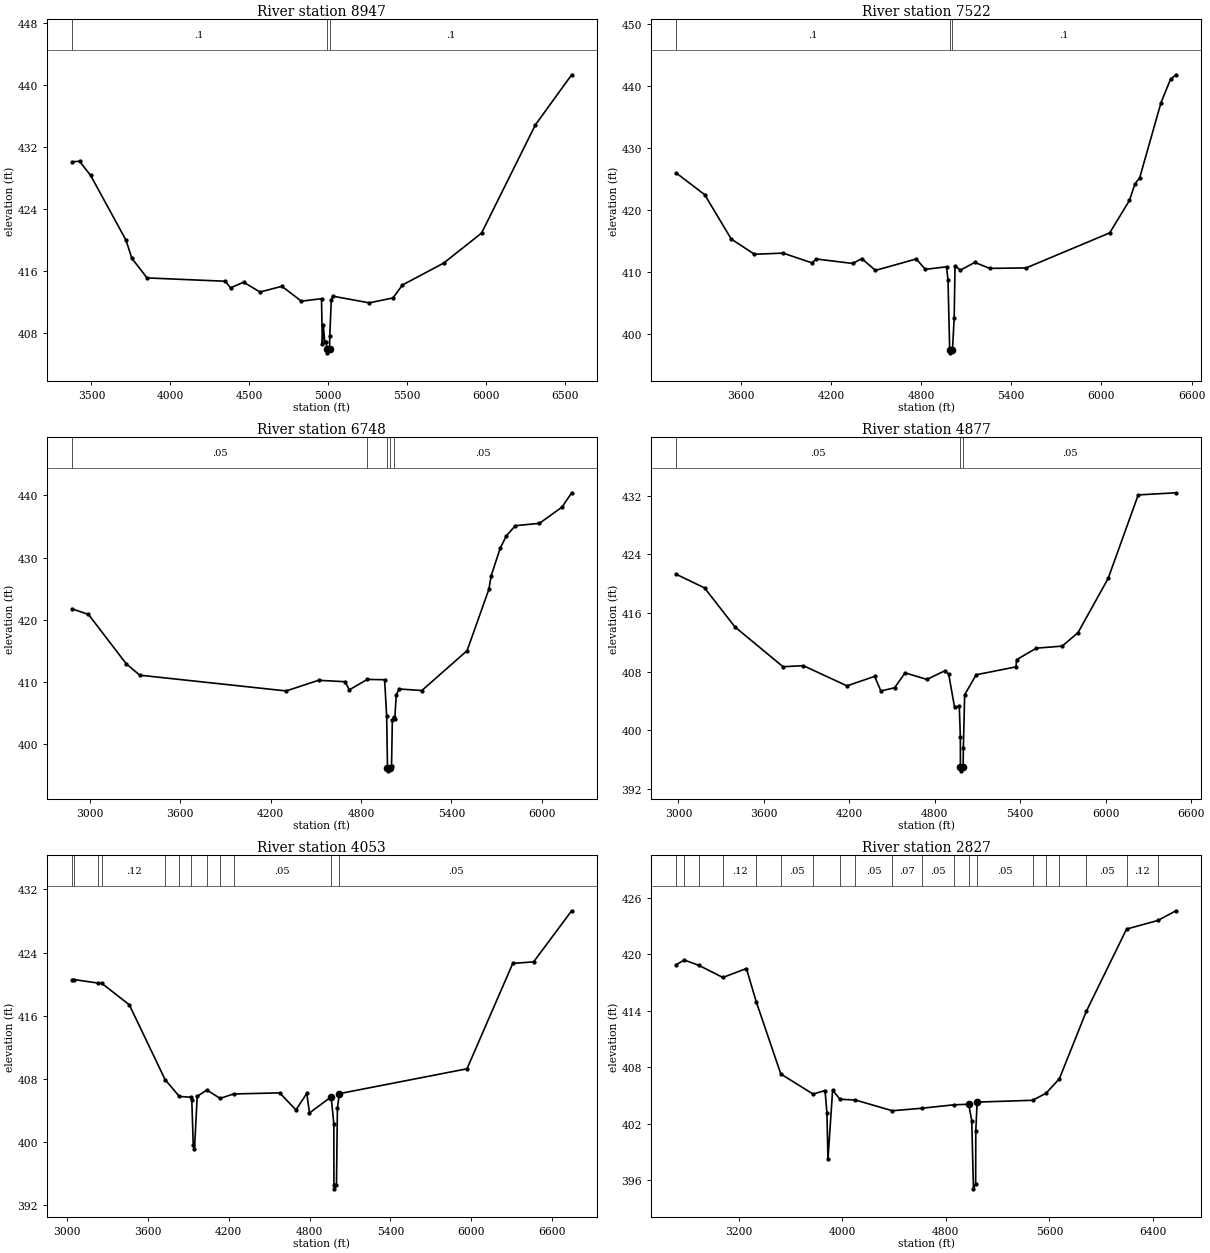
Type RM Length L Ch R = 1 ,8947    ,1425,1425,1425
BEGIN DESCRIPTION:
Mapping XS 23b0f6ab
END DESCRIPTION:
XS GIS Cut Line= 3
      2714722.47      6921133.05      2713172.99      6920633.92
      2711636.51      6920746.77
#Sta/Elev= 30
  3375.7  430.15  3424.5  430.21  3494.7  428.39  3718.7  420.04  3756.5  417.68
  3852.7  415.16  4349.4  414.73  4381.5  413.87  4464.6  414.61  4568.6  413.34
  4707.4  414.08  4830.4  412.16  4958.4  412.48  4963.9  406.57  4969.2  409.13
  4979.4  406.84  4989.9  406.91  4990.9  405.99  4992.9  405.49  5009.5  405.99
  5010.6  407.61  5020.6  412.32  5028.8  412.81  5261.3  411.94  5411.7  412.58
  5471.8  414.25  5732.5  417.07  5973.2  420.95  6314.1  434.91  6544.2  441.38
#Mann= 3 ,-1 , 0
  3375.7      .1       0  4990.9     .07       0  5009.5      .1       0
Bank Sta=4990.9,5009.5
XS Rating Curve= 0 ,0
Exp/Cntr=0.3,0.1

Type RM Length L Ch R = 1 ,7522    ,774,774,774
BEGIN DESCRIPTION:
Mapping XS 3e360e49
END DESCRIPTION:
XS GIS Cut Line= 3
      2714943.83      6919926.45      2713138.27       6919726.8
      2711671.27      6920078.36
#Sta/Elev= 30
  3170.4  425.95  3360.4  422.44    3537  415.28  3691.4  412.82  3882.5     413
  4073.7  411.43  4103.9  412.05  4345.3  411.33  4405.7  412.11  4496.3  410.21
  4767.9  412.06  4828.3  410.38  4969.1  410.79  4979.2  408.62  4990.2   397.4
  4992.2   396.9    5009   397.4  5020.1   402.5  5025.9  410.95  5061.3  410.25
  5157.1   411.5  5256.7  410.54  5498.4  410.61  6054.9  416.27  6186.1  421.51
    6223   424.2  6254.1  425.15  6396.3  437.31  6459.8  441.09  6495.5   441.8
#Mann= 3 ,-1 , 0
  3170.4      .1       0  4990.2     .07       0    5009      .1       0
Bank Sta=4990.2,5009
XS Rating Curve= 0 ,0
Exp/Cntr=0.3,0.1

Type RM Length L Ch R = 1 ,6748    ,1871,1871,1871
BEGIN DESCRIPTION:
Mapping XS f4084a2f
END DESCRIPTION:
XS GIS Cut Line= 4
      2714745.87      6918924.02      2713162.57      6919028.19
      2712669.52      6919257.36      2711482.05      6919292.08
#Sta/Elev= 30
  2879.6  421.77  2989.7  420.87  3240.2  412.96  3330.4  411.11  4302.5  408.58
  4517.7  410.29  4693.5  410.06  4721.9  408.76  4841.3  410.43  4956.3  410.38
  4969.8  404.51  4975.3  396.25  4977.3  395.75  4994.1  396.25  5002.1  396.51
  5007.6  403.92  5017.1  404.41  5023.5  404.02  5033.6  407.99  5053.6  408.89
  5203.6  408.65  5503.8  415.05  5648.4   424.9  5663.8   427.1  5723.8   431.5
  5763.9  433.46  5823.9  435.12    5984  435.49    6134   438.1    6198   440.4
#Mann= 5 ,-1 , 0
  2879.6     .05       0  4841.3      .1       0  4975.3     .07       0
  4994.1      .1       0  5017.1     .05       0
Bank Sta=4975.3,4994.1
XS Rating Curve= 0 ,0
Exp/Cntr=0.3,0.1

Type RM Length L Ch R = 1 ,4877    ,824,824,824
BEGIN DESCRIPTION:
Mapping XS 5a321424
END DESCRIPTION:
XS GIS Cut Line= 3
      2714801.42      6918243.46      2712829.24      6917840.69
      2711343.15      6918021.24
#Sta/Elev= 30
  2983.4  421.27  3182.8  419.41  3397.2  414.07    3734  408.66  3876.9   408.8
  4183.1  406.05    4377  407.34  4421.5  405.35  4517.4  405.79  4591.3  407.82
  4744.4  406.93  4870.9  408.11  4897.5  407.63  4938.4  403.17  4971.9  403.26
  4979.2  399.14  4979.9  394.96  4981.9  394.46  4998.8  394.96  5000.4  397.59
  5009.6  404.83  5090.2  407.56  5369.6  408.64  5374.6  409.62  5513.3  411.19
  5694.6  411.47  5805.4   413.3    6017  420.69  6228.5  432.09  6493.3  432.38
#Mann= 3 ,-1 , 0
  2983.4     .05       0  4979.9     .04       0  4998.8     .05       0
Bank Sta=4979.9,4998.8
XS Rating Curve= 0 ,0
Exp/Cntr=0.3,0.1

Type RM Length L Ch R = 1 ,4053    ,1226,1226,1226
BEGIN DESCRIPTION:
Mapping XS 0fce9946
END DESCRIPTION:
XS GIS Cut Line= 4
      2714870.94      6917500.42      2714051.46      6917167.08
      2712968.13      6917069.86      2711281.84      6917486.22
#Sta/Elev= 30
  3035.5  420.56  3049.1  420.59  3230.4  420.14  3258.2   420.1  3461.9  417.39
  3727.2  407.92  3833.1  405.78  3916.1  405.68  3925.7  405.37  3936.5  399.62
  3945.7   399.1  3965.8  405.78  4036.9  406.59  4136.1  405.53  4235.3  406.09
  4578.3  406.23  4698.8  404.06  4779.1  406.17  4799.2  403.69  4959.8  405.72
  4979.9  402.32  4980.5  394.57  4982.5  394.07  4999.4  394.57  5006.4  404.26
  5020.4  406.13    5968  409.28  6307.9  422.63  6462.4  422.83  6744.8   429.3
#Mann= 12 ,-1 , 0
  3035.5     .05       0  3049.1     .12       0  3230.4      .1       0
  3258.2     .12       0  3727.2     .05       0  3833.1     .12       0
  3916.1      .1       0  4036.9     .12       0  4136.1      .1       0
  4235.3     .05       0  4959.8     .04       0  5020.4     .05       0
Bank Sta=4959.8,5020.4
XS Rating Curve= 0 ,0
Exp/Cntr=0.3,0.1

Type RM Length L Ch R = 1 ,2827    ,746,746,746
BEGIN DESCRIPTION:
Mapping XS bdaa1f47
END DESCRIPTION:
XS GIS Cut Line= 3
      2714975.47      6917229.55      2713131.76      6915891.04
      2711610.93      6916333.74
#Sta/Elev= 30
  2715.7  418.88  2778.8  419.37    2889  418.82    3077  417.52  3258.8  418.47
  3334.3  414.96  3524.8  407.27  3774.2  405.14  3866.3  405.52    3881  403.15
    3889  398.21  3925.1  405.57  3981.4  404.59  4101.7  404.51  4385.8  403.37
  4617.3  403.64  4861.1     404  4976.5  404.06    5000  402.31  5013.4  395.08
  5030.3  395.58  5031.3  401.22  5041.7  404.29  5469.6  404.48  5573.5  405.22
  5677.3  406.77    5885  413.91  6196.5  422.66  6438.5  423.57    6578   424.6
#Mann= 20 ,-1 , 0
  2715.7     .05       0  2778.8     .12       0    2889      .1       0
    3077     .12       0  3334.3     .12       0  3524.8     .05       0
  3774.2      .1       0  3981.4     .07       0  4101.7     .05       0
  4385.8     .07       0  4617.3     .05       0  4861.1     .05       0
  4976.5     .04       0  5041.7     .05       0  5469.6      .1       0
  5573.5     .12       0  5677.3      .1       0    5885     .05       0
  6196.5     .12       0  6438.5     .05       0
Bank Sta=4976.5,5041.7
XS Rating Curve= 0 ,0
Exp/Cntr=0.3,0.1

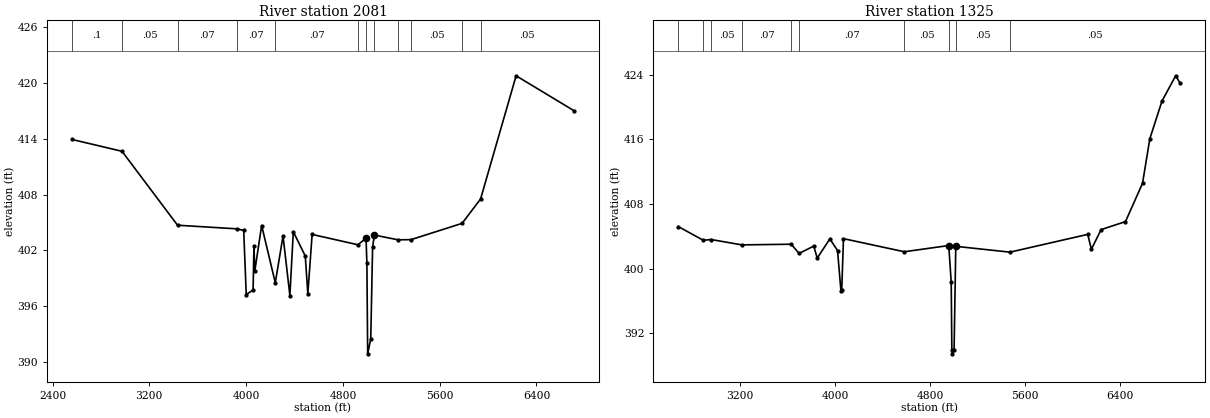
Type RM Length L Ch R = 1 ,2081    ,756,756,756
BEGIN DESCRIPTION:
Mapping XS 1819e63d
END DESCRIPTION:
XS GIS Cut Line= 3
      2714922.57      6916930.11      2713207.28      6915159.27
      2711623.94      6915728.71
#Sta/Elev= 30
  2561.6  413.93  2974.4  412.66  3433.4  404.71  3926.2  404.32  3980.1  404.15
  4001.2  397.26  4057.8  397.74  4064.8  402.46    4072  399.81  4128.5  404.68
  4241.3  398.52  4305.3  403.56  4361.9  397.15  4390.2  404.01  4489.2   401.4
  4510.3  397.33  4545.8  403.72  4924.1  402.61  4991.3  403.31  4998.3  400.69
    5005  390.88  5030.3  392.47  5045.6  402.36  5060.2  403.65  5256.9  403.14
    5363  403.16  5785.1  404.91  5938.1  407.53  6231.7  420.78  6709.6  417.03
#Mann= 12 ,-1 , 0
  2561.6      .1       0  2974.4     .05       0  3433.4     .07       0
  3926.2     .07       0  4241.3     .07       0  4924.1     .05       0
  4991.3     .04       0  5060.2     .05       0  5256.9     .07       0
    5363     .05       0  5785.1      .1       0  5938.1     .05       0
Bank Sta=4991.3,5060.2
XS Rating Curve= 0 ,0
Exp/Cntr=0.3,0.1

Type RM Length L Ch R = 1 ,1325    ,0,0,0
BEGIN DESCRIPTION:
Mapping XS 15bec447
END DESCRIPTION:
XS GIS Cut Line= 3
      2714658.66      6916332.87      2713276.72      6914471.77
       2711415.6      6914895.38
#Sta/Elev= 30
  2681.2  405.18  2890.3   403.5  2956.9  403.59  3214.9  402.93  3630.7  403.01
  3696.8  401.87  3820.6  402.78  3849.8  401.29  3956.2  403.67  4020.8  402.23
  4050.1  397.17  4056.3  397.35  4070.9   403.7  4583.1  402.08  4957.6  402.85
  4978.4  398.29  4983.6  389.95  4985.6  389.45  5002.5  389.95  5016.9  402.75
  5473.2  402.03  6128.1  404.23  6158.9  402.39    6241  404.82  6446.1  405.81
  6589.7  410.55  6651.2  416.06  6753.7  420.73  6868.7  423.85    6908   422.9
#Mann= 10 ,-1 , 0
  2681.2     .05       0  2890.3     .12       0  2956.9     .05       0
  3214.9     .07       0  3630.7     .07       0  3696.8     .07       0
  4583.1     .05       0  4957.6    .035       0  5016.9     .05       0
  5473.2     .05       0
Bank Sta=4957.6,5016.9
XS Rating Curve= 0 ,0
Exp/Cntr=0.3,0.1

Chan Stop Cuts=-1
Use User Specified Reach Order=0
Composite Channel Slope=5