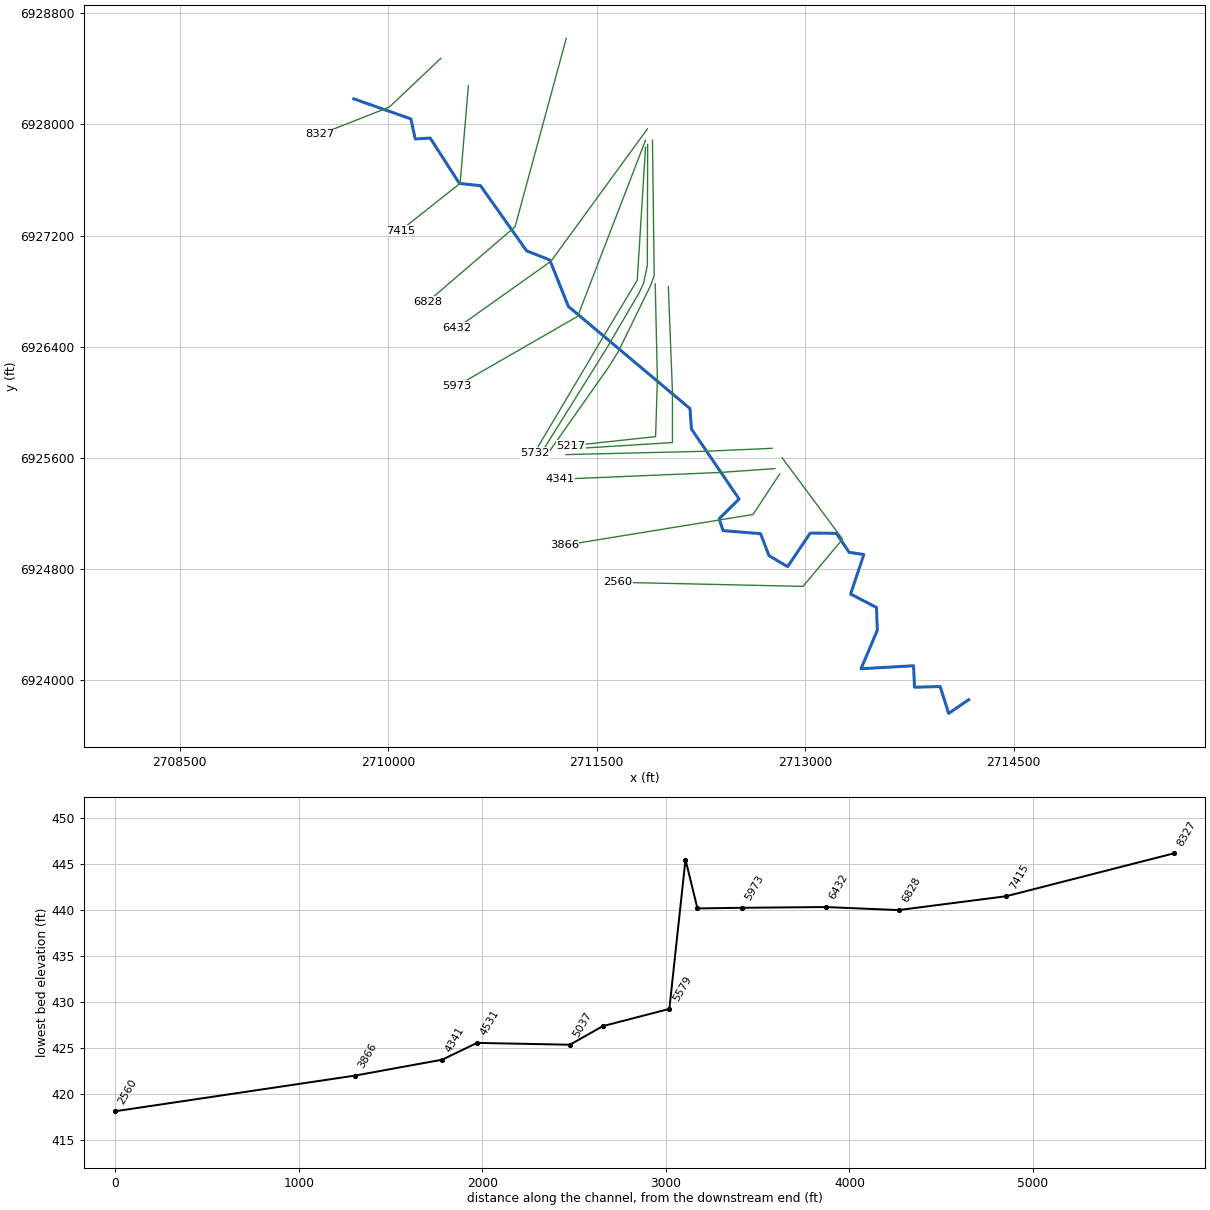
--- Wolf Creek T1.prj (project) ---

Proj Title=Wolf Creek T1 Base Level Engineering
Current Plan=p01
Default Exp/Contr=0.3,0.1
English Units
Geom File=g01
Flow File=f01
Plan File=p01
Y Axis Title=Elevation
X Axis Title(PF)=Main Channel Distance
X Axis Title(XS)=Station
BEGIN DESCRIPTION:
Wolf Creek T1
END DESCRIPTION:
DSS Export Rating Curves= 0
DSS Export Rating Curve Sorted= 0
DSS Export Volume Flow Curves= 0
DXF OffsetX= 0
DXF OffsetY= 0
DXF ScaleX= 1
DXF ScaleY= 10

--- Wolf Creek T1.p01 (plan) ---

Plan Title=Multiple Run
Short Identifier=Multiple
Geom File=g01
Flow File=f01
Subcritical Flow
K Sum by GR= 0
Std Step Tol= 0.01
Critical Tol= 0.01
Num of Std Step Trials= 20
Max Error Tol= 0.3
Flow Tol Ratio= 0.001
Split Flow NTrial= 30
Split Flow Tol= 0.02
Split Flow Ratio= 0.02
Log Output Level= 0
Friction Slope Method= 1
Unsteady Friction Slope Method= 2
Unsteady Bridges Friction Slope Method= 1
Parabolic Critical Depth
Global Vel Dist=  1 , 1 , 1
Global Log Level= 0
CheckData=True
Encroach Param= -1, 0, 0, 0
BEGIN DESCRIPTION:
Multiple Run
END DESCRIPTION:

--- Wolf Creek T1.f01 (steady flow) ---

Flow Title=Multiple
Number of Profiles=7
Profile Names=10-year,25-year,50-year,1pct_min,100-year,1pct_plu,500-year
River Rch & RM= Wolf Creek T1,Reach-1,8327
     624     831     998     594    1186    2366    1672
River Rch & RM= Wolf Creek T1,Reach-1,5579
     739     994    1200     718    1433    2860    2043
Boundary for River Rch & Prof#=Wolf Creek T1,Reach-1,1
Up Type=0
Dn Type=3
Dn Slope=0.005
Boundary for River Rch & Prof#=Wolf Creek T1,Reach-1,2
Up Type=0
Dn Type=3
Dn Slope=0.005
Boundary for River Rch & Prof#=Wolf Creek T1,Reach-1,3
Up Type=0
Dn Type=3
Dn Slope=0.005
Boundary for River Rch & Prof#=Wolf Creek T1,Reach-1,4
Up Type=0
Dn Type=3
Dn Slope=0.005
Boundary for River Rch & Prof#=Wolf Creek T1,Reach-1,5
Up Type=0
Dn Type=3
Dn Slope=0.005
Boundary for River Rch & Prof#=Wolf Creek T1,Reach-1,6
Up Type=0
Dn Type=3
Dn Slope=0.005
Boundary for River Rch & Prof#=Wolf Creek T1,Reach-1,7
Up Type=0
Dn Type=3
Dn Slope=0.005

--- Wolf Creek T1.g01 (geometry) ---

Geom Title=Existing Conditions
Program Version=4.10

River Reach=Wolf Creek T1   ,Reach-1
Reach XY= 30
      2709752.54       6928183.6      2710162.81      6928039.76
      2710194.06      6927895.23      2710302.13      6927901.74
      2710512.09      6927575.55      2710664.18      6927558.88
      2710995.59      6927090.43      2711162.55      6927024.63
      2711295.63      6926690.84      2712170.81      6925955.56
      2712181.48      6925808.56      2712524.26      6925304.84
      2712380.95      6925163.51      2712408.77      6925077.48
      2712678.71      6925055.72      2712739.26      6924897.34
      2712872.95      6924818.76      2713036.49      6925060.42
      2713224.57      6925057.93      2713315.94       6924921.4
      2713421.37      6924905.75      2713326.53      6924621.45
      2713512.63      6924524.79      2713518.44        6924361.
      2713401.52      6924083.84      2713778.98      6924105.61
      2713786.07      6923950.89      2713970.45      6923956.22
       2714031.5      6923762.96        2714176.        6923861.

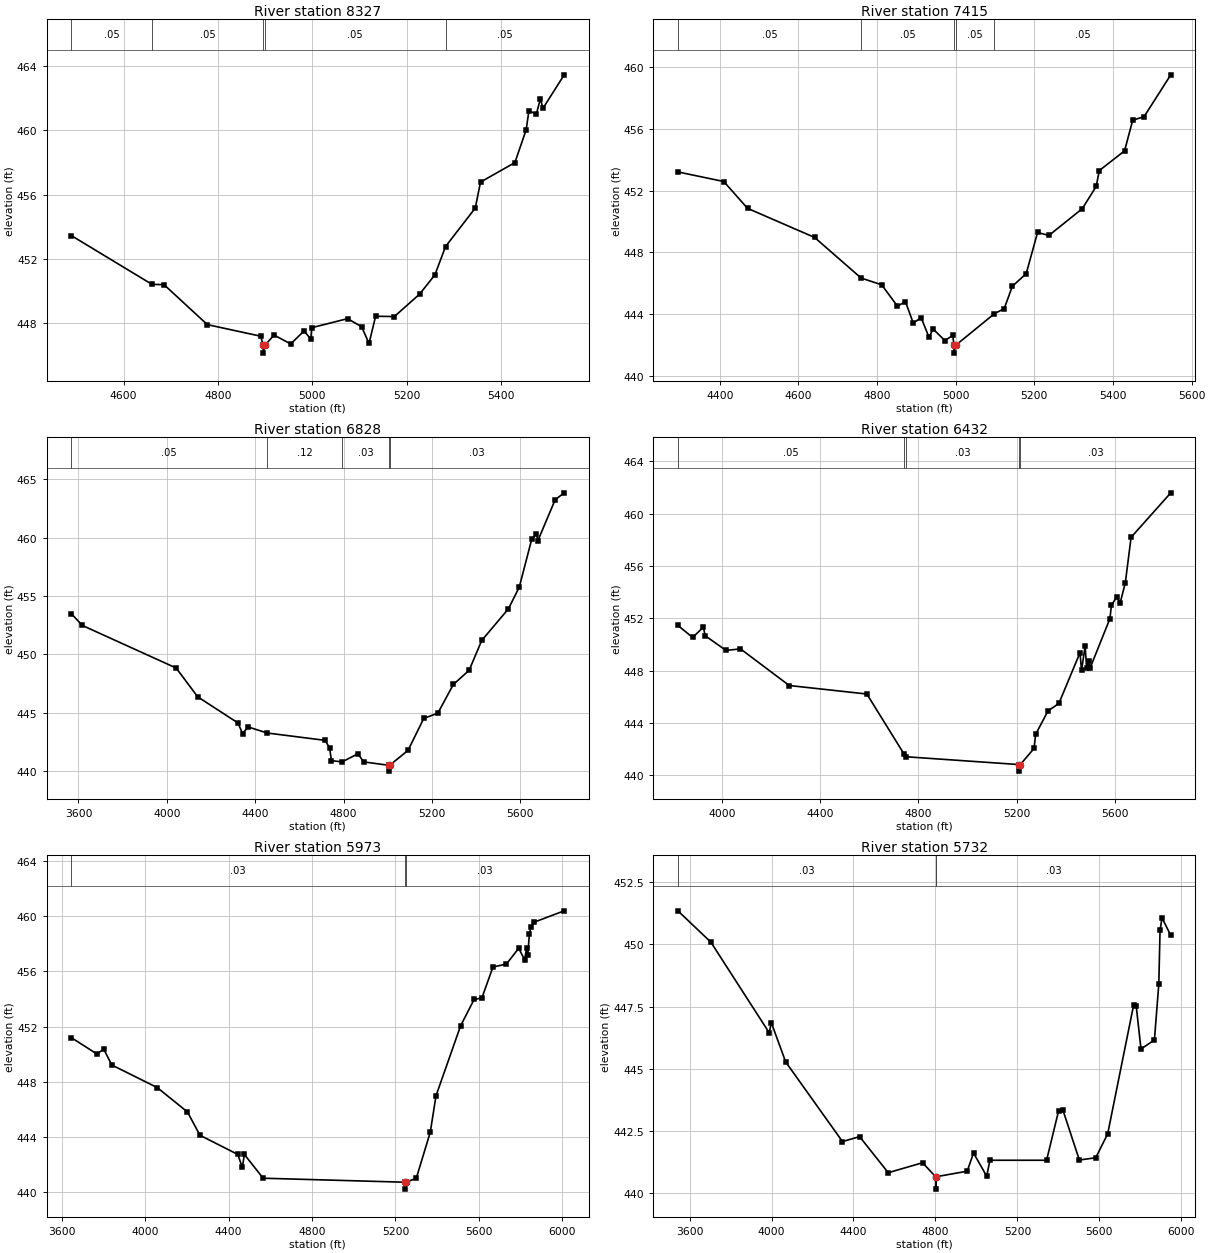
Type RM Length L Ch R = 1 ,8327    ,912,912,912
BEGIN DESCRIPTION:
Wolf Creek T1 5.0
END DESCRIPTION:
XS GIS Cut Line= 3
      2710378.99      6928475.66      2710007.86       6928124.4
      2709510.97       6927928.8
#Sta/Elev= 30
    4489  453.46    4660  450.43  4685.6  450.41  4777.4  447.93  4890.7  447.21
  4895.6  446.66  4895.8  446.16  4899.6  446.66    4919  447.28  4954.2  446.73
  4982.5  447.54  4996.7  447.03  4998.8  447.74  5074.7   448.3  5104.5   447.8
  5120.2  446.76  5134.2  448.45  5173.9  448.43  5227.7  449.83  5259.9  451.02
  5282.5  452.78  5345.5  455.17  5356.6  456.78  5429.5  457.99  5453.4  460.03
  5459.2  461.21  5474.9     461  5483.6  461.95    5489  461.36    5534  463.44
#Mann= 5 ,-1 , 0
    4489     .05       0    4660     .05       0  4895.6     .03       0
  4899.6     .05       0  5282.5     .05       0
Bank Sta=4895.6,4899.6
XS Rating Curve= 0 ,0
Exp/Cntr=0.3,0.1

Type RM Length L Ch R = 1 ,7415    ,587,587,587
BEGIN DESCRIPTION:
Mapping XS b0504bf4
END DESCRIPTION:
XS GIS Cut Line= 3
      2710576.72      6928277.39      2710517.03      6927575.66
      2710086.37      6927234.95
#Sta/Elev= 30
  4293.5   453.2  4410.3  452.58  4470.5  450.85  4641.1  448.97  4759.3  446.35
  4811.8  445.91  4851.9  444.53    4872  444.83    4892  443.44  4912.1  443.79
  4932.2  442.51  4942.2  443.07  4972.3  442.31  4992.4  442.64  4995.6     442
  4995.8   441.5  4999.6     442  5098.6  444.05  5123.2  444.37    5144  445.82
  5179.2  446.63  5208.1  449.29    5237   449.1  5321.9  450.83  5357.1  452.26
  5365.2  453.29  5429.3  454.56  5450.1  456.54    5479  456.77  5546.9  459.47
#Mann= 5 ,-1 , 0
  4293.5     .05       0  4759.3     .05       0  4995.6     .03       0
  4999.6     .05       0  5098.6     .05       0
Bank Sta=4995.6,4999.6
XS Rating Curve= 0 ,0
Exp/Cntr=0.3,0.1

Type RM Length L Ch R = 1 ,6828    ,396,396,396
BEGIN DESCRIPTION:
Mapping XS af27ef57
END DESCRIPTION:
XS GIS Cut Line= 3
      2711280.89      6928619.12      2710912.56      6927263.95
      2710285.03      6926725.06
#Sta/Elev= 30
  3567.6  453.49  3617.5  452.48  4042.3  448.83  4139.9  446.36  4322.1  444.12
  4342.9  443.21  4368.3  443.78    4454  443.26  4716.1  442.63  4736.6  442.01
  4745.5  440.89  4792.9  440.78  4864.8  441.47  4892.1  440.78  5004.9  440.49
  5005.2  439.99  5008.9  440.49  5092.1  441.77  5163.4  444.51  5227.1  444.96
  5297.3  447.42  5368.6  448.63  5425.7  451.19  5546.4   453.9  5595.8  455.77
  5652.8  459.92  5673.7  460.29  5680.3  459.76  5758.3  463.26  5799.1  463.85
#Mann= 5 ,-1 , 0
  3567.6     .05       0    4454     .12       0  4792.9     .03       0
  5004.9     .03       0  5008.9     .03       0
Bank Sta=5004.9,5008.9
XS Rating Curve= 0 ,0
Exp/Cntr=0.3,0.1

Type RM Length L Ch R = 1 ,6432    ,459,459,459
BEGIN DESCRIPTION:
Mapping XS d3422d54
END DESCRIPTION:
XS GIS Cut Line= 3
       2711864.3       6927967.5      2711170.95      6927015.46
       2710494.6      6926535.67
#Sta/Elev= 30
  3820.7  451.45  3880.8  450.53  3924.9  451.33  3931.1  450.67  4016.8  449.54
  4075.5  449.66  4274.1  446.86  4590.1  446.21  4741.4  441.63  4747.8  441.42
    5211  440.82  5211.2  440.32    5215  440.82  5271.1  442.06  5277.2  443.12
  5327.7  444.92    5372  445.49  5458.1  449.37  5464.2  448.01    5479  449.88
  5485.1  448.16  5493.8  448.71  5499.9  448.23  5579.9  451.97    5586  452.98
  5606.9  453.62  5621.7  453.18  5642.6  454.71    5666  458.18  5827.7  461.58
#Mann= 5 ,-1 , 0
  3820.7     .05       0  4741.4     .12       0  4747.8     .03       0
    5211     .03       0    5215     .03       0
Bank Sta=5211,5215
XS Rating Curve= 0 ,0
Exp/Cntr=0.3,0.1

Type RM Length L Ch R = 1 ,5973    ,241,241,241
BEGIN DESCRIPTION:
Mapping XS 749c69a2
END DESCRIPTION:
XS GIS Cut Line= 3
      2711850.99      6927885.98      2711362.84      6926619.06
      2710491.48      6926117.74
#Sta/Elev= 30
  3646.2  451.21  3769.4  450.02  3801.6  450.38    3840  449.23  4058.4  447.59
  4202.9  445.83  4262.9  444.14  4444.6  442.75    4466  441.81    4476  442.75
  4565.9  441.03  5247.5  440.74  5247.7  440.24  5251.5  440.74  5300.2  441.03
  5367.3  444.37  5394.7     447  5512.5  452.06  5577.2  453.97  5614.6  454.08
  5667.7  456.32  5732.4  456.54  5791.3  457.68  5819.4  456.85  5828.7  457.67
  5834.5  457.17  5842.5  458.72  5850.2  459.25  5865.5  459.57  6009.2  460.39
#Mann= 3 ,-1 , 0
  3646.2     .03       0  5247.5     .03       0  5251.5     .03       0
Bank Sta=5247.5,5251.5
XS Rating Curve= 0 ,0
Exp/Cntr=0.3,0.1

Type RM Length L Ch R = 1 ,5732    ,65,65,65
BEGIN DESCRIPTION:
Mapping XS 86cd4c41
END DESCRIPTION:
XS GIS Cut Line= 5
        2711851.      6927835.95      2711813.58      6927231.75
      2711791.31      6926879.02       2711537.4      6926455.84
      2711050.98      6925635.97
#Sta/Elev= 30
  3543.1  451.35  3704.1  450.09  3988.9  446.45  3998.9  446.86  4069.1  445.28
  4346.4  442.08  4429.8  442.28  4569.6  440.83  4737.2  441.23  4800.8  440.67
    4801  440.17  4804.8  440.67  4954.9  440.89    4986  441.62  5050.2  440.69
  5065.9  441.33  5342.6  441.33    5401  443.31  5422.5  443.34  5502.4  441.34
  5582.4  441.43  5640.7  442.39  5767.5  447.57  5780.1  447.52  5803.3   445.8
  5868.8  446.16  5890.2   448.4  5896.3  450.56  5905.8  451.07  5948.7  450.36
#Mann= 3 ,-1 , 0
  3543.1     .03       0  4800.8     .03       0  4804.8     .03       0
Bank Sta=4800.8,4804.8
XS Rating Curve= 0 ,0
Exp/Cntr=0.3,0.1

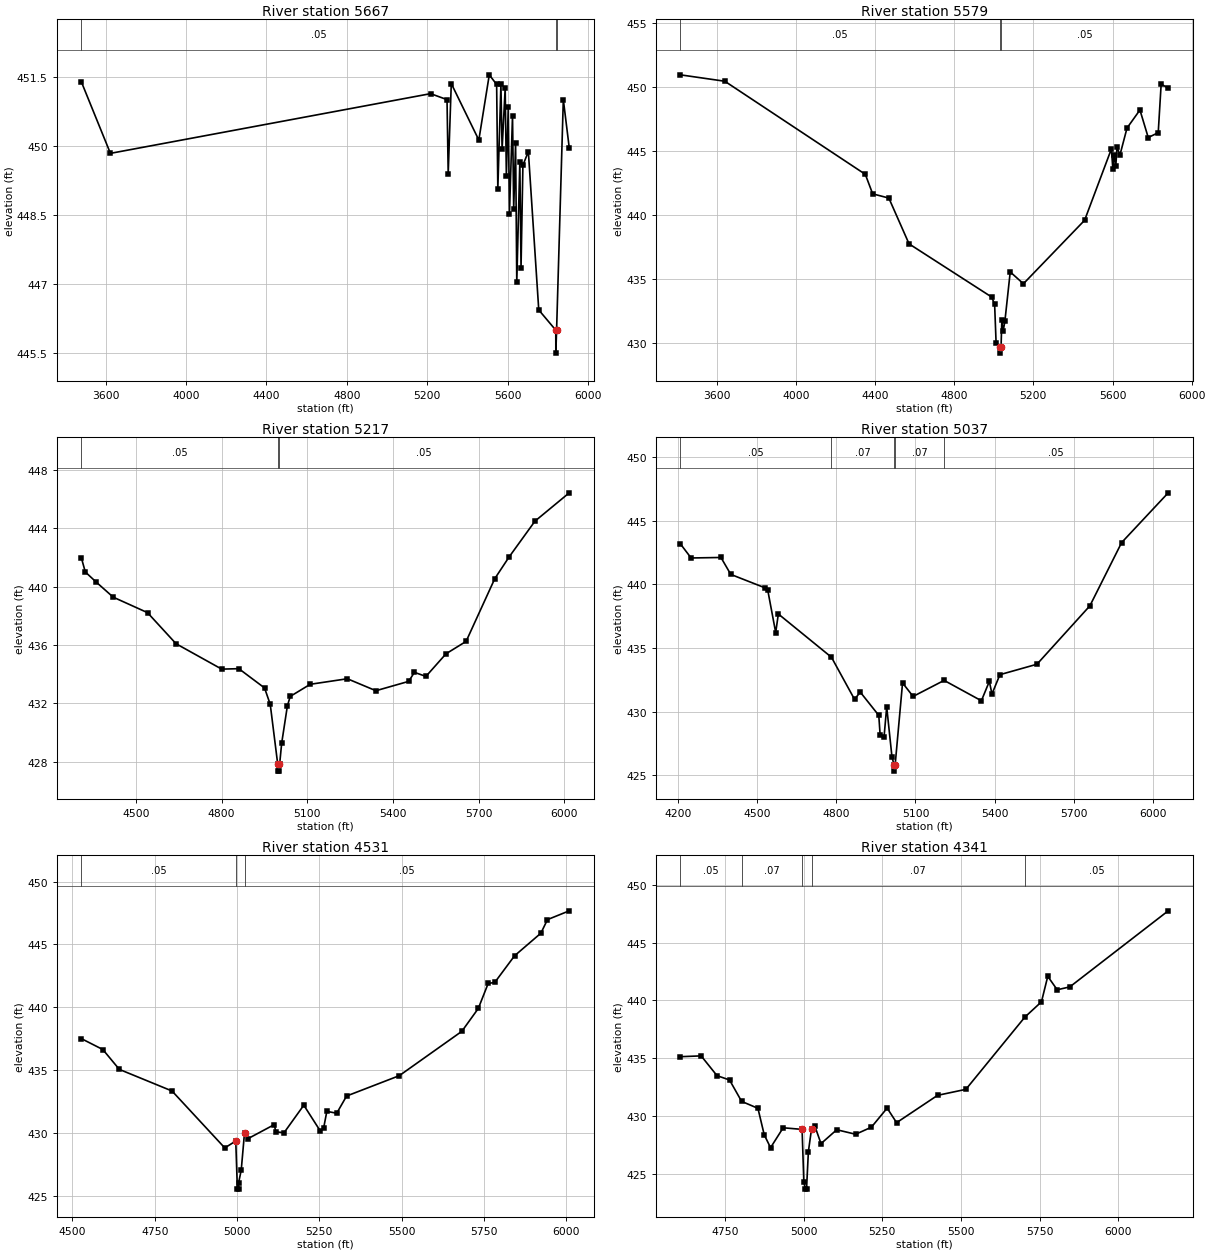
Type RM Length L Ch R = 1 ,5667    ,88,88,88
BEGIN DESCRIPTION:
Mapping XS ed996811
END DESCRIPTION:
XS GIS Cut Line= 6
      2711866.14      6927855.82      2711864.09        6926986.
      2711836.88      6926857.32      2711804.33      6926787.87
      2711578.63      6926401.59      2711101.02      6925636.04
#Sta/Elev= 30
  3479.2   451.4    3624  449.84  5217.1  451.14  5298.8  451.01  5304.7   449.4
    5320  451.36  5457.1  450.13  5509.1  451.55  5545.7  451.34  5551.6  449.06
    5567  451.34  5572.9  449.93  5588.2  451.26  5594.1  449.35  5603.5  450.84
  5609.4  448.52  5624.7  450.66  5630.6  448.63    5640  450.07  5645.9  447.03
  5661.1  449.65  5667.1  447.35  5676.4  449.58  5703.5  449.88  5755.3  446.43
    5840  445.99  5840.2  445.49    5844  445.99  5877.5  451.01    5907  449.96
#Mann= 3 ,-1 , 0
  3479.2     .05       0    5840     .04       0    5844     .05       0
Bank Sta=5840,5844
XS Rating Curve= 0 ,0
Exp/Cntr=0.3,0.1

Type RM Length L Ch R = 1 ,5579    ,362,362,362
BEGIN DESCRIPTION:
Mapping XS c9945f10
END DESCRIPTION:
XS GIS Cut Line= 6
        2711901.      6927885.99      2711913.49      6926911.78
       2711885.6      6926837.13      2711653.83      6926363.18
      2711583.52       6926251.2      2711151.02      6925636.02
#Sta/Elev= 30
  3415.7  450.93  3640.7  450.43  4350.8  443.17  4387.9  441.65  4469.7  441.32
  4571.8  437.75  4988.6  433.61  5004.2  433.06  5011.7  430.02  5032.8  429.73
    5033  429.23  5036.8  429.73  5040.7  431.81  5047.1  430.93    5056   431.7
  5083.1  435.56  5149.7  434.64    5459  439.59  5594.3  445.15  5601.9  443.56
    5608   444.7  5616.7  443.84  5622.8  445.29  5637.6  444.68  5673.3  446.78
  5738.6  448.19  5780.5  446.04    5831  446.42  5845.8   450.2  5881.5   449.9
#Mann= 3 ,-1 , 0
  3415.7     .05       0  5032.8     .04       0  5036.8     .05       0
Bank Sta=5032.8,5036.8
XS Rating Curve= 0 ,0
Exp/Cntr=0.3,0.1

Type RM Length L Ch R = 1 ,5217    ,180,180,180
BEGIN DESCRIPTION:
Mapping XS 62b5a0d1
END DESCRIPTION:
XS GIS Cut Line= 4
      2711920.75       6926852.8      2711936.38      6926160.05
      2711923.36       6925753.8      2711316.63       6925688.7
#Sta/Elev= 30
  4308.2  441.99  4322.1  441.01    4360  440.32    4420  439.28  4540.1  438.22
  4640.1  436.09  4800.1  434.35  4860.1  434.38  4950.2  433.06  4970.2  431.93
  4996.2  427.86  4996.4  427.36  4999.9  427.36  5000.2  427.86  5003.2  427.86
  5010.2  429.27  5030.2  431.83  5040.2  432.48  5110.2  433.31  5240.3  433.69
  5340.4  432.87  5455.2  433.51  5475.3  434.13  5515.6  433.85    5586   435.4
  5656.4  436.25  5756.9  440.55  5807.2  442.04  5897.7  444.49  6017.8  446.43
#Mann= 3 ,-1 , 0
  4308.2     .05       0  4996.2     .05       0  5000.2     .05       0
Bank Sta=4996.2,5000.2
XS Rating Curve= 0 ,0
Exp/Cntr=0.3,0.1

Type RM Length L Ch R = 1 ,5037    ,506,506,506
BEGIN DESCRIPTION:
Mapping XS 5f1a6ccc
END DESCRIPTION:
XS GIS Cut Line= 4
      2712015.06      6926832.02      2712044.67      6926075.78
      2712044.67      6925711.19      2711319.97      6925666.12
#Sta/Elev= 30
  4209.5   443.2  4250.5  442.08  4363.5  442.12  4400.7  440.79  4530.8  439.73
  4540.8  439.54  4570.8  436.22  4580.8  437.68  4781.9  434.28  4869.3  430.97
    4891  431.54  4961.1  429.71  4966.2  428.17  4981.1  428.03  4991.1  430.38
  5011.1  426.43  5019.1  425.83  5019.3  425.33  5023.1  425.83  5051.1  432.26
  5091.1   431.2  5208.5  432.46  5349.6  430.86  5379.7  432.38  5389.7  431.39
  5419.7  432.91    5560  433.73  5760.4  438.32  5880.6  443.29    6057   447.2
#Mann= 5 ,-1 , 0
  4209.5     .05       0  4781.9     .07       0  5019.1     .05       0
  5023.1     .07       0  5208.5     .05       0
Bank Sta=5019.1,5023.1
XS Rating Curve= 0 ,0
Exp/Cntr=0.3,0.1

Type RM Length L Ch R = 1 ,4531    ,190,190,190
BEGIN DESCRIPTION:
Mapping XS 35d2299a
END DESCRIPTION:
XS GIS Cut Line= 3
      2712761.36      6925669.76      2712292.59      6925648.93
      2711279.81      6925624.65
#Sta/Elev= 30
    4527  437.51  4592.4  436.64  4642.5  435.06  4802.6  433.34  4962.8  428.81
  4996.2  429.36  5001.1  425.53  5004.6  425.53  5004.8  426.03  5012.8  427.04
  5022.8  430.02  5032.8  429.54  5112.9  430.66  5118.1  430.09  5142.9  430.02
  5202.9  432.21  5252.9  430.16  5262.9  430.36  5272.9  431.72  5302.9  431.57
  5332.9  432.94    5493  434.56    5683  438.09    5733  439.91    5763   441.9
    5783  441.98  5843.1   444.1  5923.1   445.9  5943.1  446.98  6009.3  447.68
#Mann= 3 ,-1 , 0
    4527     .05       0  4996.2     .05       0  5022.8     .05       0
Bank Sta=4996.2,5022.8
XS Rating Curve= 0 ,0
Exp/Cntr=0.3,0.1

Type RM Length L Ch R = 1 ,4341    ,475,475,475
BEGIN DESCRIPTION:
Mapping XS 8c840039
END DESCRIPTION:
XS GIS Cut Line= 3
      2712782.15      6925523.92      2712389.81      6925496.15
      2711233.55      6925447.54
#Sta/Elev= 30
  4607.9  435.14  4674.2  435.21  4724.7   433.5  4764.4  433.13  4802.8  431.28
  4854.7  430.68  4874.7  428.39  4894.8  427.28  4934.9     429    4995  428.86
  5000.6  424.29  5005.6   423.7  5009.1   423.7    5015  426.94  5025.1  428.92
  5035.1  429.18  5055.1  427.63  5105.1  428.83  5165.2  428.44  5215.2  429.05
  5265.3   430.7  5295.3  429.44  5425.4   431.8  5515.5  432.32    5703  438.56
  5755.7  439.88  5775.7  442.08  5805.7  440.92  5845.8  441.17  6158.5  447.74
#Mann= 5 ,-1 , 0
  4607.9     .05       0  4802.8     .07       0    4995     .04       0
  5025.1     .07       0    5703     .05       0
Bank Sta=4995,5025.1
XS Rating Curve= 0 ,0
Exp/Cntr=0.3,0.1

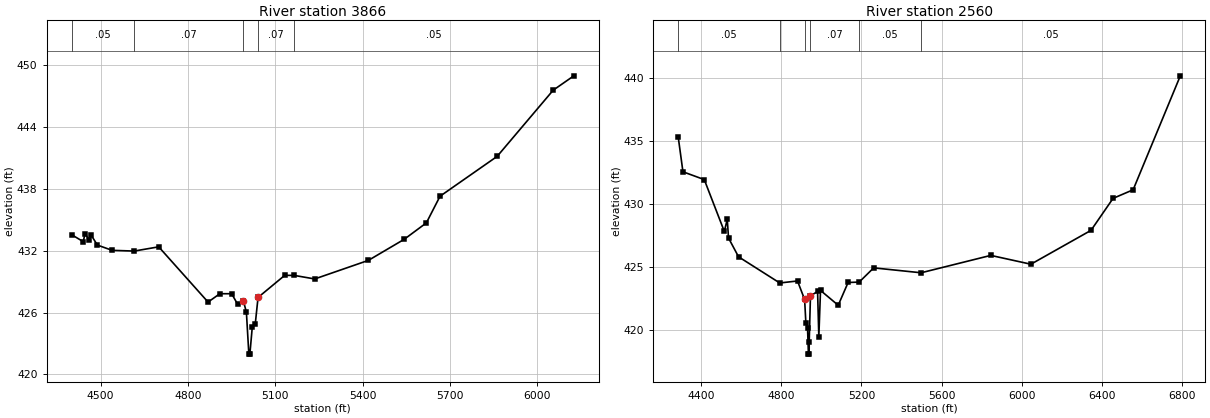
Type RM Length L Ch R = 1 ,3866    ,1306,1306,1306
BEGIN DESCRIPTION:
Mapping XS bfff3437
END DESCRIPTION:
XS GIS Cut Line= 3
      2712815.59       6925484.5      2712624.59      6925193.66
      2711266.05       6924972.3
#Sta/Elev= 30
  4401.3  433.53  4440.7  432.86  4446.7  433.63  4461.8  433.01  4467.8   433.5
  4489.2  432.53  4540.1  432.02  4615.7  431.95  4699.9  432.36  4869.4  427.01
  4909.9  427.82  4950.5  427.82  4970.7  426.81    4991  427.11  5001.1  426.01
  5009.5  421.97    5013  421.97  5021.4  424.64  5031.5  424.89  5041.1  427.46
  5132.8   429.6    5166  429.59  5235.7  429.25  5420.1  431.05  5543.1  433.09
  5619.2  434.68  5666.1  437.26  5862.3  441.12  6054.8  447.53  6125.7  448.92
#Mann= 5 ,-1 , 0
  4401.3     .05       0  4615.7     .07       0    4991     .04       0
  5041.1     .07       0    5166     .05       0
Bank Sta=4991,5041.1
XS Rating Curve= 0 ,0
Exp/Cntr=0.3,0.1

Type RM Length L Ch R = 1 ,2560    ,0,0,0
BEGIN DESCRIPTION:
Mapping XS 14a50aa4
END DESCRIPTION:
XS GIS Cut Line= 4
      2712834.09        6925601.      2713268.48      6925016.17
      2712984.03       6924676.6      2711650.62      6924705.99
#Sta/Elev= 30
  4286.1  435.32  4309.6  432.57    4416  431.95  4516.1  427.83  4530.7   428.8
    4537  427.31    4587  425.82  4792.7  423.74  4881.2   423.9  4916.7  422.43
  4922.9  420.59  4931.3  420.19  4935.7  418.09  4939.3  418.09  4939.6  419.09
  4945.9  422.71  4981.4  423.07  4987.6  419.47    4996  423.15  5084.3  421.97
  5133.7  423.78  5188.9  423.81  5261.3  424.94  5497.9  424.55  5845.7  425.93
  6045.7  425.23  6345.8  427.92  6455.8  430.46  6555.9  431.14  6791.3  440.19
#Mann= 6 ,-1 , 0
  4286.1     .05       0  4792.7     .07       0  4916.7     .04       0
  4945.9     .07       0  5188.9     .05       0  5497.9     .05       0
Bank Sta=4916.7,4945.9
XS Rating Curve= 0 ,0
Exp/Cntr=0.3,0.1

Chan Stop Cuts=-1
Use User Specified Reach Order=0
Composite Channel Slope=5