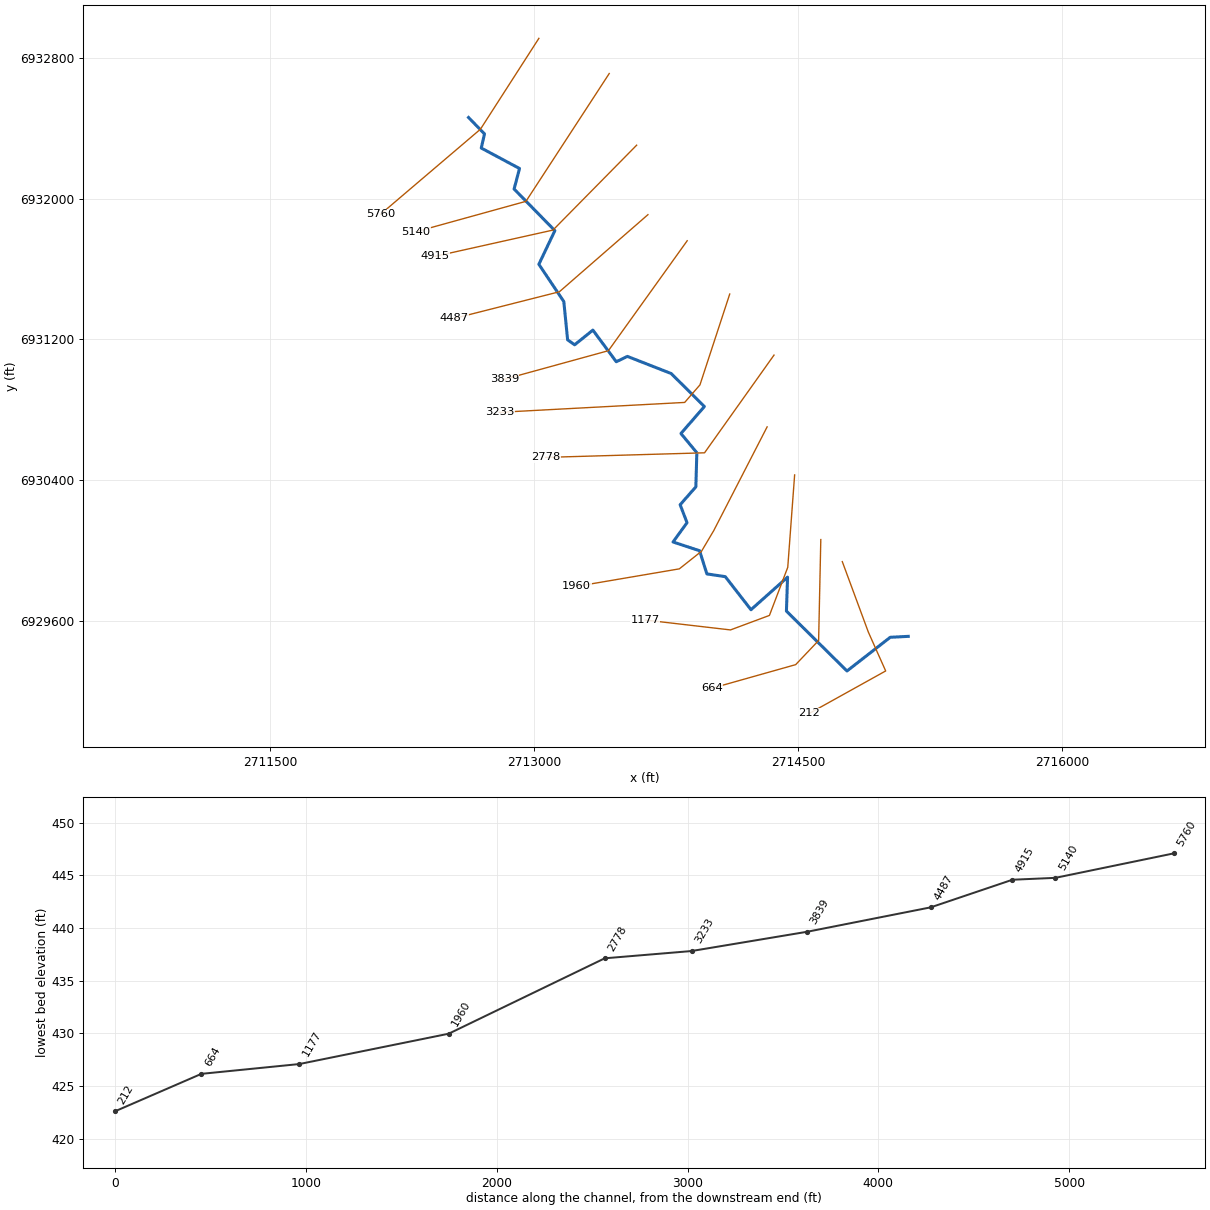
--- Wolf Creek T2_1.prj (project) ---

Proj Title=Wolf Creek T2_1 Base Level Engineering
Current Plan=p01
Default Exp/Contr=0.3,0.1
English Units
Geom File=g01
Flow File=f01
Plan File=p01
BEGIN DESCRIPTION:
Wolf Creek T2_1
END DESCRIPTION:

--- Wolf Creek T2_1.p01 (plan) ---

Plan Title=Multiple Run
Short Identifier=Multiple
Geom File=g01
Flow File=f01
Subcritical Flow
K Sum by GR= 0
Std Step Tol= 0.01
Critical Tol= 0.01
Num of Std Step Trials= 20
Max Error Tol= 0.3
Flow Tol Ratio= 0.001
Split Flow NTrial= 30
Split Flow Tol= 0.02
Split Flow Ratio= 0.02
Log Output Level= 0
Friction Slope Method= 1
Unsteady Friction Slope Method= 2
Unsteady Bridges Friction Slope Method= 1
Parabolic Critical Depth
Global Vel Dist=  1 , 1 , 1
Global Log Level= 0
CheckData=True
Encroach Param= -1, 0, 0, 0
BEGIN DESCRIPTION:
Multiple Run
END DESCRIPTION:

--- Wolf Creek T2_1.f01 (steady flow) ---

Flow Title=Multiple
Number of Profiles=7
Profile Names=10-year,25-year,50-year,1pct_min,100-year,1pct_plu,500-year
River Rch & RM= Wolf Creek T2_1,Reach-1,5760
     560     743     890     529    1055    2104    1479
Boundary for River Rch & Prof#=Wolf Creek T2_1,Reach-1,1
Up Type=0
Dn Type=3
Dn Slope=0.005
Boundary for River Rch & Prof#=Wolf Creek T2_1,Reach-1,2
Up Type=0
Dn Type=3
Dn Slope=0.005
Boundary for River Rch & Prof#=Wolf Creek T2_1,Reach-1,3
Up Type=0
Dn Type=3
Dn Slope=0.005
Boundary for River Rch & Prof#=Wolf Creek T2_1,Reach-1,4
Up Type=0
Dn Type=3
Dn Slope=0.005
Boundary for River Rch & Prof#=Wolf Creek T2_1,Reach-1,5
Up Type=0
Dn Type=3
Dn Slope=0.005
Boundary for River Rch & Prof#=Wolf Creek T2_1,Reach-1,6
Up Type=0
Dn Type=3
Dn Slope=0.005
Boundary for River Rch & Prof#=Wolf Creek T2_1,Reach-1,7
Up Type=0
Dn Type=3
Dn Slope=0.005

--- Wolf Creek T2_1.g01 (geometry) ---

Geom Title=Existing Conditions

River Reach=Wolf Creek T2_1,Reach-1
Reach XY= 30
      2712626.00      6932461.00      2712716.82      6932367.66
      2712698.36      6932287.29      2712915.93      6932171.00
      2712885.15      6932054.27      2713116.89      6931817.73
      2713025.95      6931626.34      2713167.76      6931414.23
      2713189.40      6931196.85      2713229.13      6931168.53
      2713332.95      6931252.15      2713465.98      6931072.23
      2713529.22      6931102.71      2713778.30      6931005.17
      2713967.05      6930817.67      2713833.60      6930664.34
      2713924.01      6930555.11      2713918.44      6930361.00
      2713829.18      6930259.35      2713868.24      6930157.36
      2713788.85      6930047.60      2713939.72      6929997.76
      2713981.11      6929866.11      2714085.76      6929850.47
      2714231.91      6929662.49      2714439.82      6929847.74
      2714433.37      6929654.66      2714777.65      6929314.10
      2715023.50      6929505.65      2715126.00      6929511.00

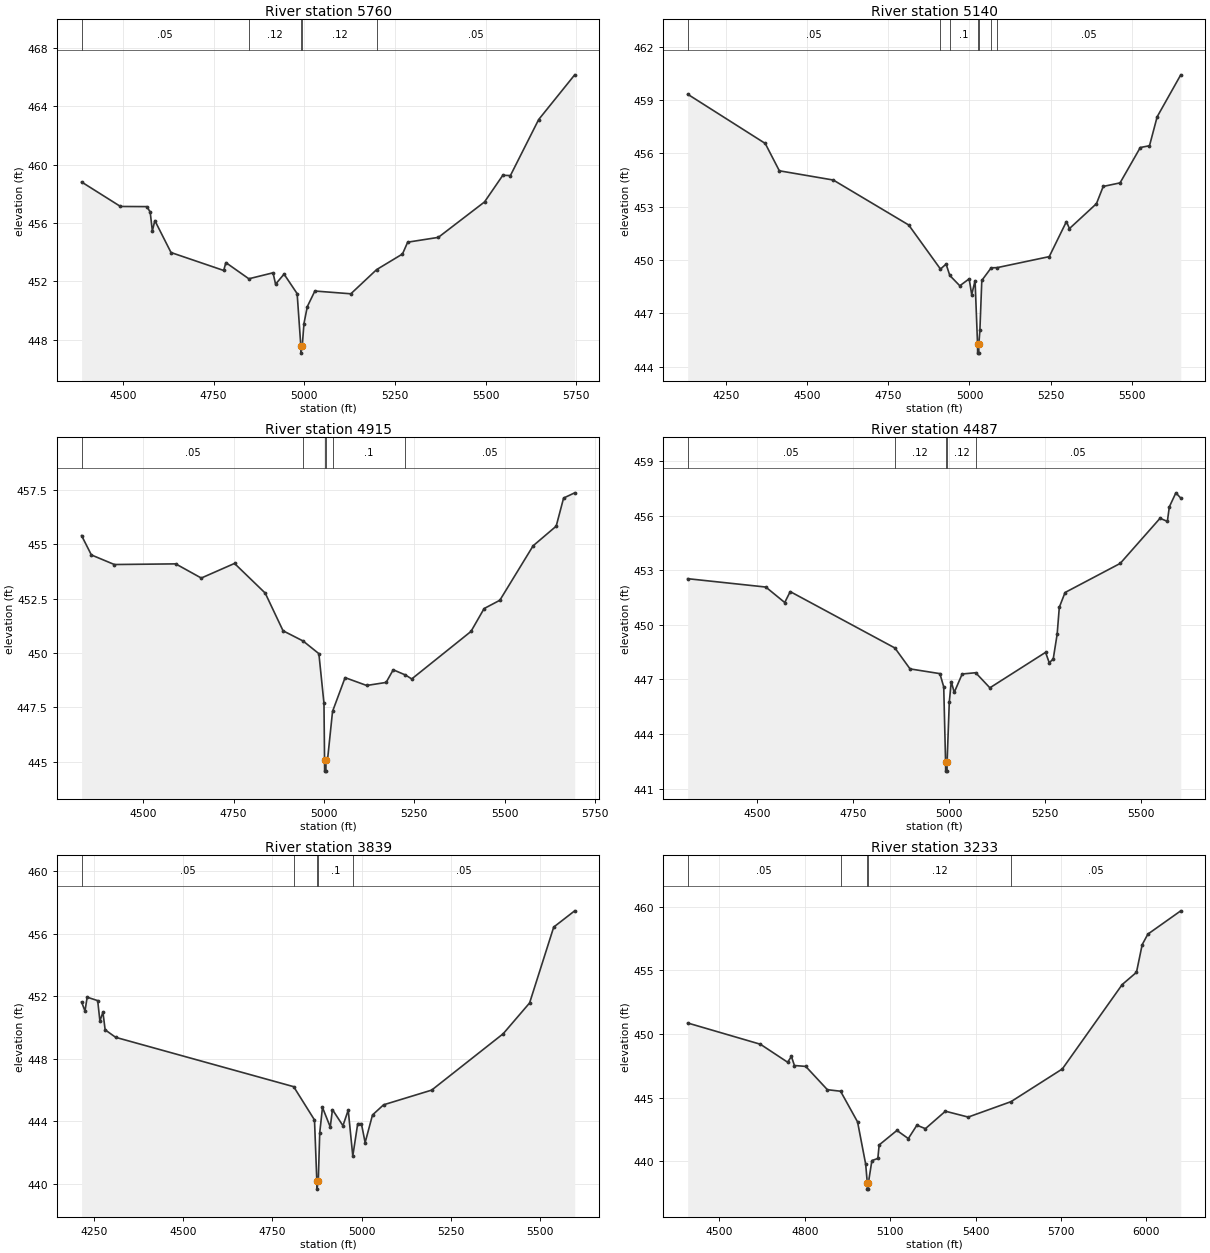
Type RM Length L Ch R = 1,5760,620,620,620
BEGIN DESCRIPTION:
Wolf Creek T2_1 7.0
END DESCRIPTION:
XS GIS Cut Line= 3
      2713026.01      6932911.01      2712693.73      6932394.33
      2712126.00      6931911.00
#Sta/Elev= 30
  4385.7  458.82  4493.0  457.14  4565.7  457.13  4574.9  456.76  4580.9  455.46
  4587.8  456.17  4632.4  453.98  4777.7  452.75  4783.6  453.29  4847.0  452.18
  4913.7  452.59  4920.7  451.81  4944.1  452.50  4980.2  451.16  4990.3  447.58
  4990.5  447.08  4994.3  447.58  4999.0  449.11  5008.2  450.27  5029.1  451.34
  5128.3  451.15  5199.4  452.81  5270.7  453.88  5285.0  454.69  5369.5  455.02
  5496.9  457.45  5547.4  459.28  5568.3  459.26  5646.2  463.10  5745.6  466.17
#Mann=5,-1,0
  4385.7    0.05       0  4847.0    0.12       0  4990.3    0.07       0
  4994.3    0.12       0  5199.4    0.05       0
Bank Sta=4990.3,4994.3
Exp/Cntr=0.3,0.1

Type RM Length L Ch R = 1,5140,225,225,225
BEGIN DESCRIPTION:
Wolf Creek T2_1 6.0
END DESCRIPTION:
XS GIS Cut Line= 3
      2713426.01      6932711.01      2712952.56      6931984.33
      2712325.99      6931811.00
#Sta/Elev= 30
  4132.7  459.33  4371.4  456.56  4414.9  455.02  4580.9  454.50  4813.0  451.97
  4910.7  449.49  4928.0  449.77  4939.4  449.13  4970.2  448.55  4999.0  448.94
  5006.8  448.05  5017.2  448.84  5024.8  445.26  5025.1  444.76  5028.6  444.76
  5028.8  445.26  5032.0  446.04  5037.9  448.85  5066.7  449.56  5084.9  449.57
  5245.4  450.19  5298.2  452.16  5307.7  451.77  5390.7  453.17  5411.5  454.14
  5463.3  454.34  5525.6  456.33  5553.9  456.43  5577.5  458.06  5650.1  460.42
#Mann=7,-1,0
  4132.7    0.05       0  4910.7    0.12       0  4939.4     0.1       0
  5024.8    0.07       0  5028.8     0.1       0  5066.7    0.12       0
  5084.9    0.05       0
Bank Sta=5024.8,5028.8
Exp/Cntr=0.3,0.1

Type RM Length L Ch R = 1,4915,428,428,428
BEGIN DESCRIPTION:
Mapping XS 6f5075db
END DESCRIPTION:
XS GIS Cut Line= 3
      2713581.83      6932303.51      2713106.16      6931820.90
      2712436.01      6931671.59
#Sta/Elev= 30
  4329.5  455.39  4356.6  454.50  4420.2  454.06  4589.9  454.09  4660.7  453.44
  4752.6  454.11  4837.5  452.75  4886.9  451.02  4942.4  450.55  4986.0  449.97
  5000.1  447.69  5001.7  445.08  5001.9  444.58  5005.4  444.58  5005.7  445.08
  5009.8  445.08  5023.8  447.32  5058.5  448.87  5118.2  448.51  5172.0  448.65
  5191.7  449.23  5225.6  448.99  5242.9  448.81  5406.8  450.99  5443.1  452.04
  5486.6  452.42  5578.7  454.92  5642.5  455.82  5663.0  457.11  5693.7  457.35
#Mann=6,-1,0
  4329.5    0.05       0  4942.4    0.12       0  5001.7    0.07       0
  5005.7    0.12       0  5023.8     0.1       0  5225.6    0.05       0
Bank Sta=5001.7,5005.7
Exp/Cntr=0.3,0.1

Type RM Length L Ch R = 1,4487,648,648,648
BEGIN DESCRIPTION:
Mapping XS 1b68dd72
END DESCRIPTION:
XS GIS Cut Line= 3
      2713646.10      6931908.58      2713142.62      6931470.21
      2712543.66      6931318.30
#Sta/Elev= 30
  4318.4  452.54  4522.2  452.08  4571.5  451.23  4585.8  451.83  4858.7  448.73
  4898.2  447.58  4976.0  447.32  4986.0  446.59  4990.8  442.46  4991.1  441.96
  4994.6  441.96  4994.8  442.46  5000.5  445.76  5005.7  446.88  5013.4  446.29
  5034.1  447.30  5069.3  447.37  5106.3  446.54  5251.5  448.49  5261.0  447.92
  5271.4  448.12  5281.7  449.49  5287.3  450.97  5302.3  451.78  5446.1  453.38
  5549.9  455.86  5569.0  455.69  5574.1  456.49  5591.2  457.26  5603.9  456.97
#Mann=5,-1,0
  4318.4    0.05       0  4858.7    0.12       0  4990.8    0.07       0
  4994.8    0.12       0  5069.3    0.05       0
Bank Sta=4990.8,4994.8
Exp/Cntr=0.3,0.1

Type RM Length L Ch R = 1,3839,606,606,606
BEGIN DESCRIPTION:
Mapping XS 85565c0e
END DESCRIPTION:
XS GIS Cut Line= 3
      2713869.20      6931760.16      2713421.26      6931135.14
      2712829.27      6930972.43
#Sta/Elev= 30
  4214.7  451.62  4224.3  451.05  4230.4  451.93  4259.9  451.71  4266.1  450.41
  4274.6  450.97  4280.8  449.84  4310.3  449.36  4809.5  446.20  4867.9  444.07
  4874.5  440.14  4874.7  439.64  4878.5  440.14  4882.6  443.25  4890.3  444.87
  4912.1  443.62  4918.3  444.73  4947.7  443.70  4962.5  444.70  4975.3  441.76
  4989.1  443.83  4999.5  443.83  5009.9  442.62  5030.6  444.39  5061.7  445.04
  5196.5  445.98  5397.1  449.59  5471.1  451.56  5538.8  456.42  5597.6  457.46
#Mann=5,-1,0
  4214.7    0.05       0  4809.5     0.1       0  4874.5    0.04       0
  4878.5     0.1       0  4975.3    0.05       0
Bank Sta=4874.5,4878.5
Exp/Cntr=0.3,0.1

Type RM Length L Ch R = 1,3233,455,455,455
BEGIN DESCRIPTION:
Mapping XS 7925ea62
END DESCRIPTION:
XS GIS Cut Line= 4
      2714111.07      6931457.31      2713941.81      6930940.84
      2713855.00      6930841.01      2712800.70      6930784.61
#Sta/Elev= 30
  4388.8  450.86  4644.3  449.19  4739.8  447.78  4753.2  448.23  4763.8  447.52
  4803.5  447.45  4879.5  445.62  4925.8  445.50  4985.5  443.09  5014.0  439.77
  5019.6  438.31  5019.8  437.81  5023.3  437.81  5023.6  438.31  5035.8  440.05
  5056.7  440.22  5061.3  441.28  5123.7  442.42  5163.7  441.78  5193.8  442.83
  5223.8  442.56  5293.9  443.93  5374.0  443.47  5524.2  444.68  5704.5  447.25
  5914.8  453.88  5964.9  454.84  5984.9  457.01  6004.9  457.84  6120.4  459.67
#Mann=5,-1,0
  4388.8    0.05       0  4925.8    0.12       0  5019.6    0.07       0
  5023.6    0.12       0  5524.2    0.05       0
Bank Sta=5019.6,5023.6
Exp/Cntr=0.3,0.1

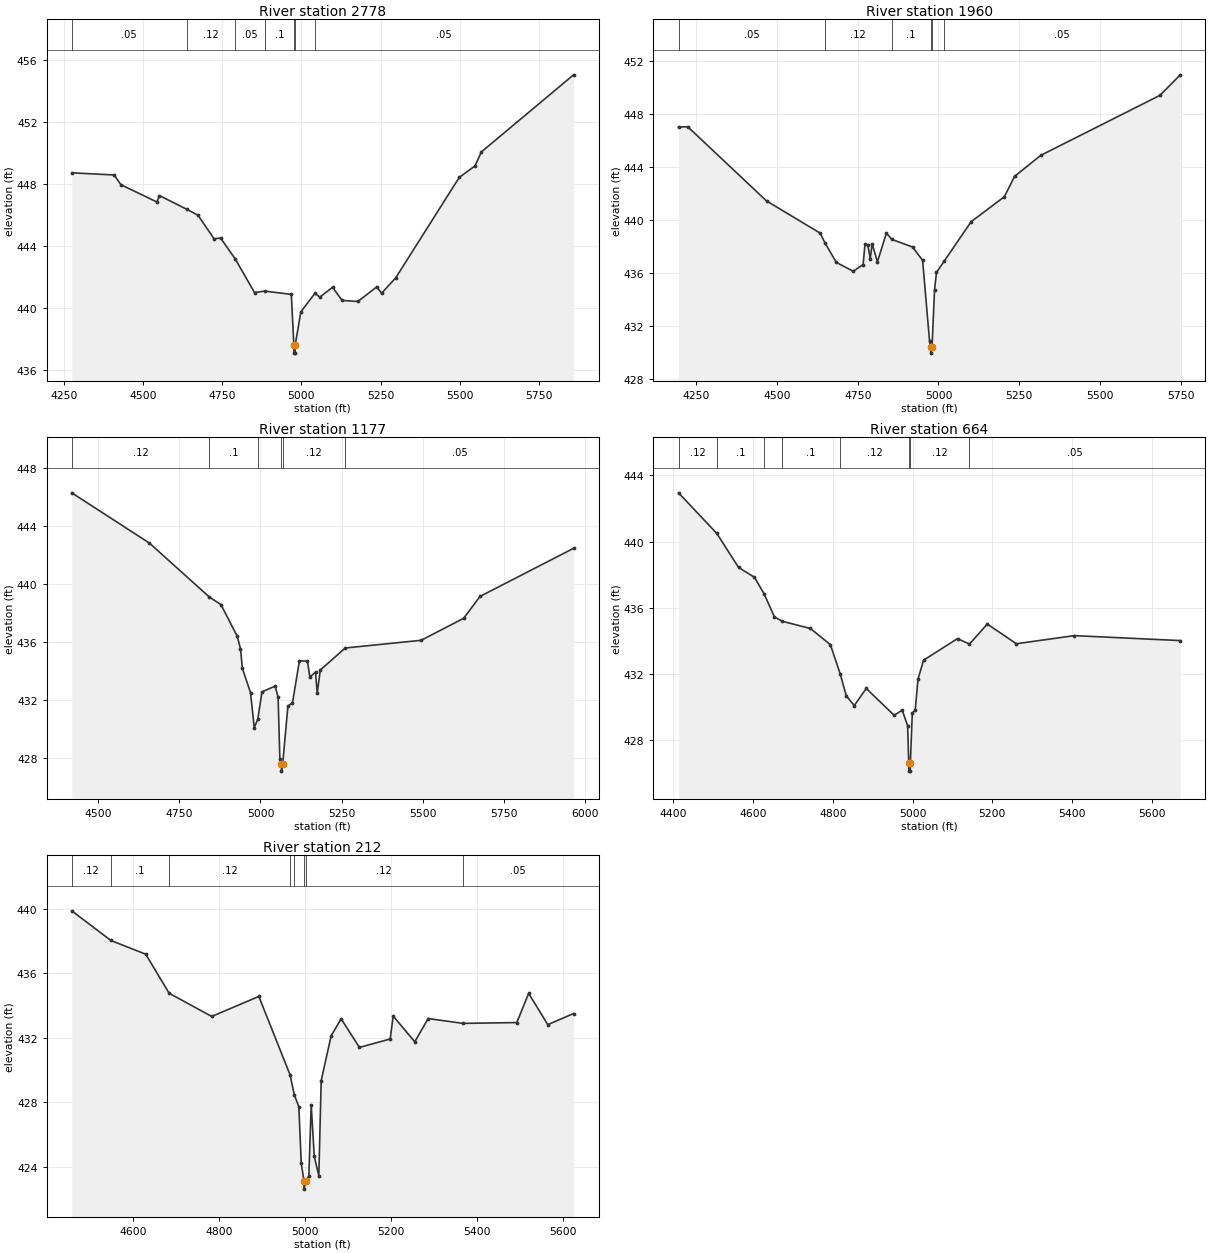
Type RM Length L Ch R = 1,2778,818,818,818
BEGIN DESCRIPTION:
Mapping XS 7543a280
END DESCRIPTION:
XS GIS Cut Line= 3
      2714362.82      6931110.11      2713967.85      6930554.55
      2713065.08      6930528.51
#Sta/Elev= 30
  4274.9  448.75  4408.8  448.61  4430.3  447.98  4543.7  446.87  4552.0  447.28
  4637.9  446.40  4673.8  446.01  4724.2  444.50  4745.1  444.54  4790.7  443.21
  4852.1  441.03  4884.2  441.12  4968.4  440.91  4976.4  437.62  4976.7  437.12
  4980.2  437.12  4980.4  437.62  4998.4  439.78  5043.0  440.98  5058.4  440.73
  5098.5  441.37  5128.5  440.52  5178.5  440.45  5238.5  441.40  5253.3  440.98
  5298.5  441.99  5498.6  448.45  5548.6  449.20  5568.7  450.10  5859.7  455.07
#Mann=7,-1,0
  4274.9    0.05       0  4637.9    0.12       0  4790.7    0.05       0
  4884.2     0.1       0  4976.4    0.07       0  4980.4     0.1       0
  5043.0    0.05       0
Bank Sta=4976.4,4980.4
Exp/Cntr=0.3,0.1

Type RM Length L Ch R = 1,1960,783,783,783
BEGIN DESCRIPTION:
Mapping XS c791c034
END DESCRIPTION:
XS GIS Cut Line= 5
      2714323.73      6930702.08      2714019.93      6930111.84
      2713950.49      6929994.66      2713824.62      6929894.83
      2713239.85      6929795.20
#Sta/Elev= 30
  4195.0  447.03  4223.6  447.05  4467.5  441.45  4633.6  439.02  4648.3  438.29
  4683.6  436.81  4736.1  436.14  4766.6  436.65  4772.3  438.17  4781.1  438.12
  4788.8  437.10  4794.4  438.21  4811.0  436.86  4838.8  439.03  4855.1  438.55
  4919.7  437.97  4950.9  436.96  4972.3  430.87  4976.1  430.46  4976.4  429.96
  4980.1  430.46  4987.7  434.72  4993.8  436.05  5017.3  436.89  5101.0  439.88
  5204.1  441.77  5235.5  443.30  5316.6  444.89  5685.7  449.42  5748.9  450.97
#Mann=6,-1,0
  4195.0    0.05       0  4648.3    0.12       0  4855.1     0.1       0
  4976.1    0.07       0  4980.1     0.1       0  5017.3    0.05       0
Bank Sta=4976.1,4980.1
Exp/Cntr=0.3,0.1

Type RM Length L Ch R = 1,1177,513,513,513
BEGIN DESCRIPTION:
Mapping XS 153ae2db
END DESCRIPTION:
XS GIS Cut Line= 5
      2714480.01      6930428.72      2714440.94      6929903.51
      2714336.77      6929630.07      2714115.42      6929547.61
      2713630.16      6929603.93
#Sta/Elev= 30
  4419.3  446.29  4657.7  442.83  4843.1  439.09  4878.3  438.58  4928.4  436.39
  4938.5  435.53  4944.3  434.17  4969.3  432.50  4980.8  430.08  4991.6  430.66
  5004.7  432.55  5045.0  432.95  5054.2  432.19  5059.6  427.94  5064.4  427.58
  5064.6  427.08  5068.4  427.58  5084.3  431.56  5098.5  431.80  5119.9  434.70
  5144.5  434.67  5152.0  433.57  5169.3  433.92  5174.6  432.46  5184.1  434.06
  5260.9  435.58  5494.3  436.11  5625.2  437.63  5675.5  439.14  5963.3  442.46
#Mann=6,-1,0
  4419.3    0.12       0  4843.1     0.1       0  4991.6    0.12       0
  5064.4    0.07       0  5068.4    0.12       0  5260.9    0.05       0
Bank Sta=5064.4,5068.4
Exp/Cntr=0.3,0.1

Type RM Length L Ch R = 1,664,452,452,452
BEGIN DESCRIPTION:
Mapping XS 6ee74571
END DESCRIPTION:
XS GIS Cut Line= 4
      2714628.82      6930061.29      2714616.44      6929487.41
      2714485.92      6929350.18      2714010.45      6929216.14
#Sta/Elev= 30
  4413.7  442.95  4509.6  440.50  4564.0  438.45  4604.0  437.85  4628.2  436.85
  4654.0  435.46  4673.2  435.20  4744.1  434.76  4794.1  433.79  4818.7  432.03
  4834.1  430.69  4854.1  430.11  4884.1  431.14  4954.1  429.52  4974.1  429.83
  4987.7  428.90  4990.6  426.65  4990.9  426.15  4994.4  426.15  4994.6  426.65
  4999.5  429.65  5006.8  429.83  5013.7  431.70  5027.8  432.85  5112.8  434.15
  5142.8  433.82  5187.4  435.03  5260.1  433.84  5405.6  434.33  5671.1  434.03
#Mann=8,-1,0
  4413.7    0.12       0  4509.6     0.1       0  4628.2    0.12       0
  4673.2     0.1       0  4818.7    0.12       0  4990.6    0.07       0
  4994.6    0.12       0  5142.8    0.05       0
Bank Sta=4990.6,4994.6
Exp/Cntr=0.3,0.1

Type RM Length L Ch R = 1,212,0,0,0
BEGIN DESCRIPTION:
Wolf Creek T2_1 1.0
END DESCRIPTION:
XS GIS Cut Line= 4
      2714751.01      6929935.97      2714899.18      6929535.06
      2714997.67      6929314.37      2714563.69      6929073.14
#Sta/Elev= 30
  4458.4  439.86  4549.4  438.02  4630.2  437.17  4684.6  434.75  4783.5  433.31
  4893.0  434.55  4965.6  429.68  4975.2  428.46  4985.9  427.71  4991.4  424.23
  4997.8  423.10  4998.0  422.60  5001.8  423.10  5009.1  423.39  5014.6  427.84
  5021.7  424.63  5032.3  423.43  5037.8  429.33  5061.0  432.12  5084.2  433.16
  5126.6  431.39  5198.0  431.91  5205.1  433.33  5255.2  431.74  5286.3  433.18
  5366.7  432.88  5492.2  432.93  5519.7  434.74  5564.2  432.80  5624.0  433.49
#Mann=8,-1,0
  4458.4    0.12       0  4549.4     0.1       0  4684.6    0.12       0
  4965.6     0.1       0  4975.2    0.12       0  4997.8    0.07       0
  5001.8    0.12       0  5366.7    0.05       0
Bank Sta=4997.8,5001.8
Exp/Cntr=0.3,0.1

Chan Stop Cuts=-1