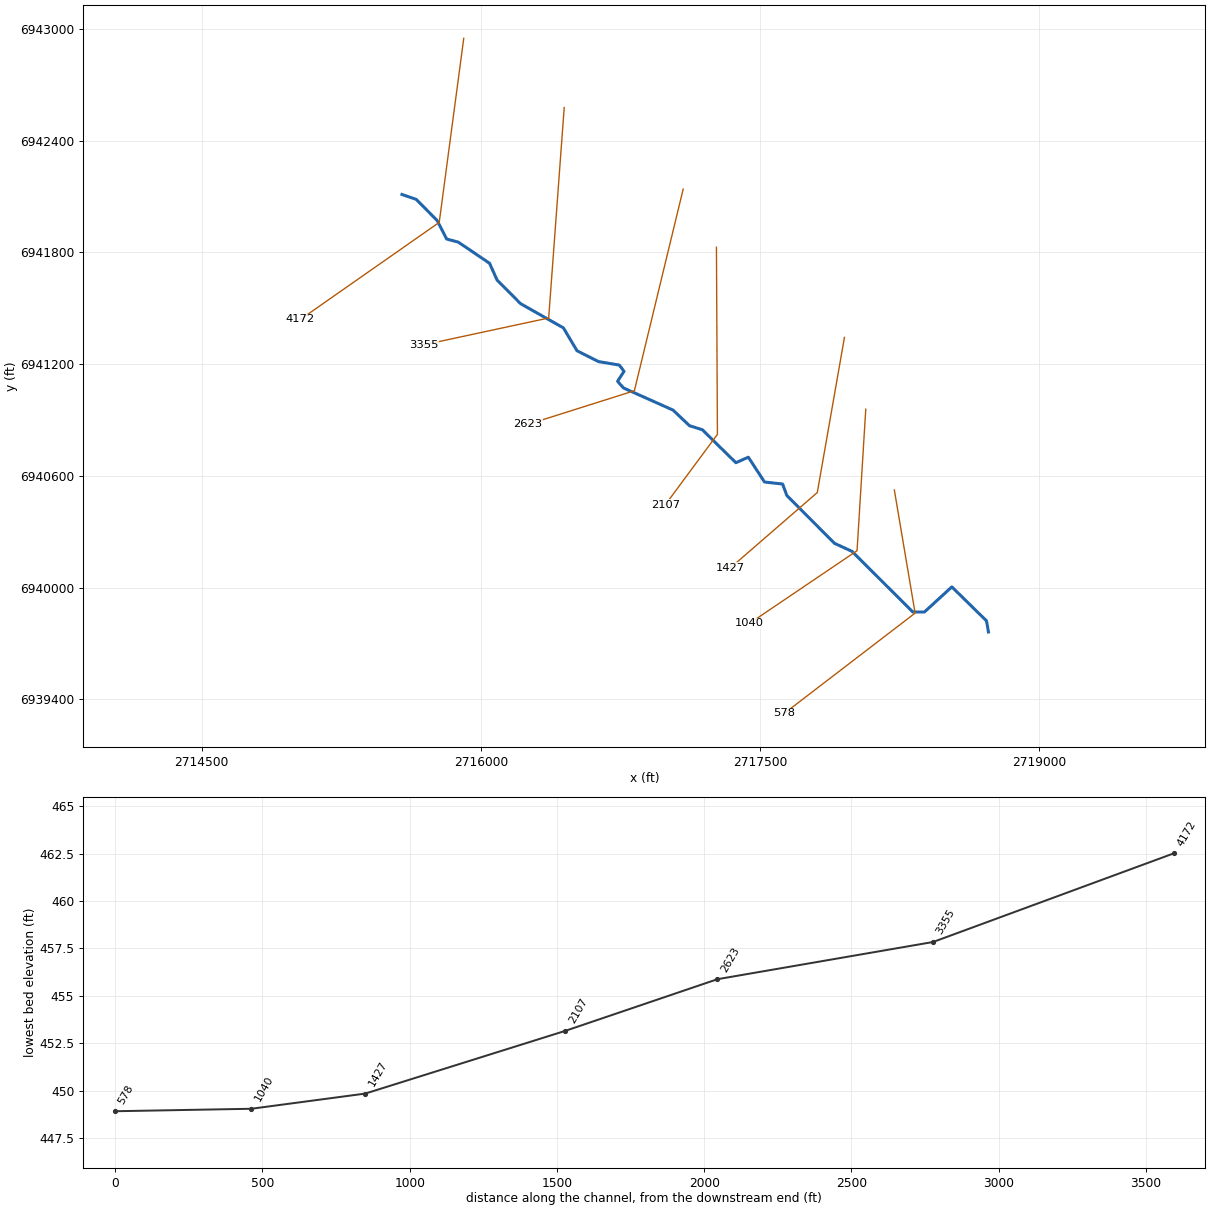
--- Wolf Creek T3.prj (project) ---

Proj Title=Wolf Creek T3 Base Level Engineering
Current Plan=p01
Default Exp/Contr=0.3,0.1
English Units
Geom File=g01
Flow File=f01
Plan File=p01
Y Axis Title=Elevation
X Axis Title(PF)=Main Channel Distance
X Axis Title(XS)=Station
BEGIN DESCRIPTION:
Wolf Creek T3
END DESCRIPTION:
DSS Export Rating Curves= 0
DSS Export Rating Curve Sorted= 0
DSS Export Volume Flow Curves= 0
DXF OffsetX= 0
DXF OffsetY= 0
DXF ScaleX= 1
DXF ScaleY= 10

--- Wolf Creek T3.p01 (plan) ---

Plan Title=Multiple Run
Short Identifier=Multiple
Geom File=g01
Flow File=f01
Subcritical Flow
K Sum by GR= 0
Std Step Tol= 0.01
Critical Tol= 0.01
Num of Std Step Trials= 20
Max Error Tol= 0.3
Flow Tol Ratio= 0.001
Split Flow NTrial= 30
Split Flow Tol= 0.02
Split Flow Ratio= 0.02
Log Output Level= 0
Friction Slope Method= 1
Unsteady Friction Slope Method= 2
Unsteady Bridges Friction Slope Method= 1
Parabolic Critical Depth
Global Vel Dist=  1 , 1 , 1
Global Log Level= 0
CheckData=True
Encroach Param= -1, 0, 0, 0
BEGIN DESCRIPTION:
Multiple Run
END DESCRIPTION:

--- Wolf Creek T3.f01 (steady flow) ---

Flow Title=Multiple
Number of Profiles=7
Profile Names=10-year,25-year,50-year,1pct_min,100-year,1pct_plu,500-year
River Rch & RM= Wolf Creek T3,Reach-1,4172
     632     848    1022     611    1219    2433    1735
Boundary for River Rch & Prof#=Wolf Creek T3,Reach-1,1
Up Type=0
Dn Type=3
Dn Slope=0.005
Boundary for River Rch & Prof#=Wolf Creek T3,Reach-1,2
Up Type=0
Dn Type=3
Dn Slope=0.005
Boundary for River Rch & Prof#=Wolf Creek T3,Reach-1,3
Up Type=0
Dn Type=3
Dn Slope=0.005
Boundary for River Rch & Prof#=Wolf Creek T3,Reach-1,4
Up Type=0
Dn Type=3
Dn Slope=0.005
Boundary for River Rch & Prof#=Wolf Creek T3,Reach-1,5
Up Type=0
Dn Type=3
Dn Slope=0.005
Boundary for River Rch & Prof#=Wolf Creek T3,Reach-1,6
Up Type=0
Dn Type=3
Dn Slope=0.005
Boundary for River Rch & Prof#=Wolf Creek T3,Reach-1,7
Up Type=0
Dn Type=3
Dn Slope=0.005

--- Wolf Creek T3.g01 (geometry) ---

Geom Title=Existing Conditions
Program Version=4.10

River Reach=Wolf Creek T3   ,Reach-1
Reach XY= 30
        2715576.        6942111.       2715652.8      6942084.65
      2715765.21      6941970.66        2715816.      6941871.65
      2715878.26      6941855.12      2716046.47      6941741.37
      2716086.79      6941651.34      2716212.79      6941524.63
      2716443.05       6941394.5        2716516.      6941271.63
      2716631.97      6941213.33      2716743.61      6941194.54
      2716768.53      6941161.23       2716733.9      6941107.43
      2716765.61      6941071.77      2717032.05      6940952.84
      2717119.96      6940869.18      2717189.21      6940847.37
      2717369.34      6940670.31      2717436.32      6940699.89
      2717523.38      6940566.45      2717620.52      6940555.74
      2717642.74      6940494.55      2717899.18       6940237.3
      2717992.67      6940194.35      2718319.95      6939868.46
      2718382.05      6939868.46      2718529.33      6940003.41
      2718715.49      6939820.79        2718726.        6939761.

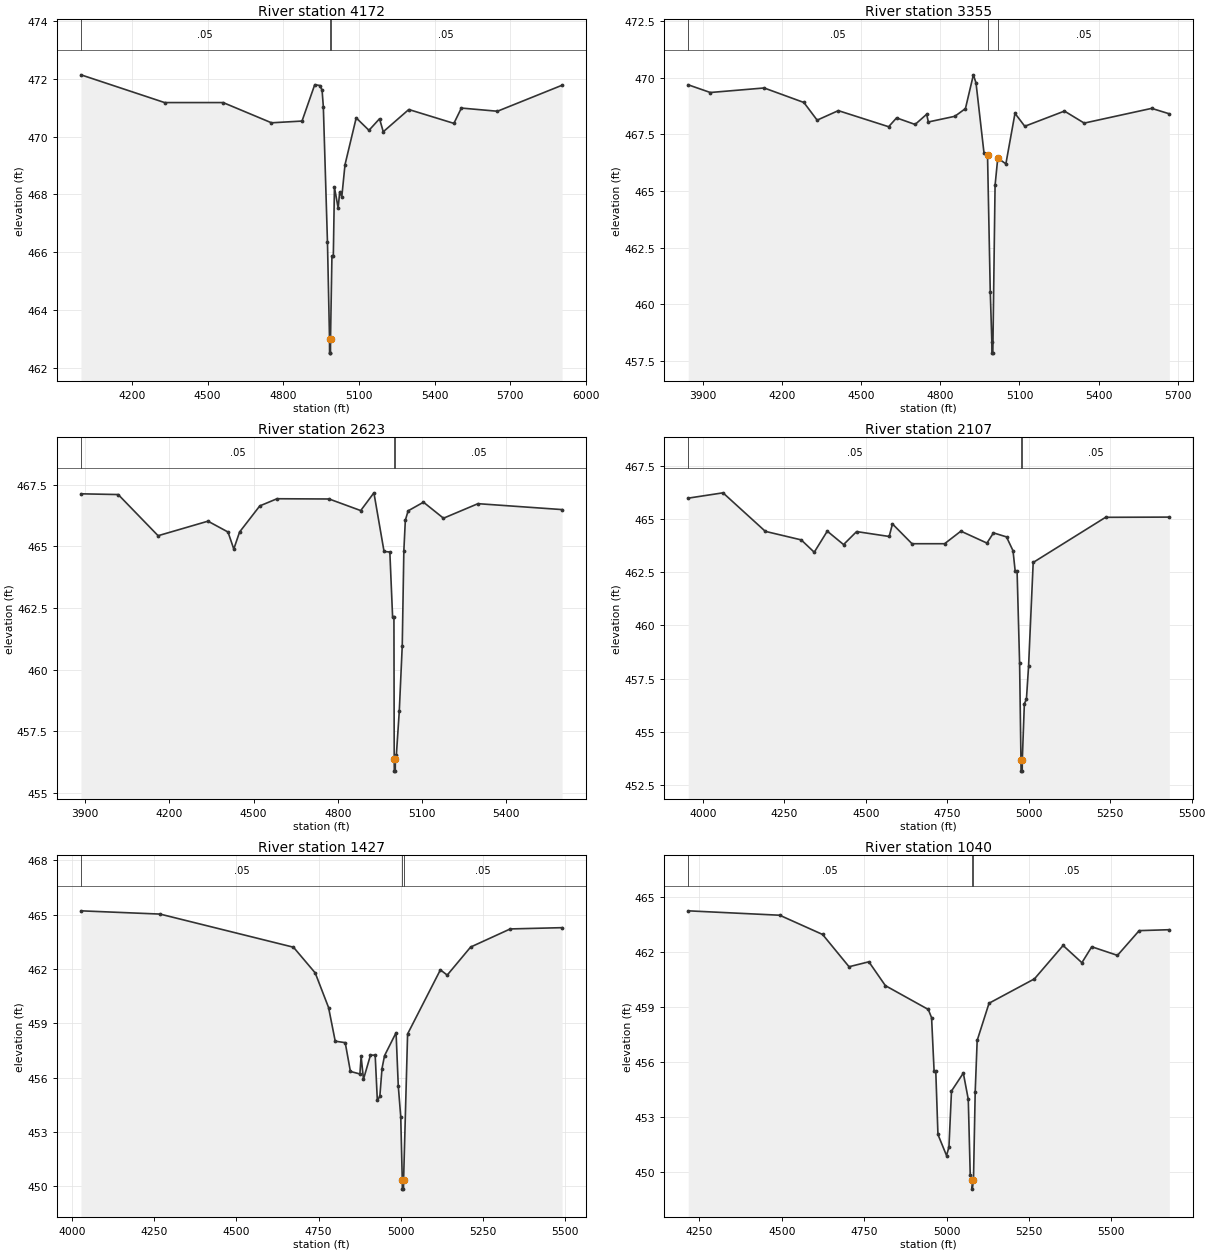
Type RM Length L Ch R = 1 ,4172    ,817,817,817
BEGIN DESCRIPTION:
Wolf Creek T3 5.0
END DESCRIPTION:
XS GIS Cut Line= 3
      2715907.69      6942949.66        2715776.        6941961.
      2715030.23       6941439.7
#Sta/Elev= 30
  3998.1  472.14  4329.7  471.18  4561.7  471.18  4753.4  470.48  4874.4  470.54
  4924.9   471.8  4945.1  471.77  4953.9  471.61  4958.9  471.04  4975.3  466.34
  4983.4  463.01  4983.7  462.51  4987.2  462.51  4987.4  463.01    4993  465.87
  4998.5  465.87  5002.9  468.25  5017.7  467.53  5023.8  468.09  5032.1  467.92
  5044.8  469.03  5089.2  470.65  5139.8  470.22  5181.7  470.62  5196.5  470.17
  5297.7  470.94  5476.5  470.46  5506.1  470.99  5649.1  470.88  5905.4  471.78
#Mann= 3 ,-1 , 0
  3998.1     .05       0  4983.4    .035       0  4987.4     .05       0
Bank Sta=4983.4,4987.4
XS Rating Curve= 0 ,0
Exp/Cntr=0.3,0.1

Type RM Length L Ch R = 1 ,3355    ,732,732,732
BEGIN DESCRIPTION:
Mapping XS d4b636e1
END DESCRIPTION:
XS GIS Cut Line= 3
      2716447.27      6942577.84      2716363.94       6941447.6
      2715691.01      6941302.98
#Sta/Elev= 30
  3845.7  469.68  3929.4  469.34  4133.3  469.54  4283.7   468.9  4333.9  468.12
  4414.1  468.54  4604.6  467.83  4634.7  468.22  4704.9  467.93  4748.5  468.38
    4755  468.04  4855.3  468.29  4895.4  468.63  4925.5  470.12  4935.5  469.76
  4965.6  466.68    4979   466.6  4989.4  460.55  4995.4  458.34  4995.6  457.84
  4999.1  457.84  5007.6  465.24  5017.8  466.45  5048.5  466.19    5083  468.42
  5120.1  467.85  5270.3  468.52  5345.1  467.99  5600.5  468.64  5667.3   468.4
#Mann= 3 ,-1 , 0
  3845.7     .05       0    4979    .035       0  5017.8     .05       0
Bank Sta=4979,5017.8
XS Rating Curve= 0 ,0
Exp/Cntr=0.3,0.1

Type RM Length L Ch R = 1 ,2623    ,516,516,516
BEGIN DESCRIPTION:
Mapping XS de3b79a7
END DESCRIPTION:
XS GIS Cut Line= 3
      2717086.31      6942139.84       2716824.2      6941056.81
      2716253.34      6940876.37
#Sta/Elev= 30
  3885.7  467.13  4018.3   467.1  4160.3  465.43  4337.9  466.02  4409.2  465.58
  4429.8  464.89  4450.4  465.58  4522.4  466.64  4583.7  466.93  4769.3  466.92
  4881.7  466.45  4928.7  467.17  4964.8  464.79  4985.4  464.77  4995.3  462.12
    5000  462.12    5001  456.38  5001.3  455.88  5004.8  455.88    5005  456.38
  5008.6  456.52  5019.1  458.33  5029.6  460.97  5035.3  464.82  5040.6  466.06
  5050.6  466.44  5105.2  466.79  5176.4  466.14  5299.2  466.73  5598.7  466.49
#Mann= 3 ,-1 , 0
  3885.7     .05       0    5001    .035       0    5005     .05       0
Bank Sta=5001,5005
XS Rating Curve= 0 ,0
Exp/Cntr=0.3,0.1

Type RM Length L Ch R = 1 ,2107    ,680,680,680
BEGIN DESCRIPTION:
Mapping XS 287e8877
END DESCRIPTION:
XS GIS Cut Line= 3
      2717264.98      6941827.78      2717270.19       6940822.6
      2716989.96      6940443.77
#Sta/Elev= 30
    3955  465.98  4061.8  466.23  4191.8  464.42  4301.8  464.02  4341.8  463.44
  4381.8  464.43  4431.8   463.8  4471.8  464.41  4571.8  464.18  4581.8  464.77
  4641.8  463.84  4741.8  463.84  4791.8  464.43  4871.8  463.87  4891.8  464.35
  4931.8  464.16  4951.8  463.51  4958.5  462.54  4964.3  462.54    4972  458.23
  4976.2  453.66  4976.5  453.16    4980  453.16  4980.2  453.66  4986.6  456.33
  4992.9  456.53  4999.5  458.08  5013.7  462.96  5235.8  465.08  5431.4  465.09
#Mann= 3 ,-1 , 0
    3955     .05       0  4976.2    .035       0  4980.2     .05       0
Bank Sta=4976.2,4980.2
XS Rating Curve= 0 ,0
Exp/Cntr=0.3,0.1

Type RM Length L Ch R = 1 ,1427    ,387,387,387
BEGIN DESCRIPTION:
Mapping XS a6cd4ebb
END DESCRIPTION:
XS GIS Cut Line= 3
      2717952.47      6941343.38      2717806.64       6940510.1
      2717339.14      6940104.92
#Sta/Elev= 30
  4026.6  465.22  4267.4  465.04  4673.5  463.21  4739.7  461.79  4780.3  459.88
  4800.6  458.02    4831  457.94  4846.8  456.35  4875.7  456.21  4879.4  457.18
  4886.6  455.92  4907.9  457.25  4922.2  457.25  4928.8  454.75  4936.4  454.97
    4943  456.51  4950.7  457.22  4985.8  458.49  4992.5  455.56    5000  453.85
  5004.7  450.35  5004.9  449.85  5008.4  449.85  5008.7  450.35  5020.9  458.42
  5120.7  461.96  5141.5  461.67  5212.8  463.22  5333.4  464.22  5491.2  464.29
#Mann= 3 ,-1 , 0
  4026.6     .05       0  5004.7     .04       0  5008.7     .05       0
Bank Sta=5004.7,5008.7
XS Rating Curve= 0 ,0
Exp/Cntr=0.3,0.1

Type RM Length L Ch R = 1 ,1040    ,462,462,462
BEGIN DESCRIPTION:
Mapping XS 303c5e9a
END DESCRIPTION:
XS GIS Cut Line= 3
      2718067.06      6940958.03      2718020.19       6940197.6
      2717442.06      6939806.97
#Sta/Elev= 30
  4216.3  464.23  4493.9  463.99  4624.1  462.94  4704.3  461.18  4764.4  461.45
  4814.5  460.15  4944.7  458.85  4954.7   458.4  4962.3  455.49  4967.4  455.49
    4974  452.03  5000.1  450.88  5007.4  451.35  5015.1   454.4    5051  455.38
    5066  453.95    5072   449.8  5077.8  449.55    5078  449.05  5081.8  449.55
    5087  454.35    5093  457.16    5129  459.19  5266.8  460.52  5353.7  462.34
  5410.7   461.4  5440.6  462.27  5518.6   461.8  5584.5  463.15  5675.9   463.2
#Mann= 3 ,-1 , 0
  4216.3     .05       0  5077.8     .04       0  5081.8     .05       0
Bank Sta=5077.8,5081.8
XS Rating Curve= 0 ,0
Exp/Cntr=0.3,0.1

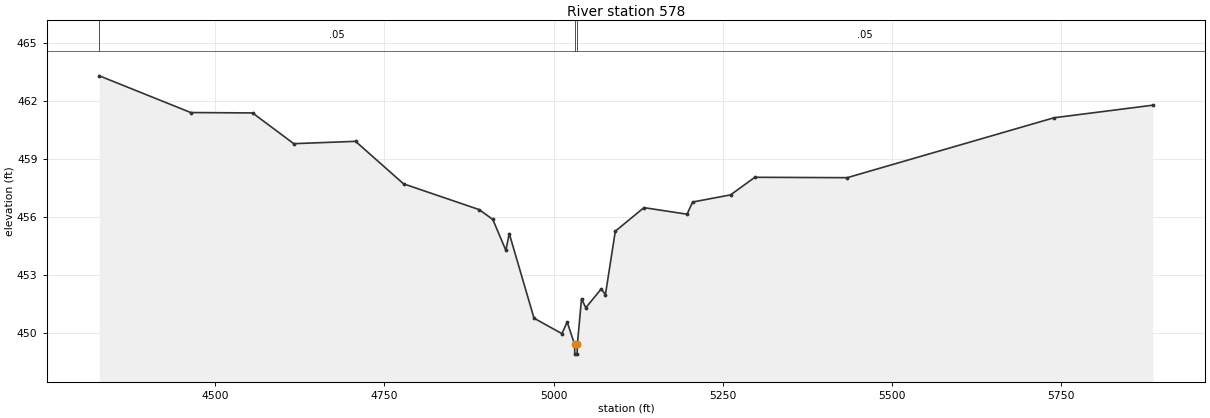
Type RM Length L Ch R = 1 ,578     ,0,0,0
BEGIN DESCRIPTION:
Wolf Creek T3 1.0
END DESCRIPTION:
XS GIS Cut Line= 3
       2718220.4      6940524.22      2718332.05      6939862.58
      2717629.45      6939323.96
#Sta/Elev= 30
    4329  463.32  4464.1  461.42  4555.4   461.4  4616.2  459.81  4707.5  459.93
  4778.5  457.73    4890   456.4  4910.3  455.89  4929.6  454.29  4934.6  455.16
  4971.2  450.78  5012.4  449.98  5020.2  450.58  5031.2  449.42  5031.4  448.92
  5034.9  448.92  5035.2  449.42  5041.4  451.78  5047.7  451.32  5070.4  452.29
  5076.7     452  5091.3  455.28  5133.6   456.5  5197.3  456.16  5205.5  456.79
  5261.6  457.16  5297.4  458.07  5433.9  458.05  5739.4  461.15  5885.3   461.8
#Mann= 3 ,-1 , 0
    4329     .05       0  5031.2     .05       0  5035.2     .05       0
Bank Sta=5031.2,5035.2
XS Rating Curve= 0 ,0
Exp/Cntr=0.3,0.1

Chan Stop Cuts=-1
Use User Specified Reach Order=0
Composite Channel Slope=5