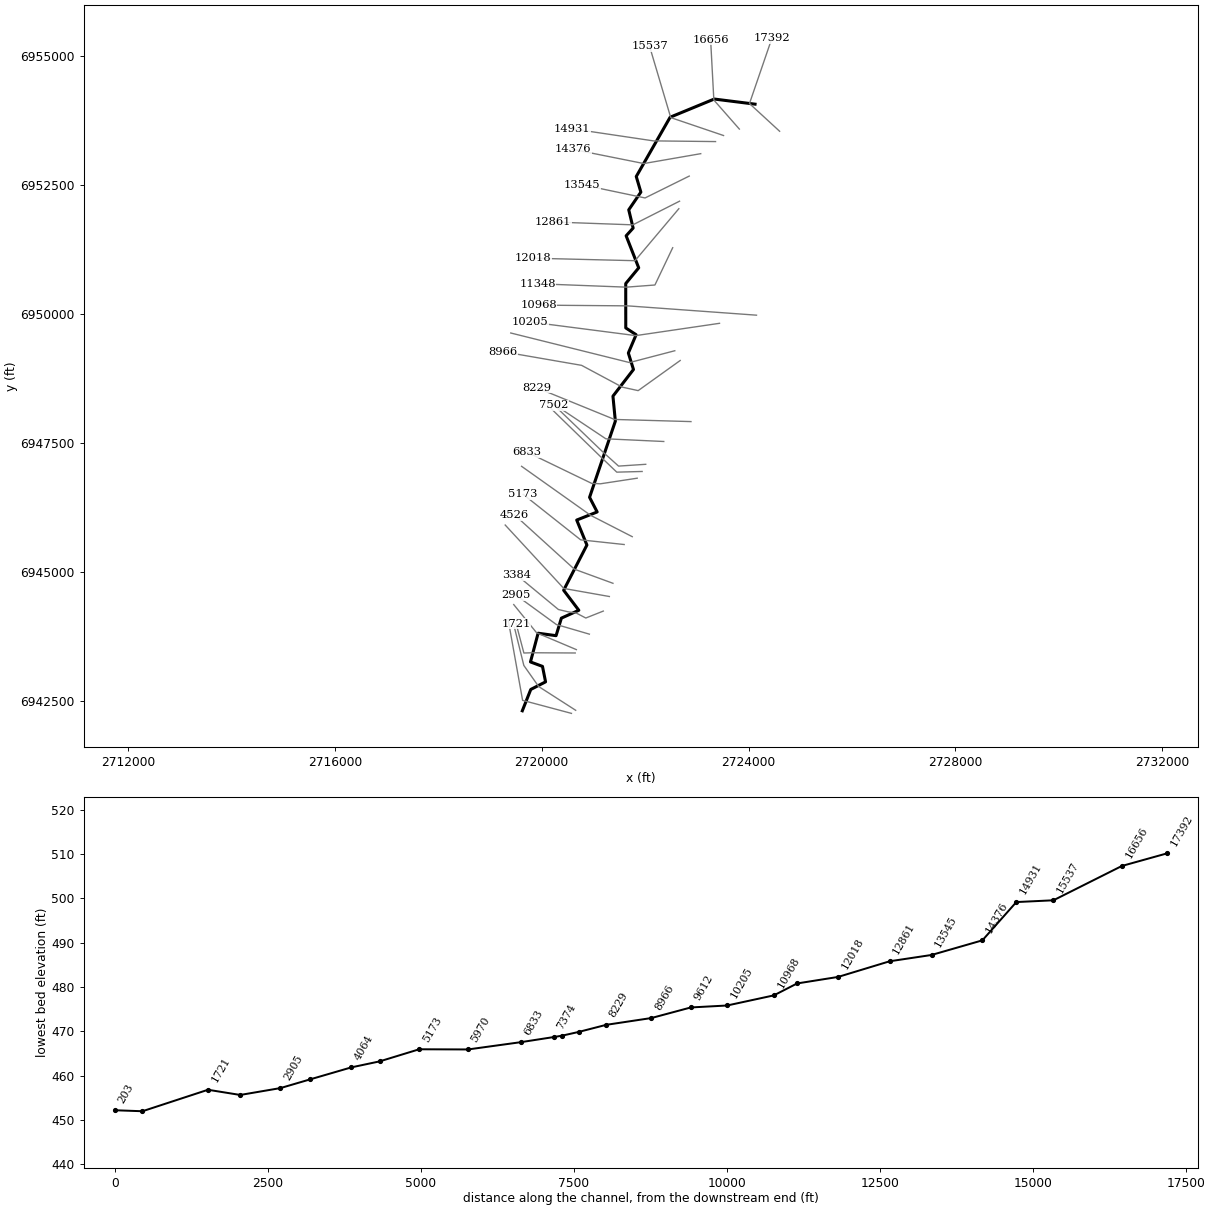
--- Wolf Creek T4.prj (project) ---

Proj Title=Wolf Creek T4 Base Level Engineering
Current Plan=p01
Default Exp/Contr=0.3,0.1
English Units
Geom File=g01
Flow File=f01
Plan File=p01
Y Axis Title=Elevation
X Axis Title(PF)=Main Channel Distance
X Axis Title(XS)=Station
BEGIN DESCRIPTION:
Wolf Creek T4
END DESCRIPTION:
DSS Export Rating Curves= 0
DSS Export Rating Curve Sorted= 0
DSS Export Volume Flow Curves= 0
DXF OffsetX= 0
DXF OffsetY= 0
DXF ScaleX= 1
DXF ScaleY= 10

--- Wolf Creek T4.p01 (plan) ---

Plan Title=Multiple Run
Short Identifier=Multiple
Geom File=g01
Flow File=f01
Subcritical Flow
K Sum by GR= 0
Std Step Tol= 0.01
Critical Tol= 0.01
Num of Std Step Trials= 20
Max Error Tol= 0.3
Flow Tol Ratio= 0.001
Split Flow NTrial= 30
Split Flow Tol= 0.02
Split Flow Ratio= 0.02
Log Output Level= 0
Friction Slope Method= 1
Unsteady Friction Slope Method= 2
Unsteady Bridges Friction Slope Method= 1
Parabolic Critical Depth
Global Vel Dist=  1 , 1 , 1
Global Log Level= 0
CheckData=True
Encroach Param= -1, 0, 0, 0
BEGIN DESCRIPTION:
Multiple Run
END DESCRIPTION:

--- Wolf Creek T4.f01 (steady flow) ---

Flow Title=Multiple
Number of Profiles=7
Profile Names=10-year,25-year,50-year,1pct_min,100-year,1pct_plu,500-year
River Rch & RM= Wolf Creek T4,Reach-1,17392
     480     630     749     443     883    1762    1224
River Rch & RM= Wolf Creek T4,Reach-1,10968
     940    1281    1560     942    1880    3751    2726
River Rch & RM= Wolf Creek T4,Reach-1,6833
    1109    1520    1860    1126    2247    4483    3279
River Rch & RM= Wolf Creek T4,Reach-1,2248
    1197    1646    2017    1223    2440    4869    3570
Boundary for River Rch & Prof#=Wolf Creek T4,Reach-1,1
Up Type=0
Dn Type=3
Dn Slope=0.005
Boundary for River Rch & Prof#=Wolf Creek T4,Reach-1,2
Up Type=0
Dn Type=3
Dn Slope=0.005
Boundary for River Rch & Prof#=Wolf Creek T4,Reach-1,3
Up Type=0
Dn Type=3
Dn Slope=0.005
Boundary for River Rch & Prof#=Wolf Creek T4,Reach-1,4
Up Type=0
Dn Type=3
Dn Slope=0.005
Boundary for River Rch & Prof#=Wolf Creek T4,Reach-1,5
Up Type=0
Dn Type=3
Dn Slope=0.005
Boundary for River Rch & Prof#=Wolf Creek T4,Reach-1,6
Up Type=0
Dn Type=3
Dn Slope=0.005
Boundary for River Rch & Prof#=Wolf Creek T4,Reach-1,7
Up Type=0
Dn Type=3
Dn Slope=0.005

--- Wolf Creek T4.g01 (geometry) ---

Geom Title=Existing Conditions
Program Version=4.10

River Reach=Wolf Creek T4   ,Reach-1
Reach XY= 30
        2724126.        6954061.      2723336.69      6954160.23
        2722484.      6953808.01      2721829.04      6952659.58
      2721918.02      6952357.67      2721683.77      6952014.41
      2721768.68       6951660.9      2721633.29      6951511.09
      2721876.47      6950890.84      2721625.47      6950586.12
      2721626.23        6949727.       2721826.3      6949595.42
      2721676.07      6949240.97      2721775.28      6948921.71
      2721378.24      6948405.07       2721424.9      6947921.55
      2720926.36      6946445.83      2721073.01      6946162.43
      2720677.85      6946005.23      2720874.95      6945521.44
      2720425.19      6944645.88       2720718.5      6944257.86
      2720381.44      6944105.81      2720278.62      6943765.98
      2719931.28      6943813.72       2719783.7       6943257.3
      2720015.97      6943171.06      2720075.53      6942871.49
      2719789.55      6942724.53        2719626.        6942311.

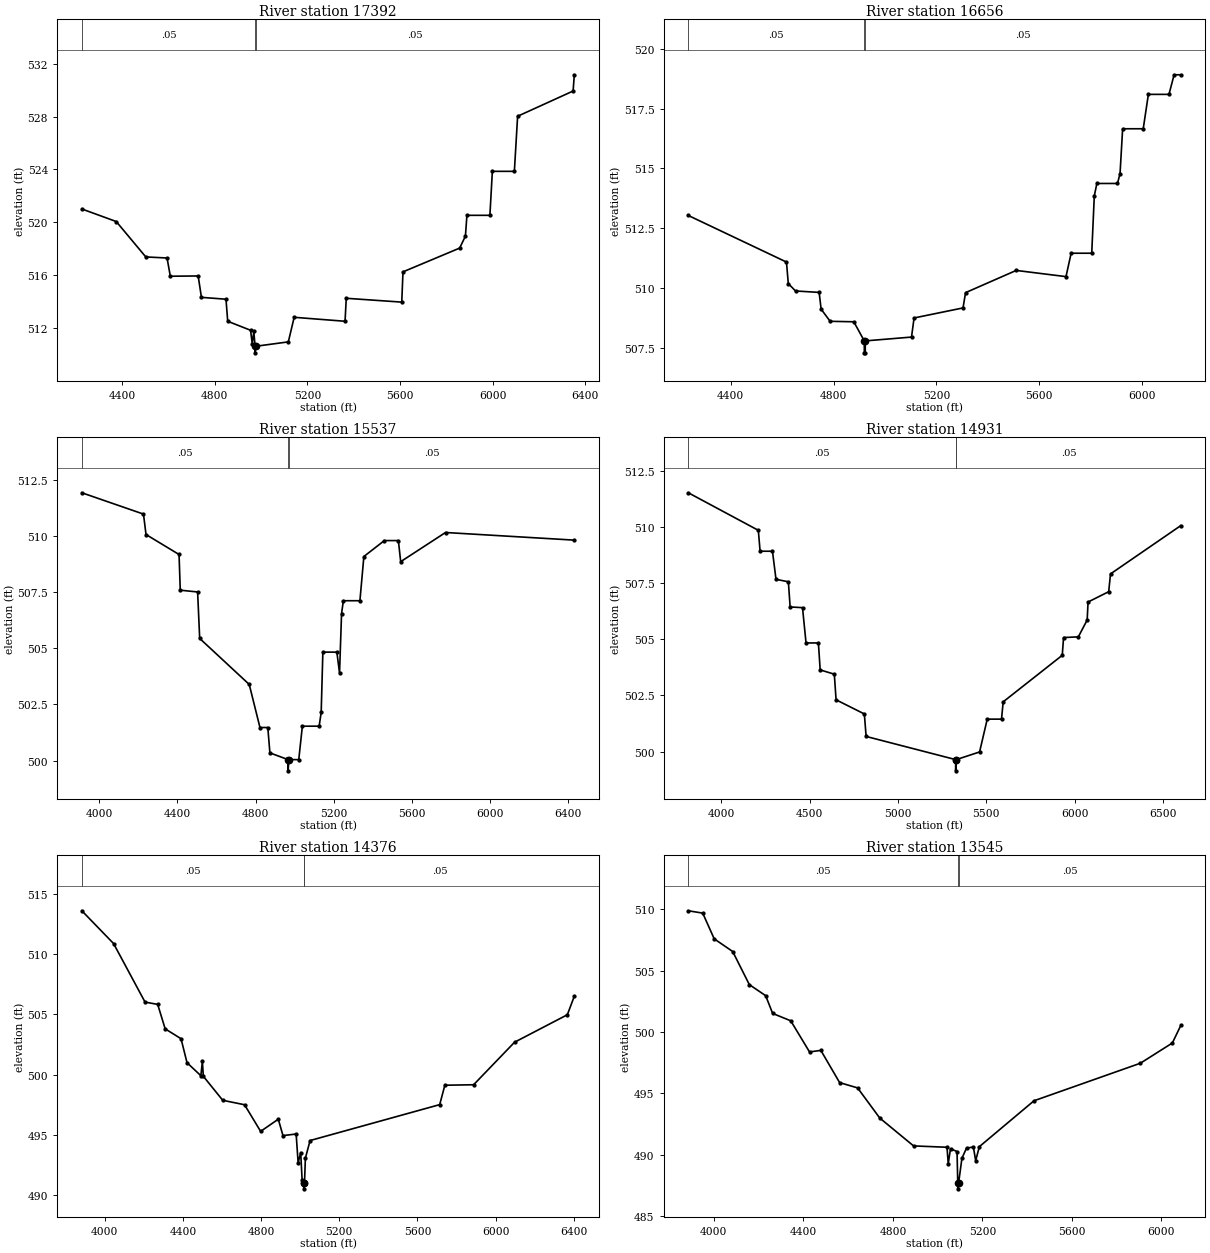
Type RM Length L Ch R = 1 ,17392   ,736,736,736
BEGIN DESCRIPTION:
Wolf Creek T4 30.0
END DESCRIPTION:
XS GIS Cut Line= 3
      2724601.02      6953535.98      2724018.31      6954073.02
        2724451.      6955336.01
#Sta/Elev= 30
  4225.4     521    4374  520.05  4501.6  517.37  4593.5  517.29  4607.6  515.91
  4727.9  515.93    4742  514.31  4848.1  514.17  4855.5   512.5  4954.1  511.82
  4961.5  510.81  4968.3  511.73  4973.7  510.61  4973.9  510.11  4977.7  510.61
  5117.4  510.94  5142.6   512.8  5362.4   512.5  5367.7  514.24  5607.4  513.95
  5612.7  516.24  5857.6  518.04  5882.5  518.95  5888.9  520.52  5988.2  520.52
  5998.8  523.85  6093.9  523.85  6107.9  528.02  6347.6  529.93  6352.9  531.16
#Mann= 3 ,-1 , 0
  4225.4     .05       0  4973.7     .04       0  4977.7     .05       0
Bank Sta=4973.7,4977.7
XS Rating Curve= 0 ,0
Exp/Cntr=0.3,0.1

Type RM Length L Ch R = 1 ,16656   ,1119,1119,1119
BEGIN DESCRIPTION:
Mapping XS cb28f480
END DESCRIPTION:
XS GIS Cut Line= 3
      2723822.35      6953578.59       2723329.3      6954141.08
      2723266.85      6955306.92
#Sta/Elev= 30
  4235.2  513.03    4617  511.08    4624  510.18  4652.1  509.87  4744.1  509.81
  4751.7  509.11  4786.8   508.6  4878.9  508.58  4919.6  507.78  4919.8  507.28
  4923.3  507.28  4923.6  507.78  5103.3  507.94  5113.3  508.74  5303.6  509.16
  5313.6   509.8  5510.6  510.73  5704.2  510.47  5724.2  511.45  5804.3  511.45
  5814.3  513.85  5824.3  514.37  5904.4  514.37  5914.4  514.78  5924.5  516.66
  6004.6  516.66  6024.6   518.1  6104.7   518.1  6124.7  518.92  6150.7  518.92
#Mann= 3 ,-1 , 0
  4235.2     .05       0  4919.6     .05       0  4923.6     .05       0
Bank Sta=4919.6,4923.6
XS Rating Curve= 0 ,0
Exp/Cntr=0.3,0.1

Type RM Length L Ch R = 1 ,15537   ,606,606,606
BEGIN DESCRIPTION:
Mapping XS 30355a73
END DESCRIPTION:
XS GIS Cut Line= 3
      2723516.81      6953453.58      2722495.97       6953800.8
      2722086.24      6955182.77
#Sta/Elev= 30
  3911.5  511.93  4226.8  510.98  4239.8  510.07  4408.8  509.18    4415  507.59
  4503.8  507.51  4514.4  505.44  4767.9  503.39  4822.8  501.47    4863  501.47
  4873.6  500.34  4966.6  500.04  4966.9  499.54  4970.6  500.04  5021.3  500.04
  5039.7  501.53  5125.6  501.53    5136  502.14  5144.6  504.83  5216.3  504.83
  5229.9   503.9  5240.3  506.55  5249.5  507.12  5334.2  507.12  5354.4  509.09
  5459.3   509.8    5531   509.8  5542.8  508.86  5772.2  510.16  6431.2  509.82
#Mann= 3 ,-1 , 0
  3911.5     .05       0  4966.6     .04       0  4970.6     .05       0
Bank Sta=4966.6,4970.6
XS Rating Curve= 0 ,0
Exp/Cntr=0.3,0.1

Type RM Length L Ch R = 1 ,14931   ,555,555,555
BEGIN DESCRIPTION:
Mapping XS 182f1fe6
END DESCRIPTION:
XS GIS Cut Line= 3
      2723362.13      6953336.26      2722161.38      6953349.78
       2720592.5      6953583.36
#Sta/Elev= 30
  3813.5  511.51  4209.7  509.84  4219.7  508.91  4289.7  508.91  4309.7  507.66
  4379.7  507.55  4389.7  506.43  4459.7   506.4  4479.7  504.83  4549.7  504.83
  4559.7  503.63  4639.7  503.44  4649.7   502.3  4809.7  501.67  4819.7  500.67
  5326.2  499.64  5326.4  499.14  5330.2  499.64  5461.8  499.98  5505.1  501.44
  5585.9  501.44  5595.4  502.21  5929.7  504.28  5937.1  505.07  6020.7   505.1
  6070.7  505.85  6075.7  506.65  6192.5  507.11  6202.7   507.9  6600.5  510.05
#Mann= 3 ,-1 , 0
  3813.5     .05       0  5326.2     .04       0  5330.2     .05       0
Bank Sta=5326.2,5330.2
XS Rating Curve= 0 ,0
Exp/Cntr=0.3,0.1

Type RM Length L Ch R = 1 ,14376   ,831,831,831
BEGIN DESCRIPTION:
Mapping XS f00de54d
END DESCRIPTION:
XS GIS Cut Line= 3
      2723075.82      6953102.02      2721975.15      6952910.57
      2720600.97      6953186.01
#Sta/Elev= 30
  3883.4  513.59  4045.6  510.87  4206.6  506.01  4271.3  505.82  4309.5  503.79
  4390.7  502.97  4421.2  500.98  4492.2   499.9  4499.7  501.09  4504.8  499.85
  4603.9  497.86  4715.5  497.49  4797.8  495.28  4888.1  496.29    4912  494.93
  4979.4  495.06  4989.6  492.66  5002.7  493.52  5009.9  491.24  5018.1  491.01
  5018.4  490.51  5022.1  491.01  5026.7  493.06  5050.7  494.52  5713.6   497.5
  5739.9  499.11    5887  499.15  6096.4  502.68  6366.4  504.96  6402.1   506.5
#Mann= 3 ,-1 , 0
  3883.4     .05       0  5018.1     .04       0  5022.1     .05       0
Bank Sta=5018.1,5022.1
XS Rating Curve= 0 ,0
Exp/Cntr=0.3,0.1

Type RM Length L Ch R = 1 ,13545   ,684,684,684
BEGIN DESCRIPTION:
Mapping XS 6998465d
END DESCRIPTION:
XS GIS Cut Line= 3
      2722853.58      6952667.97      2721999.44      6952244.38
      2720779.12      6952500.92
#Sta/Elev= 30
    3886  509.88  3950.3  509.69  4001.7  507.59  4084.2  506.56  4158.6  503.86
  4231.5  502.96  4262.8  501.51  4343.6  500.91  4427.6  498.37  4478.1   498.5
  4562.1  495.87  4642.3  495.44  4741.5  492.98  4892.4  490.71  5041.9   490.6
  5047.3  489.26  5057.5  490.48  5086.7  490.25  5089.8  487.71    5090  487.21
  5093.8  487.71  5108.6  489.71    5129  490.53  5159.7  490.62  5169.9  489.51
  5186.4  490.65  5430.5  494.39  5905.7  497.45  6048.7   499.1  6086.4  500.53
#Mann= 3 ,-1 , 0
    3886     .05       0  5089.8     .04       0  5093.8     .05       0
Bank Sta=5089.8,5093.8
XS Rating Curve= 0 ,0
Exp/Cntr=0.3,0.1

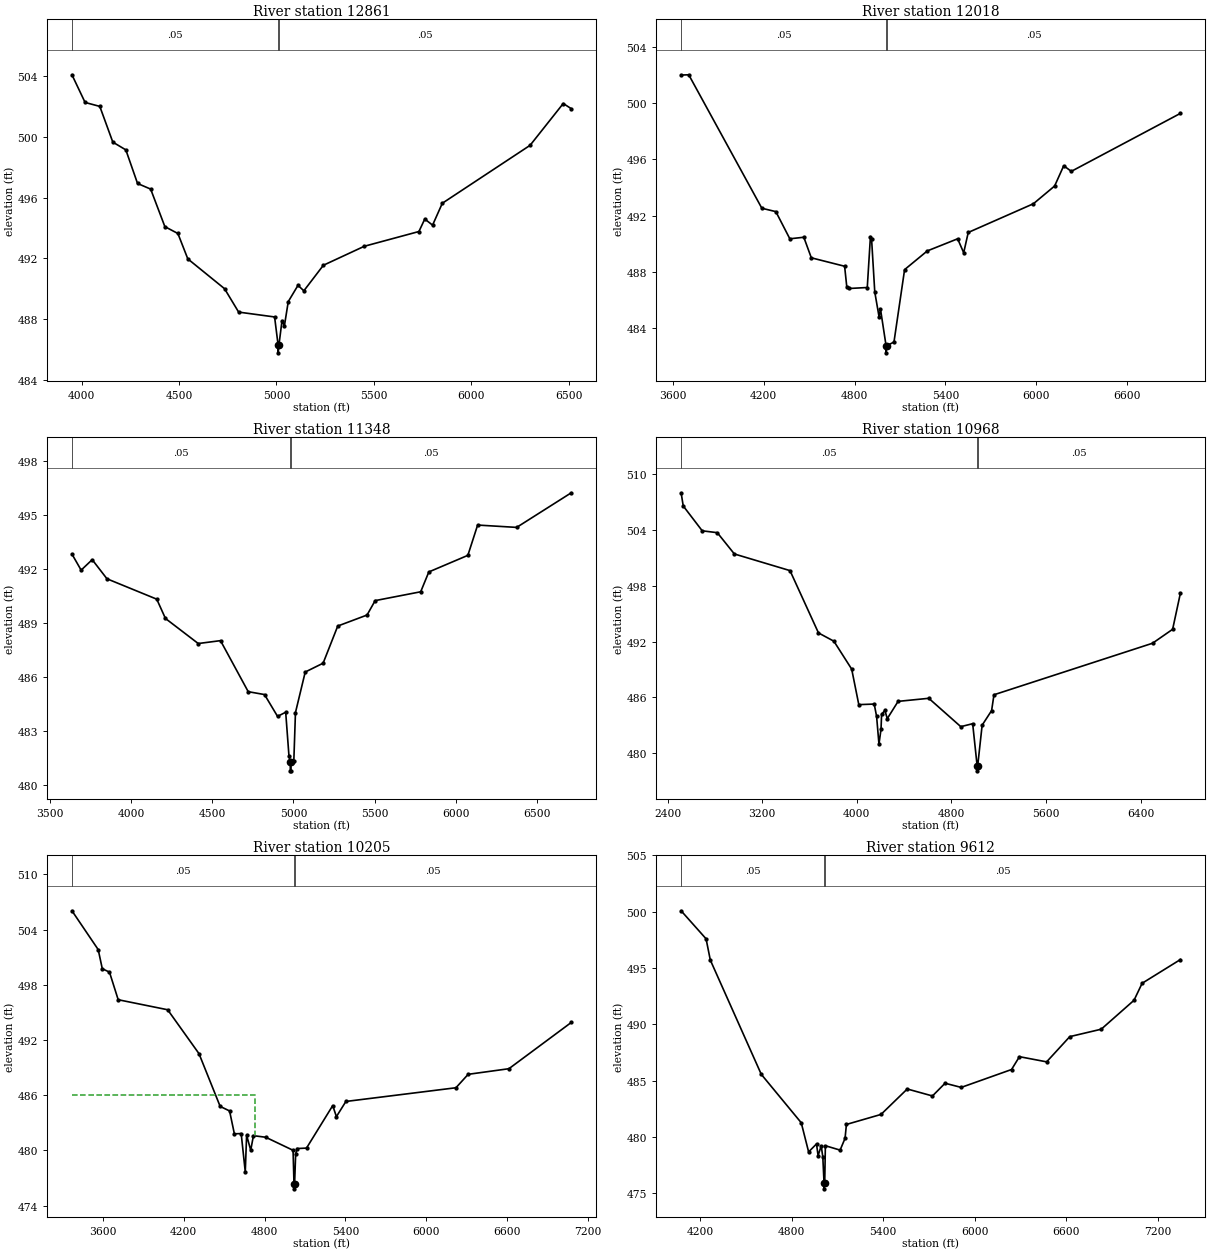
Type RM Length L Ch R = 1 ,12861   ,843,843,843
BEGIN DESCRIPTION:
Mapping XS 2f674e84
END DESCRIPTION:
XS GIS Cut Line= 3
      2722666.14      6952181.89      2721763.33      6951723.55
      2720214.72       6951779.1
#Sta/Elev= 30
  3950.9  504.08  4018.3  502.26  4093.8     502  4160.6  499.65  4227.4  499.14
  4287.5  496.93  4354.8  496.56  4427.7  494.09  4494.5  493.64  4545.4  491.97
  4733.8  490.01  4806.2  488.47  4990.7  488.15  5008.8  486.29    5009  485.79
  5012.8  486.29  5028.8  487.91  5040.8  487.55  5060.8  489.16  5110.8  490.23
  5140.8  489.87  5240.9  491.55    5451   492.8  5731.2  493.77  5761.2  494.59
  5801.3  494.19  5851.3  495.63  6301.6  499.44  6471.7  502.19    6513  501.85
#Mann= 3 ,-1 , 0
  3950.9     .05       0  5008.8     .04       0  5012.8     .05       0
Bank Sta=5008.8,5012.8
XS Rating Curve= 0 ,0
Exp/Cntr=0.3,0.1

Type RM Length L Ch R = 1 ,12018   ,670,670,670
BEGIN DESCRIPTION:
Mapping XS de0b1849
END DESCRIPTION:
XS GIS Cut Line= 3
      2722652.21      6952036.03        2721805.       6951029.1
      2719825.82      6951077.71
#Sta/Elev= 30
  3655.3  501.99  3705.7  502.01  4188.2  492.53  4280.6  492.29  4372.9  490.36
  4465.2  490.47  4514.7  489.01  4734.5  488.41  4748.8  486.95  4763.1  486.83
    4884   486.9  4904.9  490.52  4912.6  490.32  4933.5  486.58  4962.1   484.8
  4971.2  485.37  5008.2  482.76  5008.5  482.26  5012.2  482.76  5060.3  483.03
  5130.3  488.17  5280.3   489.5  5480.4  490.36  5520.4  489.37  5550.4  490.81
  5980.5  492.85  6120.6  494.11  6180.6  495.55  6230.6  495.15    6951  499.27
#Mann= 3 ,-1 , 0
  3655.3     .05       0  5008.2    .035       0  5012.2     .05       0
#XS Ineff= 2 , 0
       0  4904.9  490.52               0
Permanent Ineff=
       F       F
Bank Sta=5008.2,5012.2
XS Rating Curve= 0 ,0
Exp/Cntr=0.3,0.1

Type RM Length L Ch R = 1 ,11348   ,380,380,380
BEGIN DESCRIPTION:
Mapping XS 50e282ea
END DESCRIPTION:
XS GIS Cut Line= 4
      2722533.68      6951280.45      2722189.95      6950558.27
      2721637.87       6950516.6      2719920.09      6950582.54
#Sta/Elev= 30
  3636.8  492.81  3693.3  491.92  3761.5   492.5  3852.3  491.44  4158.6  490.31
  4212.1  489.24  4413.9  487.85  4550.9  488.01  4721.4  485.18  4821.7  485.02
  4901.9  483.81    4952  484.04  4972.1  481.62  4980.1  481.29  4980.4  480.79
  4983.9  480.79  4984.1  481.29  5002.1  481.36  5012.1  484.02  5072.2  486.27
  5182.3  486.76  5272.3  488.82  5452.5  489.43  5502.5  490.23  5782.7  490.72
  5832.7  491.82  6072.9  492.74    6133  494.42  6373.1  494.29  6709.3  496.21
#Mann= 3 ,-1 , 0
  3636.8     .05       0  4980.1     .04       0  4984.1     .05       0
Bank Sta=4980.1,4984.1
XS Rating Curve= 0 ,0
Exp/Cntr=0.3,0.1

Type RM Length L Ch R = 1 ,10968   ,763,763,763
BEGIN DESCRIPTION:
Mapping XS 9bf5c523
END DESCRIPTION:
XS GIS Cut Line= 3
      2724154.07      6949973.78      2721661.02      6950154.33
      2719939.86      6950168.21
#Sta/Elev= 30
    2515     508  2533.1  506.58  2693.5  503.91  2820.8  503.71  2965.2  501.42
  3435.5  499.63  3676.1  492.93  3806.4  492.04  3956.8  489.04    4017  485.22
  4147.3  485.28  4167.4  483.96  4187.4  480.98  4204.8  482.57  4209.8  484.18
  4237.6   484.6  4257.6  483.71  4349.2  485.57  4608.5   485.9  4879.2  482.85
  4979.5  483.17  5017.6   478.6  5017.9   478.1  5021.6   478.6  5059.6  483.01
  5139.6  484.58  5159.6  486.28  6499.7  491.82  6669.7  493.32  6735.8  497.23
#Mann= 3 ,-1 , 0
    2515     .05       0  5017.6     .05       0  5021.6     .05       0
Bank Sta=5017.6,5021.6
XS Rating Curve= 0 ,0
Exp/Cntr=0.3,0.1

Type RM Length L Ch R = 1 ,10205   ,593,593,593
BEGIN DESCRIPTION:
Mapping XS 04fe5bb7
END DESCRIPTION:
XS GIS Cut Line= 3
      2723438.83      6949816.23        2721819.      6949577.94
      2719766.88      6949843.57
#Sta/Elev= 30
  3369.9  506.05  3564.8  501.83  3595.1  499.75  3648.5  499.38  3713.2  496.38
  4080.3  495.29  4312.8  490.52  4470.1  484.78  4539.9  484.29  4575.6   481.8
  4626.1  481.83  4656.4  477.67  4666.5  481.64  4696.9  480.02  4717.1   481.6
    4808  481.43  5011.2  480.01  5018.2  476.32  5018.5  475.82  5022.4  476.32
  5030.4  479.58  5040.4   480.2    5111  480.25  5305.6  484.87  5332.9  483.67
  5403.4  485.32  6220.2  486.81  6310.9  488.27  6613.4  488.88  7076.4  493.91
#Mann= 3 ,-1 , 0
  3369.9     .05       0  5018.2     .05       0  5022.4     .05       0
#XS Ineff= 2 , 0
       0  4727.2     486               0
Permanent Ineff=
       F       F
Bank Sta=5018.2,5022.4
XS Rating Curve= 0 ,0
Exp/Cntr=0.3,0.1

Type RM Length L Ch R = 1 ,9612    ,646,646,646
BEGIN DESCRIPTION:
Mapping XS 7441c927
END DESCRIPTION:
XS GIS Cut Line= 3
      2722574.25      6949284.98      2721699.21      6949055.81
      2719402.34      6949628.73
#Sta/Elev= 30
  4076.2  500.08  4239.8  497.59  4267.6   495.7  4601.6  485.55  4863.4  481.25
  4911.7  478.66  4963.4  479.37  4973.7  478.33  4994.4   479.2  5004.7   478.2
  5012.9  475.88  5013.2  475.38  5017.1  475.88  5021.5  479.21    5118  478.82
  5150.5  479.87  5159.3   481.1    5386  481.99    5558  484.25  5723.1  483.63
  5805.7  484.76  5911.6  484.39  6241.4  485.98    6293  487.12  6471.2  486.66
  6622.8   488.9  6828.9  489.56  7043.8  492.13  7096.9  493.64    7348  495.75
#Mann= 3 ,-1 , 0
  4076.2     .05       0  5012.9     .04       0  5017.1     .05       0
Bank Sta=5012.9,5017.1
XS Rating Curve= 0 ,0
Exp/Cntr=0.3,0.1

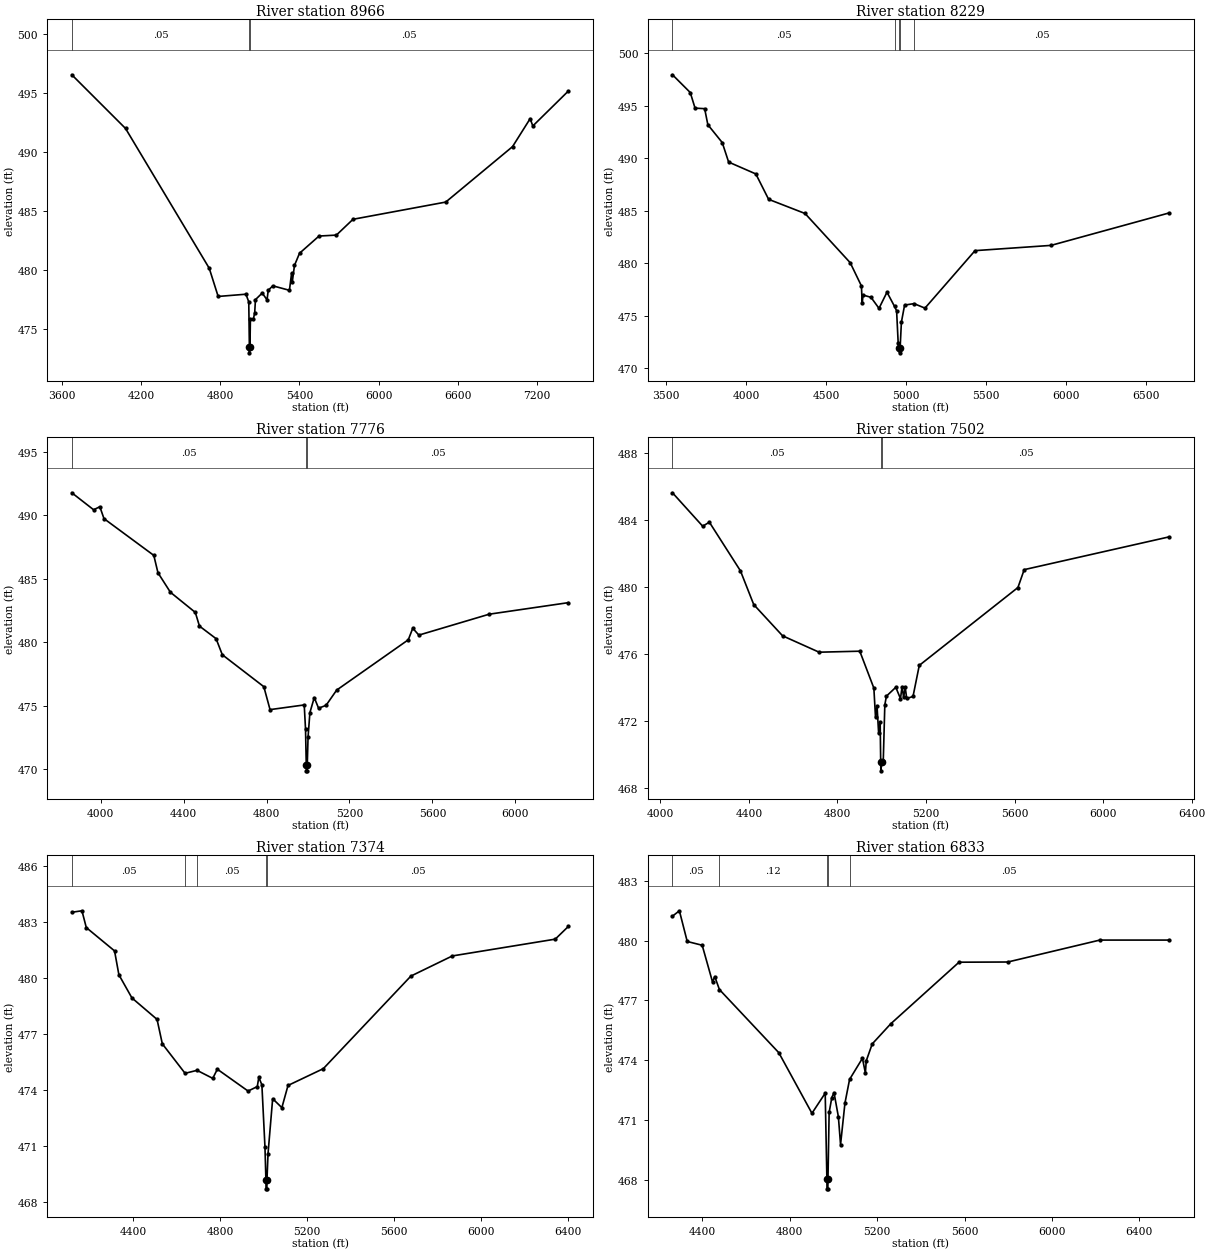
Type RM Length L Ch R = 1 ,8966    ,737,737,737
BEGIN DESCRIPTION:
Mapping XS 8252487d
END DESCRIPTION:
XS GIS Cut Line= 5
      2722678.38      6949095.74      2721865.88      6948512.41
      2721558.59      6948580.11      2720772.13      6949001.99
      2719240.94       6949267.6
#Sta/Elev= 30
  3675.7  496.56  4082.7  492.01  4716.8  480.16  4784.4  477.77  4994.9  477.96
  5016.2  477.31  5020.9  473.49  5021.2  472.99  5025.2  473.49  5028.7  475.85
  5050.6  475.82  5061.2  476.39  5066.9   477.5  5118.3  478.06  5154.6  477.48
  5163.7  478.29  5198.4  478.67  5324.3  478.29  5340.6  479.74  5346.2  479.02
  5362.5   480.4  5400.7  481.43  5548.5  482.89    5680  482.97  5805.9  484.31
  6508.4  485.77  7014.5  490.47  7147.8  492.84  7168.1  492.22  7437.1  495.18
#Mann= 3 ,-1 , 0
  3675.7     .05       0  5020.9     .04       0  5025.2     .05       0
Bank Sta=5020.9,5025.2
XS Rating Curve= 0 ,0
Exp/Cntr=0.3,0.1

Type RM Length L Ch R = 1 ,8229    ,453,453,453
BEGIN DESCRIPTION:
Mapping XS ac40981e
END DESCRIPTION:
XS GIS Cut Line= 3
       2722887.1      6947912.58      2721407.98      6947954.25
      2719902.81      6948568.81
#Sta/Elev= 30
  3539.1  497.96  3650.2  496.27  3680.3  494.78  3740.3  494.73  3760.3   493.2
  3850.3   491.5  3890.3  489.64  4060.4  488.51  4140.4  486.09  4368.2  484.74
  4650.6  480.05  4720.7  477.84  4725.8  476.17  4730.8  476.97  4780.7  476.75
  4830.7   475.7  4880.7  477.24    4928  475.88  4940.8  475.47  4950.8  472.37
  4958.6  471.96    4959  471.46    4963  471.96  4970.8  474.38  4990.8  476.01
    5050  476.15  5118.2  475.72  5431.4   481.2  5906.7   481.7  6644.6  484.79
#Mann= 5 ,-1 , 0
  3539.1     .05       0    4928     .12       0  4958.6     .07       0
    4963     .12       0    5050     .05       0
Bank Sta=4958.6,4963
XS Rating Curve= 0 ,0
Exp/Cntr=0.3,0.1

Type RM Length L Ch R = 1 ,7776    ,274,274,274
BEGIN DESCRIPTION:
Mapping XS acd2fb20
END DESCRIPTION:
XS GIS Cut Line= 3
      2722361.07      6947527.16      2721241.31      6947579.25
      2720181.96      6948286.64
#Sta/Elev= 30
  3860.8  491.79    3966  490.45    3996  490.69    4016  489.75  4256.3  486.85
  4276.3  485.48  4336.4  483.94  4456.5  482.35  4476.5  481.27  4556.6  480.28
  4586.7  479.01  4786.9  476.49  4816.9  474.68  4981.8  475.05    4988  473.16
  4991.6  470.35  4992.2  469.85  4995.9  469.85  4996.5  470.35  5000.2  472.49
  5009.1  474.44  5030.1  475.63  5051.1  474.79  5087.2  475.02  5138.2  476.22
  5483.7  480.19  5505.2   481.1  5534.7  480.56  5874.1  482.21  6255.6  483.12
#Mann= 3 ,-1 , 0
  3860.8     .05       0  4991.6     .04       0  4996.5     .05       0
Bank Sta=4991.6,4996.5
XS Rating Curve= 0 ,0
Exp/Cntr=0.3,0.1

Type RM Length L Ch R = 1 ,7502    ,128,128,128
BEGIN DESCRIPTION:
Mapping XS 00952d92
END DESCRIPTION:
XS GIS Cut Line= 4
      2722012.19      6947085.33      2721486.97       6947050.6
      2721174.47      6947332.72      2720241.34      6948231.13
#Sta/Elev= 30
  4054.7  485.64  4191.1  483.64  4221.3  483.88  4361.6  480.97  4421.7  478.95
    4552  477.08  4716.9   476.1  4900.7  476.16  4964.3  473.95  4971.7  472.21
  4978.5   472.9  4985.9  471.24  4992.7  471.93  4995.2   469.5  4995.8     469
  5000.2   469.5  5006.8  469.61  5013.8  472.95    5021  473.47  5063.4     474
  5084.5  473.32  5091.7  474.04  5098.7   473.4  5105.9  473.99  5112.8  473.33
  5141.1  473.45  5169.4  475.31    5615  479.97  5643.3  481.04  6297.4     483
#Mann= 3 ,-1 , 0
  4054.7     .05       0  4995.2     .04       0  5000.2     .05       0
Bank Sta=4995.2,5000.2
XS Rating Curve= 0 ,0
Exp/Cntr=0.3,0.1

Type RM Length L Ch R = 1 ,7374    ,541,541,541
BEGIN DESCRIPTION:
Mapping XS 50bdc32b
END DESCRIPTION:
XS GIS Cut Line= 4
      2721942.68      6946946.43      2721452.25      6946933.41
      2721157.11      6947215.53       2720163.2       6948183.4
#Sta/Elev= 30
  4116.2  483.53  4162.9  483.61  4182.9  482.71    4313  481.46    4333  480.18
    4393  478.94  4508.7  477.79    4533  476.48  4637.8   474.9  4692.7  475.06
  4765.2  474.63  4786.3  475.12  4927.8  473.95  4970.3  474.19  4977.2  474.69
  4991.4  474.28  5005.5  470.97  5009.9  469.21  5010.6  468.71  5014.3  468.71
  5014.9  469.21  5019.7   470.6    5041  473.54  5083.4  473.06  5111.7  474.25
  5274.3  475.15  5677.4  480.11  5868.3  481.19  6342.2  482.09  6402.4  482.77
#Mann= 5 ,-1 , 0
  4116.2     .05       0  4637.8     .12       0  4692.7     .05       0
  5009.9     .04       0  5014.9     .05       0
Bank Sta=5009.9,5014.9
XS Rating Curve= 0 ,0
Exp/Cntr=0.3,0.1

Type RM Length L Ch R = 1 ,6833    ,863,863,863
BEGIN DESCRIPTION:
Mapping XS 63ae8ed0
END DESCRIPTION:
XS GIS Cut Line= 4
      2721847.26      6946816.23      2721135.41      6946707.72
      2720966.14       6946716.4      2719720.77      6947319.55
#Sta/Elev= 30
  4262.6  481.23  4294.2   481.5  4330.1  479.96  4398.6  479.77  4445.9  477.93
  4456.1   478.2  4477.4  477.55  4749.4  474.38  4901.1  471.34  4961.8  472.35
  4969.5  468.05  4970.1  467.55  4973.9  467.55  4974.5  468.05  4979.8  471.38
  4992.1  472.13  5002.1  472.38  5022.1  471.17  5032.1  469.77  5052.2  471.85
  5073.4  473.04  5132.3   474.1  5145.8  473.36  5149.7  473.97  5177.1  474.82
  5261.9  475.83  5574.5  478.92    5798  478.93    6219  480.03  6535.9  480.03
#Mann= 5 ,-1 , 0
  4262.6     .05       0  4477.4     .12       0  4969.5     .07       0
  4974.5     .12       0  5073.4     .05       0
Bank Sta=4969.5,4974.5
XS Rating Curve= 0 ,0
Exp/Cntr=0.3,0.1

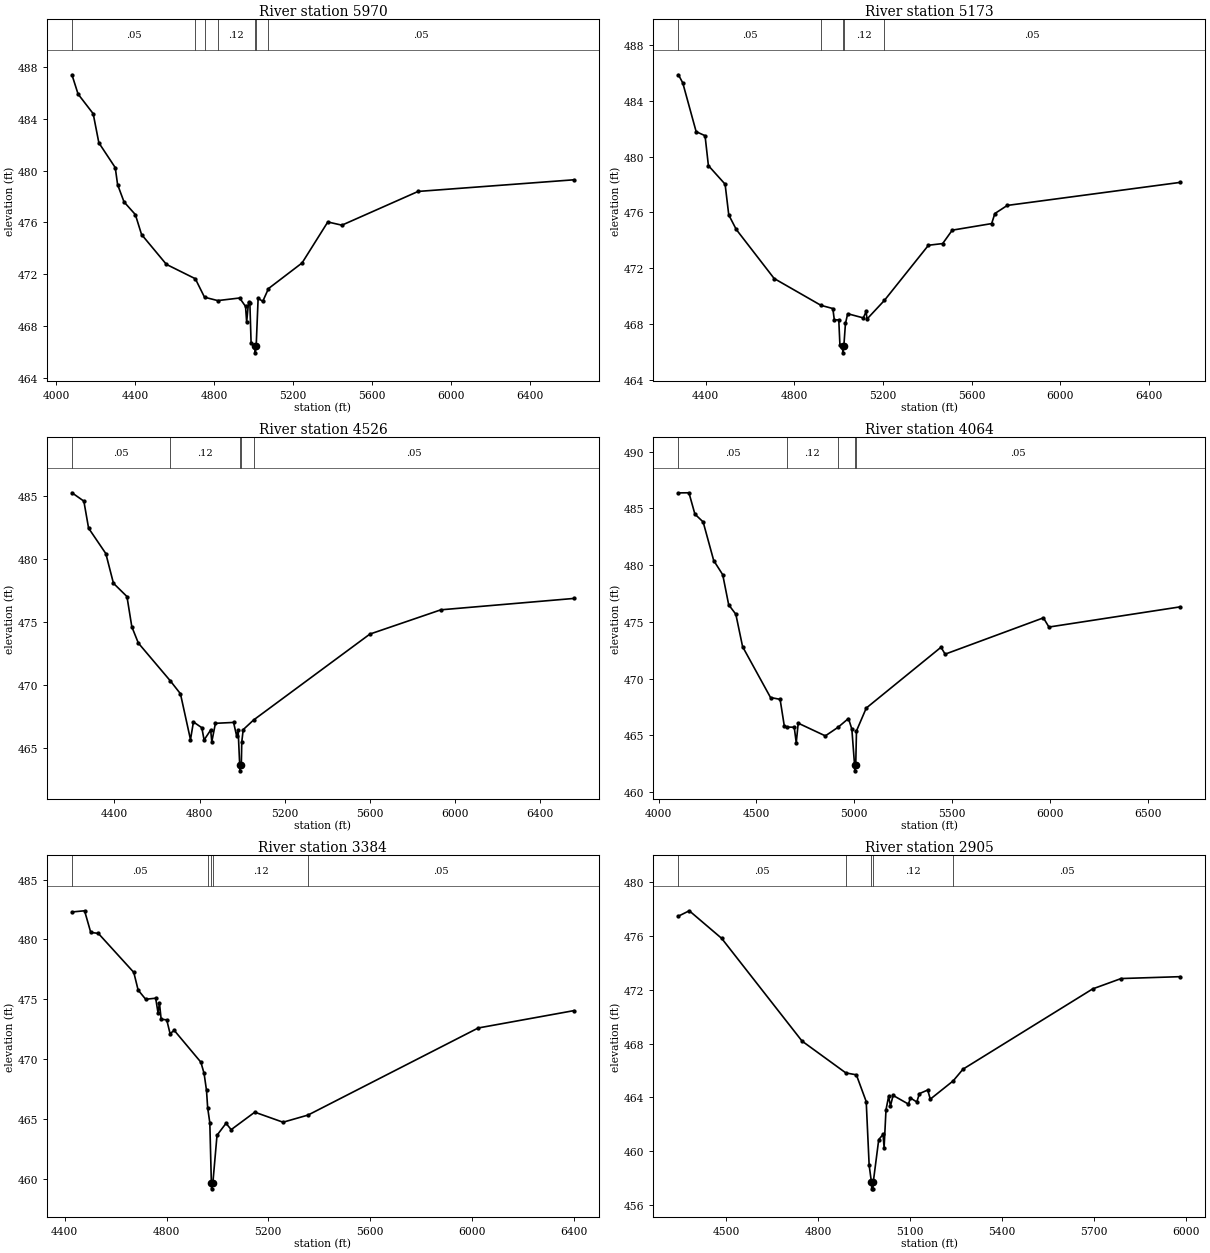
Type RM Length L Ch R = 1 ,5970    ,797,797,797
BEGIN DESCRIPTION:
Mapping XS 956b19b3
END DESCRIPTION:
XS GIS Cut Line= 3
      2721751.69      6945683.43      2720948.78      6946095.74
      2719612.11      6947046.16
#Sta/Elev= 30
  4078.6  487.41  4109.6  485.92  4186.2   484.4  4214.9  482.15    4298  480.23
  4309.8  478.92  4342.4  477.58  4399.8   476.6  4431.2  475.06  4557.1  472.75
  4703.6  471.64  4750.2  470.21  4817.4  469.95  4928.1  470.15    4958   469.5
  4963.7  468.29  4973.1  469.82  4979.9  469.78  4986.2  466.67  5006.4  466.41
  5007.2  465.91  5011.9  466.41  5021.8  470.13  5045.2  469.89  5074.3  470.88
  5244.4  472.86  5374.8  476.03  5446.1  475.78  5832.3  478.39  6621.3  479.29
#Mann= 7 ,-1 , 0
  4078.6     .05       0  4703.6     .12       0  4750.2     .05       0
  4817.4     .12       0  5006.4     .07       0  5011.9     .12       0
  5074.3     .05       0
Bank Sta=5006.4,5011.9
XS Rating Curve= 0 ,0
Exp/Cntr=0.3,0.1

Type RM Length L Ch R = 1 ,5173    ,647,647,647
BEGIN DESCRIPTION:
Mapping XS 61444c56
END DESCRIPTION:
XS GIS Cut Line= 4
       2721595.5       6945531.5      2720870.65      6945609.63
      2720753.46      6945622.65      2719642.35      6946503.72
#Sta/Elev= 30
  4276.5  485.85  4296.1  485.27  4356.5  481.78  4396.7  481.49  4411.8  479.35
  4487.2  478.02  4503.7  475.82  4537.5  474.78  4708.5  471.27  4919.7  469.35
  4973.4  469.12    4980  468.31  5000.2  468.31  5005.4  466.49  5017.5  466.45
  5018.3  465.95  5023.1  466.45  5030.3  468.05  5040.4  468.75  5110.8  468.45
  5123.5  468.91  5127.7  468.37  5205.9   469.7  5404.9  473.65    5469  473.77
  5512.3  474.73  5690.1   475.2  5704.6  475.92  5760.6   476.5  6541.5  478.15
#Mann= 5 ,-1 , 0
  4276.5     .05       0  4919.7     .12       0  5017.5     .07       0
  5023.1     .12       0  5205.9     .05       0
Bank Sta=5017.5,5023.1
XS Rating Curve= 0 ,0
Exp/Cntr=0.3,0.1

Type RM Length L Ch R = 1 ,4526    ,462,462,462
BEGIN DESCRIPTION:
Mapping XS 9a21fcca
END DESCRIPTION:
XS GIS Cut Line= 3
      2721378.45      6944780.64      2720631.94      6945054.07
      2719477.44       6946104.4
#Sta/Elev= 30
  4201.1  485.22    4257  484.56  4279.2  482.42  4360.1  480.41  4395.9  478.06
  4459.3  477.01  4482.1  474.62  4512.7  473.33  4662.8  470.34  4710.3  469.32
  4757.5  465.69  4771.3  467.09  4810.7  466.63  4821.4  465.66  4852.2  466.45
  4857.5  465.52  4874.6  466.98  4959.8  467.05  4974.2  465.97  4981.1  466.45
  4988.4  463.72  4989.3  463.22  4994.1  463.72  4996.1  463.72  4998.2   465.5
  5004.9  466.48  5053.5  467.24  5599.6  474.04  5932.7  475.96  6556.9  476.86
#Mann= 5 ,-1 , 0
  4201.1     .05       0  4662.8     .12       0  4988.4     .07       0
  4994.1     .12       0  5053.5     .05       0
Bank Sta=4988.4,4994.1
XS Rating Curve= 0 ,0
Exp/Cntr=0.3,0.1

Type RM Length L Ch R = 1 ,4064    ,680,680,680
BEGIN DESCRIPTION:
Mapping XS e3938658
END DESCRIPTION:
XS GIS Cut Line= 3
      2721309.01      6944524.56      2720427.94      6944680.81
      2719295.16      6945909.08
#Sta/Elev= 30
  4101.4  486.36  4155.2  486.37  4185.7  484.49  4227.8   483.8  4281.8   480.4
  4327.9  479.15  4358.4   476.5  4394.9  475.67  4429.5  472.81  4572.3  468.33
  4621.2  468.17  4642.7  465.82  4655.8  465.73  4693.5  465.71  4703.7  464.34
  4713.8  466.07  4852.5  464.95  4916.8   465.7  4970.7  466.48    4988  465.55
  5001.9  462.37  5002.9  461.87  5007.8  462.37  5011.7  465.39  5061.6   467.4
  5443.8  472.76  5464.8  472.15  5967.2  475.35  5995.5  474.54  6667.1  476.32
#Mann= 5 ,-1 , 0
  4101.4     .05       0  4655.8     .12       0  4916.8     .05       0
  5001.9     .04       0  5007.8     .05       0
Bank Sta=5001.9,5007.8
XS Rating Curve= 0 ,0
Exp/Cntr=0.3,0.1

Type RM Length L Ch R = 1 ,3384    ,479,479,479
BEGIN DESCRIPTION:
Mapping XS 1742c4cc
END DESCRIPTION:
XS GIS Cut Line= 6
      2721191.82      6944242.44      2720853.29      6944107.89
        2720671.      6944203.38      2720506.07      6944229.42
      2720323.78      6944272.82       2719516.5      6944941.21
#Sta/Elev= 30
  4428.3  482.29  4477.9  482.39  4502.2  480.58  4531.9   480.5  4671.3  477.24
  4688.4  475.76  4718.1  474.99  4757.4  475.08  4766.7  473.84  4772.1  474.68
  4778.9  473.32  4800.8  473.27  4813.9  472.12  4830.3  472.39    4935  469.73
  4947.6  468.79  4957.1  467.37  4961.7  465.91  4970.1  464.67  4976.2  459.64
  4977.1  459.14  4982.1  459.64  4998.4  463.62  5033.8  464.62  5054.1  464.09
  5146.8  465.55  5257.9  464.71  5356.2  465.31  6024.9  472.59  6400.8  474.04
#Mann= 5 ,-1 , 0
  4428.3     .05       0  4961.7     .12       0  4976.2     .07       0
  4982.1     .12       0  5356.2     .05       0
Bank Sta=4976.2,4982.1
XS Rating Curve= 0 ,0
Exp/Cntr=0.3,0.1

Type RM Length L Ch R = 1 ,2905    ,657,657,657
BEGIN DESCRIPTION:
Mapping XS d32ff721
END DESCRIPTION:
XS GIS Cut Line= 3
      2720922.69      6943795.41      2720284.71      6943982.02
      2719500.03      6944554.28
#Sta/Elev= 30
  4344.8  477.48  4380.2  477.88  4485.7  475.83  4747.7  468.19  4890.6  465.82
  4924.8  465.68  4956.9  463.69  4966.5  458.95  4973.9   457.7  4974.9   457.2
  4978.9   457.2  4979.9   457.7  4997.7  460.86  5011.8  461.25  5015.2  460.26
  5021.4  463.08  5029.9  464.07    5036  463.37  5044.5  464.15  5094.6   463.5
  5100.9  463.96  5121.8  463.66  5130.3  464.28  5157.3  464.55  5165.8  463.87
  5240.4  465.23  5272.4   466.1    5695  472.07  5787.7  472.84  5980.7  472.98
#Mann= 5 ,-1 , 0
  4344.8     .05       0  4890.6     .12       0  4973.9     .07       0
  4979.9     .12       0  5240.4     .05       0
Bank Sta=4973.9,4979.9
XS Rating Curve= 0 ,0
Exp/Cntr=0.3,0.1

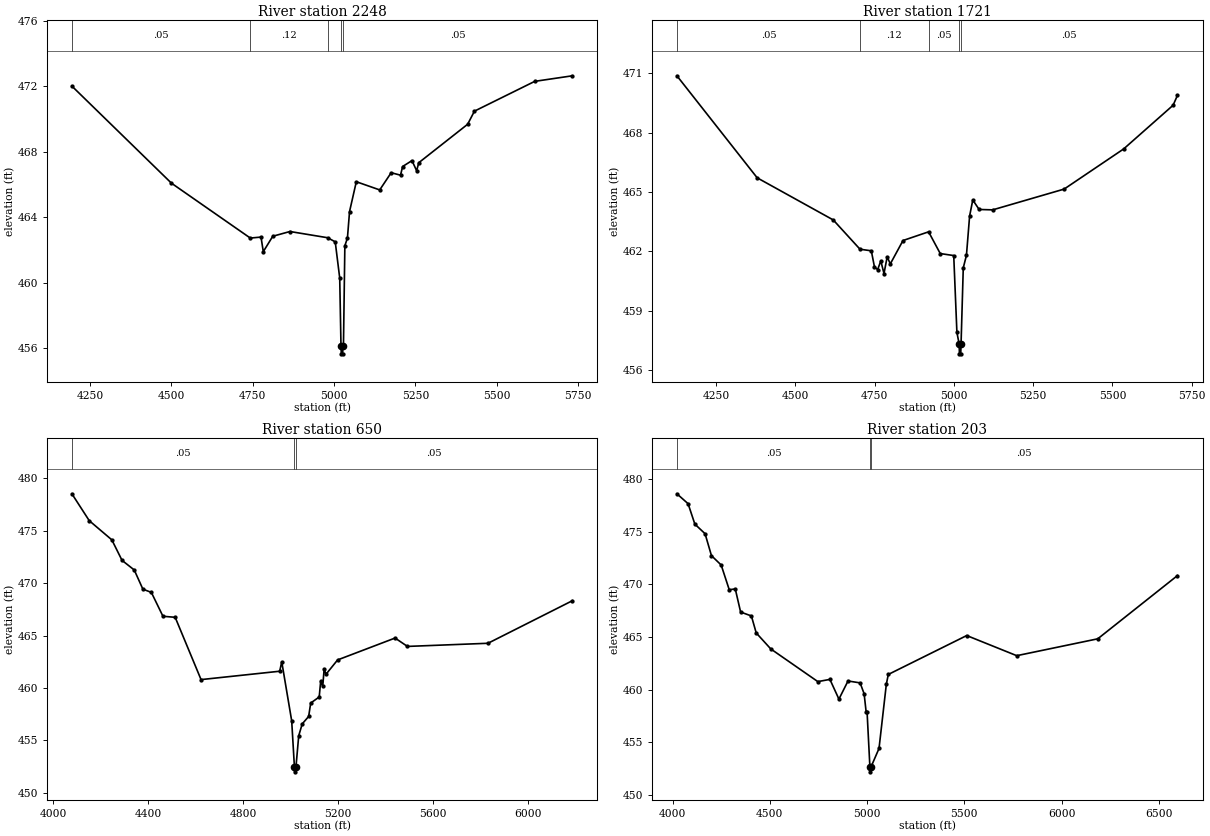
Type RM Length L Ch R = 1 ,2248    ,527,527,527
BEGIN DESCRIPTION:
Mapping XS b3bfa414
END DESCRIPTION:
XS GIS Cut Line= 3
      2720671.01      6943495.91      2719902.77      6943821.43
      2719460.04      6944368.33
#Sta/Elev= 30
  4194.7     472  4500.7  466.07  4742.9  462.72  4775.8  462.78  4782.8  461.89
  4811.9  462.83  4864.7  463.12  4980.5  462.74  5003.8  462.49  5017.6  460.28
  5021.5  456.15  5022.5  455.65  5026.6  455.65  5027.6  456.15  5029.1  456.15
  5033.4  462.25  5041.3  462.72  5047.8  464.34  5068.6  466.16  5140.5  465.66
  5175.7  466.71  5204.4  466.56  5210.9  467.09  5239.6  467.45    5254  466.83
  5260.4  467.32  5410.7  469.67  5431.5  470.47  5616.9  472.29  5732.7  472.63
#Mann= 5 ,-1 , 0
  4194.7     .05       0  4742.9     .12       0  4980.5     .05       0
  5021.5    .035       0  5027.6     .05       0
Bank Sta=5021.5,5027.6
XS Rating Curve= 0 ,0
Exp/Cntr=0.3,0.1

Type RM Length L Ch R = 1 ,1721    ,1071,1071,1071
BEGIN DESCRIPTION:
Mapping XS 74f823f7
END DESCRIPTION:
XS GIS Cut Line= 4
      2720649.31      6943430.81      2719815.96      6943435.15
      2719656.27      6943430.21       2719506.8       6943996.8
#Sta/Elev= 30
  4126.2  470.88  4379.5  465.72  4619.5  463.59  4703.8  462.11  4739.5  462.03
  4749.5  461.21  4759.5  461.08  4769.5  461.52  4779.5  460.88  4789.5  461.72
  4799.5  461.37  4839.5  462.55  4920.2  462.99    4957  461.89  4999.5  461.79
  5009.5  457.91  5016.5  457.32  5017.5  456.82  5021.6  456.82  5022.6  457.32
  5029.6  461.17  5039.6   461.8  5049.6  463.79  5059.6   464.6  5079.6  464.12
  5122.3   464.1  5347.7  465.15  5535.5  467.18  5691.5  469.39  5705.3  469.89
#Mann= 5 ,-1 , 0
  4126.2     .05       0  4703.8     .12       0  4920.2     .05       0
  5016.5     .04       0  5022.6     .05       0
Bank Sta=5016.5,5022.6
XS Rating Curve= 0 ,0
Exp/Cntr=0.3,0.1

Type RM Length L Ch R = 1 ,650     ,447,447,447
BEGIN DESCRIPTION:
Mapping XS 868430c6
END DESCRIPTION:
XS GIS Cut Line= 4
      2720657.58      6942320.96      2719941.83      6942781.21
      2719655.37       6943189.2       2719473.2      6943926.56
#Sta/Elev= 30
  4079.5  478.54  4152.7  475.97  4247.8  474.14  4290.8  472.18  4342.3  471.26
  4378.6  469.43  4414.3  469.12  4463.2  466.84  4514.7  466.74  4623.7  460.79
    4955  461.59  4963.7  462.49  5005.6  456.85    5017  452.48  5018.1  451.98
  5023.7  452.48  5035.2  455.43    5050  456.56    5077  457.27  5085.7  458.55
  5121.5  459.13  5127.6  460.61  5136.3  460.15  5142.4   461.8  5150.1   461.3
    5199  462.67  5441.1  464.76  5493.3  463.96  5832.5  464.26  6188.5  468.33
#Mann= 3 ,-1 , 0
  4079.5     .05       0    5017     .04       0  5023.7     .05       0
Bank Sta=5017,5023.7
XS Rating Curve= 0 ,0
Exp/Cntr=0.3,0.1

Type RM Length L Ch R = 1 ,203     ,0,0,0
BEGIN DESCRIPTION:
Wolf Creek T4 1.0
END DESCRIPTION:
XS GIS Cut Line= 3
        2720576.        6942261.      2719631.46      6942513.45
      2719350.75      6944084.47
#Sta/Elev= 30
  4022.3  478.58  4079.8  477.64  4114.7   475.7  4167.2  474.79    4200  472.71
    4250  471.82  4291.4  469.48  4322.5  469.55  4349.9  467.36  4405.3  466.99
  4430.1  465.38    4505  463.86  4746.9  460.76    4809  460.97  4855.3   459.1
  4902.1  460.82  4964.2  460.64  4984.9  459.61  4995.1  457.91    5000  457.91
  5014.5   452.7  5015.5   452.2  5021.2   452.7  5061.5  454.42  5099.1  460.51
  5109.2  461.44  5512.4  465.13  5769.5  463.22    6186  464.82  6595.9  470.82
#Mann= 3 ,-1 , 0
  4022.3     .05       0  5014.5     .05       0  5021.2     .05       0
Bank Sta=5014.5,5021.2
XS Rating Curve= 0 ,0
Exp/Cntr=0.3,0.1

Chan Stop Cuts=-1
Use User Specified Reach Order=0
Composite Channel Slope=5