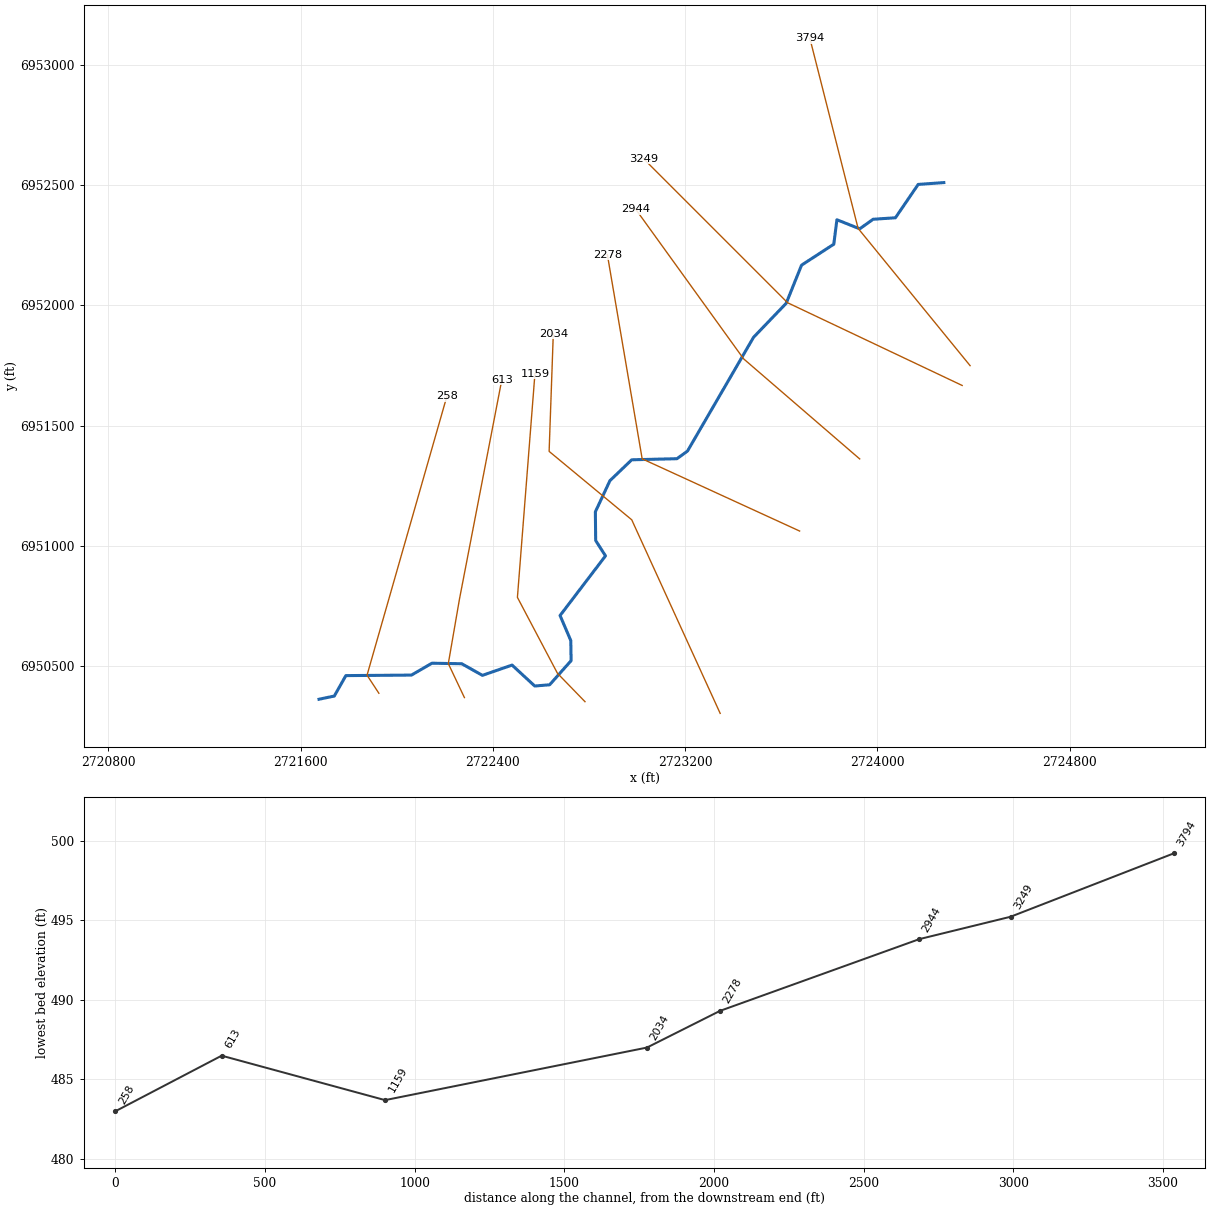
--- Wolf Creek T4_1.prj (project) ---

Proj Title=Wolf Creek T4_1 Base Level Engineering
Current Plan=p01
Default Exp/Contr=0.3,0.1
English Units
Geom File=g01
Flow File=f01
Plan File=p01
Y Axis Title=Elevation
X Axis Title(PF)=Main Channel Distance
X Axis Title(XS)=Station
BEGIN DESCRIPTION:
Wolf Creek T4_1
END DESCRIPTION:
DSS Export Rating Curves= 0
DSS Export Rating Curve Sorted= 0
DSS Export Volume Flow Curves= 0
DXF OffsetX= 0
DXF OffsetY= 0
DXF ScaleX= 1
DXF ScaleY= 10

--- Wolf Creek T4_1.p01 (plan) ---

Plan Title=Multiple Run
Short Identifier=Multiple
Geom File=g01
Flow File=f01
Subcritical Flow
K Sum by GR= 0
Std Step Tol= 0.01
Critical Tol= 0.01
Num of Std Step Trials= 20
Max Error Tol= 0.3
Flow Tol Ratio= 0.001
Split Flow NTrial= 30
Split Flow Tol= 0.02
Split Flow Ratio= 0.02
Log Output Level= 0
Friction Slope Method= 1
Unsteady Friction Slope Method= 2
Unsteady Bridges Friction Slope Method= 1
Parabolic Critical Depth
Global Vel Dist=  1 , 1 , 1
Global Log Level= 0
CheckData=True
Encroach Param= -1, 0, 0, 0
BEGIN DESCRIPTION:
Multiple Run
END DESCRIPTION:

--- Wolf Creek T4_1.f01 (steady flow) ---

Flow Title=Multiple
Program Version=4.10
Number of Profiles= 7
Profile Names=10-year,25-year,50-year,1pct_min,100-year,1pct_plu,500-year
River Rch & RM=Wolf Creek T4_1,Reach-1         ,3794
     351     451     529     309     616    1230     833
Boundary for River Rch & Prof#=Wolf Creek T4_1,Reach-1         , 1
Up Type= 0
Dn Type= 3
Dn Slope=0.009
Boundary for River Rch & Prof#=Wolf Creek T4_1,Reach-1         , 2
Up Type= 0
Dn Type= 3
Dn Slope=0.009
Boundary for River Rch & Prof#=Wolf Creek T4_1,Reach-1         , 3
Up Type= 0
Dn Type= 3
Dn Slope=0.009
Boundary for River Rch & Prof#=Wolf Creek T4_1,Reach-1         , 4
Up Type= 0
Dn Type= 3
Dn Slope=0.009
Boundary for River Rch & Prof#=Wolf Creek T4_1,Reach-1         , 5
Up Type= 0
Dn Type= 3
Dn Slope=0.009
Boundary for River Rch & Prof#=Wolf Creek T4_1,Reach-1         , 6
Up Type= 0
Dn Type= 3
Dn Slope=0.009
Boundary for River Rch & Prof#=Wolf Creek T4_1,Reach-1         , 7
Up Type= 0
Dn Type= 3
Dn Slope=0.009
DSS Import GetInterval= 0
DSS Import GetPeak= 0
DSS Import FillOption= 0

--- Wolf Creek T4_1.g01 (geometry) ---

Geom Title=Existing Conditions
Program Version=4.10

River Reach=Wolf Creek T4_1 ,Reach-1
Reach XY= 30
        2724276.        6952511.      2724169.46       6952503.4
      2724074.72      6952364.52       2723981.9      6952358.44
      2723925.96       6952318.6      2723831.26      6952356.34
      2723818.23       6952254.6      2723684.03      6952167.34
      2723620.17       6952008.7      2723484.16      6951867.05
      2723209.54      6951393.86      2723165.72      6951361.99
      2722977.45      6951357.47      2722886.75      6951270.71
      2722826.04      6951140.97      2722827.38      6951021.44
      2722868.19      6950957.59      2722679.14      6950709.36
      2722723.81      6950605.03      2722725.07      6950521.47
       2722635.7      6950421.16      2722573.71      6950416.09
      2722479.41      6950503.19      2722355.96      6950460.42
      2722270.06      6950508.75      2722146.04      6950510.95
      2722060.78      6950461.52      2721787.81      6950459.38
      2721739.74      6950374.37        2721676.        6950361.

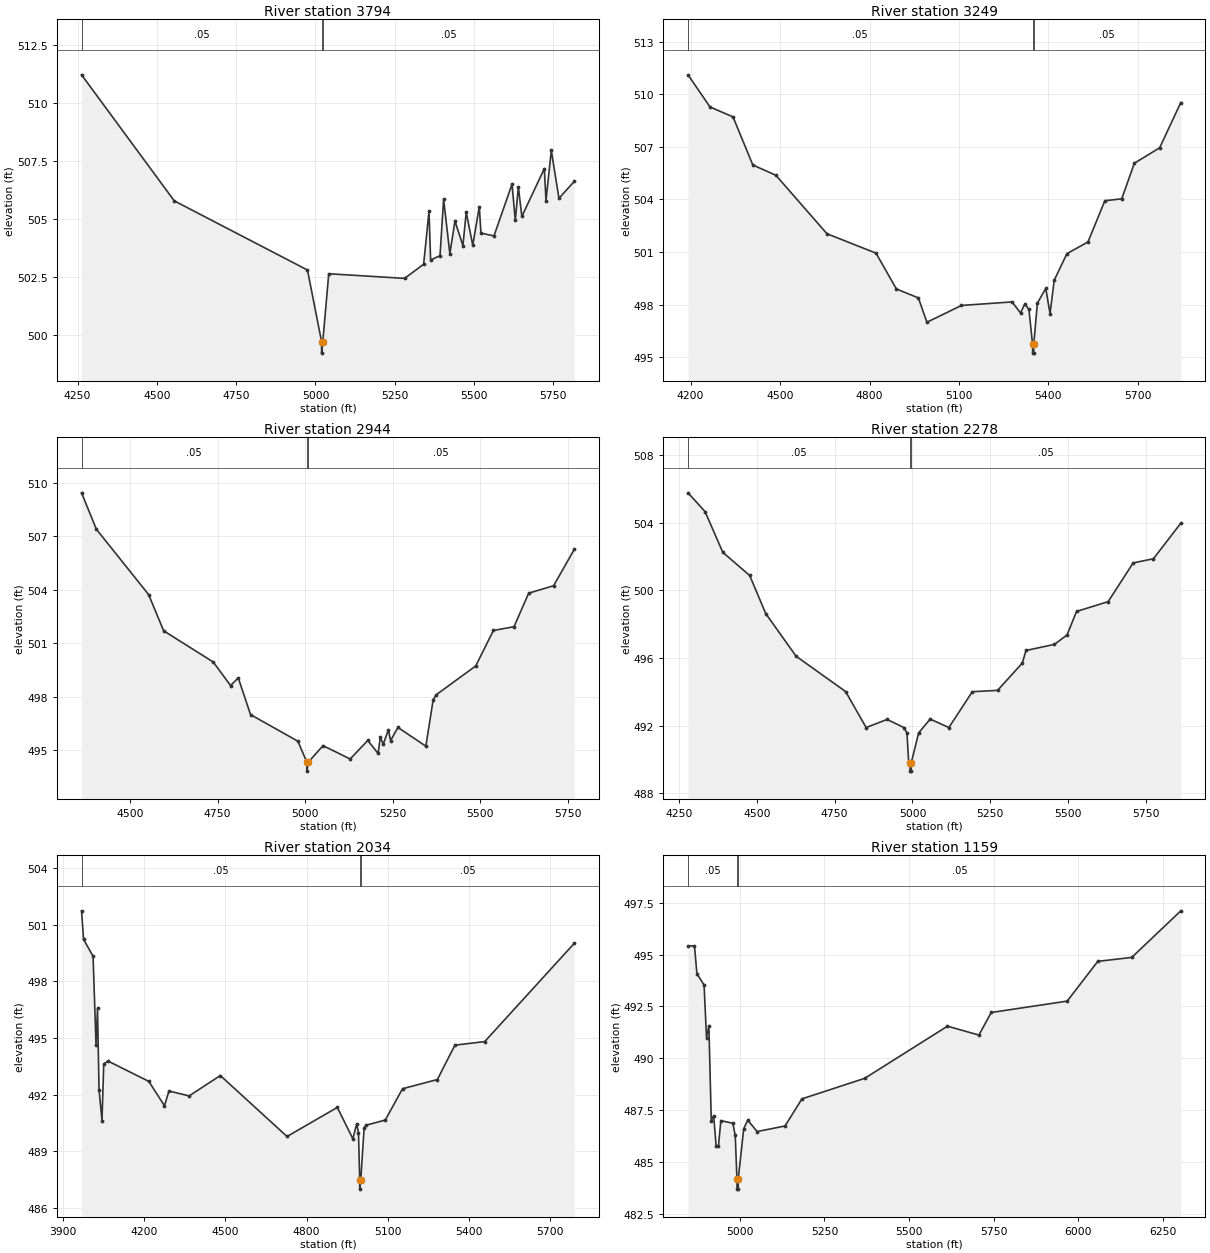
Type RM Length L Ch R = 1 ,3794    ,545,545,545
BEGIN DESCRIPTION:
Wolf Creek T4_1 5.0
END DESCRIPTION:
XS GIS Cut Line= 3
       2724385.4      6951749.22      2723919.33      6952320.53
       2723718.7      6953111.27
#Sta/Elev= 30
  4262.7  511.21  4554.9  505.78  4974.8   502.8  5019.1  499.72  5019.4  499.22
  5023.1  499.72  5041.8  502.64    5281  502.44  5340.9  503.05  5357.8  505.33
  5362.9  503.23  5392.5  503.42  5403.9  505.85  5423.5  503.51  5439.7  504.91
  5464.7  503.85  5475.1  505.29  5495.7  503.87  5516.3  505.53  5521.6  504.39
  5562.6  504.27  5619.5   506.5  5629.8  504.94  5639.4  506.38  5650.5  505.11
  5721.3  507.17  5726.5  505.79  5743.3  507.95  5767.4  505.89  5815.8  506.62
#Mann= 3 ,-1 , 0
  4262.7     .05       0  5019.1     .04       0  5023.1     .05       0
Bank Sta=5019.1,5023.1
XS Rating Curve= 0 ,0
Exp/Cntr=0.3,0.1

Type RM Length L Ch R = 1 ,3249    ,305,305,305
BEGIN DESCRIPTION:
Wolf Creek T4_1 4.0
END DESCRIPTION:
XS GIS Cut Line= 3
       2724352.4      6951666.78        2723626.        6952011.
      2723025.97      6952611.03
#Sta/Elev= 30
  4191.4   511.1    4265  509.27  4342.3   508.7  4408.7  505.96  4486.2  505.37
  4657.2  502.04  4821.9  500.93  4890.1  498.89  4963.9  498.38  4992.5  496.99
  5108.4  497.95  5278.1  498.15  5306.4  497.52  5320.5  498.02  5334.6  497.73
  5346.8  495.73    5347  495.23  5350.5  495.23  5350.8  495.73  5362.9  498.08
  5391.2  498.92  5405.3  497.48  5419.5  499.39  5461.9   500.9  5532.6  501.57
  5589.2  503.92  5645.8  504.03  5688.2  506.06    5773  506.94  5843.8  509.52
#Mann= 3 ,-1 , 0
  4191.4     .05       0  5346.8     .04       0  5350.8     .05       0
Bank Sta=5346.8,5350.8
XS Rating Curve= 0 ,0
Exp/Cntr=0.3,0.1

Type RM Length L Ch R = 1 ,2944    ,666,666,666
BEGIN DESCRIPTION:
Wolf Creek T4_1 3.0
END DESCRIPTION:
XS GIS Cut Line= 3
      2723925.96      6951361.03      2723442.95      6951777.55
      2722993.86      6952400.31
#Sta/Elev= 30
  4362.2  509.43  4404.4  507.39  4553.6  503.72  4596.4  501.69  4737.9  499.94
  4787.3  498.62  4809.2  499.05  4844.3  496.99  4979.2   495.5  5004.9  494.32
  5005.1  493.82  5008.9  494.32    5051  495.25  5128.4   494.5  5178.7  495.54
  5208.1  494.81  5214.3  495.71  5222.8  495.34  5237.5  496.13  5243.7  495.53
  5264.6  496.27  5344.3  495.22  5365.2  497.82  5373.7   498.1  5486.6  499.72
    5537  501.71  5595.8  501.92  5637.6   503.8  5708.7  504.22  5767.8  506.26
#Mann= 3 ,-1 , 0
  4362.2     .05       0  5004.9     .04       0  5008.9     .05       0
Bank Sta=5004.9,5008.9
XS Rating Curve= 0 ,0
Exp/Cntr=0.3,0.1

Type RM Length L Ch R = 1 ,2278    ,244,244,244
BEGIN DESCRIPTION:
Wolf Creek T4_1 2.0
END DESCRIPTION:
XS GIS Cut Line= 3
      2723675.99        6951061.       2723020.8      6951361.47
        2722876.      6952211.02
#Sta/Elev= 30
  4279.2  505.77  4333.9  504.66  4390.9  502.25  4477.2  500.88  4528.9  498.62
  4626.4   496.1  4785.3  494.01  4851.3  491.88  4918.8  492.36  4972.3  491.88
  4982.3  491.57  4987.8  489.86  4992.3   489.8  4992.5   489.3    4996   489.3
  4996.3   489.8  5019.8  491.56  5056.8  492.38    5117  491.88  5192.3     494
  5273.4  494.08  5352.7  495.69  5364.7  496.44    5456   496.8  5496.6  497.36
    5527  498.75  5628.5  499.33  5708.8  501.62    5774  501.87  5861.8  503.97
#Mann= 3 ,-1 , 0
  4279.2     .05       0  4992.3     .04       0  4996.3     .05       0
Bank Sta=4992.3,4996.3
XS Rating Curve= 0 ,0
Exp/Cntr=0.3,0.1

Type RM Length L Ch R = 1 ,2034    ,875,875,875
BEGIN DESCRIPTION:
Mapping XS 1fbaa57f
END DESCRIPTION:
XS GIS Cut Line= 4
      2723345.44      6950302.21      2722977.39      6951107.76
      2722633.64      6951392.48        2722651.      6951882.08
#Sta/Elev= 30
  3967.9  501.74  3975.3  500.23  4010.5  499.33  4021.4  494.63  4026.9  496.58
  4032.5  492.27  4043.5  490.62  4049.9  493.62  4065.5  493.78  4216.6   492.7
  4274.4  491.41  4291.1  492.19  4365.7  491.93  4480.9  493.01  4727.6  489.78
  4913.6  491.32    4971  489.66  4985.2  490.45  4991.8  489.99  4996.3  487.49
  4996.5  486.99  5000.3  487.49  5012.6  490.23  5020.4  490.38  5090.8  490.65
  5154.6  492.31  5283.5   492.8  5348.4  494.62  5458.5  494.81  5789.8  500.02
#Mann= 3 ,-1 , 0
  3967.9     .05       0  4996.3     .04       0  5000.3     .05       0
Bank Sta=4996.3,5000.3
XS Rating Curve= 0 ,0
Exp/Cntr=0.3,0.1

Type RM Length L Ch R = 1 ,1159    ,546,546,546
BEGIN DESCRIPTION:
Mapping XS a6c76647
END DESCRIPTION:
XS GIS Cut Line= 4
      2722782.91      6950350.84      2722668.36      6950468.87
      2722501.69      6950784.84      2722574.61      6951715.38
#Sta/Elev= 30
    4847  495.43  4866.1  495.42  4873.3  494.08  4894.4  493.54  4901.6     491
  4908.6  491.56  4915.7  486.98  4922.7  487.23  4929.9  485.78  4936.8  485.75
    4944  486.99  4979.3  486.86  4986.5  486.27  4991.4  484.18  4991.7  483.68
  4995.2  483.68  4995.4  484.18  5011.5   486.6  5023.4  487.01  5051.1  486.46
  5133.5  486.73  5183.5  488.04  5368.7  489.03  5613.2  491.55  5705.9  491.12
  5742.4  492.21  5966.7  492.76    6057  494.68  6157.3  494.87  6302.1  497.12
#Mann= 3 ,-1 , 0
    4847     .05       0  4991.4     .04       0  4995.4     .05       0
Bank Sta=4991.4,4995.4
XS Rating Curve= 0 ,0
Exp/Cntr=0.3,0.1

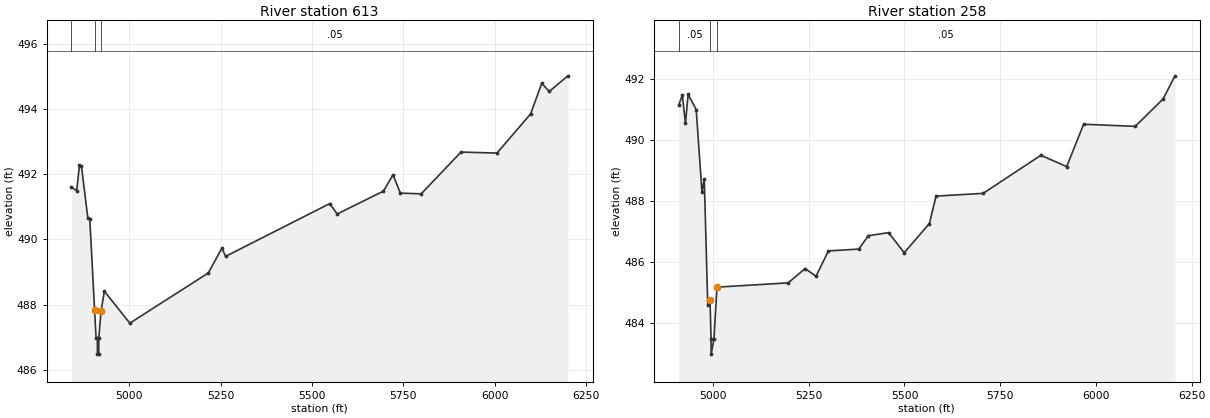
Type RM Length L Ch R = 1 ,613     ,355,355,355
BEGIN DESCRIPTION:
Mapping XS 559166ca
END DESCRIPTION:
XS GIS Cut Line= 4
      2722281.14      6950367.95      2722214.15      6950509.28
      2722260.58      6950777.92      2722436.92      6951691.22
#Sta/Elev= 30
  4841.4   491.6  4855.8   491.5  4863.2  492.28  4868.8  492.24    4886  490.67
  4891.5  490.64  4904.7 487.823  4908.7  486.99  4912.2  486.98  4912.5  486.48
    4916  486.48  4916.2  486.98  4922.2  487.79  4931.4  488.41  5001.2  487.43
    5216  488.97  5253.3  489.73  5263.4  489.48  5548.6   491.1  5568.9  490.78
  5695.4  491.48  5721.7  491.98  5742.1  491.42  5799.1   491.4  5907.9  492.68
  6006.5  492.65  6098.5  493.85  6129.1  494.79  6149.5  494.54  6200.6  495.02
#Mann= 3 ,-1 , 0
  4841.4     .05       0  4904.7    .035       0  4922.2     .05       0
Bank Sta=4904.7,4922.2
XS Rating Curve= 0 ,0
Exp/Cntr=0.3,0.1

Type RM Length L Ch R = 1 ,258     ,0,0,0
BEGIN DESCRIPTION:
Wolf Creek T4_1 1.0
END DESCRIPTION:
XS GIS Cut Line= 3
      2721925.12        6950386.       2721875.9      6950461.11
      2722207.96      6951620.91
#Sta/Elev= 30
  4910.2  491.15  4919.9  491.49  4928.1  490.56    4935  491.51  4956.1  491.01
  4971.2   488.3  4977.2  488.73  4986.3  484.58  4992.3  484.75  4994.9  483.48
  4995.2  482.98  5002.5  483.48  5010.3  485.18  5196.3  485.32  5240.4  485.79
    5269  485.54  5301.5  486.37  5380.7  486.43  5405.6  486.87  5458.6  486.97
  5499.2  486.31  5565.1  487.27  5582.4  488.17  5705.4  488.26  5856.1  489.51
  5923.6  489.14  5967.8  490.53  6102.5  490.46  6175.3  491.36  6206.4  492.12
#Mann= 3 ,-1 , 0
  4910.2     .05       0  4992.3    .035       0  5010.3     .05       0
Bank Sta=4992.3,5010.3
XS Rating Curve= 0 ,0
Exp/Cntr=0.3,0.1

Chan Stop Cuts=-1
Use User Specified Reach Order=0
Composite Channel Slope=5