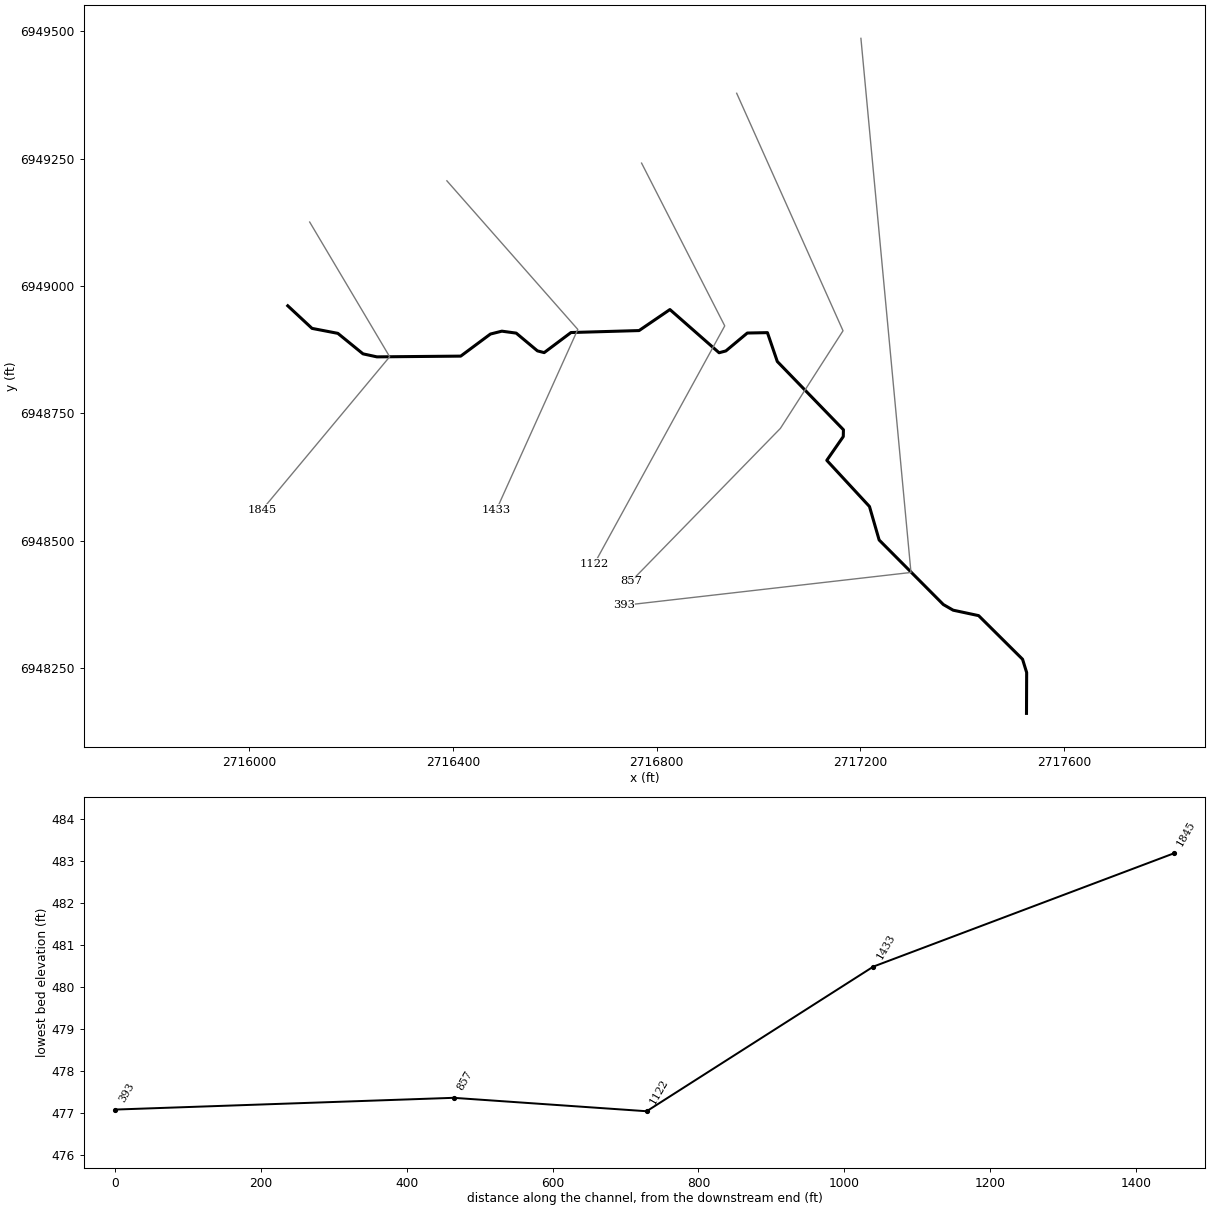
--- Wolf Creek T5.prj (project) ---

Proj Title=Wolf Creek T5 Base Level Engineering
Current Plan=p01
Default Exp/Contr=0.3,0.1
English Units
Geom File=g01
Flow File=f01
Plan File=p01
BEGIN DESCRIPTION:
Wolf Creek T5
END DESCRIPTION:

--- Wolf Creek T5.p01 (plan) ---

Plan Title=Multiple Run
Short Identifier=Multiple
Geom File=g01
Flow File=f01
Subcritical Flow
K Sum by GR= 0
Std Step Tol= 0.01
Critical Tol= 0.01
Num of Std Step Trials= 20
Max Error Tol= 0.3
Flow Tol Ratio= 0.001
Split Flow NTrial= 30
Split Flow Tol= 0.02
Split Flow Ratio= 0.02
Log Output Level= 0
Friction Slope Method= 1
Unsteady Friction Slope Method= 2
Unsteady Bridges Friction Slope Method= 1
Parabolic Critical Depth
Global Vel Dist=  1 , 1 , 1
Global Log Level= 0
CheckData=True
Encroach Param= -1, 0, 0, 0
BEGIN DESCRIPTION:
Multiple Run
END DESCRIPTION:

--- Wolf Creek T5.f01 (steady flow) ---

Flow Title=Multiple
Number of Profiles=7
Profile Names=10-year,25-year,50-year,1pct_min,100-year,1pct_plu,500-year
River Rch & RM= Wolf Creek T5,Reach-1,1845
     229     287     330     189     378     754     493
Boundary for River Rch & Prof#=Wolf Creek T5,Reach-1,1
Up Type=0
Dn Type=3
Dn Slope=0.005
Boundary for River Rch & Prof#=Wolf Creek T5,Reach-1,2
Up Type=0
Dn Type=3
Dn Slope=0.005
Boundary for River Rch & Prof#=Wolf Creek T5,Reach-1,3
Up Type=0
Dn Type=3
Dn Slope=0.005
Boundary for River Rch & Prof#=Wolf Creek T5,Reach-1,4
Up Type=0
Dn Type=3
Dn Slope=0.005
Boundary for River Rch & Prof#=Wolf Creek T5,Reach-1,5
Up Type=0
Dn Type=3
Dn Slope=0.005
Boundary for River Rch & Prof#=Wolf Creek T5,Reach-1,6
Up Type=0
Dn Type=3
Dn Slope=0.005
Boundary for River Rch & Prof#=Wolf Creek T5,Reach-1,7
Up Type=0
Dn Type=3
Dn Slope=0.005

--- Wolf Creek T5.g01 (geometry) ---

Geom Title=Existing Conditions

River Reach=Wolf Creek T5,Reach-1
Reach XY= 30
      2716076.00      6948961.00      2716123.63      6948916.67
      2716174.31      6948906.92      2716223.65      6948866.70
      2716250.91      6948860.78      2716415.50      6948862.24
      2716473.83      6948905.60      2716496.21      6948911.21
      2716524.36      6948907.39      2716566.07      6948872.53
      2716579.29      6948869.11      2716631.86      6948908.53
      2716765.56      6948912.40      2716826.10      6948953.66
      2716922.61      6948868.86      2716935.92      6948872.42
      2716978.01      6948907.56      2717017.50      6948908.33
      2717036.89      6948851.67      2717166.70      6948717.67
      2717166.38      6948704.33      2717134.02      6948657.67
      2717217.80      6948567.05      2717236.78      6948501.32
      2717362.79      6948374.63      2717382.05      6948363.54
      2717432.07      6948352.85      2717518.27      6948267.24
      2717526.33      6948241.14      2717526.00      6948161.00

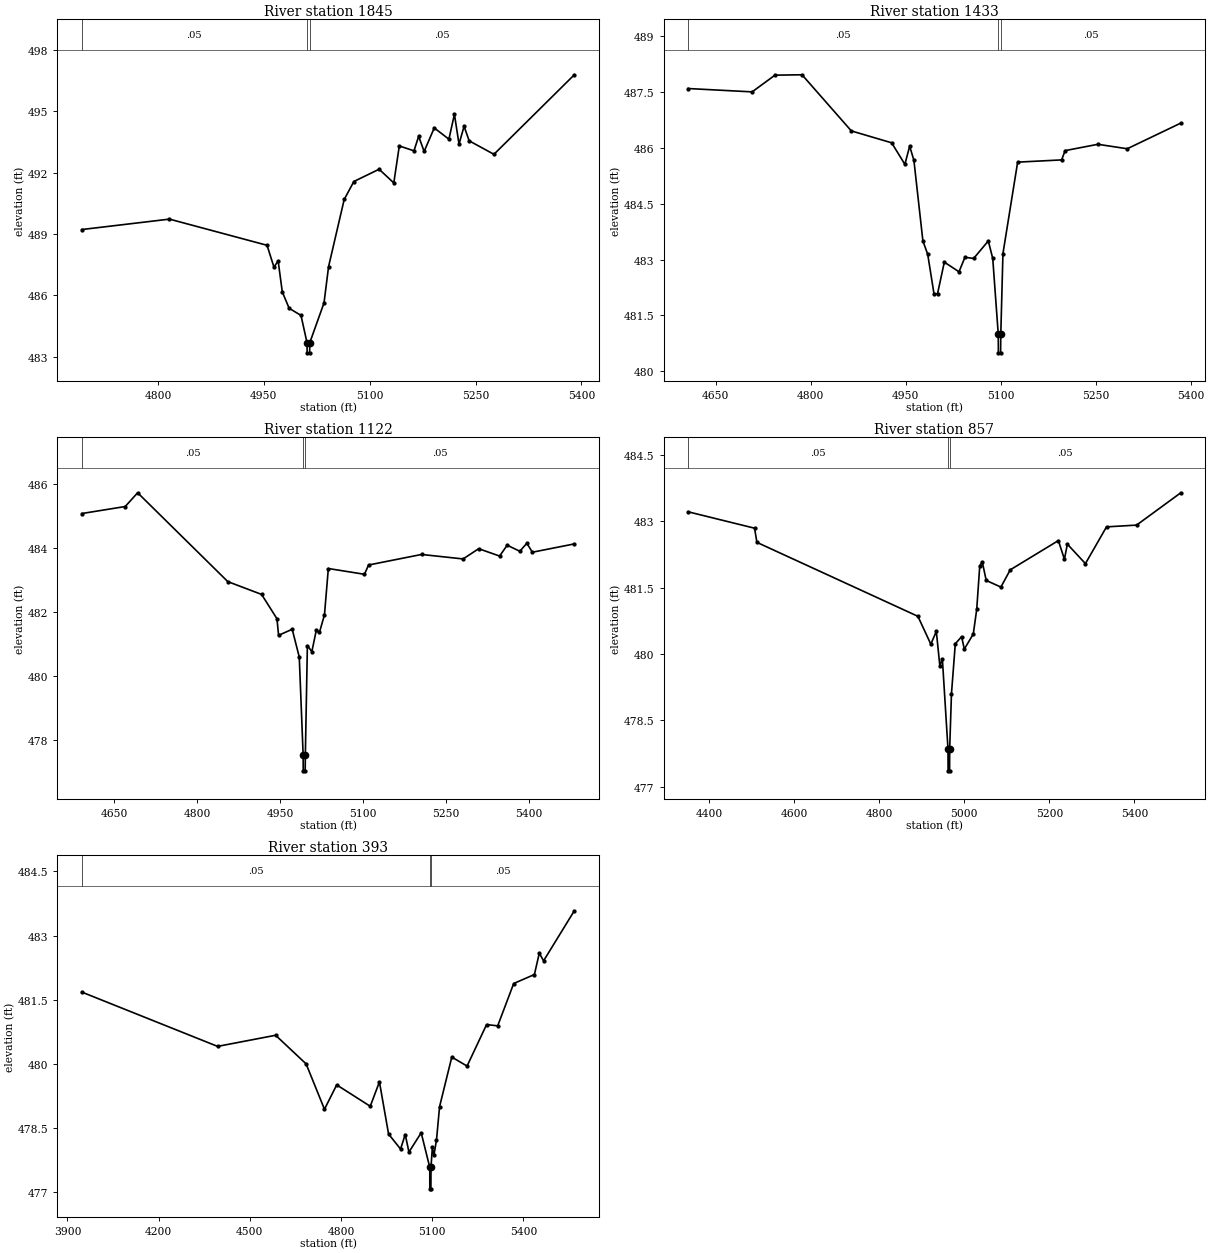
Type RM Length L Ch R = 1,1845,412,412,412
BEGIN DESCRIPTION:
Wolf Creek T5 1.0
END DESCRIPTION:
XS GIS Cut Line= 3
      2716119.02      6949125.40      2716276.00      6948861.00
      2716026.00      6948561.00
#Sta/Elev= 30
  4692.0  489.22  4816.3  489.73  4954.6  488.45  4964.4  487.38  4970.3  487.69
  4976.2  486.17  4985.9  485.37  5002.7  485.02  5011.2  483.69  5011.4  483.19
  5014.9  483.19  5015.2  483.69  5035.3  485.63  5041.8  487.41  5063.9  490.69
  5077.6  491.57  5113.4  492.17  5134.2  491.50  5142.0  493.31  5162.8  493.07
  5169.4  493.78  5177.2  493.04  5191.5  494.19  5212.3  493.64  5220.1  494.86
  5226.6  493.40  5233.8  494.27  5241.0  493.56  5276.1  492.90  5390.0  496.79
#Mann=3,-1,0
  4692.0    0.05       0  5011.2    0.04       0  5015.2    0.05       0
Bank Sta=5011.2,5015.2
Exp/Cntr=0.3,0.1

Type RM Length L Ch R = 1,1433,311,311,311
BEGIN DESCRIPTION:
Mapping XS 708ef803
END DESCRIPTION:
XS GIS Cut Line= 3
      2716388.34      6949206.32      2716645.28      6948914.66
      2716485.55      6948560.50
#Sta/Elev= 30
  4606.8  487.60  4707.7  487.51  4743.7  487.96  4786.4  487.97  4864.2  486.46
  4927.8  486.14  4948.7  485.56  4956.2  486.05  4962.9  485.67  4977.1  483.50
  4984.7  483.14  4994.6  482.08  5000.2  482.08  5010.9  482.93  5034.1  482.67
  5043.4  483.06  5057.2  483.03  5080.3  483.50  5087.3  483.03  5096.0  480.99
  5096.2  480.49  5099.7  480.49  5100.0  480.99  5103.4  483.16  5126.6  485.62
  5196.0  485.68  5201.5  485.93  5253.2  486.10  5299.5  485.98  5384.0  486.67
#Mann=3,-1,0
  4606.8    0.05       0  5096.0    0.04       0  5100.0    0.05       0
Bank Sta=5096,5100
Exp/Cntr=0.3,0.1

Type RM Length L Ch R = 1,1122,265,265,265
BEGIN DESCRIPTION:
Mapping XS eb81734c
END DESCRIPTION:
XS GIS Cut Line= 3
      2716770.48      6949241.09      2716933.70      6948921.61
      2716677.63      6948454.45
#Sta/Elev= 30
  4590.7  485.09  4669.4  485.31  4691.9  485.74  4855.1  482.96  4916.2  482.56
  4944.0  481.80  4947.0  481.28  4971.6  481.47  4984.4  480.60  4991.4  477.54
  4991.6  477.04  4995.1  477.04  4995.4  477.54  4999.1  480.96  5007.2  480.77
  5015.2  481.44  5020.9  481.37  5030.0  481.92  5037.0  483.37  5102.4  483.19
  5109.8  483.48  5205.7  483.81  5280.9  483.67  5309.1  483.99  5347.0  483.76
  5360.7  484.10  5383.5  483.91  5396.3  484.16  5406.3  483.88  5482.2  484.14
#Mann=3,-1,0
  4590.7    0.05       0  4991.4    0.04       0  4995.4    0.05       0
Bank Sta=4991.4,4995.4
Exp/Cntr=0.3,0.1

Type RM Length L Ch R = 1,857,464,464,464
BEGIN DESCRIPTION:
Mapping XS 4416ea85
END DESCRIPTION:
XS GIS Cut Line= 4
      2716957.14      6949378.20      2717165.88      6948911.99
      2717042.94      6948720.37      2716749.92      6948420.14
#Sta/Elev= 30
  4351.0  483.21  4507.0  482.84  4512.5  482.52  4891.0  480.85  4921.4  480.22
  4934.3  480.51  4942.6  479.73  4948.5  479.89  4961.7  477.86  4962.0  477.36
  4965.5  477.36  4965.7  477.86  4969.9  479.10  4978.9  480.23  4993.7  480.39
  5000.1  480.11  5021.2  480.45  5029.3  481.01  5036.4  481.99  5042.3  482.08
  5051.6  481.66  5086.1  481.51  5108.1  481.90  5221.2  482.56  5235.4  482.14
  5242.4  482.48  5284.8  482.04  5334.4  482.87  5405.1  482.91  5509.0  483.64
#Mann=3,-1,0
  4351.0    0.05       0  4961.7    0.04       0  4965.7    0.05       0
Bank Sta=4961.7,4965.7
Exp/Cntr=0.3,0.1

Type RM Length L Ch R = 1,393,0,0,0
BEGIN DESCRIPTION:
Wolf Creek T5 0.0
END DESCRIPTION:
XS GIS Cut Line= 3
      2717201.00      6949486.00      2717299.25      6948437.59
      2716735.54      6948372.99
#Sta/Elev= 30
  3947.0  481.68  4393.9  480.41  4584.8  480.67  4685.2  480.00  4745.5  478.94
  4785.7  479.51  4896.1  479.01  4926.3  479.58  4956.4  478.36  4995.8  478.01
  5011.1  478.35  5023.4  477.94  5063.7  478.39  5091.9  477.58  5092.1  477.08
  5095.6  477.08  5095.9  477.58  5100.4  478.05  5105.4  477.86  5114.0  478.22
  5124.1  479.00  5164.3  480.16  5214.6  479.95  5278.8  480.92  5315.3  480.89
  5368.0  481.88  5436.1  482.09  5452.2  482.59  5466.3  482.41  5567.4  483.58
#Mann=3,-1,0
  3947.0    0.05       0  5091.9    0.04       0  5095.9    0.05       0
Bank Sta=5091.9,5095.9
Exp/Cntr=0.3,0.1

Chan Stop Cuts=-1