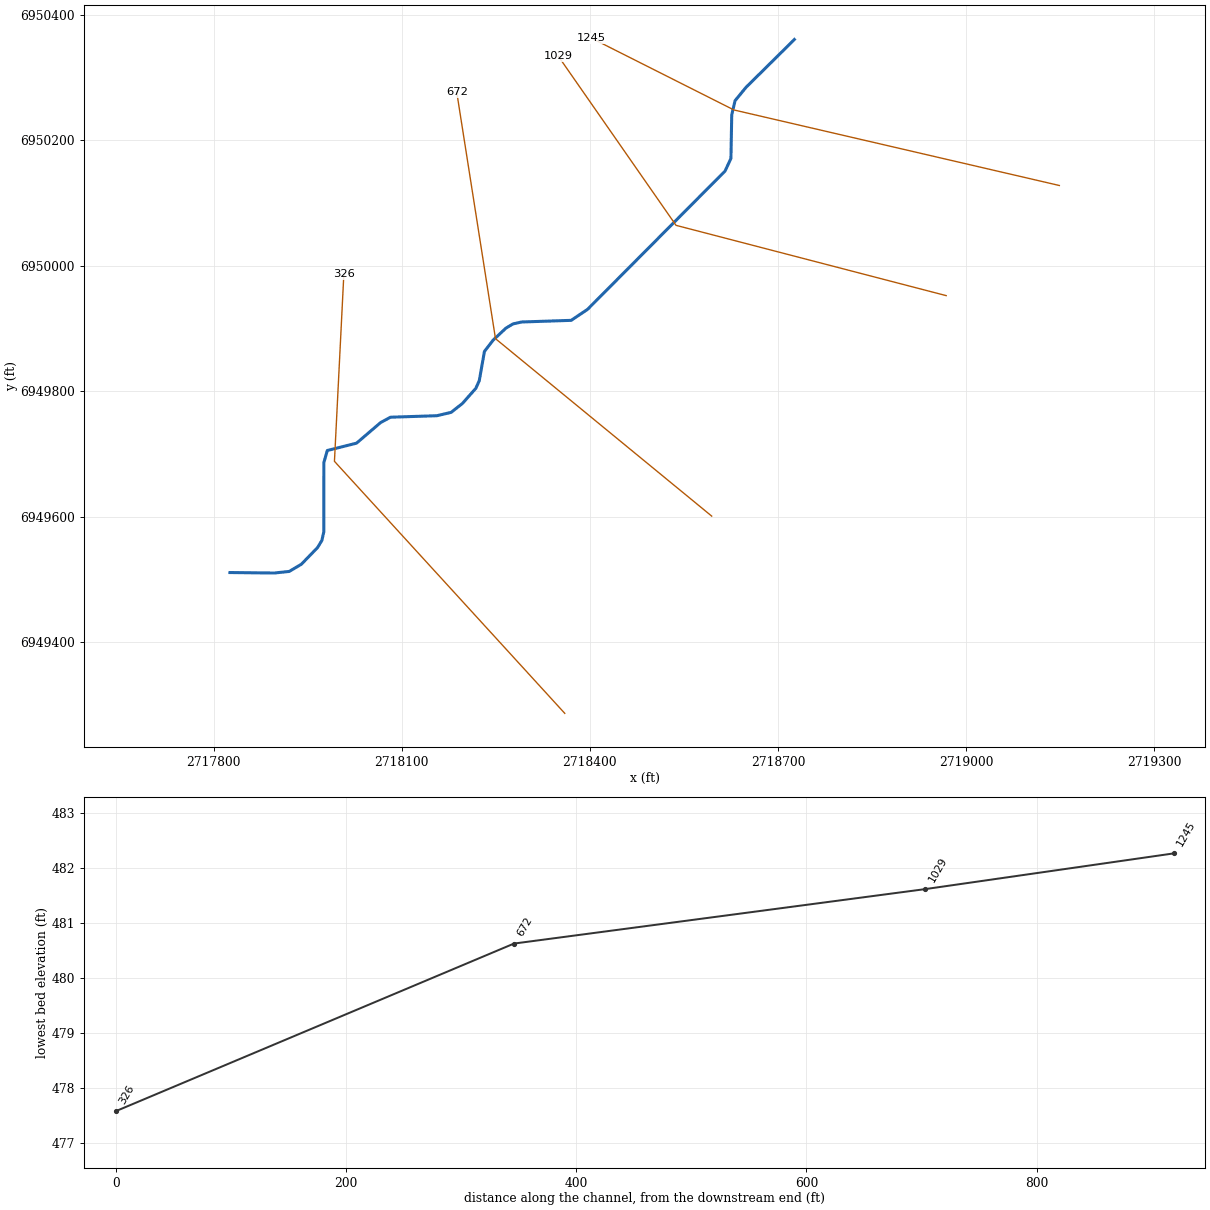
--- Wolf Creek T6.prj (project) ---

Proj Title=Wolf Creek T6 Base Level Engineering
Current Plan=p01
Default Exp/Contr=0.3,0.1
English Units
Geom File=g01
Flow File=f01
Plan File=p01
BEGIN DESCRIPTION:
Wolf Creek T6
END DESCRIPTION:

--- Wolf Creek T6.p01 (plan) ---

Plan Title=Multiple Run
Short Identifier=Multiple
Geom File=g01
Flow File=f01
Subcritical Flow
K Sum by GR= 0
Std Step Tol= 0.01
Critical Tol= 0.01
Num of Std Step Trials= 20
Max Error Tol= 0.3
Flow Tol Ratio= 0.001
Split Flow NTrial= 30
Split Flow Tol= 0.02
Split Flow Ratio= 0.02
Log Output Level= 0
Friction Slope Method= 1
Unsteady Friction Slope Method= 2
Unsteady Bridges Friction Slope Method= 1
Parabolic Critical Depth
Global Vel Dist=  1 , 1 , 1
Global Log Level= 0
CheckData=True
Encroach Param= -1, 0, 0, 0
BEGIN DESCRIPTION:
Multiple Run
END DESCRIPTION:

--- Wolf Creek T6.f01 (steady flow) ---

Flow Title=Multiple
Number of Profiles=7
Profile Names=10-year,25-year,50-year,1pct_min,100-year,1pct_plu,500-year
River Rch & RM= Wolf Creek T6,Reach-1,1245
      80      92     100      54     109     217     127
Boundary for River Rch & Prof#=Wolf Creek T6,Reach-1,1
Up Type=0
Dn Type=3
Dn Slope=0.005
Boundary for River Rch & Prof#=Wolf Creek T6,Reach-1,2
Up Type=0
Dn Type=3
Dn Slope=0.005
Boundary for River Rch & Prof#=Wolf Creek T6,Reach-1,3
Up Type=0
Dn Type=3
Dn Slope=0.005
Boundary for River Rch & Prof#=Wolf Creek T6,Reach-1,4
Up Type=0
Dn Type=3
Dn Slope=0.005
Boundary for River Rch & Prof#=Wolf Creek T6,Reach-1,5
Up Type=0
Dn Type=3
Dn Slope=0.005
Boundary for River Rch & Prof#=Wolf Creek T6,Reach-1,6
Up Type=0
Dn Type=3
Dn Slope=0.005
Boundary for River Rch & Prof#=Wolf Creek T6,Reach-1,7
Up Type=0
Dn Type=3
Dn Slope=0.005

--- Wolf Creek T6.g01 (geometry) ---

Geom Title=Existing Conditions

River Reach=Wolf Creek T6,Reach-1
Reach XY= 30
      2718726.00      6950361.00      2718648.77      6950284.57
      2718631.46      6950263.45      2718626.13      6950240.95
      2718624.84      6950171.48      2718615.48      6950151.21
      2718396.15      6949930.63      2718370.10      6949913.15
      2718291.09      6949910.53      2718277.28      6949907.47
      2718265.90      6949900.61      2718245.60      6949881.56
      2718231.75      6949863.55      2718223.53      6949816.89
      2718217.97      6949804.65      2718196.54      6949780.47
      2718178.67      6949766.42      2718156.05      6949761.08
      2718081.94      6949758.68      2718066.29      6949750.19
      2718027.78      6949717.30      2717981.18      6949705.59
      2717975.69      6949686.21      2717975.66      6949576.04
      2717972.57      6949562.23      2717965.70      6949550.83
      2717939.79      6949524.16      2717920.48      6949512.76
      2717896.41      6949510.22      2717826.00      6949511.00

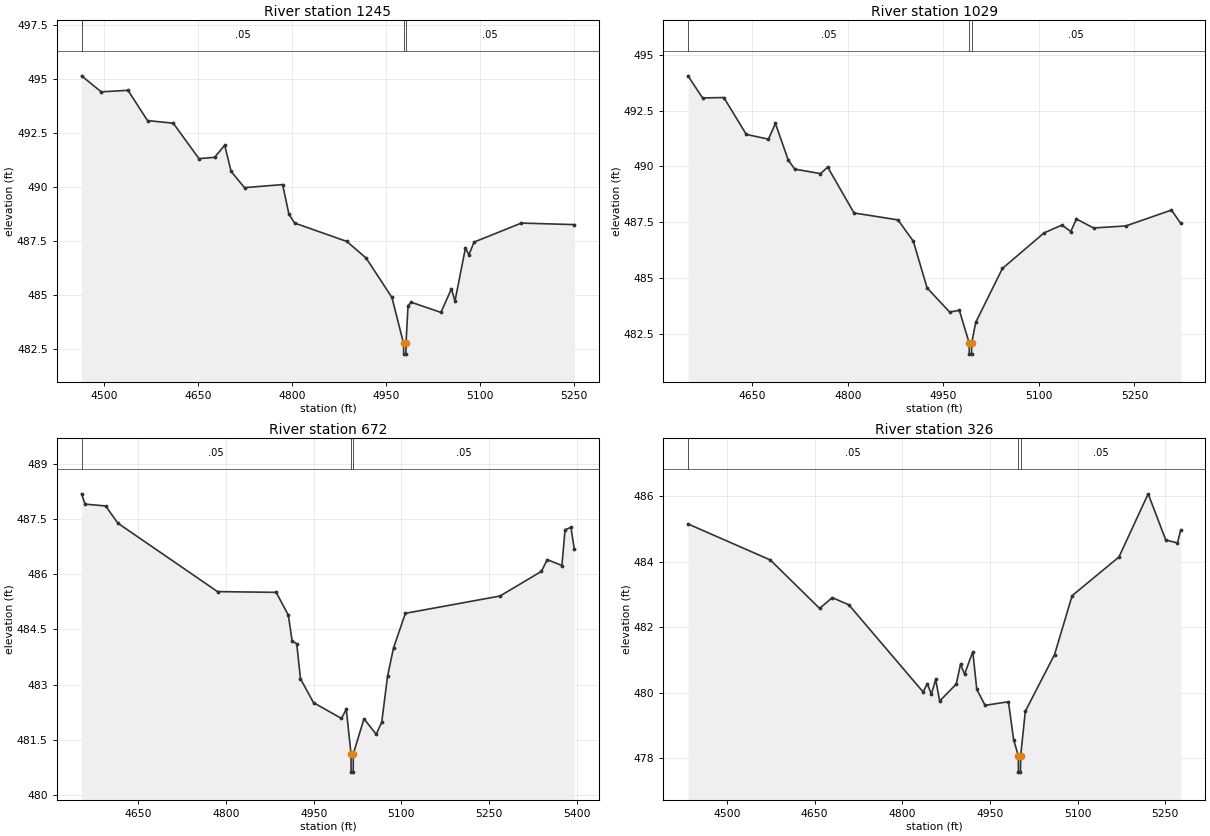
Type RM Length L Ch R = 1,1245,216,216,216
BEGIN DESCRIPTION:
Wolf Creek T6 1.0
END DESCRIPTION:
XS GIS Cut Line= 3
      2719148.56      6950128.19      2718629.65      6950248.63
      2718403.01      6950362.85
#Sta/Elev= 30
  4464.4  495.13  4495.8  494.39  4538.5  494.46  4569.7  493.06  4610.8  492.94
  4651.8  491.30  4676.7  491.36  4692.9  491.92  4703.1  490.71  4724.5  489.96
  4785.3  490.10  4795.5  488.72  4804.6  488.32  4887.9  487.47  4918.7  486.70
  4959.8  484.88  4978.3  482.76  4978.6  482.26  4982.1  482.26  4982.3  482.76
  4985.5  484.50  4990.6  484.66  5038.0  484.19  5054.8  485.28  5060.4  484.71
  5077.1  487.16  5082.7  486.85  5090.8  487.44  5166.3  488.32  5250.9  488.25
#Mann=3,-1,0
  4464.4    0.05       0  4978.3    0.04       0  4982.3    0.05       0
Bank Sta=4978.3,4982.3
Exp/Cntr=0.3,0.1

Type RM Length L Ch R = 1,1029,357,357,357
BEGIN DESCRIPTION:
Mapping XS 1e7f410e
END DESCRIPTION:
XS GIS Cut Line= 3
      2718968.10      6949952.57      2718537.30      6950064.65
      2718349.85      6950334.00
#Sta/Elev= 30
  4549.4  494.05  4572.2  493.06  4605.6  493.08  4640.9  491.43  4675.6  491.22
  4686.6  491.92  4706.6  490.29  4716.8  489.88  4757.3  489.68  4768.6  489.97
  4809.9  487.92  4878.9  487.61  4902.9  486.66  4924.6  484.57  4960.0  483.49
  4975.2  483.57  4990.6  482.11  4990.9  481.61  4994.4  481.61  4994.6  482.11
  5000.9  483.03  5042.8  485.44  5108.2  487.03  5136.3  487.38  5150.1  487.09
  5158.9  487.65  5185.9  487.25  5236.5  487.34  5308.1  488.05  5322.7  487.45
#Mann=3,-1,0
  4549.4    0.05       0  4990.6    0.04       0  4994.6    0.05       0
Bank Sta=4990.6,4994.6
Exp/Cntr=0.3,0.1

Type RM Length L Ch R = 1,672,346,346,346
BEGIN DESCRIPTION:
Mapping XS 1f9826a4
END DESCRIPTION:
XS GIS Cut Line= 3
      2718594.17      6949601.00      2718249.40      6949883.92
      2718187.66      6950276.71
#Sta/Elev= 30
  4552.6  488.19  4558.6  487.91  4593.8  487.86  4614.9  487.39  4785.4  485.53
  4885.8  485.51  4906.6  484.89  4913.1  484.19  4921.0  484.11  4927.4  483.16
  4949.7  482.51  4997.6  482.08  5005.8  482.33  5013.9  481.12  5014.1  480.62
  5017.6  480.62  5017.9  481.12  5036.1  482.07  5057.1  481.65  5066.5  481.98
  5076.6  483.24  5086.7  484.00  5107.0  484.94  5269.0  485.41  5339.8  486.08
  5349.9  486.40  5375.0  486.24  5380.3  487.21  5390.4  487.28  5396.2  486.68
#Mann=3,-1,0
  4552.6    0.05       0  5013.9    0.04       0  5017.9    0.05       0
Bank Sta=5013.9,5017.9
Exp/Cntr=0.3,0.1

Type RM Length L Ch R = 1,326,0,0,0
BEGIN DESCRIPTION:
Wolf Creek T6 0.0
END DESCRIPTION:
XS GIS Cut Line= 3
      2718359.91      6949286.42      2717992.60      6949688.33
      2718007.59      6949986.69
#Sta/Elev= 30
  4433.5  485.15  4574.3  484.05  4658.7  482.57  4680.3  482.90  4708.7  482.68
  4835.7  480.02  4843.1  480.27  4849.9  479.95  4857.3  480.40  4864.1  479.74
  4892.5  480.26  4899.9  480.87  4906.7  480.56  4920.8  481.25  4927.6  480.10
  4941.8  479.61  4981.8  479.72  4990.7  478.56  4998.7  478.07  4998.9  477.57
  5002.4  477.57  5002.7  478.07  5010.7  479.43  5060.7  481.16  5090.8  482.96
  5170.9  484.14  5220.9  486.07  5251.0  484.66  5271.0  484.57  5276.7  484.97
#Mann=3,-1,0
  4433.5    0.05       0  4998.7    0.04       0  5002.7    0.05       0
Bank Sta=4998.7,5002.7
Exp/Cntr=0.3,0.1

Chan Stop Cuts=-1