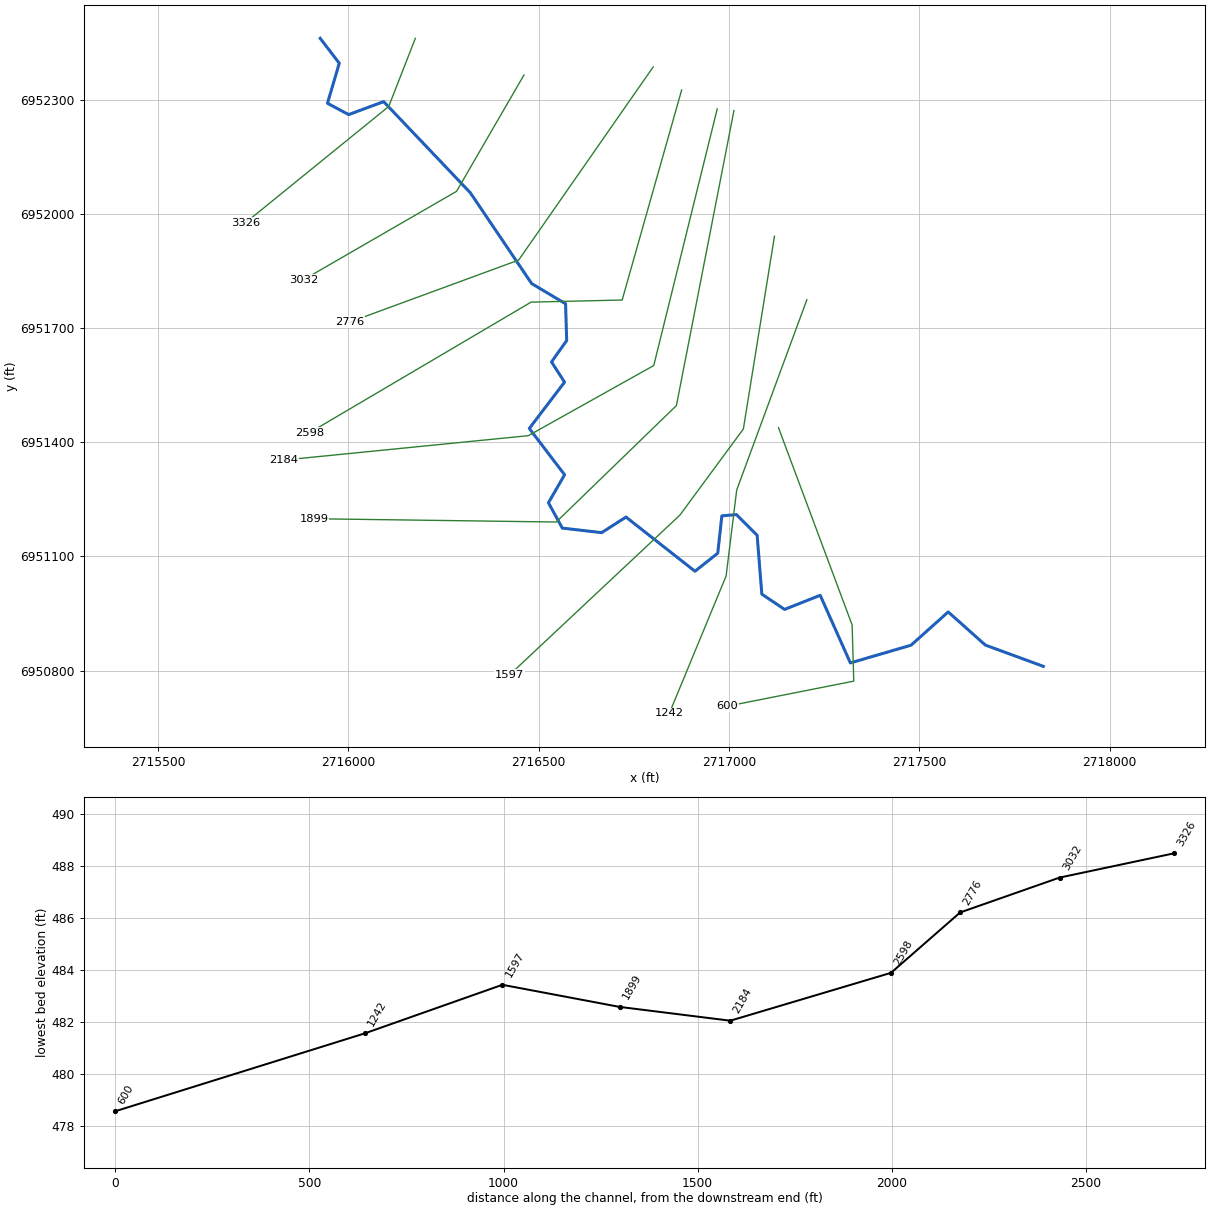
--- Wolf Creek T7.prj (project) ---

Proj Title=Wolf Creek T7 Base Level Engineering
Current Plan=p01
Default Exp/Contr=0.3,0.1
English Units
Geom File=g01
Flow File=f01
Plan File=p01
Y Axis Title=Elevation
X Axis Title(PF)=Main Channel Distance
X Axis Title(XS)=Station
BEGIN DESCRIPTION:
Wolf Creek T7
END DESCRIPTION:
DSS Export Rating Curves= 0
DSS Export Rating Curve Sorted= 0
DSS Export Volume Flow Curves= 0
DXF OffsetX= 0
DXF OffsetY= 0
DXF ScaleX= 1
DXF ScaleY= 10

--- Wolf Creek T7.p01 (plan) ---

Plan Title=Multiple Run
Short Identifier=Multiple
Geom File=g01
Flow File=f01
Subcritical Flow
K Sum by GR= 0
Std Step Tol= 0.01
Critical Tol= 0.01
Num of Std Step Trials= 20
Max Error Tol= 0.3
Flow Tol Ratio= 0.001
Split Flow NTrial= 30
Split Flow Tol= 0.02
Split Flow Ratio= 0.02
Log Output Level= 0
Friction Slope Method= 1
Unsteady Friction Slope Method= 2
Unsteady Bridges Friction Slope Method= 1
Parabolic Critical Depth
Global Vel Dist=  1 , 1 , 1
Global Log Level= 0
CheckData=True
Encroach Param= -1, 0, 0, 0
BEGIN DESCRIPTION:
Multiple Run
END DESCRIPTION:

--- Wolf Creek T7.f01 (steady flow) ---

Flow Title=Multiple
Number of Profiles=7
Profile Names=10-year,25-year,50-year,1pct_min,100-year,1pct_plu,500-year
River Rch & RM= Wolf Creek T7,Reach-1,3326
     505     666     795     470     939    1873    1307
Boundary for River Rch & Prof#=Wolf Creek T7,Reach-1,1
Up Type=0
Dn Type=3
Dn Slope=0.005
Boundary for River Rch & Prof#=Wolf Creek T7,Reach-1,2
Up Type=0
Dn Type=3
Dn Slope=0.005
Boundary for River Rch & Prof#=Wolf Creek T7,Reach-1,3
Up Type=0
Dn Type=3
Dn Slope=0.005
Boundary for River Rch & Prof#=Wolf Creek T7,Reach-1,4
Up Type=0
Dn Type=3
Dn Slope=0.005
Boundary for River Rch & Prof#=Wolf Creek T7,Reach-1,5
Up Type=0
Dn Type=3
Dn Slope=0.005
Boundary for River Rch & Prof#=Wolf Creek T7,Reach-1,6
Up Type=0
Dn Type=3
Dn Slope=0.005
Boundary for River Rch & Prof#=Wolf Creek T7,Reach-1,7
Up Type=0
Dn Type=3
Dn Slope=0.005

--- Wolf Creek T7.g01 (geometry) ---

Geom Title=Existing Conditions
Program Version=4.10

River Reach=Wolf Creek T7   ,Reach-1
Reach XY= 30
        2715926.        6952461.      2715976.17      6952395.56
      2715945.13      6952290.38      2716000.82       6952260.6
      2716092.74      6952294.71      2716320.38      6952055.38
      2716481.65      6951816.64      2716570.67      6951763.66
      2716573.65       6951666.9      2716533.81       6951610.9
      2716567.99      6951557.67      2716475.42        6951436.
      2716568.16       6951314.4      2716525.72      6951240.76
      2716562.21      6951174.19      2716665.51      6951162.27
      2716729.42       6951203.2      2716910.78      6951060.83
      2716970.55      6951108.32      2716981.29      6951206.42
      2717019.69       6951209.7      2717073.98      6951155.39
      2717086.35      6951000.77      2717146.05      6950960.63
      2717239.79      6950997.63      2717318.93      6950819.99
      2717478.43      6950866.55        2717576.      6950953.91
      2717673.69      6950866.85        2717826.        6950811.

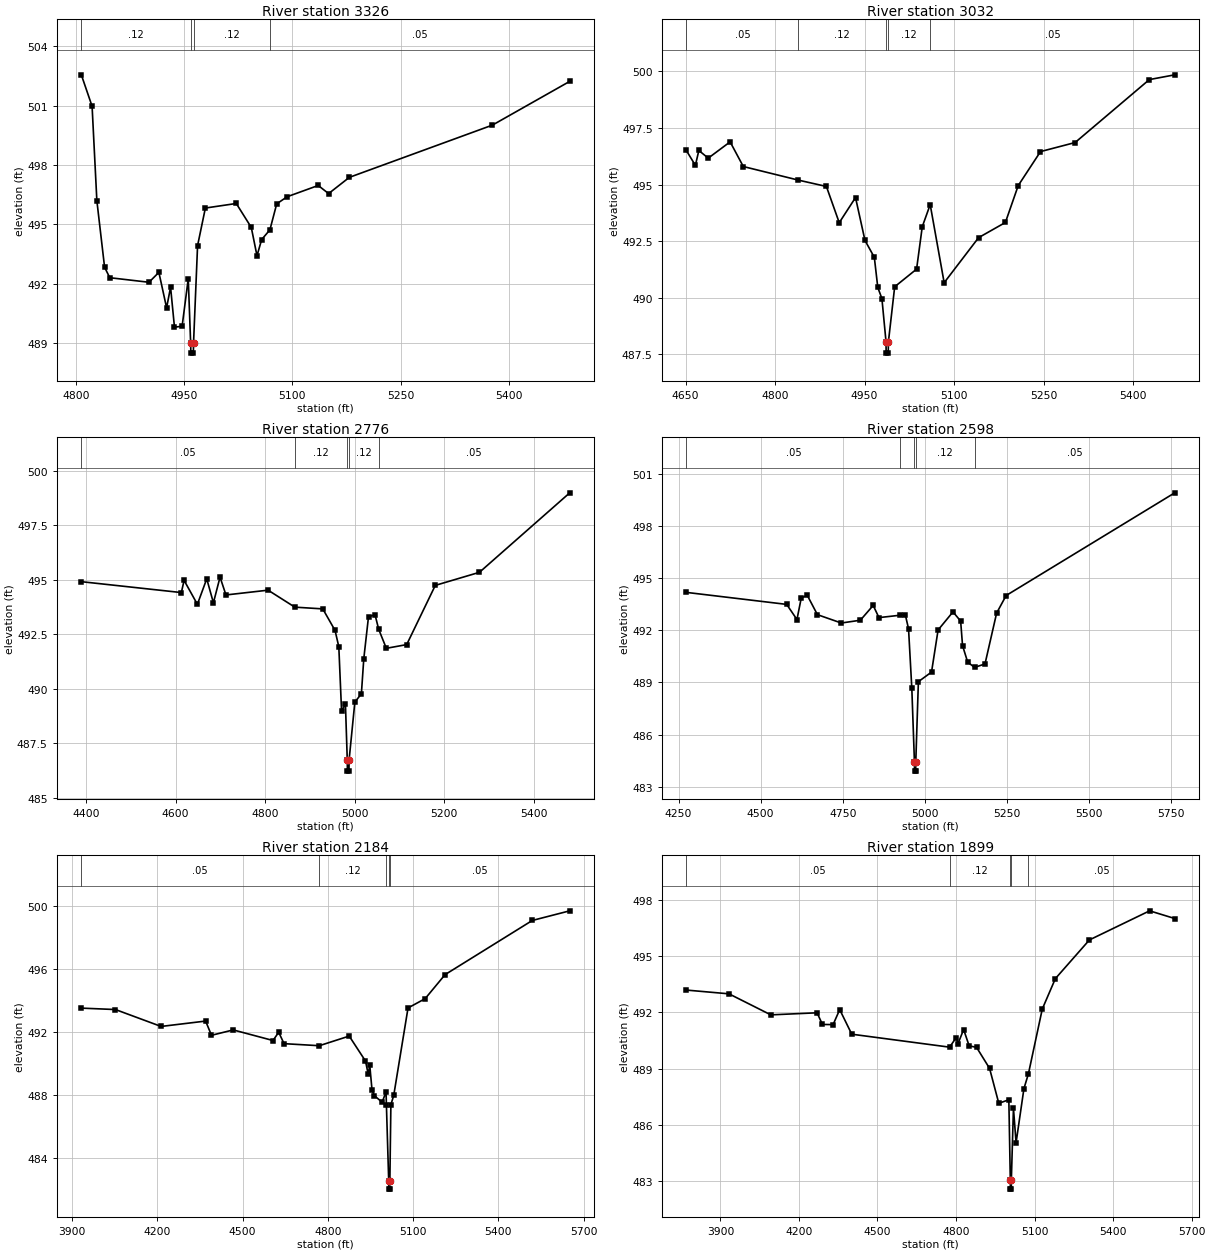
Type RM Length L Ch R = 1 ,3326    ,294,294,294
BEGIN DESCRIPTION:
Wolf Creek T7 2.0
END DESCRIPTION:
XS GIS Cut Line= 3
        2716176.        6952461.      2716106.09      6952281.97
      2715730.07      6951976.76
#Sta/Elev= 30
  4807.8  502.55  4822.7  500.96  4829.3  496.19    4840  492.83  4847.2   492.3
  4901.5  492.07  4915.2  492.57  4925.9  490.78  4931.4  491.82  4936.8   489.8
  4947.4  489.85  4955.9  492.25  4959.2  488.99  4959.5  488.49    4963  488.49
  4963.2  488.99  4968.8  493.92  4979.6  495.82  5022.4  496.05  5043.2  494.84
  5051.1  493.41  5057.6  494.23    5069  494.72  5078.4  496.03  5092.8  496.39
  5135.9  496.96  5150.3  496.55    5179  497.37  5377.2  500.01  5484.3  502.22
#Mann= 4 ,-1 , 0
  4807.8     .12       0  4959.2     .07       0  4963.2     .12       0
    5069     .05       0
Bank Sta=4959.2,4963.2
XS Rating Curve= 0 ,0
Exp/Cntr=0.3,0.1

Type RM Length L Ch R = 1 ,3032    ,256,256,256
BEGIN DESCRIPTION:
Mapping XS 3cea86ae
END DESCRIPTION:
XS GIS Cut Line= 3
      2716461.31      6952364.52      2716284.22      6952058.96
      2715881.45      6951826.32
#Sta/Elev= 30
  4651.3  496.51  4666.5  495.85  4672.3  496.51    4688  496.17  4724.7  496.89
  4746.8   495.8  4839.1   495.2    4886  494.92  4907.5  493.32  4934.8  494.43
  4950.6  492.54  4966.3  491.79  4972.1  490.46    4979  489.97  4985.9  488.06
  4986.1  487.56  4989.6  487.56  4989.9  488.06  5000.4  490.49  5037.1  491.27
  5046.6  493.14  5059.9  494.12  5083.3  490.67    5141  492.66  5185.9  493.33
  5207.4  494.96  5244.7  496.46  5302.7  496.86  5427.1  499.64  5469.6  499.85
#Mann= 5 ,-1 , 0
  4651.3     .05       0  4839.1     .12       0  4985.9     .07       0
  4989.9     .12       0  5059.9     .05       0
Bank Sta=4985.9,4989.9
XS Rating Curve= 0 ,0
Exp/Cntr=0.3,0.1

Type RM Length L Ch R = 1 ,2776    ,178,178,178
BEGIN DESCRIPTION:
Mapping XS 6e8b6d12
END DESCRIPTION:
XS GIS Cut Line= 3
      2716801.01      6952386.01      2716447.41       6951878.4
      2716004.09      6951715.61
#Sta/Elev= 30
  4389.6  494.92    4613  494.42  4619.1  494.98  4648.8  493.88  4669.7  495.05
  4684.6  493.95  4699.4  495.13  4712.6  494.31  4806.7  494.53  4866.5  493.75
  4928.9  493.67  4956.3  492.68  4964.7  491.93  4970.8  488.99  4979.5  489.29
  4983.6  486.72  4983.9  486.22  4987.4  486.22  4987.6  486.72  5000.5  489.39
  5015.1  489.77  5020.5  491.39    5031  493.31  5045.6   493.4  5053.8  492.73
  5070.8  491.86  5116.3  492.03  5180.2  494.75  5278.8  495.35  5480.5     499
#Mann= 5 ,-1 , 0
  4389.6     .05       0  4866.5     .12       0  4983.6     .07       0
  4987.6     .12       0  5053.8     .05       0
Bank Sta=4983.6,4987.6
XS Rating Curve= 0 ,0
Exp/Cntr=0.3,0.1

Type RM Length L Ch R = 1 ,2598    ,414,414,414
BEGIN DESCRIPTION:
Mapping XS 2820cba2
END DESCRIPTION:
XS GIS Cut Line= 4
       2716875.7      6952325.22      2716719.39      6951773.48
      2716480.15      6951767.94      2715898.64       6951425.3
#Sta/Elev= 30
  4273.6  494.17  4579.3  493.48  4610.6  492.61  4623.6  493.84  4641.8  494.01
  4672.9  492.89  4745.7  492.41  4803.7  492.57  4842.8  493.42  4860.4  492.72
    4926  492.86  4940.5  492.89  4950.5  492.08  4960.5  488.65  4968.5   484.4
  4968.7   483.9  4972.2   483.9  4972.5   484.4  4980.5  489.04  5020.5  489.59
  5040.5  492.01  5085.9  493.05  5109.2  492.52    5115  491.11  5130.7  490.16
  5151.7  489.86  5183.4  490.06  5218.8  492.98  5247.8  493.99  5761.3  499.89
#Mann= 5 ,-1 , 0
  4273.6     .05       0    4926     .12       0  4968.5     .07       0
  4972.5     .12       0  5151.7     .05       0
Bank Sta=4968.5,4972.5
XS Rating Curve= 0 ,0
Exp/Cntr=0.3,0.1

Type RM Length L Ch R = 1 ,2184    ,285,285,285
BEGIN DESCRIPTION:
Mapping XS e3cab7e4
END DESCRIPTION:
XS GIS Cut Line= 4
      2716969.07      6952275.38      2716802.43      6951601.36
       2716472.9      6951417.09      2715829.87      6951352.93
#Sta/Elev= 30
  3932.9  493.52  4052.9  493.43  4213.5  492.36  4370.1   492.7  4390.7   491.8
  4467.2  492.14    4607  491.47  4627.2  491.99    4646  491.27  4769.9  491.14
  4875.2  491.75  4932.5  490.17  4941.9  489.35  4947.6  489.89  4955.4  488.34
  4963.6  487.98    4991  487.56  5004.8  488.22  5006.1  487.36  5014.2  482.56
  5014.5  482.06    5018  482.06  5018.2  482.56  5021.8  487.41  5031.8  487.99
  5082.1  493.53  5142.4  494.12  5212.4  495.64  5519.3  499.07    5651  499.68
#Mann= 5 ,-1 , 0
  3932.9     .05       0  4769.9     .12       0  5006.1     .05       0
  5014.2     .07       0  5018.2     .05       0
Bank Sta=5014.2,5018.2
XS Rating Curve= 0 ,0
Exp/Cntr=0.3,0.1

Type RM Length L Ch R = 1 ,1899    ,302,302,302
BEGIN DESCRIPTION:
Mapping XS 457c554e
END DESCRIPTION:
XS GIS Cut Line= 4
      2717013.09      6952271.23      2716861.96      6951496.23
      2716546.23      6951190.19       2715910.1      6951198.81
#Sta/Elev= 30
  3769.9  493.19  3932.8  492.99  4092.7  491.87  4269.4  491.98  4289.7  491.36
  4330.5  491.35  4355.8  492.15  4401.8  490.84  4775.5  490.15  4800.8  490.66
  4807.8  490.34  4829.1  491.09  4850.2  490.22  4878.5  490.14  4928.2  489.02
  4963.4  487.16  5001.8  487.35  5007.4  483.09  5007.7  482.59  5011.2  482.59
  5011.4  483.09  5019.4   486.9  5029.4  485.06  5059.4  487.94  5076.7  488.74
  5129.5  492.18  5179.5   493.8  5309.5  495.86  5539.5  497.41  5635.4     497
#Mann= 5 ,-1 , 0
  3769.9     .05       0  4775.5     .12       0  5007.4     .07       0
  5011.4     .12       0  5076.7     .05       0
Bank Sta=5007.4,5011.4
XS Rating Curve= 0 ,0
Exp/Cntr=0.3,0.1

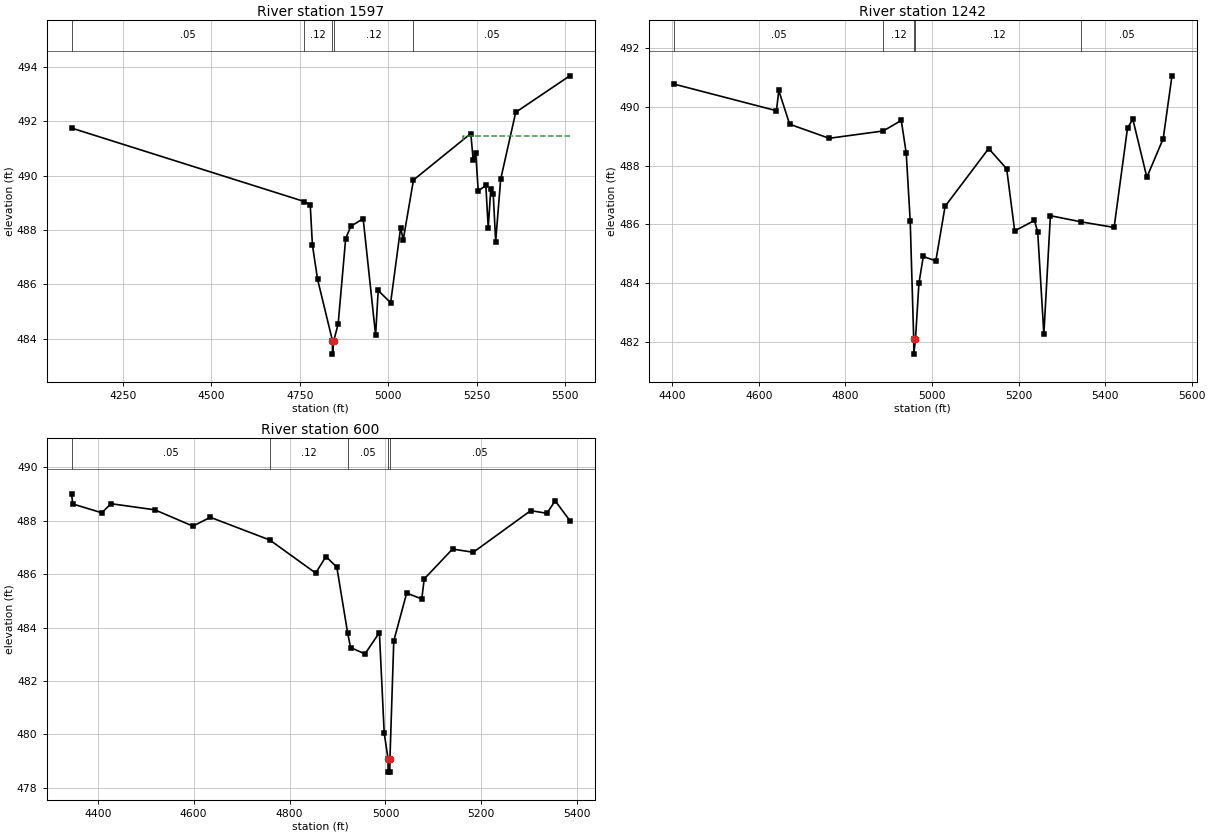
Type RM Length L Ch R = 1 ,1597    ,355,355,355
BEGIN DESCRIPTION:
Mapping XS caee2383
END DESCRIPTION:
XS GIS Cut Line= 4
      2717119.56      6951941.18       2717037.8      6951434.59
      2716871.03      6951208.26      2716423.11      6950788.12
#Sta/Elev= 30
  4105.1  491.75  4762.8  489.05  4779.7  488.94  4785.9  487.46  4800.5  486.19
  4842.5  483.94  4842.7  483.44  4846.5  483.94  4858.7  484.55    4880  487.69
  4894.6  488.14  4929.4  488.42  4964.6  484.14  4971.9  485.78  5007.1  485.33
  5035.4  488.09  5042.7  487.64  5071.6  489.84  5233.7  491.55  5240.5  490.58
  5247.8  490.82  5254.7  489.44  5276.2  489.64    5283  488.08  5290.2  489.51
  5297.2  489.31    5304  487.58  5318.2  489.87  5360.7  492.33  5513.5  493.67
#Mann= 5 ,-1 , 0
  4105.1     .05       0  4762.8     .12       0  4842.5     .07       0
  4846.5     .12       0  5071.6     .05       0
#XS Ineff= 2 , 0
       0                  5212.2       0  491.46
Permanent Ineff=
       F       F
Bank Sta=4842.5,4846.5
XS Rating Curve= 0 ,0
Exp/Cntr=0.3,0.1

Type RM Length L Ch R = 1 ,1242    ,642,642,642
BEGIN DESCRIPTION:
Mapping XS 220a96ea
END DESCRIPTION:
XS GIS Cut Line= 4
      2717204.67      6951774.29      2717020.33      6951274.23
      2716992.55      6951048.54      2716843.25      6950687.44
#Sta/Elev= 30
  4403.4  490.78  4640.7  489.87    4646  490.56  4671.1  489.41  4762.4  488.93
  4887.4  489.18  4929.1  489.54  4940.5  488.42  4949.7  486.11  4957.8  482.07
    4958  481.57  4961.8  482.07  4969.8  483.98  4979.9   484.9  5008.9  484.75
  5030.3  486.61    5131  488.58  5172.6  487.89  5191.1  485.77  5236.8  486.13
  5244.3  485.73  5258.5  482.25  5273.6  486.29  5344.8  486.08  5420.8  485.89
  5451.8  489.28  5464.1  489.58  5496.5   487.6  5534.3  488.92  5554.5  491.06
#Mann= 5 ,-1 , 0
  4403.4     .05       0  4887.4     .12       0  4957.8     .07       0
  4961.8     .12       0  5344.8     .05       0
Bank Sta=4957.8,4961.8
XS Rating Curve= 0 ,0
Exp/Cntr=0.3,0.1

Type RM Length L Ch R = 1 ,600     ,0,0,0
BEGIN DESCRIPTION:
Wolf Creek T7 1.0
END DESCRIPTION:
XS GIS Cut Line= 4
      2717130.11       6951438.1      2717323.57      6950919.74
      2717327.91      6950772.17      2716996.08      6950706.41
#Sta/Elev= 30
  4345.3  489.01  4347.7  488.63  4408.3   488.3  4427.6  488.64  4518.9  488.41
  4598.4   487.8  4634.8  488.13  4758.7  487.28  4854.5  486.04  4875.9  486.66
  4898.6  486.26  4921.2  483.79  4927.3  483.25  4957.3  483.01  4987.4  483.81
  4997.4  480.05  5005.4  479.08  5005.6  478.58  5009.1  478.58  5009.4  479.08
  5017.4   483.5  5044.3  485.29  5075.8  485.07  5080.9  485.82  5139.9  486.94
  5183.3  486.82    5303  488.38  5336.9  488.28    5354  488.75  5384.5  488.01
#Mann= 5 ,-1 , 0
  4345.3     .05       0  4758.7     .12       0  4921.2     .05       0
  5005.4     .04       0  5009.4     .05       0
Bank Sta=5005.4,5009.4
XS Rating Curve= 0 ,0
Exp/Cntr=0.3,0.1

Chan Stop Cuts=-1
Use User Specified Reach Order=0
Composite Channel Slope=5