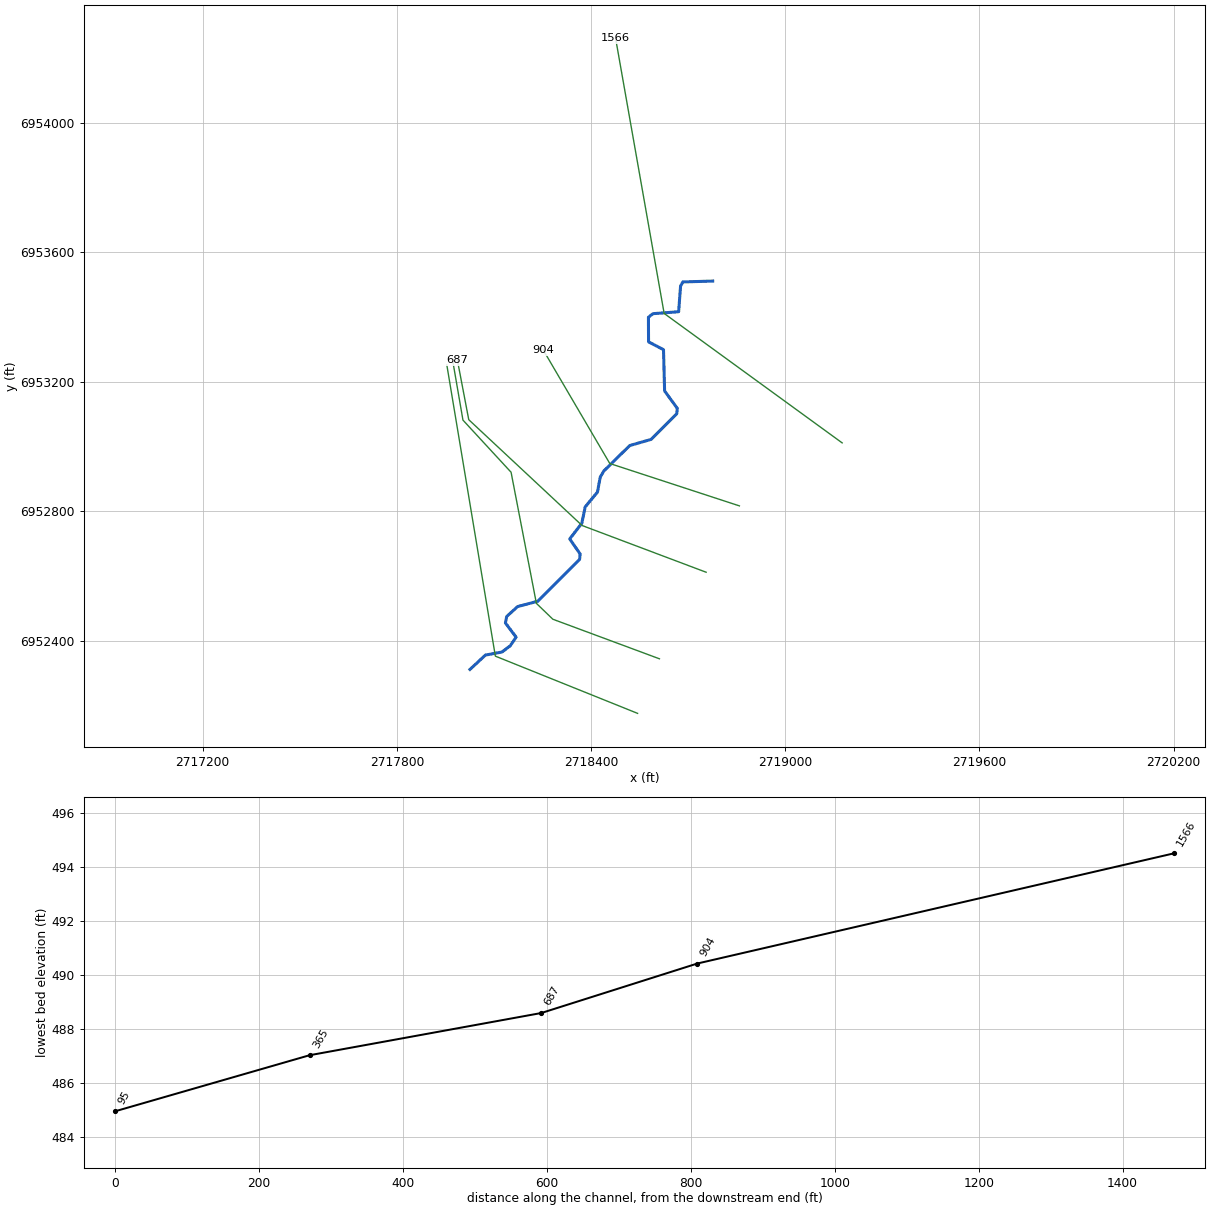
--- Wolf Creek T8.prj (project) ---

Proj Title=Wolf Creek T8 Base Level Engineering
Current Plan=p01
Default Exp/Contr=0.3,0.1
English Units
Geom File=g01
Flow File=f01
Plan File=p01
BEGIN DESCRIPTION:
Wolf Creek T8
END DESCRIPTION:

--- Wolf Creek T8.p01 (plan) ---

Plan Title=Multiple Run
Short Identifier=Multiple
Geom File=g01
Flow File=f01
Subcritical Flow
K Sum by GR= 0
Std Step Tol= 0.01
Critical Tol= 0.01
Num of Std Step Trials= 20
Max Error Tol= 0.3
Flow Tol Ratio= 0.001
Split Flow NTrial= 30
Split Flow Tol= 0.02
Split Flow Ratio= 0.02
Log Output Level= 0
Friction Slope Method= 1
Unsteady Friction Slope Method= 2
Unsteady Bridges Friction Slope Method= 1
Parabolic Critical Depth
Global Vel Dist=  1 , 1 , 1
Global Log Level= 0
CheckData=True
Encroach Param= -1, 0, 0, 0
BEGIN DESCRIPTION:
Multiple Run
END DESCRIPTION:

--- Wolf Creek T8.f01 (steady flow) ---

Flow Title=Multiple
Number of Profiles=7
Profile Names=10-year,25-year,50-year,1pct_min,100-year,1pct_plu,500-year
River Rch & RM= Wolf Creek T8,Reach-1,1566
     242     302     347     199     397     791     515
Boundary for River Rch & Prof#=Wolf Creek T8,Reach-1,1
Up Type=0
Dn Type=3
Dn Slope=0.005
Boundary for River Rch & Prof#=Wolf Creek T8,Reach-1,2
Up Type=0
Dn Type=3
Dn Slope=0.005
Boundary for River Rch & Prof#=Wolf Creek T8,Reach-1,3
Up Type=0
Dn Type=3
Dn Slope=0.005
Boundary for River Rch & Prof#=Wolf Creek T8,Reach-1,4
Up Type=0
Dn Type=3
Dn Slope=0.005
Boundary for River Rch & Prof#=Wolf Creek T8,Reach-1,5
Up Type=0
Dn Type=3
Dn Slope=0.005
Boundary for River Rch & Prof#=Wolf Creek T8,Reach-1,6
Up Type=0
Dn Type=3
Dn Slope=0.005
Boundary for River Rch & Prof#=Wolf Creek T8,Reach-1,7
Up Type=0
Dn Type=3
Dn Slope=0.005

--- Wolf Creek T8.g01 (geometry) ---

Geom Title=Existing Conditions

River Reach=Wolf Creek T8,Reach-1
Reach XY= 30
      2718776.00      6953511.00      2718683.73      6953508.27
      2718676.71      6953495.29      2718670.79      6953416.21
      2718591.69      6953410.21      2718577.40      6953399.30
      2718577.80      6953323.13      2718624.01      6953299.03
      2718627.41      6953171.45      2718666.72      6953117.52
      2718664.91      6953100.92      2718585.72      6953021.78
      2718519.94      6953002.85      2718439.61      6952924.24
      2718428.49      6952904.97      2718419.89      6952858.81
      2718382.05      6952813.19      2718371.59      6952762.63
      2718334.25      6952714.23      2718366.40      6952667.66
      2718364.76      6952651.00      2718235.65      6952521.78
      2718173.17      6952505.14      2718139.51      6952474.68
      2718135.56      6952454.47      2718168.54      6952410.80
      2718150.41      6952384.00      2718124.93      6952364.81
      2718073.72      6952355.29      2718026.00      6952311.00

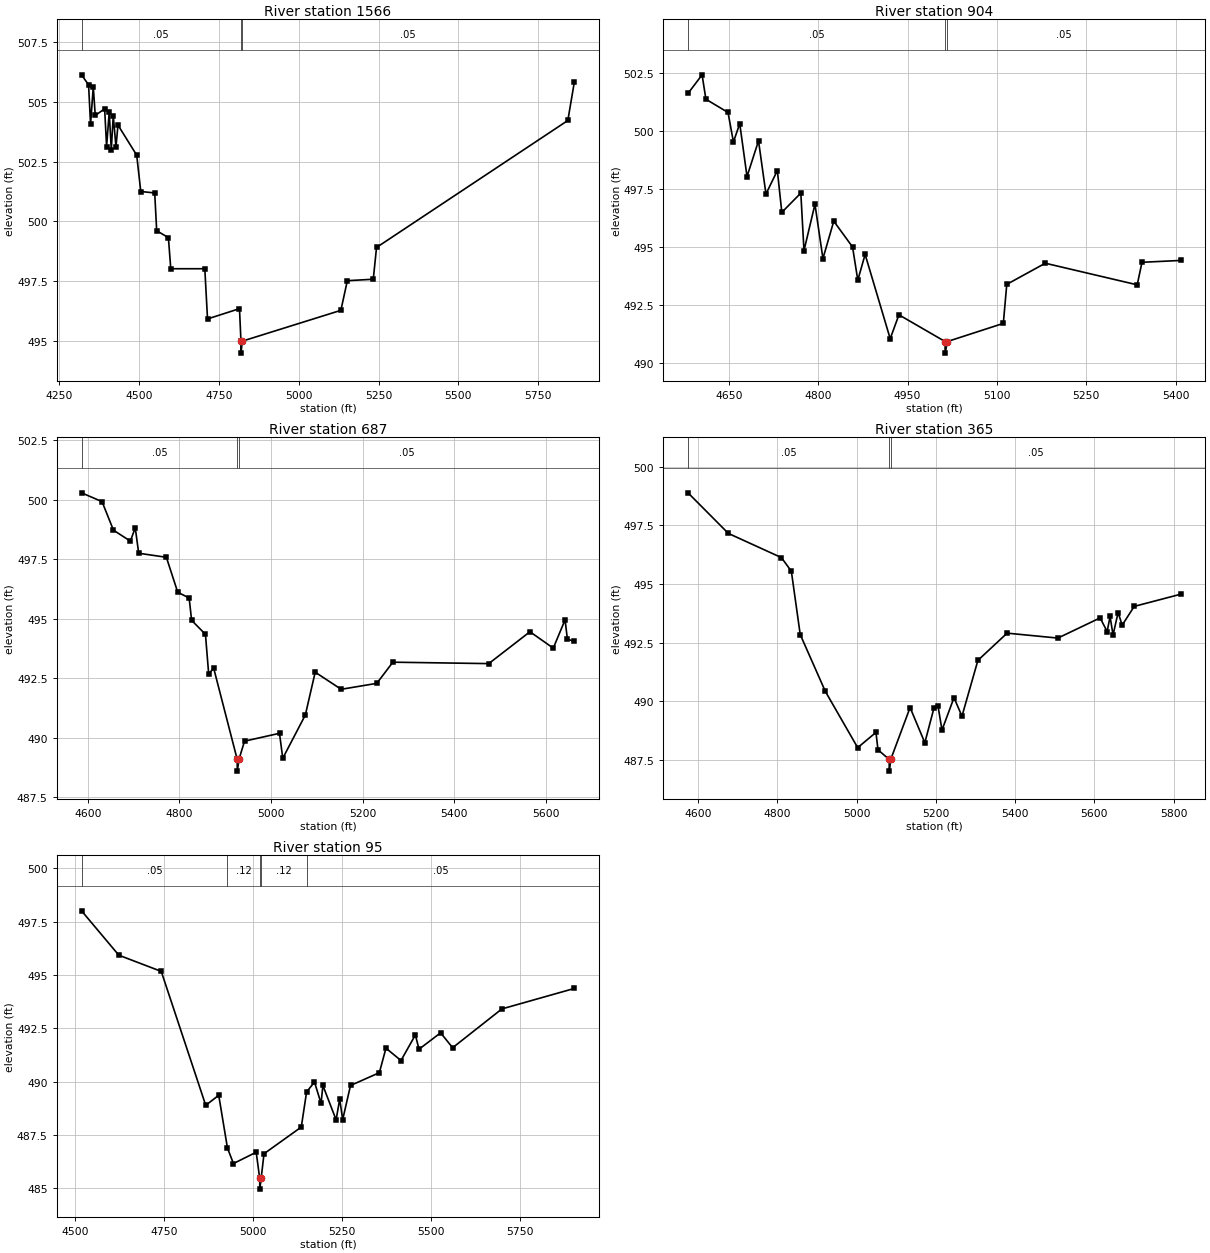
Type RM Length L Ch R = 1,1566,662,662,662
BEGIN DESCRIPTION:
Wolf Creek T8 2.0
END DESCRIPTION:
XS GIS Cut Line= 3
      2719176.00      6953011.00      2718626.00      6953411.00
      2718476.00      6954260.99
#Sta/Elev= 30
  4319.9  506.13  4341.9  505.71  4348.1  504.06  4356.6  505.63  4362.8  504.43
  4392.2  504.71  4398.3  503.13  4406.5  504.57  4413.0  503.00  4419.2  504.42
  4427.7  503.11  4433.9  504.03  4492.6  502.77  4505.4  501.25  4549.0  501.19
  4555.2  499.61  4591.9  499.32  4599.3  498.02  4705.9  498.02  4714.4  495.92
  4814.5  496.35  4819.1  494.99  4819.3  494.49  4823.1  494.99  5132.0  496.28
  5152.3  497.52  5233.5  497.58  5243.7  498.91  5842.8  504.22  5863.1  505.82
#Mann=3,-1,0
  4319.9    0.05       0  4819.1    0.04       0  4823.1    0.05       0
Bank Sta=4819.1,4823.1
Exp/Cntr=0.3,0.1

Type RM Length L Ch R = 1,904,217,217,217
BEGIN DESCRIPTION:
Mapping XS cbac9d60
END DESCRIPTION:
XS GIS Cut Line= 3
      2718858.46      6952816.35      2718457.98      6952947.31
      2718252.91      6953297.20
#Sta/Elev= 30
  4581.6  501.60  4605.2  502.40  4611.6  501.35  4648.7  500.78  4657.8  499.51
  4668.4  500.30  4680.6  498.02  4699.9  499.56  4712.4  497.27  4731.5  498.28
  4739.0  496.48  4770.9  497.31  4776.2  494.83  4794.6  496.83  4808.0  494.49
  4826.2  496.10  4857.7  494.99  4866.5  493.56  4878.8  494.67  4920.9  491.04
  4935.5  492.07  5012.9  490.92  5013.1  490.42  5016.9  490.92  5110.7  491.70
  5116.5  493.38  5181.1  494.29  5335.4  493.36  5343.4  494.33  5408.5  494.41
#Mann=3,-1,0
  4581.6    0.05       0  5012.9    0.04       0  5016.9    0.05       0
Bank Sta=5012.9,5016.9
Exp/Cntr=0.3,0.1

Type RM Length L Ch R = 1,687,322,322,322
BEGIN DESCRIPTION:
Mapping XS 2a9b4bc2
END DESCRIPTION:
XS GIS Cut Line= 4
      2718755.69      6952611.32      2718372.40      6952755.70
      2718022.24      6953082.67      2717987.27      6953266.10
#Sta/Elev= 30
  4586.4  500.29  4631.1  499.92  4656.0  498.72  4692.9  498.26  4703.6  498.82
  4711.1  497.75  4771.5  497.58  4796.3  496.11  4821.2  495.87  4826.6  494.93
  4856.8  494.34  4863.9  492.66  4874.6  492.93  4926.0  489.09  4926.3  488.59
  4930.0  489.09  4942.1  489.85  5018.4  490.18  5025.5  489.13  5074.8  490.95
  5096.3  492.75  5153.0  492.03  5230.7  492.28  5265.8  493.17  5475.1  493.11
  5565.0  494.45  5615.9  493.76  5641.6  494.95  5646.7  494.14  5661.8  494.04
#Mann=3,-1,0
  4586.4    0.05       0  4926.0    0.04       0  4930.0    0.05       0
Bank Sta=4926,4930
Exp/Cntr=0.3,0.1

Type RM Length L Ch R = 1,365,270,270,270
BEGIN DESCRIPTION:
Mapping XS e0996521
END DESCRIPTION:
XS GIS Cut Line= 6
      2718611.45      6952343.83      2718282.14      6952466.07
      2718231.23      6952515.11      2718153.02      6952920.26
      2718004.35      6953081.33      2717972.35      6953266.79
#Sta/Elev= 30
  4574.8  498.89  4676.6  497.16  4810.4  496.13  4835.5  495.55  4857.9  492.85
  4921.2  490.43  5002.9  488.03  5049.0  488.68  5054.1  487.94  5082.3  487.53
  5082.6  487.03  5086.3  487.53  5135.1  489.74  5172.3  488.24  5195.5  489.73
  5205.6  489.80  5215.6  488.78  5245.9  490.16  5266.0  489.37  5306.2  491.75
  5379.9  492.91  5508.0  492.70  5614.6  493.56  5632.3  492.98  5639.7  493.62
  5647.2  492.83  5660.0  493.79  5670.2  493.25  5700.6  494.05  5818.1  494.57
#Mann=3,-1,0
  4574.8    0.05       0  5082.3    0.04       0  5086.3    0.05       0
Bank Sta=5082.3,5086.3
Exp/Cntr=0.3,0.1

Type RM Length L Ch R = 1,95,0,0,0
BEGIN DESCRIPTION:
Wolf Creek T8 1.0
END DESCRIPTION:
XS GIS Cut Line= 3
      2718544.02      6952175.19      2718104.43      6952352.03
      2717954.44      6953251.99
#Sta/Elev= 30
  4517.2  498.01  4622.0  495.93  4741.4  495.17  4866.5  488.89  4903.1  489.36
  4927.6  486.89  4944.5  486.16  5008.5  486.69  5018.4  485.46  5018.6  484.96
  5022.4  485.46  5030.5  486.62  5135.3  487.87  5150.3  489.52  5172.5  489.98
  5191.0  488.98  5196.1  489.82  5233.3  488.21  5243.4  489.18  5251.8  488.22
  5273.8  489.82  5355.0  490.42  5373.5  491.57  5415.8  490.99  5456.3  492.19
  5466.5  491.52  5527.3  492.29  5561.1  491.59  5699.6  493.41  5903.4  494.37
#Mann=5,-1,0
  4517.2    0.05       0  4927.6    0.12       0  5018.4    0.07       0
  5022.4    0.12       0  5150.3    0.05       0
Bank Sta=5018.4,5022.4
Exp/Cntr=0.3,0.1

Chan Stop Cuts=-1