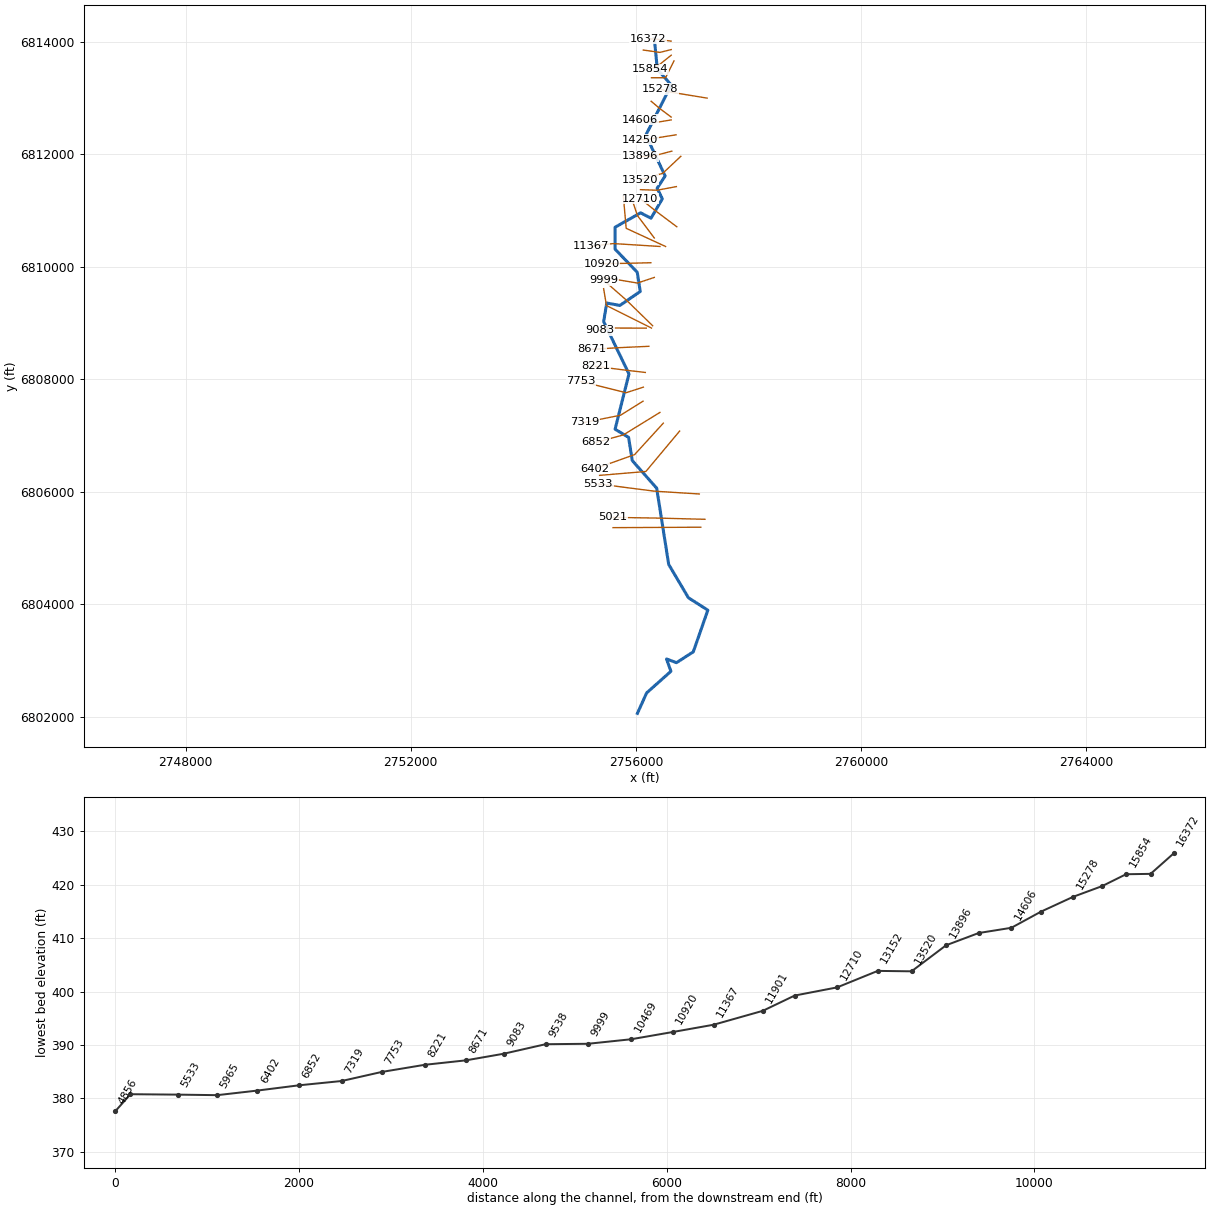
--- Briar Creek.prj (project) ---

Proj Title=Briar Creek Base Level Engineering
Current Plan=p01
Default Exp/Contr=0.3,0.1
English Units
Geom File=g01
Flow File=f01
Plan File=p01
Y Axis Title=Elevation
X Axis Title(PF)=Main Channel Distance
X Axis Title(XS)=Station
BEGIN DESCRIPTION:
Briar Creek
END DESCRIPTION:
DSS Export Rating Curves= 0
DSS Export Rating Curve Sorted= 0
DSS Export Volume Flow Curves= 0
DXF OffsetX= 0
DXF OffsetY= 0
DXF ScaleX= 1
DXF ScaleY= 10

--- Briar Creek.p01 (plan) ---

Plan Title=Multiple Run
Program Version=4.10
Short Identifier=Multiple
Geom File=g01
Flow File=f01
Subcritical Flow
K Sum by GR= 0
Std Step Tol= 0.01
Critical Tol= 0.01
Num of Std Step Trials= 20
Max Error Tol= 0.3
Flow Tol Ratio= 0.001
Split Flow NTrial= 30
Split Flow Tol= 0.02
Split Flow Ratio= 0.02
Log Output Level= 0
Friction Slope Method= 1
Unsteady Friction Slope Method= 2
Unsteady Bridges Friction Slope Method= 1
Parabolic Critical Depth
Global Vel Dist= 1 , 1 , 1
Global Log Level= 0
CheckData=True
Encroach Param=-1 ,0,0, 0
BEGIN DESCRIPTION:
Multiple Run
END DESCRIPTION:
Computation Interval=1HOUR
Output Interval=1HOUR
Run HTab= 0
Run UNet= 0
Run PostProcess= 0
Run WQNet= 0
UNET Theta= 1
UNET Theta Warmup= 1
UNET ZTol= 0.02
UNET ZSATol= 0.05
UNET MxIter= 20
UNET MaxInSteps= 0
UNET DtIC= 0
UNET DtMin= 0
UNET MaxCRTS= 20
UNET WFStab= 2
UNET SFStab= 1
UNET WFX= 1
UNET SFX= 1
UNET DSS MLevel= 4
UNET DZMax Abort= 100
UNET Convert EG Bridges= 0
UNET Use Existing IB Tables=-1
UNET Froude Reduction=False
UNET Froude Limit= 1
UNET Froude Power= 10
UNET Time Slicing=0,0, 5
UNET Junction Losses=0
Instantaneous Interval=1HOUR
Write IC File= 0
Write IC File at Sim End=0
Echo Input=False
Echo Parameters=False
Echo Output=False
Write Detailed= 0
WQ AD Non Conservative
WQ ULTIMATE=-1
WQ Max Comp Step=1HOUR
WQ Output Interval=15MIN
WQ Output Selected Increments= 0
WQ Output face flow=0
WQ Output face velocity=0
WQ Output face area=0
WQ Output face dispersion=0
WQ Output cell volume=0
WQ Output cell surface area=0
WQ Output cell continuity=0
WQ Output cumulative cell continuity=0
WQ Output face conc=0
WQ Output face dconc_dx=0
WQ Output face courant=0
WQ Output face peclet=0
WQ Output face adv mass=0
WQ Output face disp mass=0
WQ Output cell mass=0
WQ Output cell source sink temp=0
WQ Output cell source sink nsm=0
WQ Output MaxMinRange=-1
WQ Daily Max Min Mean=-1
WQ Daily Range=0
WQ Daily Time=0
WQ Create Restart=0
WQ Fixed Restart=0
WQ System Summary=0
WQ Use Fixed Temperature=0
Sorting and Armoring Iterations= 10
XS Update Threshold= 0.02
Hydraulics Update Threshold= 0.02
Energy Slope Method= 1
Volume Change Method= 0
XS Weighting Method= 0
Number of US Weighted Cross Sections= 1
Number of DS Weighted Cross Sections= 1
Upstream XS Weight=0.25
Main XS Weight=0.5
Downstream XS Weight=0.25
Number of DS XS's Weighted with US Boundary= 1
Upstream Boundary Weight= 1
Weight of XSs Associated with US Boundary= 0
Number of US XS's Weighted with DS Boundary= 1
Downstream Boundary Weight= 0.5
Weight of XSs Associated with DS Boundary= 0.5
Sediment Output Level= 4
Mass or Volume Output= 0
Output Increment Type= 1
Profile and TS Output Increment= 10
XS Output Flag= 0
XS Output Increment= 10
Disregard all LS=0
Disregard all Conn=0
Disregard all Breaches=0
Disregard all Pumps=0

--- Briar Creek.f01 (steady flow) ---

Flow Title=Multiple
Number of Profiles=7
Profile Names=10-year,25-year,50-year,1pct_min,100-year,1pct_plu,500-year
River Rch & RM= Briar Creek,Reach-1,16372
     571     772     936     566    1128    2251    1641
River Rch & RM= Briar Creek,Reach-1,13152
     784    1077    1320     804    1604    3200    2374
River Rch & RM= Briar Creek,Reach-1,9999
    1037    1445    1788    1099    2192    4374    3303
River Rch & RM= Briar Creek,Reach-1,9083
    1182    1646    2035    1247    2488    4965    3733
River Rch & RM= Briar Creek,Reach-1,2784
    1224    1704    2107    1292    2577    5142    3866
Boundary for River Rch & Prof#=Briar Creek,Reach-1,1
Up Type=0
Dn Type=3
Dn Slope=0.005
Boundary for River Rch & Prof#=Briar Creek,Reach-1,2
Up Type=0
Dn Type=3
Dn Slope=0.005
Boundary for River Rch & Prof#=Briar Creek,Reach-1,3
Up Type=0
Dn Type=3
Dn Slope=0.005
Boundary for River Rch & Prof#=Briar Creek,Reach-1,4
Up Type=0
Dn Type=3
Dn Slope=0.005
Boundary for River Rch & Prof#=Briar Creek,Reach-1,5
Up Type=0
Dn Type=3
Dn Slope=0.005
Boundary for River Rch & Prof#=Briar Creek,Reach-1,6
Up Type=0
Dn Type=3
Dn Slope=0.005
Boundary for River Rch & Prof#=Briar Creek,Reach-1,7
Up Type=0
Dn Type=3
Dn Slope=0.005

--- Briar Creek.g01 (geometry) ---

Geom Title=Existing Conditions

River Reach=Briar Creek,Reach-1
Reach XY= 30
      2756326.00      6814061.00      2756379.54      6813512.46
      2756626.62      6813231.27      2756175.72      6812340.79
      2756518.40      6811614.34      2756376.36      6811395.73
      2756468.53      6811207.66      2756267.53      6810863.58
      2756082.12      6810959.24      2755628.62      6810702.54
      2755629.52      6810312.46      2756022.93      6809902.70
      2756076.00      6809561.00      2755713.98      6809312.19
      2755481.08      6809355.98      2755426.38      6809026.16
      2755876.10      6808095.64      2755629.45      6807112.48
      2755868.32      6806967.52      2755935.15      6806554.27
      2756367.95      6806064.32      2756581.76      6804708.47
      2756931.58      6804116.58      2757276.79      6803895.63
      2757018.25      6803154.55      2756719.91      6802962.58
      2756542.33      6803028.34      2756621.13      6802808.81
      2756189.45      6802424.63      2756026.00      6802061.00

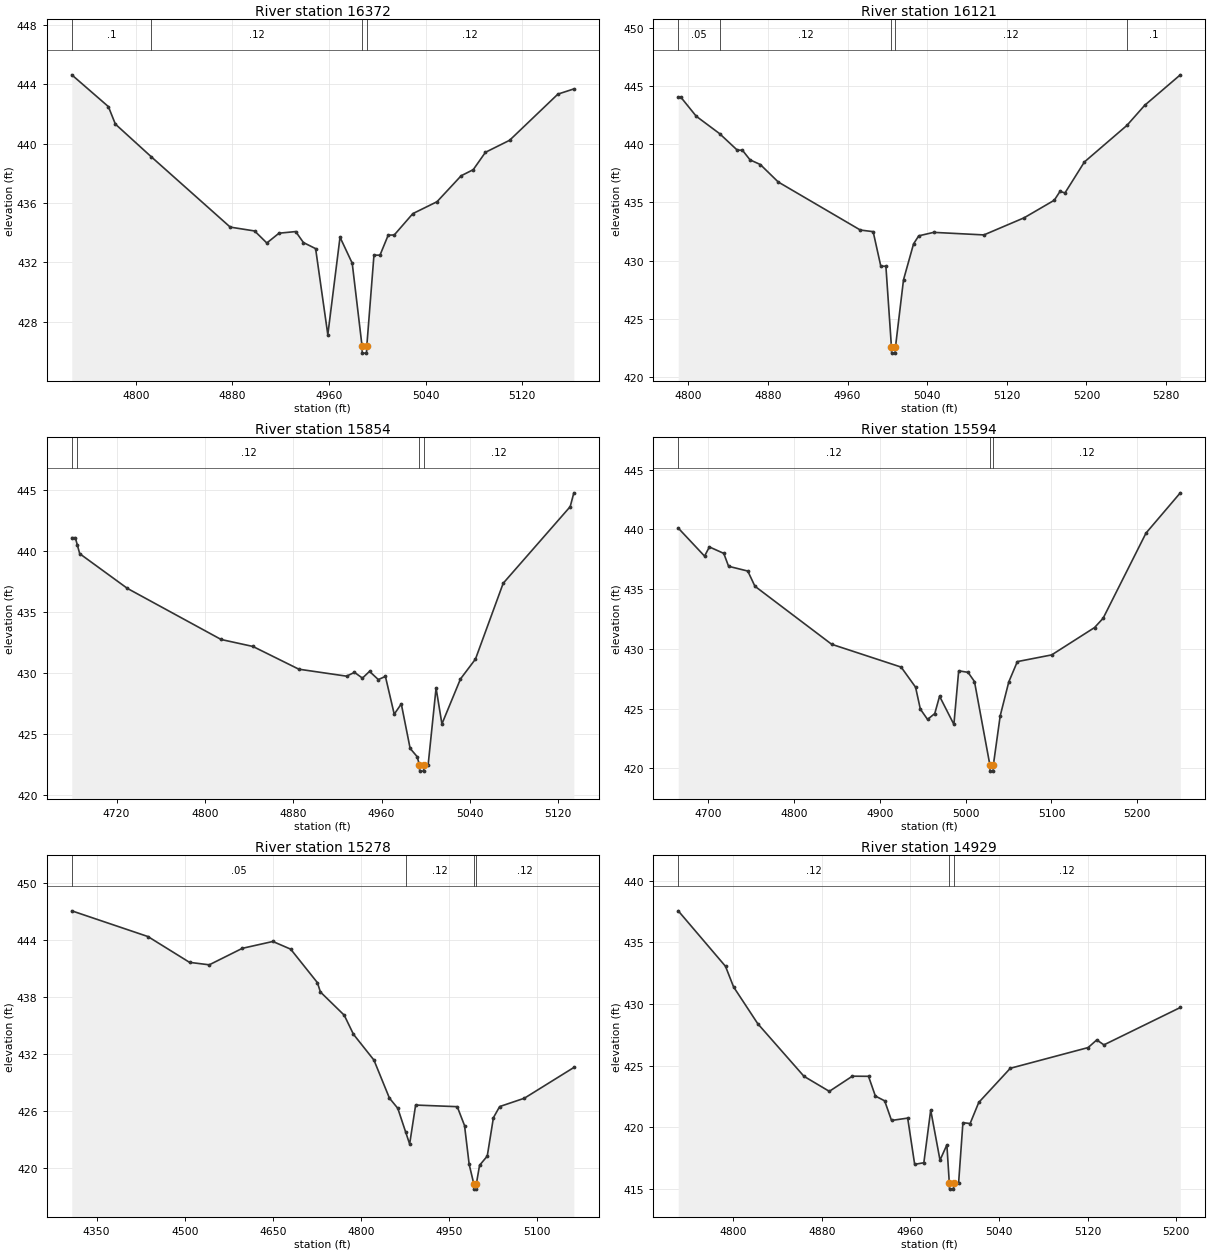
Type RM Length L Ch R = 1,16372,251,251,251
BEGIN DESCRIPTION:
Briar Creek 37.0
END DESCRIPTION:
XS GIS Cut Line= 3
      2756626.02      6814011.00      2756375.36      6814045.38
      2756212.84      6814052.83
#Sta/Elev= 30
  4747.0  444.63  4777.3  442.49  4783.1  441.31  4812.8  439.11  4878.2  434.37
  4898.4  434.11  4908.5  433.30  4918.6  433.96  4932.4  434.07  4938.8  433.33
  4948.9  432.92  4959.0  427.12  4969.1  433.69  4979.2  431.94  4987.3  426.38
  4987.5  425.88  4991.0  425.88  4991.3  426.38  4997.2  432.48  5002.2  432.48
  5009.0  433.83  5014.0  433.84  5029.4  435.28  5049.4  436.08  5069.4  437.83
  5079.4  438.24  5089.5  439.41  5109.5  440.22  5149.5  443.33  5162.7  443.68
#Mann=4,-1,0
  4747.0     0.1       0  4812.8    0.12       0  4987.3    0.07       0
  4991.3    0.12       0
Bank Sta=4987.3,4991.3
Exp/Cntr=0.3,0.1

Type RM Length L Ch R = 1,16121,267,267,267
BEGIN DESCRIPTION:
Briar Creek 36.0
END DESCRIPTION:
XS GIS Cut Line= 3
      2756626.03      6813861.01      2756426.00      6813811.00
      2756130.54      6813852.86
#Sta/Elev= 30
  4789.8  444.05  4792.4  444.05  4807.9  442.41  4831.3  440.92  4849.1  439.50
  4854.3  439.49  4862.0  438.66  4872.3  438.26  4890.3  436.76  4972.8  432.63
  4985.7  432.49  4993.4  429.52  4998.5  429.52  5004.1  422.55  5004.3  422.05
  5007.8  422.05  5008.1  422.55  5016.2  428.35  5026.3  431.44  5031.5  432.13
  5046.5  432.43  5097.0  432.21  5137.4  433.68  5167.7  435.19  5173.5  435.95
  5178.5  435.82  5198.0  438.48  5240.7  441.62  5258.6  443.35  5294.4  445.97
#Mann=5,-1,0
  4789.8    0.05       0  4831.3    0.12       0  5004.1    0.07       0
  5008.1    0.12       0  5240.7     0.1       0
Bank Sta=5004.1,5008.1
Exp/Cntr=0.3,0.1

Type RM Length L Ch R = 1,15854,260,260,260
BEGIN DESCRIPTION:
Briar Creek 35.0
END DESCRIPTION:
XS GIS Cut Line= 3
      2756625.99      6813761.00      2756376.00      6813561.00
      2756249.74      6813514.20
#Sta/Elev= 30
  4679.4  441.08  4682.6  441.08  4684.5  440.46  4686.6  439.77  4729.8  436.93
  4814.7  432.75  4843.5  432.18  4885.1  430.32  4928.3  429.75  4935.5  430.06
  4942.7  429.59  4949.1  430.14  4957.1  429.47  4963.5  429.73  4971.5  426.64
  4977.9  427.48  4985.9  423.84  4992.3  423.16  4994.3  422.48  4994.6  421.98
  4998.1  421.98  4998.3  422.48  5002.2  422.48  5009.4  428.78  5014.7  425.84
  5031.5  429.52  5045.1  431.15  5070.2  437.35  5130.9  443.62  5134.2  444.75
#Mann=4,-1,0
  4679.4    0.05       0  4684.5    0.12       0  4994.3    0.07       0
  4998.3    0.12       0
Bank Sta=4994.3,4998.3
Exp/Cntr=0.3,0.1

Type RM Length L Ch R = 1,15594,316,316,316
BEGIN DESCRIPTION:
Briar Creek 34.0
END DESCRIPTION:
XS GIS Cut Line= 3
      2756676.00      6813661.00      2756526.00      6813361.00
      2756276.01      6813361.00
#Sta/Elev= 30
  4664.8  440.11  4695.5  437.76  4701.1  438.53  4717.9  437.99  4723.5  436.91
  4745.9  436.51  4754.2  435.24  4843.7  430.38  4924.7  428.47  4941.5  426.79
  4947.1  424.95  4955.5  424.09  4963.9  424.58  4969.5  426.03  4986.2  423.67
  4991.8  428.16  5002.7  428.03  5010.2  427.26  5028.2  420.26  5028.5  419.76
  5032.0  419.76  5032.2  420.26  5040.2  424.39  5050.2  427.23  5060.2  428.93
  5100.2  429.49  5150.2  431.78  5160.2  432.56  5210.2  439.69  5250.2  443.06
#Mann=3,-1,0
  4664.8    0.12       0  5028.2    0.07       0  5032.2    0.12       0
Bank Sta=5028.2,5032.2
Exp/Cntr=0.3,0.1

Type RM Length L Ch R = 1,15278,349,349,349
BEGIN DESCRIPTION:
Briar Creek 33.0
END DESCRIPTION:
XS GIS Cut Line= 3
      2757264.00      6812998.49      2756576.00      6813111.00
      2756426.05      6813160.98
#Sta/Elev= 30
  4307.6  447.08  4437.3  444.37  4508.2  441.65  4541.8  441.39  4598.2  443.13
  4650.1  443.85  4680.5  443.04  4726.0  439.51  4731.1  438.53  4771.7  436.08
  4787.4  434.07  4822.3  431.35  4848.7  427.34  4862.9  426.27  4876.3  423.77
  4883.1  422.50  4893.3  426.61  4964.2  426.44  4976.6  424.45  4984.5  420.36
  4992.6  418.25  4992.9  417.75  4996.4  417.75  4996.6  418.25  5002.2  420.26
  5015.3  421.23  5025.8  425.28  5036.4  426.45  5078.5  427.33  5162.8  430.57
#Mann=4,-1,0
  4307.6    0.05       0  4876.3    0.12       0  4992.6    0.07       0
  4996.6    0.12       0
Bank Sta=4992.6,4996.6
Exp/Cntr=0.3,0.1

Type RM Length L Ch R = 1,14929,323,323,323
BEGIN DESCRIPTION:
Briar Creek 32.0
END DESCRIPTION:
XS GIS Cut Line= 3
      2756626.01      6812660.99      2756426.00      6812811.00
      2756270.39      6812942.28
#Sta/Elev= 30
  4750.2  437.55  4792.9  433.05  4800.2  431.38  4822.1  428.39  4863.8  424.13
  4886.7  422.91  4907.5  424.14  4922.1  424.13  4928.3  422.53  4936.7  422.14
  4942.9  420.55  4957.5  420.74  4963.8  416.99  4972.1  417.12  4978.3  421.39
  4986.7  417.33  4992.9  418.57  4995.1  415.48  4995.3  414.98  4998.8  414.98
  4999.1  415.48  5003.5  415.48  5007.4  420.37  5013.9  420.30  5021.7  422.01
  5050.2  424.78  5120.5  426.46  5128.3  427.08  5134.8  426.68  5203.8  429.71
#Mann=3,-1,0
  4750.2    0.12       0  4995.1    0.07       0  4999.1    0.12       0
Bank Sta=4995.1,4999.1
Exp/Cntr=0.3,0.1

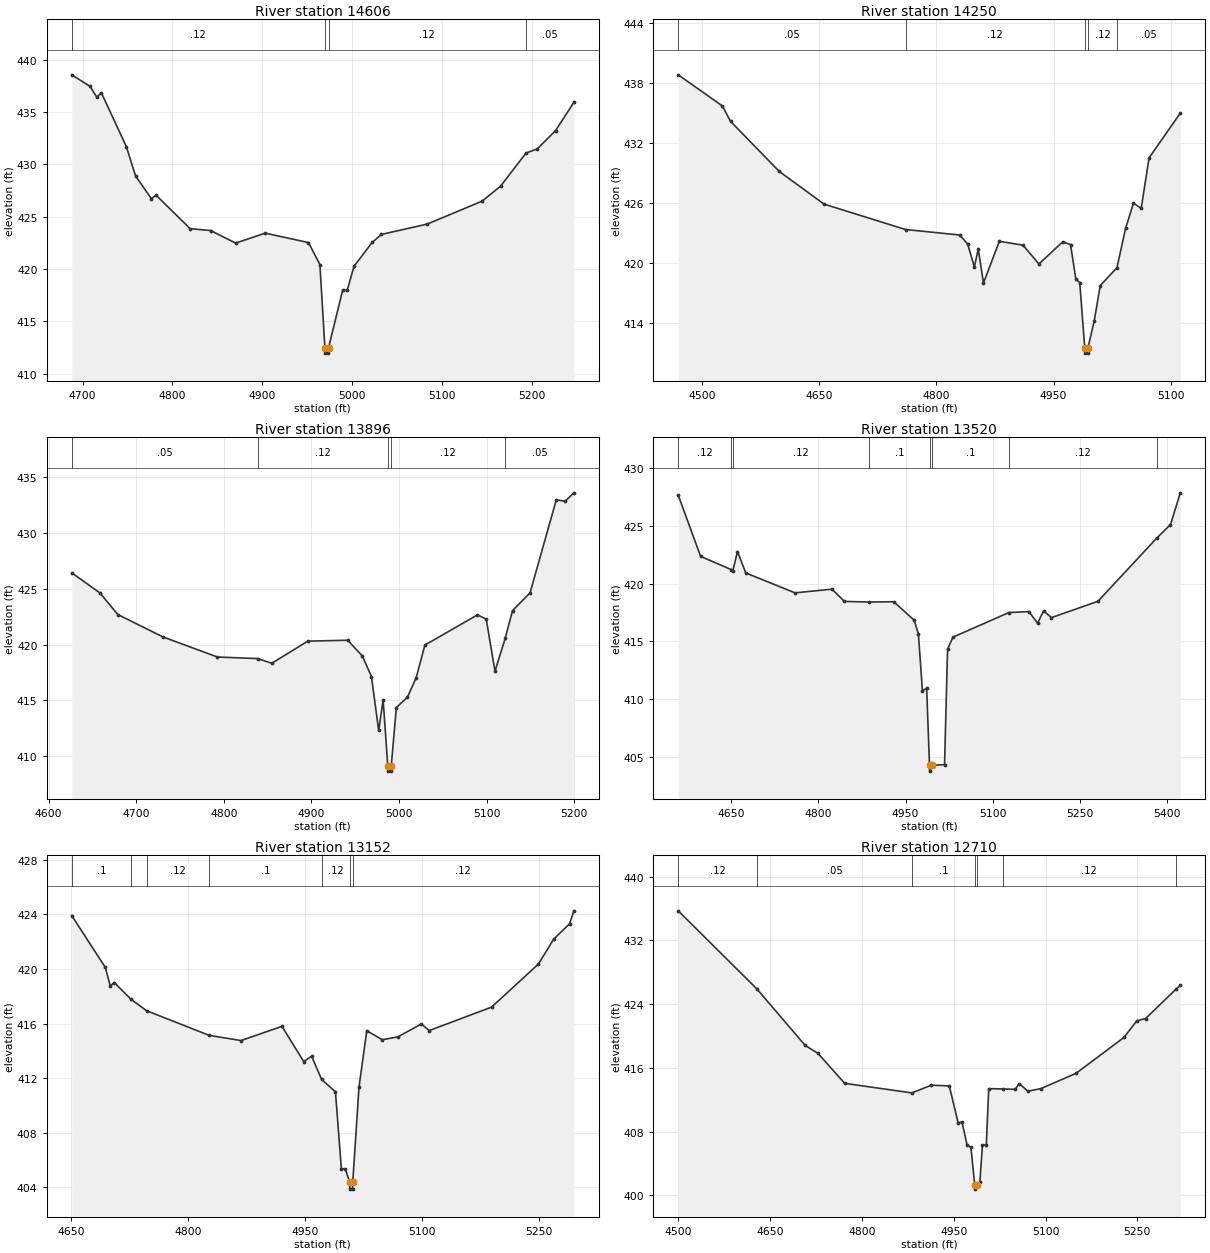
Type RM Length L Ch R = 1,14606,356,356,356
BEGIN DESCRIPTION:
Briar Creek 31.0
END DESCRIPTION:
XS GIS Cut Line= 3
      2756625.99      6812611.00      2756326.00      6812561.00
      2756075.98      6812611.00
#Sta/Elev= 30
  4687.9  438.58  4708.2  437.48  4715.8  436.44  4720.8  436.87  4748.7  431.71
  4758.9  428.91  4776.6  426.72  4781.7  427.07  4819.7  423.86  4842.5  423.68
  4870.4  422.48  4903.3  423.43  4951.5  422.53  4964.2  420.43  4969.8  412.45
  4970.0  411.95  4973.5  411.95  4973.8  412.45  4989.5  417.95  4994.6  417.95
  5002.2  420.26  5022.6  422.56  5032.8  423.31  5083.8  424.30  5145.0  426.50
  5165.4  427.93  5193.7  431.09  5206.2  431.49  5226.6  433.24  5247.0  435.94
#Mann=4,-1,0
  4687.9    0.12       0  4969.8    0.07       0  4973.8    0.12       0
  5193.7    0.05       0
Bank Sta=4969.8,4973.8
Exp/Cntr=0.3,0.1

Type RM Length L Ch R = 1,14250,354,354,354
BEGIN DESCRIPTION:
Briar Creek 30.0
END DESCRIPTION:
XS GIS Cut Line= 3
      2756711.94      6812345.68      2756176.00      6812261.00
      2756075.99      6812261.00
#Sta/Elev= 30
  4469.7  438.82  4526.3  435.70  4536.6  434.17  4599.0  429.15  4656.4  425.88
  4760.6  423.34  4830.1  422.79  4840.2  421.87  4848.7  419.60  4853.7  421.39
  4860.4  417.99  4880.7  422.16  4911.1  421.77  4931.3  419.89  4961.7  422.10
  4971.8  421.84  4978.6  418.37  4983.6  418.03  4990.0  411.47  4990.3  410.97
  4993.8  410.97  4994.0  411.47  5002.2  414.22  5009.8  417.73  5031.2  419.52
  5042.3  423.46  5052.3  425.97  5062.3  425.47  5072.3  430.51  5112.3  434.99
#Mann=5,-1,0
  4469.7    0.05       0  4760.6    0.12       0  4990.0    0.07       0
  4994.0    0.12       0  5031.2    0.05       0
Bank Sta=4990,4994
Exp/Cntr=0.3,0.1

Type RM Length L Ch R = 1,13896,376,376,376
BEGIN DESCRIPTION:
Briar Creek 29.0
END DESCRIPTION:
XS GIS Cut Line= 3
      2756636.90      6812055.49      2756276.00      6811961.00
      2756075.97      6811961.00
#Sta/Elev= 30
  4626.5  426.42  4658.4  424.64  4679.1  422.69  4730.8  420.68  4792.8  418.89
  4838.6  418.75  4854.8  418.33  4895.9  420.31  4941.5  420.39  4958.2  418.98
  4968.6  417.14  4976.8  412.33  4981.9  415.04  4987.2  409.18  4987.5  408.68
  4991.0  408.68  4991.2  409.18  4997.0  414.37  5009.6  415.29  5019.6  417.03
  5029.6  419.96  5089.6  422.66  5099.6  422.28  5109.6  417.62  5121.2  420.55
  5129.6  423.04  5149.6  424.63  5179.6  432.96  5189.6  432.82  5199.6  433.58
#Mann=5,-1,0
  4626.5    0.05       0  4838.6    0.12       0  4987.2    0.07       0
  4991.2    0.12       0  5121.2    0.05       0
Bank Sta=4987.2,4991.2
Exp/Cntr=0.3,0.1

Type RM Length L Ch R = 1,13520,368,368,368
BEGIN DESCRIPTION:
Briar Creek 28.0
END DESCRIPTION:
XS GIS Cut Line= 3
      2756797.20      6811964.14      2756476.00      6811661.00
      2756069.73      6811544.14
#Sta/Elev= 30
  4558.7  427.64  4597.2  422.35  4649.8  421.21  4652.5  421.06  4660.7  422.77
  4674.9  420.92  4759.8  419.20  4823.4  419.52  4844.8  418.46  4887.3  418.41
  4929.8  418.43  4965.0  416.83  4972.2  415.64  4979.1  410.74  4986.4  410.96
  4991.3  404.30  4991.5  403.80  4995.3  404.30  5017.2  404.36  5022.4  414.32
  5031.6  415.37  5128.0  417.50  5162.4  417.58  5177.3  416.58  5187.7  417.64
  5201.3  417.06  5281.3  418.47  5382.9  423.95  5406.2  425.10  5423.1  427.84
#Mann=8,-1,0
  4558.7    0.12       0  4649.8    0.05       0  4652.5    0.12       0
  4887.3     0.1       0  4991.3    0.07       0  4995.3     0.1       0
  5128.0    0.12       0  5382.9     0.1       0
Bank Sta=4991.3,4995.3
Exp/Cntr=0.3,0.1

Type RM Length L Ch R = 1,13152,442,442,442
BEGIN DESCRIPTION:
Briar Creek 27.0
END DESCRIPTION:
XS GIS Cut Line= 3
      2756718.37      6811425.35      2756376.00      6811361.00
      2756080.53      6811370.86
#Sta/Elev= 30
  4650.8  423.91  4693.9  420.11  4700.2  418.74  4705.3  419.01  4726.8  417.78
  4746.9  416.94  4827.1  415.14  4867.9  414.76  4920.4  415.80  4948.3  413.22
  4958.5  413.61  4971.3  411.91  4989.0  411.01  4996.6  405.37  5001.7  405.37
  5007.2  404.38  5007.4  403.88  5010.9  403.88  5011.2  404.38  5019.2  411.34
  5029.2  415.48  5049.2  414.82  5069.2  415.03  5099.2  415.98  5109.2  415.49
  5189.3  417.21  5249.3  420.36  5269.3  422.21  5289.3  423.31  5294.8  424.26
#Mann=7,-1,0
  4650.8     0.1       0  4726.8    0.05       0  4746.9    0.12       0
  4827.1     0.1       0  4971.3    0.12       0  5007.2    0.07       0
  5011.2    0.12       0
Bank Sta=5007.2,5011.2
Exp/Cntr=0.3,0.1

Type RM Length L Ch R = 1,12710,462,462,462
BEGIN DESCRIPTION:
Briar Creek 26.0
END DESCRIPTION:
XS GIS Cut Line= 3
      2756725.98      6810711.01      2756326.00      6811011.00
      2756076.03      6811210.98
#Sta/Elev= 30
  4500.1  435.70  4628.5  425.91  4707.4  418.82  4728.2  417.83  4772.0  414.06
  4881.8  412.86  4913.6  413.83  4942.8  413.74  4957.4  409.09  4963.6  409.21
  4972.0  406.29  4978.2  406.05  4984.4  401.29  4984.7  400.79  4988.6  401.29
  4992.8  401.66  4997.0  406.34  5003.3  406.34  5007.3  413.39  5030.3  413.36
  5050.5  413.31  5056.9  414.02  5071.3  413.08  5092.1  413.39  5149.8  415.31
  5228.2  419.82  5249.0  421.90  5263.4  422.18  5312.8  425.85  5320.2  426.36
#Mann=7,-1,0
  4500.1    0.12       0  4628.5    0.05       0  4881.8     0.1       0
  4984.4    0.07       0  4988.6     0.1       0  5030.3    0.12       0
  5312.8     0.1       0
Bank Sta=4984.4,4988.6
Exp/Cntr=0.3,0.1

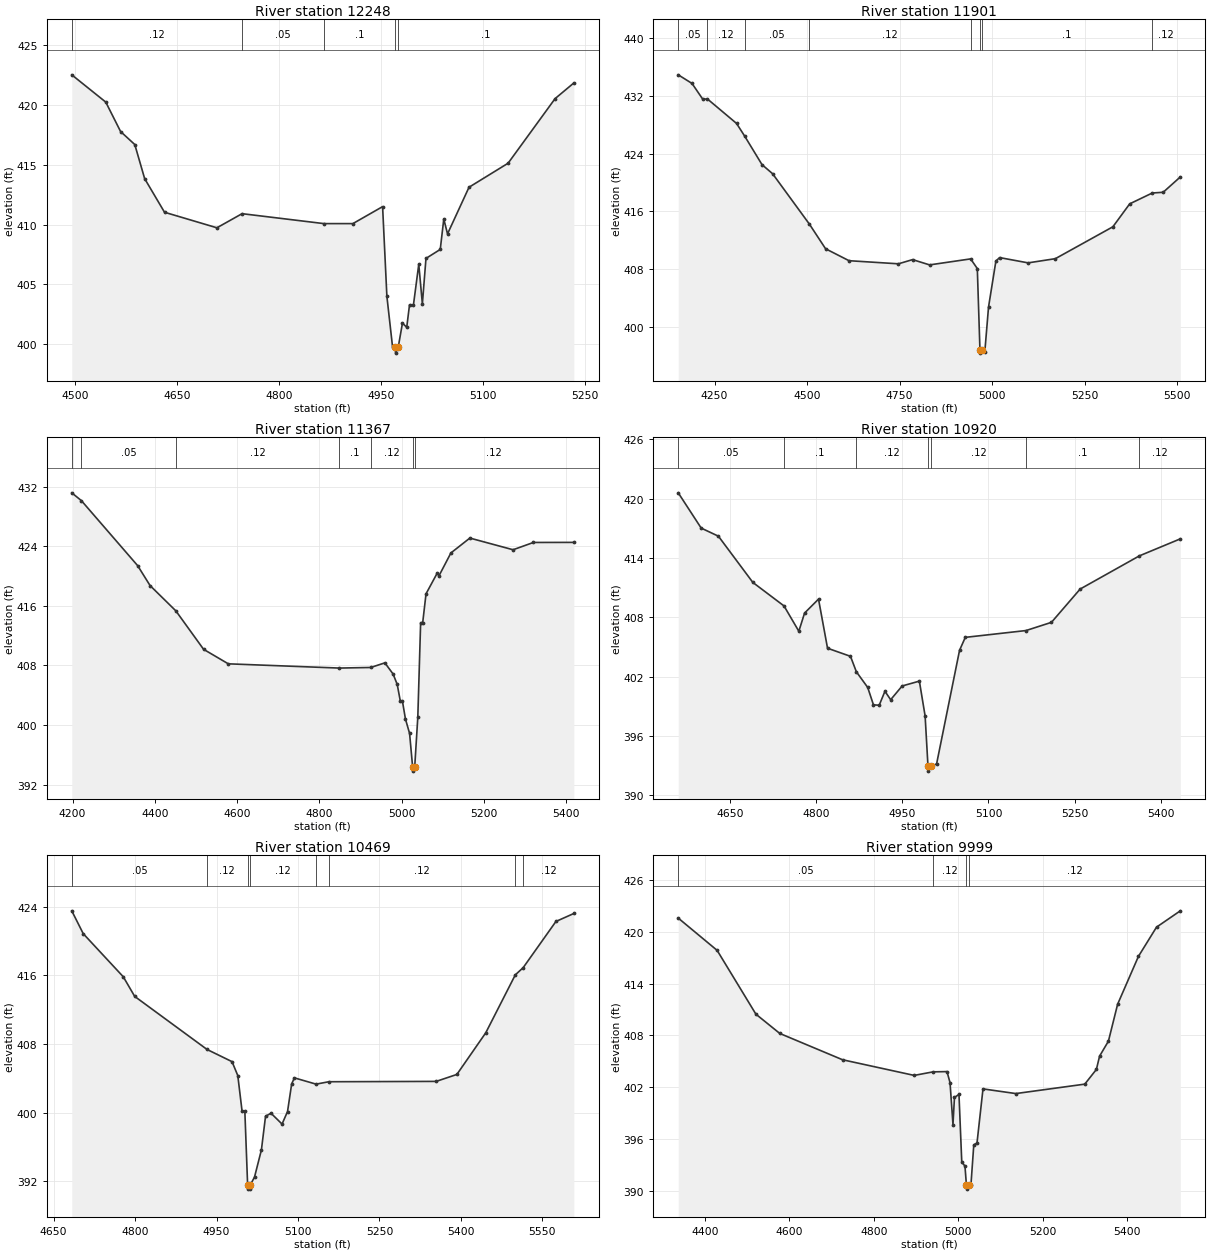
Type RM Length L Ch R = 1,12248,347,347,347
BEGIN DESCRIPTION:
Briar Creek 25.0
END DESCRIPTION:
XS GIS Cut Line= 3
      2756325.97      6810511.04      2756026.00      6810911.00
      2755950.05      6811137.14
#Sta/Elev= 30
  4495.4  422.53  4545.4  420.25  4567.2  417.79  4588.1  416.70  4602.6  413.85
  4631.8  411.04  4708.9  409.74  4745.9  410.92  4866.2  410.09  4908.9  410.09
  4952.6  411.51  4958.9  404.01  4967.2  399.80  4971.3  399.76  4971.7  399.26
  4975.6  399.76  4981.8  401.77  4988.1  401.42  4992.2  403.30  4998.0  403.30
  5005.8  406.69  5011.1  403.38  5016.4  407.18  5037.4  407.93  5042.6  410.47
  5048.1  409.23  5079.7  413.13  5137.2  415.14  5206.3  420.54  5233.9  421.85
#Mann=5,-1,0
  4495.4    0.12       0  4745.9    0.05       0  4866.2     0.1       0
  4971.3    0.07       0  4975.6     0.1       0
Bank Sta=4971.3,4975.6
Exp/Cntr=0.3,0.1

Type RM Length L Ch R = 1,11901,534,534,534
BEGIN DESCRIPTION:
Briar Creek 24.0
END DESCRIPTION:
XS GIS Cut Line= 3
      2756526.03      6810360.98      2755826.53      6810683.69
      2755774.94      6811267.16
#Sta/Elev= 30
  4152.0  434.88  4189.2  433.69  4218.1  431.52  4230.9  431.54  4309.5  428.16
  4332.0  426.36  4378.3  422.46  4406.8  421.21  4506.5  414.22  4550.0  410.83
  4613.3  409.18  4746.7  408.75  4785.0  409.33  4830.9  408.60  4941.8  409.43
  4959.8  408.09  4966.9  396.90  4967.5  396.40  4971.8  396.90  4979.9  396.49
  4990.1  402.77  5010.0  409.13  5020.0  409.61  5097.0  408.88  5170.6  409.46
  5326.0  413.87  5371.4  417.04  5432.4  418.54  5461.8  418.64  5508.1  420.76
#Mann=8,-1,0
  4152.0    0.05       0  4230.9    0.12       0  4332.0    0.05       0
  4506.5    0.12       0  4941.8     0.1       0  4966.9    0.07       0
  4971.8     0.1       0  5432.4    0.12       0
Bank Sta=4966.9,4971.8
Exp/Cntr=0.3,0.1

Type RM Length L Ch R = 1,11367,447,447,447
BEGIN DESCRIPTION:
Briar Creek 23.0
END DESCRIPTION:
XS GIS Cut Line= 4
      2756425.99      6810361.00      2755626.00      6810411.00
      2755577.17      6810411.00      2755209.43      6810364.08
#Sta/Elev= 30
  4198.0  431.20  4221.4  430.15  4358.3  421.41  4388.4  418.74  4451.1  415.34
  4518.6  410.17  4578.7  408.22  4848.4  407.65  4925.2  407.73  4959.5  408.35
  4979.5  406.85  4989.5  405.46  4997.0  403.23  5002.1  403.23  5009.6  400.79
  5019.6  398.87  5027.1  394.30  5027.7  393.80  5032.0  394.30  5039.6  401.05
  5046.5  413.75  5051.5  413.75  5059.6  417.63  5086.4  420.37  5091.4  420.08
  5120.1  423.12  5166.2  425.12  5271.3  423.55  5320.8  424.53  5419.1  424.54
#Mann=7,-1,0
  4198.0    0.12       0  4221.4    0.05       0  4451.1    0.12       0
  4848.4     0.1       0  4925.2    0.12       0  5027.1    0.07       0
  5032.0    0.12       0
Bank Sta=5027.1,5032
Exp/Cntr=0.3,0.1

Type RM Length L Ch R = 1,10920,451,451,451
BEGIN DESCRIPTION:
Briar Creek 22.0
END DESCRIPTION:
XS GIS Cut Line= 3
      2756265.99      6810072.20      2755826.00      6810061.00
      2755391.47      6810055.31
#Sta/Elev= 30
  4559.5  420.60  4599.5  417.03  4629.5  416.21  4689.5  411.53  4743.8  409.15
  4769.6  406.59  4779.6  408.43  4803.9  409.84  4819.6  404.87  4859.6  404.05
  4869.8  402.49  4889.6  400.90  4899.6  399.14  4909.6  399.10  4919.6  400.51
  4929.6  399.66  4949.6  401.05  4979.6  401.54  4989.6  398.02  4994.6  392.93
  4995.3  392.43  4999.6  392.93  5009.6  393.16  5049.6  404.66  5059.6  405.97
  5165.4  406.66  5209.7  407.49  5259.7  410.86  5362.9  414.22  5434.2  415.94
#Mann=7,-1,0
  4559.5    0.05       0  4743.8     0.1       0  4869.8    0.12       0
  4994.6    0.07       0  4999.6    0.12       0  5165.4     0.1       0
  5362.9    0.12       0
Bank Sta=4994.6,4999.6
Exp/Cntr=0.3,0.1

Type RM Length L Ch R = 1,10469,470,470,470
BEGIN DESCRIPTION:
Briar Creek 21.0
END DESCRIPTION:
XS GIS Cut Line= 3
      2756325.98      6809810.99      2756026.00      6809711.00
      2755425.99      6809811.00
#Sta/Elev= 30
  4683.4  423.50  4704.5  420.84  4778.2  415.82  4799.3  413.53  4932.5  407.35
  4978.5  405.93  4989.1  404.31  4997.0  400.15  5002.1  400.15  5007.2  391.58
  5007.8  391.08  5011.6  391.08  5012.2  391.58  5019.9  392.48  5032.6  395.65
  5040.2  399.57  5050.3  399.92  5070.6  398.66  5080.7  400.12  5088.3  403.34
  5093.4  404.04  5133.3  403.31  5156.7  403.59  5354.4  403.63  5392.5  404.44
  5445.7  409.29  5500.1  416.04  5514.6  416.88  5574.9  422.26  5607.9  423.19
#Mann=8,-1,0
  4683.4    0.05       0  4932.5    0.12       0  5007.2    0.07       0
  5012.2    0.12       0  5133.3     0.1       0  5156.7    0.12       0
  5500.1     0.1       0  5514.6    0.12       0
Bank Sta=5007.2,5012.2
Exp/Cntr=0.3,0.1

Type RM Length L Ch R = 1,9999,461,461,461
BEGIN DESCRIPTION:
Briar Creek 20.0
END DESCRIPTION:
XS GIS Cut Line= 3
      2756296.86      6808951.61      2755826.00      6809411.00
      2755426.04      6809760.97
#Sta/Elev= 30
  4336.9  421.57  4429.0  417.84  4520.9  410.46  4577.5  408.23  4726.1  405.19
  4895.8  403.38  4940.6  403.79  4973.5  403.82  4980.7  402.55  4987.7  397.70
  4991.2  400.83  5001.9  401.18  5008.5  393.37  5016.1  392.89  5019.5  390.73
  5020.5  390.23  5026.0  390.73  5030.3  390.76  5037.0  395.35  5044.6  395.56
  5058.8  401.82  5136.6  401.28  5299.9  402.37  5327.4  404.07  5335.0  405.61
  5355.9  407.34  5377.7  411.61  5427.1  417.15  5469.8  420.52  5526.2  422.41
#Mann=4,-1,0
  4336.9    0.05       0  4940.6    0.12       0  5019.5    0.07       0
  5026.0    0.12       0
Bank Sta=5019.5,5026
Exp/Cntr=0.3,0.1

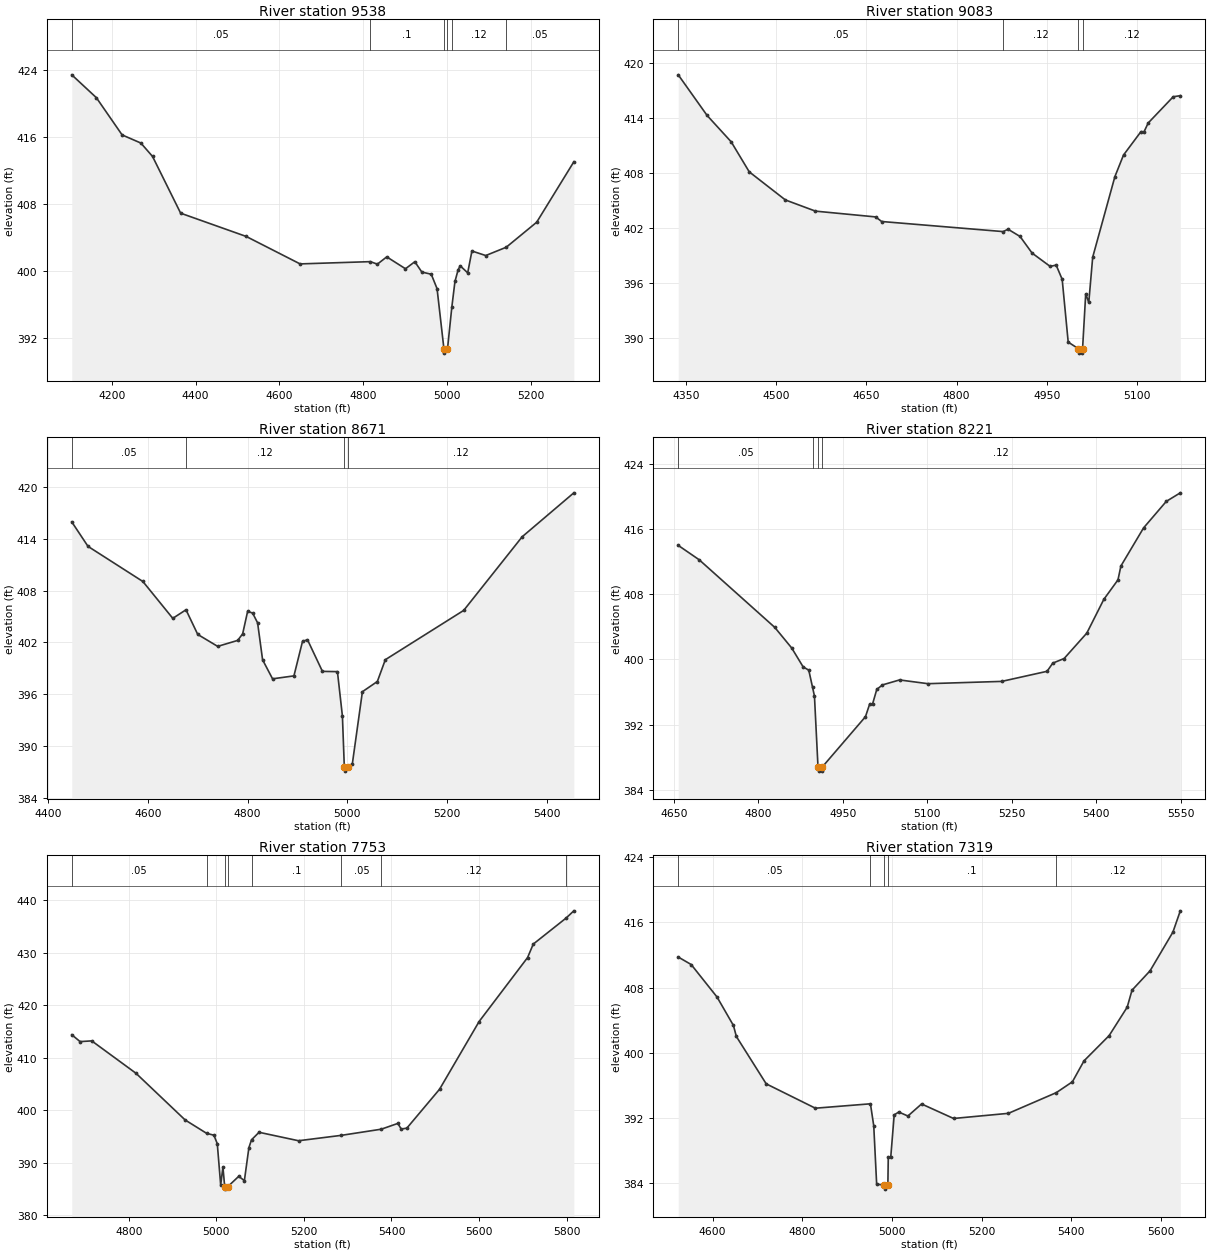
Type RM Length L Ch R = 1,9538,455,455,455
BEGIN DESCRIPTION:
Briar Creek 19.0
END DESCRIPTION:
XS GIS Cut Line= 3
      2756275.98      6808911.01      2755476.00      6809311.00
      2755426.01      6809610.96
#Sta/Elev= 30
  4104.3  423.40  4163.0  420.67  4224.5  416.22  4269.2  415.25  4297.1  413.65
  4364.2  406.87  4520.7  404.09  4649.3  400.81  4817.0  401.08  4833.8  400.78
  4856.2  401.65  4900.9  400.23  4923.2  401.07  4940.0  399.83  4962.4  399.58
  4976.3  397.85  4992.7  390.65  4993.7  390.15  4999.2  390.65  5001.2  390.65
  5011.6  395.68  5019.0  398.71  5026.6  400.11  5031.6  400.58  5049.4  399.74
  5059.5  402.35  5092.5  401.81  5141.4  402.80  5214.1  405.79  5302.8  413.01
#Mann=6,-1,0
  4104.3    0.05       0  4817.0     0.1       0  4992.7    0.07       0
  4999.2     0.1       0  5011.6    0.12       0  5141.4    0.05       0
Bank Sta=4992.7,4999.2
Exp/Cntr=0.3,0.1

Type RM Length L Ch R = 1,9083,412,412,412
BEGIN DESCRIPTION:
Briar Creek 18.0
END DESCRIPTION:
XS GIS Cut Line= 3
      2756183.96      6808909.89      2755526.00      6808911.00
      2755353.93      6808872.43
#Sta/Elev= 30
  4337.4  418.69  4385.4  414.26  4425.4  411.39  4455.4  408.12  4515.4  405.06
  4565.4  403.84  4665.4  403.21  4675.4  402.71  4877.4  401.61  4885.4  401.87
  4905.4  401.08  4925.4  399.27  4955.4  397.82  4965.4  397.96  4975.4  396.41
  4985.4  389.57  5001.9  388.87  5003.1  388.37  5008.2  388.37  5009.3  388.87
  5014.5  394.83  5019.6  393.89  5026.1  398.82  5063.0  407.60  5077.3  409.95
  5106.3  412.50  5111.4  412.48  5118.3  413.44  5159.9  416.30  5171.7  416.42
#Mann=4,-1,0
  4337.4    0.05       0  4877.4    0.12       0  5001.9    0.07       0
  5009.3    0.12       0
Bank Sta=5001.9,5009.3
Exp/Cntr=0.3,0.1

Type RM Length L Ch R = 1,8671,450,450,450
BEGIN DESCRIPTION:
Briar Creek 17.0
END DESCRIPTION:
XS GIS Cut Line= 3
      2756228.52      6808586.26      2755676.00      6808561.00
      2755222.56      6808531.54
#Sta/Elev= 30
  4447.3  415.94  4479.9  413.11  4590.0  409.05  4650.0  404.79  4676.5  405.78
  4700.1  402.93  4740.1  401.55  4780.2  402.24  4790.2  403.00  4800.2  405.60
  4810.2  405.40  4820.2  404.27  4830.2  400.00  4850.2  397.80  4893.1  398.14
  4910.3  402.12  4920.3  402.32  4950.3  398.66  4980.4  398.63  4990.4  393.49
  4994.2  387.63  4995.3  387.13  5001.6  387.63  5010.4  388.01  5030.5  396.31
  5060.5  397.49  5076.5  400.01  5233.8  405.71  5351.1  414.22  5454.8  419.30
#Mann=4,-1,0
  4447.3    0.05       0  4676.5    0.12       0  4994.2    0.07       0
  5001.6    0.12       0
Bank Sta=4994.2,5001.6
Exp/Cntr=0.3,0.1

Type RM Length L Ch R = 1,8221,468,468,468
BEGIN DESCRIPTION:
Briar Creek 16.0
END DESCRIPTION:
XS GIS Cut Line= 3
      2756166.27      6808121.49      2755826.00      6808161.00
      2755281.30      6808229.90
#Sta/Elev= 30
  4657.5  413.99  4694.8  412.22  4828.9  403.93  4859.1  401.39  4879.3  399.08
  4889.3  398.68  4896.0  396.58  4899.4  395.51  4905.7  386.79  4906.9  386.29
  4912.1  386.29  4913.2  386.79  4990.0  392.97  4997.5  394.53  5002.6  394.53
  5010.1  396.32  5020.2  396.87  5050.5  397.48  5100.9  397.02  5231.9  397.30
  5312.5  398.54  5322.6  399.54  5342.8  400.11  5383.1  403.23  5413.3  407.37
  5438.4  409.76  5443.6  411.46  5483.9  416.14  5524.2  419.39  5549.1  420.44
#Mann=4,-1,0
  4657.5    0.05       0  4896.0    0.12       0  4905.7    0.07       0
  4913.2    0.12       0
Bank Sta=4905.7,4913.2
Exp/Cntr=0.3,0.1

Type RM Length L Ch R = 1,7753,434,434,434
BEGIN DESCRIPTION:
Briar Creek 15.0
END DESCRIPTION:
XS GIS Cut Line= 3
      2756132.13      6807860.87      2755826.00      6807761.00
      2755026.03      6807960.99
#Sta/Elev= 30
  4669.9  414.37  4688.9  413.06  4715.5  413.20  4816.5  407.03  4928.8  398.13
  4977.7  395.59  4994.5  395.22  5002.2  393.61  5010.0  385.73  5015.1  389.17
  5019.1  385.45  5020.2  384.95  5026.6  385.45  5051.2  387.39  5064.1  386.57
  5074.4  392.85  5080.4  394.35  5097.6  395.78  5187.8  394.17  5285.7  395.20
  5376.7  396.37  5414.5  397.47  5422.3  396.40  5435.1  396.57  5509.9  403.99
  5600.1  416.88  5710.9  429.08  5723.8  431.64  5798.8  436.60  5816.5  437.98
#Mann=8,-1,0
  4669.9    0.05       0  4977.7    0.12       0  5019.1    0.07       0
  5026.6    0.12       0  5080.4     0.1       0  5285.7    0.05       0
  5376.7    0.12       0  5798.8    0.05       0
Bank Sta=5019.1,5026.6
Exp/Cntr=0.3,0.1

Type RM Length L Ch R = 1,7319,467,467,467
BEGIN DESCRIPTION:
Briar Creek 14.0
END DESCRIPTION:
XS GIS Cut Line= 3
      2756125.97      6807610.98      2755726.00      6807361.00
      2755089.82      6807234.01
#Sta/Elev= 30
  4523.2  411.74  4552.1  410.82  4609.8  406.83  4646.4  403.34  4652.9  401.99
  4719.5  396.18  4829.2  393.19  4952.1  393.73  4959.5  391.03  4966.0  383.86
  4983.4  383.76  4984.6  383.26  4991.0  383.76  4991.9  387.16  4997.4  387.16
  5005.1  392.37  5015.3  392.72  5035.7  392.23  5066.2  393.71  5137.6  391.93
  5260.0  392.56  5366.9  395.10  5402.8  396.43  5428.7  399.00  5484.8  402.10
  5525.1  405.59  5535.8  407.67  5576.1  410.05  5627.1  414.80  5643.6  417.41
#Mann=5,-1,0
  4523.2    0.05       0  4952.1     0.1       0  4983.4    0.07       0
  4991.0     0.1       0  5366.9    0.12       0
Bank Sta=4983.4,4991
Exp/Cntr=0.3,0.1

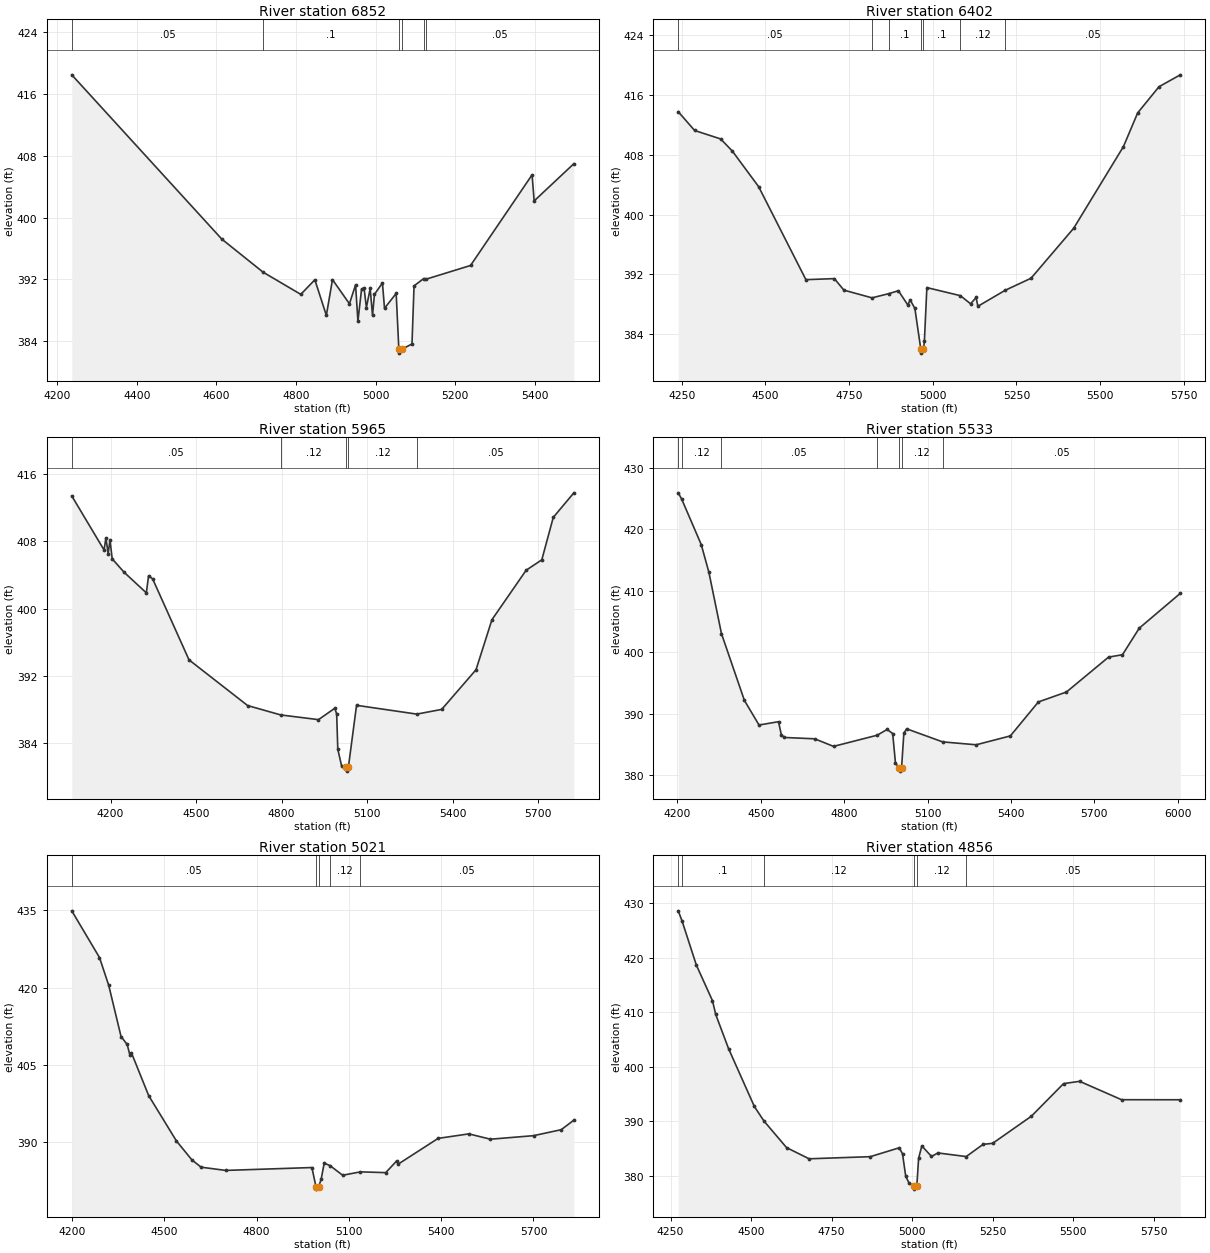
Type RM Length L Ch R = 1,6852,450,450,450
BEGIN DESCRIPTION:
Briar Creek 13.0
END DESCRIPTION:
XS GIS Cut Line= 3
      2756425.98      6807410.99      2755776.00      6807011.00
      2755295.69      6806879.43
#Sta/Elev= 30
  4236.8  418.49  4613.6  397.22  4717.5  392.93  4812.1  390.06  4847.4  391.95
  4876.3  387.34  4891.7  391.97  4934.3  388.84  4949.7  391.29  4955.6  386.59
  4964.8  390.75  4971.0  390.89  4976.9  388.35  4986.4  390.82  4992.3  387.33
  4997.1  390.05  5017.2  391.54  5022.4  388.26  5051.7  390.18  5058.4  382.95
  5059.6  382.45  5066.1  382.95  5091.4  383.64  5096.6  391.16  5121.0  392.11
  5125.8  392.01  5238.5  393.80  5393.1  405.54  5398.3  402.16  5498.0  406.98
#Mann=6,-1,0
  4236.8    0.05       0  4717.5     0.1       0  5058.4    0.07       0
  5066.1     0.1       0  5121.0    0.12       0  5125.8    0.05       0
Bank Sta=5058.4,5066.1
Exp/Cntr=0.3,0.1

Type RM Length L Ch R = 1,6402,437,437,437
BEGIN DESCRIPTION:
Briar Creek 12.0
END DESCRIPTION:
XS GIS Cut Line= 3
      2756485.96      6807220.02      2755976.00      6806661.00
      2755275.98      6806410.99
#Sta/Elev= 30
  4239.5  413.74  4288.5  411.23  4366.2  410.10  4401.3  408.47  4479.7  403.72
  4620.9  391.29  4706.0  391.43  4734.4  389.89  4818.4  388.86  4869.4  389.43
  4897.2  389.81  4925.6  387.89  4932.3  388.59  4946.5  387.44  4964.3  381.97
  4965.4  381.47  4972.0  381.97  4974.9  383.04  4982.3  390.23  5082.5  389.15
  5113.0  388.06  5129.4  388.91  5134.7  387.73  5215.9  389.86  5293.5  391.48
  5420.9  398.16  5569.6  409.08  5612.1  413.58  5675.8  417.08  5739.5  418.67
#Mann=7,-1,0
  4239.5    0.05       0  4818.4    0.12       0  4869.4     0.1       0
  4964.3    0.07       0  4972.0     0.1       0  5082.5    0.12       0
  5215.9    0.05       0
Bank Sta=4964.3,4972
Exp/Cntr=0.3,0.1

Type RM Length L Ch R = 1,5965,432,432,432
BEGIN DESCRIPTION:
Briar Creek 11.0
END DESCRIPTION:
XS GIS Cut Line= 3
      2756776.14      6807079.87      2756176.00      6806361.00
      2755354.04      6806292.03
#Sta/Elev= 30
  4063.8  413.43  4177.1  406.98  4183.6  408.44  4191.4  406.55  4197.9  408.18
  4205.6  405.93  4247.3  404.33  4325.4  401.87  4333.2  403.90  4347.5  403.54
  4475.1  393.88  4680.7  388.43  4797.0  387.31  4929.3  386.75  4986.6  388.11
  4993.1  387.42  4997.0  383.23  5010.3  381.24  5026.5  381.11  5027.7  380.61
  5034.3  381.11  5062.8  388.46  5274.2  387.41  5361.5  387.97  5481.9  392.70
  5537.8  398.67  5657.8  404.57  5712.7  405.81  5752.9  410.87  5825.1  413.80
#Mann=5,-1,0
  4063.8    0.05       0  4797.0    0.12       0  5026.5    0.07       0
  5034.3    0.12       0  5274.2    0.05       0
Bank Sta=5026.5,5034.3
Exp/Cntr=0.3,0.1

Type RM Length L Ch R = 1,5533,512,512,512
BEGIN DESCRIPTION:
Briar Creek 10.0
END DESCRIPTION:
XS GIS Cut Line= 3
      2757126.01      6805961.00      2756326.00      6806011.00
      2755329.65      6806139.70
#Sta/Elev= 30
  4203.0  425.92  4215.6  424.88  4285.7  417.52  4313.2  413.03  4358.5  403.05
  4441.0  392.20  4493.6  388.20  4563.7  388.74  4573.7  386.66  4583.8  386.18
  4694.0  385.96  4761.6  384.73  4918.5  386.54  4954.5  387.48  4974.5  386.81
  4984.5  382.01  4997.8  381.21  4999.0  380.71  5006.4  381.21  5014.7  386.89
  5024.7  387.58  5154.2  385.46  5274.8  384.99  5397.8  386.43  5498.6  391.95
  5599.5  393.56  5751.0  399.23  5801.1  399.62  5861.6  403.94  6009.2  409.59
#Mann=7,-1,0
  4203.0    0.05       0  4215.6    0.12       0  4358.5    0.05       0
  4918.5    0.12       0  4997.8    0.07       0  5006.4    0.12       0
  5154.2    0.05       0
Bank Sta=4997.8,5006.4
Exp/Cntr=0.3,0.1

Type RM Length L Ch R = 1,5021,165,165,165
BEGIN DESCRIPTION:
Briar Creek 9.0
END DESCRIPTION:
XS GIS Cut Line= 3
      2757226.03      6805511.00      2756426.00      6805531.83
      2755594.91      6805545.40
#Sta/Elev= 30
  4199.7  434.93  4289.8  425.84  4319.8  420.43  4359.8  410.48  4379.8  408.93
  4388.3  406.94  4393.3  407.35  4449.8  398.96  4539.8  390.16  4589.9  386.49
  4619.9  385.06  4699.9  384.43  4980.0  384.99  4993.1  381.29  4994.4  380.79
  5002.0  381.29  5010.0  382.70  5020.0  385.83  5038.6  385.38  5080.0  383.49
  5137.7  384.15  5220.0  384.00  5255.3  386.27  5260.3  385.65  5390.1  390.66
  5490.1  391.54  5560.1  390.50  5700.1  391.19  5790.1  392.35  5831.2  394.21
#Mann=5,-1,0
  4199.7    0.05       0  4993.1    0.03       0  5002.0    0.05       0
  5038.6    0.12       0  5137.7    0.05       0
Bank Sta=4993.1,5002
Exp/Cntr=0.3,0.1

Type RM Length L Ch R = 1,4856,274,274,274
BEGIN DESCRIPTION:
Mapping XS d247e005
END DESCRIPTION:
XS GIS Cut Line= 2
      2757152.26      6805370.20      2755593.48      6805362.65
#Sta/Elev= 30
  4273.7  428.61  4285.5  426.76  4330.0  418.66  4380.0  412.14  4390.0  409.63
  4430.0  403.34  4510.0  392.75  4539.9  390.08  4610.0  385.21  4680.0  383.16
  4870.0  383.55  4960.0  385.18  4970.0  384.08  4980.0  379.95  4990.0  378.75
  5005.5  378.10  5006.8  377.60  5014.4  378.10  5020.0  383.25  5030.0  385.52
  5060.0  383.59  5080.0  384.23  5167.8  383.57  5220.0  385.80  5250.0  386.00
  5370.0  390.96  5470.0  396.94  5520.0  397.36  5650.0  393.99  5832.5  393.98
#Mann=6,-1,0
  4273.7    0.12       0  4285.5     0.1       0  4539.9    0.12       0
  5005.5    0.07       0  5014.4    0.12       0  5167.8    0.05       0
Bank Sta=5005.5,5014.4
Exp/Cntr=0.3,0.1