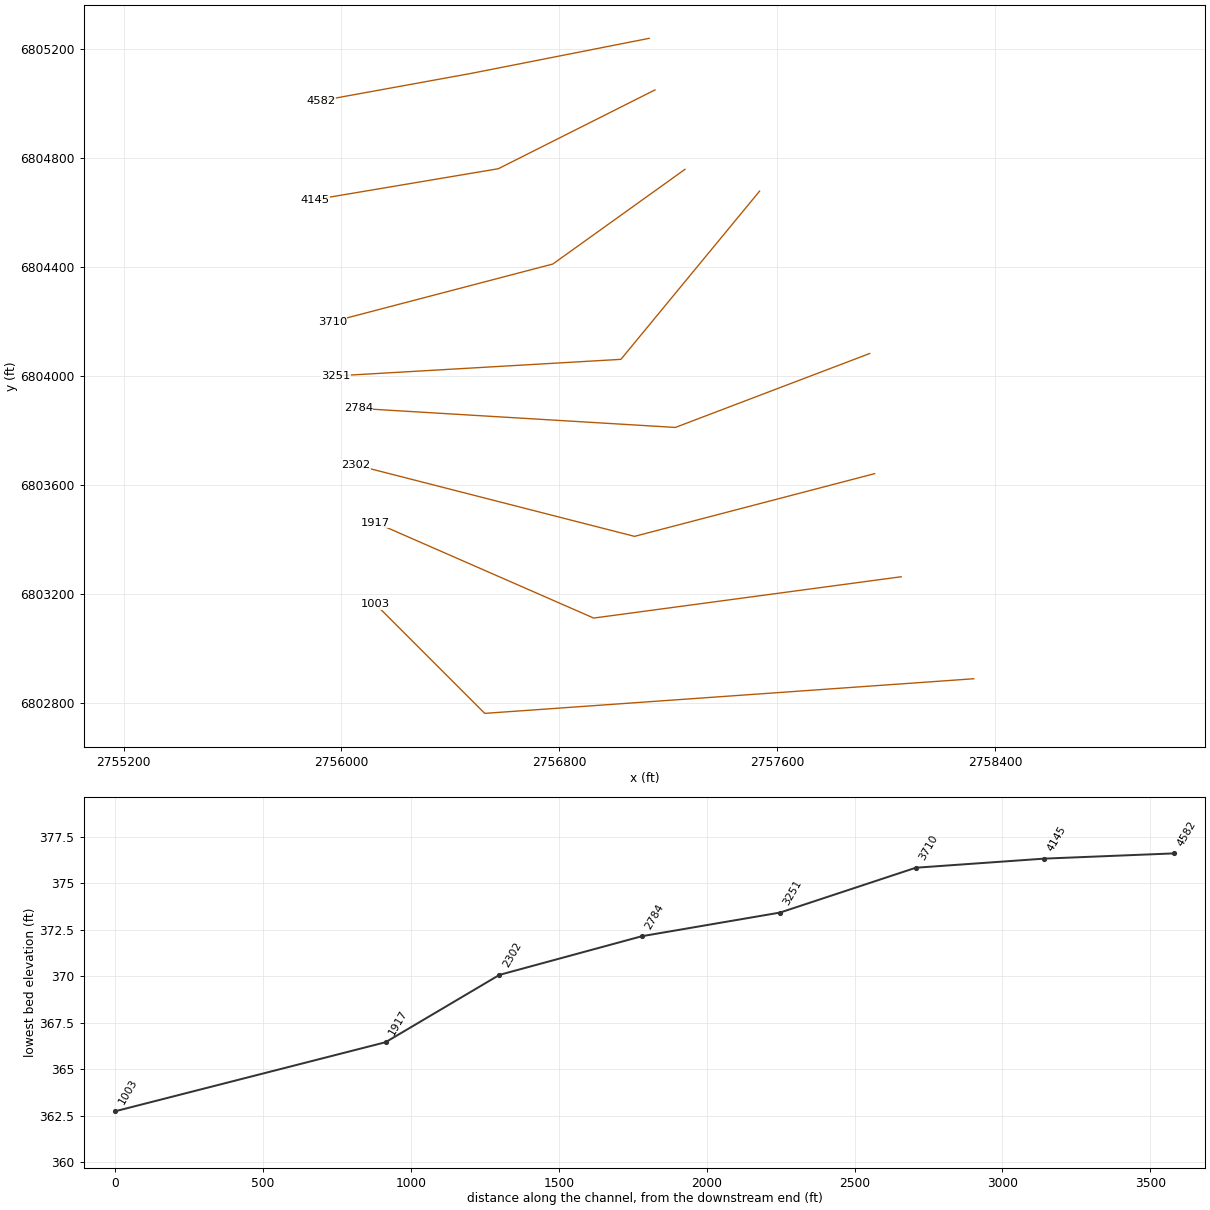
HEC-RAS study Briar Creek.prj: Briar Creek Base Level Engineering

--- Briar Creek.g01 (geometry) --- (continued)

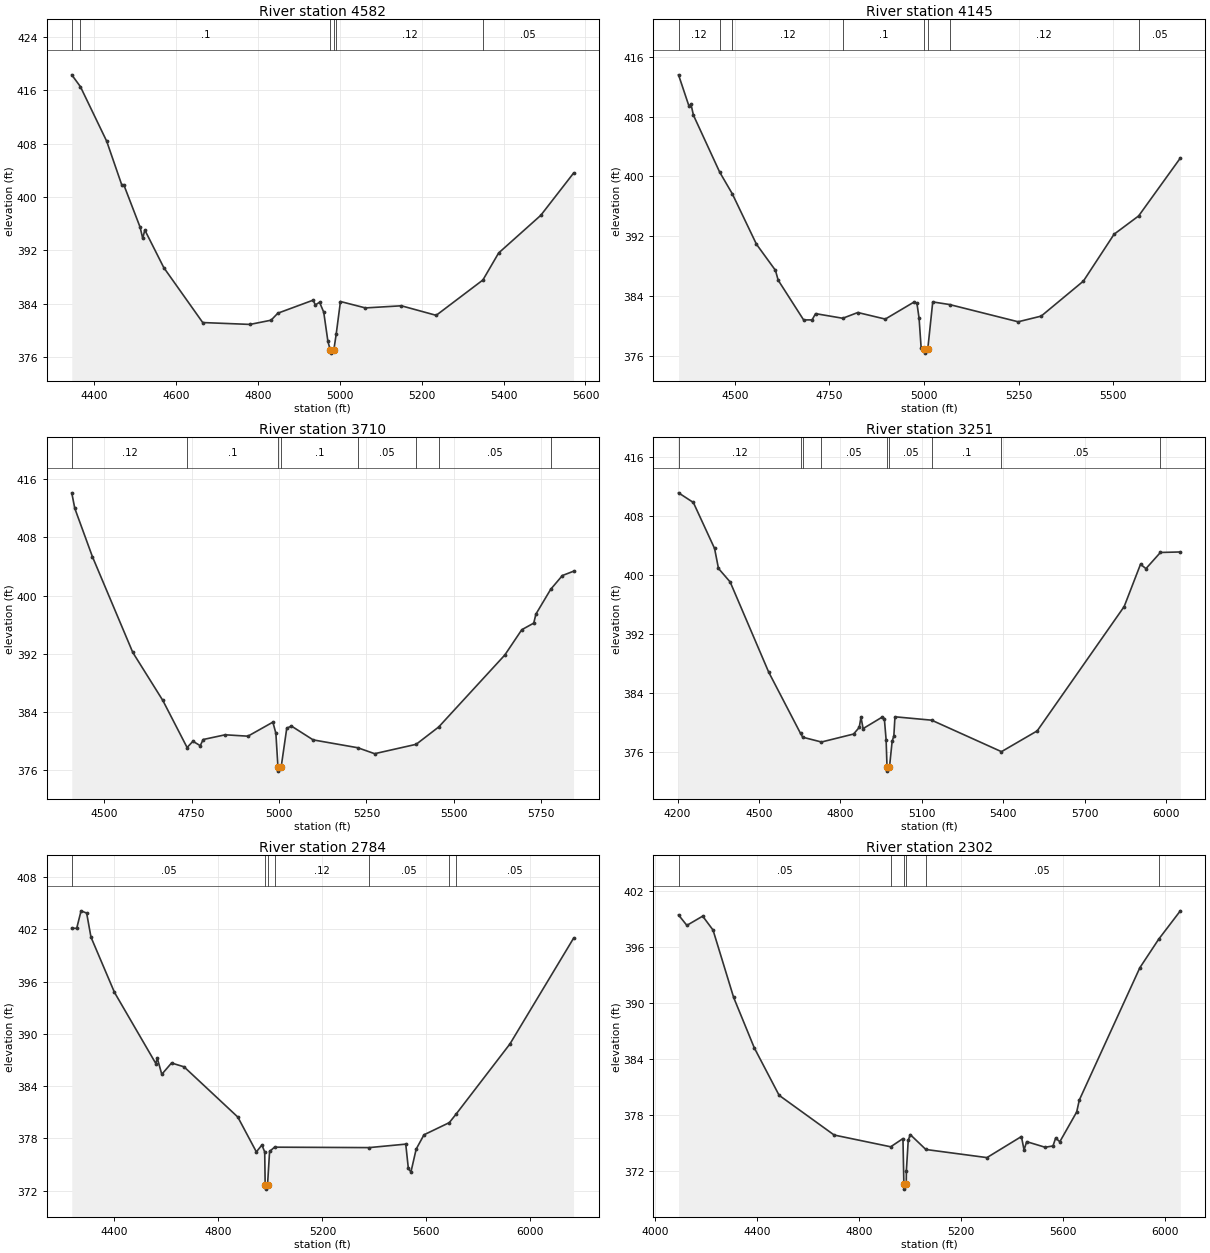
Type RM Length L Ch R = 1,4582,437,437,437
BEGIN DESCRIPTION:
Briar Creek 8.0
END DESCRIPTION:
XS GIS Cut Line= 3
      2757129.73      6805239.76      2756476.00      6805111.00
      2755926.00      6805011.00
#Sta/Elev= 30
  4345.6  418.29  4366.7  416.52  4430.9  408.35  4467.6  401.82  4472.7  401.82
  4512.5  395.47  4518.9  393.79  4524.0  395.05  4570.3  389.42  4665.4  381.19
  4780.8  380.91  4832.2  381.54  4848.8  382.59  4934.9  384.54  4940.5  383.83
  4950.7  384.23  4960.9  382.74  4971.1  378.36  4976.7  377.11  4978.0  376.61
  4985.6  377.11  4991.2  379.40  5001.7  384.34  5062.7  383.38  5150.4  383.70
  5235.5  382.27  5349.5  387.56  5388.0  391.61  5490.9  397.25  5570.9  403.57
#Mann=6,-1,0
  4345.6    0.12       0  4366.7     0.1       0  4976.7    0.07       0
  4985.6     0.1       0  4991.2    0.12       0  5349.5    0.05       0
Bank Sta=4976.7,4985.6
Exp/Cntr=0.3,0.1

Type RM Length L Ch R = 1,4145,435,435,435
BEGIN DESCRIPTION:
Briar Creek 7.0
END DESCRIPTION:
XS GIS Cut Line= 3
      2757151.21      6805050.42      2756576.00      6804761.00
      2755903.48      6804647.78
#Sta/Elev= 30
  4351.3  413.61  4378.7  409.45  4384.3  409.65  4390.7  408.20  4459.9  400.59
  4493.5  397.66  4557.2  390.92  4607.4  387.42  4614.6  386.10  4681.8  380.78
  4704.2  380.78  4713.4  381.62  4785.2  381.00  4825.0  381.77  4897.6  380.89
  4972.8  383.15  4981.3  382.98  4986.9  381.02  4992.4  376.99  5000.9  376.83
  5002.2  376.33  5009.8  376.83  5023.0  383.19  5067.3  382.84  5248.7  380.53
  5309.6  381.29  5421.1  385.98  5502.2  392.26  5567.1  394.71  5677.2  402.46
#Mann=8,-1,0
  4351.3    0.12       0  4459.9     0.1       0  4493.5    0.12       0
  4785.2     0.1       0  5000.9    0.07       0  5009.8     0.1       0
  5067.3    0.12       0  5567.1    0.05       0
Bank Sta=5000.9,5009.8
Exp/Cntr=0.3,0.1

Type RM Length L Ch R = 1,3710,459,459,459
BEGIN DESCRIPTION:
Briar Creek 6.0
END DESCRIPTION:
XS GIS Cut Line= 3
      2757261.29      6804758.71      2756776.00      6804411.00
      2755965.87      6804199.02
#Sta/Elev= 30
  4407.7  414.14  4416.4  412.00  4466.7  405.36  4582.2  392.17  4668.1  385.56
  4737.4  379.09  4754.1  379.95  4775.0  379.34  4783.3  380.19  4846.3  380.84
  4911.3  380.65  4982.6  382.58  4991.2  381.04  4997.2  376.34  4998.5  375.84
  5006.1  376.34  5022.3  381.75  5035.7  382.04  5097.7  380.14  5225.2  379.06
  5273.5  378.24  5392.2  379.53  5456.7  381.92  5645.6  391.82  5694.1  395.30
  5728.3  396.21  5734.5  397.45  5776.7  400.86  5810.2  402.76  5842.1  403.35
#Mann=8,-1,0
  4407.7    0.12       0  4737.4     0.1       0  4997.2    0.07       0
  5006.1     0.1       0  5225.2    0.05       0  5392.2    0.12       0
  5456.7    0.05       0  5776.7    0.12       0
Bank Sta=4997.2,5006.1
Exp/Cntr=0.3,0.1

Type RM Length L Ch R = 1,3251,467,467,467
BEGIN DESCRIPTION:
Briar Creek 5.0
END DESCRIPTION:
XS GIS Cut Line= 3
      2757535.29      6804678.74      2757026.00      6804061.00
      2755979.57      6804000.25
#Sta/Elev= 30
  4203.7  411.18  4258.3  409.87  4336.5  403.63  4350.9  400.92  4393.9  399.09
  4535.9  386.86  4653.3  378.54  4661.3  378.03  4730.3  377.38  4848.6  378.46
  4869.5  379.36  4875.9  380.74  4883.8  379.20  4954.1  380.76  4962.0  380.55
  4968.5  377.70  4971.9  373.93  4973.2  373.43  4980.8  373.93  4990.7  377.46
  4997.1  378.24  5001.1  380.80  5136.3  380.34  5393.5  376.07  5525.2  378.89
  5845.7  395.76  5905.8  401.49  5925.9  400.90  5979.1  403.09  6052.5  403.16
#Mann=9,-1,0
  4203.7    0.12       0  4653.3    0.05       0  4661.3    0.12       0
  4730.3    0.05       0  4971.9    0.04       0  4980.8    0.05       0
  5136.3     0.1       0  5393.5    0.05       0  5979.1    0.12       0
Bank Sta=4971.9,4980.8
Exp/Cntr=0.3,0.1

Type RM Length L Ch R = 1,2784,482,482,482
BEGIN DESCRIPTION:
Briar Creek 4.0
END DESCRIPTION:
XS GIS Cut Line= 3
      2757939.55      6804082.46      2757226.00      6803811.00
      2756061.84      6803880.97
#Sta/Elev= 30
  4236.1  402.13  4255.1  402.12  4272.0  404.13  4293.4  403.87  4310.0  401.11
  4400.4  394.76  4559.6  386.58  4564.9  387.22  4582.3  385.35  4619.8  386.65
  4667.9  386.21  4874.7  380.44  4946.0  376.44  4967.4  377.23  4978.1  376.43
  4979.9  372.66  4981.3  372.16  4989.0  372.66  4996.9  376.49  5015.9  376.98
  5379.8  376.93  5520.5  377.33  5530.5  374.53  5540.5  374.13  5560.6  376.76
  5590.6  378.40  5688.0  379.80  5713.1  380.74  5921.2  388.84  6165.8  400.98
#Mann=7,-1,0
  4236.1    0.05       0  4979.9    0.04       0  4989.0    0.05       0
  5015.9    0.12       0  5379.8    0.05       0  5688.0     0.1       0
  5713.1    0.05       0
Bank Sta=4979.9,4989
Exp/Cntr=0.3,0.1

Type RM Length L Ch R = 1,2302,385,385,385
BEGIN DESCRIPTION:
Briar Creek 3.0
END DESCRIPTION:
XS GIS Cut Line= 3
      2757957.66      6803641.29      2757076.00      6803411.00
      2756052.21      6803672.92
#Sta/Elev= 30
  4092.9  399.48  4125.6  398.36  4187.6  399.35  4228.2  397.86  4309.1  390.63
  4390.0  385.23  4487.4  380.14  4703.3  375.88  4925.0  374.62  4973.1  375.50
  4976.7  370.58  4978.0  370.08  4986.0  370.58  4986.5  372.06  4993.8  375.31
  5001.6  375.93  5062.9  374.33  5302.5  373.46  5437.7  375.72  5448.0  374.28
  5458.3  375.17  5530.6  374.57  5561.5  374.71  5571.9  375.56  5588.3  375.16
  5654.4  378.35  5664.7  379.63  5902.2  393.82  5975.3  396.85  6060.9  399.92
#Mann=6,-1,0
  4092.9    0.05       0  4925.0    0.12       0  4976.7    0.07       0
  4986.0    0.12       0  5062.9    0.05       0  5975.3    0.12       0
Bank Sta=4976.7,4986
Exp/Cntr=0.3,0.1

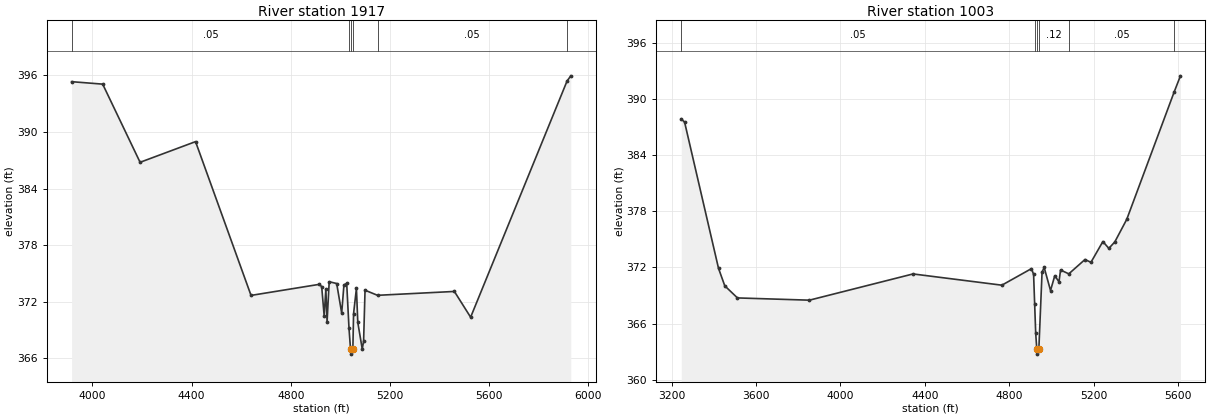
Type RM Length L Ch R = 1,1917,914,914,914
BEGIN DESCRIPTION:
Briar Creek 2.0
END DESCRIPTION:
XS GIS Cut Line= 3
      2758055.12      6803262.66      2756926.00      6803111.00
      2756125.97      6803461.01
#Sta/Elev= 30
  3916.7  395.32  4041.9  395.06  4192.7  386.78  4416.3  388.97  4640.0  372.68
  4914.7  373.85  4924.8  373.62  4934.9  370.50  4941.6  373.36  4946.6  369.89
  4955.1  374.13  4985.3  373.94  5005.5  370.81  5014.5  373.78  5025.7  373.96
  5035.0  369.18  5041.2  366.96  5042.6  366.46  5050.5  366.96  5053.4  370.75
  5064.9  373.43  5070.4  369.82  5088.3  367.01  5093.8  367.80  5099.6  373.23
  5150.0  372.69  5459.8  373.10  5525.3  370.37  5914.1  395.39  5929.2  395.94
#Mann=6,-1,0
  3916.7    0.05       0  5035.0    0.12       0  5041.2    0.04       0
  5050.5    0.12       0  5150.0    0.05       0  5914.1    0.12       0
Bank Sta=5041.2,5050.5
Exp/Cntr=0.3,0.1

Type RM Length L Ch R = 1,1003,0,0,0
BEGIN DESCRIPTION:
Briar Creek 1.0
END DESCRIPTION:
XS GIS Cut Line= 3
      2758321.65      6802888.15      2756526.00      6802761.00
      2756126.02      6803160.98
#Sta/Elev= 30
  3245.4  387.86  3261.1  387.52  3421.9  371.91  3451.6  370.04  3511.7  368.75
  3852.6  368.51  4343.8  371.31  4764.8  370.11  4905.2  371.88  4915.2  371.26
  4920.3  368.05  4925.2  364.96  4930.5  363.25  4931.9  362.75  4940.0  363.25
  4955.3  371.51  4965.3  372.00  4995.4  369.54  5015.5  371.12  5035.5  370.47
  5043.0  371.73  5082.0  371.32  5158.7  372.85  5187.0  372.55  5243.5  374.77
  5271.8  374.04  5300.1  374.73  5356.7  377.14  5581.1  390.72  5611.2  392.46
#Mann=6,-1,0
  3245.4    0.05       0  4920.3    0.12       0  4930.5    0.07       0
  4940.0    0.12       0  5082.0    0.05       0  5581.1    0.12       0
Bank Sta=4930.5,4940
Exp/Cntr=0.3,0.1

Chan Stop Cuts=-1