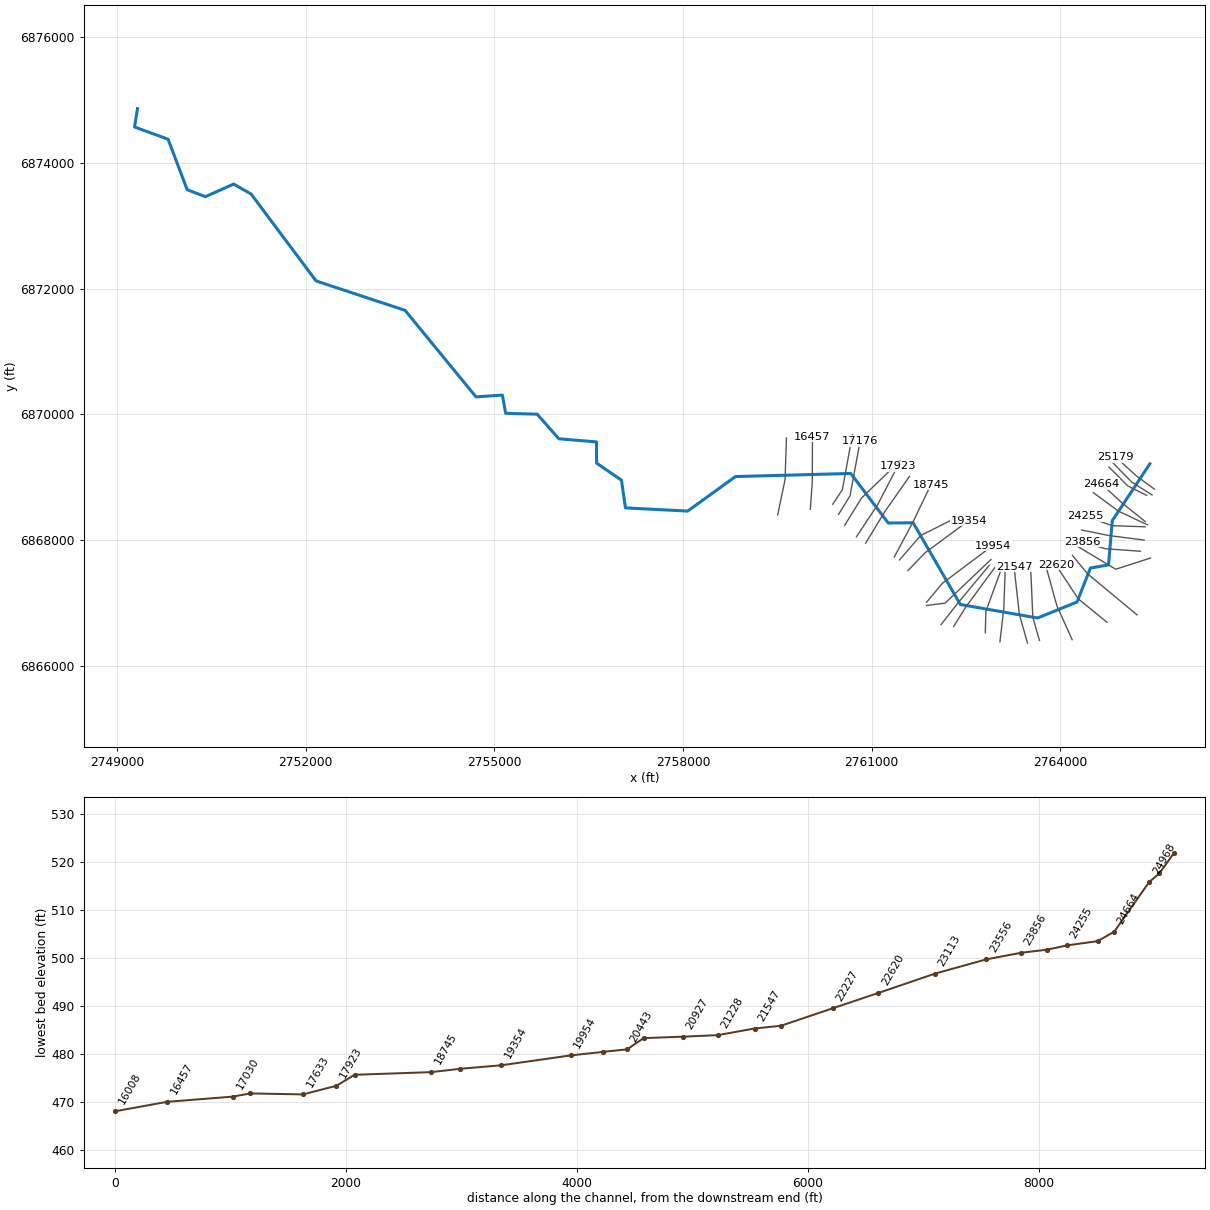
--- Buck Branch.prj (project) ---

Proj Title=Buck Branch Base Level Engineering
Current Plan=p01
Default Exp/Contr=0.3,0.1
English Units
Geom File=g01
Flow File=f01
Plan File=p01
Y Axis Title=Elevation
X Axis Title(PF)=Main Channel Distance
X Axis Title(XS)=Station
BEGIN DESCRIPTION:
Buck Branch
END DESCRIPTION:
DSS Export Rating Curves= 0
DSS Export Rating Curve Sorted= 0
DSS Export Volume Flow Curves= 0
DXF OffsetX= 0
DXF OffsetY= 0
DXF ScaleX= 1
DXF ScaleY= 10

--- Buck Branch.p01 (plan) ---

Plan Title=Multiple Run
Short Identifier=Multiple
Geom File=g01
Flow File=f01
Subcritical Flow
K Sum by GR= 0
Std Step Tol= 0.01
Critical Tol= 0.01
Num of Std Step Trials= 20
Max Error Tol= 0.3
Flow Tol Ratio= 0.001
Split Flow NTrial= 30
Split Flow Tol= 0.02
Split Flow Ratio= 0.02
Log Output Level= 0
Friction Slope Method= 1
Unsteady Friction Slope Method= 2
Unsteady Bridges Friction Slope Method= 1
Parabolic Critical Depth
Global Vel Dist=  1 , 1 , 1
Global Log Level= 0
CheckData=True
Encroach Param= -1, 0, 0, 0
BEGIN DESCRIPTION:
Multiple Run
END DESCRIPTION:

--- Buck Branch.f01 (steady flow) ---

Flow Title=Multiple
Number of Profiles=7
Profile Names=10-year,25-year,50-year,1pct_min,100-year,1pct_plu,500-year
River Rch & RM= Buck Branch,Reach-1,25179
     531     718     871     527    1051    2097    1531
River Rch & RM= Buck Branch,Reach-1,23113
     900    1251    1547     951    1898    3788    2863
River Rch & RM= Buck Branch,Reach-1,21228
    1019    1412    1741    1065    2125    4241    3177
River Rch & RM= Buck Branch,Reach-1,13904
    1736    2468    3097    1926    3842    7666    5930
River Rch & RM= Buck Branch,Reach-1,11121
    1736    2466    3092    1921    3832    7646    5904
River Rch & RM= Buck Branch,Reach-1,10643
    1755    2480    3099    1918    3826    7634    5849
River Rch & RM= Buck Branch,Reach-1,6558
    1828    2580    3219    1988    3967    7916    6044
Boundary for River Rch & Prof#=Buck Branch,Reach-1,1
Up Type=0
Dn Type=3
Dn Slope=0.005
Boundary for River Rch & Prof#=Buck Branch,Reach-1,2
Up Type=0
Dn Type=3
Dn Slope=0.005
Boundary for River Rch & Prof#=Buck Branch,Reach-1,3
Up Type=0
Dn Type=3
Dn Slope=0.005
Boundary for River Rch & Prof#=Buck Branch,Reach-1,4
Up Type=0
Dn Type=3
Dn Slope=0.005
Boundary for River Rch & Prof#=Buck Branch,Reach-1,5
Up Type=0
Dn Type=3
Dn Slope=0.005
Boundary for River Rch & Prof#=Buck Branch,Reach-1,6
Up Type=0
Dn Type=3
Dn Slope=0.005
Boundary for River Rch & Prof#=Buck Branch,Reach-1,7
Up Type=0
Dn Type=3
Dn Slope=0.005

--- Buck Branch.g01 (geometry) ---

Geom Title=Existing Conditions
Program Version=4.10

River Reach=Buck Branch     ,Reach-1
Reach XY= 30
        2765426.        6869211.      2764829.55      6868309.53
      2764769.02      6867604.86      2764481.61      6867555.41
      2764268.02      6867014.22       2763641.2      6866760.51
      2762412.73      6866974.62      2761662.54      6868274.63
      2761265.97      6868271.01      2760670.03      6869058.83
      2758836.55      6869009.92        2758076.        6868461.
      2757086.97      6868511.51      2757023.04      6868952.68
      2756627.51      6869223.15        2756626.        6869561.
        2756026.        6869611.      2755682.66      6870002.01
      2755181.58      6870015.76      2755128.78      6870305.64
      2754709.33       6870277.2      2753582.06      6871652.86
      2752165.84      6872121.36      2751132.52      6873503.32
      2750855.97      6873661.44       2750405.8      6873461.02
        2750116.      6873571.65      2749812.74      6874374.79
      2749279.07       6874569.3        2749326.        6874861.

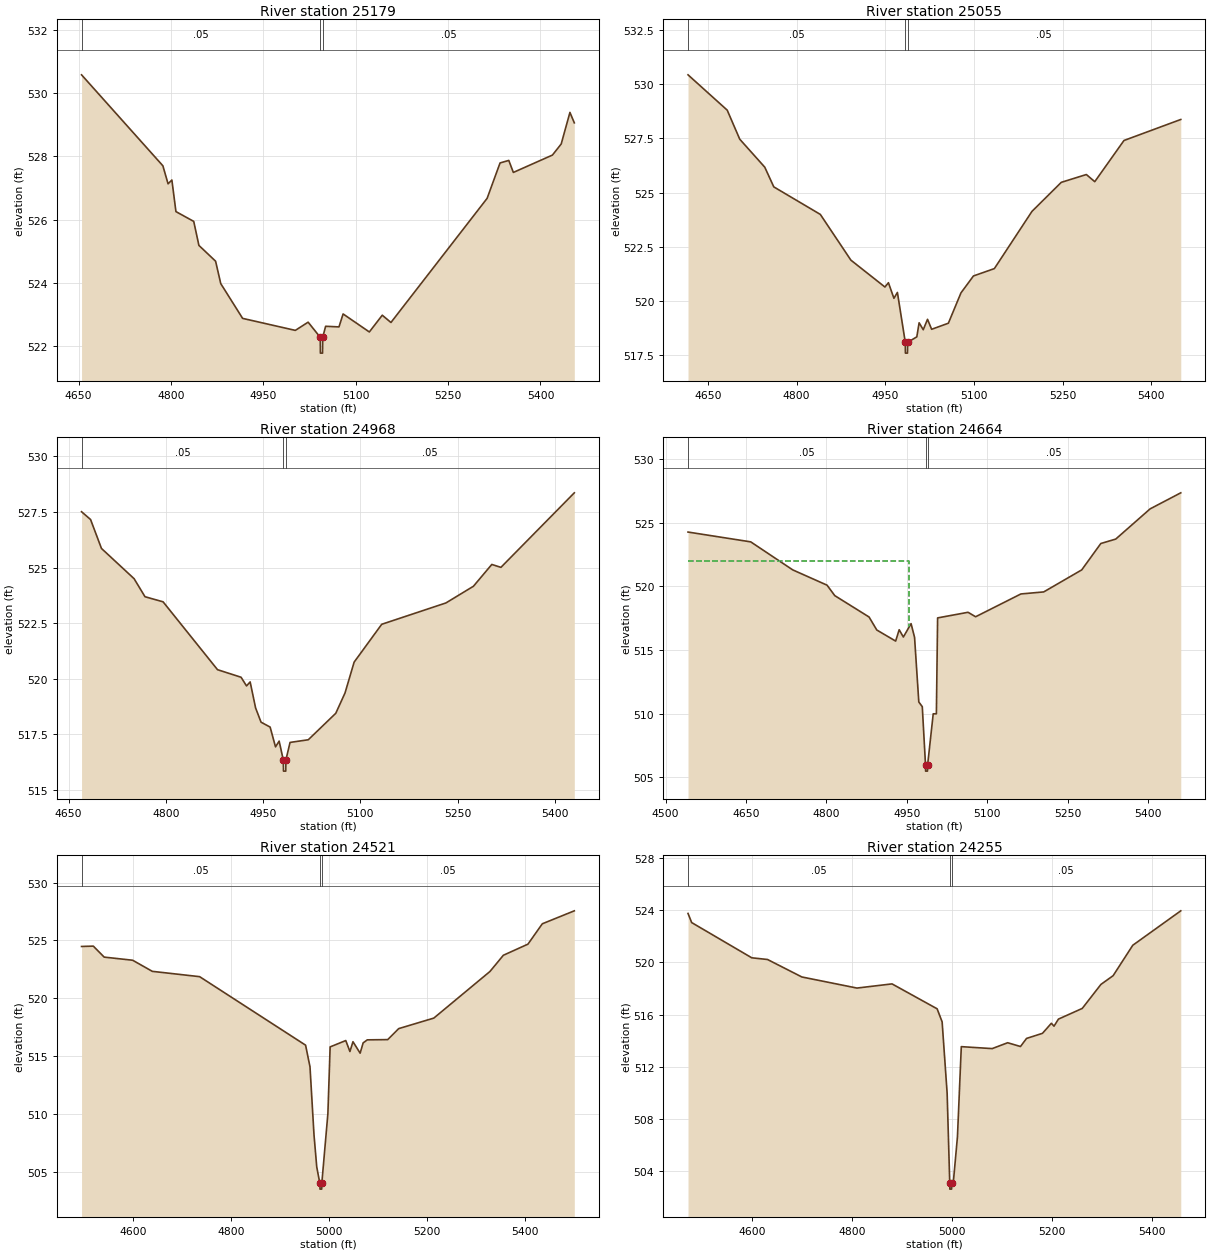
Type RM Length L Ch R = 1 ,25179   ,124,124,124
BEGIN DESCRIPTION:
Buck Branch 3232
END DESCRIPTION:
XS GIS Cut Line= 3
      2765499.34      6868809.09      2765216.76      6869017.76
      2764883.49      6869318.69
#Sta/Elev= 30
  4654.7  530.58  4786.8   527.7  4795.2  527.13  4801.4  527.25    4808  526.25
  4836.9  525.94  4845.3  525.18  4872.4  524.68  4880.8  523.97  4916.3  522.87
  5001.9  522.49  5022.7  522.75  5042.4  522.27  5042.6  521.77  5046.1  521.77
  5046.4  522.27  5051.1  522.62  5072.8   522.6  5079.5  523.01  5122.1  522.44
  5143.1  522.97  5157.2  522.74  5313.4  526.67  5334.4  527.79  5348.6  527.87
    5356  527.49  5419.5  528.04  5433.7  528.39  5447.9  529.39    5455  529.06
#Mann= 3 ,-1 , 0
  4654.7     .05       0  5042.4     .04       0  5046.4     .05       0
Bank Sta=5042.4,5046.4
XS Rating Curve= 0 ,0
Exp/Cntr=0.3,0.1

Type RM Length L Ch R = 1 ,25055   ,87,87,87
BEGIN DESCRIPTION:
Buck Branch 3231
END DESCRIPTION:
XS GIS Cut Line= 3
      2765461.97      6868717.25      2765135.38      6868924.84
      2764823.64      6869244.52
#Sta/Elev= 30
  4616.5  530.43  4682.8   528.8    4704  527.46  4746.3  526.17  4761.6  525.26
  4840.3  523.99    4892  521.88  4949.6  520.64  4955.5  520.84  4964.8  520.12
  4970.7  520.39    4984  518.09  4984.2  517.59  4987.7  517.59    4988  518.09
  5003.5  518.34  5007.4  518.99  5014.4  518.67  5021.6  519.15  5028.6  518.69
  5056.9  518.97  5078.2  520.37  5099.3  521.15  5134.7  521.49  5198.3  524.13
  5247.9  525.47  5290.3  525.83  5304.5   525.5  5353.9   527.4    5450  528.37
#Mann= 3 ,-1 , 0
  4616.5     .05       0    4984     .04       0    4988     .05       0
Bank Sta=4984,4988
XS Rating Curve= 0 ,0
Exp/Cntr=0.3,0.1

Type RM Length L Ch R = 1 ,24968   ,304,304,304
BEGIN DESCRIPTION:
Buck Branch 38
END DESCRIPTION:
XS GIS Cut Line= 3
      2765375.97      6868711.01        2765076.        6868861.
      2764776.03      6869160.97
#Sta/Elev= 30
  4670.1  527.51    4684  527.16  4700.8  525.86  4751.1   524.5  4767.9  523.69
  4795.8  523.46  4879.7  520.41    4916  520.07  4924.4  519.68    4930  519.86
  4938.4  518.69  4946.8  518.05  4960.8  517.83  4969.1  516.94  4974.7   517.2
  4981.1  516.35  4981.4  515.85  4984.9  515.85  4985.1  516.35  4991.5  517.14
  5019.6  517.26    5062  518.45  5076.2  519.36  5090.3  520.75  5132.8  522.45
  5231.8  523.41  5274.2  524.16  5302.5  525.14  5316.6  525.01  5429.7  528.36
#Mann= 3 ,-1 , 0
  4670.1     .05       0  4981.1     .04       0  4985.1     .05       0
Bank Sta=4981.1,4985.1
XS Rating Curve= 0 ,0
Exp/Cntr=0.3,0.1

Type RM Length L Ch R = 1 ,24664   ,143,143,143
BEGIN DESCRIPTION:
Buck Branch 3227
END DESCRIPTION:
XS GIS Cut Line= 3
      2765353.44      6868293.79      2764991.84       6868583.6
       2764656.2      6868892.26
#Sta/Elev= 30
  4541.9  524.25  4658.9  523.48  4737.3  521.28  4801.3  520.08  4815.7  519.26
  4879.7  517.58  4894.1  516.56  4929.3  515.69  4935.9  516.58  4943.7  516.01
  4958.1  517.06  4964.6  515.98  4972.5  510.91    4979  510.54    4985  505.98
  4985.2  505.48  4988.7  505.48    4989  505.98  4999.4  509.98  5005.3  509.98
  5007.6  517.51  5064.4  517.95  5078.5   517.6    5163  519.39  5205.6  519.55
  5276.5  521.28  5312.1  523.35    5340   523.7  5404.1  526.07  5461.3  527.33
#Mann= 3 ,-1 , 0
  4541.9     .05       0    4985     .04       0    4989     .05       0
#XS Ineff= 2 , 0
       0    4955     522               0
Permanent Ineff=
       F       F
Bank Sta=4985,4989
XS Rating Curve= 0 ,0
Exp/Cntr=0.3,0.1

Type RM Length L Ch R = 1 ,24521   ,266,266,266
BEGIN DESCRIPTION:
Buck Branch 3229
END DESCRIPTION:
XS GIS Cut Line= 3
      2765387.75      6868242.65      2764926.63      6868459.91
      2764527.44      6868754.06
#Sta/Elev= 30
  4495.2  524.48  4519.2  524.51  4541.4  523.56  4599.5  523.29  4639.6  522.33
  4736.2  521.87  4952.4  515.95  4961.4  514.08  4969.6  508.18  4975.2  505.42
  4981.5  504.01  4981.8  503.51  4985.3  503.51  4985.5  504.01  4997.9  510.03
  5002.5   515.8  5034.4  516.35  5042.9   515.4  5049.1  516.25  5063.7  515.26
  5069.9  516.15  5078.3  516.41    5120  516.43  5142.4  517.38  5214.1  518.29
  5328.7  522.32    5356  523.72  5406.2  524.68  5435.5  526.44  5500.8  527.56
#Mann= 3 ,-1 , 0
  4495.2     .05       0  4981.5     .04       0  4985.5     .05       0
Bank Sta=4981.5,4985.5
XS Rating Curve= 0 ,0
Exp/Cntr=0.3,0.1

Type RM Length L Ch R = 1 ,24255   ,173,173,173
BEGIN DESCRIPTION:
Buck Branch 3228
END DESCRIPTION:
XS GIS Cut Line= 3
      2765353.27      6868210.63      2764826.62      6868228.85
      2764395.66      6868381.93
#Sta/Elev= 30
  4472.5  523.75  4479.8  523.05  4599.8  520.35  4631.3  520.22  4699.9  518.88
    4810  518.03    4880  518.35  4970.1  516.44  4980.1  515.44  4990.1  509.97
  4995.3  503.12  4995.5  502.62    4999  502.62  4999.3  503.12  5002.4  503.12
  5010.7  506.63  5018.4  513.54  5080.1  513.39    5111  513.84  5136.6  513.55
  5148.7  514.17  5180.5  514.56  5198.3  515.33  5203.6  515.11  5212.4  515.65
    5260  516.47  5297.3  518.31  5321.7  518.98  5360.9  521.31  5456.8  523.95
#Mann= 3 ,-1 , 0
  4472.5     .05       0  4995.3     .04       0  4999.3     .05       0
Bank Sta=4995.3,4999.3
XS Rating Curve= 0 ,0
Exp/Cntr=0.3,0.1

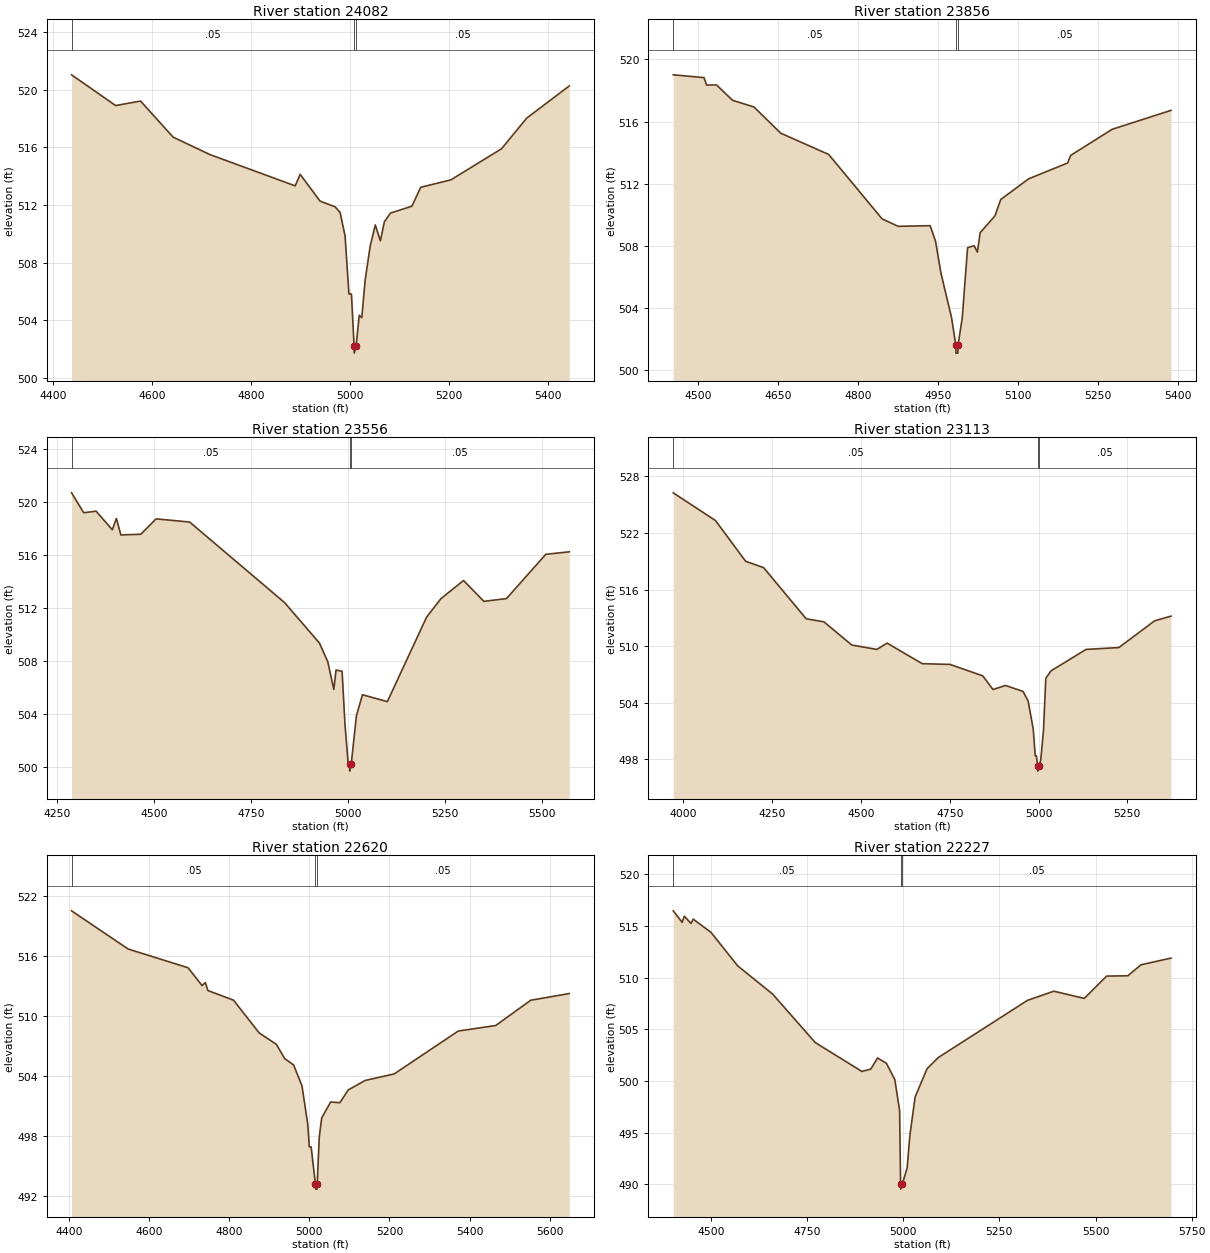
Type RM Length L Ch R = 1 ,24082   ,226,226,226
BEGIN DESCRIPTION:
Buck Branch 3230
END DESCRIPTION:
XS GIS Cut Line= 3
      2765334.32      6867999.74      2764775.44      6868071.73
      2764341.69      6868159.78
#Sta/Elev= 30
  4436.6  521.03  4525.7   518.9  4576.1  519.21  4641.9  516.71  4716.3   515.5
  4888.6  513.33  4898.7  514.13    4939  512.27  4969.3  511.88  4979.4  511.49
  4989.5  509.85  4997.3  505.83  5002.4  505.83  5007.7  502.23    5008  501.73
  5011.7  502.23  5018.2  504.36  5023.3  504.19  5030.1   506.8  5040.3  509.16
  5050.6  510.62  5060.8  509.52  5068.9  510.83  5081.2  511.44  5124.6  511.92
  5142.4  513.23  5203.6  513.75  5305.7   515.9  5356.7  518.03  5442.7  520.26
#Mann= 3 ,-1 , 0
  4436.6     .05       0  5007.7     .04       0  5011.7     .05       0
Bank Sta=5007.7,5011.7
XS Rating Curve= 0 ,0
Exp/Cntr=0.3,0.1

Type RM Length L Ch R = 1 ,23856   ,300,300,300
BEGIN DESCRIPTION:
Buck Branch 3226
END DESCRIPTION:
XS GIS Cut Line= 3
      2765276.96      6867821.69      2764716.73      6867862.46
      2764360.32      6867970.36
#Sta/Elev= 30
  4452.8  519.01  4510.5  518.83  4515.5  518.35    4534  518.36  4564.1  517.37
  4604.2  516.94  4654.6  515.25  4744.5  513.88  4844.8  509.73  4874.9  509.25
    4935  509.29  4945.1  508.29  4955.1  506.25  4975.1  503.37  4983.2  501.58
  4983.4  501.08  4986.9  501.08  4987.2  501.58  4995.2  503.35  5005.2  507.87
  5017.5     508  5023.6  507.59  5028.8  508.84  5056.5  509.92  5067.5  510.98
  5119.8  512.31  5192.9  513.33  5198.7  513.82  5276.5   515.5  5386.9  516.72
#Mann= 3 ,-1 , 0
  4452.8     .05       0  4983.2     .04       0  4987.2     .05       0
Bank Sta=4983.2,4987.2
XS Rating Curve= 0 ,0
Exp/Cntr=0.3,0.1

Type RM Length L Ch R = 1 ,23556   ,443,443,443
BEGIN DESCRIPTION:
Buck Branch 3225
END DESCRIPTION:
XS GIS Cut Line= 4
      2765435.97      6867713.89      2764931.37      6867550.82
      2764883.28      6867536.65      2764279.36      6867897.42
#Sta/Elev= 30
  4286.5  520.67    4318  519.17  4349.7  519.29  4391.6  517.89  4402.1  518.74
  4413.8   517.5  4465.1  517.55  4504.6  518.71  4591.2  518.47  4835.9  512.41
    4926  509.36  4947.4  507.96    4963  505.87  4968.8  507.33  4984.4  507.23
  4991.9   503.2  4999.9  500.37  5003.8  500.22    5004  499.72  5007.8  500.22
  5021.3  503.89  5036.9  505.47  5101.1  504.95  5202.3  511.31  5239.2   512.7
  5297.6  514.07  5350.2   512.5  5408.5  512.71  5509.7  516.04  5570.4  516.23
#Mann= 3 ,-1 , 0
  4286.5     .05       0  5003.8     .04       0  5007.8     .05       0
Bank Sta=5003.8,5007.8
XS Rating Curve= 0 ,0
Exp/Cntr=0.3,0.1

Type RM Length L Ch R = 1 ,23113   ,493,493,493
BEGIN DESCRIPTION:
Buck Branch 3224
END DESCRIPTION:
XS GIS Cut Line= 3
       2765222.6      6866809.86       2764435.9       6867463.3
      2764195.35      6867756.07
#Sta/Elev= 30
  3971.4  526.26  4090.5  523.32  4175.1  519.01  4225.9  518.33  4345.7  512.91
    4396  512.58    4474  510.13  4544.9  509.66  4573.6  510.33  4672.5  508.15
  4750.7  508.07  4843.1  506.86  4871.8  505.41  4906.9  505.84  4956.4  505.21
  4970.7   504.2  4985.1  501.23  4990.8  498.39  4994.1  498.39  4997.5  497.26
  4997.9  496.76  5001.9  497.26  5006.2  497.91    5014  501.05  5020.5  506.59
  5034.9  507.38  5133.9  509.66  5226.4  509.86  5326.9  512.69    5373  513.19
#Mann= 3 ,-1 , 0
  3971.4     .05       0  4997.5     .04       0  5001.9     .05       0
Bank Sta=4997.5,5001.9
XS Rating Curve= 0 ,0
Exp/Cntr=0.3,0.1

Type RM Length L Ch R = 1 ,22620   ,393,393,393
BEGIN DESCRIPTION:
Buck Branch 3223
END DESCRIPTION:
XS GIS Cut Line= 3
      2764745.53      6866691.59      2764284.89      6867067.33
      2763930.26      6867609.37
#Sta/Elev= 30
  4406.5  520.48  4547.8  516.67  4697.3   514.8  4732.4  513.02  4740.3  513.33
  4746.8  512.53  4810.7  511.57  4874.6  508.31  4917.7  507.16  4938.5  505.74
  4960.8   505.1  4981.6  503.02    4996  499.19  4999.9  496.93  5004.5  496.93
  5015.1  493.22  5015.5  492.72  5019.1  492.72  5019.5  493.22  5024.8  497.95
  5030.8  499.82  5053.1  501.41  5076.1  501.34  5097.2  502.62  5139.3  503.56
  5211.7  504.21  5371.6  508.49  5465.1  509.04  5552.5  511.56  5648.7  512.23
#Mann= 3 ,-1 , 0
  4406.5     .05       0  5015.1     .04       0  5019.5     .05       0
Bank Sta=5015.1,5019.5
XS Rating Curve= 0 ,0
Exp/Cntr=0.3,0.1

Type RM Length L Ch R = 1 ,22227   ,451,451,451
BEGIN DESCRIPTION:
Buck Branch 3221
END DESCRIPTION:
XS GIS Cut Line= 3
      2764190.82      6866415.56      2763946.98      6866957.75
      2763760.57      6867632.16
#Sta/Elev= 30
    4402  516.46  4425.2  515.35  4430.7  515.94  4448.3  515.24  4453.8  515.66
  4500.1  514.38  4569.6  511.14  4660.2  508.42  4771.3  503.72  4892.5  500.93
  4915.7  501.16  4933.4  502.23  4956.2  501.72  4978.1  500.15  4990.6  497.16
  4993.2  490.05  4993.7  489.55  4997.9  490.05  5010.2  491.61  5017.2  494.71
    5031  498.47  5062.1   501.2    5091  502.27    5323   507.8  5391.6  508.69
  5470.7  507.99    5529  510.15    5584  510.18  5618.3  511.24  5696.2  511.89
#Mann= 3 ,-1 , 0
    4402     .05       0  4993.2     .04       0  4997.9     .05       0
Bank Sta=4993.2,4997.9
XS Rating Curve= 0 ,0
Exp/Cntr=0.3,0.1

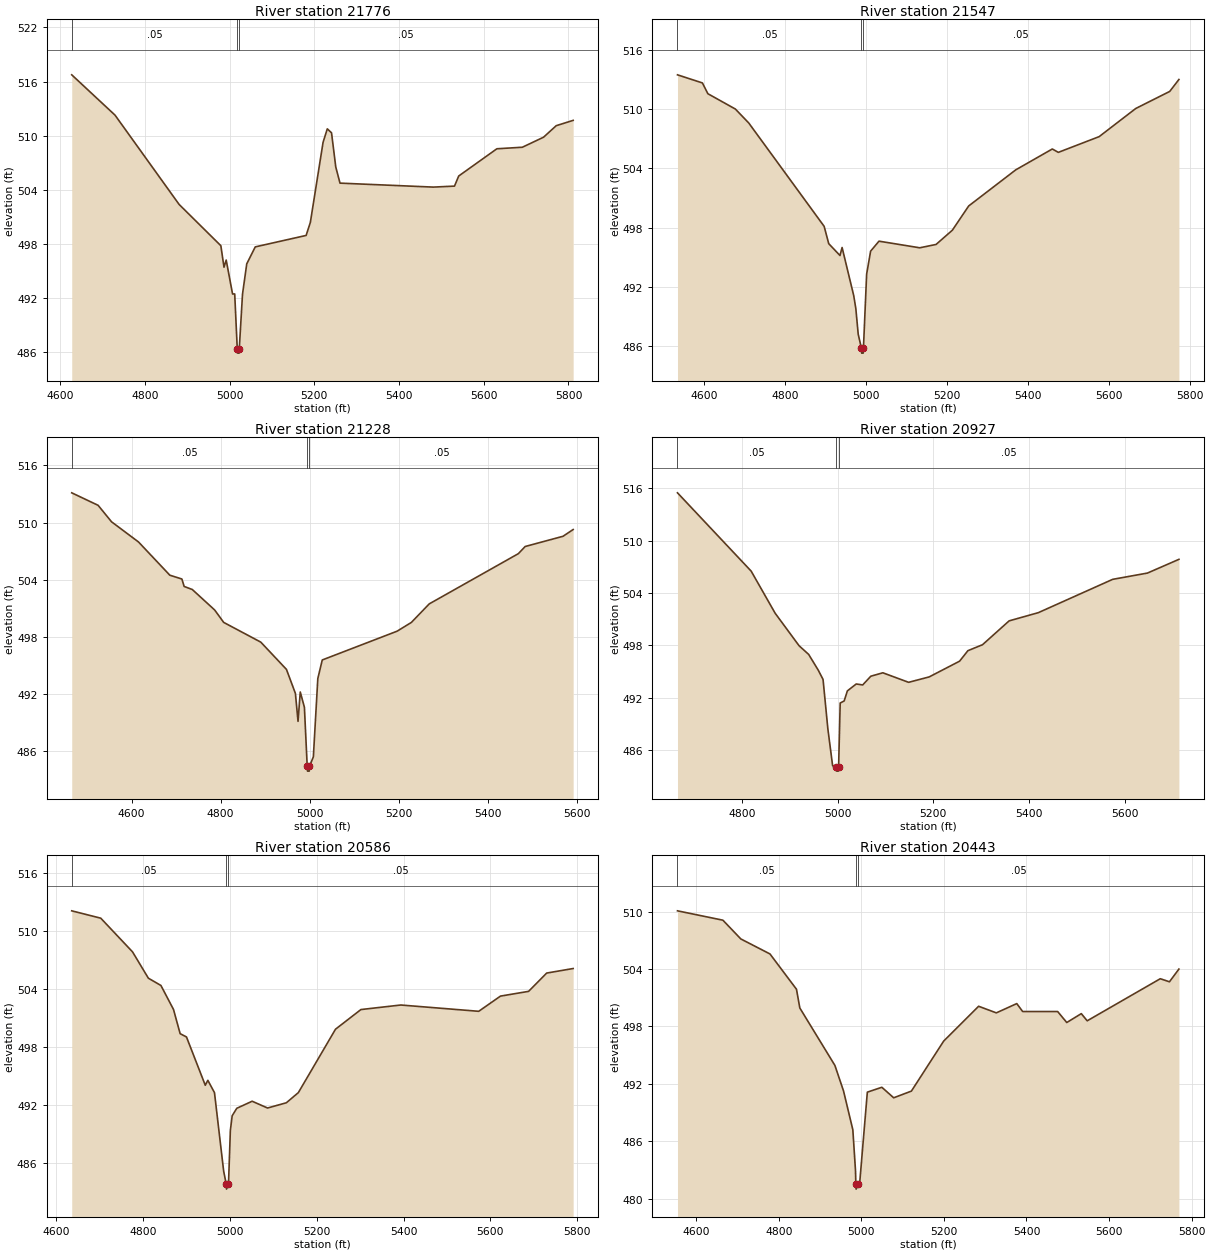
Type RM Length L Ch R = 1 ,21776   ,229,229,229
BEGIN DESCRIPTION:
Buck Branch 3222
END DESCRIPTION:
XS GIS Cut Line= 3
      2763671.47      6866402.79      2763565.58      6866769.11
      2763530.48      6867570.93
#Sta/Elev= 30
  4627.2  516.75  4729.4  512.28  4880.7  502.38  4979.3   497.8  4986.7  495.42
  4991.9  496.21  5006.9  492.45    5012  492.45    5018  486.39  5018.6  485.89
  5022.3  485.89  5022.8  486.39  5030.4  492.42  5040.4  495.79  5060.5  497.67
  5180.6  498.94  5190.6  500.39  5220.6  509.26  5230.6  510.76  5240.6  510.32
  5250.6  506.53  5260.6  504.74  5480.9   504.3  5530.9  504.41  5540.9  505.53
    5631  508.55  5691.1  508.72  5741.1  509.83  5771.1  511.11  5811.1   511.7
#Mann= 3 ,-1 , 0
  4627.2     .05       0    5018     .04       0  5022.8     .05       0
Bank Sta=5018,5022.8
XS Rating Curve= 0 ,0
Exp/Cntr=0.3,0.1

Type RM Length L Ch R = 1 ,21547   ,319,319,319
BEGIN DESCRIPTION:
Buck Branch 3220
END DESCRIPTION:
XS GIS Cut Line= 4
      2763480.88      6866361.82      2763350.72      6866820.99
      2763268.87      6867554.14      2763266.18      6867576.71
#Sta/Elev= 30
  4534.1  513.46  4595.6  512.64  4609.1  511.55    4677     510    4710  508.59
  4896.1  498.14  4907.4  496.39  4935.2  495.19  4940.4     496  4969.1  491.14
  4974.3  489.83  4980.2  487.23  4988.1  485.82  4988.7  485.32  4992.5  485.32
  4993.1  485.82    5001  493.31  5010.8  495.63  5031.5  496.64  5132.1  495.97
  5172.4  496.31  5212.6  497.75  5252.9   500.2    5369  503.85  5459.3  505.96
  5474.2  505.62  5574.9  507.21  5665.4  510.06  5749.1  511.78  5771.8  512.99
#Mann= 3 ,-1 , 0
  4534.1     .05       0  4988.1     .04       0  4993.1     .05       0
Bank Sta=4988.1,4993.1
XS Rating Curve= 0 ,0
Exp/Cntr=0.3,0.1

Type RM Length L Ch R = 1 ,21228   ,301,301,301
BEGIN DESCRIPTION:
Buck Branch 3219
END DESCRIPTION:
XS GIS Cut Line= 3
       2763042.2      6866382.23      2763104.03      6866913.65
      2763124.78      6867503.88
#Sta/Elev= 30
  4465.7  513.13  4524.9  511.82  4555.1  510.09  4615.5  507.98  4685.9  504.49
    4713  504.09    4718  503.31  4736.3  502.99  4786.6  500.84  4806.8  499.54
  4890.1  497.47  4947.7  494.61  4967.8  492.09  4973.7  489.16  4978.7  492.24
    4988  490.64  4994.3  484.44    4995  483.94  4998.8  483.94  4999.4  484.44
  5008.1  485.44  5018.1  493.65  5028.1   495.6  5196.2  498.62  5228.2  499.54
  5268.2  501.48  5468.3  506.75  5483.6   507.5  5568.4  508.57  5591.3  509.28
#Mann= 3 ,-1 , 0
  4465.7     .05       0  4994.3     .04       0  4999.4     .05       0
Bank Sta=4994.3,4999.4
XS Rating Curve= 0 ,0
Exp/Cntr=0.3,0.1

Type RM Length L Ch R = 1 ,20927   ,341,341,341
BEGIN DESCRIPTION:
Buck Branch 3218
END DESCRIPTION:
XS GIS Cut Line= 3
      2762809.64      6866527.15       2762818.9      6866867.69
      2763062.47      6867530.91
#Sta/Elev= 30
  4665.8  515.46  4819.7   506.5  4869.7  501.69  4919.7  497.97  4939.8  496.97
  4959.8  495.17  4969.8  494.11  4979.8  488.48  4989.8  484.23  4997.2  484.12
  4997.9  483.62  5001.7  483.62  5002.3  484.12  5005.6  491.41  5013.9  491.65
  5020.6   492.8  5039.1  493.59  5052.6  493.48  5069.6  494.48  5094.7  494.87
  5148.5  493.78  5191.5   494.4    5255   496.2  5272.3   497.4  5302.8  498.08
  5358.4  500.81  5419.4  501.75  5574.6  505.56  5647.3  506.28    5713  507.85
#Mann= 3 ,-1 , 0
  4665.8     .05       0  4997.2     .04       0  5002.3     .05       0
Bank Sta=4997.2,5002.3
XS Rating Curve= 0 ,0
Exp/Cntr=0.3,0.1

Type RM Length L Ch R = 1 ,20586   ,143,143,143
BEGIN DESCRIPTION:
Buck Branch 3216
END DESCRIPTION:
XS GIS Cut Line= 3
      2762307.35      6866626.53      2762504.38       6866943.1
      2762968.97      6867572.78
#Sta/Elev= 30
  4635.5  512.07  4702.4  511.31  4775.6  507.83  4812.1  505.11    4841  504.36
    4870  501.88  4885.3  499.38  4899.9  499.04  4943.2  494.05  4949.1  494.56
  4964.4  493.29  4985.6  485.17  4991.6  483.82  4992.2  483.32  4996.7  483.82
    5001  489.38  5005.2   490.9  5015.8  491.67  5051.2   492.4  5086.7   491.7
    5130  492.24  5157.7  493.29  5243.3  499.84  5301.8  501.87  5393.7  502.34
  5573.3  501.69  5623.4  503.26  5688.2  503.75  5729.9  505.64  5790.9  506.11
#Mann= 3 ,-1 , 0
  4635.5     .05       0  4991.6     .04       0  4996.7     .05       0
Bank Sta=4991.6,4996.7
XS Rating Curve= 0 ,0
Exp/Cntr=0.3,0.1

Type RM Length L Ch R = 1 ,20443   ,208,208,208
BEGIN DESCRIPTION:
Buck Branch 3215
END DESCRIPTION:
XS GIS Cut Line= 3
      2762106.31      6866655.43      2762375.28      6866999.69
      2762872.41      6867597.52
#Sta/Elev= 30
  4554.8  510.08  4664.8   509.1  4708.2  507.14  4778.8  505.57    4843  501.88
  4851.1  499.92  4936.1  493.91  4956.9  491.25  4979.5  487.18  4985.9  482.93
  4986.8  481.48  4987.4  480.98  4991.9  481.48  4995.8  481.48  5014.6  491.12
  5049.7  491.63  5078.4  490.53  5121.3  491.23  5199.5  496.46  5284.1   500.1
    5327  499.41  5376.5  500.38  5390.8  499.55  5475.5  499.55  5497.6   498.4
  5532.8  499.33  5547.1  498.58  5724.1  502.98  5746.3  502.66  5769.2  503.99
#Mann= 3 ,-1 , 0
  4554.8     .05       0  4986.8     .04       0  4991.9     .05       0
Bank Sta=4986.8,4991.9
XS Rating Curve= 0 ,0
Exp/Cntr=0.3,0.1

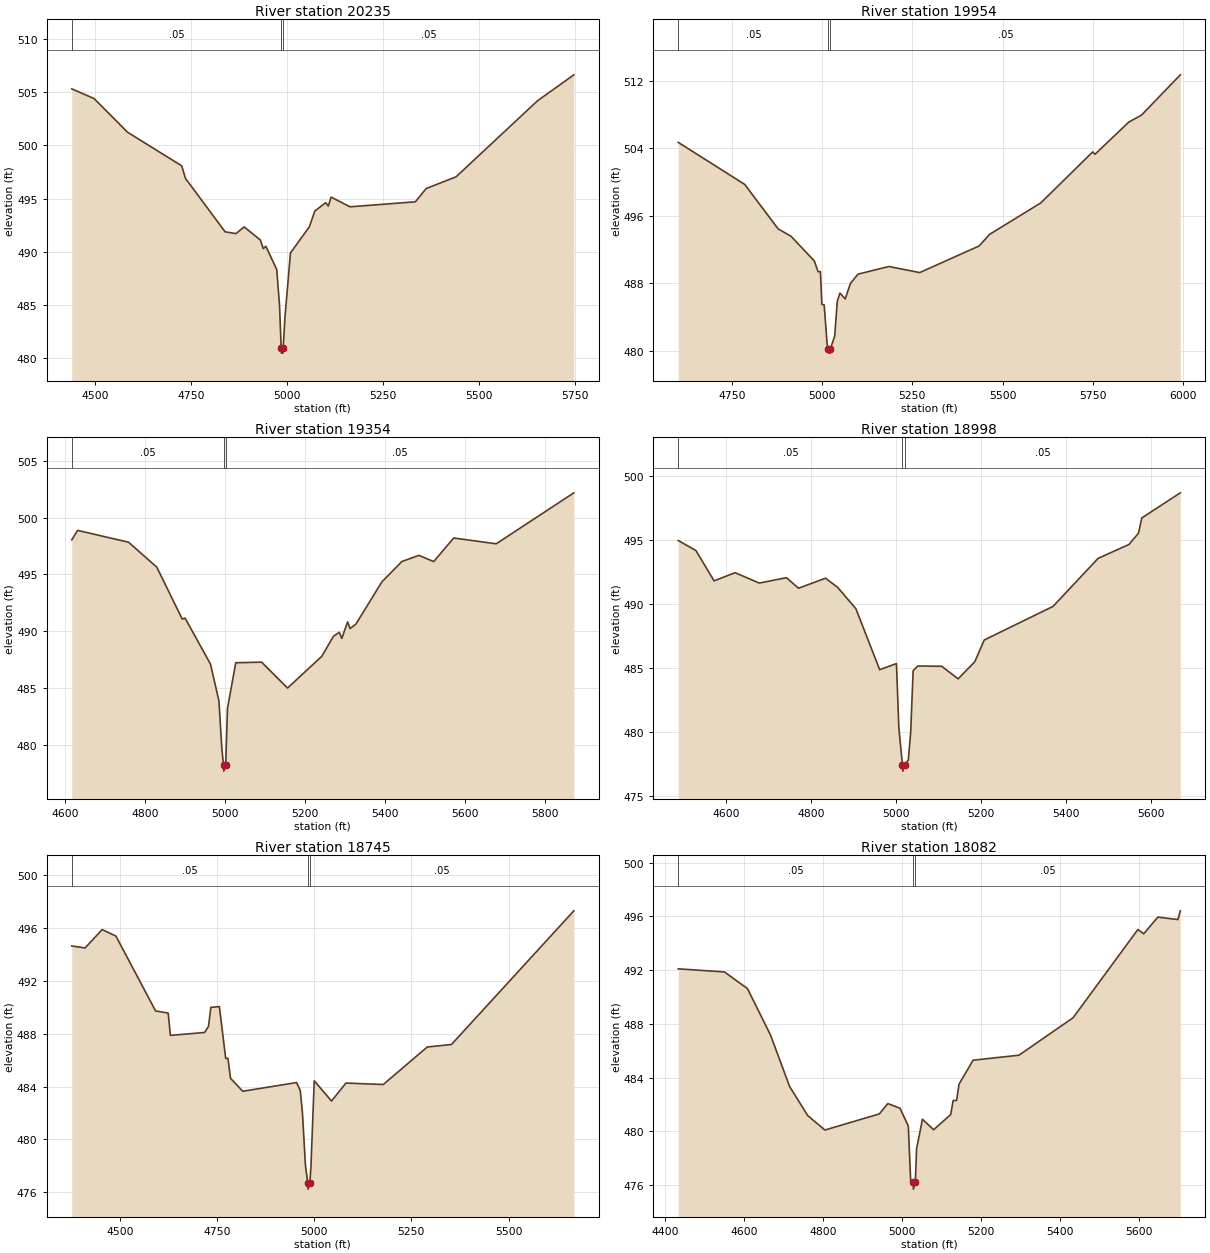
Type RM Length L Ch R = 1 ,20235   ,281,281,281
BEGIN DESCRIPTION:
Buck Branch 3217
END DESCRIPTION:
XS GIS Cut Line= 3
      2761872.02      6866958.77      2762170.56      6866997.27
      2762900.03      6867690.58
#Sta/Elev= 30
  4438.9  505.33  4496.9  504.42  4584.1  501.25  4725.1  498.09  4735.1   496.9
  4838.4  491.87  4866.7  491.71  4887.8  492.34  4930.2   491.1  4937.5  490.29
  4944.4  490.51  4972.7  488.32  4979.9  484.95  4984.2  480.96  4984.9  480.46
  4988.7  480.46  4989.4  480.96  4994.1  483.85  5008.3  489.88  5057.6  492.35
  5071.8  493.83  5100.1  494.62    5107   494.3  5114.2  495.14  5163.6  494.23
  5333.5   494.7  5361.8  495.95  5439.5  497.05  5651.8  504.21  5746.3  506.65
#Mann= 3 ,-1 , 0
  4438.9     .05       0  4984.2     .04       0  4989.4     .05       0
Bank Sta=4984.2,4989.4
XS Rating Curve= 0 ,0
Exp/Cntr=0.3,0.1

Type RM Length L Ch R = 1 ,19954   ,600,600,600
BEGIN DESCRIPTION:
Buck Branch 37
END DESCRIPTION:
XS GIS Cut Line= 3
      2761875.98      6867010.98        2762126.        6867311.
      2762925.97      6867910.97
#Sta/Elev= 30
  4601.6  504.68  4785.8   499.7  4878.2  494.44    4914  493.56  4978.5  490.64
  4988.9  489.37  4995.3  489.37  4999.4  485.49  5005.7  485.44    5014  480.78
  5017.7  480.22  5018.4  479.72  5022.2  479.72  5022.9  480.22  5034.9  481.73
  5042.1  485.85  5049.4  486.83    5064  486.14  5078.6  487.98  5099.4  489.07
  5184.9  489.98  5270.3  489.26  5434.9  492.41    5464  493.79  5605.7  497.51
  5749.4  503.55  5755.7  503.27  5849.4  507.08  5884.9  507.92  5992.1  512.68
#Mann= 3 ,-1 , 0
  4601.6     .05       0  5017.7     .04       0  5022.9     .05       0
Bank Sta=5017.7,5022.9
XS Rating Curve= 0 ,0
Exp/Cntr=0.3,0.1

Type RM Length L Ch R = 1 ,19354   ,356,356,356
BEGIN DESCRIPTION:
Buck Branch 3214
END DESCRIPTION:
XS GIS Cut Line= 3
      2761580.97      6867515.36       2761851.5      6867797.34
      2762547.94      6868310.59
#Sta/Elev= 30
  4616.3  498.05  4630.9  498.88  4758.3  497.84    4829  495.64  4892.6  491.07
  4899.8  491.15  4963.3   487.1  4984.4  483.86  4991.6  479.71  4995.9  478.17
  4996.6  477.67  5001.3  478.17  5005.8  483.19  5026.5  487.22  5091.2  487.27
    5156  484.99  5241.6  487.78  5270.9  489.55  5285.5   489.9  5291.8  489.37
  5306.4  490.82  5312.6  490.23  5327.2  490.63    5392  494.34  5442.1  496.14
  5484.7  496.68  5521.6  496.13  5571.7  498.21  5678.1   497.7  5872.2  502.19
#Mann= 3 ,-1 , 0
  4616.3     .05       0  4995.9     .04       0  5001.3     .05       0
Bank Sta=4995.9,5001.3
XS Rating Curve= 0 ,0
Exp/Cntr=0.3,0.1

Type RM Length L Ch R = 1 ,18998   ,253,253,253
BEGIN DESCRIPTION:
Buck Branch 3213
END DESCRIPTION:
XS GIS Cut Line= 3
      2761444.77       6867683.5      2761780.95      6868070.97
      2762376.86      6868371.31
#Sta/Elev= 30
  4488.2  494.93  4529.7  494.15  4572.5  491.78  4621.8  492.42  4678.8  491.61
  4742.5  492.03    4771  491.21  4834.6  491.99  4863.1  491.27  4905.8  489.61
  4961.8  484.85  5001.2  485.33  5006.8  480.33  5015.3  477.44  5016.1  476.94
  5020.7  477.44  5029.1  477.81  5034.7  479.99  5040.4  484.77  5051.4  485.14
  5107.6  485.12  5146.2  484.14  5185.3  485.47  5207.6  487.17  5369.3  489.79
  5475.3  493.54  5547.8  494.62  5570.1   495.5    5578  496.69  5668.5  498.65
#Mann= 3 ,-1 , 0
  4488.2     .05       0  5015.3     .04       0  5020.7     .05       0
Bank Sta=5015.3,5020.7
XS Rating Curve= 0 ,0
Exp/Cntr=0.3,0.1

Type RM Length L Ch R = 1 ,18745   ,663,663,663
BEGIN DESCRIPTION:
Buck Branch 3212
END DESCRIPTION:
XS GIS Cut Line= 3
       2761362.1      6867730.78      2761658.98      6868286.19
      2761945.99      6868882.87
#Sta/Elev= 30
  4376.2  494.65  4410.5   494.5  4454.4  495.89  4489.8   495.4  4591.9  489.73
  4624.3  489.57    4630  487.88  4717.8   488.1    4728  488.56  4734.1     490
    4756  490.06  4772.3  486.13    4778  486.15  4784.7  484.63  4816.2  483.65
  4954.7  484.31  4964.1  483.71  4969.8  482.01  4977.4  478.06  4983.3  476.74
  4984.1  476.24  4988.9  476.74  4991.7     478  5000.1  484.44  5044.6  482.91
  5081.6  484.27  5177.8  484.16  5290.9     487  5353.2  487.19  5668.1  497.31
#Mann= 3 ,-1 , 0
  4376.2     .05       0  4983.3     .04       0  4988.9     .05       0
Bank Sta=4983.3,4988.9
XS Rating Curve= 0 ,0
Exp/Cntr=0.3,0.1

Type RM Length L Ch R = 1 ,18082   ,159,159,159
BEGIN DESCRIPTION:
Buck Branch 3211
END DESCRIPTION:
XS GIS Cut Line= 3
      2760907.55      6867950.86      2761205.94      6868443.95
      2761603.76      6869012.19
#Sta/Elev= 30
  4434.1  492.09    4551  491.86  4609.2  490.62  4667.4  487.17  4715.9  483.33
  4761.5  481.17  4805.1  480.09  4942.8  481.29  4964.2  482.06  4995.2  481.71
  5016.1  480.38  5022.2   476.2  5028.1  476.19    5029  475.69  5033.8  476.19
    5037   478.7  5051.9  480.89  5080.1  480.11  5123.3  481.24  5129.5  482.29
  5138.2  482.29  5144.3   483.5    5180  485.29    5296  485.66  5432.9  488.45
  5596.8  495.02  5611.6   494.7  5647.3  495.94  5697.9  495.76  5704.1  496.41
#Mann= 3 ,-1 , 0
  4434.1     .05       0  5028.1     .04       0  5033.8     .05       0
Bank Sta=5028.1,5033.8
XS Rating Curve= 0 ,0
Exp/Cntr=0.3,0.1

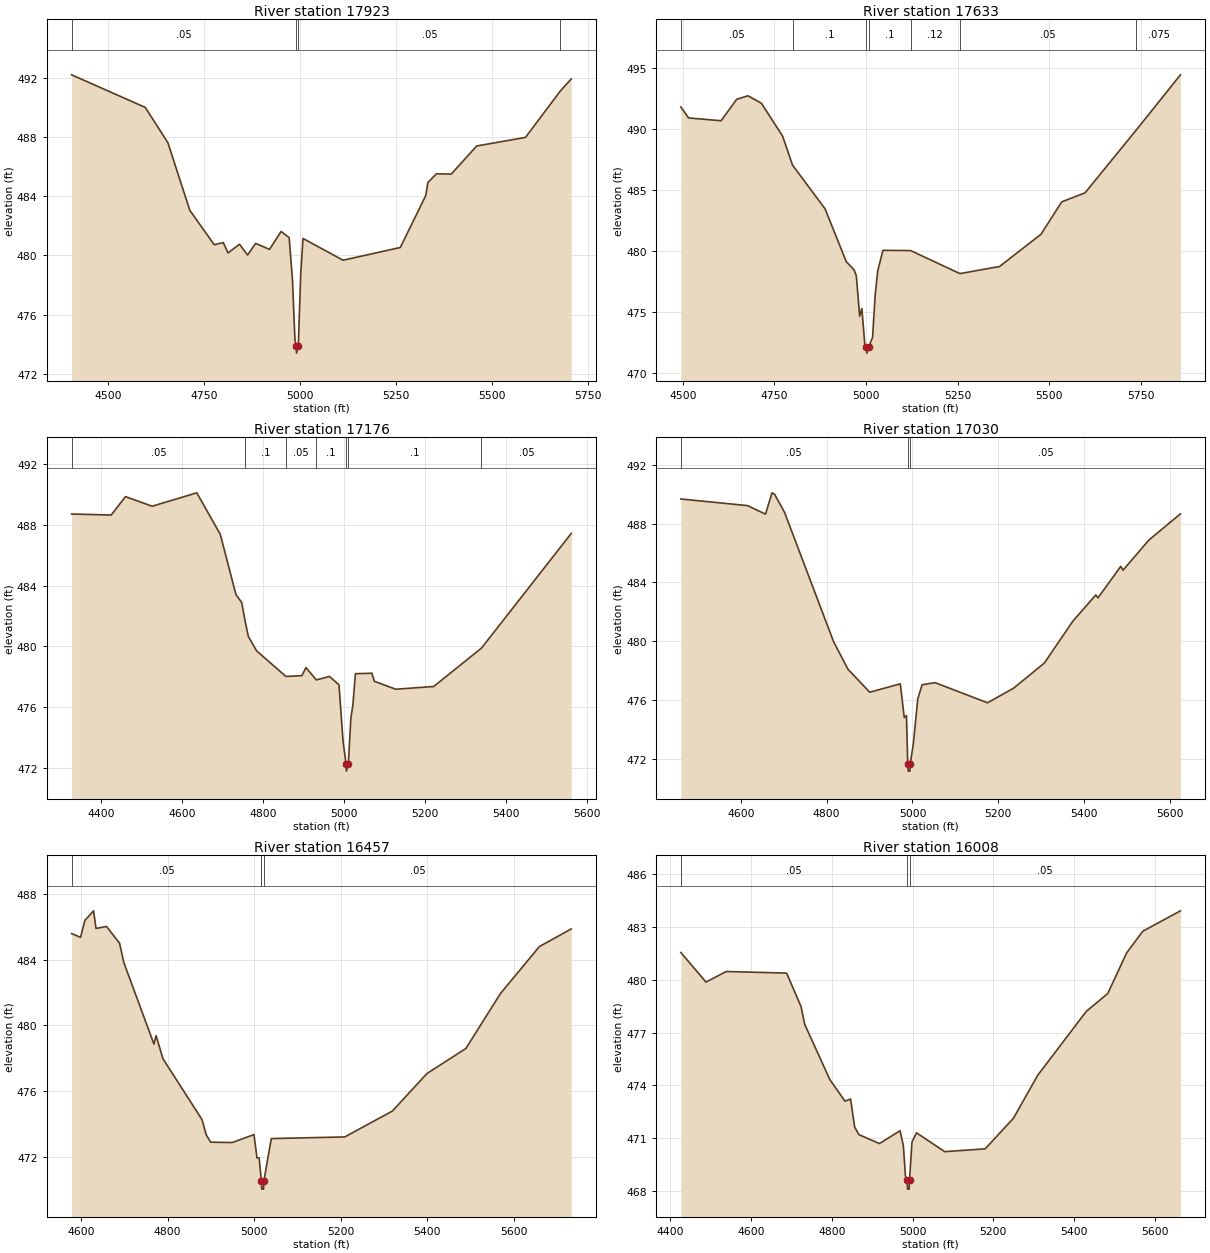
Type RM Length L Ch R = 1 ,17923   ,290,290,290
BEGIN DESCRIPTION:
Buck Branch 3209
END DESCRIPTION:
XS GIS Cut Line= 3
      2760759.78      6868051.17      2761095.26      6868558.14
      2761414.85      6869173.82
#Sta/Elev= 30
  4404.9   492.2  4596.6     490  4655.7  487.61  4712.8  483.04  4776.4  480.72
  4800.1  480.86  4812.4  480.16  4842.2  480.75  4863.2  480.02  4884.3  480.81
  4920.4   480.4  4950.5  481.61  4971.6   481.2  4980.3  478.32  4986.6  474.32
  4989.8  473.89  4990.7  473.39  4995.5  473.89  5001.7  478.72  5007.7  481.14
    5112  479.67  5261.2  480.53  5327.5  484.04  5333.1  484.92  5355.3  485.51
  5393.9  485.49  5460.2  487.39  5587.3  487.97  5678.2  491.11  5706.5  491.92
#Mann= 4 ,-1 , 0
  4404.9     .05       0  4989.8     .05       0  4995.5     .05       0
  5678.2    .075       0
Bank Sta=4989.8,4995.5
XS Rating Curve= 0 ,0
Exp/Cntr=0.3,0.1

Type RM Length L Ch R = 1 ,17633   ,457,457,457
BEGIN DESCRIPTION:
Buck Branch 3210
END DESCRIPTION:
XS GIS Cut Line= 3
      2760572.58      6868233.66      2760841.54      6868668.83
      2761454.58      6869260.54
#Sta/Elev= 30
  4494.5  491.81  4515.6  490.91  4604.3  490.68  4646.9  492.44  4677.6  492.73
  4714.3  492.12  4772.2  489.42  4799.3  487.04  4888.1  483.45    4946  479.11
  4967.2  478.44  4973.4  477.96  4982.6  474.63  4988.5  475.26  4996.9  472.22
  5001.1   472.1    5002   471.6  5006.8   472.1  5017.8  472.89    5025  476.42
    5032  478.36  5046.1  480.04  5121.7  480.02  5256.2  478.13  5364.3  478.71
  5477.5  481.36  5534.1  484.02  5597.7  484.76  5738.1  489.94  5858.1  494.45
#Mann= 7 ,-1 , 0
  4494.5     .05       0  4799.3      .1       0  5001.1     .07       0
  5006.8      .1       0  5121.7     .12       0  5256.2     .05       0
  5738.1    .075       0
Bank Sta=5001.1,5006.8
XS Rating Curve= 0 ,0
Exp/Cntr=0.3,0.1

Type RM Length L Ch R = 1 ,17176   ,146,146,146
BEGIN DESCRIPTION:
Buck Branch 3208
END DESCRIPTION:
XS GIS Cut Line= 3
      2760475.82      6868407.91      2760657.95       6868703.3
      2760819.37      6869574.85
#Sta/Elev= 30
  4327.2   488.7  4424.8  488.63  4460.1  489.84  4526.1  489.21  4636.2  490.09
  4694.1  487.37  4732.9   483.4    4747  482.89  4756.2  481.57  4763.4  480.66
  4783.8  479.71  4856.2  478.03  4895.6  478.08  4905.7  478.61  4931.3   477.8
  4963.6  478.03  4987.2  477.48  4997.3  473.76  5004.6  472.31  5005.5  471.81
  5010.4  472.31  5016.5  475.27  5021.6  476.17  5027.8  478.21  5068.5  478.24
  5074.5  477.71  5127.4  477.19  5221.1  477.37    5339  479.89  5560.6  487.42
#Mann= 7 ,-1 , 0
  4327.2     .05       0  4756.2      .1       0  4856.2     .05       0
  4931.3      .1       0  5004.6     .07       0  5010.4      .1       0
    5339     .05       0
Bank Sta=5004.6,5010.4
XS Rating Curve= 0 ,0
Exp/Cntr=0.3,0.1

Type RM Length L Ch R = 1 ,17030   ,573,573,573
BEGIN DESCRIPTION:
Buck Branch 3207
END DESCRIPTION:
XS GIS Cut Line= 3
      2760383.78      6868569.28      2760536.65      6868801.65
      2760695.88      6869673.18
#Sta/Elev= 30
  4460.3  489.67  4615.5  489.22  4657.6  488.64  4672.7  490.09  4678.7  489.99
  4701.8  488.77  4816.2  479.96  4849.6  478.09  4900.4  476.52  4971.6  477.09
  4980.9   474.8    4986  474.93    4989  471.65  4989.9  471.15  4993.9  471.15
  4994.8  471.65  5002.1  473.03  5012.3  476.05  5022.4  477.03  5052.9  477.17
  5174.9   475.8  5235.9   476.8  5307.1   478.5  5373.9  481.36  5427.2  483.14
  5432.2  482.94  5485.5  485.09  5490.6  484.82    5551  486.88  5624.4  488.66
#Mann= 3 ,-1 , 0
  4460.3     .05       0    4989     .05       0  4994.8     .05       0
Bank Sta=4989,4994.8
XS Rating Curve= 0 ,0
Exp/Cntr=0.3,0.1

Type RM Length L Ch R = 1 ,16457   ,449,449,449
BEGIN DESCRIPTION:
Buck Branch 3206
END DESCRIPTION:
XS GIS Cut Line= 3
      2760026.84      6868490.47      2760058.17      6868919.84
      2760060.27      6869644.63
#Sta/Elev= 30
  4578.2  485.58  4598.8  485.35  4608.8  486.38  4628.9  486.96  4634.6  485.89
  4658.9  486.01    4689  484.99    4699  483.81  4768.5  478.87  4773.5  479.38
  4789.3  477.98  4879.5  474.29  4889.6  473.35  4899.6  472.91  4949.7  472.89
  4999.8  473.37  5006.8  471.96  5011.8  471.96  5016.9  470.56  5017.9  470.06
  5021.9  470.06  5022.8  470.56  5039.9  473.13  5209.9  473.23  5319.9   474.8
  5399.9  477.08  5489.9   478.6  5569.9  481.94  5659.9  484.79  5733.5  485.86
#Mann= 3 ,-1 , 0
  4578.2     .05       0  5016.9     .04       0  5022.8     .05       0
Bank Sta=5016.9,5022.8
XS Rating Curve= 0 ,0
Exp/Cntr=0.3,0.1

Type RM Length L Ch R = 1 ,16008   ,433,433,433
BEGIN DESCRIPTION:
Buck Branch 3205
END DESCRIPTION:
XS GIS Cut Line= 3
      2759507.22      6868399.79      2759625.55      6868963.82
      2759646.85      6869624.17
#Sta/Elev= 30
  4426.2  481.55  4488.5  479.87  4538.4  480.47  4688.1  480.38  4723.8  478.48
  4732.8  477.47  4795.3  474.32  4832.6   473.1  4846.4  473.22  4856.6  471.63
  4866.8   471.2  4917.9  470.69    4969  471.42  4977.2  470.56  4982.3  468.84
  4986.4   468.6  4987.4   468.1  4991.4   468.1  4992.4   468.6  4998.5  470.78
  5009.7   471.3  5079.7  470.23  5179.8  470.39  5249.8  472.13  5309.8  474.57
  5429.9   478.2  5483.3  479.22    5530  481.53    5570  482.76  5663.2  483.92
#Mann= 3 ,-1 , 0
  4426.2     .05       0  4986.4     .04       0  4992.4     .05       0
Bank Sta=4986.4,4992.4
XS Rating Curve= 0 ,0
Exp/Cntr=0.3,0.1