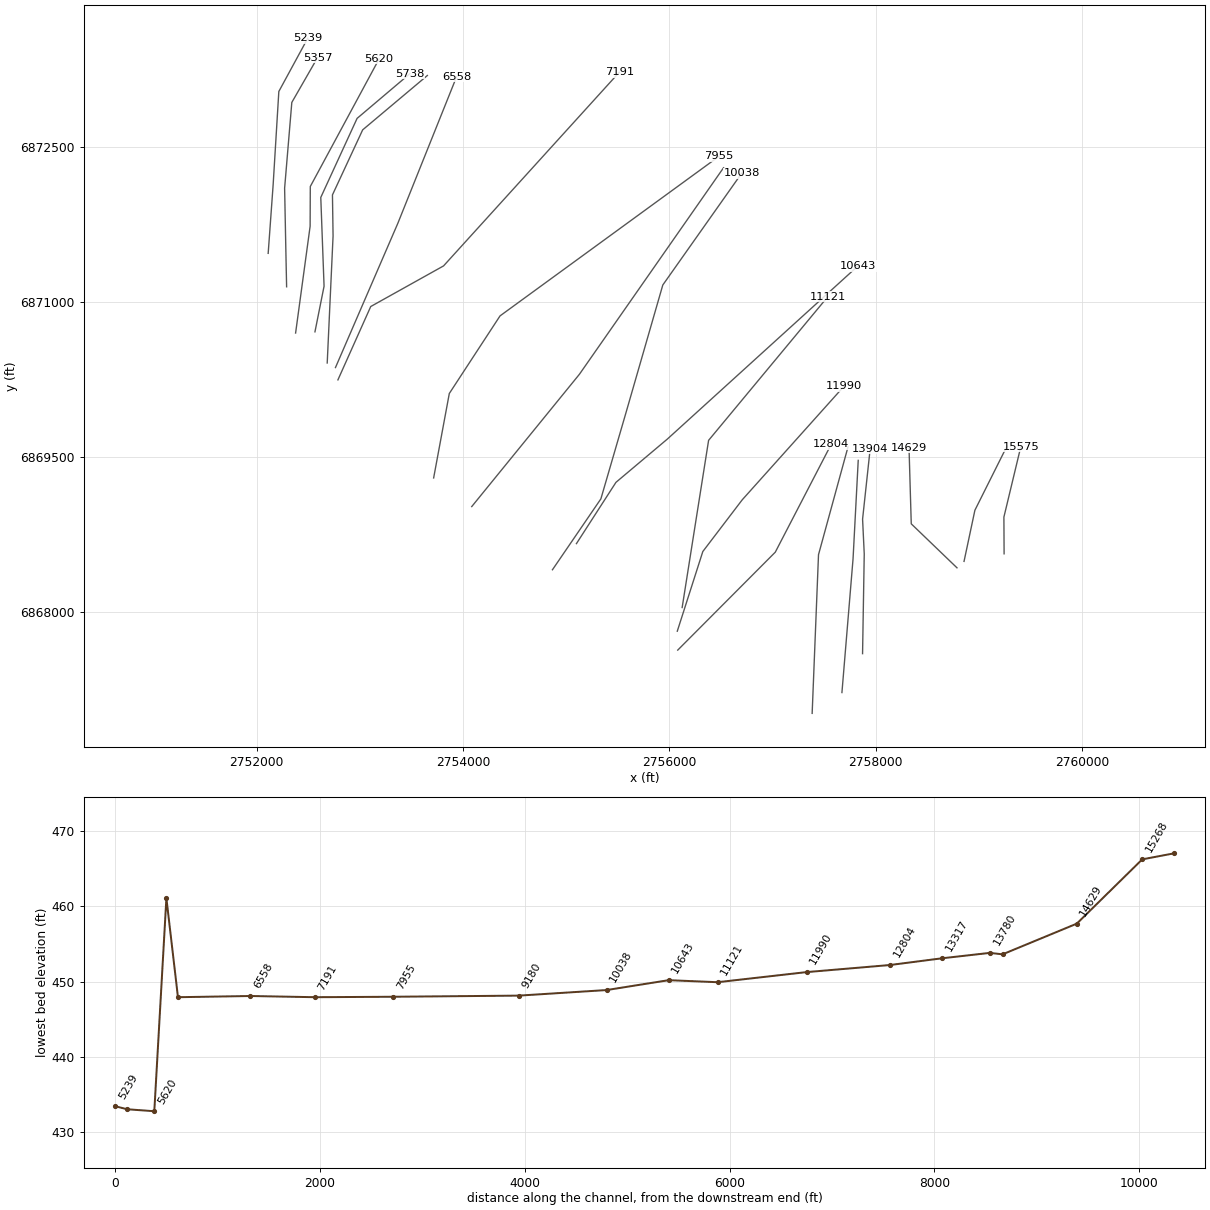
HEC-RAS study Buck Branch.prj: Buck Branch Base Level Engineering

--- Buck Branch.g01 (geometry) --- (continued)

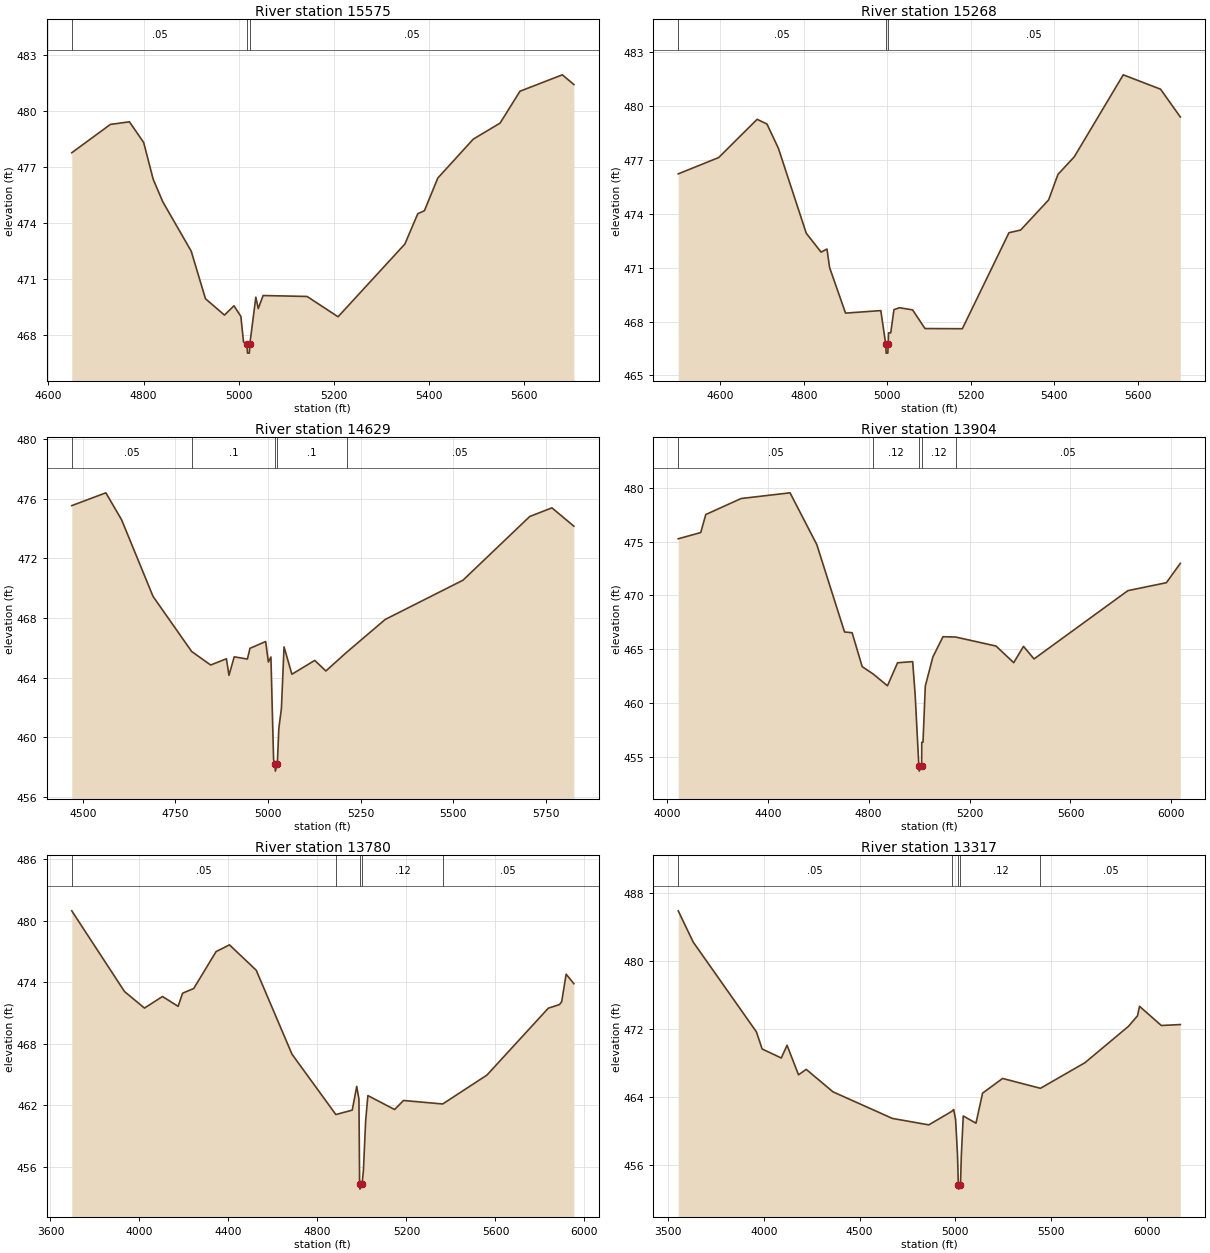
Type RM Length L Ch R = 1 ,15575   ,307,307,307
BEGIN DESCRIPTION:
Buck Branch 3204
END DESCRIPTION:
XS GIS Cut Line= 3
      2759245.71      6868559.73      2759243.62      6868915.52
      2759407.32      6869596.73
#Sta/Elev= 30
    4649  477.78  4730.3   479.3  4770.3  479.44  4800.3  478.33  4820.3  476.36
  4840.3  475.16  4900.3   472.5  4930.3  469.95  4970.3  469.07  4990.3  469.57
  5004.8     469  5010.4  467.62  5017.7  467.53  5018.7  467.03  5022.7  467.03
  5023.7  467.53  5036.3  470.03  5041.4  469.42  5051.6  470.12  5144.1  470.07
  5209.3  468.98  5349.8  472.88  5377.1  474.51    5391  474.67  5419.1  476.42
  5493.8  478.51  5550.2  479.37  5592.1  481.08  5681.2  481.96  5705.4  481.44
#Mann= 3 ,-1 , 0
    4649     .05       0  5017.7     .04       0  5023.7     .05       0
Bank Sta=5017.7,5023.7
XS Rating Curve= 0 ,0
Exp/Cntr=0.3,0.1

Type RM Length L Ch R = 1 ,15268   ,639,639,639
BEGIN DESCRIPTION:
Buck Branch 3140
END DESCRIPTION:
XS GIS Cut Line= 3
      2758857.24      6868486.17      2758962.55      6868982.26
      2759273.95      6869604.66
#Sta/Elev= 30
  4499.1  476.23    4596  477.14  4688.1  479.27  4711.7  479.01  4739.2  477.65
  4805.9  472.92  4841.4  471.87  4855.5  472.04  4861.8  471.01    4900  468.47
  4984.5  468.61  4996.3  466.74  4997.3  466.24  5001.3  466.24  5002.3  466.74
    5003  467.37  5008.3  467.37    5016  468.66    5029  468.77  5060.7  468.65
  5090.4  467.61  5179.9   467.6  5291.6  472.95  5319.6   473.1  5386.7  474.78
    5409   476.2  5448.1  477.18  5565.5  481.75  5654.9  480.95  5702.2   479.4
#Mann= 3 ,-1 , 0
  4499.1     .05       0  4996.3     .04       0  5002.3     .05       0
Bank Sta=4996.3,5002.3
XS Rating Curve= 0 ,0
Exp/Cntr=0.3,0.1

Type RM Length L Ch R = 1 ,14629   ,725,725,725
BEGIN DESCRIPTION:
Buck Branch 3139
END DESCRIPTION:
XS GIS Cut Line= 3
      2758789.01      6868423.86       2758345.6      6868850.31
      2758323.89       6869590.1
#Sta/Elev= 30
  4470.3  475.55  4562.3  476.41  4604.8   474.6  4689.7  469.45  4793.9  465.75
  4845.3  464.84  4887.8  465.26  4894.7  464.15  4908.8  465.39  4944.4  465.24
  4951.3  465.96  4993.7  466.42    5001  465.04  5007.9  465.38  5015.1  458.48
  5018.8  458.21  5019.9  457.71  5025.2  458.21  5029.3  460.59  5036.2  461.92
  5043.3  466.06  5064.5  464.22  5126.2  465.15  5156.2  464.44  5212.1  465.69
  5316.3   467.9  5526.4  470.54  5706.5  474.82  5766.5   475.4  5825.6  474.17
#Mann= 5 ,-1 , 0
  4470.3     .05       0  4793.9      .1       0  5018.8     .07       0
  5025.2      .1       0  5212.1     .05       0
Bank Sta=5018.8,5025.2
XS Rating Curve= 0 ,0
Exp/Cntr=0.3,0.1

Type RM Length L Ch R = 1 ,13904   ,124,124,124
BEGIN DESCRIPTION:
Buck Branch 3137
END DESCRIPTION:
XS GIS Cut Line= 4
      2757873.54      6867591.85      2757889.84      6868557.76
      2757873.74      6868895.73      2757947.29      6869577.48
#Sta/Elev= 30
  4045.2  475.28  4134.4  475.86  4154.4  477.54  4294.4  479.03  4488.4  479.56
  4594.4  474.74  4704.4   466.6  4734.4  466.53  4774.4  463.37  4817.7  462.69
  4874.5  461.59  4914.5  463.73  4974.5  463.84  4984.5  460.69  4998.9  454.14
  5000.4  453.64    5010  454.14  5010.4  456.33  5015.4  456.33  5024.5  461.56
  5054.5  464.27  5094.6  466.16  5144.5  466.13  5304.8  465.29    5375  463.74
  5413.7  465.26  5455.5  464.09  5827.6  470.45  5980.1  471.19  6035.3  472.99
#Mann= 5 ,-1 , 0
  4045.2     .05       0  4817.7     .12       0  4998.9     .07       0
    5010     .12       0  5144.5     .05       0
Bank Sta=4998.9,5010
XS Rating Curve= 0 ,0
Exp/Cntr=0.3,0.1

Type RM Length L Ch R = 1 ,13780   ,463,463,463
BEGIN DESCRIPTION:
Buck Branch 3138
END DESCRIPTION:
XS GIS Cut Line= 3
      2757673.55      6867214.65      2757781.39      6868511.84
      2757831.54      6869465.56
#Sta/Elev= 30
  3695.7  480.99  3932.9  473.11  4022.6   471.5  4103.4  472.63  4173.7  471.67
  4193.8  472.95  4243.9  473.41  4344.3  477.01  4404.5  477.67  4524.9  475.19
  4685.5     467  4882.7  461.11  4956.4  461.54  4976.5  463.86  4986.5  462.62
  4989.5  454.33    4991  453.83  5000.6  454.33  5006.5  455.63  5016.5  460.44
  5026.6  462.96  5146.7   461.6  5186.8  462.48    5363  462.14  5561.8  464.96
  5837.7  471.49  5887.8  471.84  5897.8  472.13  5917.8  474.81  5952.4  473.88
#Mann= 5 ,-1 , 0
  3695.7     .05       0  4882.7     .12       0  4989.5     .07       0
  5000.6     .12       0    5363     .05       0
Bank Sta=4989.5,5000.6
XS Rating Curve= 0 ,0
Exp/Cntr=0.3,0.1

Type RM Length L Ch R = 1 ,13317   ,513,513,513
BEGIN DESCRIPTION:
Buck Branch 3136
END DESCRIPTION:
XS GIS Cut Line= 3
      2757384.89      6867012.87      2757446.49       6868551.3
      2757732.72      6869596.66
#Sta/Elev= 30
  3552.2  485.91  3630.4  482.23  3960.7  471.65  3990.7  469.63  4090.8  468.57
  4120.8  470.07  4180.8  466.59  4220.9  467.23    4361  464.58  4671.2  461.45
  4861.4  460.69  4980.7  462.27  4991.5   462.5  5001.5  461.33  5011.5  457.16
  5015.9  453.62  5017.5  453.12  5027.1  453.62  5031.5   457.1  5041.5  461.74
    5108  460.89  5142.5  464.43  5247.1  466.16  5444.9     465  5677.1  468.01
  5904.8   472.3  5952.1  473.54  5962.5  474.66  6076.5   472.4  6175.7  472.51
#Mann= 5 ,-1 , 0
  3552.2     .05       0  4980.7     .12       0  5015.9     .07       0
  5027.1     .12       0  5444.9     .05       0
Bank Sta=5015.9,5027.1
XS Rating Curve= 0 ,0
Exp/Cntr=0.3,0.1

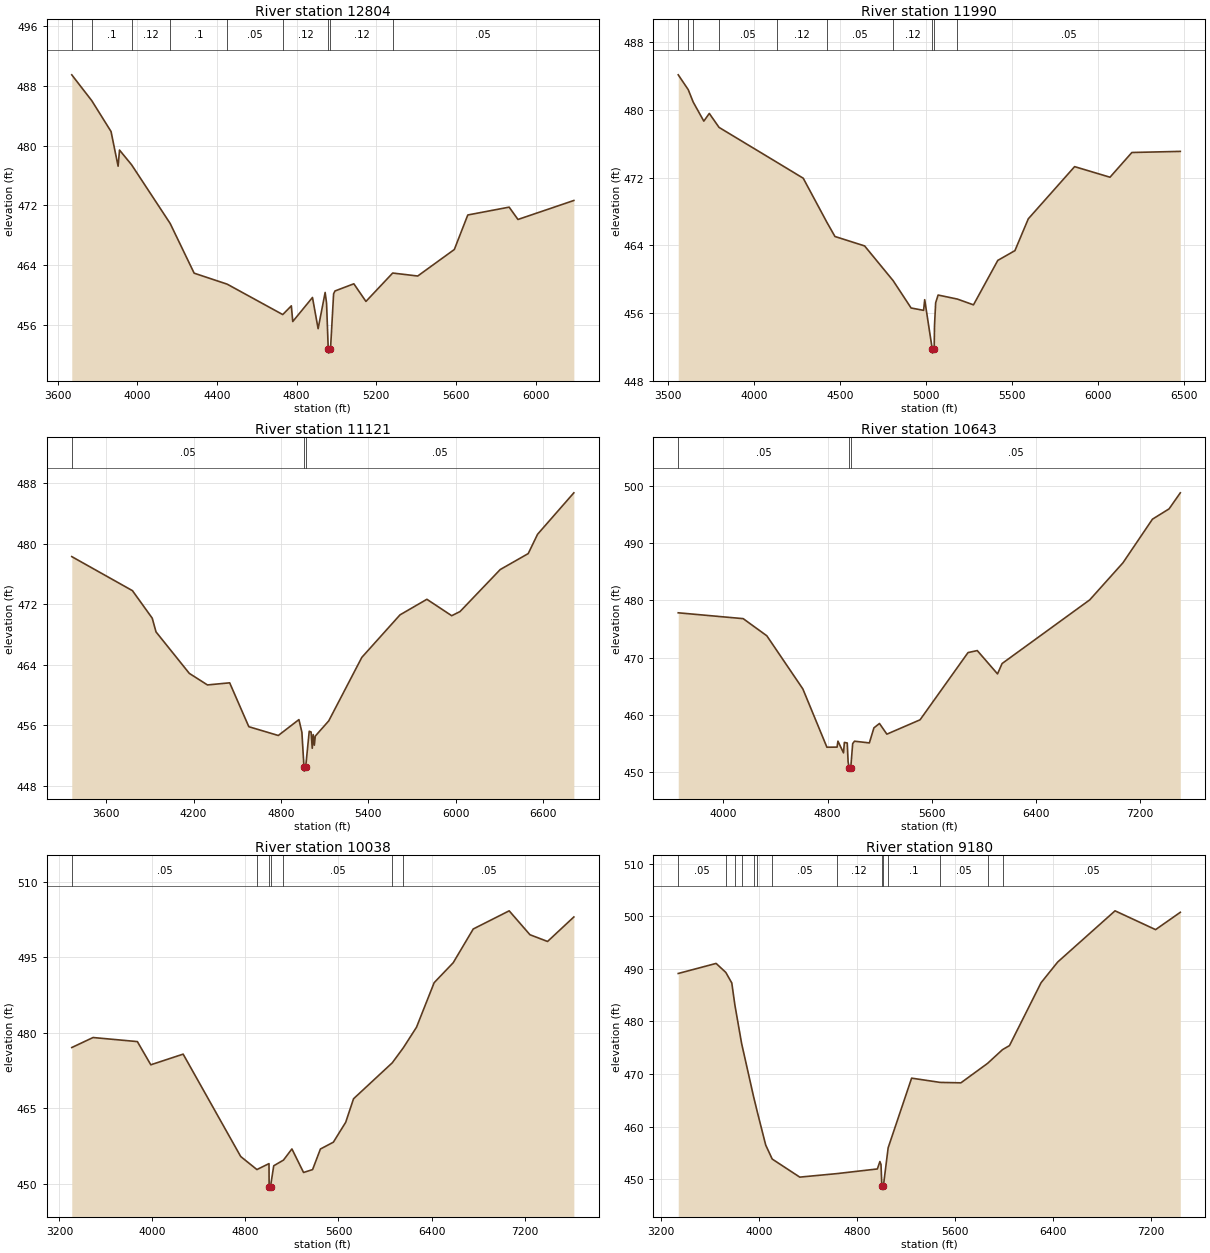
Type RM Length L Ch R = 1 ,12804   ,814,814,814
BEGIN DESCRIPTION:
Buck Branch 3135
END DESCRIPTION:
XS GIS Cut Line= 3
      2756081.87      6867626.21      2757027.55      6868575.74
      2757570.79      6869623.68
#Sta/Elev= 30
  3671.2  489.47  3771.9     486  3868.4  481.88  3903.8  477.24  3910.9   479.4
  3971.5  477.43  4165.1  469.58  4285.6  462.92  4451.5  461.45  4730.3  457.38
  4773.5  458.55  4780.6  456.45  4879.6  459.67  4907.9  455.49  4943.2  460.34
  4950.3  458.91  4958.8  452.72  4960.4  452.22    4970  452.72  4985.7  460.16
  4992.7  460.54  5087.2   461.5    5148  459.14  5282.3  462.94  5407.9  462.54
  5591.7  466.09  5659.3  470.71  5866.9  471.76  5911.2  470.11  6191.7  472.65
#Mann= 9 ,-1 , 0
  3671.2     .05       0  3771.9      .1       0  3971.5     .12       0
  4165.1      .1       0  4451.5     .05       0  4730.3     .12       0
  4958.8     .07       0    4970     .12       0  5282.3     .05       0
Bank Sta=4958.8,4970
XS Rating Curve= 0 ,0
Exp/Cntr=0.3,0.1

Type RM Length L Ch R = 1 ,11990   ,869,869,869
BEGIN DESCRIPTION:
Buck Branch 3134
END DESCRIPTION:
XS GIS Cut Line= 4
      2756077.42      6867809.39      2756325.01      6868581.93
      2756706.95      6869083.15      2757691.97       6870182.1
#Sta/Elev= 30
  3560.7  484.14  3618.8  482.39  3647.7  480.92  3709.4  478.67  3741.2  479.58
    3798  477.93  4136.7  473.78    4287  471.93  4425.2   466.7  4471.4  465.05
  4643.5  463.94  4809.6  459.83  4913.7  456.61  4986.4  456.33  4992.7  457.59
  5036.5  451.78  5038.1  451.28  5047.8  451.78  5049.7  454.52  5056.4  457.22
  5070.6  458.14    5183  457.66  5276.2  456.98  5417.5  462.23  5516.9  463.38
  5594.7  467.14  5863.8   473.3  6069.4  472.05  6196.5  474.97  6477.9   475.1
#Mann= 10 ,-1 , 0
  3560.7     .05       0  3618.8      .1       0  3647.7     .12       0
    3798     .05       0  4136.7     .12       0  4425.2     .05       0
  4809.6     .12       0  5036.5     .07       0  5047.8     .12       0
    5183     .05       0
Bank Sta=5036.5,5047.8
XS Rating Curve= 0 ,0
Exp/Cntr=0.3,0.1

Type RM Length L Ch R = 1 ,11121   ,478,478,478
BEGIN DESCRIPTION:
Buck Branch 3133
END DESCRIPTION:
XS GIS Cut Line= 3
      2756124.67       6868039.1      2756381.01       6869659.7
      2757536.75      6871052.22
#Sta/Elev= 30
  3362.6  478.29  3779.6  473.79  3915.7  470.15  3941.6  468.34  4170.3  462.86
  4295.1  461.33  4447.8  461.61  4579.4  455.81  4781.9  454.65  4923.7  456.75
  4944.1  455.08  4958.5  450.44    4960  449.94  4969.9  450.44  4994.5  455.21
  5007.4  455.11  5015.3  452.96  5021.8  454.77  5029.6  453.37  5036.1  454.57
  5128.5  456.58  5355.9  464.97  5618.2  470.59  5803.1  472.65  5973.7  470.48
    6031  471.03    6307  476.58  6499.5  478.69  6563.6  481.24    6813  486.72
#Mann= 3 ,-1 , 0
  3362.6     .05       0  4958.5     .04       0  4969.9     .05       0
Bank Sta=4958.5,4969.9
XS Rating Curve= 0 ,0
Exp/Cntr=0.3,0.1

Type RM Length L Ch R = 1 ,10643   ,605,605,605
BEGIN DESCRIPTION:
Buck Branch 3131
END DESCRIPTION:
XS GIS Cut Line= 4
      2755099.74      6868658.48      2755482.91      6869252.51
      2755980.74      6869671.61      2757828.92      6871350.31
#Sta/Elev= 30
  3652.7  477.83  4151.3  476.81  4332.8  473.82  4609.4  464.55  4794.1  454.38
  4872.2   454.4  4878.7  455.44  4921.6   453.4  4928.1  455.22  4950.2  455.12
  4956.7  451.87  4965.2  450.71  4966.8  450.21  4976.8  450.71  4991.9  455.01
    5006  455.43  5119.9  455.13    5155  457.76  5197.6  458.52  5254.3  456.66
  5509.1  459.16  5877.4  470.89  5948.4  471.24  6103.8  467.17  6138.9  468.98
    6812  480.09  7066.7  486.55  7293.1  494.16  7420.8  495.96  7507.1  498.76
#Mann= 3 ,-1 , 0
  3652.7     .05       0  4965.2     .04       0  4976.8     .05       0
Bank Sta=4965.2,4976.8
XS Rating Curve= 0 ,0
Exp/Cntr=0.3,0.1

Type RM Length L Ch R = 1 ,10038   ,858,858,858
BEGIN DESCRIPTION:
Buck Branch 3132
END DESCRIPTION:
XS GIS Cut Line= 5
      2754867.34      6868405.15      2755336.79      6869092.29
      2755578.36       6869921.6      2755937.09      6871165.69
      2756702.12      6872249.54
#Sta/Elev= 30
  3306.6  477.04  3489.8  479.03  3870.8  478.22  3986.3  473.61  4264.4  475.73
  4759.4  455.38  4898.7  452.79  5002.6  453.97  5003.8   449.4  5005.4   448.9
  5015.5   449.4  5043.3  453.54  5127.1  454.67  5199.7  456.89  5299.7  452.21
  5377.4  452.78  5444.7  456.87  5556.1  458.23  5662.3  462.19  5729.6  466.86
  6062.8  474.01  6157.3  476.98  6270.9  481.07  6422.8  489.93  6586.5  493.89
  6758.9   500.6    7068  504.21  7246.5  499.46    7398  498.12    7624  502.99
#Mann= 7 ,-1 , 0
  3306.6     .05       0  4898.7     .12       0  5003.8     .07       0
  5015.5     .12       0  5127.1     .05       0  6062.8     .12       0
  6157.3     .05       0
Bank Sta=5003.8,5015.5
XS Rating Curve= 0 ,0
Exp/Cntr=0.3,0.1

Type RM Length L Ch R = 1 ,9180    ,1225,1225,1225
BEGIN DESCRIPTION:
Buck Branch 3130
END DESCRIPTION:
XS GIS Cut Line= 4
      2754084.94      6869017.66      2754309.28      6869293.31
      2755128.82      6870300.33      2756525.85       6872302.2
#Sta/Elev= 30
  3342.3  489.12  3651.2  491.03  3730.3  489.32  3779.1  487.32  3804.1  483.17
    3859  475.85  3956.5  465.76  3987.7  462.78  4055.7  456.53  4108.8  453.87
  4333.5  450.44  4633.9   451.1  4966.3  451.99  4987.1   453.4  4996.1  452.83
  5003.2  448.66  5004.8  448.16    5015  448.66  5054.4  456.01  5245.7  469.24
  5478.7  468.43  5647.8  468.35    5865  472.04  5987.4  474.66  6043.9  475.42
  6301.7  487.37  6437.3   491.3  6904.9  501.02  7235.5  497.45  7437.2  500.74
#Mann= 14 ,-1 , 0
  3342.3     .05       0  3730.3      .1       0  3804.1     .12       0
    3859      .1       0  3956.5     .12       0  3987.7      .1       0
  4108.8     .05       0  4633.9     .12       0  5003.2     .07       0
    5015     .12       0  5054.4      .1       0  5478.7     .05       0
    5865     .12       0  5987.4     .05       0
Bank Sta=5003.2,5015
XS Rating Curve= 0 ,0
Exp/Cntr=0.3,0.1

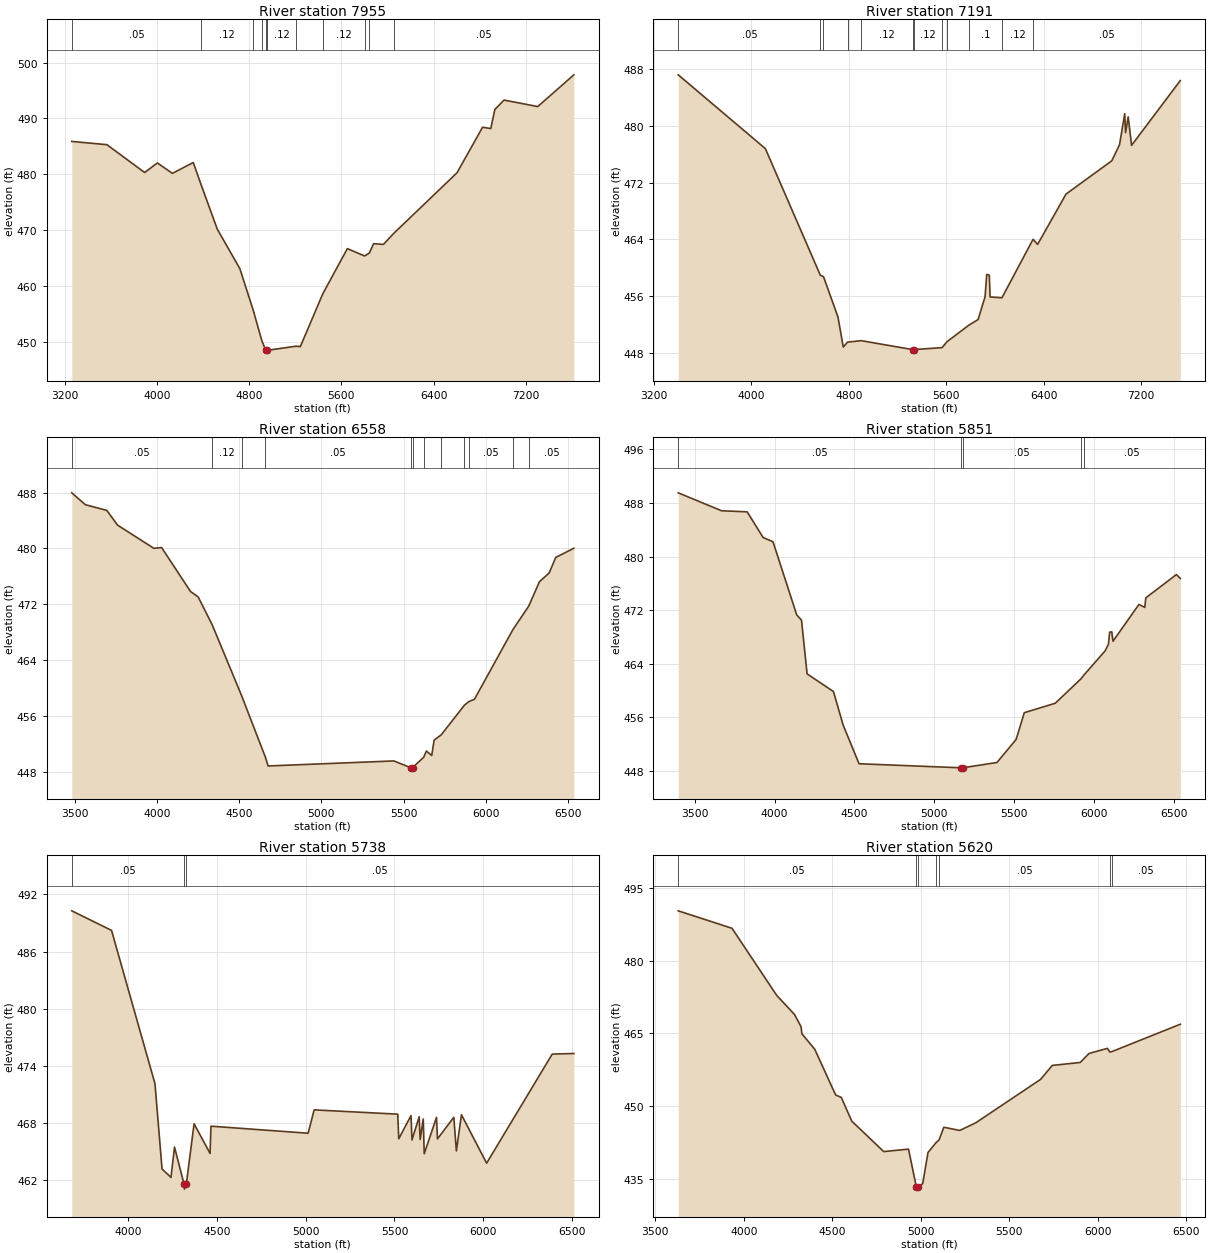
Type RM Length L Ch R = 1 ,7955    ,764,764,764
BEGIN DESCRIPTION:
Buck Branch 3129
END DESCRIPTION:
XS GIS Cut Line= 5
      2753715.52      6869295.11      2753867.38      6870113.85
      2754359.18      6870866.13      2755274.99      6871533.47
      2756481.14      6872412.46
#Sta/Elev= 30
  3259.8  485.89  3564.9  485.31  3892.2  480.33  4002.9  482.04  4133.3  480.18
  4314.3  482.12    4382  478.16  4522.3  470.21  4718.4  463.13  4834.2  455.71
  4909.5  450.22  4943.4  448.51    4945  448.01  4955.2  448.51  5206.2  449.25
  5243.4  449.18  5438.4  458.63  5651.3  466.71  5800.9   465.4  5842.1  465.91
  5879.2  467.59    5965  467.47  6052.8  469.42  6603.1  480.28  6824.8  488.43
  6895.9   488.2  6931.5  491.61    7011  493.29  7303.8  492.13  7616.9  497.81
#Mann= 11 ,-1 , 0
  3259.8     .05       0    4382     .12       0  4834.2      .1       0
  4909.5     .12       0  4943.4     .07       0  4955.2     .12       0
  5206.2      .1       0  5438.4     .12       0  5800.9      .1       0
  5842.1     .12       0  6052.8     .05       0
Bank Sta=4943.4,4955.2
XS Rating Curve= 0 ,0
Exp/Cntr=0.3,0.1

Type RM Length L Ch R = 1 ,7191    ,633,633,633
BEGIN DESCRIPTION:
Buck Branch 3128
END DESCRIPTION:
XS GIS Cut Line= 4
      2752787.57      6870245.85      2753105.72      6870956.96
       2753811.7      6871350.74      2755514.49      6873227.19
#Sta/Elev= 30
  3399.6  487.23    4115  476.81  4566.6  458.92  4591.8  458.76  4710.9  453.04
  4754.3  448.81  4789.1   449.5    4901  449.71    5324  448.45  5325.7  447.95
  5335.9  448.45  5565.7  448.73  5606.3  449.57  5786.3  451.91  5861.1  452.69
  5917.9  455.89  5932.1  459.06    5953  458.95  5959.8  455.88  6056.7  455.76
  6312.1  464.01  6349.7   463.3  6582.9   470.4  6958.6   475.1  7022.1  477.37
  7064.7  481.74  7071.5  479.07  7093.1   481.3  7120.9  477.28  7520.9  486.42
#Mann= 12 ,-1 , 0
  3399.6     .05       0  4566.6     .12       0  4591.8      .1       0
  4789.1     .05       0    4901     .12       0    5324     .07       0
  5335.9     .12       0  5565.7      .1       0  5606.3     .12       0
  5786.3      .1       0  6056.7     .12       0  6312.1     .05       0
Bank Sta=5324,5335.9
XS Rating Curve= 0 ,0
Exp/Cntr=0.3,0.1

Type RM Length L Ch R = 1 ,6558    ,707,707,707
BEGIN DESCRIPTION:
Buck Branch 3127
END DESCRIPTION:
XS GIS Cut Line= 4
      2752763.89       6870365.3      2753049.04      6871024.86
      2753368.69       6871764.3      2753937.52      6873183.19
#Sta/Elev= 30
  3482.2  487.97  3564.7  486.27  3695.4  485.45  3760.8  483.34  3981.5  480.02
  4028.5  480.13  4203.9  473.85  4250.8  473.06  4336.6  469.04  4515.6  458.88
  4659.9  450.08  4675.9  448.85  5440.8  449.57  5542.4  448.61  5544.1  448.11
  5554.5  448.61  5622.4  450.11  5638.4  450.99  5670.8  450.35  5685.6  452.56
  5728.9  453.31  5869.8  457.56  5896.7  458.07  5930.5   458.4  6163.4  468.33
  6261.3  471.77    6326  475.25  6385.1  476.49  6424.9  478.72    6535  480.03
#Mann= 12 ,-1 , 0
  3482.2     .05       0  4336.6     .12       0  4515.6      .1       0
  4659.9     .05       0  5542.4     .03       0  5554.5     .05       0
  5622.4     .12       0  5728.9     .05       0  5869.8     .12       0
  5896.7     .05       0  6163.4     .12       0  6261.3     .05       0
Bank Sta=5542.4,5554.5
XS Rating Curve= 0 ,0
Exp/Cntr=0.3,0.1

Type RM Length L Ch R = 1 ,5851    ,113,113,113
BEGIN DESCRIPTION:
Buck Branch 3126
END DESCRIPTION:
XS GIS Cut Line= 5
      2752683.81      6870409.63      2752740.57      6871640.84
      2752734.59      6872039.01      2753027.53      6872669.56
      2753654.72      6873196.55
#Sta/Elev= 30
  3396.6  489.52  3668.3  486.84  3828.4  486.68  3928.5  482.84  3990.3  482.21
  4138.8  471.29  4168.8   470.5    4204  462.47    4369  459.84  4429.1  454.87
  4529.2  449.05  5166.8  448.45  5168.5  447.95  5178.9  448.45  5393.2  449.24
  5513.2  452.68  5564.5  456.68  5758.5  458.09  5919.6  461.74  5937.2  462.28
  6070.7  465.91  6091.5   466.9  6099.3   468.7  6112.4  468.76  6120.1  467.36
  6282.7  472.85  6319.1  472.41  6325.6  473.83  6517.3  477.31  6541.8  476.73
#Mann= 5 ,-1 , 0
  3396.6     .05       0  5166.8     .05       0  5178.9     .05       0
  5919.6     .12       0  5937.2     .05       0
Bank Sta=5166.8,5178.9
XS Rating Curve= 0 ,0
Exp/Cntr=0.3,0.1

Type RM Length L Ch R = 1 ,5738    ,118,118,118
BEGIN DESCRIPTION:
Buck Branch 3124
END DESCRIPTION:
XS GIS Cut Line= 5
      2752564.95      6870711.54      2752653.29      6871153.82
      2752621.44      6872014.62      2752973.47      6872780.81
      2753484.78      6873213.79
#Sta/Elev= 30
    3684  490.27  3907.8  488.22  4152.2  472.15  4192.1   463.2  4242.3  462.32
  4262.3   465.5  4316.3  461.59    4318  461.09  4328.4  461.59  4372.4  467.94
  4462.4  464.83  4467.4  467.69  5014.1  466.95  5048.1   469.4  5518.7  468.95
  5524.2  466.37  5593.2   468.8  5598.7  466.24  5639.1  468.68  5644.6   466.3
  5662.1  468.44  5667.6   464.8  5736.6  468.61  5742.1  466.36    5834  468.62
  5848.5   465.1  5877.1  468.89  6018.8  463.81    6388  475.25  6509.6  475.31
#Mann= 3 ,-1 , 0
    3684     .05       0  4316.3     .05       0  4328.4     .05       0
Bank Sta=4316.3,4328.4
XS Rating Curve= 0 ,0
Exp/Cntr=0.3,0.1

Type RM Length L Ch R = 1 ,5620    ,263,263,263
BEGIN DESCRIPTION:
Buck Branch 3125
END DESCRIPTION:
XS GIS Cut Line= 4
      2752377.35      6870700.03      2752518.13      6871735.03
      2752519.81       6872120.4      2753186.91      6873357.49
#Sta/Elev= 30
  3629.7  490.34  3933.4  486.73  4185.7  472.87  4286.7   468.9  4323.3  466.38
  4328.3  464.92  4400.7  461.73  4518.8  452.27  4550.6  451.78  4609.6  446.88
  4790.2  440.58  4930.2  441.09  4974.2  433.32  4975.9  432.82  4986.3  433.32
  5010.2  433.93  5040.2  440.39  5085.8  442.43  5102.8  443.01  5129.7  445.61
  5219.3  444.95  5309.7  446.52  5676.3  455.51    5742  458.39  5900.1     459
  5949.6  460.86  6053.4  461.91  6067.1  461.15  6077.8  461.23  6465.1   466.9
#Mann= 7 ,-1 , 0
  3629.7     .05       0  4974.2     .05       0  4986.3     .05       0
  5085.8     .12       0  5102.8     .05       0  6067.1     .12       0
  6077.8     .05       0
Bank Sta=4974.2,4986.3
XS Rating Curve= 0 ,0
Exp/Cntr=0.3,0.1

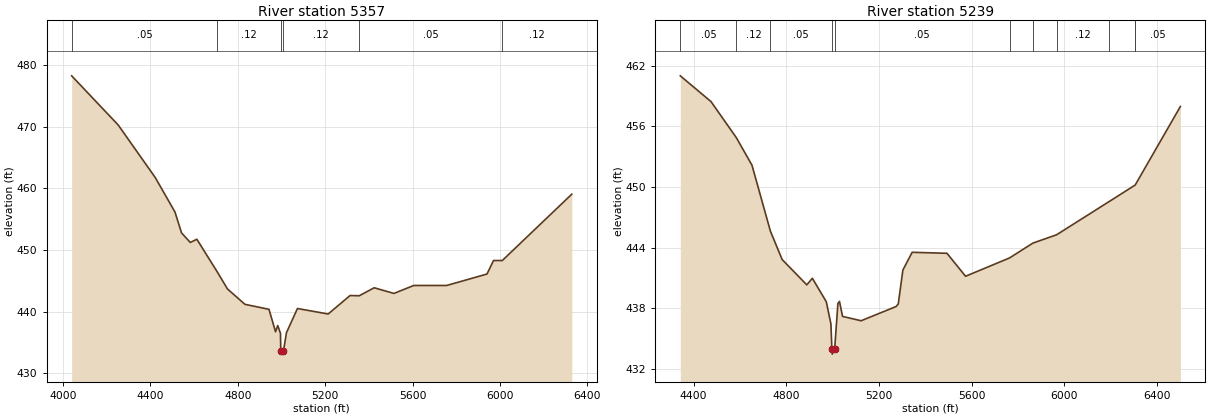
Type RM Length L Ch R = 1 ,5357    ,118,118,118
BEGIN DESCRIPTION:
Buck Branch 3121
END DESCRIPTION:
XS GIS Cut Line= 5
      2752290.18      6871148.26       2752282.4      6871521.94
      2752270.89      6872103.55      2752340.64      6872935.64
      2752588.69      6873367.48
#Sta/Elev= 30
  4040.3  478.29  4253.1  470.31  4423.1  461.75  4513.1  456.16  4543.1  452.77
  4583.2  451.22  4613.2  451.74  4707.4  446.39  4753.2  443.67  4833.2  441.17
  4943.2  440.36  4973.2  436.71  4983.2  437.72  4995.8  436.46  4997.2  433.58
  4998.9  433.08  5009.3  433.58  5023.3  436.57  5073.5  440.49    5214   439.6
  5314.3   442.6  5356.2  442.56  5424.7  443.86    5515  442.94  5605.4  444.23
  5755.9  444.23  5940.8  446.09  5970.8  448.29  6010.6  448.28  6328.8  459.06
#Mann= 6 ,-1 , 0
  4040.3     .05       0  4707.4     .12       0  4997.2     .07       0
  5009.3     .12       0  5356.2     .05       0  6010.6     .12       0
Bank Sta=4997.2,5009.3
XS Rating Curve= 0 ,0
Exp/Cntr=0.3,0.1

Type RM Length L Ch R = 1 ,5239    ,614,614,614
BEGIN DESCRIPTION:
Buck Branch 3122
END DESCRIPTION:
XS GIS Cut Line= 4
      2752111.51      6871472.33      2752159.63      6872137.22
      2752214.79       6873041.7      2752494.64       6873556.8
#Sta/Elev= 30
  4342.7     461  4475.4  458.45  4584.8  454.88  4652.2  452.16  4731.7  445.64
  4782.5  442.83  4888.8  440.33  4912.9  440.98    4973  438.66  4993.1  436.45
    4997  433.98  4998.7  433.48  5009.1  433.98  5023.1  438.49    5030  438.69
  5043.2  437.21  5123.3  436.78  5273.6  438.18  5283.6  438.43  5303.7   441.8
  5343.7  443.55    5494  443.45  5574.2  441.18    5764  442.99    5865  444.46
  5967.1  445.28  6192.9  448.55  6304.3  450.17  6306.2  450.19  6501.7  457.97
#Mann= 11 ,-1 , 0
  4342.7     .05       0  4584.8     .12       0  4731.7     .05       0
    4997     .03       0  5009.1     .05       0    5764     .12       0
    5865     .05       0  5967.1     .12       0  6192.9     .05       0
  6304.3     .12       0  6306.2     .05       0
Bank Sta=4997,5009.1
XS Rating Curve= 0 ,0
Exp/Cntr=0.3,0.1