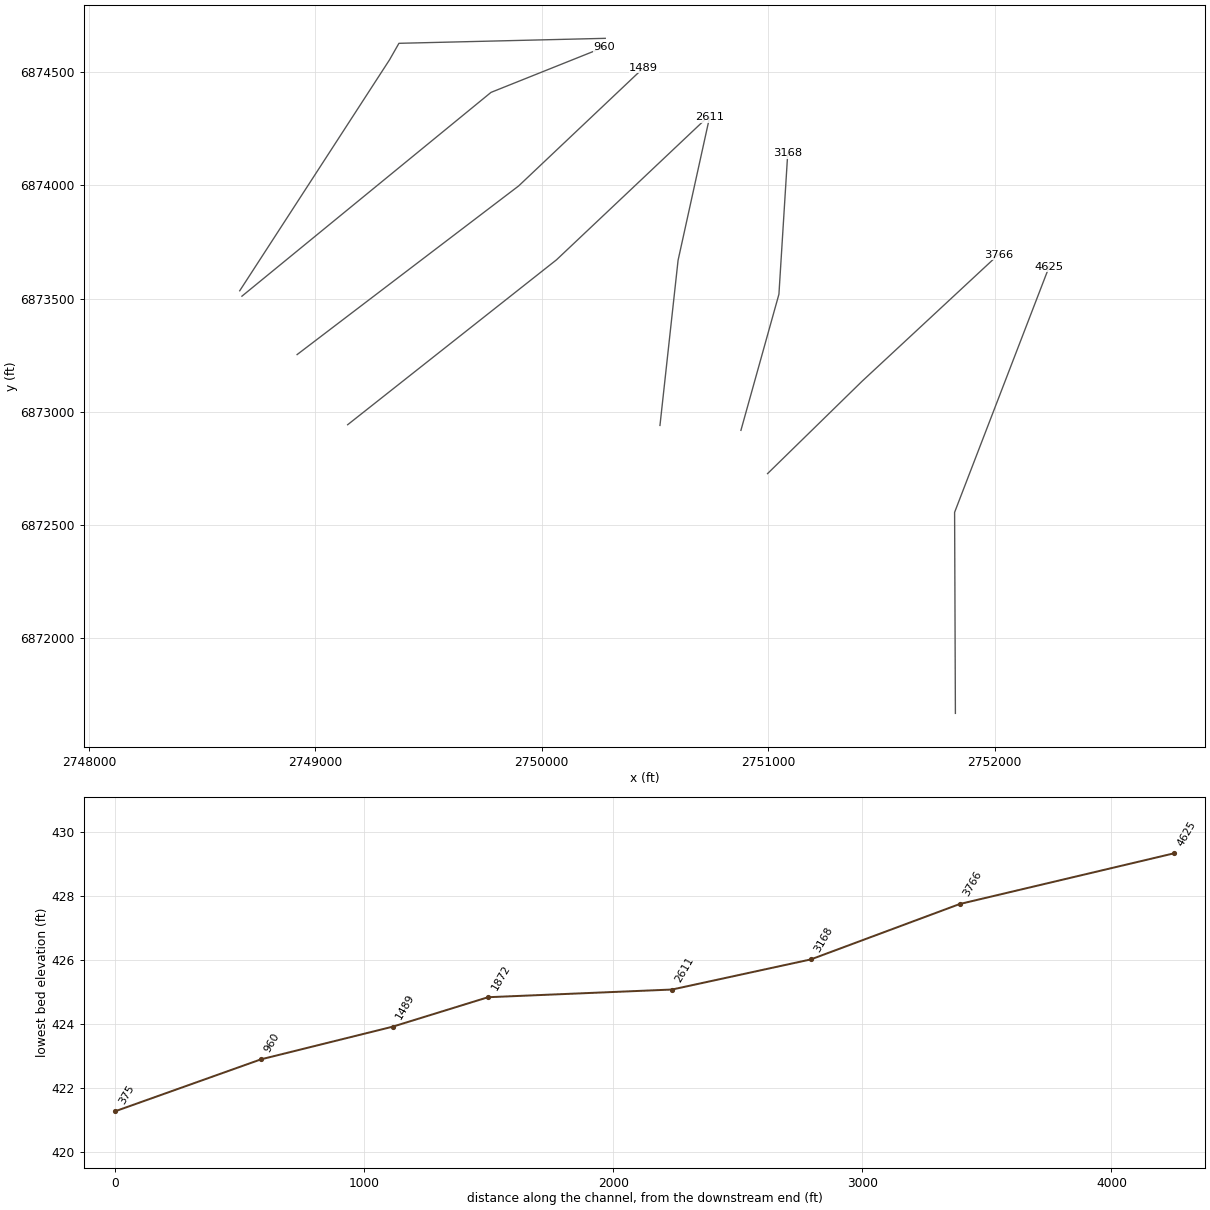
HEC-RAS study Buck Branch.prj: Buck Branch Base Level Engineering

--- Buck Branch.g01 (geometry) --- (continued)

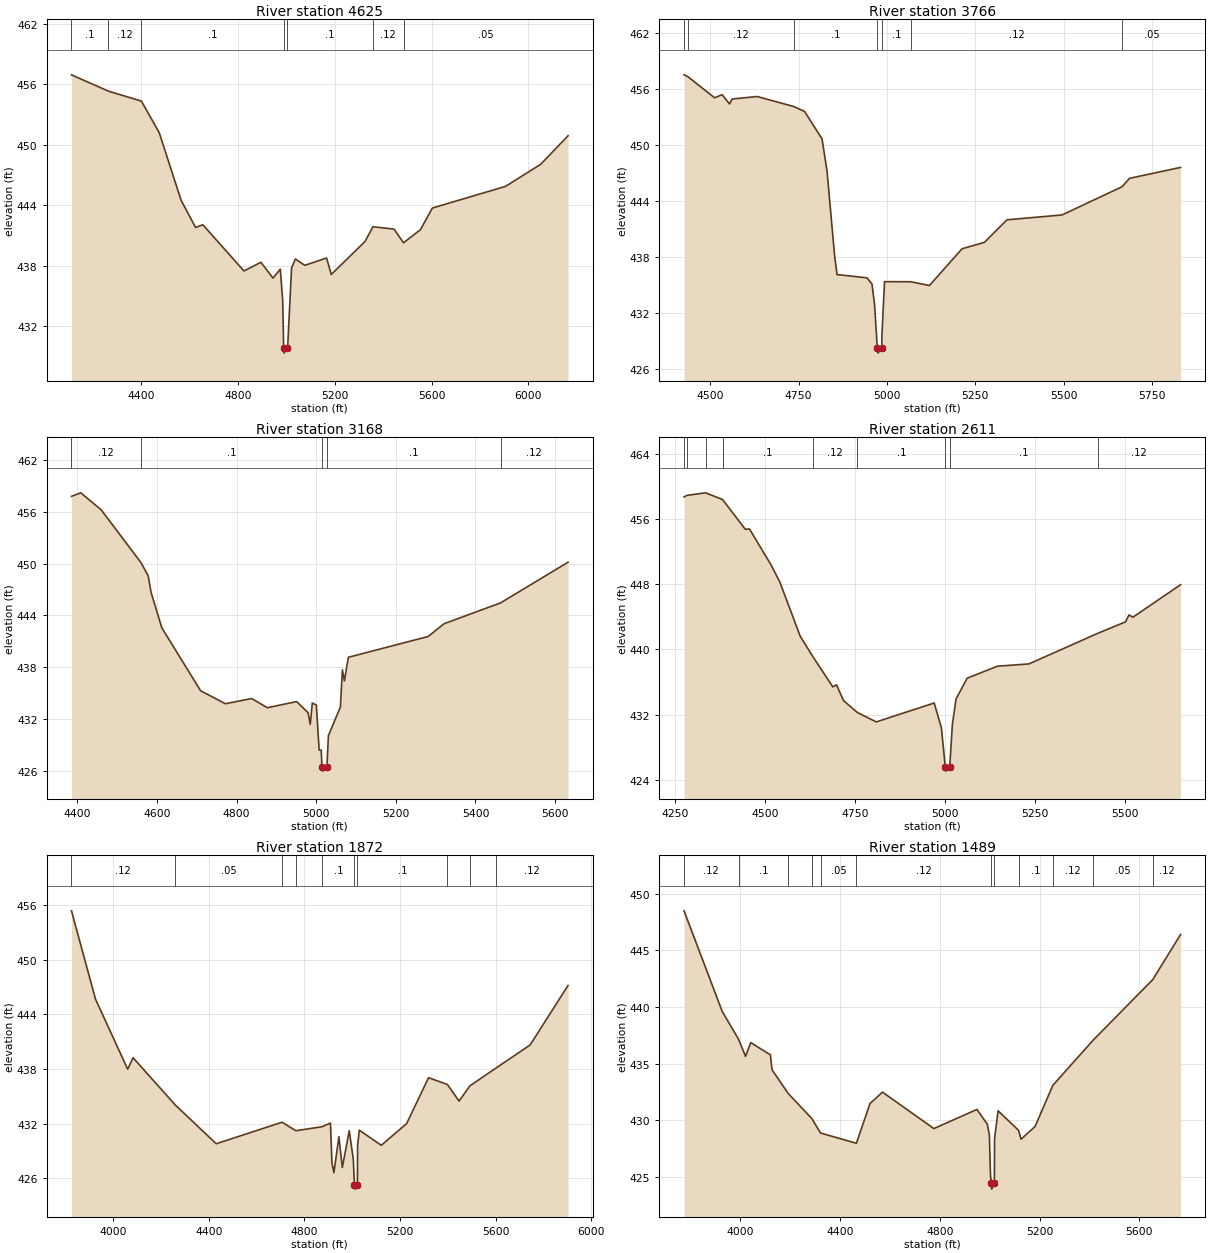
Type RM Length L Ch R = 1 ,4625    ,859,859,859
BEGIN DESCRIPTION:
Buck Branch 3123
END DESCRIPTION:
XS GIS Cut Line= 3
       2751826.8      6871668.53       2751823.3      6872556.41
      2752241.18      6873641.97
#Sta/Elev= 30
  4112.7  456.96  4265.2  455.34  4401.5  454.35  4475.2  451.21  4565.2  444.52
  4625.2   441.8  4655.2  442.07  4825.2  437.48  4895.2  438.34  4945.2  436.77
  4975.2  437.66  4985.2  434.54  4989.1  429.82  4990.8  429.32  5001.3  429.82
  5005.7  429.94  5021.8  437.79  5037.7  438.67  5076.4  438.04  5166.4  438.77
  5185.7  437.13  5324.9   440.4  5358.1  441.87  5444.9  441.64  5484.2  440.28
  5554.1  441.58  5603.4  443.73  5905.6  445.88  6051.1  448.08  6163.8  450.91
#Mann= 7 ,-1 , 0
  4112.7      .1       0  4265.2     .12       0  4401.5      .1       0
  4989.1     .07       0  5001.3      .1       0  5358.1     .12       0
  5484.2     .05       0
Bank Sta=4989.1,5001.3
XS Rating Curve= 0 ,0
Exp/Cntr=0.3,0.1

Type RM Length L Ch R = 1 ,3766    ,598,598,598
BEGIN DESCRIPTION:
Buck Branch 3120
END DESCRIPTION:
XS GIS Cut Line= 3
       2750997.3      6872727.39      2751413.78      6873134.45
      2752016.67      6873694.58
#Sta/Elev= 30
  4425.8  457.53  4436.9  457.33  4512.3  455.07  4533.6  455.41  4554.7  454.41
  4561.8  454.94  4632.6  455.21  4736.2  454.14  4766.9  453.61  4816.3  450.68
  4830.4  447.26  4851.7  438.27  4858.7  436.15  4943.6   435.8  4957.7  435.13
  4964.9  432.98  4972.9  428.24  4974.6  427.74  4985.2  428.24    4986  429.73
  4993.2  435.39  5067.7  435.38  5120.4  434.98  5212.6  438.91  5276.1   439.6
  5339.6  442.01  5495.5  442.53  5665.4  445.55  5686.6  446.45  5831.1  447.62
#Mann= 7 ,-1 , 0
  4425.8      .1       0  4436.9     .12       0  4736.2      .1       0
  4972.9     .07       0  4985.2      .1       0  5067.7     .12       0
  5665.4     .05       0
Bank Sta=4972.9,4985.2
XS Rating Curve= 0 ,0
Exp/Cntr=0.3,0.1

Type RM Length L Ch R = 1 ,3168    ,557,557,557
BEGIN DESCRIPTION:
Buck Branch 3119
END DESCRIPTION:
XS GIS Cut Line= 3
      2750879.65      6872918.51      2751047.47      6873519.58
      2751086.37       6874141.8
#Sta/Elev= 30
    4385  457.77  4408.4  458.18  4459.7  456.21  4559.2  450.14  4577.8  448.58
  4584.9  446.68    4612  442.57  4709.4   435.3  4771.7   433.8  4837.7   434.4
  4877.1  433.34  4950.6  434.05  4979.4  432.76  4984.8  431.42    4990  433.88
  5000.2  433.65  5007.2  428.44  5012.3  428.44  5014.4  426.51  5016.1  426.01
  5026.7  426.51  5030.5  430.12  5060.6  433.42  5065.6  437.71  5070.6  436.43
  5080.6  439.17    5281  441.57  5321.1  443.05  5463.1  445.46  5632.5  450.16
#Mann= 5 ,-1 , 0
    4385     .12       0  4559.2      .1       0  5014.4     .07       0
  5026.7      .1       0  5463.1     .12       0
Bank Sta=5014.4,5026.7
XS Rating Curve= 0 ,0
Exp/Cntr=0.3,0.1

Type RM Length L Ch R = 1 ,2611    ,739,739,739
BEGIN DESCRIPTION:
Buck Branch 3118
END DESCRIPTION:
XS GIS Cut Line= 3
      2750522.11      6872940.16       2750602.1      6873669.45
      2750740.97      6874300.18
#Sta/Elev= 30
  4274.9  458.67  4283.1  458.87  4334.8  459.18  4381.9  458.36  4444.9  454.72
  4456.8  454.75  4517.2   450.3  4541.1  448.24  4597.7   441.6  4631.8  439.17
  4688.2   435.4  4698.3  435.65  4718.3   433.7  4756.3  432.26  4808.9   431.1
  4969.9  433.42    4990  430.35  5000.7  425.57  5002.4  425.07    5013  425.57
  5020.4   430.8  5030.6  433.91  5061.4  436.46  5145.7  437.93  5233.1  438.21
  5423.8  441.95  5501.7  443.37  5510.9  444.21  5522.1  443.94  5654.4  447.92
#Mann= 9 ,-1 , 0
  4274.9     .05       0  4283.1      .1       0  4334.8     .12       0
  4381.9      .1       0  4631.8     .12       0  4756.3      .1       0
  5000.7     .07       0    5013      .1       0  5423.8     .12       0
Bank Sta=5000.7,5013
XS Rating Curve= 0 ,0
Exp/Cntr=0.3,0.1

Type RM Length L Ch R = 1 ,1872    ,383,383,383
BEGIN DESCRIPTION:
Buck Branch 3117
END DESCRIPTION:
XS GIS Cut Line= 3
      2749142.85      6872943.27      2750065.26      6873671.64
      2750720.68      6874290.59
#Sta/Elev= 30
    3826  455.37  3926.4  445.68    4061  437.99  4083.5  439.25  4259.9  434.07
  4431.3  429.81  4706.7  432.17  4764.6  431.24  4874.4  431.68  4909.1  432.08
  4915.5  427.68  4923.6  426.64  4944.4  430.59  4958.8   427.2  4987.7  431.24
  5004.5  428.16  5009.5  425.33  5011.3  424.83  5021.9  425.33  5022.6  429.66
  5029.8   431.3  5121.7  429.64  5227.7  432.02  5319.5  437.06  5398.5  436.31
    5447  434.49  5491.8  436.15  5603.2  438.15  5744.3  440.65  5902.8  447.18
#Mann= 10 ,-1 , 0
    3826     .12       0  4259.9     .05       0  4706.7     .12       0
  4764.6     .05       0  4874.4      .1       0  5009.5     .07       0
  5021.9      .1       0  5398.5     .12       0  5491.8      .1       0
  5603.2     .12       0
Bank Sta=5009.5,5021.9
XS Rating Curve= 0 ,0
Exp/Cntr=0.3,0.1

Type RM Length L Ch R = 1 ,1489    ,529,529,529
BEGIN DESCRIPTION:
Buck Branch 3116
END DESCRIPTION:
XS GIS Cut Line= 3
      2748919.63      6873253.07      2749898.15      6873997.94
      2750450.53      6874520.41
#Sta/Elev= 30
  3775.3   448.5  3928.3  439.61  3993.9  437.15  4021.8  435.64  4042.6  436.86
  4121.6  435.77  4127.9  434.46  4192.1  432.38  4287.7  430.14  4322.4  428.87
    4466  427.96  4520.8  431.48  4570.7  432.48  4776.6  429.26  4949.1  430.95
  4990.7  429.65    4999  428.69  5003.5  425.12  5006.7  424.41  5008.4  423.91
  5019.1  424.41  5019.8  428.37  5033.9  430.83  5116.3   429.1    5126  428.32
  5182.4  429.45  5253.4  433.08  5415.3  437.08  5653.8  442.42  5765.4  446.41
#Mann= 12 ,-1 , 0
  3775.3     .12       0  3993.9      .1       0  4192.1     .05       0
  4287.7     .12       0  4322.4     .05       0    4466     .12       0
  5006.7     .07       0  5019.1     .12       0  5116.3      .1       0
  5253.4     .12       0  5415.3     .05       0  5653.8     .12       0
Bank Sta=5006.7,5019.1
XS Rating Curve= 0 ,0
Exp/Cntr=0.3,0.1

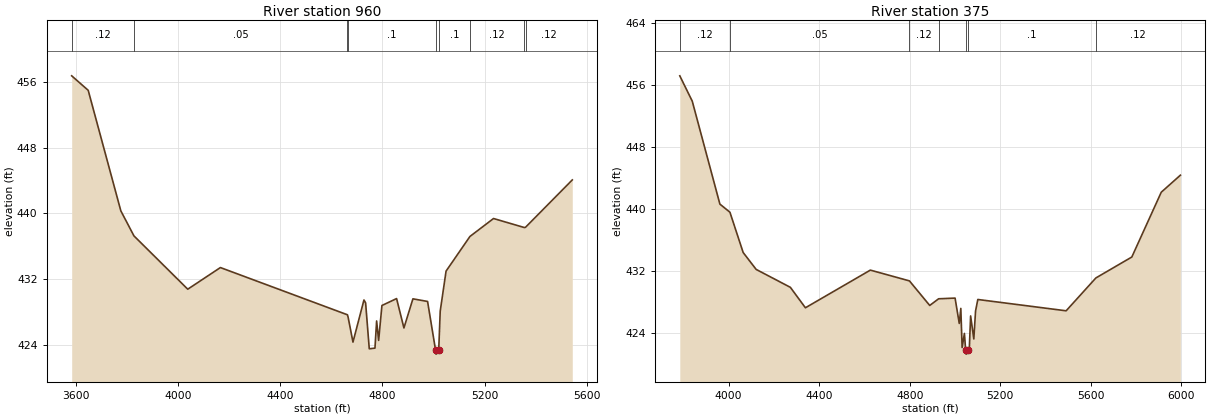
Type RM Length L Ch R = 1 ,960     ,585,585,585
BEGIN DESCRIPTION:
Buck Branch 36
END DESCRIPTION:
XS GIS Cut Line= 3
      2748675.97      6873510.98        2749776.        6874411.
      2750275.98      6874610.99
#Sta/Elev= 30
  3583.3  456.71  3647.9  454.95  3775.7   440.3    3827  437.26  4037.7  430.78
  4165.5  433.41  4662.9  427.67  4665.7  427.35  4684.5  424.35  4727.5  429.47
    4734  429.12  4748.3  423.54  4770.6  423.62  4777.1  426.92    4785  424.56
  4797.9   428.8  4855.3  429.64    4884  426.07  4919.2  429.61  4976.6  429.29
  5007.8  423.39  5009.6  422.89  5020.2  423.39  5026.1  428.12    5049  432.98
  5142.5  437.19  5234.8  439.37  5355.8  438.27  5360.2  438.31  5543.1  444.06
#Mann= 9 ,-1 , 0
  3583.3     .12       0    3827     .05       0  4662.9     .12       0
  4665.7      .1       0  5007.8     .07       0  5020.2      .1       0
  5142.5     .12       0  5355.8     .05       0  5360.2     .12       0
Bank Sta=5007.8,5020.2
XS Rating Curve= 0 ,0
Exp/Cntr=0.3,0.1

Type RM Length L Ch R = 1 ,375     ,0,0,0
BEGIN DESCRIPTION:
Buck Branch 3115
END DESCRIPTION:
XS GIS Cut Line= 4
      2748666.25      6873534.86      2749327.89      6874554.98
       2749369.3      6874627.68      2750280.47      6874649.67
#Sta/Elev= 30
  3784.1  457.18  3839.1  453.91  3961.2  440.63  4005.5  439.58    4064  434.38
  4121.4   432.2  4272.4  429.89  4338.9  427.25  4625.8  432.11  4798.4  430.72
    4888  427.55  4927.2  428.41    5000   428.5  5018.4  425.23  5025.3  427.17
  5031.1  422.12  5041.2  423.94  5046.7  421.77  5048.5  421.27  5059.2  421.77
  5062.8  421.93  5068.6   426.2  5082.7  423.23  5090.4  426.83  5100.4  428.32
  5490.5  426.86  5621.9   431.1  5780.6   433.8  5910.6  442.16  5995.1  444.36
#Mann= 7 ,-1 , 0
  3784.1     .12       0  4005.5     .05       0  4798.4     .12       0
  4927.2      .1       0  5046.7     .07       0  5059.2      .1       0
  5621.9     .12       0
Bank Sta=5046.7,5059.2
XS Rating Curve= 0 ,0
Exp/Cntr=0.3,0.1

Chan Stop Cuts=-1
Use User Specified Reach Order=0
Composite Channel Slope=5