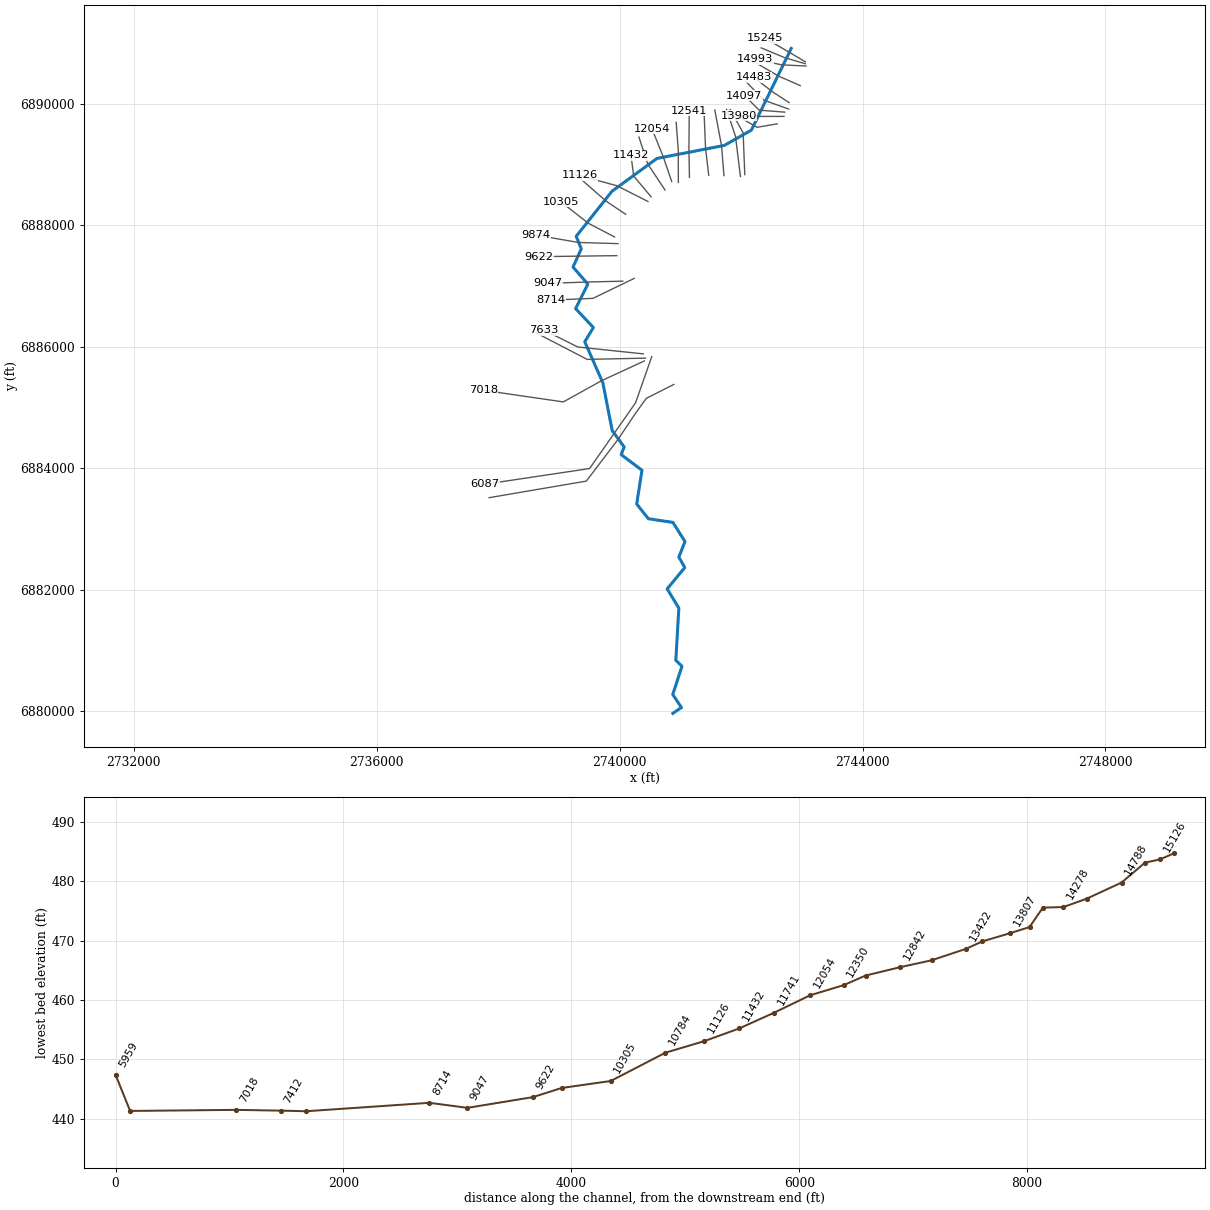
--- Camp Branch.prj (project) ---

Proj Title=Camp Branch Base Level Engineering
Current Plan=p01
Default Exp/Contr=0.3,0.1
English Units
Geom File=g01
Flow File=f01
Plan File=p01
BEGIN DESCRIPTION:
Camp Branch
END DESCRIPTION:

--- Camp Branch.p01 (plan) ---

Plan Title=Multiple Run
Short Identifier=Multiple
Geom File=g01
Flow File=f01
Subcritical Flow
K Sum by GR= 0
Std Step Tol= 0.01
Critical Tol= 0.01
Num of Std Step Trials= 20
Max Error Tol= 0.3
Flow Tol Ratio= 0.001
Split Flow NTrial= 30
Split Flow Tol= 0.02
Split Flow Ratio= 0.02
Log Output Level= 0
Friction Slope Method= 1
Unsteady Friction Slope Method= 2
Unsteady Bridges Friction Slope Method= 1
Parabolic Critical Depth
Global Vel Dist=  1 , 1 , 1
Global Log Level= 0
CheckData=True
Encroach Param= -1, 0, 0, 0
BEGIN DESCRIPTION:
Multiple Run
END DESCRIPTION:

--- Camp Branch.f01 (steady flow) ---

Flow Title=Multiple
Number of Profiles=7
Profile Names=10-year,25-year,50-year,1pct_min,100-year,1pct_plu,500-year
River Rch & RM= Camp Branch,Reach-1,15245
     122     147     166      94     187     373     237
River Rch & RM= Camp Branch,Reach-1,13422
     346     451     534     315     629    1255     873
River Rch & RM= Camp Branch,Reach-1,11126
     635     856    1036     624    1245    2484    1800
River Rch & RM= Camp Branch,Reach-1,7018
     707     957    1161     700    1397    2788    2027
River Rch & RM= Camp Branch,Reach-1,6087
     798    1087    1325     802    1601    3194    2342
River Rch & RM= Camp Branch,Reach-1,4902
     941    1290    1579     958    1912    3815    2813
Boundary for River Rch & Prof#=Camp Branch,Reach-1,1
Up Type=0
Dn Type=3
Dn Slope=0.005
Boundary for River Rch & Prof#=Camp Branch,Reach-1,2
Up Type=0
Dn Type=3
Dn Slope=0.005
Boundary for River Rch & Prof#=Camp Branch,Reach-1,3
Up Type=0
Dn Type=3
Dn Slope=0.005
Boundary for River Rch & Prof#=Camp Branch,Reach-1,4
Up Type=0
Dn Type=3
Dn Slope=0.005
Boundary for River Rch & Prof#=Camp Branch,Reach-1,5
Up Type=0
Dn Type=3
Dn Slope=0.005
Boundary for River Rch & Prof#=Camp Branch,Reach-1,6
Up Type=0
Dn Type=3
Dn Slope=0.005
Boundary for River Rch & Prof#=Camp Branch,Reach-1,7
Up Type=0
Dn Type=3
Dn Slope=0.005

--- Camp Branch.g01 (geometry) ---

Geom Title=Existing Conditions

River Reach=Camp Branch,Reach-1
Reach XY= 30
      2742826.00      6890911.00      2742170.39      6889566.59
      2741724.73      6889314.48      2740616.02      6889100.31
      2739876.00      6888561.00      2739285.01      6887818.02
      2739368.44      6887611.00      2739233.09      6887311.00
      2739476.50      6887031.23      2739276.09      6886626.39
      2739568.18      6886314.27      2739425.88      6886081.10
      2739723.73      6885405.06      2739878.23      6884616.92
      2740074.53      6884348.87      2740026.54      6884221.48
      2740368.32      6883964.70      2740281.41      6883408.58
      2740473.53      6883166.45      2740878.50      6883105.65
      2741076.35      6882790.79      2740975.59      6882536.00
      2741072.96      6882362.45      2740783.08      6882011.02
      2740975.32      6881695.16      2740925.68      6880835.80
      2741026.53      6880736.12      2740875.21      6880271.04
      2741018.44      6880057.66      2740876.00      6879961.00

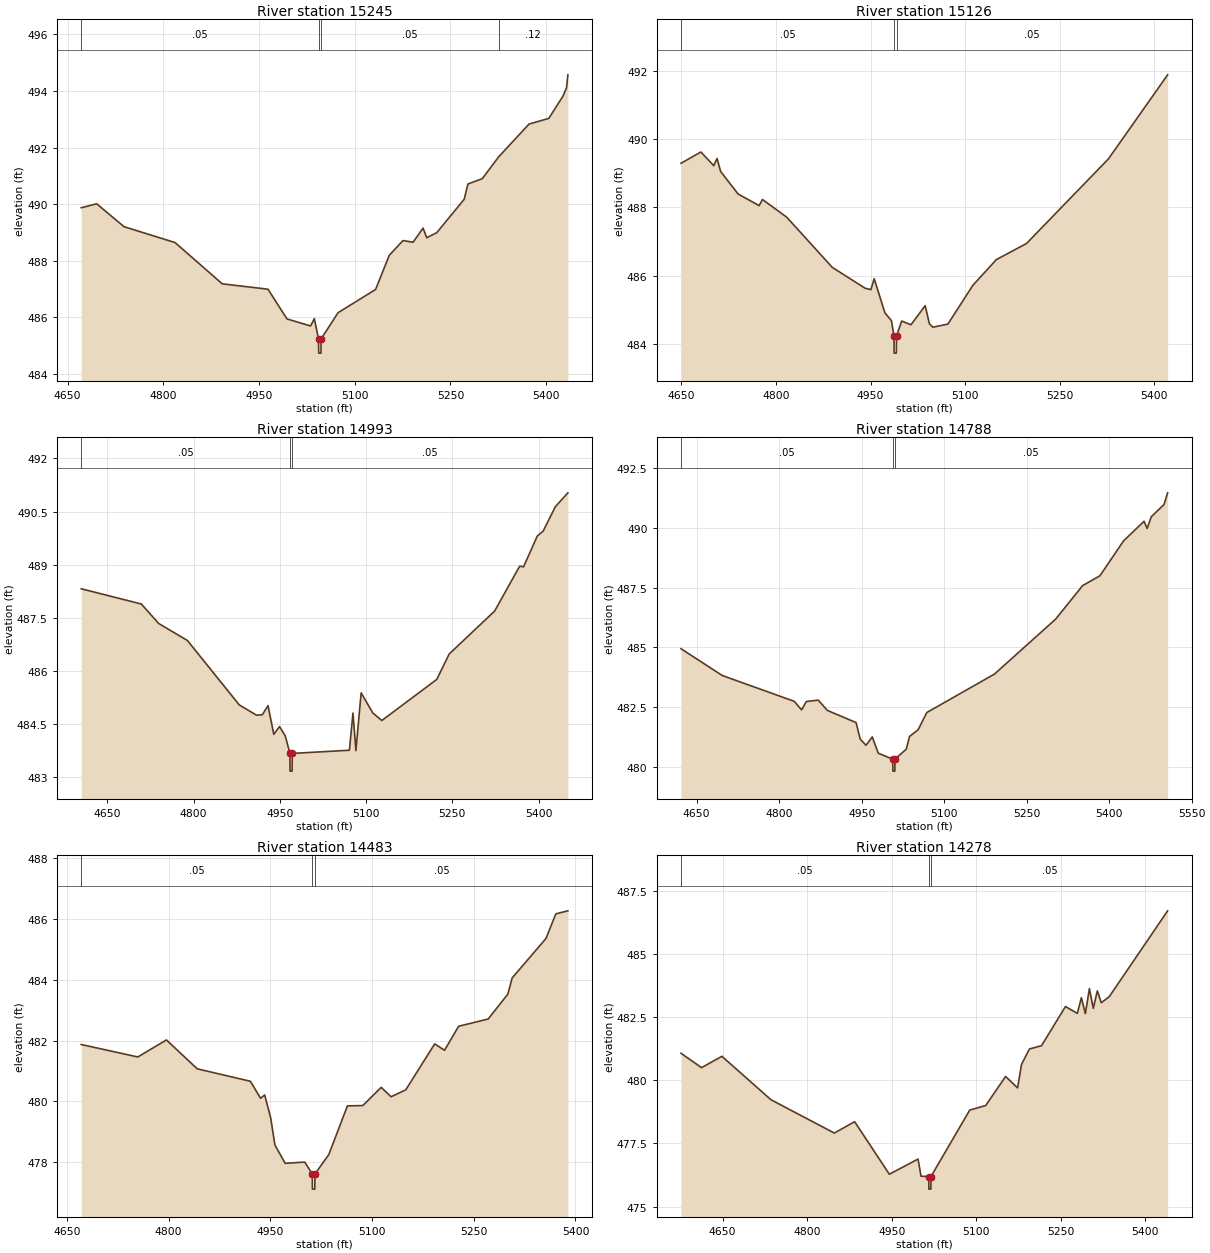
Type RM Length L Ch R = 1,15245,119,119,119
BEGIN DESCRIPTION:
Camp Branch 2102
END DESCRIPTION:
XS GIS Cut Line= 3
      2743057.75      6890691.23      2742775.06      6890858.95
      2742400.21      6891077.67
#Sta/Elev= 30
  4671.3  489.87  4695.5  490.01  4738.4  489.20  4818.3  488.64  4892.3  487.18
  4964.0  486.99  4993.7  485.94  5030.8  485.69  5036.6  485.95  5043.2  485.23
  5043.5  484.73  5047.0  484.73  5047.2  485.23  5073.8  486.16  5132.6  486.98
  5154.1  488.19  5175.5  488.71  5191.3  488.65  5207.0  489.15  5212.8  488.81
  5228.5  488.99  5271.5  490.17  5277.3  490.71  5299.9  490.90  5325.5  491.67
  5373.2  492.83  5404.1  493.03  5426.1  493.81  5431.9  494.11  5434.0  494.57
#Mann=4,-1,0
  4671.3    0.05       0  5043.2    0.04       0  5047.2    0.05       0
  5325.5    0.12       0
Bank Sta=5043.2,5047.2
Exp/Cntr=0.3,0.1

Type RM Length L Ch R = 1,15126,133,133,133
BEGIN DESCRIPTION:
Camp Branch 2101
END DESCRIPTION:
XS GIS Cut Line= 3
      2743056.35      6890660.00      2742719.87      6890758.83
      2742330.83      6890920.51
#Sta/Elev= 30
  4649.3  489.29  4680.9  489.62  4701.3  489.22  4706.5  489.43  4712.2  489.05
  4739.9  488.39  4773.3  488.05  4778.5  488.23  4817.1  487.71  4889.4  486.24
  4941.5  485.63  4950.6  485.59  4955.8  485.91  4972.8  484.91  4983.2  484.68
  4987.2  484.23  4987.4  483.73  4990.9  483.73  4991.2  484.23  4999.4  484.67
  5014.1  484.56  5036.7  485.12  5043.4  484.59  5048.8  484.49  5072.7  484.58
  5112.5  485.72  5149.7  486.47  5197.4  486.94  5327.5  489.42  5421.3  491.88
#Mann=3,-1,0
  4649.3    0.05       0  4987.2    0.04       0  4991.2    0.05       0
Bank Sta=4987.2,4991.2
Exp/Cntr=0.3,0.1

Type RM Length L Ch R = 1,14993,205,205,205
BEGIN DESCRIPTION:
Camp Branch 2100
END DESCRIPTION:
XS GIS Cut Line= 3
      2743070.42      6890621.38      2742672.12      6890640.91
      2742233.92      6890731.26
#Sta/Elev= 30
  4604.7  488.32  4709.2  487.89  4739.3  487.34  4789.3  486.86  4879.5  485.04
  4909.5  484.75  4919.5  484.76  4929.5  485.02  4939.5  484.21  4949.5  484.43
  4959.5  484.16  4967.6  483.67  4967.8  483.17  4971.3  483.17  4971.6  483.67
  5071.0  483.76  5077.2  484.81  5082.3  483.75  5091.4  485.38  5111.8  484.81
  5127.4  484.60  5222.9  485.76  5244.6  486.48  5323.5  487.69  5367.1  488.96
  5373.8  488.94  5397.7  489.81  5407.9  489.95  5429.2  490.64  5450.9  491.03
#Mann=3,-1,0
  4604.7    0.05       0  4967.6    0.04       0  4971.6    0.05       0
Bank Sta=4967.6,4971.6
Exp/Cntr=0.3,0.1

Type RM Length L Ch R = 1,14788,305,305,305
BEGIN DESCRIPTION:
Camp Branch 2099
END DESCRIPTION:
XS GIS Cut Line= 3
      2742974.77      6890299.56      2742618.98      6890454.72
      2742190.35      6890705.59
#Sta/Elev= 30
  4621.5  484.94  4696.5  483.82  4827.4  482.74  4840.8  482.38  4849.3  482.73
  4871.1  482.79  4887.6  482.36  4939.9  481.85  4947.4  481.16  4957.9  480.90
  4969.3  481.25  4980.2  480.57  5006.5  480.32  5006.8  479.82  5010.3  479.82
  5010.5  480.32  5031.2  480.74  5037.0  481.27  5052.7  481.55  5068.4  482.27
  5191.5  483.88  5302.8  486.18  5351.8  487.58  5383.2  487.99  5426.2  489.45
  5463.4  490.27  5469.1  489.97  5476.6  490.46  5499.7  490.97  5506.3  491.46
#Mann=3,-1,0
  4621.5    0.05       0  5006.5    0.04       0  5010.5    0.05       0
Bank Sta=5006.5,5010.5
Exp/Cntr=0.3,0.1

Type RM Length L Ch R = 1,14483,205,205,205
BEGIN DESCRIPTION:
Camp Branch 2097
END DESCRIPTION:
XS GIS Cut Line= 3
      2742789.99      6890019.81      2742517.32      6890197.71
      2742206.43      6890436.53
#Sta/Elev= 30
  4671.2  481.87  4754.6  481.46  4796.8  482.02  4842.2  481.07  4920.6  480.66
  4935.7  480.10  4941.7  480.21  4950.6  479.45  4956.8  478.56  4971.9  477.96
  5000.8  478.00  5011.9  477.61  5012.1  477.11  5015.6  477.11  5015.9  477.61
  5036.3  478.25  5063.7  479.85  5086.4  479.86  5113.5  480.46  5128.1  480.15
  5149.8  480.38  5192.4  481.89  5206.9  481.68  5227.7  482.47  5271.3  482.71
  5300.3  483.53  5306.6  484.06  5356.5  485.36  5371.0  486.17  5388.8  486.27
#Mann=3,-1,0
  4671.2    0.05       0  5011.9    0.04       0  5015.9    0.05       0
Bank Sta=5011.9,5015.9
Exp/Cntr=0.3,0.1

Type RM Length L Ch R = 1,14278,181,181,181
BEGIN DESCRIPTION:
Camp Branch 2098
END DESCRIPTION:
XS GIS Cut Line= 3
      2742783.76      6889913.15      2742375.41      6890059.24
      2742077.60      6890369.00
#Sta/Elev= 30
  4576.1  481.07  4612.6  480.50  4648.7  480.95  4735.7  479.23  4848.2  477.91
  4884.2  478.36  4945.8  476.28  4996.7  476.88  5002.0  476.20  5015.7  476.19
  5015.9  475.69  5019.4  475.69  5019.7  476.19  5088.4  478.82  5116.7  479.00
  5152.0  480.15  5173.3  479.70  5180.3  480.63  5194.4  481.24  5215.8  481.37
  5258.2  482.92  5279.3  482.65  5286.5  483.27  5293.5  482.64  5300.7  483.63
  5307.6  482.85  5314.8  483.54  5321.8  483.07  5335.9  483.31  5439.5  486.71
#Mann=3,-1,0
  4576.1    0.05       0  5015.7    0.04       0  5019.7    0.05       0
Bank Sta=5015.7,5019.7
Exp/Cntr=0.3,0.1

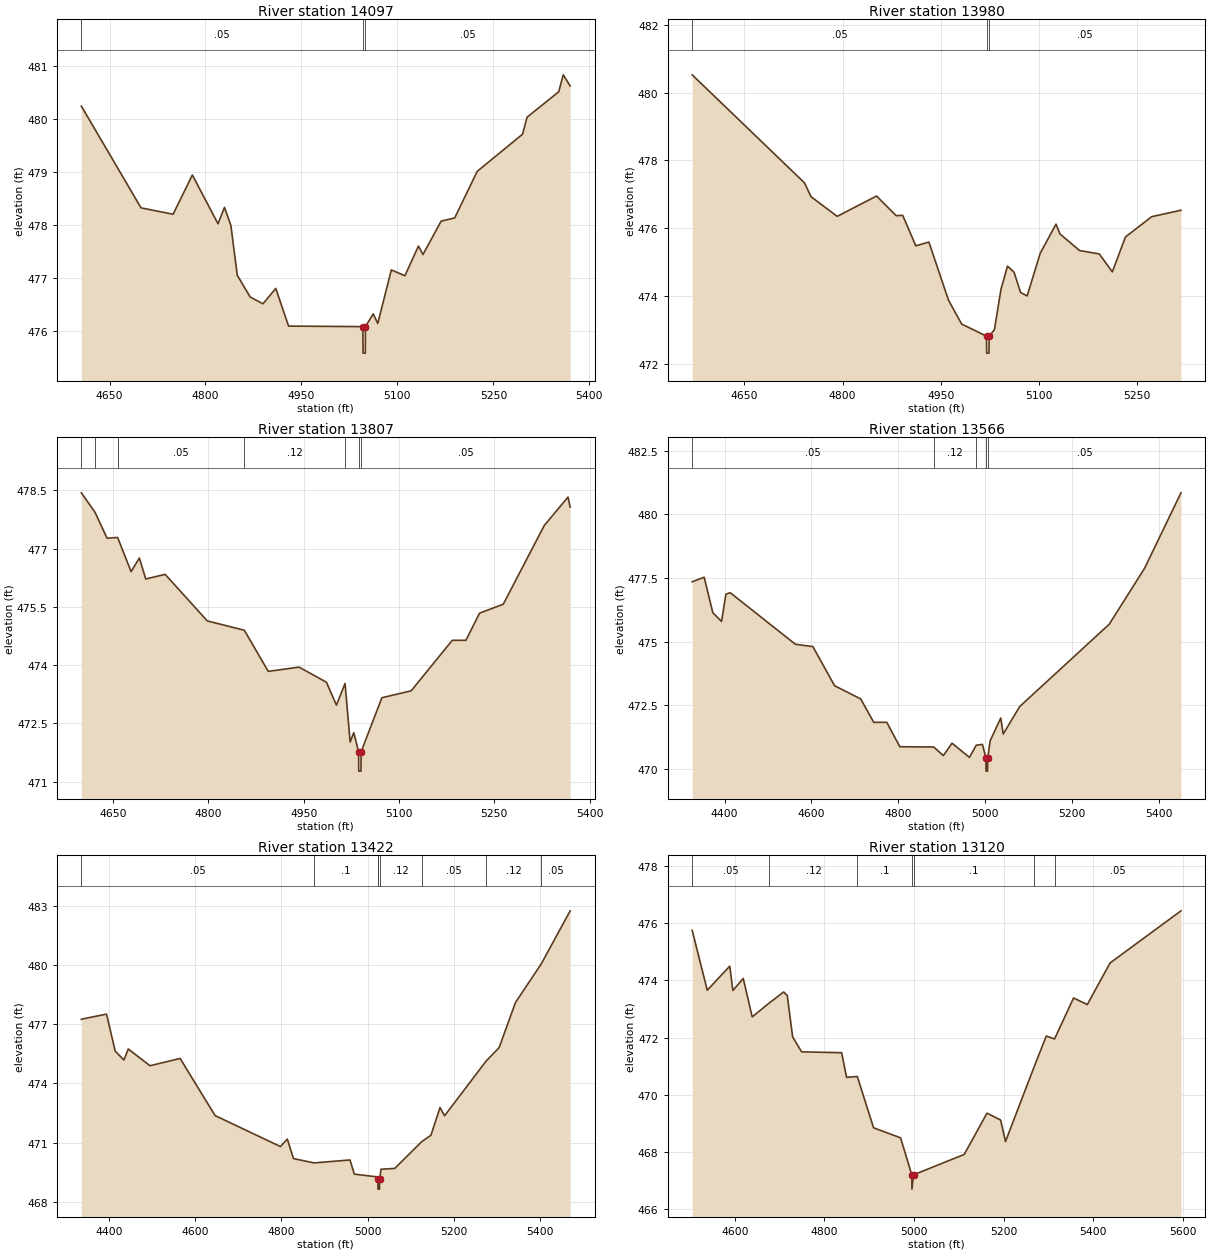
Type RM Length L Ch R = 1,14097,117,117,117
BEGIN DESCRIPTION:
Camp Branch 2093
END DESCRIPTION:
XS GIS Cut Line= 3
      2742718.99      6889862.24      2742298.79      6889894.65
      2742055.54      6890135.84
#Sta/Elev= 30
  4606.0  480.25  4699.3  478.33  4749.4  478.21  4779.5  478.95  4819.6  478.03
  4829.7  478.34  4839.7  478.00  4849.7  477.06  4869.8  476.65  4889.8  476.52
  4909.9  476.81  4929.9  476.10  5046.0  476.09  5046.3  475.59  5049.8  475.59
  5050.0  476.09  5062.2  476.33  5069.3  476.15  5090.5  477.16  5111.7  477.05
  5132.9  477.61  5140.0  477.45  5168.3  478.08  5189.5  478.14  5224.8  479.02
  5295.6  479.72  5302.6  480.04  5352.1  480.52  5359.2  480.84  5370.0  480.63
#Mann=3,-1,0
  4606.0    0.05       0  5046.0    0.04       0  5050.0    0.05       0
Bank Sta=5046,5050
Exp/Cntr=0.3,0.1

Type RM Length L Ch R = 1,13980,173,173,173
BEGIN DESCRIPTION:
Camp Branch 2092
END DESCRIPTION:
XS GIS Cut Line= 3
      2742707.47      6889791.83      2742273.99      6889791.85
      2741961.26      6889802.56
#Sta/Elev= 30
  4570.4  480.53  4741.9  477.34  4751.9  476.93  4791.9  476.35  4851.9  476.95
  4881.9  476.37  4891.9  476.38  4911.9  475.48  4931.9  475.59  4961.9  473.87
  4981.9  473.17  5019.9  472.81  5020.1  472.31  5023.6  472.31  5023.9  472.81
  5031.9  473.00  5041.9  474.19  5051.9  474.88  5061.9  474.70  5071.9  474.10
  5081.9  474.00  5101.9  475.26  5126.0  476.12  5132.0  475.83  5162.0  475.34
  5192.0  475.24  5212.0  474.71  5232.0  475.74  5272.0  476.34  5316.8  476.53
#Mann=3,-1,0
  4570.4    0.05       0  5019.9    0.04       0  5023.9    0.05       0
Bank Sta=5019.9,5023.9
Exp/Cntr=0.3,0.1

Type RM Length L Ch R = 1,13807,241,241,241
BEGIN DESCRIPTION:
Camp Branch 2094
END DESCRIPTION:
XS GIS Cut Line= 3
      2742595.96      6889669.67      2742262.88      6889612.35
      2741889.52      6889828.52
#Sta/Elev= 30
  4600.1  478.44  4621.6  477.94  4640.6  477.27  4657.2  477.29  4678.4  476.41
  4691.4  476.76  4701.5  476.22  4732.0  476.34  4798.3  475.14  4856.6  474.90
  4894.3  473.84  4942.8  473.95  4985.9  473.56  5001.6  472.97  5015.2  473.53
  5023.2  472.02  5028.9  472.26  5036.5  471.77  5036.7  471.27  5040.2  471.27
  5040.5  471.77  5073.1  473.16  5119.3  473.34  5183.9  474.64  5205.4  474.64
  5226.9  475.34  5264.2  475.57  5328.8  477.60  5366.1  478.33  5369.5  478.07
#Mann=7,-1,0
  4600.1    0.05       0  4621.6    0.12       0  4657.2    0.05       0
  4856.6    0.12       0  5015.2    0.05       0  5036.5    0.07       0
  5040.5    0.05       0
Bank Sta=5036.5,5040.5
Exp/Cntr=0.3,0.1

Type RM Length L Ch R = 1,13566,144,144,144
BEGIN DESCRIPTION:
Camp Branch 2096
END DESCRIPTION:
XS GIS Cut Line= 3
      2742061.47      6888833.45      2742034.03      6889521.15
      2741822.48      6889903.14
#Sta/Elev= 30
  4325.5  477.35  4353.1  477.53  4373.1  476.13  4393.1  475.79  4403.1  476.86
  4413.1  476.92  4563.2  474.89  4603.3  474.80  4653.3  473.26  4713.4  472.74
  4743.4  471.82  4773.4  471.82  4803.4  470.86  4881.4  470.85  4903.5  470.51
  4923.5  471.00  4963.6  470.44  4979.3  470.92  4993.6  470.95  5001.6  470.40
  5001.8  469.90  5005.3  469.90  5005.6  470.40  5011.2  471.09  5035.7  471.99
  5041.4  471.36  5079.2  472.44  5285.3  475.68  5366.6  477.88  5450.4  480.85
#Mann=5,-1,0
  4325.5    0.05       0  4881.4    0.12       0  4979.3    0.05       0
  5001.6    0.04       0  5005.6    0.05       0
Bank Sta=5001.6,5005.6
Exp/Cntr=0.3,0.1

Type RM Length L Ch R = 1,13422,302,302,302
BEGIN DESCRIPTION:
Camp Branch 2095
END DESCRIPTION:
XS GIS Cut Line= 3
      2741989.58      6888803.12      2741907.72      6889466.18
      2741761.44      6889907.27
#Sta/Elev= 30
  4336.5  477.26  4394.8  477.52  4415.0  475.64  4435.1  475.19  4445.2  475.75
  4495.6  474.90  4565.4  475.27  4646.5  472.37  4797.9  470.80  4813.8  471.18
  4828.1  470.19  4875.6  469.97  4959.1  470.12  4969.1  469.40  5022.9  469.26
  5023.7  469.14  5024.0  468.64  5027.5  468.64  5027.7  469.14  5031.0  469.65
  5062.7  469.69  5125.3  471.05  5146.6  471.37  5167.7  472.78  5178.2  472.36
  5274.6  475.14  5304.7  475.82  5342.6  478.11  5402.1  480.06  5469.3  482.76
#Mann=8,-1,0
  4336.5    0.05       0  4875.6     0.1       0  5022.9    0.12       0
  5023.7    0.07       0  5027.7    0.12       0  5125.3    0.05       0
  5274.6    0.12       0  5402.1    0.05       0
Bank Sta=5023.7,5027.7
Exp/Cntr=0.3,0.1

Type RM Length L Ch R = 1,13120,278,278,278
BEGIN DESCRIPTION:
Camp Branch 2091
END DESCRIPTION:
XS GIS Cut Line= 3
      2741718.59      6888817.42      2741678.22      6889310.03
      2741567.48      6889896.51
#Sta/Elev= 30
  4504.9  475.74  4538.6  473.65  4588.8  474.49  4595.8  473.64  4618.9  474.06
  4638.9  472.72  4677.5  473.21  4709.2  473.59  4717.2  473.46  4729.2  472.02
  4749.3  471.50  4838.6  471.47  4849.6  470.61  4873.5  470.64  4909.8  468.85
  4970.1  468.50  4995.1  467.21  4995.4  466.71  4999.1  467.21  5112.1  467.92
  5163.0  469.36  5193.5  469.12  5204.3  468.37  5268.8  471.00  5295.3  472.05
  5313.8  471.95  5356.3  473.38  5386.9  473.15  5437.7  474.60  5596.0  476.42
#Mann=7,-1,0
  4504.9    0.05       0  4677.5    0.12       0  4873.5     0.1       0
  4995.1    0.07       0  4999.1     0.1       0  5268.8    0.12       0
  5313.8    0.05       0
Bank Sta=4995.1,4999.1
Exp/Cntr=0.3,0.1

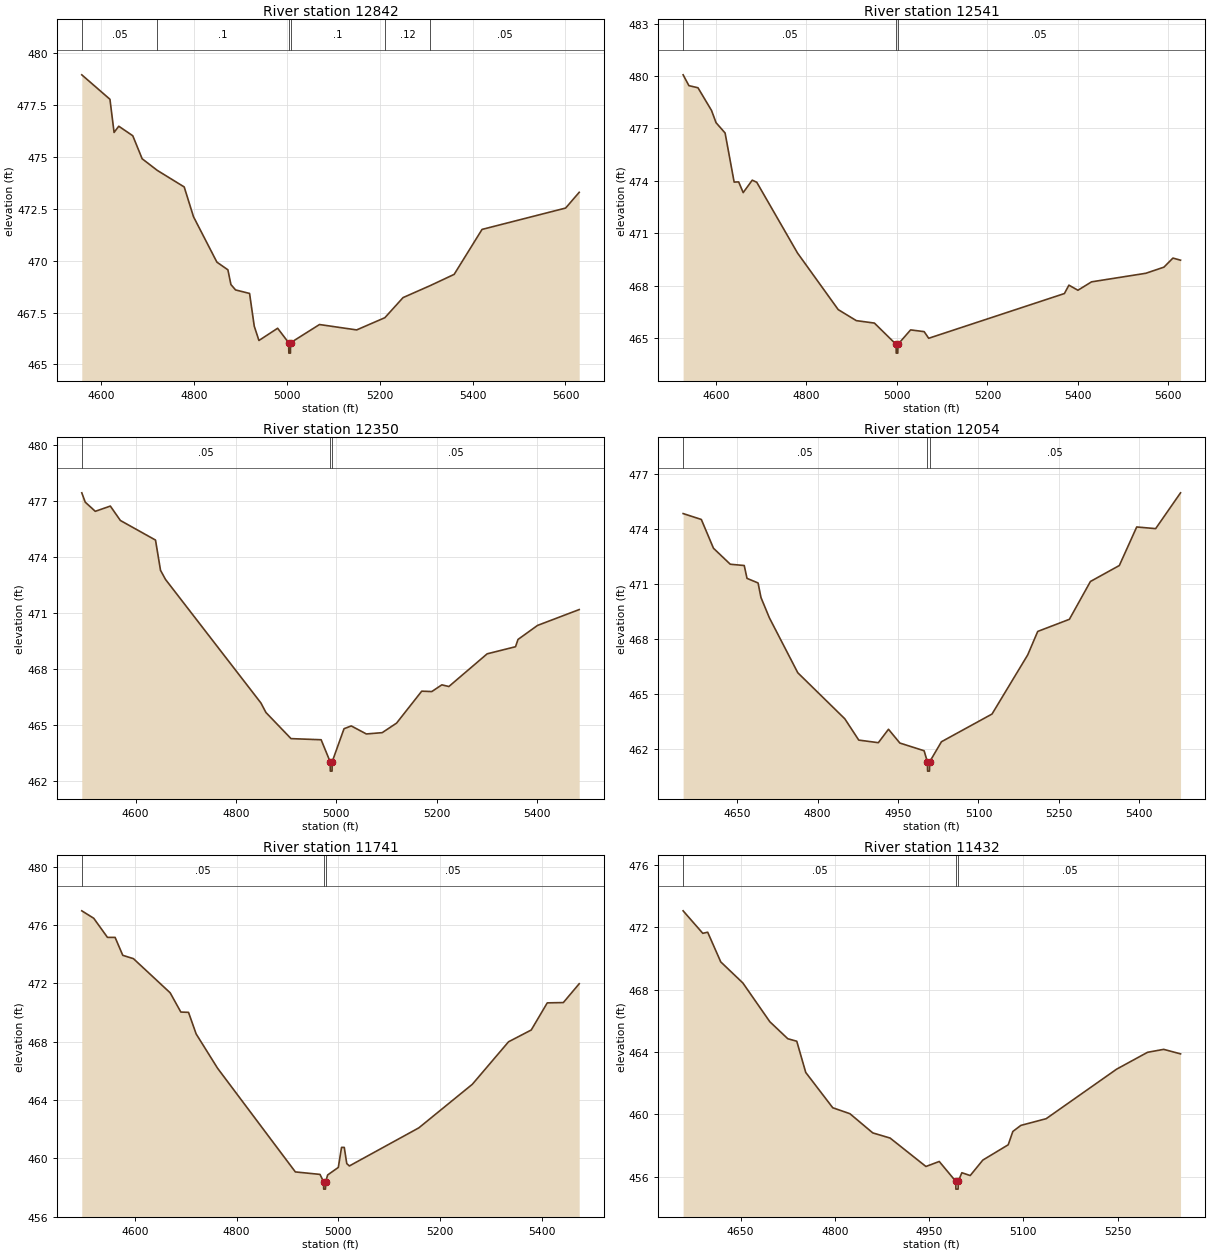
Type RM Length L Ch R = 1,12842,301,301,301
BEGIN DESCRIPTION:
Camp Branch 2090
END DESCRIPTION:
XS GIS Cut Line= 3
      2741467.64      6888821.84      2741415.20      6889267.38
      2741389.32      6889890.23
#Sta/Elev= 30
  4557.6  478.97  4618.3  477.79  4627.2  476.19  4637.3  476.49  4667.5  476.03
  4687.7  474.92  4720.2  474.36  4778.3  473.56  4798.4  472.12  4848.8  469.93
  4872.5  469.56  4879.0  468.85  4889.0  468.59  4919.2  468.42  4929.3  466.84
  4939.4  466.15  4979.7  466.74  5003.5  466.04  5003.8  465.54  5007.3  465.54
  5007.5  466.04  5069.9  466.92  5150.0  466.66  5210.8  467.25  5250.0  468.22
  5308.7  468.80  5360.1  469.34  5420.2  471.51  5600.3  472.54  5629.6  473.30
#Mann=6,-1,0
  4557.6    0.05       0  4720.2     0.1       0  5003.5    0.07       0
  5007.5     0.1       0  5210.8    0.12       0  5308.7    0.05       0
Bank Sta=5003.5,5007.5
Exp/Cntr=0.3,0.1

Type RM Length L Ch R = 1,12541,191,191,191
BEGIN DESCRIPTION:
Camp Branch 2068
END DESCRIPTION:
XS GIS Cut Line= 3
      2741149.90      6888788.19      2741141.43      6889265.94
      2741147.06      6889887.79
#Sta/Elev= 30
  4527.3  480.07  4540.1  479.45  4560.1  479.33  4590.1  478.03  4600.1  477.33
  4620.1  476.74  4640.1  473.93  4650.1  473.94  4660.1  473.33  4680.1  474.04
  4690.1  473.92  4780.2  469.87  4870.2  466.63  4910.2  466.00  4950.2  465.86
  4998.2  464.64  4998.4  464.14  5001.9  464.14  5002.2  464.64  5030.2  465.47
  5060.2  465.37  5070.2  464.99  5370.2  467.55  5380.2  468.03  5400.2  467.74
  5430.2  468.22  5550.2  468.71  5590.2  469.06  5610.2  469.58  5627.0  469.46
#Mann=3,-1,0
  4527.3    0.05       0  4998.2    0.05       0  5002.2    0.05       0
Bank Sta=4998.2,5002.2
Exp/Cntr=0.3,0.1

Type RM Length L Ch R = 1,12350,296,296,296
BEGIN DESCRIPTION:
Camp Branch 2067
END DESCRIPTION:
XS GIS Cut Line= 3
      2740967.08      6888704.09      2740966.33      6889227.13
      2740931.72      6889693.91
#Sta/Elev= 30
  4492.7  477.43  4499.6  476.93  4519.6  476.44  4549.6  476.72  4569.6  475.95
  4639.6  474.90  4649.6  473.28  4659.6  472.79  4849.6  466.18  4859.6  465.67
  4909.6  464.27  4969.6  464.21  4987.6  463.03  4987.9  462.53  4991.4  462.53
  4991.6  463.03  5015.2  464.80  5029.6  464.95  5059.7  464.52  5091.3  464.59
  5119.9  465.10  5170.0  466.81  5190.1  466.79  5210.1  467.15  5224.1  467.06
  5300.4  468.81  5356.9  469.19  5361.9  469.58  5400.7  470.33  5483.8  471.18
#Mann=3,-1,0
  4492.7    0.05       0  4987.6    0.04       0  4991.6    0.05       0
Bank Sta=4987.6,4991.6
Exp/Cntr=0.3,0.1

Type RM Length L Ch R = 1,12054,313,313,313
BEGIN DESCRIPTION:
Camp Branch 2069
END DESCRIPTION:
XS GIS Cut Line= 3
      2740858.16      6888718.90      2740713.14      6889141.42
      2740532.61      6889586.70
#Sta/Elev= 30
  4549.5  474.84  4583.4  474.52  4606.1  472.95  4637.4  472.08  4663.4  472.01
  4668.6  471.31  4689.2  471.06  4694.6  470.27  4710.3  469.16  4763.2  466.17
  4850.9  463.66  4876.9  462.50  4913.4  462.36  4932.3  463.09  4953.5  462.34
  4998.7  461.92  5004.9  461.31  5005.2  460.81  5008.7  460.81  5008.9  461.31
  5031.0  462.41  5125.3  463.92  5191.8  467.14  5210.5  468.42  5269.5  469.08
  5308.7  471.14  5362.6  472.01  5395.0  474.11  5430.3  474.02  5476.7  475.97
#Mann=3,-1,0
  4549.5    0.05       0  5004.9    0.05       0  5008.9    0.05       0
Bank Sta=5004.9,5008.9
Exp/Cntr=0.3,0.1

Type RM Length L Ch R = 1,11741,309,309,309
BEGIN DESCRIPTION:
Camp Branch 2070
END DESCRIPTION:
XS GIS Cut Line= 3
      2740747.06      6888581.11      2740464.03      6889007.33
      2740318.51      6889450.62
#Sta/Elev= 30
  4495.6  476.98  4519.1  476.47  4546.1  475.16  4561.1  475.16  4576.2  473.93
  4597.2  473.70  4669.4  471.36  4690.4  470.04  4705.5  470.02  4720.5  468.54
  4762.6  466.19  4915.6  459.08  4964.1  458.91  4971.1  458.40  4971.3  457.90
  4974.8  457.90  4975.1  458.40  4979.1  458.87  5000.1  459.39  5006.4  460.76
  5011.8  460.76  5016.7  459.65  5021.9  459.49  5158.4  462.10  5263.7  465.09
  5334.8  468.00  5379.5  468.81  5411.0  470.67  5442.6  470.69  5473.8  471.98
#Mann=3,-1,0
  4495.6    0.05       0  4971.1    0.05       0  4975.1    0.05       0
Bank Sta=4971.1,4975.1
Exp/Cntr=0.3,0.1

Type RM Length L Ch R = 1,11432,306,306,306
BEGIN DESCRIPTION:
Camp Branch 2066
END DESCRIPTION:
XS GIS Cut Line= 3
      2740517.97      6888468.28      2740231.07      6888811.27
      2740187.71      6889153.17
#Sta/Elev= 30
  4558.5  473.04  4589.8  471.60  4597.6  471.67  4618.4  469.77  4653.6  468.42
  4696.5  465.94  4725.1  464.85  4739.4  464.69  4753.7  462.69  4796.7  460.43
  4824.0  460.05  4860.4  458.82  4888.0  458.49  4945.0  456.67  4966.2  456.99
  4992.5  455.72  4992.7  455.22  4996.2  455.22  4996.5  455.72  5002.2  456.27
  5015.5  456.09  5035.6  457.08  5076.0  458.06  5083.3  458.91  5096.1  459.30
  5136.4  459.73  5248.5  462.90  5297.7  463.98  5323.5  464.17  5350.3  463.88
#Mann=3,-1,0
  4558.5    0.05       0  4992.5    0.04       0  4996.5    0.05       0
Bank Sta=4992.5,4996.5
Exp/Cntr=0.3,0.1

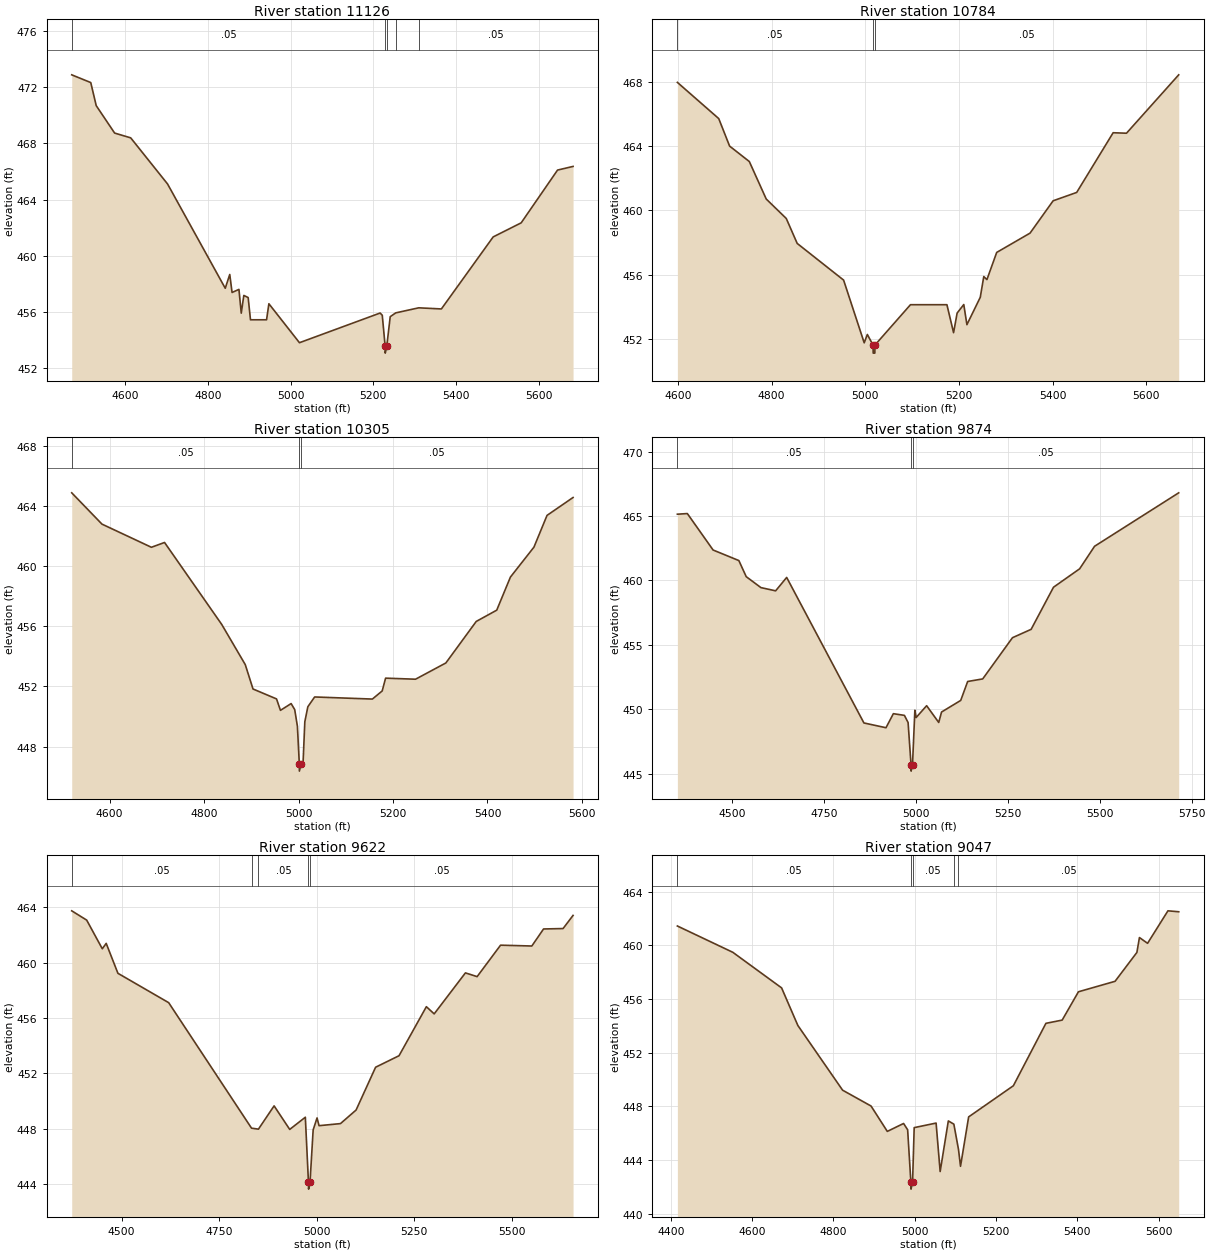
Type RM Length L Ch R = 1,11126,342,342,342
BEGIN DESCRIPTION:
Camp Branch 2065
END DESCRIPTION:
XS GIS Cut Line= 3
      2740466.99      6888390.88      2739956.57      6888649.73
      2739339.81      6888819.12
#Sta/Elev= 30
  4471.1  472.87  4517.1  472.32  4530.3  470.68  4574.8  468.73  4613.7  468.39
  4702.8  465.11  4842.2  457.70  4853.1  458.68  4858.7  457.40  4875.3  457.62
  4880.9  455.93  4887.1  457.19  4897.6  457.04  4903.2  455.46  4942.1  455.46
  4947.7  456.60  5021.6  453.83  5216.6  455.94  5221.8  455.78  5228.7  453.59
  5228.9  453.09  5232.7  453.59  5241.0  455.68  5254.3  455.95  5309.8  456.31
  5364.7  456.23  5489.9  461.35  5557.6  462.35  5645.5  466.10  5683.0  466.36
#Mann=5,-1,0
  4471.1    0.05       0  5228.7    0.04       0  5232.7    0.05       0
  5254.3    0.12       0  5309.8    0.05       0
Bank Sta=5228.7,5232.7
Exp/Cntr=0.3,0.1

Type RM Length L Ch R = 1,10784,479,479,479
BEGIN DESCRIPTION:
Camp Branch 2064
END DESCRIPTION:
XS GIS Cut Line= 3
      2740099.43      6888181.20      2739777.72      6888395.68
      2739263.30      6888846.11
#Sta/Elev= 30
  4598.9  467.96  4687.2  465.71  4710.4  464.00  4752.5  463.04  4788.6  460.71
  4831.4  459.50  4854.7  457.95  4953.8  455.67  4997.8  451.77  5004.5  452.29
  5016.7  451.63  5017.0  451.13  5020.5  451.13  5020.7  451.63  5096.6  454.14
  5174.4  454.14  5188.6  452.40  5196.2  453.62  5210.4  454.15  5217.1  452.90
  5245.6  454.60  5253.1  455.89  5259.8  455.70  5280.7  457.39  5351.9  458.59
  5401.2  460.60  5451.5  461.12  5529.3  464.83  5557.8  464.80  5669.3  468.43
#Mann=3,-1,0
  4598.9    0.05       0  5016.7    0.04       0  5020.7    0.05       0
Bank Sta=5016.7,5020.7
Exp/Cntr=0.3,0.1

Type RM Length L Ch R = 1,10305,431,431,431
BEGIN DESCRIPTION:
Camp Branch 2062
END DESCRIPTION:
XS GIS Cut Line= 3
      2739917.63      6887806.29      2739486.85      6888031.55
      2739032.49      6888384.41
#Sta/Elev= 30
  4519.8  464.87  4583.8  462.79  4688.5  461.25  4716.3  461.57  4837.4  456.12
  4887.2  453.45  4903.6  451.83  4953.4  451.17  4961.7  450.41  4984.3  450.86
  4991.9  450.46  4997.6  449.35  5001.6  446.87  5001.8  446.37  5005.6  446.87
  5009.5  446.87  5013.3  449.65  5019.7  450.65  5034.1  451.30  5156.3  451.16
  5177.1  451.70  5184.3  452.55  5247.7  452.48  5311.9  453.56  5376.2  456.32
  5419.6  457.07  5448.6  459.27  5498.4  461.26  5526.1  463.37  5581.2  464.56
#Mann=3,-1,0
  4519.8    0.05       0  5001.6    0.04       0  5005.6    0.05       0
Bank Sta=5001.6,5005.6
Exp/Cntr=0.3,0.1

Type RM Length L Ch R = 1,9874,252,252,252
BEGIN DESCRIPTION:
Camp Branch 2063
END DESCRIPTION:
XS GIS Cut Line= 3
      2739973.09      6887696.78      2739324.20      6887715.95
      2738620.52      6887837.66
#Sta/Elev= 30
  4351.6  465.14  4378.7  465.19  4448.7  462.36  4518.8  461.54  4538.8  460.29
  4578.8  459.44  4618.8  459.19  4648.8  460.23  4858.9  448.93  4918.9  448.56
  4938.9  449.65  4969.0  449.52  4979.0  448.96  4987.0  445.69  4987.2  445.19
  4991.0  445.69  4997.4  449.92  5000.8  449.35  5029.4  450.27  5062.3  448.97
  5070.0  449.78  5122.1  450.68  5141.0  452.15  5181.9  452.35  5262.8  455.55
  5313.6  456.20  5374.4  459.47  5445.5  460.90  5486.1  462.65  5714.9  466.80
#Mann=3,-1,0
  4351.6    0.05       0  4987.0    0.04       0  4991.0    0.05       0
Bank Sta=4987,4991
Exp/Cntr=0.3,0.1

Type RM Length L Ch R = 1,9622,575,575,575
BEGIN DESCRIPTION:
Camp Branch 2061
END DESCRIPTION:
XS GIS Cut Line= 3
      2739954.25      6887498.90      2739320.76      6887490.74
      2738670.36      6887482.17
#Sta/Elev= 30
  4372.5  463.74  4410.8  463.07  4450.8  461.00  4460.8  461.39  4490.8  459.23
  4620.8  457.11  4833.0  448.05  4850.7  447.98  4890.8  449.66  4930.8  447.96
  4970.8  448.84  4978.8  444.15  4979.1  443.65  4982.8  444.15  4990.8  447.92
  5000.8  448.79  5005.9  448.23  5060.8  448.38  5100.8  449.36  5150.8  452.45
  5210.8  453.28  5280.8  456.82  5300.8  456.30  5380.8  459.26  5410.8  458.99
  5470.8  461.26  5550.9  461.20  5580.9  462.43  5630.9  462.46  5656.5  463.41
#Mann=5,-1,0
  4372.5    0.05       0  4833.0    0.12       0  4850.7    0.05       0
  4978.8    0.04       0  4982.8    0.05       0
Bank Sta=4978.8,4982.8
Exp/Cntr=0.3,0.1

Type RM Length L Ch R = 1,9047,333,333,333
BEGIN DESCRIPTION:
Camp Branch 2060
END DESCRIPTION:
XS GIS Cut Line= 3
      2740052.34      6887078.69      2739468.80      6887064.78
      2738819.49      6887042.41
#Sta/Elev= 30
  4416.3  461.44  4552.7  459.48  4672.7  456.83  4712.7  454.03  4822.8  449.21
  4892.8  448.03  4932.8  446.14  4972.8  446.73  4982.8  446.26  4990.8  442.34
  4991.1  441.84  4994.9  442.34  4998.9  446.42  5052.8  446.76  5062.8  443.15
  5082.9  446.92  5096.5  446.68  5107.9  444.80  5112.9  443.54  5132.9  447.22
  5242.9  449.54  5323.0  454.19  5363.0  454.43  5403.0  456.54  5493.1  457.32
  5546.8  459.47  5553.1  460.58  5573.1  460.15  5623.2  462.57  5649.7  462.50
#Mann=5,-1,0
  4416.3    0.05       0  4990.8    0.04       0  4994.9    0.05       0
  5096.5    0.12       0  5107.9    0.05       0
Bank Sta=4990.8,4994.9
Exp/Cntr=0.3,0.1

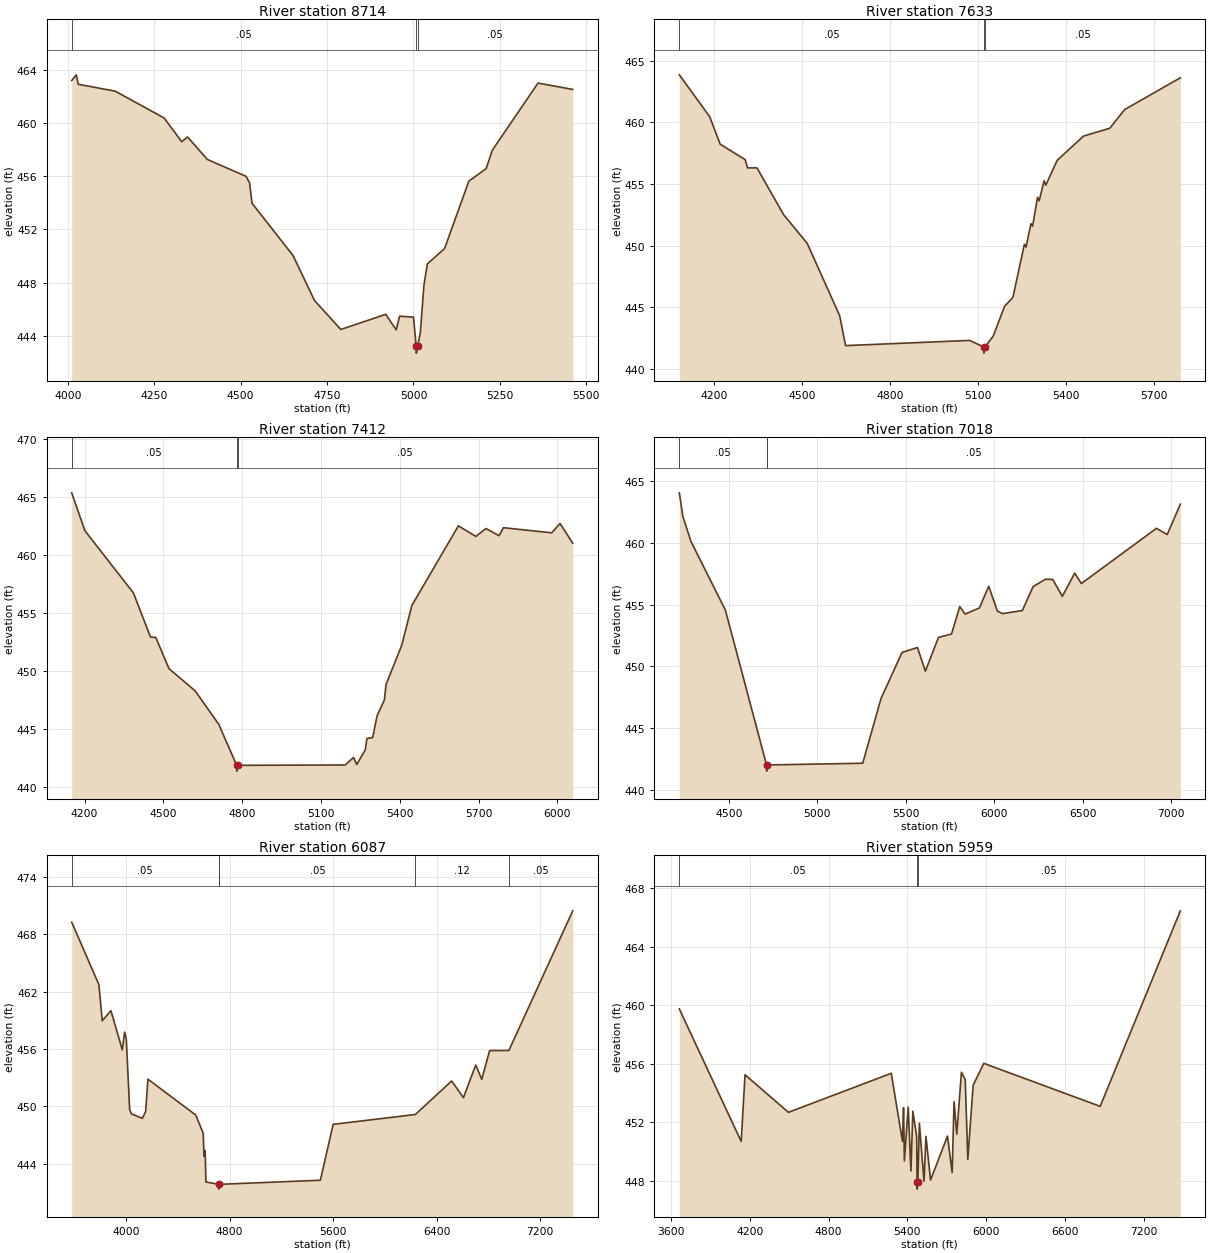
Type RM Length L Ch R = 1,8714,1081,1081,1081
BEGIN DESCRIPTION:
Camp Branch 2059
END DESCRIPTION:
XS GIS Cut Line= 3
      2740239.38      6887123.45      2739560.60      6886795.53
      2738865.65      6886766.41
#Sta/Elev= 30
  4011.4  463.20  4024.6  463.63  4030.2  462.92  4137.3  462.40  4278.8  460.38
  4329.5  458.60  4346.6  458.95  4403.9  457.26  4515.9  455.99  4526.0  455.49
  4532.9  453.97  4651.5  450.04  4713.7  446.65  4789.9  444.47  4920.0  445.61
  4950.0  444.44  4960.0  445.47  5000.0  445.40  5008.0  443.19  5008.3  442.69
  5012.1  443.19  5020.1  444.29  5030.1  447.76  5040.1  449.40  5090.1  450.56
  5160.2  455.63  5210.2  456.57  5228.4  457.97  5360.4  463.01  5460.8  462.53
#Mann=3,-1,0
  4011.4    0.05       0  5008.0    0.04       0  5012.1    0.05       0
Bank Sta=5008,5012.1
Exp/Cntr=0.3,0.1

Type RM Length L Ch R = 1,7633,221,221,221
BEGIN DESCRIPTION:
Camp Branch 2058
END DESCRIPTION:
XS GIS Cut Line= 3
      2740388.94      6885881.39      2739311.21      6885994.70
      2738754.49      6886272.37
#Sta/Elev= 30
  4082.9  463.85  4186.4  460.45  4222.1  458.22  4307.1  456.97  4315.2  456.30
  4347.3  456.30  4437.8  452.51  4518.2  450.18  4628.8  444.31  4648.9  441.88
  5071.3  442.30  5119.3  441.77  5119.7  441.27  5123.7  441.77  5151.7  442.66
  5190.5  445.08  5218.5  445.78  5257.7  450.10  5263.2  449.87  5280.0  451.77
  5285.6  451.56  5302.4  453.92  5308.0  453.63  5324.8  455.26  5330.4  454.89
  5369.5  456.92  5459.1  458.88  5548.6  459.52  5598.9  461.03  5788.7  463.61
#Mann=3,-1,0
  4082.9    0.05       0  5119.3    0.03       0  5123.7    0.05       0
Bank Sta=5119.3,5123.7
Exp/Cntr=0.3,0.1

Type RM Length L Ch R = 1,7412,394,394,394
BEGIN DESCRIPTION:
Camp Branch 44
END DESCRIPTION:
XS GIS Cut Line= 3
      2740426.01      6885811.00      2739465.71      6885790.56
      2738625.11      6886226.87
#Sta/Elev= 30
  4151.2  465.38  4201.2  462.12  4386.2  456.74  4451.3  452.93  4471.3  452.90
  4521.3  450.22  4621.3  448.29  4711.3  445.40  4779.2  441.87  4779.6  441.37
  4783.6  441.87  5192.3  441.90  5224.1  442.55  5236.5  441.94  5269.1  443.22
  5275.1  444.18  5297.2  444.27  5313.7  446.14  5341.5  447.50  5348.0  448.85
  5407.8  452.23  5446.4  455.67  5623.4  462.53  5689.8  461.62  5728.4  462.30
  5778.2  461.68  5794.7  462.37  5978.9  461.93  6010.3  462.74  6058.8  461.03
#Mann=3,-1,0
  4151.2    0.05       0  4779.2    0.03       0  4783.6    0.05       0
Bank Sta=4779.2,4783.6
Exp/Cntr=0.3,0.1

Type RM Length L Ch R = 1,7018,931,931,931
BEGIN DESCRIPTION:
Camp Branch 2010
END DESCRIPTION:
XS GIS Cut Line= 4
      2740407.73      6885765.08      2739696.71      6885436.41
      2739073.08      6885090.23      2737752.54      6885282.22
#Sta/Elev= 30
  4220.8  464.08  4240.8  462.17  4286.7  460.13  4481.2  454.56  4713.6  442.00
  4714.2  441.50  4718.4  442.00  5257.2  442.14  5360.2  447.38  5479.2  451.13
  5566.2  451.53  5611.1  449.61  5685.2  452.35  5758.7  452.62  5805.4  454.85
  5835.7  454.24  5916.5  454.74  5969.1  456.50  6017.6  454.49  6047.9  454.28
  6159.1  454.53  6219.7  456.47  6290.4  457.07  6330.8  457.05  6384.7  455.68
  6454.8  457.56  6492.5  456.72  6916.9  461.20  6977.6  460.70  7051.8  463.16
#Mann=3,-1,0
  4220.8    0.05       0  4713.6    0.03       0  4718.4    0.05       0
Bank Sta=4713.6,4718.4
Exp/Cntr=0.3,0.1

Type RM Length L Ch R = 1,6087,128,128,128
BEGIN DESCRIPTION:
Camp Branch 2008
END DESCRIPTION:
XS GIS Cut Line= 4
      2740529.69      6885836.72      2740262.79      6885075.84
      2739505.60      6883993.09      2737780.72      6883734.70
#Sta/Elev= 30
  3579.8  469.26  3789.9  462.72  3815.6  458.94  3882.9  460.00  3970.6  455.90
  3988.6  457.75  4001.6  457.03  4027.3  449.66  4041.5  449.19  4126.3  448.73
  4151.3  449.46  4168.7  452.83  4538.5  449.07  4596.0  447.16  4602.1  444.75
  4610.8  445.37  4616.9  442.07  4715.6  441.82  4716.2  441.32  4720.5  441.82
  5501.2  442.25  5600.1  448.10  6235.1  449.13  6515.9  452.64  6606.9  450.89
  6701.6  454.31  6748.5  452.81  6809.1  455.82  6957.9  455.83  7451.5  470.45
#Mann=5,-1,0
  3579.8    0.05       0  4715.6    0.03       0  4720.5    0.05       0
  6235.1    0.12       0  6957.9    0.05       0
Bank Sta=4715.6,4720.5
Exp/Cntr=0.3,0.1

Type RM Length L Ch R = 1,5959,128,128,128
BEGIN DESCRIPTION:
Camp Branch 2006
END DESCRIPTION:
XS GIS Cut Line= 6
      2740892.72      6885377.78      2740440.02      6885149.34
      2740263.90      6884906.15      2739969.23      6884466.18
      2739451.00      6883786.00      2737850.37      6883513.15
#Sta/Elev= 30
  3663.8  459.75  4135.0  450.69  4164.2  455.25  4494.9  452.68  5277.9  455.35
  5363.1  450.70  5371.4  453.00  5377.7  449.36  5406.7  453.04  5427.6  448.67
  5442.1  452.76  5471.2  451.05  5474.8  447.93  5475.5  447.43  5480.1  447.93
  5492.0  451.93  5527.3  447.97  5541.9  451.04  5577.2  448.05  5706.1  451.06
  5741.5  448.57  5756.0  453.41  5776.8  451.19  5812.2  455.42  5841.2  454.91
  5860.8  449.47  5901.4  454.53  5982.6  456.03  6868.8  453.09  7479.5  466.46
#Mann=3,-1,0
  3663.8    0.05       0  5474.8    0.03       0  5480.1    0.05       0
Bank Sta=5474.8,5480.1
Exp/Cntr=0.3,0.1