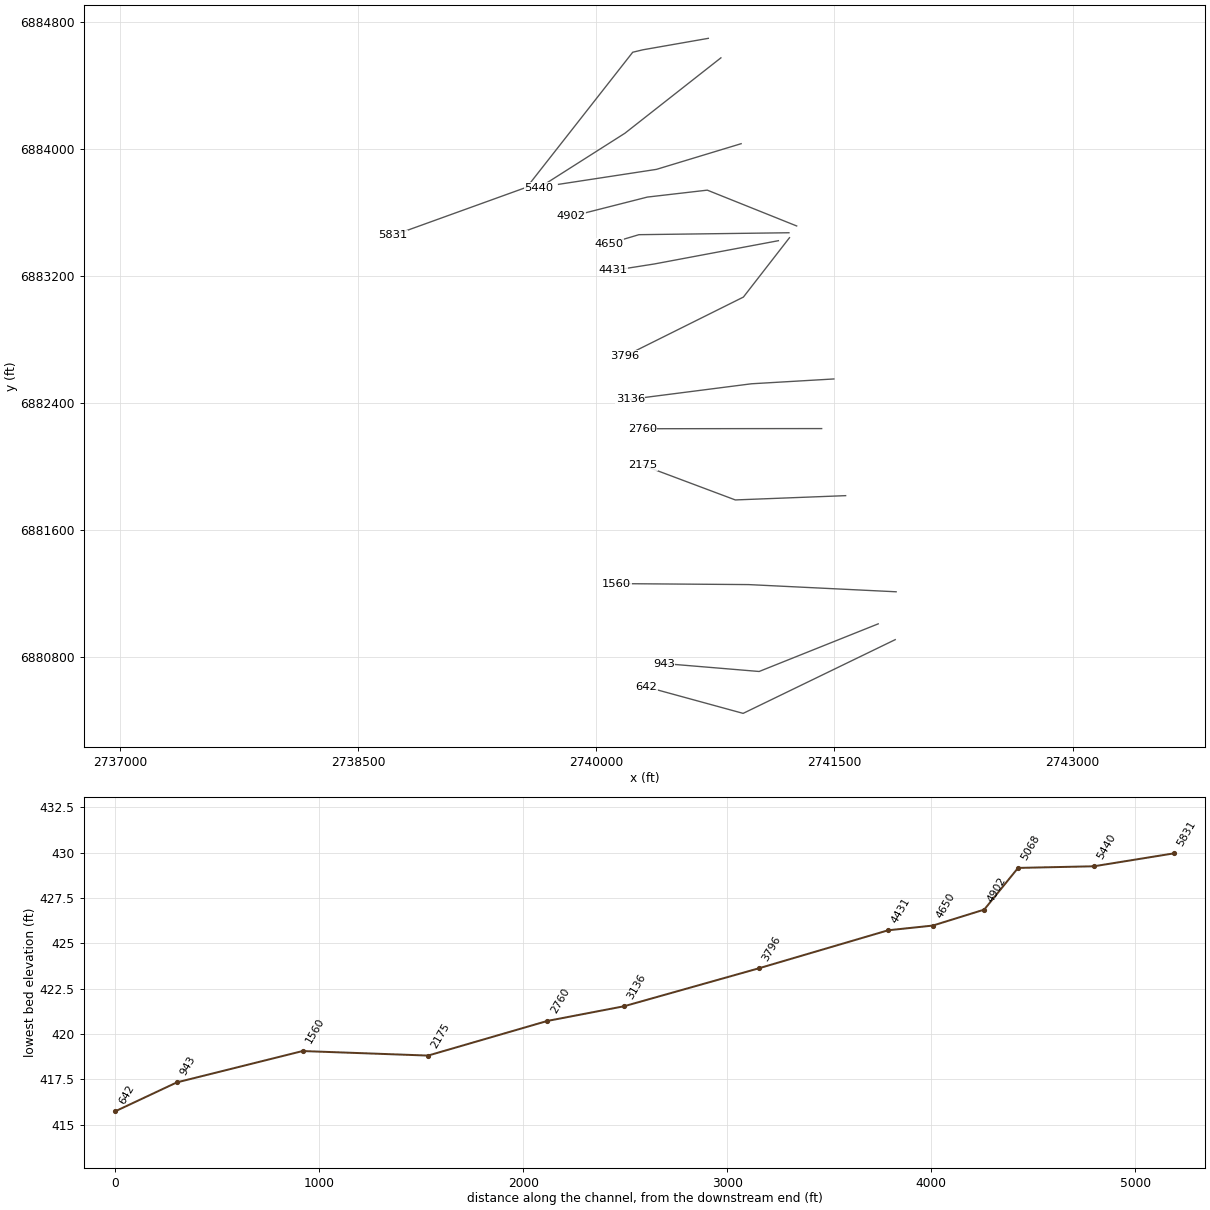
HEC-RAS study Camp Branch.prj: Camp Branch Base Level Engineering

--- Camp Branch.g01 (geometry) --- (continued)

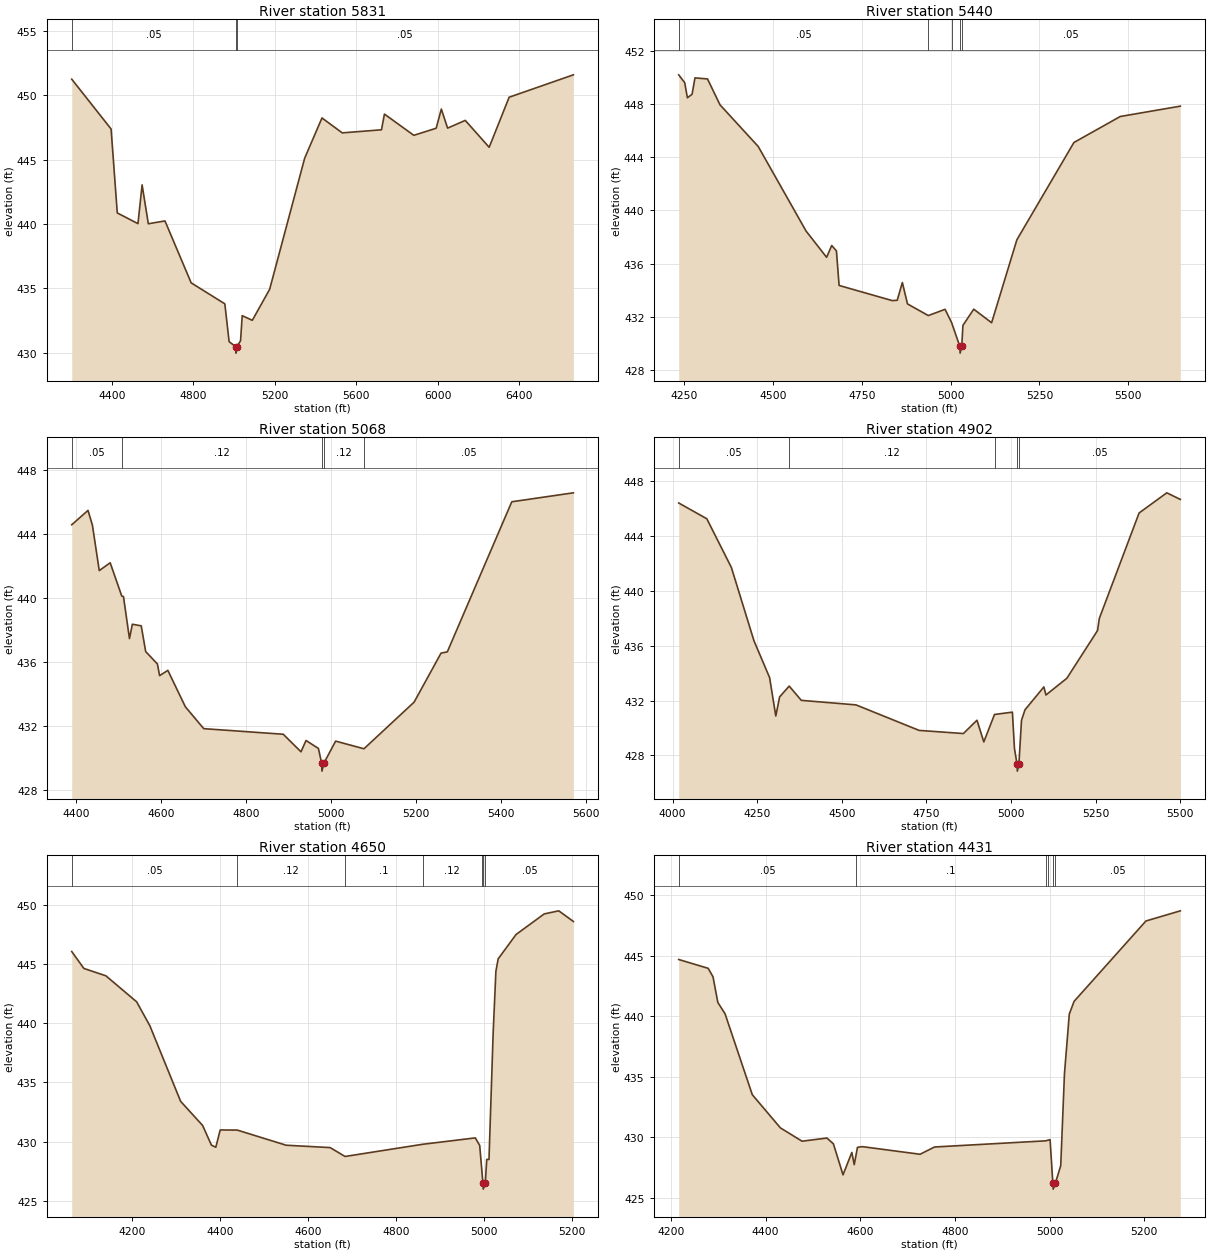
Type RM Length L Ch R = 1,5831,391,391,391
BEGIN DESCRIPTION:
Camp Branch 2007
END DESCRIPTION:
XS GIS Cut Line= 5
      2740706.02      6884698.48      2740294.05      6884626.32
      2740229.86      6884610.93      2739563.50      6883761.39
      2738719.66      6883456.77
#Sta/Elev= 30
  4203.7  451.24  4396.8  447.37  4427.1  440.85  4528.6  440.02  4548.9  443.03
  4579.4  440.01  4661.1  440.23  4789.6  435.42  4954.8  433.79  4975.8  430.85
  5008.4  430.46  5009.2  429.96  5013.7  430.46  5031.9  430.92  5040.0  432.87
  5089.7  432.51  5174.7  434.92  5346.4  445.10  5431.4  448.23  5530.8  447.07
  5723.4  447.31  5737.8  448.53  5881.9  446.88  5991.6  447.43  6017.0  448.92
  6047.7  447.44  6134.4  448.04  6251.7  445.95  6349.7  449.84  6664.8  451.58
#Mann=3,-1,0
  4203.7    0.05       0  5008.4    0.04       0  5013.7    0.05       0
Bank Sta=5008.4,5013.7
Exp/Cntr=0.3,0.1

Type RM Length L Ch R = 1,5440,372,372,372
BEGIN DESCRIPTION:
Camp Branch 2009
END DESCRIPTION:
XS GIS Cut Line= 3
      2740785.27      6884575.69      2740180.41      6884100.61
      2739637.63      6883755.55
#Sta/Elev= 30
  4234.3  450.22  4251.2  449.63  4258.8  448.49  4272.0  448.76  4280.1  449.99
  4315.4  449.91  4350.6  447.96  4458.2  444.82  4592.9  438.45  4650.7  436.47
  4665.1  437.36  4678.4  436.95  4685.9  434.35  4835.1  433.21  4849.5  433.23
  4864.0  434.57  4878.4  432.96  4937.0  432.08  4984.2  432.55  5002.5  431.56
  5025.9  429.75  5026.6  429.25  5031.2  429.75  5034.5  431.34  5065.0  432.56
  5115.3  431.54  5186.4  437.79  5347.0  445.12  5477.4  447.08  5646.6  447.86
#Mann=5,-1,0
  4234.3    0.05       0  4937.0    0.12       0  5002.5    0.05       0
  5025.9    0.07       0  5031.2    0.05       0
Bank Sta=5025.9,5031.2
Exp/Cntr=0.3,0.1

Type RM Length L Ch R = 1,5068,166,166,166
BEGIN DESCRIPTION:
Camp Branch 2005
END DESCRIPTION:
XS GIS Cut Line= 3
      2740912.61      6884034.95      2740379.49      6883873.29
      2739762.65      6883778.93
#Sta/Elev= 30
  4390.0  444.59  4428.3  445.49  4438.7  444.56  4454.8  441.72  4480.5  442.21
  4507.7  440.13  4511.8  440.09  4525.9  437.46  4532.7  438.36  4553.6  438.26
  4564.1  436.65  4591.7  435.87  4596.9  435.14  4616.3  435.47  4657.5  433.19
  4700.8  431.82  4888.0  431.47  4929.8  430.37  4941.6  431.08  4970.8  430.58
  4978.3  429.66  4979.1  429.16  4983.7  429.66  5011.3  431.04  5078.0  430.56
  5196.1  433.48  5259.5  436.55  5274.3  436.63  5426.1  446.03  5571.1  446.59
#Mann=5,-1,0
  4390.0    0.05       0  4507.7    0.12       0  4978.3    0.07       0
  4983.7    0.12       0  5078.0    0.05       0
Bank Sta=4978.3,4983.7
Exp/Cntr=0.3,0.1

Type RM Length L Ch R = 1,4902,252,252,252
BEGIN DESCRIPTION:
Camp Branch 2004
END DESCRIPTION:
XS GIS Cut Line= 4
      2741262.41      6883516.83      2740699.52      6883742.38
      2740322.03      6883698.75      2739840.93      6883576.47
#Sta/Elev= 30
  4017.8  446.41  4100.9  445.26  4173.5  441.71  4240.2  436.37  4286.5  433.68
  4304.8  430.88  4316.1  432.27  4344.4  433.06  4380.2  432.02  4541.8  431.69
  4728.4  429.83  4859.3  429.60  4899.5  430.57  4919.7  428.99  4951.3  430.99
  5004.2  431.16  5010.3  428.51  5018.0  427.36  5018.8  426.86  5023.4  427.36
  5031.1  430.57  5041.4  431.33  5097.3  433.00  5103.3  432.41  5165.2  433.63
  5255.9  437.11  5261.1  437.99  5378.7  445.68  5460.6  447.15  5500.6  446.67
#Mann=5,-1,0
  4017.8    0.05       0  4344.4    0.12       0  4951.3    0.05       0
  5018.0    0.05       0  5023.4    0.05       0
Bank Sta=5018,5023.4
Exp/Cntr=0.3,0.1

Type RM Length L Ch R = 1,4650,219,219,219
BEGIN DESCRIPTION:
Camp Branch 2003
END DESCRIPTION:
XS GIS Cut Line= 3
      2741213.59      6883474.10      2740268.99      6883461.96
      2740081.14      6883405.94
#Sta/Elev= 30
  4062.6  446.06  4090.2  444.63  4140.2  444.01  4210.2  441.81  4240.2  439.79
  4310.2  433.40  4360.2  431.36  4380.2  429.70  4390.2  429.52  4400.2  430.98
  4439.0  430.97  4550.2  429.69  4650.2  429.49  4684.1  428.74  4860.6  429.77
  4980.3  430.31  4990.3  429.67  4994.9  427.66  4997.6  426.48  4998.4  425.98
  5003.0  426.48  5006.3  428.49  5011.4  428.49  5020.8  439.09  5027.1  444.39
  5032.3  445.44  5073.0  447.50  5137.0  449.24  5170.1  449.50  5203.3  448.60
#Mann=7,-1,0
  4062.6    0.05       0  4439.0    0.12       0  4684.1     0.1       0
  4860.6    0.12       0  4994.9    0.05       0  4997.6    0.04       0
  5003.0    0.05       0
Bank Sta=4997.6,5003
Exp/Cntr=0.3,0.1

Type RM Length L Ch R = 1,4431,635,635,635
BEGIN DESCRIPTION:
Camp Branch 2002
END DESCRIPTION:
XS GIS Cut Line= 3
      2741147.26      6883424.03      2740364.36      6883277.20
      2740104.20      6883236.36
#Sta/Elev= 30
  4216.3  444.69  4278.6  443.96  4288.8  443.26  4299.0  441.14  4314.2  440.21
  4371.8  433.52  4431.2  430.78  4476.9  429.68  4529.5  429.94  4543.2  429.46
  4563.5  426.90  4582.1  428.75  4587.2  427.74  4591.1  428.56  4594.0  429.17
  4604.2  429.23  4726.3  428.60  4756.8  429.20  4992.0  429.71  4997.4  429.77
  5001.0  429.81  5006.8  426.22  5007.6  425.72  5012.2  426.22  5023.5  427.66
  5031.4  435.26  5041.6  440.18  5051.7  441.23  5203.5  447.87  5276.2  448.71
#Mann=6,-1,0
  4216.3    0.05       0  4591.1     0.1       0  4992.0    0.12       0
  4997.4    0.05       0  5006.8    0.04       0  5012.2    0.05       0
Bank Sta=5006.8,5012.2
Exp/Cntr=0.3,0.1

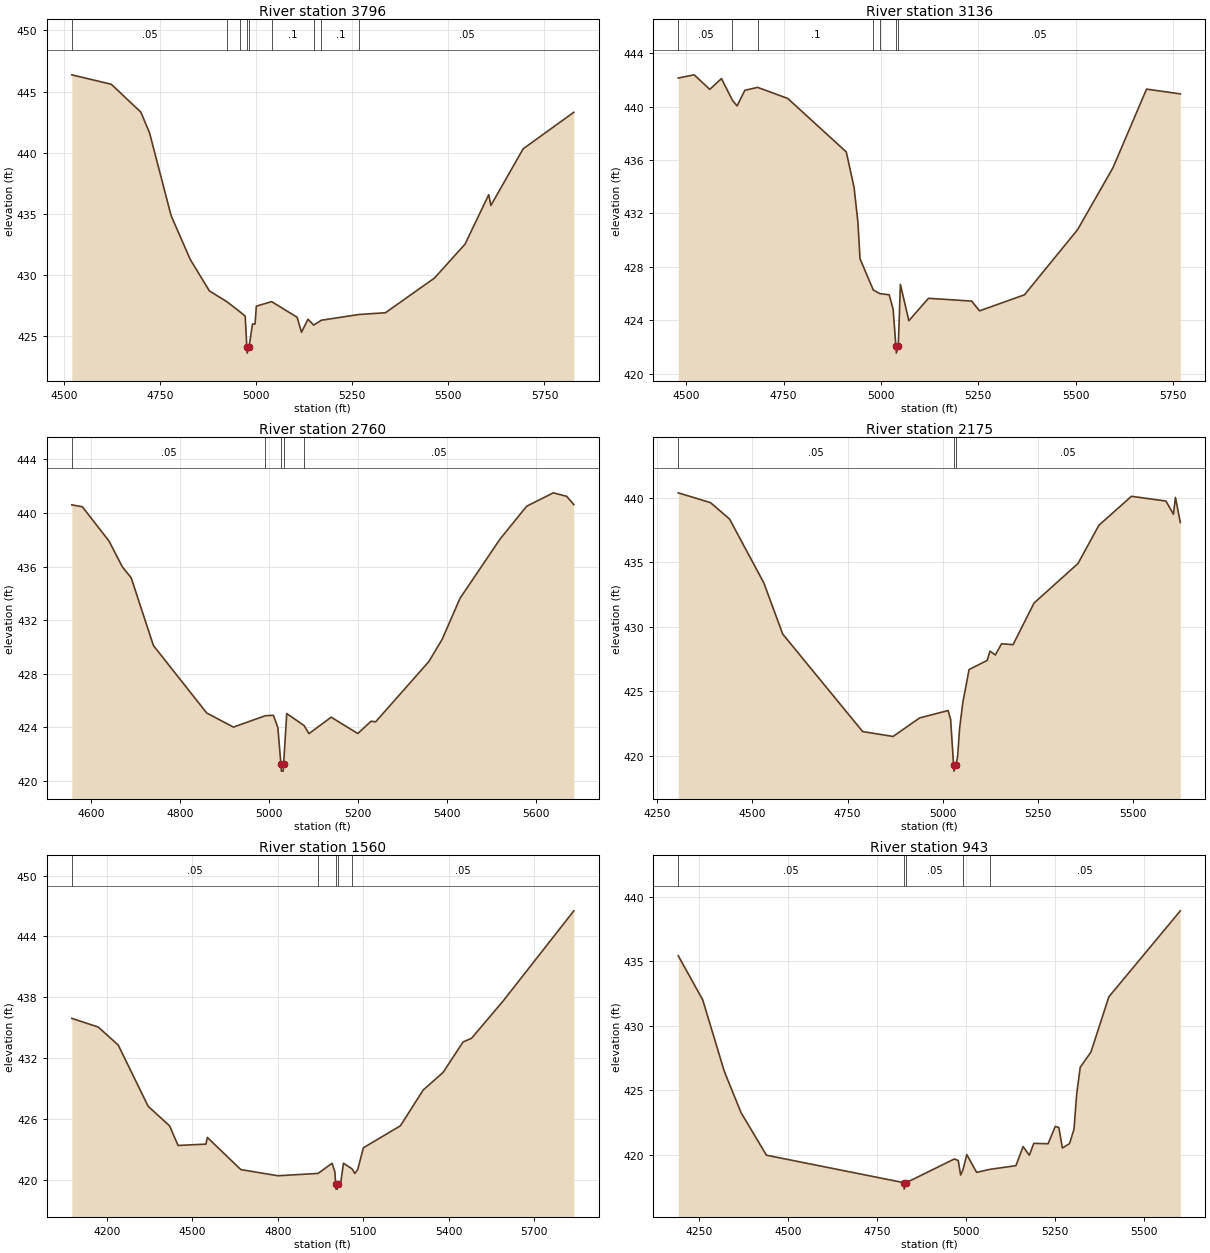
Type RM Length L Ch R = 1,3796,660,660,660
BEGIN DESCRIPTION:
Camp Branch 2000
END DESCRIPTION:
XS GIS Cut Line= 3
      2741217.20      6883442.98      2740926.85      6883068.95
      2740181.61      6882697.91
#Sta/Elev= 30
  4520.4  446.37  4623.1  445.60  4700.1  443.32  4722.7  441.63  4778.8  434.86
  4828.6  431.28  4878.3  428.71  4924.5  427.81  4957.4  427.01  4971.6  426.64
  4975.7  424.12  4976.6  423.62  4981.6  424.12  4990.5  426.00  4997.2  426.00
  5000.5  427.46  5040.4  427.83  5106.6  426.55  5118.0  425.33  5134.8  426.39
  5149.7  425.91  5169.6  426.31  5268.1  426.78  5336.3  426.92  5464.0  429.76
  5543.4  432.53  5605.0  436.57  5610.6  435.69  5694.5  440.32  5826.4  443.31
#Mann=9,-1,0
  4520.4    0.05       0  4924.5    0.12       0  4957.4    0.05       0
  4975.7    0.04       0  4981.6    0.05       0  5040.4     0.1       0
  5149.7    0.05       0  5169.6     0.1       0  5268.1    0.05       0
Bank Sta=4975.7,4981.6
Exp/Cntr=0.3,0.1

Type RM Length L Ch R = 1,3136,376,376,376
BEGIN DESCRIPTION:
Camp Branch 2001
END DESCRIPTION:
XS GIS Cut Line= 3
      2741496.84      6882553.33      2740978.03      6882522.92
      2740214.48      6882425.05
#Sta/Elev= 30
  4479.3  442.15  4520.2  442.39  4560.3  441.30  4590.3  442.11  4618.4  440.49
  4630.4  440.06  4650.4  441.23  4683.2  441.45  4760.6  440.62  4910.9  436.61
  4930.9  433.96  4940.9  431.30  4946.2  428.60  4980.3  426.26  4997.1  425.99
  5021.2  425.90  5031.3  424.80  5038.4  422.03  5039.4  421.53  5044.4  422.03
  5049.9  426.68  5071.6  423.96  5122.0  425.64  5232.9  425.43  5253.1  424.70
  5368.5  425.90  5505.1  430.79  5595.9  435.43  5682.1  441.32  5768.8  440.96
#Mann=7,-1,0
  4479.3    0.05       0  4618.4    0.12       0  4683.2     0.1       0
  4980.3    0.12       0  4997.1    0.05       0  5038.4    0.04       0
  5044.4    0.05       0
Bank Sta=5038.4,5044.4
Exp/Cntr=0.3,0.1

Type RM Length L Ch R = 1,2760,585,585,585
BEGIN DESCRIPTION:
Camp Branch 1999
END DESCRIPTION:
XS GIS Cut Line= 3
      2741419.76      6882240.79      2740975.23      6882240.57
      2740289.76      6882239.78
#Sta/Elev= 30
  4555.8  440.61  4579.6  440.47  4639.6  437.91  4669.6  435.98  4689.6  435.16
  4739.6  430.10  4859.6  425.06  4919.6  424.01  4991.6  424.86  5009.6  424.89
  5019.6  423.98  5026.6  421.22  5027.6  420.72  5031.6  420.72  5032.6  421.22
  5039.6  425.02  5078.9  424.12  5089.6  423.52  5139.6  424.75  5199.6  423.53
  5229.6  424.45  5239.6  424.40  5359.6  428.91  5389.6  430.58  5429.6  433.63
  5519.6  438.05  5579.6  440.51  5639.6  441.51  5669.6  441.25  5685.8  440.63
#Mann=5,-1,0
  4555.8    0.05       0  4991.6    0.12       0  5026.6    0.07       0
  5032.6    0.12       0  5078.9    0.05       0
Bank Sta=5026.6,5032.6
Exp/Cntr=0.3,0.1

Type RM Length L Ch R = 1,2175,615,615,615
BEGIN DESCRIPTION:
Camp Branch 1997
END DESCRIPTION:
XS GIS Cut Line= 3
      2741570.76      6881818.38      2740875.91      6881791.40
      2740290.29      6882010.97
#Sta/Elev= 30
  4304.7  440.40  4389.5  439.64  4439.6  438.37  4529.6  433.43  4579.7  429.44
  4789.8  421.88  4869.9  421.50  4939.9  422.94  5014.6  423.51  5021.3  422.83
  5029.0  419.31  5030.0  418.81  5035.1  419.31  5039.5  419.90  5044.8  422.10
  5053.4  424.14  5069.8  426.69  5117.5  427.40  5124.9  428.12  5138.8  427.82
  5155.2  428.69  5185.5  428.62  5240.7  431.85  5356.4  434.92  5411.5  437.89
  5497.0  440.13  5587.8  439.76  5607.4  438.74  5612.7  440.05  5625.5  438.10
#Mann=3,-1,0
  4304.7    0.05       0  5029.0    0.04       0  5035.1    0.05       0
Bank Sta=5029,5035.1
Exp/Cntr=0.3,0.1

Type RM Length L Ch R = 1,1560,617,617,617
BEGIN DESCRIPTION:
Camp Branch 1996
END DESCRIPTION:
XS GIS Cut Line= 3
      2741888.89      6881212.93      2740959.06      6881258.26
      2740127.02      6881264.39
#Sta/Elev= 30
  4076.7  435.91  4169.7  435.05  4239.8  433.28  4345.0  427.23  4420.0  425.31
  4450.0  423.37  4547.8  423.50  4552.8  424.16  4670.3  420.99  4800.5  420.38
  4941.5  420.61  4990.7  421.61  5000.7  420.76  5003.3  419.56  5004.4  419.06
  5008.9  419.06  5010.0  419.56  5020.7  419.60  5030.7  421.62  5061.3  421.05
  5070.7  420.60  5080.7  420.99  5100.7  423.14  5230.7  425.31  5310.7  428.84
  5380.7  430.58  5450.7  433.58  5480.7  433.95  5590.7  437.60  5839.7  446.52
#Mann=5,-1,0
  4076.7    0.05       0  4941.5    0.12       0  5003.3    0.07       0
  5010.0    0.12       0  5061.3    0.05       0
Bank Sta=5003.3,5010
Exp/Cntr=0.3,0.1

Type RM Length L Ch R = 1,943,301,301,301
BEGIN DESCRIPTION:
Camp Branch 43
END DESCRIPTION:
XS GIS Cut Line= 3
      2741776.04      6881011.02      2741026.00      6880711.00
      2740426.00      6880761.00
#Sta/Elev= 30
  4192.6  435.43  4261.3  432.01  4321.9  426.47  4369.0  423.26  4440.4  419.96
  4826.1  417.83  4827.1  417.33  4832.8  417.83  4968.1  419.67  4978.9  419.55
  4985.6  418.42  4992.7  418.88  5002.9  420.01  5030.5  418.63  5067.2  418.86
  5140.9  419.15  5161.0  420.63  5178.5  419.96  5191.1  420.88  5231.2  420.85
  5251.3  422.19  5261.3  422.11  5271.4  420.52  5291.4  420.86  5304.0  421.98
  5311.5  424.70  5321.5  426.78  5351.6  427.96  5401.8  432.24  5602.5  438.91
#Mann=5,-1,0
  4192.6    0.05       0  4826.1    0.07       0  4832.8    0.05       0
  4992.7    0.12       0  5067.2    0.05       0
Bank Sta=4826.1,4832.8
Exp/Cntr=0.3,0.1

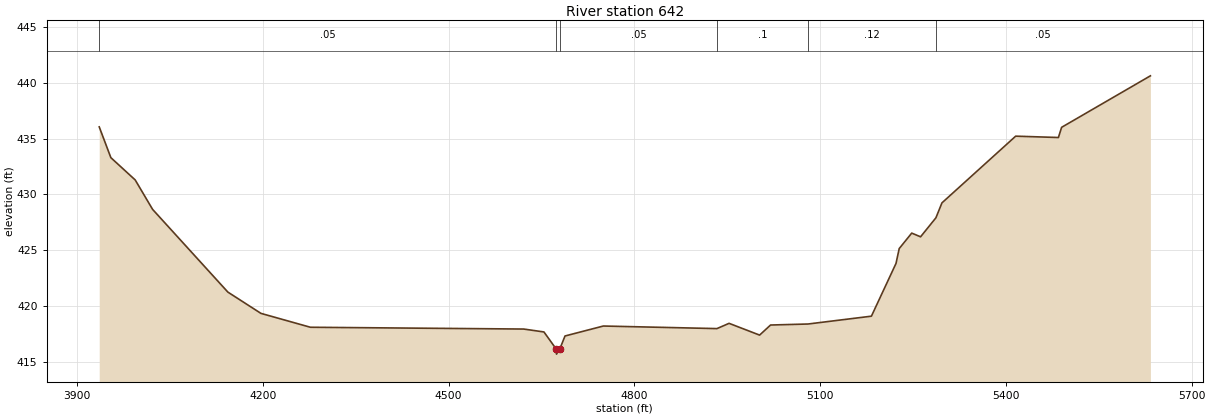
Type RM Length L Ch R = 1,642,0,0,0
BEGIN DESCRIPTION:
Camp Branch 1995
END DESCRIPTION:
XS GIS Cut Line= 3
      2741882.95      6880911.47      2740925.16      6880447.17
      2740314.18      6880614.23
#Sta/Elev= 30
  3935.6  436.04  3954.4  433.29  3993.7  431.30  4021.8  428.67  4143.4  421.28
  4196.8  419.38  4276.7  418.14  4621.2  417.98  4653.9  417.72  4673.1  416.24
  4674.2  415.74  4679.8  416.24  4687.9  417.36  4749.8  418.25  4933.3  418.02
  4952.9  418.49  5002.2  417.44  5019.9  418.34  5080.4  418.43  5182.8  419.13
  5222.5  423.84  5227.7  425.17  5247.9  426.55  5262.2  426.22  5287.0  427.92
  5296.7  429.25  5415.8  435.21  5484.8  435.09  5490.0  436.00  5633.4  440.60
#Mann=6,-1,0
  3935.6    0.05       0  4673.1    0.07       0  4679.8    0.05       0
  4933.3     0.1       0  5080.4    0.12       0  5287.0    0.05       0
Bank Sta=4673.1,4679.8
Exp/Cntr=0.3,0.1

Chan Stop Cuts=-1