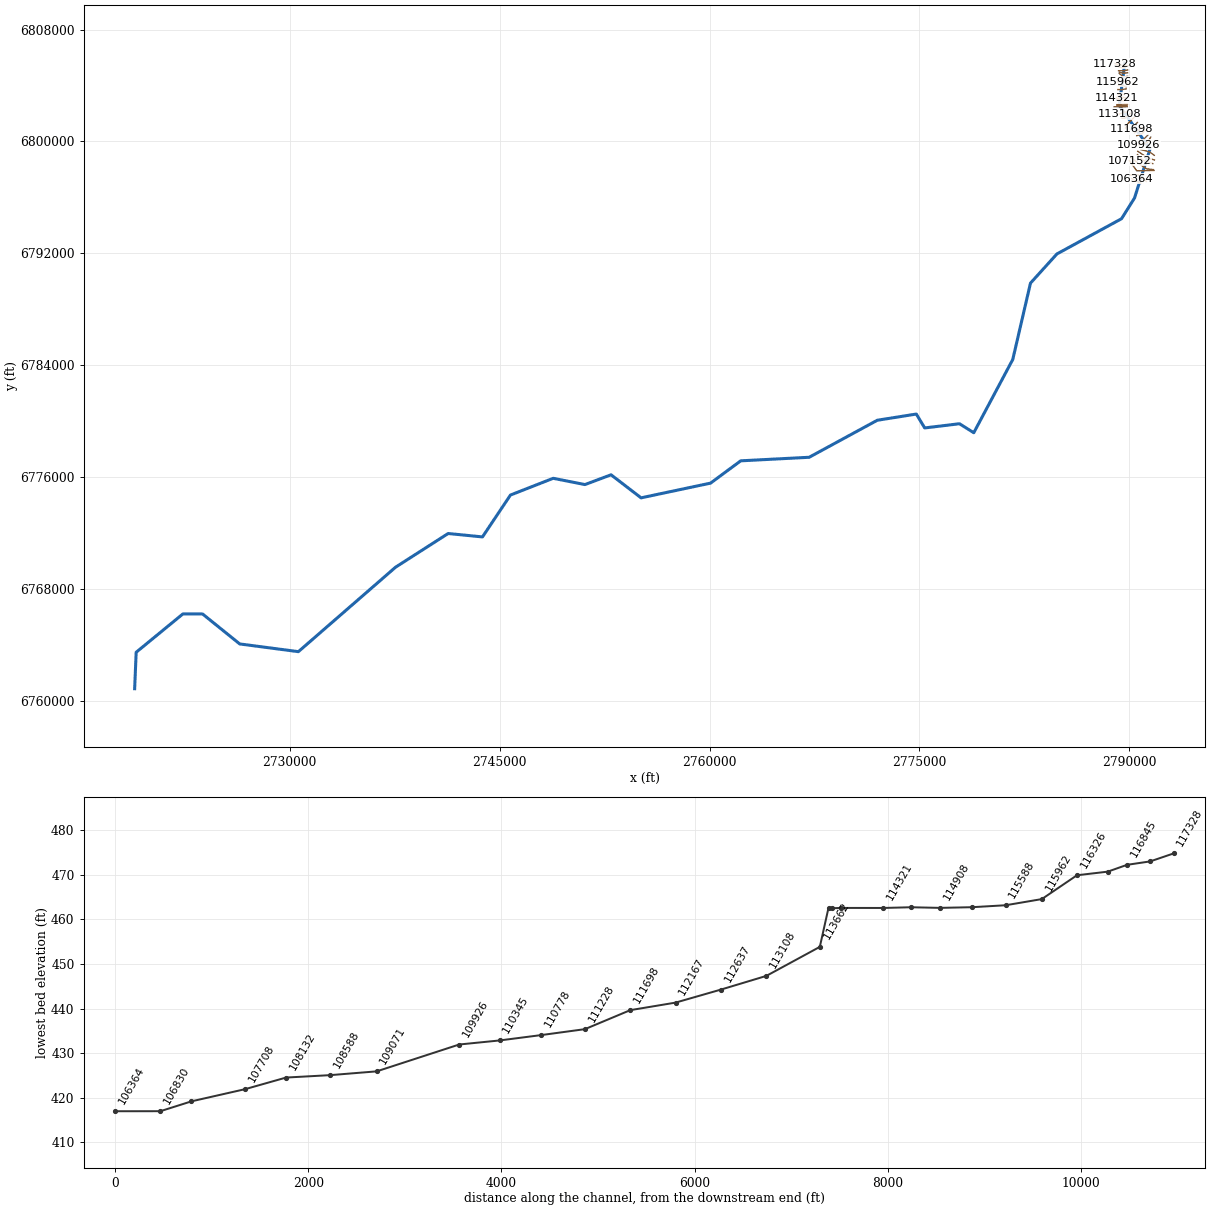
--- Caney Creek.prj (project) ---

Proj Title=Caney Creek Base Level Engineering
Current Plan=p01
Default Exp/Contr=0.3,0.1
English Units
Geom File=g01
Flow File=f01
Plan File=p01
Y Axis Title=Elevation
X Axis Title(PF)=Main Channel Distance
X Axis Title(XS)=Station
BEGIN DESCRIPTION:
Caney Creek
END DESCRIPTION:
DSS Export Rating Curves= 0
DSS Export Rating Curve Sorted= 0
DSS Export Volume Flow Curves= 0
DXF OffsetX= 0
DXF OffsetY= 0
DXF ScaleX= 1
DXF ScaleY= 10

--- Caney Creek.p01 (plan) ---

Plan Title=Multiple Run
Program Version=3.12
Short Identifier=Multiple
Geom File=g01
Flow File=f01
Subcritical Flow
K Sum by GR= 0
Std Step Tol= 0.01
Critical Tol= 0.01
Num of Std Step Trials= 20
Max Error Tol= 0.3
Flow Tol Ratio= 0.001
Split Flow NTrial= 30
Split Flow Tol= 0.02
Split Flow Ratio= 0.02
Log Output Level= 0
Friction Slope Method= 1
Unsteady Friction Slope Method= 2
Unsteady Bridges Friction Slope Method= 1
Parabolic Critical Depth
Global Vel Dist= 1 , 1 , 1
Global Log Level= 0
CheckData=True
Encroach Param=-1 ,0,0, 0
BEGIN DESCRIPTION:
Multiple Run
END DESCRIPTION:
Computation Interval=1HOUR
Output Interval=1HOUR
Run HTab= 0
Run UNet= 0
Run PostProcess= 0
UNET Theta= 1
UNET Theta Warmup= 1
UNET ZTol= 0.02
UNET ZSATol= 0.05
UNET MxIter= 20
UNET MaxInSteps= 0
UNET DtIC= 0
UNET DtMin= 0
UNET MaxCRTS= 20
UNET WFStab= 2
UNET SFStab= 1
UNET WFX= 1
UNET SFX= 1
UNET DSS MLevel= 4
UNET DZMax Abort= 100
UNET Convert EG Bridges=-1
UNET Use Existing IB Tables=-1
UNET Froude Reduction=False
UNET Froude Limit= 1
UNET Froude Power= 10
Instantaneous Interval=1HOUR
Write IC File= 0
Echo Input=False
Echo Output=False
Write Detailed= 0
Detailed Automatic Start=False, 10

--- Caney Creek.f01 (steady flow) ---

Flow Title=Multiple
Number of Profiles=7
Profile Names=10-year,25-year,50-year,1pct_min,100-year,1pct_plu,500-year
River Rch & RM= Caney Creek,Reach-1,117328
     167     207     236     135     269     538     350
River Rch & RM= Caney Creek,Reach-1,115962
     588     793     961     579    1156    2306    1673
River Rch & RM= Caney Creek,Reach-1,113108
     662     897    1091     659    1315    2623    1914
River Rch & RM= Caney Creek,Reach-1,109071
    1707    2416    3020    1869    3730    7442    5709
River Rch & RM= Caney Creek,Reach-1,103109
    2133    3044    3829    2383    4754    9485    7353
River Rch & RM= Caney Creek,Reach-1,101366
    2230    3180    3997    2485    4959    9894    7656
River Rch & RM= Caney Creek,Reach-1,97809
    2194    3119    3911    2426    4840    9657    7436
River Rch & RM= Caney Creek,Reach-1,95409
    2625    3754    4727    2942    5869   11711    9080
River Rch & RM= Caney Creek,Reach-1,92120
    3098    4435    5587    3477    6937   13842   10730
River Rch & RM= Caney Creek,Reach-1,85983
    3064    4378    5508    3423    6830   13628   10535
River Rch & RM= Caney Creek,Reach-1,83502
    4466    6461    8200    5136   10248   20447   16053
River Rch & RM= Caney Creek,Reach-1,80569
    4709    6783    8581    5355   10685   21319   16615
River Rch & RM= Caney Creek,Reach-1,75656
    5222    7582    9647    6055   12081   24106   19003
River Rch & RM= Caney Creek,Reach-1,72166
    5390    7825    9955    6247   12465   24871   19599
River Rch & RM= Caney Creek,Reach-1,70398
    5475    7930   10071    6309   12588   25117   19719
River Rch & RM= Caney Creek,Reach-1,66637
    5412    7814    9902    6188   12347   24636   19250
River Rch & RM= Caney Creek,Reach-1,62174
    5459    7869    9961    6218   12406   24753   19294
River Rch & RM= Caney Creek,Reach-1,57923
    5463    7871    9959    6214   12399   24740   19269
River Rch & RM= Caney Creek,Reach-1,56691
    5538    7981   10100    6303   12577   25094   19550
River Rch & RM= Caney Creek,Reach-1,56286
    5998    8660   10976    6858   13684   27304   21324
River Rch & RM= Caney Creek,Reach-1,54091
    5965    8597   10884    6792   13552   27041   21066
River Rch & RM= Caney Creek,Reach-1,49484
    5917    8502   10738    6685   13339   26615   20634
River Rch & RM= Caney Creek,Reach-1,46646
    5884    8440   10648    6621   13212   26361   20388
River Rch & RM= Caney Creek,Reach-1,43766
    5707    8175   10302    6398   12766   25472   19656
River Rch & RM= Caney Creek,Reach-1,38860
    6023    8670   10963    6832   13632   27199   21136
River Rch & RM= Caney Creek,Reach-1,36545
    5999    8612   10869    6760   13488   26913   20829
River Rch & RM= Caney Creek,Reach-1,33247
    5996    8599   10845    6740   13449   26834   20736
River Rch & RM= Caney Creek,Reach-1,31148
    5936    8502   10713    6653   13274   26484   20430
River Rch & RM= Caney Creek,Reach-1,30429
    6011    8593   10814    6705   13378   26692   20526
River Rch & RM= Caney Creek,Reach-1,25425
    6010    8580   10787    6681   13330   26598   20408
River Rch & RM= Caney Creek,Reach-1,21902
    6117    8713   10937    6762   13491   26919   20577
River Rch & RM= Caney Creek,Reach-1,15659
    6153    8760   10992    6793   13553   27042   20651
River Rch & RM= Caney Creek,Reach-1,12966
    6204    8827   11071    6838   13644   27224   20769
River Rch & RM= Caney Creek,Reach-1,11900
    6174    8772   10991    6781   13530   26997   20548
River Rch & RM= Caney Creek,Reach-1,8103
    6161    8746   10952    6753   13473   26882   20435
River Rch & RM= Caney Creek,Reach-1,6720
    8733   12442   15624    9653   19261   38430   29309
Boundary for River Rch & Prof#=Caney Creek,Reach-1,1
Up Type=0
Dn Type=3
Dn Slope=0.005
Boundary for River Rch & Prof#=Caney Creek,Reach-1,2
Up Type=0
Dn Type=3
Dn Slope=0.005
Boundary for River Rch & Prof#=Caney Creek,Reach-1,3
Up Type=0
Dn Type=3
Dn Slope=0.005
Boundary for River Rch & Prof#=Caney Creek,Reach-1,4
Up Type=0
Dn Type=3
Dn Slope=0.005
Boundary for River Rch & Prof#=Caney Creek,Reach-1,5
Up Type=0
Dn Type=3
Dn Slope=0.005
Boundary for River Rch & Prof#=Caney Creek,Reach-1,6
Up Type=0
Dn Type=3
Dn Slope=0.005
Boundary for River Rch & Prof#=Caney Creek,Reach-1,7
Up Type=0
Dn Type=3
Dn Slope=0.005

--- Caney Creek.g01 (geometry) ---

Geom Title=Existing Conditions

River Reach=Caney Creek,Reach-1
Reach XY= 30
      2789676.00      6805611.00      2789277.76      6802567.13
      2791476.00      6799461.00      2790367.15      6795954.05
      2789439.61      6794473.94      2784819.66      6791952.98
      2782933.48      6789867.07      2781668.21      6784407.58
      2778882.06      6779169.14      2777860.27      6779811.35
      2775376.00      6779511.00      2774776.30      6780503.74
      2771986.44      6780059.95      2767119.61      6777412.52
      2762231.31      6777158.98      2760074.38      6775564.12
      2755110.78      6774511.49      2752965.50      6776159.80
      2751101.12      6775460.88      2748831.65      6775909.02
      2745776.00      6774711.00      2743778.45      6771716.47
      2741326.00      6771961.00      2737569.95      6769552.84
      2730626.00      6763511.00      2726431.93      6764063.25
      2723778.45      6766205.53      2722376.00      6766211.00
      2719034.14      6763467.06      2718926.00      6760861.00

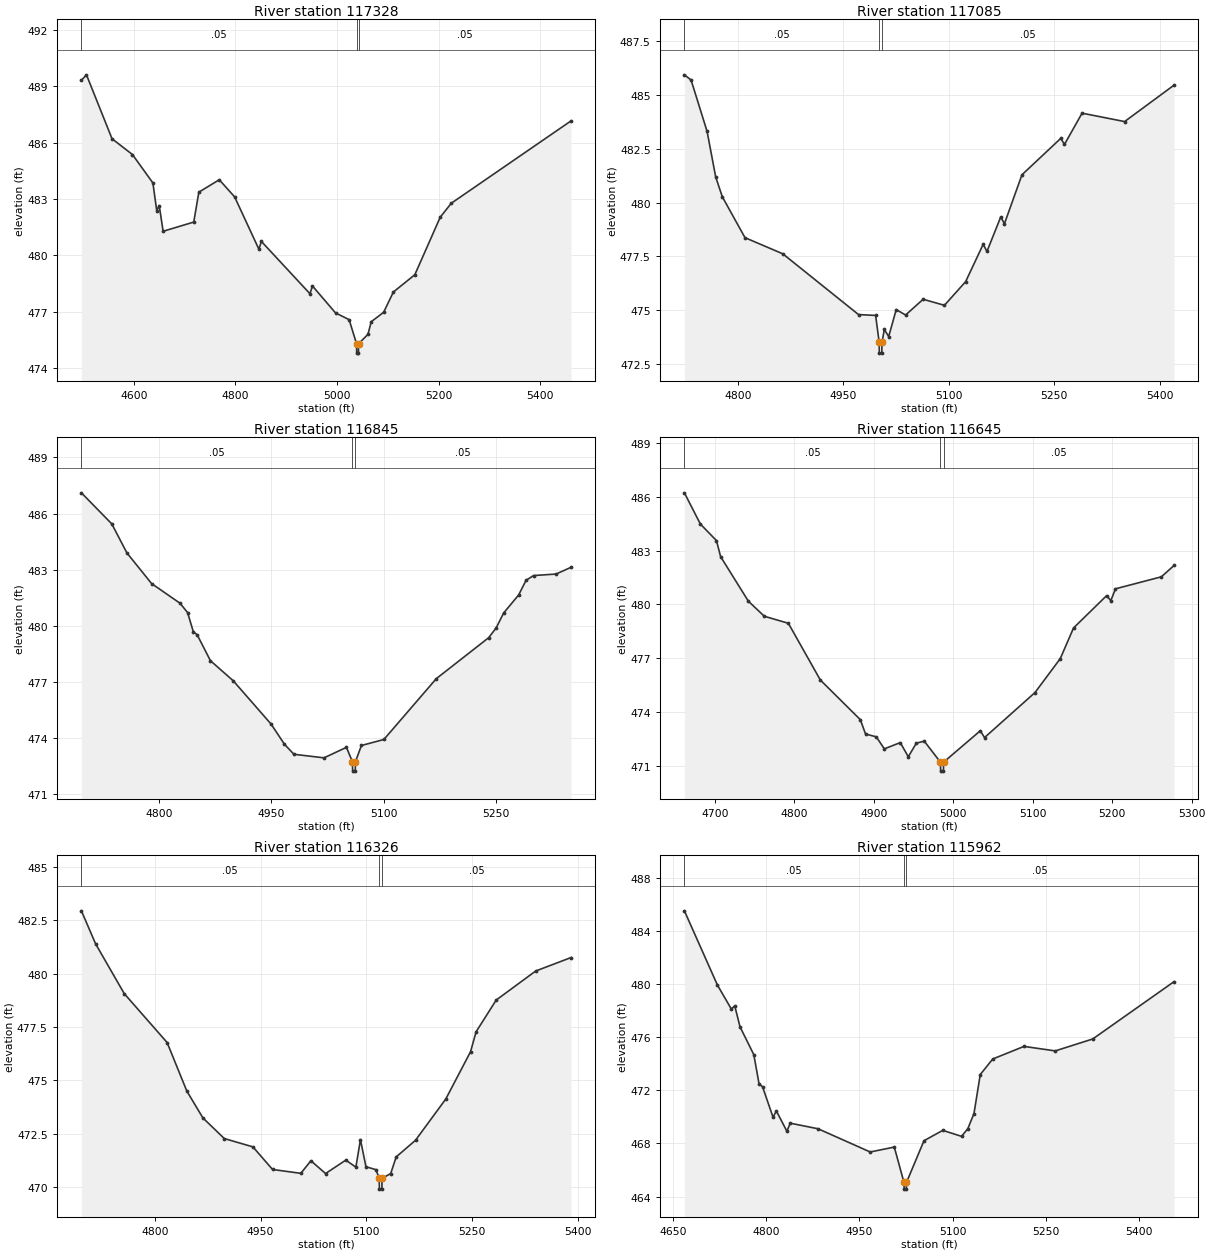
Type RM Length L Ch R = 1,117328,243,243,243
BEGIN DESCRIPTION:
Caney Creek 158.0
END DESCRIPTION:
XS GIS Cut Line= 3
      2789925.97      6805411.00      2789426.00      6805461.00
      2788976.04      6805560.99
#Sta/Elev= 30
  4497.1  489.31  4507.1  489.60  4557.4  486.20  4597.6  485.36  4637.8  483.85
  4645.3  482.38  4650.3  482.64  4657.9  481.28  4718.2  481.77  4728.2  483.36
  4768.4  484.02  4798.6  483.11  4846.3  480.33  4851.3  480.74  4946.8  477.96
  4951.8  478.37  4997.1  476.94  5023.9  476.58  5038.5  475.30  5038.8  474.80
  5042.3  474.80  5042.5  475.30  5061.0  475.80  5067.4  476.47  5091.8  476.97
  5111.0  478.05  5153.2  478.97  5203.2  482.03  5224.9  482.77  5460.5  487.15
#Mann=3,-1,0
  4497.1    0.05       0  5038.5    0.04       0  5042.5    0.05       0
Bank Sta=5038.5,5042.5
Exp/Cntr=0.3,0.1

Type RM Length L Ch R = 1,117085,240,240,240
BEGIN DESCRIPTION:
Caney Creek 157.0
END DESCRIPTION:
XS GIS Cut Line= 3
      2789726.03      6805361.01      2789476.00      6805261.00
      2789075.99      6805411.00
#Sta/Elev= 30
  4724.1  485.93  4733.6  485.69  4756.4  483.30  4768.6  481.19  4778.0  480.27
  4810.3  478.37  4864.1  477.62  4971.8  474.80  4996.1  474.76  5001.2  473.51
  5001.4  473.01  5004.9  473.01  5005.2  473.51  5008.5  474.11  5014.7  473.78
  5025.4  475.03  5038.8  474.78  5063.7  475.51  5094.0  475.23  5124.2  476.33
  5149.1  478.06  5154.5  477.73  5174.1  479.33  5179.4  479.02  5204.3  481.29
  5259.5  482.98  5264.8  482.70  5289.8  484.15  5350.3  483.76  5420.6  485.45
#Mann=3,-1,0
  4724.1    0.05       0  5001.2    0.04       0  5005.2    0.05       0
Bank Sta=5001.2,5005.2
Exp/Cntr=0.3,0.1

Type RM Length L Ch R = 1,116845,200,200,200
BEGIN DESCRIPTION:
Caney Creek 156.0
END DESCRIPTION:
XS GIS Cut Line= 3
      2789876.01      6805111.00      2789576.00      6805061.00
      2789226.05      6805061.00
#Sta/Elev= 30
  4696.3  487.11  4736.9  485.45  4757.1  483.90  4790.1  482.26  4828.1  481.21
  4838.2  480.71  4845.8  479.69  4850.9  479.53  4868.7  478.14  4899.1  477.07
  4949.8  474.75  4967.5  473.68  4980.2  473.14  5020.4  472.95  5050.4  473.51
  5058.4  472.74  5058.7  472.24  5062.2  472.24  5062.4  472.74  5070.4  473.61
  5100.4  473.93  5170.4  477.18  5240.4  479.37  5250.4  479.89  5260.4  480.69
  5280.4  481.65  5290.4  482.44  5300.4  482.69  5330.4  482.77  5350.4  483.13
#Mann=3,-1,0
  4696.3    0.05       0  5058.4    0.04       0  5062.4    0.05       0
Bank Sta=5058.4,5062.4
Exp/Cntr=0.3,0.1

Type RM Length L Ch R = 1,116645,319,319,319
BEGIN DESCRIPTION:
Caney Creek 155.0
END DESCRIPTION:
XS GIS Cut Line= 3
      2789876.02      6804911.00      2789539.84      6804874.16
      2789275.96      6804961.01
#Sta/Elev= 30
  4661.8  486.22  4681.9  484.48  4702.1  483.56  4707.4  482.66  4742.3  480.18
  4762.4  479.34  4792.6  478.95  4832.8  475.79  4883.1  473.58  4889.7  472.78
  4903.3  472.62  4913.3  471.95  4933.4  472.30  4943.5  471.51  4953.6  472.27
  4963.6  472.38  4983.9  471.21  4984.2  470.71  4987.7  470.71  4987.9  471.21
  5034.1  472.96  5039.4  472.58  5102.9  475.09  5134.7  476.98  5151.4  478.69
  5193.0  480.49  5198.3  480.21  5204.1  480.87  5261.9  481.54  5277.8  482.17
#Mann=3,-1,0
  4661.8    0.05       0  4983.9    0.05       0  4987.9    0.05       0
Bank Sta=4983.9,4987.9
Exp/Cntr=0.3,0.1

Type RM Length L Ch R = 1,116326,364,364,364
BEGIN DESCRIPTION:
Caney Creek 154.0
END DESCRIPTION:
XS GIS Cut Line= 3
      2789875.97      6804661.00      2789576.00      6804611.00
      2789276.02      6804860.99
#Sta/Elev= 30
  4695.8  482.94  4716.0  481.39  4756.6  479.06  4817.4  476.77  4845.3  474.50
  4868.1  473.24  4898.5  472.27  4939.1  471.88  4967.0  470.82  5007.1  470.64
  5021.4  471.23  5042.2  470.63  5070.9  471.26  5085.2  470.93  5091.7  472.22
  5099.5  470.95  5113.8  470.81  5118.3  470.40  5118.6  469.90  5122.1  469.90
  5122.3  470.40  5134.6  470.63  5142.4  471.41  5169.8  472.19  5212.7  474.12
  5247.9  476.34  5255.7  477.27  5284.3  478.76  5340.3  480.12  5390.4  480.75
#Mann=3,-1,0
  4695.8    0.05       0  5118.3    0.05       0  5122.3    0.05       0
Bank Sta=5118.3,5122.3
Exp/Cntr=0.3,0.1

Type RM Length L Ch R = 1,115962,374,374,374
BEGIN DESCRIPTION:
Caney Creek 153.0
END DESCRIPTION:
XS GIS Cut Line= 3
      2789876.01      6804161.00      2789576.00      6804311.00
      2789125.99      6804261.00
#Sta/Elev= 30
  4668.4  485.54  4721.5  479.95  4743.9  478.14  4749.5  478.37  4757.9  476.80
  4780.2  474.69  4788.6  472.49  4794.2  472.28  4811.0  469.99  4816.5  470.45
  4833.3  468.93  4838.9  469.53  4883.6  469.11  4967.5  467.36  5006.3  467.73
  5021.9  465.06  5022.2  464.56  5025.7  464.56  5025.9  465.06  5054.1  468.21
  5084.3  468.99  5114.5  468.54  5124.6  469.11  5134.6  470.26  5144.7  473.20
  5164.8  474.37  5215.1  475.32  5265.4  474.98  5325.8  475.88  5456.6  480.20
#Mann=3,-1,0
  4668.4    0.05       0  5021.9    0.04       0  5025.9    0.05       0
Bank Sta=5021.9,5025.9
Exp/Cntr=0.3,0.1

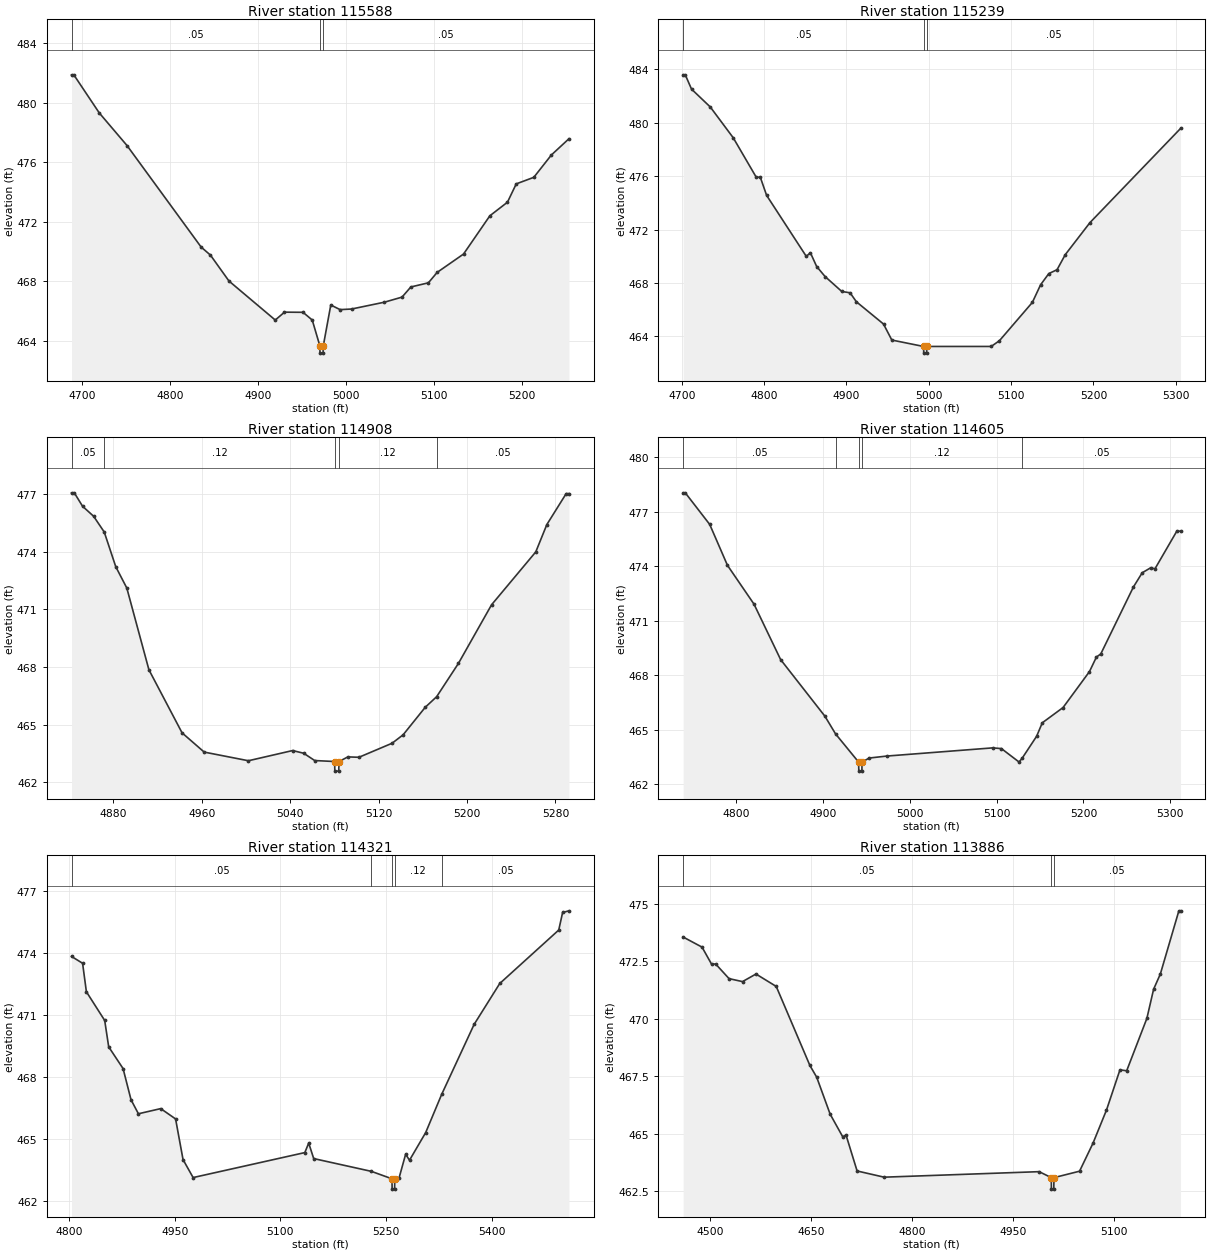
Type RM Length L Ch R = 1,115588,349,349,349
BEGIN DESCRIPTION:
Caney Creek 152.0
END DESCRIPTION:
XS GIS Cut Line= 3
      2789775.98      6803911.01      2789476.00      6804011.00
      2789226.00      6804011.00
#Sta/Elev= 30
  4687.6  481.86  4690.2  481.86  4719.2  479.30  4750.8  477.11  4835.1  470.30
  4845.7  469.76  4866.8  468.02  4919.5  465.40  4930.0  465.93  4951.1  465.92
  4961.6  465.40  4970.2  463.68  4970.4  463.18  4973.9  463.18  4974.2  463.68
  4982.7  466.41  4993.3  466.10  5006.3  466.14  5043.8  466.60  5063.8  466.94
  5073.8  467.62  5093.8  467.90  5103.8  468.60  5133.8  469.83  5163.8  472.40
  5183.8  473.31  5193.8  474.54  5213.8  474.98  5233.8  476.48  5253.8  477.57
#Mann=3,-1,0
  4687.6    0.05       0  4970.2    0.04       0  4974.2    0.05       0
Bank Sta=4970.2,4974.2
Exp/Cntr=0.3,0.1

Type RM Length L Ch R = 1,115239,331,331,331
BEGIN DESCRIPTION:
Caney Creek 151.0
END DESCRIPTION:
XS GIS Cut Line= 3
      2789776.04      6803761.01      2789476.00      6803711.00
      2789175.98      6803711.00
#Sta/Elev= 30
  4701.6  483.59  4704.2  483.59  4711.8  482.52  4734.6  481.18  4762.5  478.87
  4790.3  475.93  4795.4  475.91  4803.0  474.56  4851.2  469.99  4856.2  470.26
  4863.8  469.23  4874.0  468.48  4894.3  467.36  4904.4  467.26  4912.0  466.59
  4945.0  464.92  4955.1  463.72  4993.6  463.24  4993.9  462.74  4997.4  462.74
  4997.6  463.24  5075.8  463.24  5085.8  463.67  5125.8  466.54  5135.8  467.86
  5145.8  468.70  5155.8  468.99  5165.8  470.12  5195.8  472.52  5305.8  479.57
#Mann=3,-1,0
  4701.6    0.05       0  4993.6    0.04       0  4997.6    0.05       0
Bank Sta=4993.6,4997.6
Exp/Cntr=0.3,0.1

Type RM Length L Ch R = 1,114908,303,303,303
BEGIN DESCRIPTION:
Caney Creek 150.0
END DESCRIPTION:
XS GIS Cut Line= 3
      2789625.99      6803411.00      2789476.00      6803411.00
      2789175.99      6803411.00
#Sta/Elev= 30
  4842.2  477.06  4844.7  477.06  4852.2  476.36  4862.2  475.84  4871.8  475.02
  4882.2  473.22  4892.2  472.11  4912.2  467.86  4942.2  464.58  4962.2  463.58
  5002.2  463.13  5042.2  463.66  5052.2  463.52  5062.2  463.14  5080.2  463.09
  5080.4  462.59  5083.9  462.59  5084.2  463.09  5092.2  463.33  5102.2  463.31
  5132.2  464.04  5142.2  464.48  5162.2  465.91  5172.5  466.46  5192.2  468.19
  5222.2  471.24  5262.2  473.99  5272.2  475.41  5289.7  477.02  5292.2  477.02
#Mann=5,-1,0
  4842.2    0.05       0  4871.8    0.12       0  5080.2    0.07       0
  5084.2    0.12       0  5172.5    0.05       0
Bank Sta=5080.2,5084.2
Exp/Cntr=0.3,0.1

Type RM Length L Ch R = 1,114605,284,284,284
BEGIN DESCRIPTION:
Caney Creek 149.0
END DESCRIPTION:
XS GIS Cut Line= 3
      2789725.99      6803111.00      2789476.00      6803161.00
      2789162.45      6803210.69
#Sta/Elev= 30
  4739.3  478.05  4741.8  478.05  4769.9  476.31  4790.3  474.06  4820.9  471.92
  4851.5  468.87  4902.5  465.75  4914.7  464.78  4941.2  463.23  4941.5  462.73
  4945.0  462.73  4945.2  463.23  4953.4  463.45  4973.8  463.56  5095.5  464.01
  5105.6  463.97  5125.9  463.23  5129.7  463.46  5146.1  464.65  5152.6  465.39
  5176.5  466.23  5206.9  468.21  5214.9  469.01  5219.9  469.18  5257.5  472.87
  5267.6  473.65  5277.2  473.92  5282.3  473.87  5307.4  475.94  5311.7  475.94
#Mann=5,-1,0
  4739.3    0.05       0  4914.7    0.12       0  4941.2    0.07       0
  4945.2    0.12       0  5129.7    0.05       0
Bank Sta=4941.2,4945.2
Exp/Cntr=0.3,0.1

Type RM Length L Ch R = 1,114321,435,435,435
BEGIN DESCRIPTION:
Caney Creek 148.0
END DESCRIPTION:
XS GIS Cut Line= 3
      2789725.99      6802961.00      2789539.80      6802897.86
      2789076.73      6803111.54
#Sta/Elev= 30
  4803.4  473.84  4819.1  473.51  4824.5  472.13  4850.5  470.74  4856.2  469.46
  4876.6  468.41  4887.9  466.90  4898.4  466.22  4930.1  466.47  4951.2  465.97
  4961.8  464.00  4976.1  463.13  5134.8  464.34  5140.3  464.80  5147.4  464.05
  5229.4  463.43  5258.6  463.07  5258.8  462.57  5262.3  462.57  5262.6  463.07
  5268.5  463.09  5278.0  464.26  5283.5  463.97  5306.5  465.31  5329.2  467.16
  5375.3  470.55  5411.7  472.53  5495.5  475.12  5501.0  475.97  5510.0  476.05
#Mann=5,-1,0
  4803.4    0.05       0  5229.4    0.12       0  5258.6    0.03       0
  5262.6    0.12       0  5329.2    0.05       0
Bank Sta=5258.6,5262.6
Exp/Cntr=0.3,0.1

Type RM Length L Ch R = 1,113886,93,93,93
BEGIN DESCRIPTION:
Caney Creek 147.0
END DESCRIPTION:
XS GIS Cut Line= 3
      2789864.10      6802688.10      2789326.00      6802661.00
      2789125.99      6802661.00
#Sta/Elev= 30
  4460.5  473.55  4488.6  473.11  4502.9  472.36  4508.7  472.38  4528.7  471.74
  4548.7  471.61  4568.7  471.94  4598.8  471.40  4648.8  467.96  4658.9  467.45
  4678.9  465.84  4697.5  464.86  4702.5  464.93  4718.9  463.37  4759.0  463.10
  4989.3  463.34  5007.3  463.08  5007.5  462.58  5011.0  462.58  5011.3  463.08
  5049.3  463.36  5069.3  464.58  5089.3  466.02  5109.3  467.77  5119.3  467.73
  5149.3  470.01  5159.3  471.28  5169.3  471.94  5196.8  474.69  5199.3  474.69
#Mann=3,-1,0
  4460.5    0.05       0  5007.3    0.04       0  5011.3    0.05       0
Bank Sta=5007.3,5011.3
Exp/Cntr=0.3,0.1

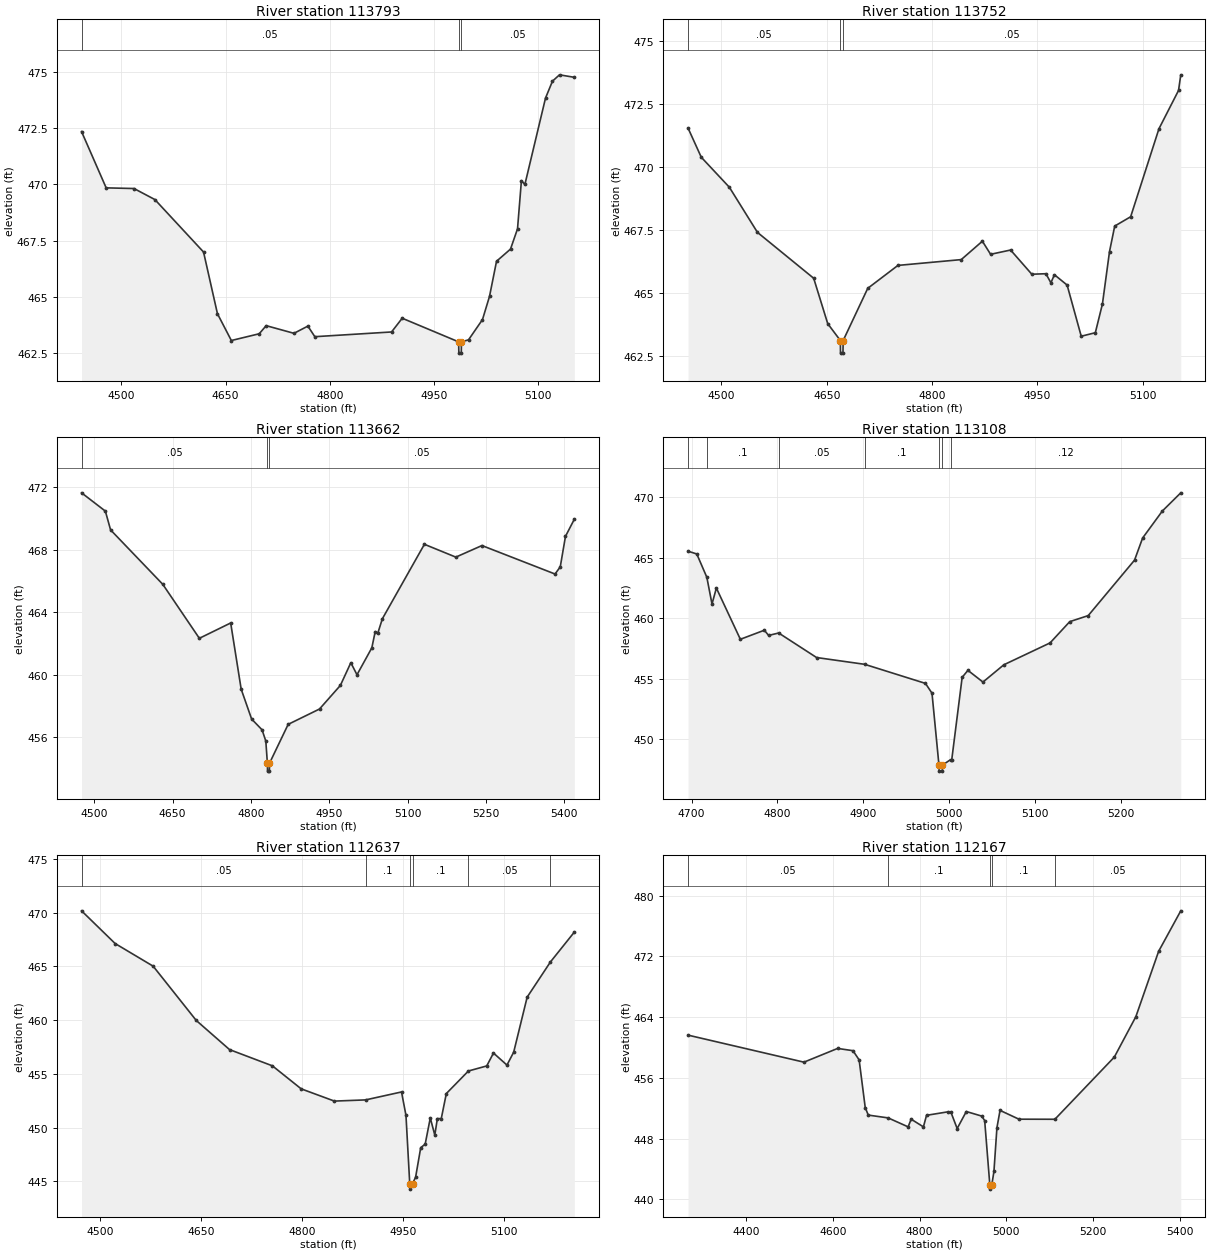
Type RM Length L Ch R = 1,113793,41,41,41
BEGIN DESCRIPTION:
Mapping XS 7f8fd1f9
END DESCRIPTION:
XS GIS Cut Line= 3
      2789831.42      6802581.12      2789434.62      6802568.48
      2789124.85      6802604.80
#Sta/Elev= 30
  4442.8  472.35  4478.2  469.85  4518.3  469.82  4548.3  469.33  4618.3  467.00
  4638.3  464.26  4658.3  463.07  4698.4  463.37  4708.4  463.73  4748.4  463.39
  4768.4  463.71  4778.4  463.24  4888.8  463.45  4904.1  464.06  4985.3  463.01
  4985.6  462.51  4989.1  462.51  4989.3  463.01  4999.5  463.10  5019.6  464.00
  5029.7  465.03  5039.8  466.59  5059.9  467.13  5070.0  468.03  5075.6  470.17
  5080.6  470.00  5110.3  473.84  5120.3  474.59  5130.4  474.87  5151.7  474.76
#Mann=3,-1,0
  4442.8    0.05       0  4985.3    0.04       0  4989.3    0.05       0
Bank Sta=4985.3,4989.3
Exp/Cntr=0.3,0.1

Type RM Length L Ch R = 1,113752,90,90,90
BEGIN DESCRIPTION:
Mapping XS 37faa867
END DESCRIPTION:
XS GIS Cut Line= 4
      2789834.93      6802529.25      2789576.92      6802525.32
      2789422.25      6802534.40      2789135.07      6802566.04
#Sta/Elev= 30
  4452.4  471.53  4471.3  470.37  4511.3  469.18  4551.3  467.39  4631.4  465.57
  4651.4  463.77  4669.4  463.10  4669.6  462.60  4673.1  462.60  4673.4  463.10
  4708.4  465.17  4751.4  466.08  4841.6  466.31  4871.7  467.04  4883.4  466.52
  4911.9  466.69  4942.1  465.73  4962.2  465.75  4969.3  465.39  4974.3  465.71
  4992.4  465.30  5012.5  463.27  5032.6  463.41  5042.7  464.55  5052.8  466.63
  5060.2  467.64  5082.9  468.01  5123.2  471.50  5151.1  473.02  5154.3  473.64
#Mann=3,-1,0
  4452.4    0.05       0  4669.4    0.04       0  4673.4    0.05       0
Bank Sta=4669.4,4673.4
Exp/Cntr=0.3,0.1

Type RM Length L Ch R = 1,113662,554,554,554
BEGIN DESCRIPTION:
Caney Creek 146.0
END DESCRIPTION:
XS GIS Cut Line= 4
      2789851.54      6802485.51      2789327.43      6802471.47
      2789174.07      6802489.15      2788909.08      6802485.03
#Sta/Elev= 30
  4475.7  471.64  4521.3  470.47  4531.3  469.27  4631.3  465.79  4701.3  462.34
  4761.3  463.32  4781.4  459.09  4801.4  457.18  4821.4  456.49  4828.6  455.77
  4831.6  454.35  4831.9  453.85  4835.4  453.85  4835.6  454.35  4871.4  456.84
  4931.4  457.82  4971.4  459.33  4991.4  460.78  5003.2  460.01  5031.6  461.73
  5038.1  462.77  5043.1  462.67  5051.8  463.59  5132.3  468.35  5192.5  467.53
  5242.5  468.27  5382.5  466.45  5392.5  466.91  5402.5  468.86  5419.4  469.95
#Mann=3,-1,0
  4475.7    0.05       0  4831.6    0.04       0  4835.6    0.05       0
Bank Sta=4831.6,4835.6
Exp/Cntr=0.3,0.1

Type RM Length L Ch R = 1,113108,471,471,471
BEGIN DESCRIPTION:
Caney Creek 145.0
END DESCRIPTION:
XS GIS Cut Line= 3
      2789826.05      6802111.01      2789526.00      6802061.00
      2789276.04      6801961.02
#Sta/Elev= 30
  4695.9  465.54  4706.1  465.31  4717.8  463.38  4723.8  461.17  4728.9  462.49
  4756.8  458.25  4784.7  459.00  4789.7  458.57  4801.4  458.77  4845.5  456.74
  4901.4  456.18  4972.2  454.60  4979.8  453.79  4987.9  447.84  4988.2  447.34
  4991.7  447.34  4992.0  447.84  5001.4  448.29  5002.8  448.29  5014.9  455.10
  5021.6  455.68  5039.1  454.71  5063.4  456.14  5117.2  457.95  5140.1  459.71
  5161.6  460.21  5215.5  464.80  5224.9  466.63  5247.8  468.86  5269.3  470.37
#Mann=7,-1,0
  4695.9    0.05       0  4717.8     0.1       0  4801.4    0.05       0
  4901.4     0.1       0  4987.9    0.07       0  4992.0     0.1       0
  5001.4    0.12       0
Bank Sta=4987.9,4992
Exp/Cntr=0.3,0.1

Type RM Length L Ch R = 1,112637,470,470,470
BEGIN DESCRIPTION:
Caney Creek 144.0
END DESCRIPTION:
XS GIS Cut Line= 3
      2790075.97      6802010.98      2789676.00      6801661.00
      2789475.97      6801661.00
#Sta/Elev= 30
  4473.0  470.16  4522.8  467.12  4579.3  465.01  4643.3  459.96  4692.7  457.25
  4756.3  455.74  4799.0  453.60  4848.3  452.46  4894.6  452.57  4948.0  453.31
  4954.6  451.13  4960.2  444.77  4960.5  444.27  4964.3  444.77  4968.9  445.38
  4976.5  448.13  4983.1  448.45  4990.7  450.89  4997.4  449.30  5001.2  450.83
  5007.0  450.83  5014.5  453.16  5047.3  455.26  5074.5  455.73  5084.5  456.93
  5104.5  455.81  5114.5  457.01  5134.5  462.13  5169.0  465.40  5204.5  468.18
#Mann=6,-1,0
  4473.0    0.05       0  4894.6     0.1       0  4960.2    0.07       0
  4964.3     0.1       0  5047.3    0.05       0  5169.0    0.12       0
Bank Sta=4960.2,4964.3
Exp/Cntr=0.3,0.1

Type RM Length L Ch R = 1,112167,469,469,469
BEGIN DESCRIPTION:
Caney Creek 143.0
END DESCRIPTION:
XS GIS Cut Line= 3
      2790438.73      6801836.73      2789926.00      6801311.00
      2789725.98      6800960.97
#Sta/Elev= 30
  4265.4  461.63  4533.0  458.07  4610.8  459.88  4646.2  459.58  4660.4  458.37
  4674.5  452.09  4681.5  451.10  4727.4  450.73  4773.5  449.55  4780.5  450.56
  4808.8  449.55  4816.0  451.07  4865.4  451.53  4872.5  451.45  4886.7  449.33
  4907.8  451.57  4943.3  450.97  4950.2  450.38  4962.2  441.85  4962.6  441.35
  4966.5  441.85  4971.6  443.68  4978.5  449.44  4985.7  451.72  5029.3  450.56
  5112.3  450.55  5249.5  458.74  5299.2  464.06  5351.8  472.67  5402.9  478.00
#Mann=5,-1,0
  4265.4    0.05       0  4727.4     0.1       0  4962.2    0.07       0
  4966.5     0.1       0  5112.3    0.05       0
Bank Sta=4962.2,4966.5
Exp/Cntr=0.3,0.1

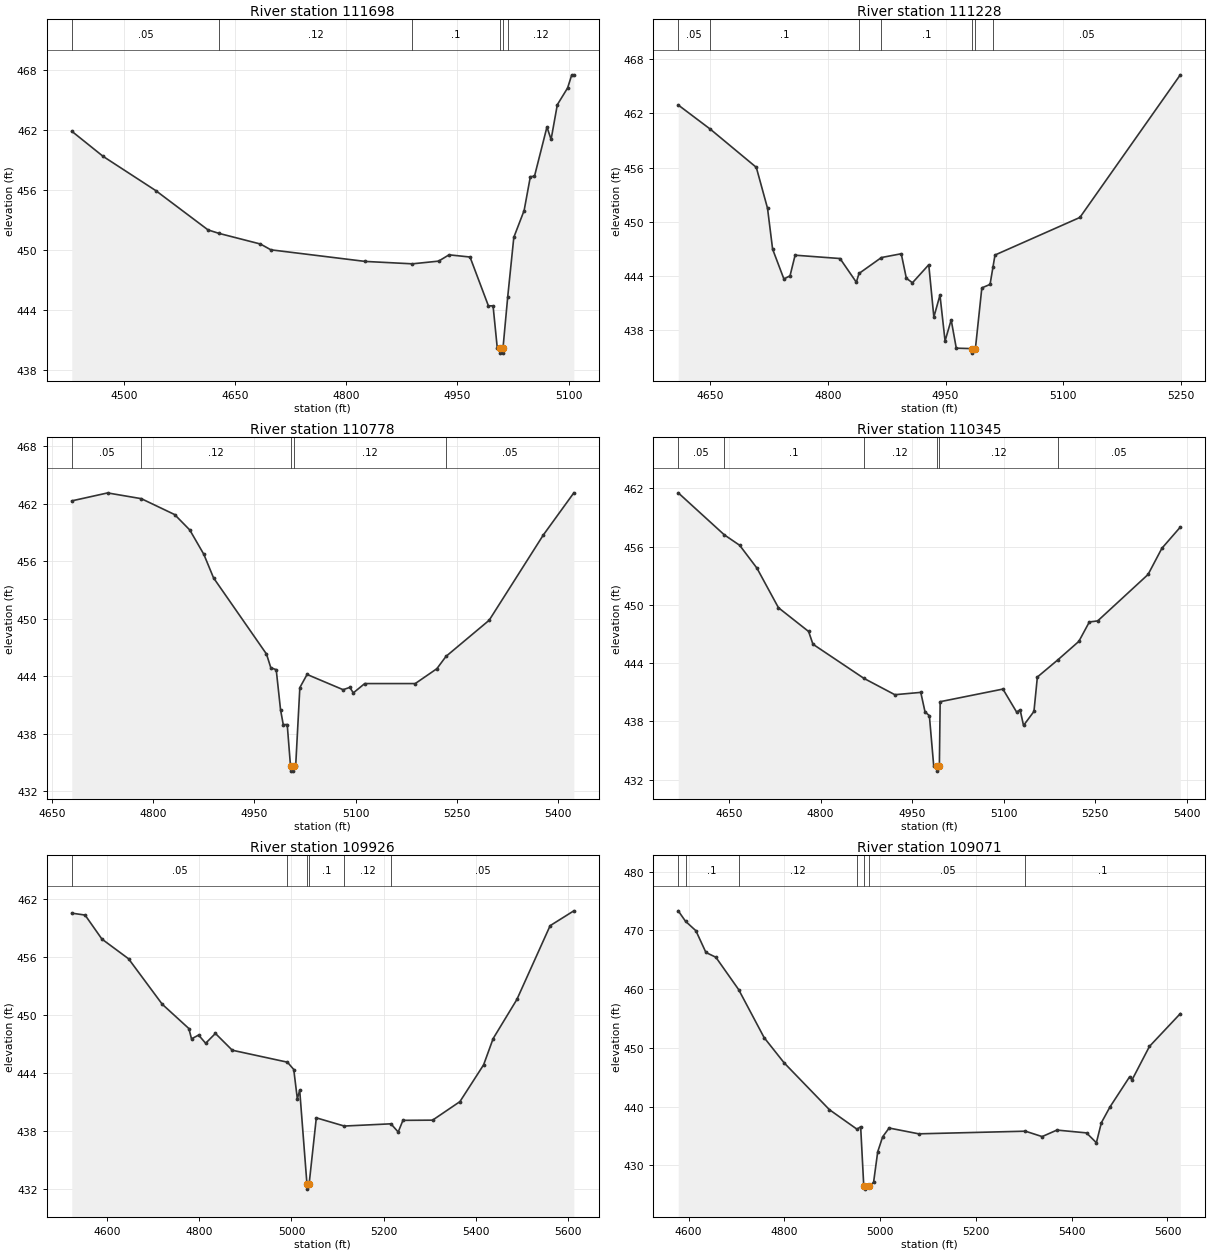
Type RM Length L Ch R = 1,111698,470,470,470
BEGIN DESCRIPTION:
Caney Creek 142.0
END DESCRIPTION:
XS GIS Cut Line= 3
      2790576.02      6801361.02      2790176.00      6800961.00
      2790126.01      6800861.01
#Sta/Elev= 30
  4429.7  461.85  4472.1  459.33  4542.9  455.92  4613.6  451.98  4628.6  451.63
  4684.3  450.57  4698.4  449.99  4825.7  448.83  4889.3  448.59  4924.7  448.86
  4938.8  449.49  4967.1  449.27  4991.9  444.39  4998.2  444.39  5003.8  440.22
  5007.2  440.16  5007.6  439.66  5011.2  439.66  5011.6  440.16  5018.0  445.31
  5026.2  451.24  5040.1  453.92  5048.5  457.30  5054.1  457.35  5070.9  462.27
  5076.5  461.03  5084.9  464.50  5098.8  466.18  5104.4  467.49  5107.2  467.49
#Mann=6,-1,0
  4429.7    0.05       0  4628.6    0.12       0  4889.3     0.1       0
  5007.2    0.07       0  5011.6     0.1       0  5018.0    0.12       0
Bank Sta=5007.2,5011.6
Exp/Cntr=0.3,0.1

Type RM Length L Ch R = 1,111228,450,450,450
BEGIN DESCRIPTION:
Caney Creek 141.0
END DESCRIPTION:
XS GIS Cut Line= 3
      2790876.02      6801011.02      2790576.00      6800761.00
      2790376.04      6800611.03
#Sta/Elev= 30
  4608.9  462.94  4649.8  460.26  4708.5  456.02  4722.8  451.48  4729.3  446.94
  4743.7  443.63  4751.5  443.98  4758.0  446.27  4815.3  445.90  4836.1  443.27
  4839.5  444.24  4868.1  446.01  4893.4  446.43  4899.9  443.71  4907.7  443.21
  4928.5  445.21  4935.0  439.40  4942.8  441.84  4949.3  436.75  4957.1  439.09
  4963.6  435.95  4983.5  435.90  4984.0  435.40  4988.0  435.90  4996.2  442.64
  5006.7  443.03  5010.5  445.00  5013.0  446.29  5121.3  450.46  5249.4  466.29
#Mann=7,-1,0
  4608.9    0.05       0  4649.8     0.1       0  4839.5    0.12       0
  4868.1     0.1       0  4983.5    0.07       0  4988.0     0.1       0
  5010.5    0.05       0
Bank Sta=4983.5,4988
Exp/Cntr=0.3,0.1

Type RM Length L Ch R = 1,110778,433,433,433
BEGIN DESCRIPTION:
Caney Creek 140.0
END DESCRIPTION:
XS GIS Cut Line= 3
      2791123.78      6800808.03      2790926.00      6800561.00
      2790526.05      6800411.02
#Sta/Elev= 30
  4679.4  462.29  4732.5  463.12  4782.4  462.52  4831.8  460.86  4854.2  459.25
  4875.0  456.71  4889.4  454.25  4967.8  446.30  4974.2  444.87  4982.2  444.67
  4988.6  440.49  4992.6  438.94  4998.5  438.94  5003.4  434.58  5003.8  434.08
  5007.4  434.08  5007.9  434.58  5011.0  434.59  5017.2  442.80  5027.9  444.17
  5081.3  442.58  5091.1  442.82  5096.4  442.25  5113.3  443.22  5188.1  443.22
  5220.1  444.77  5233.7  446.06  5297.6  449.83  5377.7  458.72  5423.0  463.13
#Mann=5,-1,0
  4679.4    0.05       0  4782.4    0.12       0  5003.4    0.07       0
  5007.9    0.12       0  5233.7    0.05       0
Bank Sta=5003.4,5007.9
Exp/Cntr=0.3,0.1

Type RM Length L Ch R = 1,110345,419,419,419
BEGIN DESCRIPTION:
Caney Creek 139.0
END DESCRIPTION:
XS GIS Cut Line= 3
      2791332.46      6800466.92      2791026.00      6800161.00
      2790673.71      6799993.04
#Sta/Elev= 30
  4566.5  461.53  4642.1  457.20  4667.2  456.13  4695.5  453.78  4730.8  449.70
  4780.3  447.25  4787.4  445.94  4871.1  442.42  4921.7  440.74  4964.2  440.98
  4971.2  438.97  4978.3  438.58  4985.4  433.43  4990.1  433.37  4990.6  432.87
  4994.7  433.37  4996.0  440.02  5098.9  441.32  5121.4  438.95  5127.1  439.19
  5132.7  437.57  5149.8  439.02  5155.4  442.56  5188.8  444.32  5223.4  446.23
  5240.6  448.23  5254.3  448.34  5336.9  453.12  5359.6  455.82  5389.8  458.00
#Mann=6,-1,0
  4566.5    0.05       0  4642.1     0.1       0  4871.1    0.12       0
  4990.1    0.07       0  4994.7    0.12       0  5188.8    0.05       0
Bank Sta=4990.1,4994.7
Exp/Cntr=0.3,0.1

Type RM Length L Ch R = 1,109926,855,855,855
BEGIN DESCRIPTION:
Caney Creek 138.0
END DESCRIPTION:
XS GIS Cut Line= 3
      2791526.01      6800311.02      2791276.00      6799911.00
      2790675.99      6799761.00
#Sta/Elev= 30
  4523.0  460.57  4551.9  460.37  4588.5  457.88  4646.3  455.84  4719.4  451.13
  4777.2  448.61  4783.0  447.54  4798.4  447.93  4813.7  447.08  4834.9  448.10
  4871.5  446.36  4991.3  445.12  5005.0  444.36  5012.8  441.32  5017.9  442.22
  5033.7  432.46  5034.2  431.96  5038.3  432.46  5054.0  439.35  5114.6  438.50
  5216.0  438.73  5231.8  437.88  5242.1  439.09  5306.5  439.11  5365.8  441.03
  5417.3  444.85  5438.0  447.57  5489.5  451.62  5561.7  459.27  5613.2  460.81
#Mann=6,-1,0
  4523.0    0.05       0  4991.3     0.1       0  5033.7    0.07       0
  5038.3     0.1       0  5114.6    0.12       0  5216.0    0.05       0
Bank Sta=5033.7,5038.3
Exp/Cntr=0.3,0.1

Type RM Length L Ch R = 1,109071,483,483,483
BEGIN DESCRIPTION:
Caney Creek 137.0
END DESCRIPTION:
XS GIS Cut Line= 3
      2791776.00      6799011.00      2791426.00      6799261.00
      2790825.98      6799411.00
#Sta/Elev= 30
  4578.2  473.35  4593.5  471.56  4615.1  469.96  4636.0  466.26  4656.8  465.44
  4704.3  459.94  4757.6  451.75  4799.4  447.45  4894.0  439.47  4951.7  436.14
  4959.2  436.57  4965.7  426.44  4967.3  425.94  4977.1  426.44  4986.2  427.10
  4994.8  432.30  5005.2  434.86  5018.6  436.35  5080.5  435.36  5303.3  435.81
  5338.2  434.89  5369.1  436.00  5430.9  435.52  5451.5  433.84  5461.9  437.25
  5479.9  439.94  5521.1  445.10  5526.3  444.60  5562.4  450.26  5626.8  455.84
#Mann=7,-1,0
  4578.2    0.05       0  4593.5     0.1       0  4704.3    0.12       0
  4951.7    0.05       0  4965.7    0.05       0  4977.1    0.05       0
  5303.3     0.1       0
Bank Sta=4965.7,4977.1
Exp/Cntr=0.3,0.1

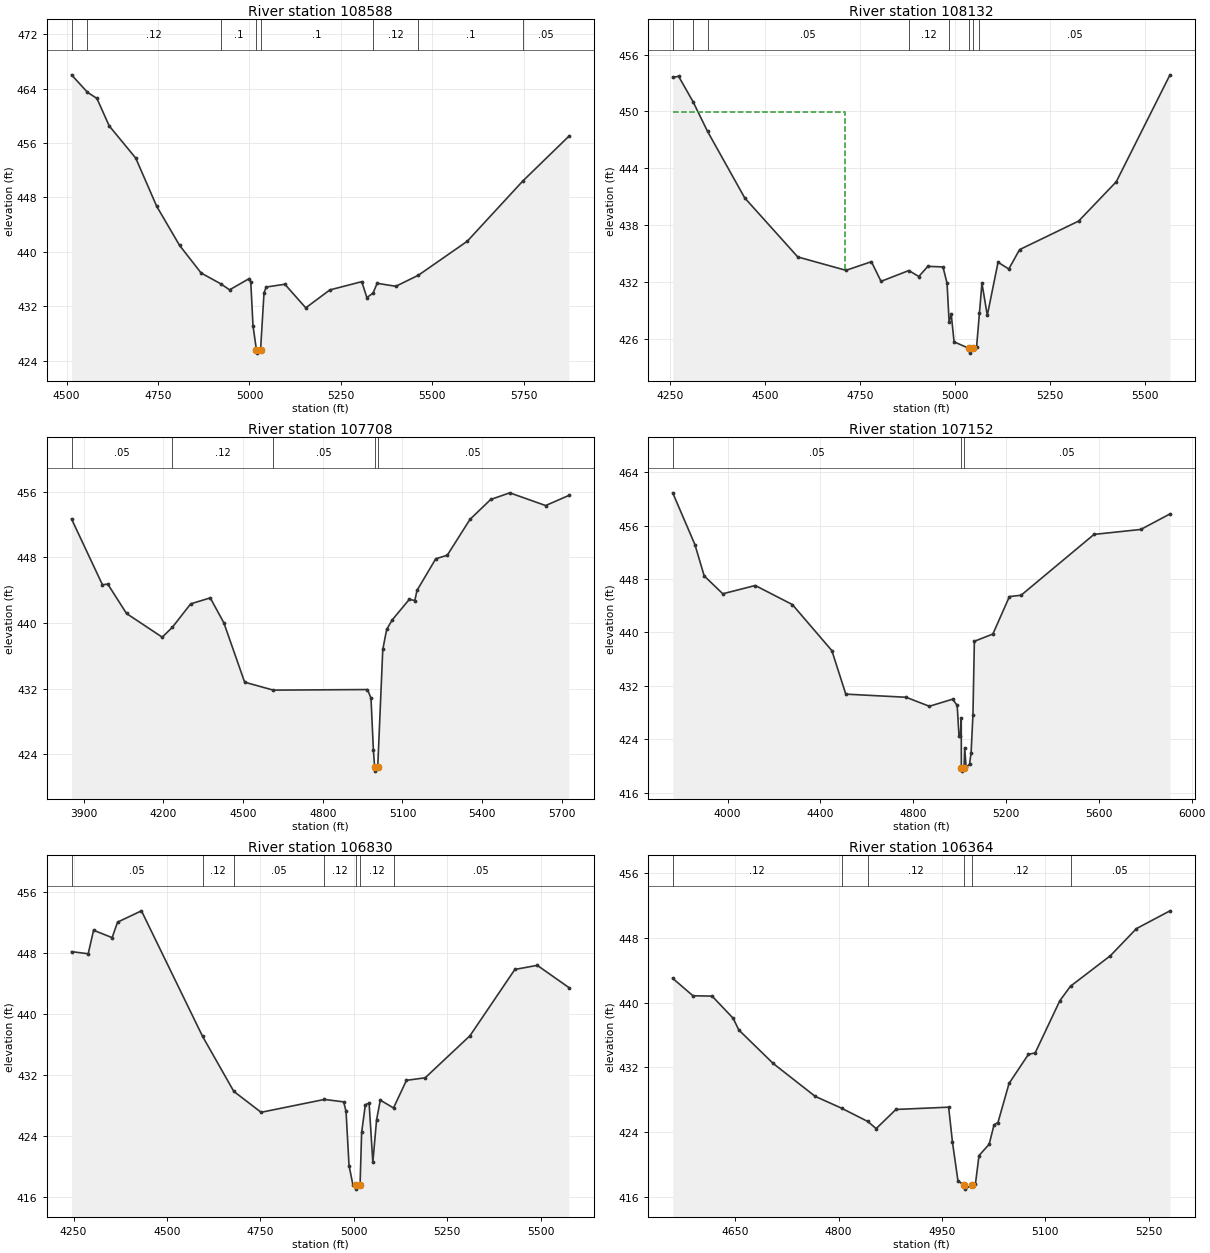
Type RM Length L Ch R = 1,108588,456,456,456
BEGIN DESCRIPTION:
Caney Creek 136.0
END DESCRIPTION:
XS GIS Cut Line= 3
      2791789.75      6798677.40      2791326.00      6798811.00
      2790597.14      6799298.36
#Sta/Elev= 30
  4513.6  466.02  4557.2  463.45  4583.0  462.55  4616.6  458.51  4689.2  453.77
  4746.4  446.69  4808.9  440.94  4868.0  436.87  4921.0  435.30  4945.7  434.40
  4999.2  436.05  5003.7  435.49  5009.7  429.12  5019.0  425.59  5020.6  425.09
  5030.4  425.59  5039.8  433.96  5045.8  434.81  5096.8  435.22  5153.9  431.75
  5219.9  434.39  5307.0  435.60  5321.0  433.26  5337.8  433.92  5349.1  435.36
  5400.1  434.92  5461.9  436.55  5595.3  441.54  5747.0  450.39  5873.0  456.98
#Mann=8,-1,0
  4513.6    0.05       0  4557.2    0.12       0  4921.0     0.1       0
  5019.0    0.07       0  5030.4     0.1       0  5337.8    0.12       0
  5461.9     0.1       0  5747.0    0.05       0
Bank Sta=5019,5030.4
Exp/Cntr=0.3,0.1

Type RM Length L Ch R = 1,108132,424,424,424
BEGIN DESCRIPTION:
Caney Creek 135.0
END DESCRIPTION:
XS GIS Cut Line= 3
      2791675.99      6798411.00      2790976.00      6798661.00
      2790575.99      6799061.01
#Sta/Elev= 30
  4256.3  453.58  4271.7  453.71  4309.8  451.03  4348.0  447.90  4445.8  440.90
  4585.5  434.68  4712.4  433.27  4779.3  434.18  4804.7  432.11  4877.9  433.25
  4904.0  432.62  4927.9  433.69  4967.7  433.63  4978.4  431.92  4983.9  427.83
  4989.5  428.63  4996.9  425.74  5036.3  425.05  5037.9  424.55  5047.8  425.05
  5056.2  425.21  5063.8  428.82  5070.3  431.91  5084.4  428.53  5112.7  434.12
  5141.0  433.41  5169.3  435.45  5324.9  438.46  5423.9  442.60  5565.3  453.86
#Mann=8,-1,0
  4256.3    0.05       0  4309.8    0.12       0  4348.0    0.05       0
  4877.9    0.12       0  4983.9     0.1       0  5036.3    0.07       0
  5047.8     0.1       0  5063.8    0.05       0
#XS Ineff=2,0
    0.00 4709.60  449.97               0
Permanent Ineff=
       F       F
Bank Sta=5036.3,5047.8
Exp/Cntr=0.3,0.1

Type RM Length L Ch R = 1,107708,556,556,556
BEGIN DESCRIPTION:
Caney Creek 134.0
END DESCRIPTION:
XS GIS Cut Line= 4
      2791711.60      6797988.22      2791235.10      6798041.49
      2790676.00      6798411.00      2790102.49      6798849.37
#Sta/Elev= 30
  3854.6  452.68  3970.9  444.66  3991.0  444.74  4061.5  441.16  4196.0  438.27
  4234.1  439.48  4303.0  442.33  4376.7  443.06  4427.9  440.02  4506.1  432.79
  4613.9  431.82  4968.3  431.89  4981.6  430.85  4990.7  424.48  4995.4  422.45
  4997.0  421.95  5007.0  422.45  5026.0  436.77  5040.6  439.21  5061.4  440.37
  5125.8  442.88  5146.6  442.74  5154.8  443.97  5225.5  447.83  5268.6  448.25
  5354.3  452.63  5432.2  455.05  5503.9  455.86  5639.0  454.31  5726.1  455.54
#Mann=5,-1,0
  3854.6    0.05       0  4234.1    0.12       0  4613.9    0.05       0
  4995.4    0.04       0  5007.0    0.05       0
Bank Sta=4995.4,5007
Exp/Cntr=0.3,0.1

Type RM Length L Ch R = 1,107152,322,322,322
BEGIN DESCRIPTION:
Caney Creek 133.0
END DESCRIPTION:
XS GIS Cut Line= 3
      2791761.72      6797927.15      2790525.50      6797900.83
      2789997.01      6798637.46
#Sta/Elev= 30
  3763.5  460.93  3859.2  453.17  3899.2  448.48  3979.3  445.80  4119.3  447.04
  4279.3  444.18  4449.4  437.28  4509.4  430.76  4769.4  430.29  4869.5  428.94
  4969.5  430.00  4989.5  429.07  4997.2  424.54  5003.2  424.54  5007.0  427.12
  5007.4  419.72  5009.0  419.22  5019.0  419.72  5021.8  422.73  5027.9  419.80
  5042.7  420.25  5049.4  421.97  5057.4  427.65  5063.5  438.68  5143.3  439.77
  5214.6  445.38  5264.9  445.58  5579.3  454.70  5780.7  455.44  5906.6  457.77
#Mann=3,-1,0
  3763.5    0.05       0  5007.4    0.03       0  5019.0    0.05       0
Bank Sta=5007.4,5019
Exp/Cntr=0.3,0.1

Type RM Length L Ch R = 1,106830,466,466,466
BEGIN DESCRIPTION:
Caney Creek 132.0
END DESCRIPTION:
XS GIS Cut Line= 3
      2791216.76      6797138.85      2790626.00      6797611.00
      2790051.64      6797601.16
#Sta/Elev= 30
  4244.4  448.20  4289.0  447.92  4303.4  451.01  4353.1  450.04  4367.5  452.07
  4431.5  453.56  4595.1  437.07  4678.6  429.85  4751.7  427.10  4921.2  428.79
  4972.6  428.47  4979.0  427.23  4987.0  420.10  4997.5  417.55  5004.9  417.51
  5006.5  417.01  5016.5  417.51  5020.7  424.45  5030.7  428.09  5040.7  428.31
  5050.7  420.51  5060.7  426.11  5070.7  428.70  5106.0  427.67  5140.7  431.30
  5190.7  431.63  5310.7  437.16  5430.7  445.86  5490.7  446.40  5575.1  443.49
#Mann=7,-1,0
  4244.4    0.05       0  4595.1    0.12       0  4678.6    0.05       0
  4921.2    0.12       0  5004.9    0.07       0  5016.5    0.12       0
  5106.0    0.05       0
Bank Sta=5004.9,5016.5
Exp/Cntr=0.3,0.1

Type RM Length L Ch R = 1,106364,430,430,430
BEGIN DESCRIPTION:
Caney Creek 131.0
END DESCRIPTION:
XS GIS Cut Line= 3
      2790813.95      6797010.86      2790426.00      6797211.00
      2790175.78      6797347.99
#Sta/Elev= 30
  4559.3  442.98  4588.7  440.83  4616.5  440.79  4647.0  438.06  4655.2  436.62
  4705.1  432.49  4766.0  428.44  4804.5  426.97  4842.4  425.34  4854.6  424.46
  4883.3  426.82  4959.8  427.10  4965.4  422.76  4973.3  418.04  4981.7  417.50
  4983.4  417.00  4993.4  417.50  4998.7  417.65  5003.9  421.14  5018.6  422.53
  5025.7  424.92  5031.4  425.21  5047.5  430.03  5075.6  433.61  5085.4  433.79
  5121.2  440.22  5136.7  442.01  5194.5  445.76  5232.4  449.11  5281.1  451.30
#Mann=6,-1,0
  4559.3    0.12       0  4804.5    0.05       0  4842.4    0.12       0
  4981.7    0.07       0  4993.4    0.12       0  5136.7    0.05       0
Bank Sta=4981.7,4993.4
Exp/Cntr=0.3,0.1