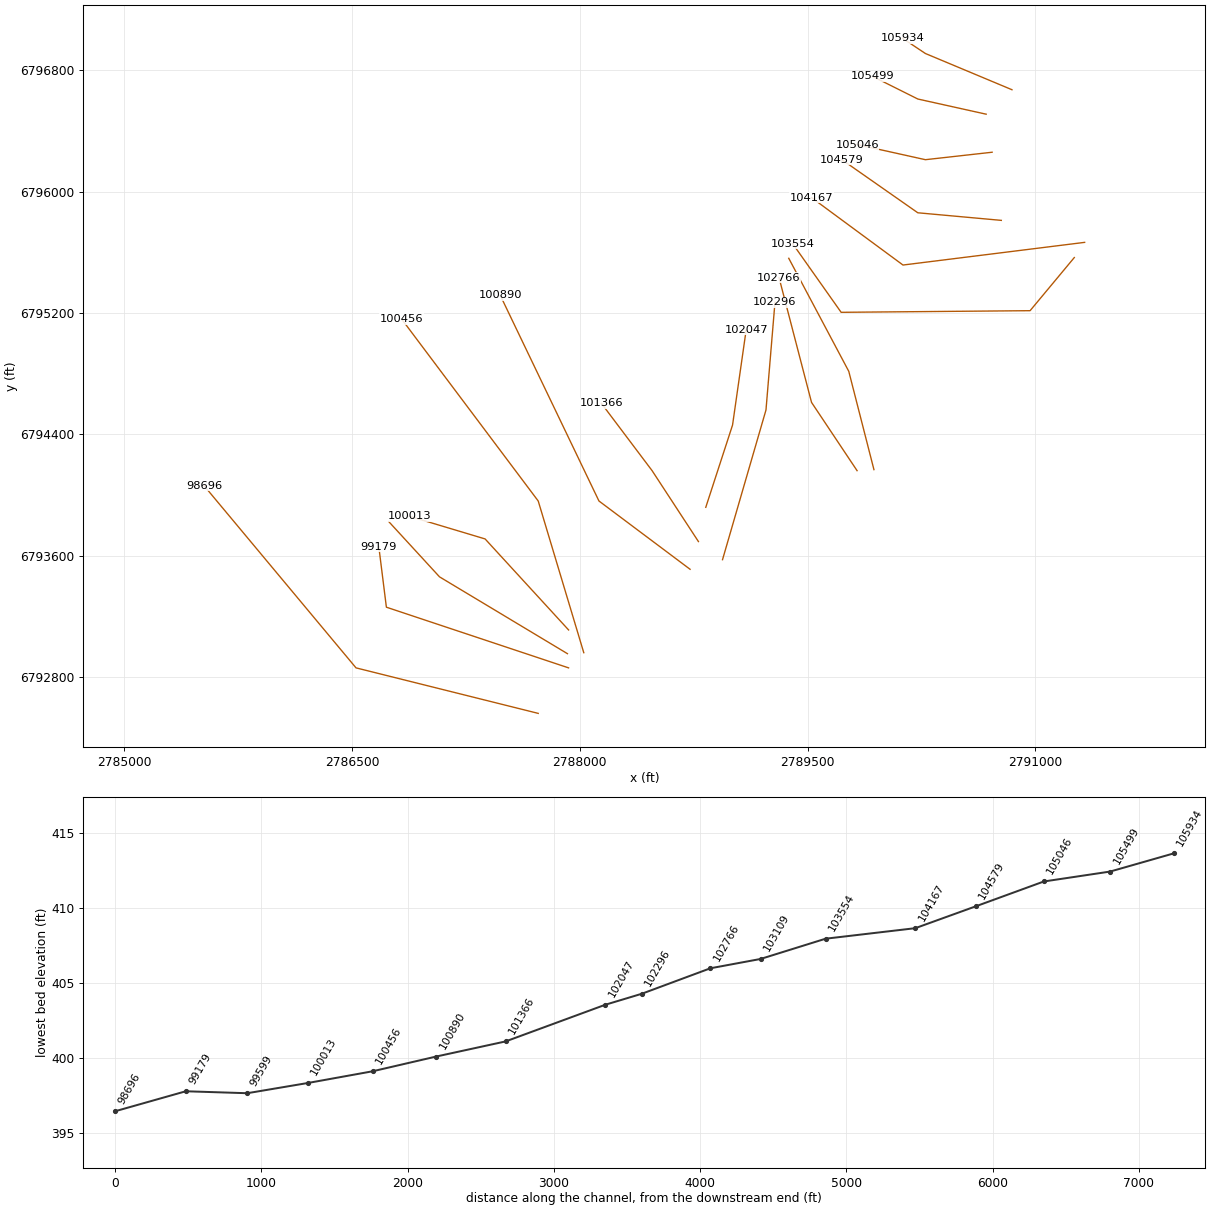
HEC-RAS study Caney Creek.prj: Caney Creek Base Level Engineering

--- Caney Creek.g01 (geometry) --- (continued)

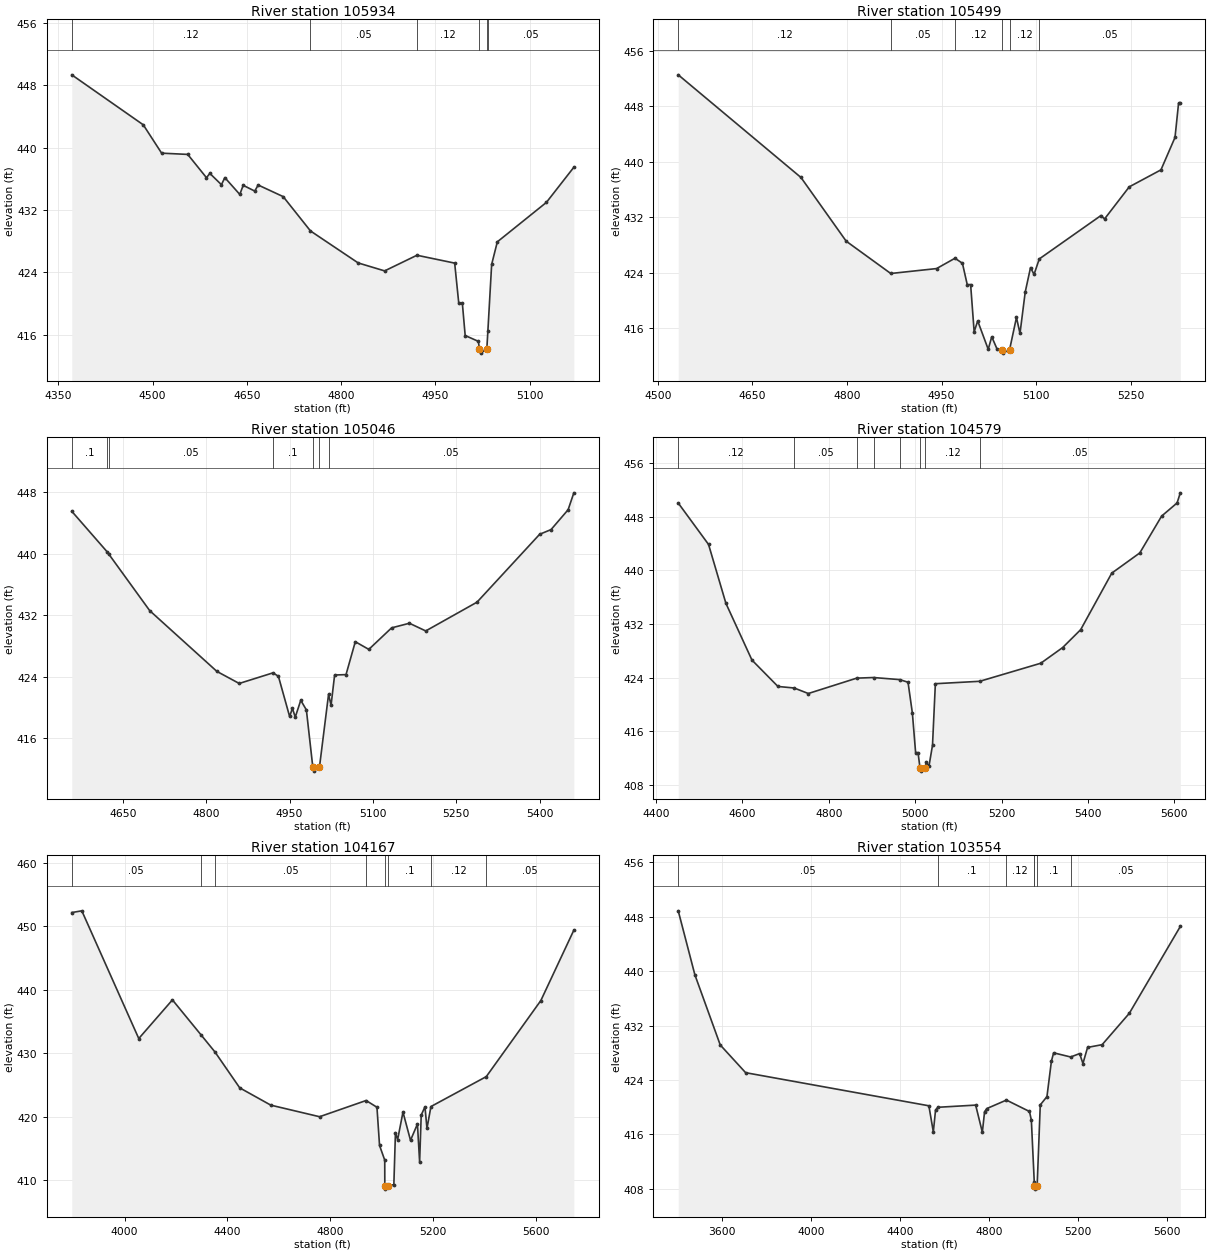
Type RM Length L Ch R = 1,105934,435,435,435
BEGIN DESCRIPTION:
Caney Creek 130.0
END DESCRIPTION:
XS GIS Cut Line= 3
      2790846.12      6796672.21      2790276.00      6796911.00
      2790125.98      6797011.01
#Sta/Elev= 30
  4371.6  449.36  4485.3  442.94  4514.5  439.30  4556.0  439.14  4585.8  436.15
  4591.2  436.70  4609.6  435.25  4615.0  436.16  4638.8  434.00  4644.2  435.17
  4662.6  434.43  4668.0  435.21  4707.8  433.72  4751.2  429.31  4827.1  425.20
  4869.1  424.18  4920.5  426.19  4980.5  425.18  4987.0  420.03  4992.7  420.03
  4997.2  415.88  5018.2  415.13  5019.9  414.12  5021.6  413.62  5031.6  414.12
  5033.3  416.46  5039.3  425.01  5048.3  427.91  5126.4  432.98  5170.0  437.49
#Mann=6,-1,0
  4371.6    0.12       0  4751.2    0.05       0  4920.5    0.12       0
  5019.9    0.07       0  5031.6    0.12       0  5033.3    0.05       0
Bank Sta=5019.9,5031.6
Exp/Cntr=0.3,0.1

Type RM Length L Ch R = 1,105499,453,453,453
BEGIN DESCRIPTION:
Caney Creek 129.0
END DESCRIPTION:
XS GIS Cut Line= 3
      2790676.02      6796510.99      2790226.00      6796611.00
      2789926.01      6796761.00
#Sta/Elev= 30
  4532.4  452.53  4727.1  437.73  4798.8  428.55  4869.5  423.89  4942.2  424.60
  4971.4  426.09  4983.2  425.36  4990.8  422.29  4996.2  422.29  5001.8  415.47
  5007.4  417.06  5024.1  412.96  5029.7  414.77  5038.1  413.00  5046.1  412.91
  5047.8  412.41  5058.0  412.91  5068.9  417.55  5074.5  415.25  5082.8  421.22
  5091.2  424.74  5096.8  423.76  5105.1  425.99  5203.0  432.25  5208.6  431.75
  5247.8  436.38  5298.1  438.83  5320.4  443.51  5326.0  448.41  5328.8  448.41
#Mann=6,-1,0
  4532.4    0.12       0  4869.5    0.05       0  4971.4    0.12       0
  5046.1    0.07       0  5058.0    0.12       0  5105.1    0.05       0
Bank Sta=5046.1,5058
Exp/Cntr=0.3,0.1

Type RM Length L Ch R = 1,105046,467,467,467
BEGIN DESCRIPTION:
Caney Creek 128.0
END DESCRIPTION:
XS GIS Cut Line= 3
      2790715.35      6796260.19      2790276.00      6796211.00
      2789825.97      6796311.01
#Sta/Elev= 30
  4558.3  445.54  4622.4  440.23  4625.2  439.94  4698.5  432.62  4819.3  424.72
  4859.5  423.15  4920.3  424.53  4930.0  424.08  4950.1  418.87  4955.3  419.90
  4960.3  418.77  4970.2  420.96  4980.3  419.71  4991.9  412.25  4993.6  411.75
  5003.8  412.25  5020.2  421.74  5024.7  420.32  5031.1  424.25  5051.6  424.30
  5068.3  428.58  5092.6  427.58  5133.6  430.38  5165.6  430.98  5195.0  429.98
  5287.2  433.72  5399.9  442.55  5420.4  443.16  5451.1  445.74  5461.4  447.94
#Mann=7,-1,0
  4558.3     0.1       0  4622.4    0.12       0  4625.2    0.05       0
  4920.3     0.1       0  4991.9    0.07       0  5003.8     0.1       0
  5020.2    0.05       0
Bank Sta=4991.9,5003.8
Exp/Cntr=0.3,0.1

Type RM Length L Ch R = 1,104579,412,412,412
BEGIN DESCRIPTION:
Caney Creek 127.0
END DESCRIPTION:
XS GIS Cut Line= 3
      2790775.96      6795811.00      2790226.00      6795861.00
      2789725.96      6796211.03
#Sta/Elev= 30
  4451.4  450.02  4521.6  443.85  4561.8  435.08  4622.1  426.63  4682.3  422.70
  4719.9  422.47  4752.6  421.65  4864.7  423.94  4903.6  424.03  4964.3  423.72
  4983.5  423.33  4993.6  418.72  5001.1  412.83  5006.7  412.83  5011.2  410.59
  5012.8  410.09  5023.1  410.59  5025.9  411.41  5032.0  410.83  5040.2  413.95
  5046.8  423.11  5149.6  423.47  5290.9  426.16  5341.5  428.49  5383.3  431.16
  5455.3  439.58  5520.2  442.59  5570.8  448.08  5606.5  450.03  5614.0  451.54
#Mann=8,-1,0
  4451.4    0.12       0  4719.9    0.05       0  4864.7    0.12       0
  4903.6     0.1       0  4964.3    0.12       0  5011.2    0.07       0
  5023.1    0.12       0  5149.6    0.05       0
Bank Sta=5011.2,5023.1
Exp/Cntr=0.3,0.1

Type RM Length L Ch R = 1,104167,613,613,613
BEGIN DESCRIPTION:
Caney Creek 126.0
END DESCRIPTION:
XS GIS Cut Line= 3
      2791324.78      6795666.01      2790128.38      6795516.54
      2789526.00      6795961.00
#Sta/Elev= 30
  3794.3  452.15  3833.4  452.42  4055.1  432.33  4186.1  438.41  4296.6  432.95
  4351.8  430.21  4448.1  424.57  4569.1  421.85  4758.9  420.03  4940.0  422.58
  4982.2  421.52  4992.3  415.51  5012.5  413.20  5012.8  409.14  5014.5  408.64
  5024.7  409.14  5048.0  409.35  5054.2  417.52  5062.7  416.43  5083.5  420.76
  5112.8  416.32  5139.8  418.88  5148.3  412.91  5154.5  420.29  5169.1  421.59
  5176.9  418.18  5192.3  421.63  5407.8  426.34  5620.2  438.31  5748.6  449.38
#Mann=8,-1,0
  3794.3    0.05       0  4296.6    0.12       0  4351.8    0.05       0
  4940.0     0.1       0  5012.8    0.07       0  5024.7     0.1       0
  5192.3    0.12       0  5407.8    0.05       0
Bank Sta=5012.8,5024.7
Exp/Cntr=0.3,0.1

Type RM Length L Ch R = 1,103554,445,445,445
BEGIN DESCRIPTION:
Mapping XS e0eec372
END DESCRIPTION:
XS GIS Cut Line= 4
      2791256.64      6795565.95      2790965.37      6795215.63
      2789720.95      6795204.91      2789401.88      6795657.25
#Sta/Elev= 30
  3404.9  448.88  3479.6  439.47  3593.4  429.15  3707.4  425.07  4529.9  420.20
  4549.9  416.36  4559.9  419.58  4570.2  419.98  4739.9  420.30  4769.9  416.31
  4779.9  419.32  4789.9  419.79  4878.0  421.04  4981.5  419.36  4989.9  418.09
  5003.0  408.94  5003.9  408.44  5005.6  407.94  5015.9  408.44  5029.9  420.33
  5059.9  421.55  5079.9  426.76  5089.9  427.99  5166.3  427.38  5206.6  427.88
  5221.4  426.42  5242.3  428.79  5307.6  429.19  5429.5  433.80  5658.5  446.58
#Mann=7,-1,0
  3404.9    0.05       0  4570.2     0.1       0  4878.0    0.12       0
  5003.0     0.1       0  5003.9    0.07       0  5015.9     0.1       0
  5166.3    0.05       0
Bank Sta=5003.9,5015.9
Exp/Cntr=0.3,0.1

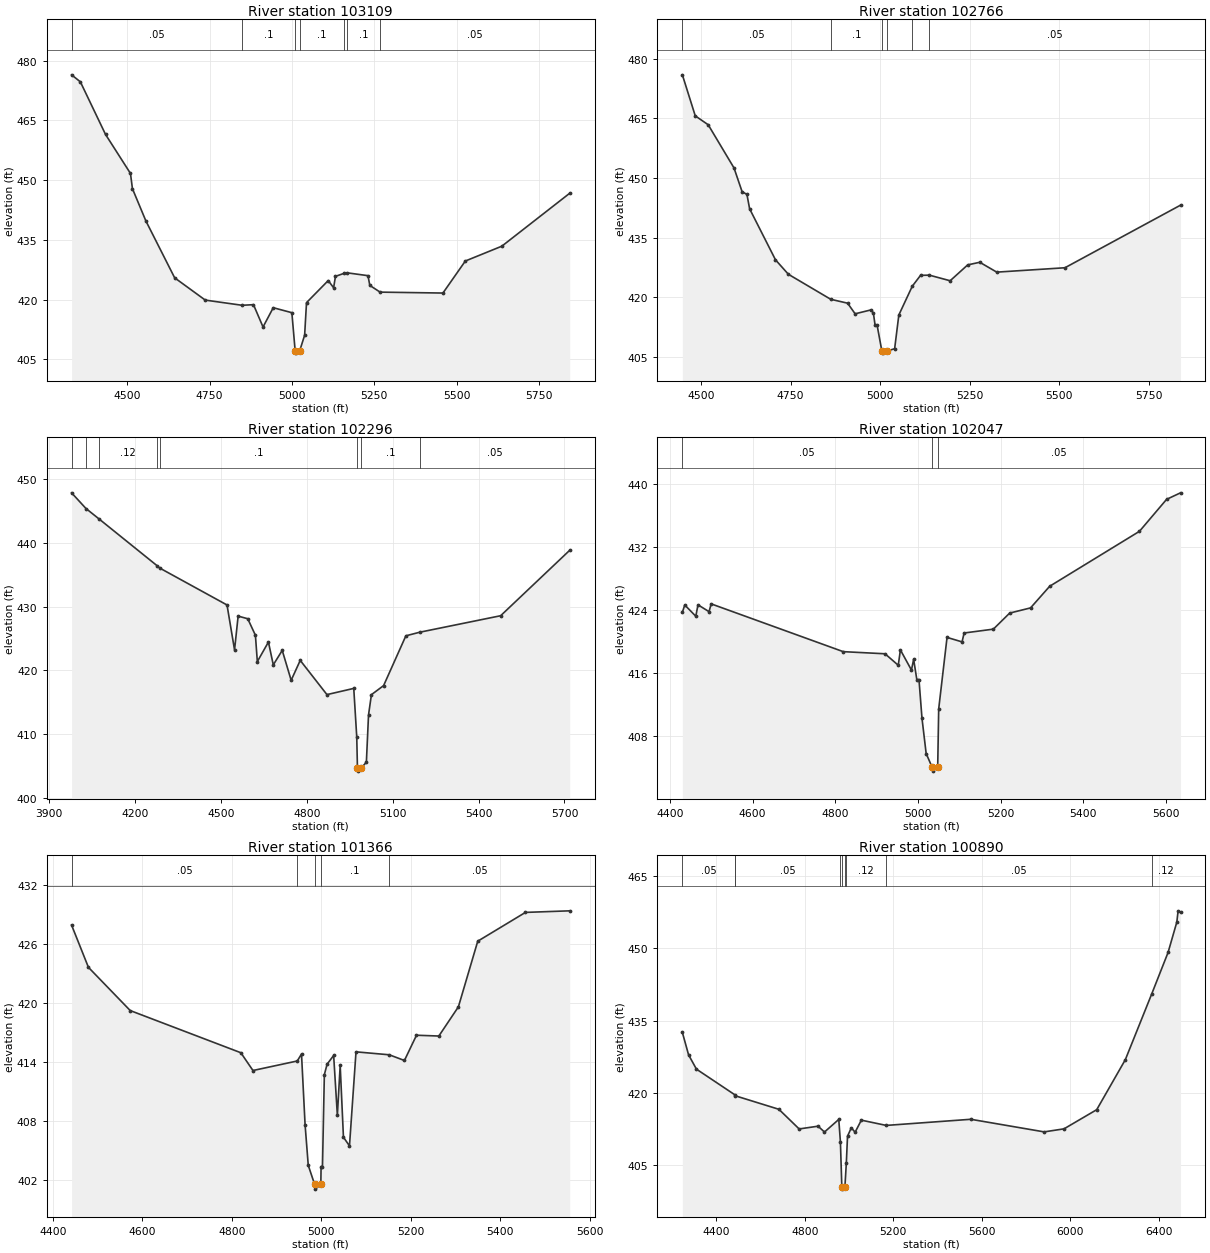
Type RM Length L Ch R = 1,103109,343,343,343
BEGIN DESCRIPTION:
Caney Creek 125.0
END DESCRIPTION:
XS GIS Cut Line= 3
      2789936.99      6794167.79      2789771.32      6794815.75
      2789376.01      6795560.99
#Sta/Elev= 30
  4331.2  476.44  4357.9  474.68  4434.3  461.48  4510.0  451.69  4516.0  447.86
  4556.8  439.77  4644.2  425.49  4737.1  419.90  4848.9  418.60  4883.5  418.75
  4912.5  413.15  4943.5  417.99  5000.0  416.74  5010.1  407.09  5012.0  406.59
  5023.5  407.09  5038.8  411.09  5044.5  419.26  5110.4  424.80  5126.8  423.00
  5132.4  425.86  5158.4  426.61  5168.3  426.74  5231.1  426.03  5236.7  423.59
  5267.9  421.90  5458.7  421.67  5526.7  429.71  5637.5  433.43  5843.6  446.72
#Mann=7,-1,0
  4331.2    0.05       0  4848.9     0.1       0  5010.1    0.07       0
  5023.5     0.1       0  5158.4    0.12       0  5168.3     0.1       0
  5267.9    0.05       0
Bank Sta=5010.1,5023.5
Exp/Cntr=0.3,0.1

Type RM Length L Ch R = 1,102766,470,470,470
BEGIN DESCRIPTION:
Caney Creek 124.0
END DESCRIPTION:
XS GIS Cut Line= 3
      2789825.98      6794161.03      2789526.00      6794611.00
      2789312.08      6795433.24
#Sta/Elev= 30
  4447.7  475.96  4483.7  465.64  4519.8  463.40  4591.9  452.53  4614.4  446.57
  4627.9  445.89  4635.4  442.27  4707.6  429.44  4743.6  425.80  4861.8  419.51
  4908.9  418.53  4929.9  415.86  4975.0  416.86  4981.0  415.97  4985.5  413.07
  4991.1  413.07  5004.6  406.47  5006.5  405.97  5018.0  406.47  5040.2  407.08
  5051.9  415.56  5089.5  422.81  5112.5  425.53  5137.1  425.58  5195.1  424.17
  5244.1  428.16  5277.8  428.82  5325.2  426.34  5515.5  427.44  5838.1  443.18
#Mann=6,-1,0
  4447.7    0.05       0  4861.8     0.1       0  5004.6    0.07       0
  5018.0     0.1       0  5089.5    0.12       0  5137.1    0.05       0
Bank Sta=5004.6,5018
Exp/Cntr=0.3,0.1

Type RM Length L Ch R = 1,102296,249,249,249
BEGIN DESCRIPTION:
Caney Creek 123.0
END DESCRIPTION:
XS GIS Cut Line= 3
      2788939.78      6793574.16      2789226.00      6794561.00
      2789285.28      6795271.42
#Sta/Elev= 30
  3978.0  447.77  4028.3  445.32  4072.8  443.73  4278.1  436.33  4286.0  436.01
  4521.1  430.24  4547.4  423.22  4559.9  428.50  4593.5  428.09  4620.3  425.51
  4627.0  421.39  4665.8  424.45  4682.7  420.88  4714.0  423.14  4745.2  418.47
  4776.9  421.58  4870.2  416.23  4963.9  417.20  4974.3  409.64  4976.8  404.77
  4978.7  404.27  4990.2  404.77  5008.0  405.67  5015.5  413.05  5025.6  416.22
  5068.2  417.64  5146.0  425.42  5194.2  425.98  5477.1  428.56  5718.4  438.79
#Mann=8,-1,0
  3978.0    0.12       0  4028.3     0.1       0  4072.8    0.12       0
  4278.1    0.05       0  4286.0     0.1       0  4976.8    0.07       0
  4990.2     0.1       0  5194.2    0.05       0
Bank Sta=4976.8,4990.2
Exp/Cntr=0.3,0.1

Type RM Length L Ch R = 1,102047,681,681,681
BEGIN DESCRIPTION:
Caney Creek 122.0
END DESCRIPTION:
XS GIS Cut Line= 3
      2788829.52      6793919.44      2789005.79      6794461.50
      2789095.67      6795090.01
#Sta/Elev= 30
  4430.0  423.72  4435.8  424.65  4462.5  423.22  4467.8  424.67  4494.5  423.80
  4499.7  424.79  4819.1  418.72  4920.2  418.45  4952.2  416.99  4957.4  418.94
  4984.1  416.38  4989.4  417.75  4997.1  415.17  5002.3  415.17  5009.6  410.25
  5019.7  405.77  5034.1  404.04  5036.1  403.54  5047.6  404.04  5050.0  411.44
  5070.2  420.53  5106.5  419.96  5111.5  421.09  5182.2  421.58  5221.7  423.62
  5272.2  424.28  5318.5  427.03  5535.6  434.01  5601.2  438.07  5634.9  438.90
#Mann=3,-1,0
  4430.0    0.05       0  5034.1    0.05       0  5047.6    0.05       0
Bank Sta=5034.1,5047.6
Exp/Cntr=0.3,0.1

Type RM Length L Ch R = 1,101366,476,476,476
BEGIN DESCRIPTION:
Caney Creek 121.0
END DESCRIPTION:
XS GIS Cut Line= 3
      2788781.10      6793693.69      2788476.00      6794161.00
      2788141.65      6794605.38
#Sta/Elev= 30
  4441.5  427.97  4479.2  423.67  4572.7  419.27  4820.1  414.98  4847.2  413.17
  4946.3  414.14  4955.8  414.85  4963.8  407.65  4970.9  403.52  4985.0  401.60
  4987.0  401.10  4999.0  401.60  4999.6  403.40  5002.7  403.40  5006.9  412.75
  5013.1  413.82  5027.7  414.70  5036.0  408.61  5042.3  413.69  5049.6  406.38
  5063.1  405.50  5077.7  415.07  5152.1  414.77  5186.0  414.19  5213.0  416.76
  5263.0  416.68  5306.7  419.65  5350.0  426.33  5456.7  429.26  5555.7  429.42
#Mann=5,-1,0
  4441.5    0.05       0  4946.3     0.1       0  4985.0    0.07       0
  4999.0     0.1       0  5152.1    0.05       0
Bank Sta=4985,4999
Exp/Cntr=0.3,0.1

Type RM Length L Ch R = 1,100890,434,434,434
BEGIN DESCRIPTION:
Caney Creek 120.0
END DESCRIPTION:
XS GIS Cut Line= 3
      2788726.02      6793510.99      2788126.00      6793961.00
      2787476.35      6795315.99
#Sta/Elev= 30
  4246.3  432.56  4274.4  427.91  4309.9  424.95  4484.4  419.61  4486.2  419.42
  4682.8  416.63  4774.4  412.56  4859.9  413.13  4889.0  411.92  4953.6  414.53
  4961.0  409.87  4967.4  400.59  4969.4  400.09  4981.4  400.59  4987.7  405.43
  4993.2  411.07  5010.4  412.79  5027.5  411.88  5055.7  414.38  5168.3  413.29
  5550.8  414.56  5882.4  411.95  5972.2  412.58  6120.1  416.55  6249.5  426.91
  6368.4  440.48  6442.8  449.13  6482.4  455.43  6488.1  457.75  6499.0  457.43
#Mann=9,-1,0
  4246.3    0.05       0  4484.4    0.12       0  4486.2    0.05       0
  4961.0     0.1       0  4967.4    0.07       0  4981.4     0.1       0
  4987.7    0.12       0  5168.3    0.05       0  6368.4    0.12       0
Bank Sta=4967.4,4981.4
Exp/Cntr=0.3,0.1

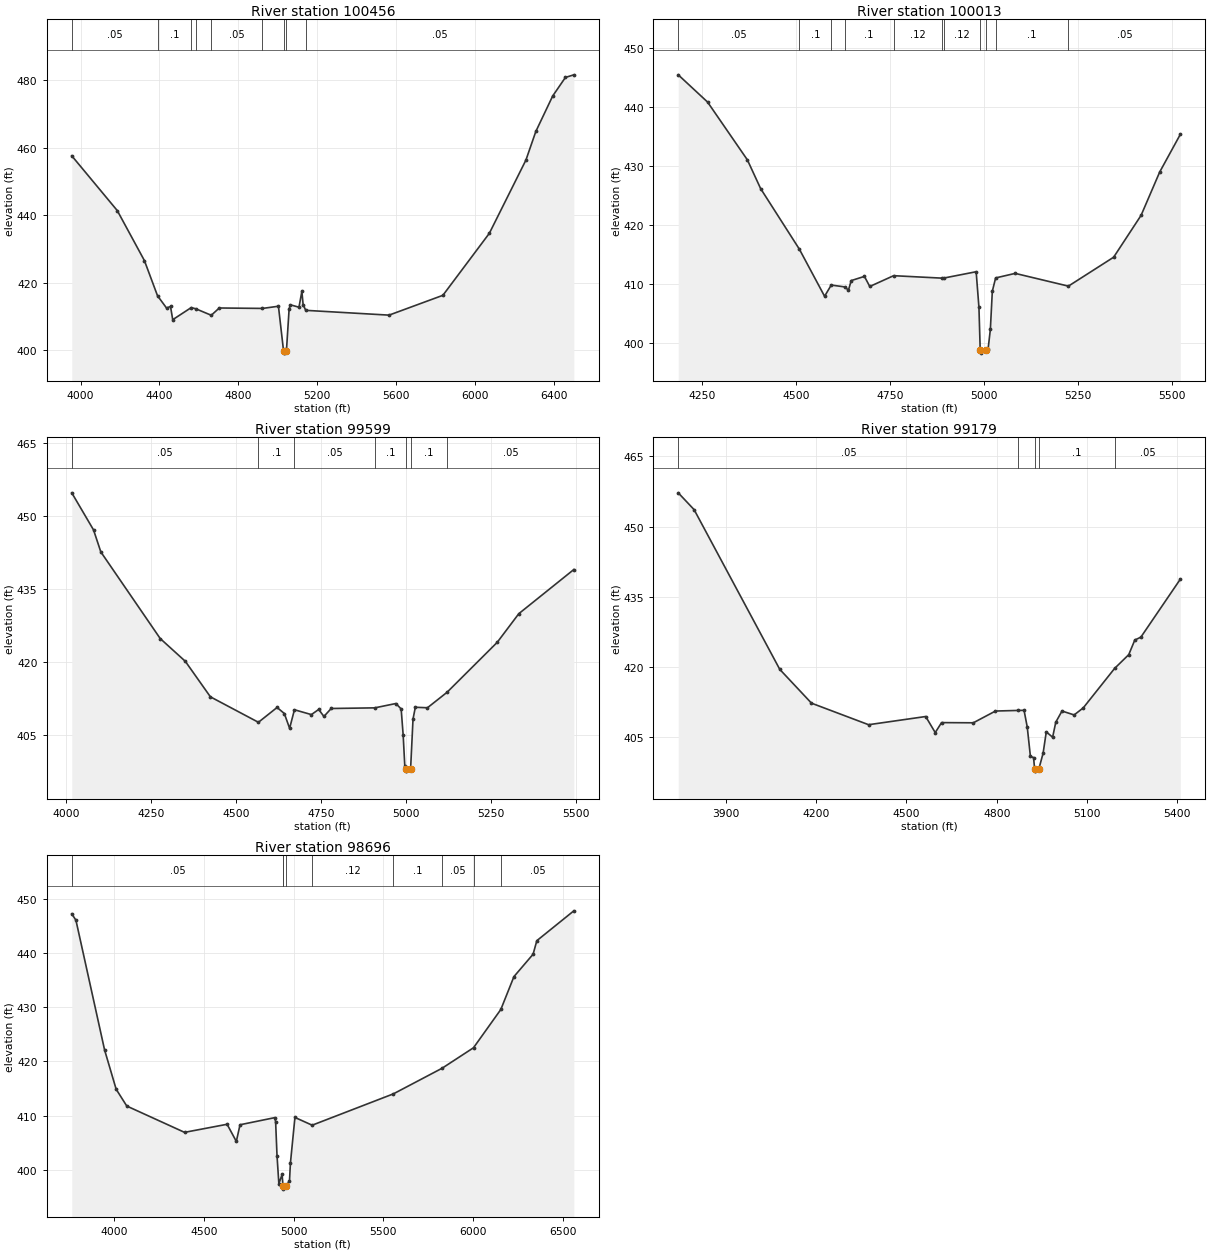
Type RM Length L Ch R = 1,100456,443,443,443
BEGIN DESCRIPTION:
Caney Creek 119.0
END DESCRIPTION:
XS GIS Cut Line= 3
      2788026.00      6792961.00      2787726.00      6793961.00
      2786826.02      6795160.97
#Sta/Elev= 30
  3955.7  457.64  4186.3  441.39  4323.7  426.57  4390.3  416.11  4436.0  412.48
  4456.0  412.95  4467.3  409.03  4561.1  412.62  4584.7  412.25  4662.6  410.34
  4703.1  412.50  4922.1  412.37  5002.9  413.02  5029.1  399.61  5031.1  399.11
  5043.2  399.61  5057.0  412.22  5063.3  413.44  5107.0  412.73  5121.6  417.43
  5127.9  413.53  5141.1  411.80  5563.3  410.38  5836.2  416.26  6071.6  434.66
  6257.0  456.39  6307.0  464.85  6392.4  475.37  6457.0  480.89  6499.7  481.66
#Mann=9,-1,0
  3955.7    0.05       0  4390.3     0.1       0  4561.1    0.12       0
  4584.7     0.1       0  4662.6    0.05       0  4922.1    0.12       0
  5029.1    0.07       0  5043.2    0.12       0  5141.1    0.05       0
Bank Sta=5029.1,5043.2
Exp/Cntr=0.3,0.1

Type RM Length L Ch R = 1,100013,414,414,414
BEGIN DESCRIPTION:
Caney Creek 118.0
END DESCRIPTION:
XS GIS Cut Line= 3
      2787925.99      6793111.01      2787376.00      6793711.00
      2786876.04      6793860.99
#Sta/Elev= 30
  4186.3  445.48  4264.3  440.87  4370.3  431.07  4405.5  426.21  4508.6  415.94
  4575.7  407.96  4593.4  409.86  4629.4  409.55  4639.2  409.00  4646.6  410.62
  4681.7  411.33  4695.9  409.62  4759.4  411.45  4889.4  411.03  4892.3  411.04
  4979.0  412.12  4986.4  406.08  4989.8  398.83  4991.8  398.33  5003.9  398.83
  5010.7  399.00  5016.8  402.35  5022.0  408.81  5030.8  411.07  5082.9  411.84
  5224.4  409.68  5344.8  414.58  5417.8  421.67  5467.4  429.02  5522.2  435.39
#Mann=11,-1,0
  4186.3    0.05       0  4508.6     0.1       0  4593.4    0.12       0
  4629.4     0.1       0  4759.4    0.12       0  4889.4    0.05       0
  4892.3    0.12       0  4989.8    0.07       0  5003.9    0.12       0
  5030.8     0.1       0  5224.4    0.05       0
Bank Sta=4989.8,5003.9
Exp/Cntr=0.3,0.1

Type RM Length L Ch R = 1,99599,420,420,420
BEGIN DESCRIPTION:
Caney Creek 117.0
END DESCRIPTION:
XS GIS Cut Line= 3
      2787918.48      6792954.48      2787076.00      6793461.00
      2786741.54      6793825.34
#Sta/Elev= 30
  4017.0  454.70  4081.1  447.09  4102.5  442.59  4277.3  424.83  4351.2  420.16
  4425.0  412.88  4566.3  407.66  4621.2  410.70  4642.6  409.46  4658.1  406.42
  4672.3  410.23  4722.2  409.24  4743.6  410.29  4759.1  408.86  4780.5  410.49
  4908.6  410.62  4970.9  411.51  4986.4  410.39  4992.3  405.03  4997.1  398.70
  5000.0  398.15  5002.0  397.65  5014.2  398.15  5021.3  408.33  5028.1  410.74
  5063.8  410.64  5121.4  413.81  5269.2  424.06  5332.7  429.93  5494.6  438.98
#Mann=7,-1,0
  4017.0    0.05       0  4566.3     0.1       0  4672.3    0.05       0
  4908.6     0.1       0  5000.0    0.07       0  5014.2     0.1       0
  5121.4    0.05       0
Bank Sta=5000,5014.2
Exp/Cntr=0.3,0.1

Type RM Length L Ch R = 1,99179,483,483,483
BEGIN DESCRIPTION:
Caney Creek 116.0
END DESCRIPTION:
XS GIS Cut Line= 3
      2787925.95      6792861.02      2786726.00      6793261.00
      2786676.00      6793661.02
#Sta/Elev= 30
  3741.7  457.20  3794.4  453.61  4079.0  419.51  4184.4  412.29  4374.1  407.69
  4563.8  409.44  4595.5  406.01  4616.5  408.14  4722.0  408.10  4795.7  410.61
  4871.9  410.74  4890.6  410.76  4901.2  407.19  4911.7  400.91  4922.2  400.68
  4925.6  398.28  4927.6  397.78  4939.9  398.28  4953.9  401.61  4964.4  406.16
  4985.5  405.02  4996.0  408.23  5016.6  410.61  5057.0  409.78  5087.2  411.28
  5191.6  419.72  5238.4  422.65  5258.5  425.77  5278.7  426.39  5409.7  438.76
#Mann=5,-1,0
  3741.7    0.05       0  4871.9     0.1       0  4925.6    0.07       0
  4939.9     0.1       0  5191.6    0.05       0
Bank Sta=4925.6,4939.9
Exp/Cntr=0.3,0.1

Type RM Length L Ch R = 1,98696,418,418,418
BEGIN DESCRIPTION:
Caney Creek 115.0
END DESCRIPTION:
XS GIS Cut Line= 3
      2787726.02      6792561.00      2786526.00      6792861.00
      2785526.00      6794061.00
#Sta/Elev= 30
  3763.1  447.18  3786.3  446.00  3946.1  422.09  4010.5  414.86  4069.8  411.76
  4391.9  406.91  4629.0  408.40  4680.5  405.24  4701.1  408.31  4894.4  409.62
  4899.5  408.90  4907.3  402.63  4917.6  397.44  4935.6  399.16  4940.8  396.99
  4941.4  396.95  4943.4  396.45  4955.7  396.95  4976.9  397.98  4982.0  401.22
  5007.2  409.66  5103.3  408.23  5556.5  414.01  5827.9  418.73  6002.7  422.50
  6155.0  429.55  6228.2  435.61  6335.0  439.74  6355.8  442.23  6562.1  447.73
#Mann=9,-1,0
  3763.1    0.05       0  4940.8     0.1       0  4941.4    0.07       0
  4955.7     0.1       0  5103.3    0.12       0  5556.5     0.1       0
  5827.9    0.05       0  6002.7    0.12       0  6155.0    0.05       0
Bank Sta=4941.4,4955.7
Exp/Cntr=0.3,0.1