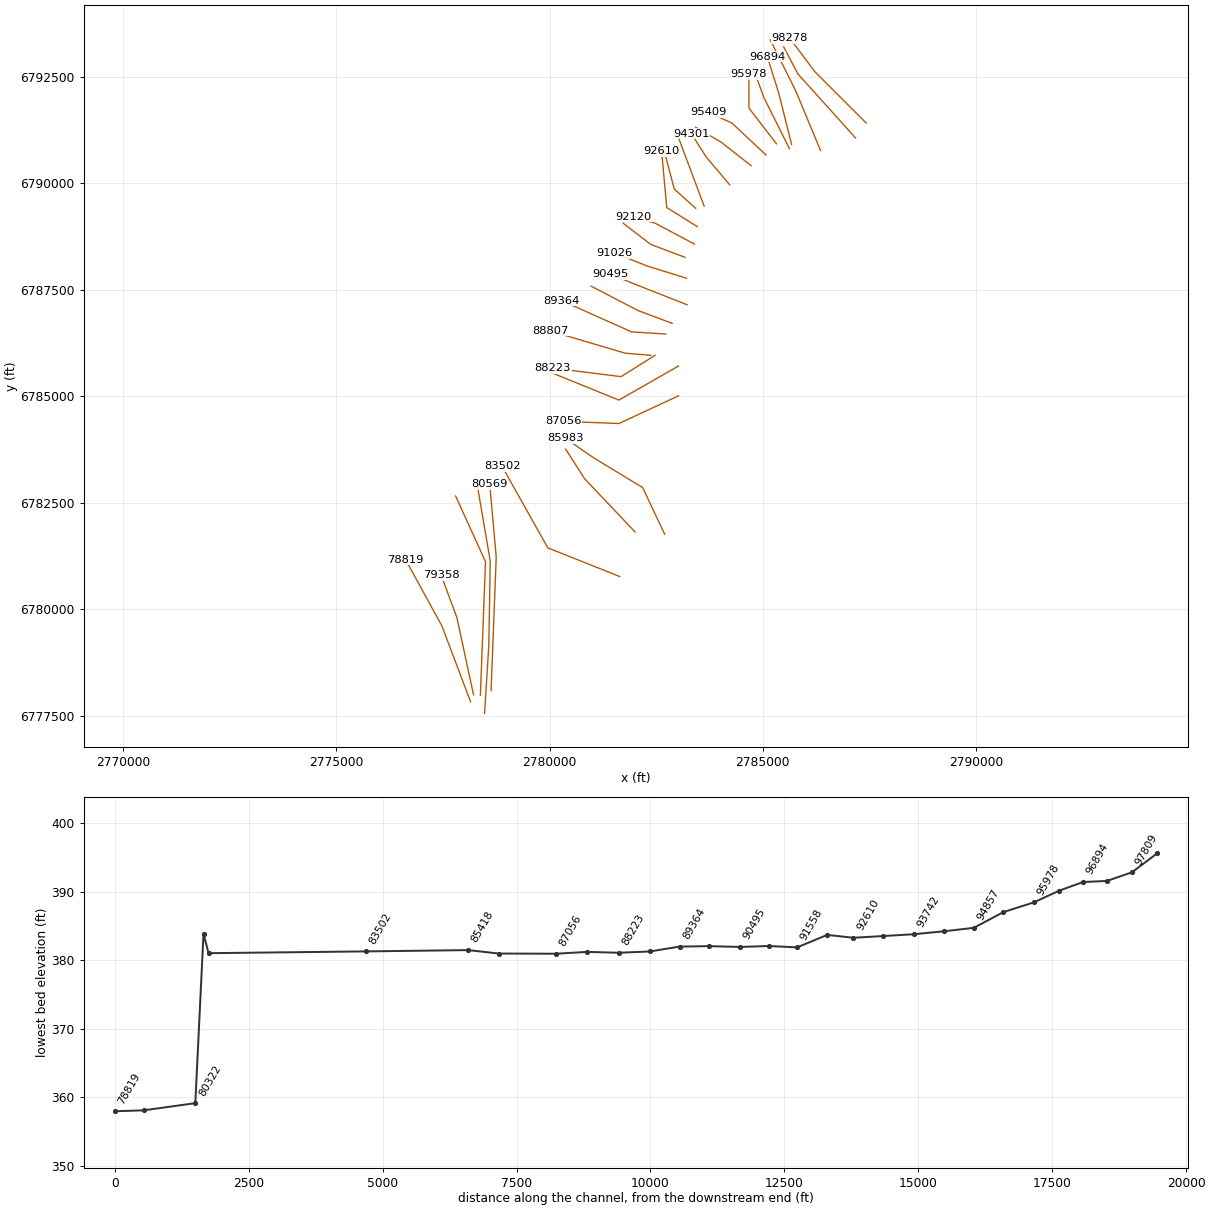
HEC-RAS study Caney Creek.prj: Caney Creek Base Level Engineering

--- Caney Creek.g01 (geometry) --- (continued)

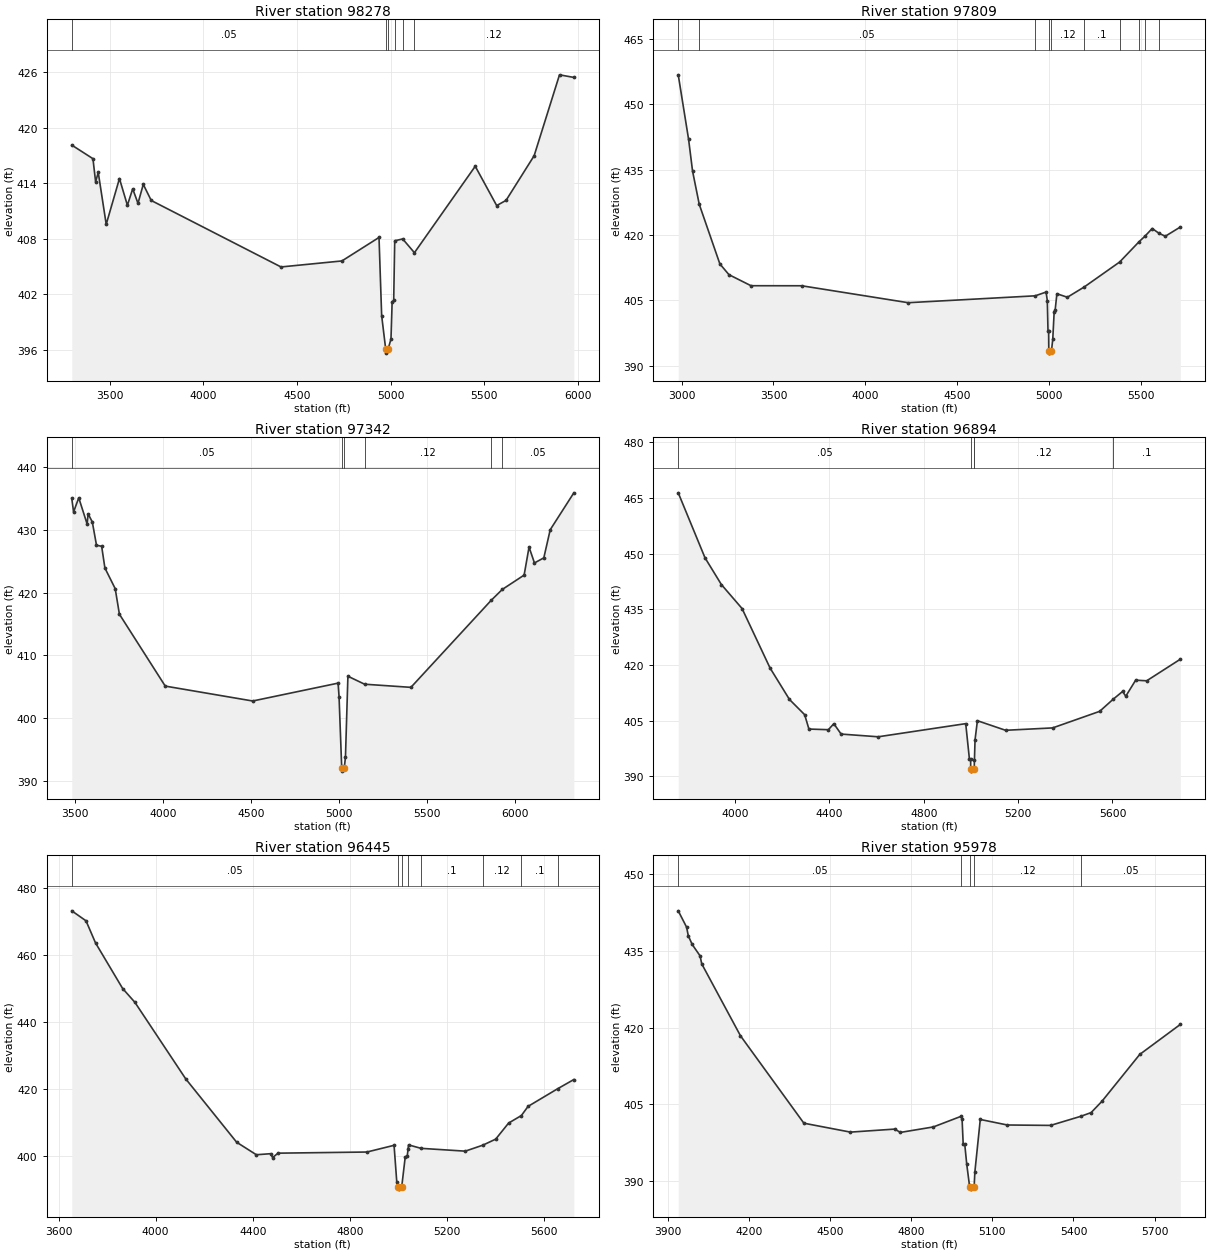
Type RM Length L Ch R = 1,98278,469,469,469
BEGIN DESCRIPTION:
Caney Creek 114.0
END DESCRIPTION:
XS GIS Cut Line= 3
      2787426.00      6791411.00      2786226.00      6792611.00
      2785635.22      6793397.59
#Sta/Elev= 30
  3297.5  418.12  3410.6  416.65  3424.8  414.15  3438.9  415.16  3481.4  409.55
  3552.1  414.50  3594.5  411.61  3622.8  413.39  3651.1  411.82  3679.3  413.87
  3721.8  412.13  4414.7  404.94  4740.0  405.59  4938.0  408.13  4952.1  399.68
  4973.3  396.12  4975.3  395.62  4987.6  396.12  5001.9  397.15  5008.1  401.15
  5016.4  401.33  5021.9  407.77  5064.4  407.97  5127.1  406.48  5451.8  415.83
  5566.3  411.58  5616.3  412.14  5766.3  416.97  5901.7  425.72  5978.3  425.44
#Mann=6,-1,0
  3297.5    0.05       0  4973.3    0.04       0  4987.6    0.05       0
  5021.9    0.12       0  5064.4     0.1       0  5127.1    0.12       0
Bank Sta=4973.3,4987.6
Exp/Cntr=0.3,0.1

Type RM Length L Ch R = 1,97809,467,467,467
BEGIN DESCRIPTION:
Caney Creek 113.0
END DESCRIPTION:
XS GIS Cut Line= 3
      2787175.99      6791061.01      2785826.00      6792561.00
      2785492.15      6793196.17
#Sta/Elev= 30
  2981.2  456.77  3037.6  441.96  3059.3  434.65  3095.7  427.03  3208.0  413.35
  3257.4  410.88  3377.7  408.34  3653.9  408.33  4234.2  404.44  4926.1  406.02
  4985.4  406.88  4992.1  404.94  4995.9  397.95  4999.2  397.95  5000.2  393.36
  5002.2  392.86  5014.7  393.36  5021.8  396.02  5029.5  402.34  5035.1  402.84
  5044.4  406.50  5101.3  405.69  5192.9  408.04  5386.2  413.78  5492.7  418.47
  5524.1  419.71  5563.6  421.48  5602.0  420.34  5635.4  419.71  5716.8  421.82
#Mann=10,-1,0
  2981.2    0.12       0  3095.7    0.05       0  4926.1    0.12       0
  5000.2    0.07       0  5014.7    0.12       0  5192.9     0.1       0
  5386.2    0.12       0  5492.7    0.05       0  5524.1     0.1       0
  5602.0    0.05       0
Bank Sta=5000.2,5014.7
Exp/Cntr=0.3,0.1

Type RM Length L Ch R = 1,97342,448,448,448
BEGIN DESCRIPTION:
Caney Creek 112.0
END DESCRIPTION:
XS GIS Cut Line= 3
      2786355.20      6790767.11      2785776.00      6792161.00
      2785175.99      6793361.02
#Sta/Elev= 30
  3482.1  434.96  3492.4  432.81  3521.7  435.06  3569.4  430.88  3574.8  432.51
  3598.7  431.22  3622.5  427.52  3651.8  427.35  3670.2  423.90  3728.8  420.61
  3752.6  416.55  4012.9  405.12  4509.5  402.75  4994.3  405.59  4999.9  403.45
  5015.0  392.10  5017.0  391.60  5029.6  392.10  5036.3  393.84  5050.2  406.69
  5145.0  405.42  5408.0  404.92  5863.9  418.76  5926.9  420.49  6050.9  422.77
  6078.8  427.22  6109.6  424.70  6162.7  425.51  6199.0  429.98  6333.2  435.85
#Mann=6,-1,0
  3482.1    0.05       0  5015.0    0.04       0  5029.6    0.05       0
  5145.0    0.12       0  5863.9     0.1       0  5926.9    0.05       0
Bank Sta=5015,5029.6
Exp/Cntr=0.3,0.1

Type RM Length L Ch R = 1,96894,449,449,449
BEGIN DESCRIPTION:
Caney Creek 111.0
END DESCRIPTION:
XS GIS Cut Line= 3
      2785676.00      6790910.98      2785376.00      6792111.00
      2785108.05      6792961.54
#Sta/Elev= 30
  3758.9  466.40  3872.3  448.91  3941.9  441.69  4029.5  435.24  4148.0  419.24
  4230.5  410.74  4294.9  406.64  4313.0  402.77  4395.4  402.60  4418.6  404.21
  4449.5  401.42  4606.7  400.69  4977.8  404.23  4993.3  394.78  4998.5  394.78
  4999.0  391.94  5001.0  391.44  5013.6  391.94  5014.8  394.51  5017.3  399.86
  5027.3  405.02  5146.7  402.44  5346.2  403.08  5545.6  407.54  5601.9  410.75
  5642.7  412.89  5656.4  411.62  5698.3  415.94  5745.1  415.77  5887.6  421.58
#Mann=5,-1,0
  3758.9    0.05       0  4999.0    0.04       0  5013.6    0.05       0
  5014.8    0.12       0  5601.9     0.1       0
Bank Sta=4999,5013.6
Exp/Cntr=0.3,0.1

Type RM Length L Ch R = 1,96445,467,467,467
BEGIN DESCRIPTION:
Caney Creek 110.0
END DESCRIPTION:
XS GIS Cut Line= 3
      2785626.00      6790810.99      2785026.00      6792011.00
      2784776.38      6792693.43
#Sta/Elev= 30
  3654.6  473.12  3713.3  470.14  3752.4  463.56  3864.2  449.96  3914.6  445.85
  4124.2  423.01  4333.8  404.14  4414.9  400.41  4473.6  400.72  4482.0  399.57
  4504.3  400.88  4870.5  401.22  4982.3  403.22  4993.5  392.25  4998.9  390.66
  5000.9  390.16  5013.5  390.66  5028.2  399.69  5036.7  400.11  5039.8  402.01
  5042.0  403.35  5093.2  402.32  5275.6  401.48  5347.8  403.26  5400.9  405.06
  5454.1  409.85  5506.8  412.10  5534.4  414.83  5655.8  420.07  5722.9  422.83
#Mann=8,-1,0
  3654.6    0.05       0  4998.9    0.04       0  5013.5    0.05       0
  5039.8    0.12       0  5093.2     0.1       0  5347.8    0.12       0
  5506.8     0.1       0  5655.8    0.05       0
Bank Sta=4998.9,5013.5
Exp/Cntr=0.3,0.1

Type RM Length L Ch R = 1,95978,569,569,569
BEGIN DESCRIPTION:
Caney Creek 109.0
END DESCRIPTION:
XS GIS Cut Line= 3
      2785321.20      6790923.32      2784676.00      6791761.00
      2784676.00      6792561.05
#Sta/Elev= 30
  3937.9  442.80  3968.8  439.61  3975.1  437.93  3989.6  436.23  4018.6  434.01
  4024.9  432.44  4168.1  418.41  4402.7  401.34  4574.9  399.60  4738.9  400.19
  4759.7  399.54  4881.7  400.61  4983.6  402.67  4988.0  402.08  4992.1  397.24
  4997.8  397.24  5005.3  393.28  5015.3  389.20  5017.9  388.97  5019.9  388.47
  5032.6  388.97  5035.3  391.84  5055.3  402.07  5155.3  400.99  5315.3  400.91
  5426.8  402.68  5465.3  403.41  5505.3  405.61  5645.3  414.77  5795.3  420.62
#Mann=5,-1,0
  3937.9    0.05       0  4983.6    0.12       0  5017.9    0.07       0
  5032.6    0.12       0  5426.8    0.05       0
Bank Sta=5017.9,5032.6
Exp/Cntr=0.3,0.1

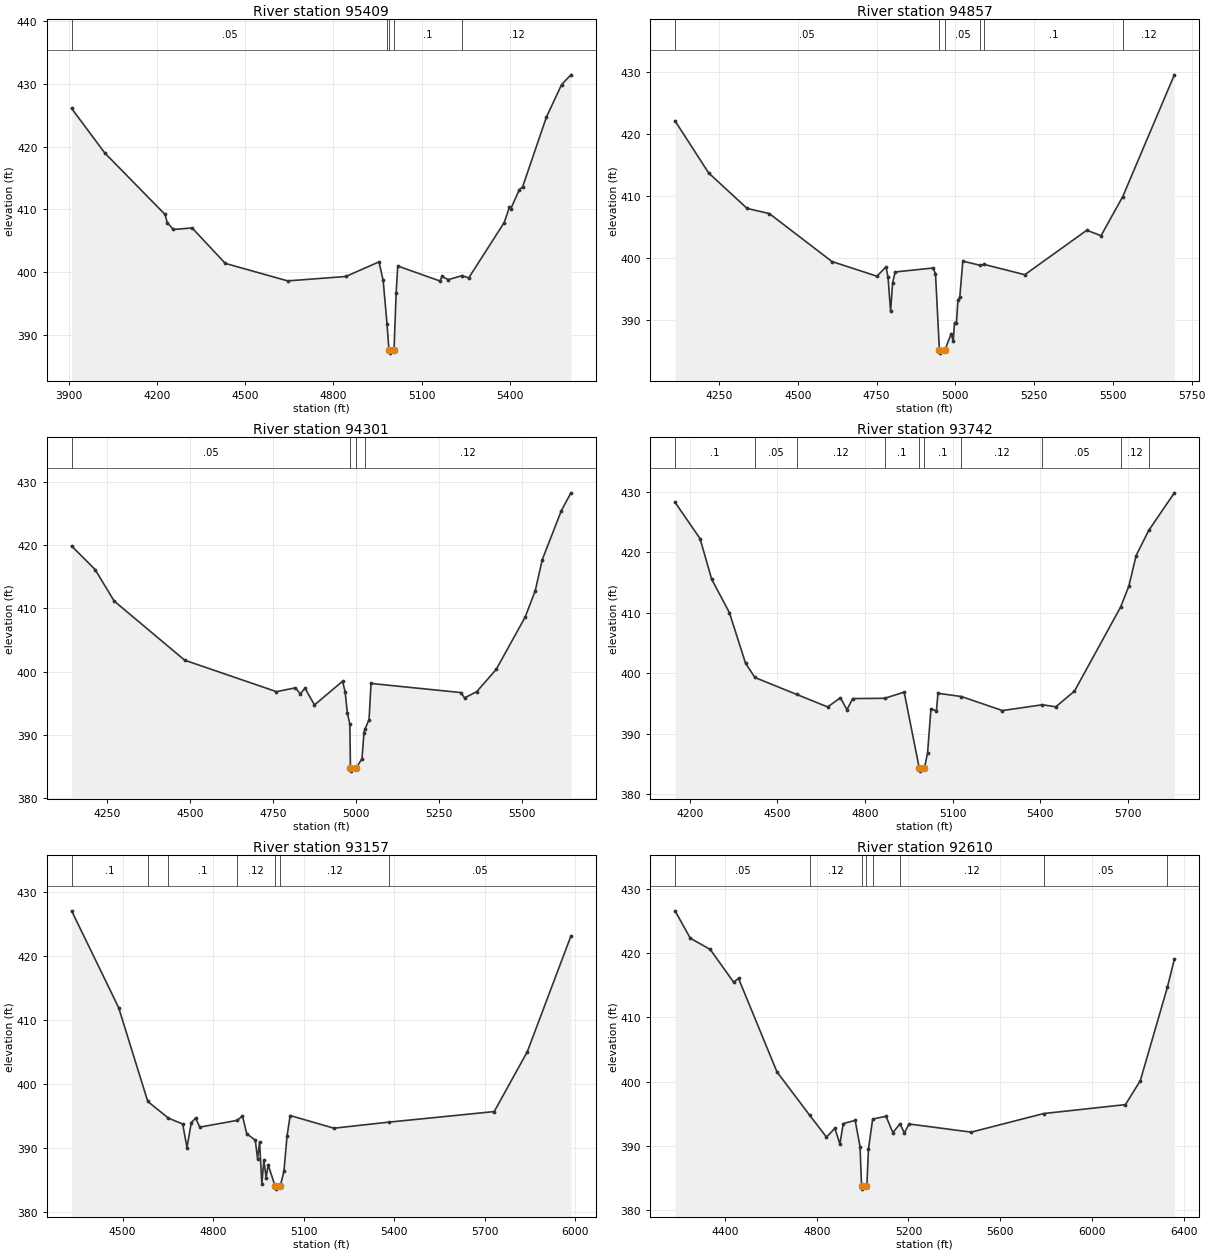
Type RM Length L Ch R = 1,95409,552,552,552
BEGIN DESCRIPTION:
Caney Creek 108.0
END DESCRIPTION:
XS GIS Cut Line= 3
      2785076.01      6790660.99      2784276.00      6791411.00
      2783725.96      6791661.02
#Sta/Elev= 30
  3908.1  426.07  4021.2  418.96  4226.4  409.16  4233.7  407.86  4254.7  406.77
  4318.6  407.01  4431.5  401.36  4644.0  398.57  4841.8  399.27  4955.1  401.60
  4969.3  398.64  4982.4  391.70  4989.0  387.55  4991.0  387.05  5006.3  387.55
  5013.5  396.64  5019.0  400.94  5162.9  398.55  5169.5  399.27  5191.4  398.77
  5238.3  399.41  5260.6  399.04  5381.5  407.87  5399.0  410.29  5404.5  410.11
  5433.1  413.13  5444.1  413.54  5525.4  424.69  5577.0  429.87  5608.9  431.43
#Mann=5,-1,0
  3908.1    0.05       0  4982.4     0.1       0  4989.0    0.07       0
  5006.3     0.1       0  5238.3    0.12       0
Bank Sta=4989,5006.3
Exp/Cntr=0.3,0.1

Type RM Length L Ch R = 1,94857,556,556,556
BEGIN DESCRIPTION:
Caney Creek 107.0
END DESCRIPTION:
XS GIS Cut Line= 3
      2784726.03      6790410.98      2784026.00      6790961.00
      2783425.99      6791311.01
#Sta/Elev= 30
  4110.2  422.09  4216.9  413.72  4338.9  408.02  4409.4  407.19  4608.2  399.48
  4751.0  397.12  4779.9  398.63  4786.3  396.93  4794.4  391.46  4800.7  396.03
  4808.8  397.80  4929.1  398.44  4936.9  397.52  4949.3  385.25  4951.3  384.75
  4966.6  385.25  4986.9  387.89  4993.2  386.63  4997.3  389.65  5003.4  389.65
  5008.3  393.29  5014.1  393.79  5023.6  399.55  5078.4  398.87  5091.7  399.01
  5220.4  397.36  5417.2  404.51  5462.3  403.63  5531.4  409.93  5695.1  429.50
#Mann=6,-1,0
  4110.2    0.05       0  4949.3    0.04       0  4966.6    0.05       0
  5078.4    0.12       0  5091.7     0.1       0  5531.4    0.12       0
Bank Sta=4949.3,4966.6
Exp/Cntr=0.3,0.1

Type RM Length L Ch R = 1,94301,559,559,559
BEGIN DESCRIPTION:
Caney Creek 106.0
END DESCRIPTION:
XS GIS Cut Line= 3
      2784225.97      6789961.03      2783676.00      6790611.00
      2783326.03      6791160.96
#Sta/Elev= 30
  4143.0  419.89  4213.8  416.16  4271.0  411.18  4483.5  401.81  4759.8  396.83
  4817.0  397.44  4831.3  396.48  4845.6  397.37  4874.2  394.73  4958.7  398.48
  4966.4  396.83  4973.0  393.51  4980.7  391.67  4982.4  384.75  4984.4  384.25
  5000.0  384.75  5017.3  386.24  5023.2  390.34  5026.1  390.89  5038.5  392.41
  5044.4  398.13  5314.5  396.69  5326.3  395.84  5362.7  396.84  5421.1  400.34
  5508.3  408.62  5538.8  412.80  5560.0  417.74  5617.6  425.51  5646.3  428.31
#Mann=4,-1,0
  4143.0    0.05       0  4982.4    0.04       0  5000.0    0.05       0
  5026.1    0.12       0
Bank Sta=4982.4,5000
Exp/Cntr=0.3,0.1

Type RM Length L Ch R = 1,93742,585,585,585
BEGIN DESCRIPTION:
Caney Creek 105.0
END DESCRIPTION:
XS GIS Cut Line= 3
      2783626.00      6789461.00      2783326.00      6790261.00
      2783026.00      6791061.00
#Sta/Elev= 30
  4149.9  428.29  4235.3  422.30  4275.4  415.55  4335.9  410.04  4391.1  401.68
  4423.2  399.31  4566.6  396.50  4672.3  394.44  4715.9  395.96  4738.2  393.98
  4757.8  395.82  4867.5  395.87  4934.0  396.89  4985.7  384.32  4987.7  383.82
  5003.3  384.32  5014.1  386.82  5025.7  394.14  5044.4  393.78  5049.7  396.70
  5129.7  396.16  5270.4  393.84  5407.2  394.80  5452.9  394.46  5516.9  397.06
  5674.5  410.94  5703.0  414.43  5727.9  419.49  5771.0  423.64  5858.7  429.86
#Mann=10,-1,0
  4149.9     0.1       0  4423.2    0.05       0  4566.6    0.12       0
  4867.5     0.1       0  4985.7    0.07       0  5003.3     0.1       0
  5129.7    0.12       0  5407.2    0.05       0  5674.5    0.12       0
  5771.0     0.1       0
Bank Sta=4985.7,5003.3
Exp/Cntr=0.3,0.1

Type RM Length L Ch R = 1,93157,547,547,547
BEGIN DESCRIPTION:
Caney Creek 104.0
END DESCRIPTION:
XS GIS Cut Line= 3
      2783426.01      6789411.00      2782926.00      6789861.00
      2782676.01      6790810.97
#Sta/Elev= 30
  4331.1  427.08  4486.9  411.94  4583.5  397.26  4652.1  394.65  4699.2  393.74
  4713.4  390.04  4727.6  393.92  4741.8  394.66  4756.0  393.25  4880.6  394.31
  4897.3  395.02  4911.5  392.22  4939.9  391.19  4947.4  388.29  4954.1  390.95
  4961.6  384.37  4968.3  388.04  4975.8  385.36  4982.5  387.36  5005.3  384.05
  5007.3  383.55  5022.9  384.05  5034.8  386.36  5045.1  391.86  5055.5  395.06
  5200.3  393.08  5382.8  394.03  5731.8  395.68  5841.4  405.04  5986.1  423.15
#Mann=7,-1,0
  4331.1     0.1       0  4583.5    0.12       0  4652.1     0.1       0
  4880.6    0.12       0  5005.3    0.07       0  5022.9    0.12       0
  5382.8    0.05       0
Bank Sta=5005.3,5022.9
Exp/Cntr=0.3,0.1

Type RM Length L Ch R = 1,92610,490,490,490
BEGIN DESCRIPTION:
Mapping XS 853610c2
END DESCRIPTION:
XS GIS Cut Line= 3
      2783466.46      6788980.22      2782748.97      6789426.33
      2782627.40      6790753.40
#Sta/Elev= 30
  4182.0  426.57  4248.5  422.31  4335.6  420.56  4437.4  415.48  4458.7  416.07
  4626.3  401.54  4769.9  394.75  4842.4  391.39  4879.0  392.76  4900.8  390.31
  4915.6  393.49  4967.5  393.99  4988.8  389.89  4995.3  383.80  4997.3  383.30
  5013.0  383.80  5018.6  383.82  5025.4  389.51  5043.7  394.18  5101.9  394.63
  5132.0  392.09  5163.0  393.45  5182.2  392.03  5202.3  393.43  5473.4  392.16
  5789.3  395.05  6146.2  396.44  6210.9  400.16  6329.5  414.74  6359.5  419.05
#Mann=8,-1,0
  4182.0    0.05       0  4769.9    0.12       0  4995.3    0.07       0
  5013.0    0.12       0  5043.7     0.1       0  5163.0    0.12       0
  5789.3    0.05       0  6329.5    0.12       0
Bank Sta=4995.3,5013
Exp/Cntr=0.3,0.1

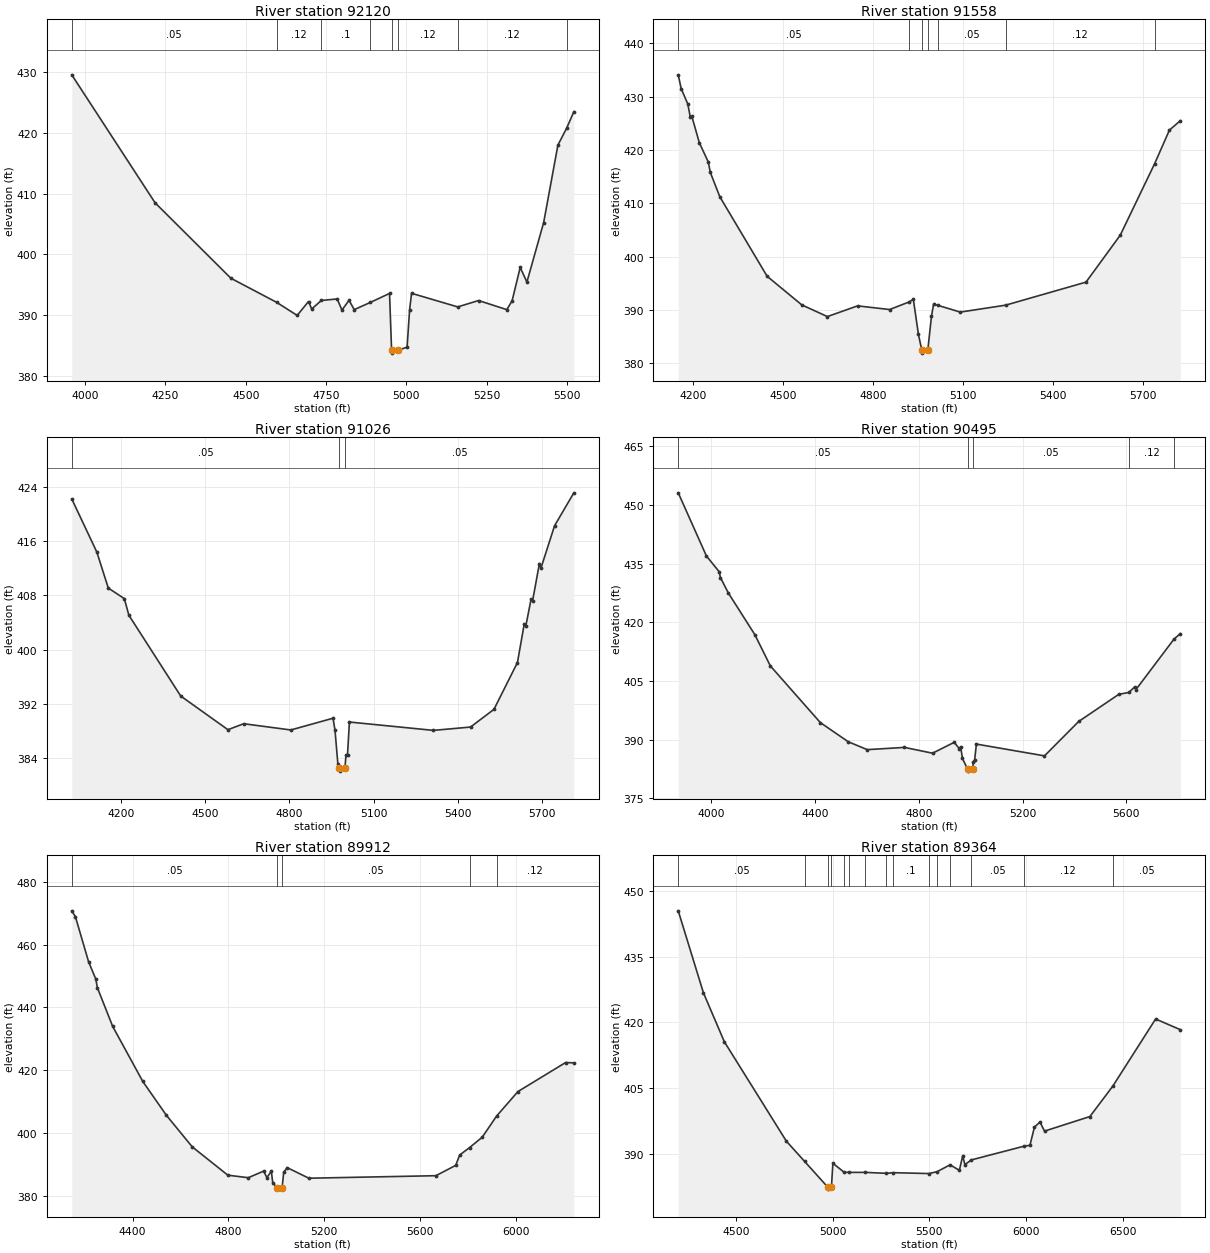
Type RM Length L Ch R = 1,92120,562,562,562
BEGIN DESCRIPTION:
Caney Creek 103.0
END DESCRIPTION:
XS GIS Cut Line= 3
      2783395.99      6788572.00      2782476.00      6789061.00
      2781975.99      6789211.00
#Sta/Elev= 30
  3958.1  429.54  4217.6  408.47  4453.7  396.05  4596.3  392.08  4660.2  389.93
  4695.5  392.22  4705.5  390.99  4735.4  392.39  4784.8  392.64  4799.7  390.81
  4821.7  392.42  4838.0  390.88  4888.6  392.08  4947.9  393.55  4954.3  384.22
  4956.3  383.72  4974.0  384.22  5002.6  384.69  5010.4  390.85  5016.5  393.57
  5160.2  391.33  5225.3  392.38  5313.2  390.88  5329.7  392.34  5354.9  397.83
  5375.8  395.42  5428.0  405.22  5472.4  417.98  5499.5  420.75  5522.0  423.47
#Mann=8,-1,0
  3958.1    0.05       0  4596.3    0.12       0  4735.4     0.1       0
  4888.6    0.12       0  4954.3    0.05       0  4974.0    0.12       0
  5160.2    0.12       0  5499.5    0.05       0
Bank Sta=4954.3,4974
Exp/Cntr=0.3,0.1

Type RM Length L Ch R = 1,91558,532,532,532
BEGIN DESCRIPTION:
Caney Creek 102.0
END DESCRIPTION:
XS GIS Cut Line= 3
      2783176.00      6788261.00      2782376.00      6788561.00
      2781725.97      6789061.02
#Sta/Elev= 30
  4149.7  434.07  4159.5  431.49  4181.7  428.59  4189.8  426.18  4195.1  426.28
  4220.0  421.35  4250.3  417.68  4256.5  415.80  4288.5  411.20  4446.1  396.31
  4561.8  390.94  4647.2  388.75  4747.8  390.76  4854.6  390.07  4920.3  391.51
  4933.8  391.99  4950.7  385.44  4962.2  382.40  4964.2  381.90  4981.9  382.40
  4994.3  388.81  5001.4  391.07  5016.2  390.85  5090.2  389.59  5241.5  390.89
  5509.7  395.21  5623.9  404.01  5738.7  417.43  5787.9  423.71  5824.2  425.47
#Mann=7,-1,0
  4149.7    0.05       0  4920.3    0.12       0  4962.2    0.07       0
  4981.9    0.12       0  5016.2    0.05       0  5241.5    0.12       0
  5738.7    0.05       0
Bank Sta=4962.2,4981.9
Exp/Cntr=0.3,0.1

Type RM Length L Ch R = 1,91026,531,531,531
BEGIN DESCRIPTION:
Caney Creek 101.0
END DESCRIPTION:
XS GIS Cut Line= 3
      2783210.06      6787770.69      2782276.00      6788061.00
      2781526.01      6788361.00
#Sta/Elev= 30
  4026.0  422.18  4115.3  414.34  4155.9  409.06  4212.9  407.50  4229.2  405.05
  4413.5  393.16  4581.5  388.20  4637.6  389.08  4805.2  388.16  4955.3  389.89
  4962.3  388.14  4972.7  383.08  4978.0  382.60  4980.0  382.10  4997.7  382.60
  5001.5  384.50  5006.8  384.50  5013.6  389.33  5312.4  388.10  5444.4  388.59
  5527.8  391.20  5611.3  398.09  5635.5  403.77  5640.9  403.43  5659.8  407.42
  5665.2  407.18  5689.4  412.67  5694.8  411.98  5743.3  418.23  5811.9  423.08
#Mann=3,-1,0
  4026.0    0.05       0  4978.0    0.04       0  4997.7    0.05       0
Bank Sta=4978,4997.7
Exp/Cntr=0.3,0.1

Type RM Length L Ch R = 1,90495,583,583,583
BEGIN DESCRIPTION:
Caney Creek 100.0
END DESCRIPTION:
XS GIS Cut Line= 3
      2783225.73      6787147.60      2782176.00      6787561.00
      2781425.97      6787861.01
#Sta/Elev= 30
  3871.8  453.06  3980.5  436.92  4029.3  432.94  4034.6  431.41  4065.0  427.47
  4167.3  416.81  4226.9  408.85  4419.6  394.37  4527.4  389.46  4600.6  387.45
  4744.1  388.02  4852.4  386.54  4936.3  389.33  4955.3  387.69  4960.7  388.21
  4967.8  385.21  4987.5  382.46  4989.5  381.96  5007.2  382.46  5009.4  384.24
  5014.8  384.82  5021.5  388.87  5284.1  385.86  5416.0  394.65  5570.8  401.59
  5609.3  402.05  5631.4  403.45  5636.8  402.80  5783.3  415.68  5807.8  417.09
#Mann=5,-1,0
  3871.8    0.05       0  4987.5    0.04       0  5007.2    0.05       0
  5609.3    0.12       0  5783.3    0.05       0
Bank Sta=4987.5,5007.2
Exp/Cntr=0.3,0.1

Type RM Length L Ch R = 1,89912,548,548,548
BEGIN DESCRIPTION:
Caney Creek 99.0
END DESCRIPTION:
XS GIS Cut Line= 3
      2782876.03      6786710.99      2782076.00      6787011.00
      2780974.69      6787584.25
#Sta/Elev= 30
  4146.0  470.80  4161.2  468.93  4216.3  454.54  4246.6  448.98  4252.8  446.31
  4316.9  433.94  4442.4  416.42  4541.2  405.60  4648.9  395.56  4797.5  386.53
  4882.9  385.72  4947.0  387.83  4960.4  385.77  4979.1  387.79  4985.3  383.95
  5004.4  382.58  5006.4  382.08  5024.2  382.58  5030.8  387.49  5045.5  388.93
  5135.6  385.56  5666.1  386.36  5748.9  389.66  5765.3  392.94  5806.6  395.32
  5859.4  398.62  5919.6  405.38  6008.5  413.18  6207.4  422.43  6242.0  422.34
#Mann=5,-1,0
  4146.0    0.05       0  5004.4    0.04       0  5024.2    0.05       0
  5806.6     0.1       0  5919.6    0.12       0
Bank Sta=5004.4,5024.2
Exp/Cntr=0.3,0.1

Type RM Length L Ch R = 1,89364,557,557,557
BEGIN DESCRIPTION:
Caney Creek 98.0
END DESCRIPTION:
XS GIS Cut Line= 3
      2782725.99      6786461.00      2781926.00      6786511.00
      2780289.45      6787241.66
#Sta/Elev= 30
  4202.9  445.43  4333.1  426.74  4440.9  415.61  4761.5  392.94  4855.7  388.33
  4974.5  382.51  4976.5  382.01  4994.4  382.51  5001.9  387.90  5059.4  385.88
  5083.4  385.82  5169.0  385.83  5278.5  385.61  5311.5  385.76  5497.6  385.56
  5539.7  385.98  5607.1  387.54  5655.3  386.30  5672.5  389.60  5684.0  387.58
  5716.6  388.66  5988.0  391.78  6019.9  392.00  6043.1  396.15  6071.8  397.30
  6095.1  395.23  6329.6  398.55  6448.1  405.49  6669.1  420.78  6796.7  418.35
#Mann=15,-1,0
  4202.9    0.05       0  4855.7    0.12       0  4974.5    0.07       0
  4994.4    0.12       0  5059.4     0.1       0  5083.4    0.12       0
  5169.0     0.1       0  5278.5    0.12       0  5311.5     0.1       0
  5497.6    0.12       0  5539.7    0.05       0  5607.1    0.12       0
  5716.6    0.05       0  5988.0    0.12       0  6448.1    0.05       0
Bank Sta=4974.5,4994.4
Exp/Cntr=0.3,0.1

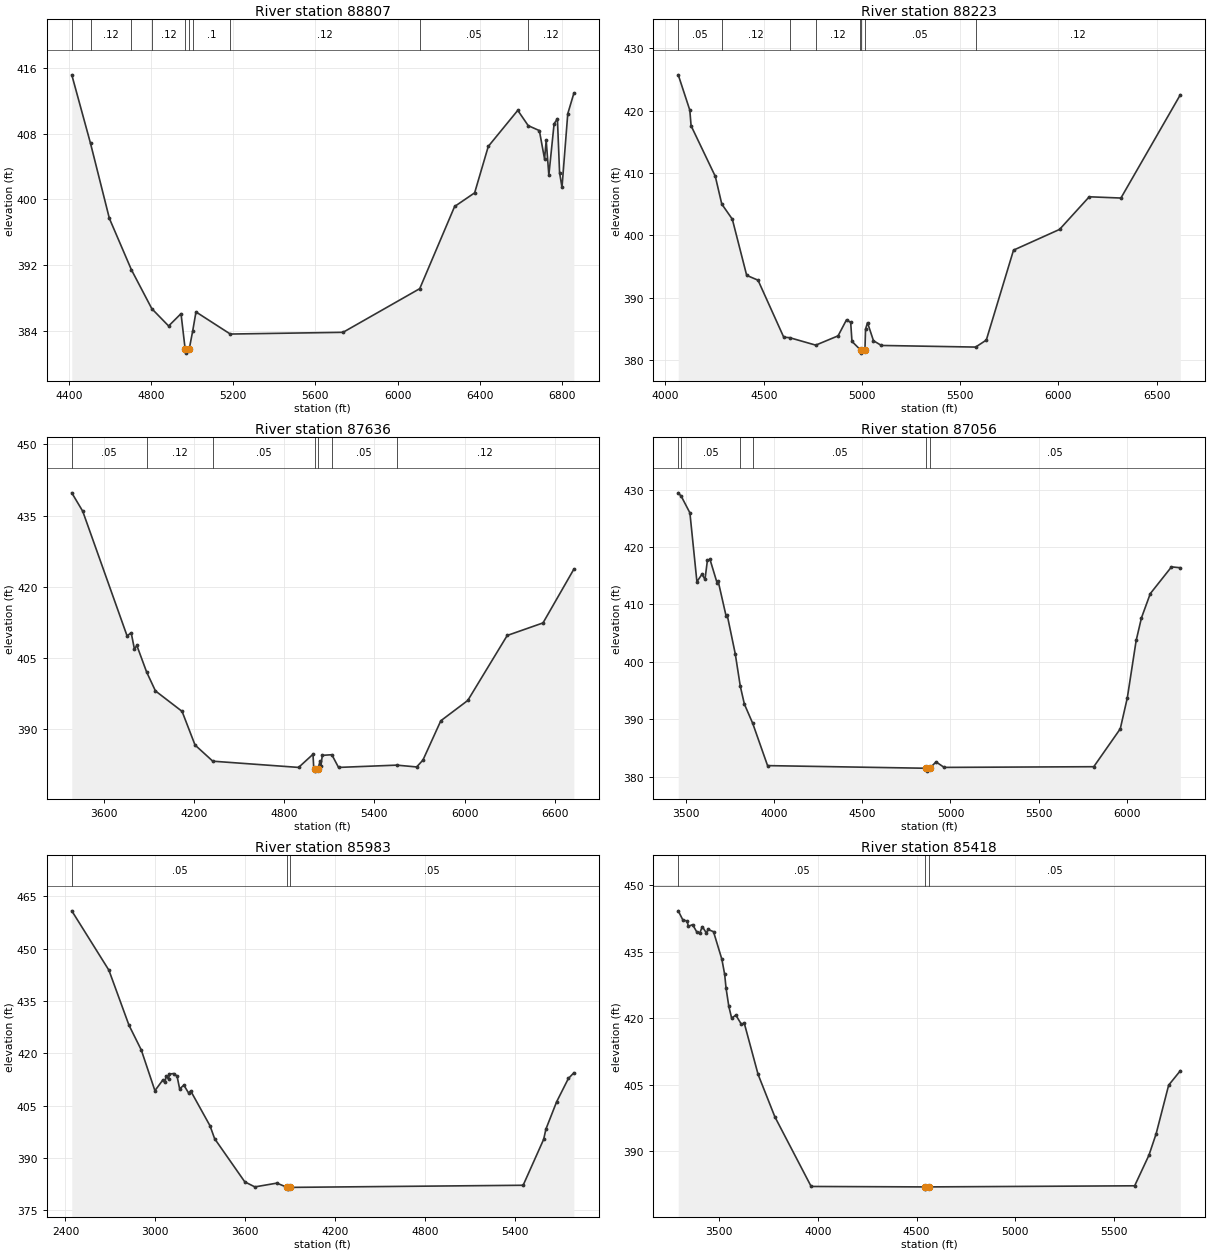
Type RM Length L Ch R = 1,88807,584,584,584
BEGIN DESCRIPTION:
Caney Creek 97.0
END DESCRIPTION:
XS GIS Cut Line= 3
      2782376.02      6785961.00      2781776.00      6786011.00
      2780009.32      6786533.43
#Sta/Elev= 30
  4413.9  415.14  4505.2  406.80  4597.0  397.68  4704.2  391.44  4803.7  386.70
  4885.5  384.60  4945.8  386.10  4965.9  381.80  4967.9  381.30  4985.8  381.80
  5002.7  384.00  5018.6  386.31  5185.7  383.62  5734.6  383.83  6108.0  389.14
  6277.8  399.13  6375.3  400.79  6441.8  406.44  6585.3  410.82  6636.2  408.96
  6690.4  408.36  6715.8  404.90  6723.6  407.18  6736.6  402.94  6762.1  409.18
  6778.3  409.81  6788.8  403.26  6800.6  401.45  6828.7  410.41  6858.3  412.89
#Mann=10,-1,0
  4413.9    0.05       0  4505.2    0.12       0  4704.2    0.05       0
  4803.7    0.12       0  4965.9    0.07       0  4985.8    0.12       0
  5002.7     0.1       0  5185.7    0.12       0  6108.0    0.05       0
  6636.2    0.12       0
Bank Sta=4965.9,4985.8
Exp/Cntr=0.3,0.1

Type RM Length L Ch R = 1,88223,587,587,587
BEGIN DESCRIPTION:
Caney Creek 96.0
END DESCRIPTION:
XS GIS Cut Line= 3
      2782475.98      6785960.99      2781676.00      6785461.00
      2780076.02      6785661.00
#Sta/Elev= 30
  4065.0  425.72  4123.9  420.06  4130.4  417.56  4253.7  409.44  4286.7  405.00
  4340.3  402.58  4413.4  393.58  4471.2  392.80  4602.1  383.66  4631.7  383.59
  4765.0  382.39  4878.7  383.88  4921.7  386.46  4942.9  386.02  4949.4  382.99
  4990.6  381.69  4995.5  381.61  4997.5  381.11  5015.4  381.61  5018.5  384.96
  5028.5  385.99  5058.8  383.10  5099.1  382.34  5578.9  382.08  5633.2  383.20
  5771.8  397.62  6006.1  400.94  6157.2  406.17  6318.5  405.97  6620.8  422.52
#Mann=8,-1,0
  4065.0    0.05       0  4286.7    0.12       0  4631.7     0.1       0
  4765.0    0.12       0  4990.6    0.05       0  4995.5    0.03       0
  5015.4    0.05       0  5578.9    0.12       0
Bank Sta=4995.5,5015.4
Exp/Cntr=0.3,0.1

Type RM Length L Ch R = 1,87636,580,580,580
BEGIN DESCRIPTION:
Caney Creek 95.0
END DESCRIPTION:
XS GIS Cut Line= 3
      2783026.03      6785711.02      2781626.00      6784911.00
      2780025.98      6785561.01
#Sta/Elev= 30
  3387.5  439.77  3460.2  435.91  3755.4  409.68  3782.7  410.35  3804.3  406.90
  3820.2  407.68  3885.3  402.09  3944.0  398.11  4121.1  393.81  4207.4  386.73
  4325.5  383.33  4896.3  382.02  4992.1  384.79  4997.1  381.77  5004.8  381.74
  5006.8  381.24  5024.7  381.74  5038.8  383.29  5044.2  382.24  5054.0  384.56
  5117.3  384.69  5161.9  382.02  5548.7  382.50  5681.4  382.12  5723.2  383.56
  5842.1  391.83  6021.4  396.10  6283.8  409.77  6521.9  412.41  6727.0  423.71
#Mann=7,-1,0
  3387.5    0.05       0  3885.3    0.12       0  4325.5    0.05       0
  5004.8    0.03       0  5024.7    0.05       0  5117.3    0.05       0
  5548.7    0.12       0
Bank Sta=5004.8,5024.7
Exp/Cntr=0.3,0.1

Type RM Length L Ch R = 1,87056,1073,1073,1073
BEGIN DESCRIPTION:
Caney Creek 94.0
END DESCRIPTION:
XS GIS Cut Line= 3
      2783025.96      6785010.98      2781626.00      6784361.00
      2780326.05      6784411.00
#Sta/Elev= 30
  3457.6  429.45  3475.3  428.82  3523.7  425.96  3563.4  413.96  3591.8  415.26
  3609.2  414.38  3622.9  417.70  3637.6  417.84  3677.8  413.75  3683.4  414.12
  3729.2  407.93  3734.7  408.21  3780.5  401.43  3809.3  395.74  3832.4  392.64
  3879.2  389.32  3963.7  381.93  4862.4  381.47  4864.4  380.97  4882.3  381.47
  4918.2  382.58  4964.0  381.62  5811.7  381.74  5961.8  388.34  6001.8  393.74
  6051.9  403.73  6081.9  407.67  6131.9  411.89  6252.0  416.55  6302.0  416.40
#Mann=6,-1,0
  3457.6    0.12       0  3475.3    0.05       0  3809.3    0.12       0
  3879.2    0.05       0  4862.4    0.03       0  4882.3    0.05       0
Bank Sta=4862.4,4882.3
Exp/Cntr=0.3,0.1

Type RM Length L Ch R = 1,85983,565,565,565
BEGIN DESCRIPTION:
Caney Creek 93.0
END DESCRIPTION:
XS GIS Cut Line= 4
      2782698.44      6781765.58      2782184.10      6782858.49
      2781026.00      6783561.00      2780375.98      6784011.01
#Sta/Elev= 30
  2442.2  460.87  2690.2  443.83  2824.0  428.07  2906.4  420.94  2997.5  409.25
  3048.7  412.23  3065.9  411.72  3071.4  413.50  3088.7  412.55  3094.2  414.00
  3122.6  414.18  3145.4  413.43  3162.6  409.78  3190.9  410.84  3221.8  408.62
  3236.5  409.17  3365.5  399.17  3396.1  395.49  3597.6  383.09  3665.0  381.64
  3811.6  382.72  3881.6  381.50  3883.6  381.00  3902.0  381.50  5456.6  382.11
  5593.8  395.31  5608.7  398.23  5680.3  406.07  5758.7  412.76  5795.2  414.37
#Mann=3,-1,0
  2442.2    0.05       0  3881.6    0.03       0  3902.0    0.05       0
Bank Sta=3881.6,3902
Exp/Cntr=0.3,0.1

Type RM Length L Ch R = 1,85418,1916,1916,1916
BEGIN DESCRIPTION:
Caney Creek 92.0
END DESCRIPTION:
XS GIS Cut Line= 3
      2782005.35      6781817.52      2780826.00      6783061.00
      2780375.98      6783761.03
#Sta/Elev= 30
  3291.3  444.16  3314.5  442.13  3335.9  441.86  3342.8  440.67  3364.2  441.05
  3385.2  439.41  3399.4  439.08  3413.6  440.59  3434.6  439.13  3441.9  439.98
  3470.2  439.46  3512.7  433.23  3526.8  429.84  3533.7  426.77  3547.9  422.63
  3562.0  420.01  3583.4  420.68  3611.8  418.59  3625.9  418.91  3696.3  407.32
  3781.3  397.78  3965.3  382.10  4542.0  382.00  4544.1  381.50  4562.5  382.00
  5605.8  382.25  5678.4  389.16  5714.8  393.98  5778.2  404.91  5837.3  408.15
#Mann=3,-1,0
  3291.3    0.05       0  4542.0    0.03       0  4562.5    0.05       0
Bank Sta=4542,4562.5
Exp/Cntr=0.3,0.1

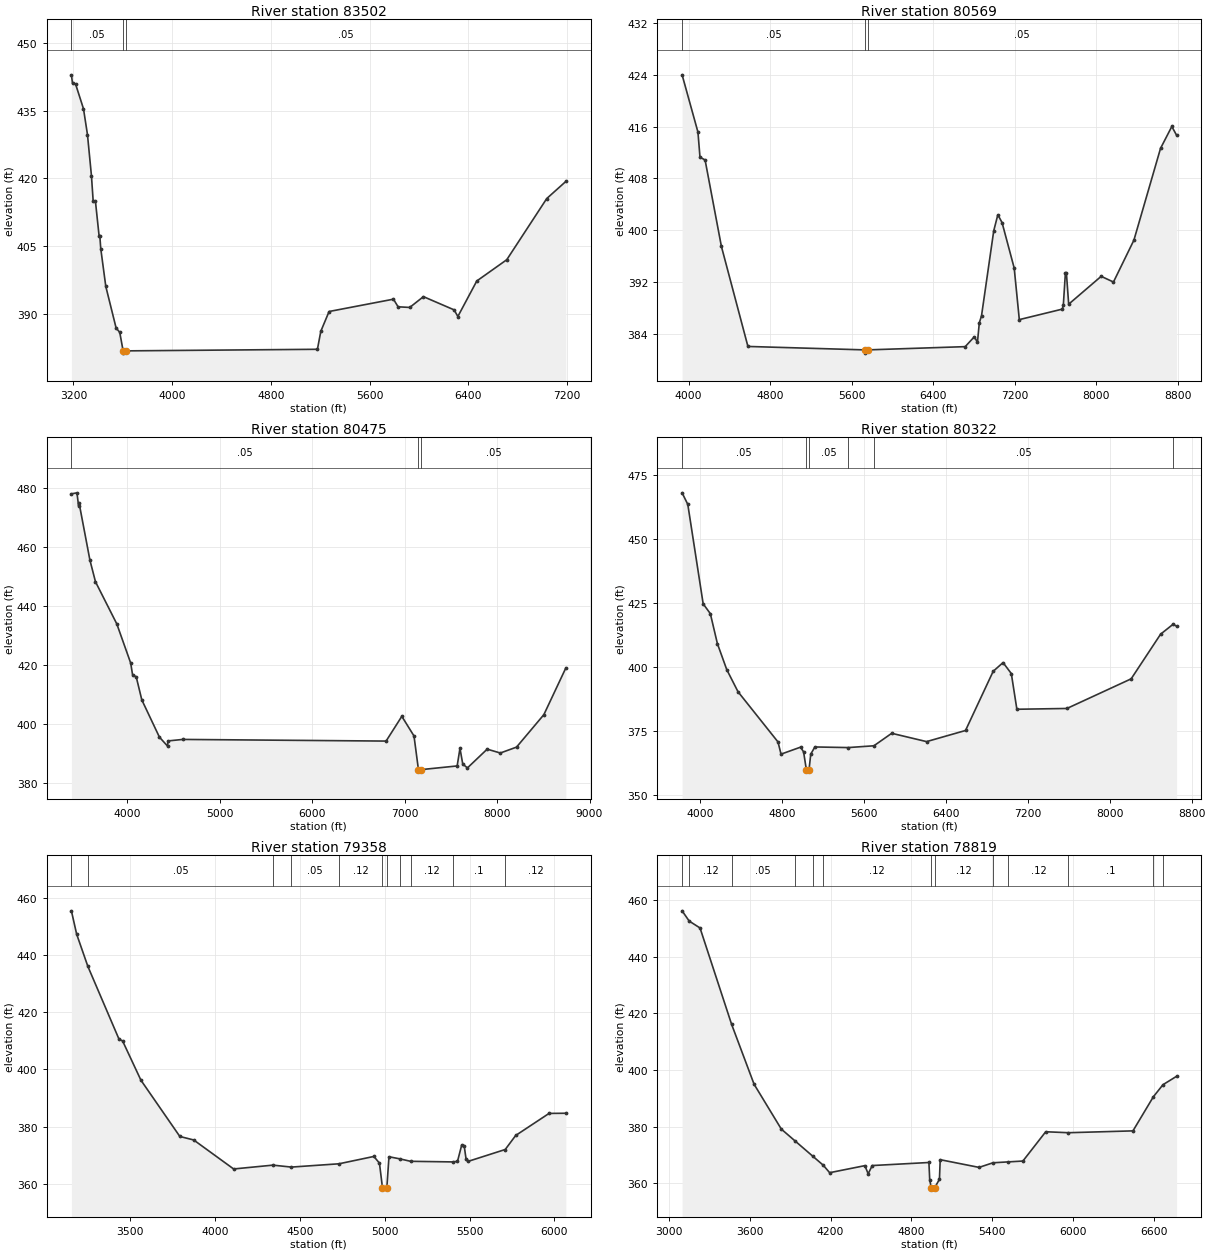
Type RM Length L Ch R = 1,83502,2933,2933,2933
BEGIN DESCRIPTION:
Caney Creek 91.0
END DESCRIPTION:
XS GIS Cut Line= 3
      2781647.01      6780771.60      2779959.18      6781444.17
      2778887.15      6783354.53
#Sta/Elev= 30
  3183.1  442.95  3192.3  441.06  3216.5  440.95  3281.2  435.42  3313.4  429.72
  3345.7  420.58  3359.4  415.07  3378.0  414.94  3408.0  407.18  3413.4  407.33
  3421.0  404.47  3461.9  396.09  3545.5  386.88  3575.1  385.91  3602.3  381.81
  3604.8  381.31  3627.3  381.81  5177.1  382.16  5204.6  386.15  5271.6  390.53
  5793.3  393.26  5830.9  391.57  5925.2  391.43  6036.3  393.82  6285.0  390.89
  6315.1  389.42  6468.7  397.29  6711.7  402.00  7035.7  415.55  7190.6  419.34
#Mann=3,-1,0
  3183.1    0.05       0  3602.3    0.03       0  3627.3    0.05       0
Bank Sta=3602.3,3627.3
Exp/Cntr=0.3,0.1

Type RM Length L Ch R = 1,80569,94,94,94
BEGIN DESCRIPTION:
Mapping XS ba7d4617
END DESCRIPTION:
XS GIS Cut Line= 3
      2778628.79      6778095.69      2778749.32      6781229.00
      2778596.42      6782937.84
#Sta/Elev= 30
  3936.1  423.99  4091.5  415.15  4111.5  411.28  4161.6  410.85  4321.7  397.51
  4581.9  382.08  5729.8  381.55  5732.4  381.05  5755.6  381.55  6713.5  382.05
  6803.5  383.58  6833.6  382.70  6851.9  385.71  6873.6  386.81  6993.7  399.94
  7033.7  402.40  7075.2  401.19  7194.2  394.18  7244.4  386.22  7666.1  387.84
  7676.1  388.40  7696.2  393.34  7706.3  393.43  7728.8  388.60  8047.6  392.90
  8168.1  392.02  8368.9  398.49  8629.9  412.64  8740.7  416.02  8787.4  414.67
#Mann=3,-1,0
  3936.1    0.05       0  5729.8    0.05       0  5755.6    0.05       0
Bank Sta=5729.8,5755.6
Exp/Cntr=0.3,0.1

Type RM Length L Ch R = 1,80475,153,153,153
BEGIN DESCRIPTION:
Caney Creek 90.0
END DESCRIPTION:
XS GIS Cut Line= 4
      2778476.00      6777561.00      2778576.00      6779161.00
      2778608.59      6781136.41      2778310.86      6782879.87
#Sta/Elev= 30
  3396.8  478.02  3456.9  478.37  3474.5  473.96  3479.5  475.01  3597.2  455.52
  3657.3  448.18  3887.8  433.88  4038.1  420.58  4058.1  416.66  4098.2  415.87
  4158.3  408.09  4348.7  395.45  4436.3  392.41  4441.3  394.15  4601.7  394.66
  6800.2  394.10  6970.2  402.50  7102.0  395.83  7150.0  384.40  7152.5  383.90
  7175.8  384.40  7568.7  385.66  7599.1  391.63  7629.5  386.27  7680.2  385.00
  7893.3  391.36  8035.5  390.05  8210.8  392.05  8506.4  403.07  8744.3  418.94
#Mann=3,-1,0
  3396.8    0.05       0  7150.0    0.05       0  7175.8    0.05       0
Bank Sta=7150,7175.8
Exp/Cntr=0.3,0.1

Type RM Length L Ch R = 1,80322,964,964,964
BEGIN DESCRIPTION:
Mapping XS 80b8f415
END DESCRIPTION:
XS GIS Cut Line= 3
      2778377.61      6777985.48      2778498.17      6781118.82
      2777797.42      6782660.03
#Sta/Elev= 30
  3824.2  467.96  3879.8  463.43  4029.9  424.56  4099.9  420.72  4168.7  409.01
  4260.0  398.86  4370.1  390.19  4760.4  370.57  4790.4  365.79  4980.6  368.52
  5010.6  366.67  5037.7  359.65  5040.3  359.15  5063.5  359.65  5080.6  365.81
  5120.7  368.60  5446.3  368.36  5697.3  369.06  5871.2  373.94  6211.5  370.69
  6591.8  375.04  6862.0  398.18  6958.4  401.59  7039.1  397.29  7093.3  383.34
  7582.1  383.65  8209.2  395.23  8497.0  412.70  8617.8  416.54  8652.9  415.84
#Mann=6,-1,0
  3824.2    0.05       0  5037.7    0.04       0  5063.5    0.05       0
  5446.3    0.12       0  5697.3    0.05       0  8617.8    0.12       0
Bank Sta=5037.7,5063.5
Exp/Cntr=0.3,0.1

Type RM Length L Ch R = 1,79358,539,539,539
BEGIN DESCRIPTION:
Caney Creek 88.0
END DESCRIPTION:
XS GIS Cut Line= 3
      2778217.72      6777996.33      2777826.00      6779811.00
      2777457.81      6780802.48
#Sta/Elev= 30
  3153.7  455.44  3184.8  447.26  3250.9  435.99  3434.7  410.50  3455.2  409.96
  3563.6  396.19  3792.8  376.52  3874.6  375.29  4109.9  365.15  4341.4  366.49
  4450.0  365.81  4730.5  366.96  4936.3  369.53  4969.2  367.19  4987.0  358.60
  4989.6  358.10  5012.8  358.60  5025.3  369.43  5089.1  368.69  5152.6  367.83
  5399.8  367.62  5429.1  367.80  5454.1  373.55  5468.9  373.11  5479.2  368.81
  5490.2  367.78  5710.5  371.96  5772.1  376.87  5968.7  384.58  6067.8  384.64
#Mann=11,-1,0
  3153.7    0.12       0  3250.9    0.05       0  4341.4    0.12       0
  4450.0    0.05       0  4730.5    0.12       0  4987.0    0.07       0
  5012.8    0.12       0  5089.1     0.1       0  5152.6    0.12       0
  5399.8     0.1       0  5710.5    0.12       0
Bank Sta=4987,5012.8
Exp/Cntr=0.3,0.1

Type RM Length L Ch R = 1,78819,550,550,550
BEGIN DESCRIPTION:
Caney Creek 87.0
END DESCRIPTION:
XS GIS Cut Line= 3
      2778148.22      6777832.22      2777476.00      6779611.00
      2776626.01      6781160.97
#Sta/Elev= 30
  3098.7  456.19  3151.3  452.57  3231.7  450.14  3465.9  416.15  3632.8  394.99
  3835.0  379.15  3933.4  375.12  4069.8  369.53  4146.3  366.40  4193.6  363.77
  4455.1  366.26  4479.4  363.37  4509.5  366.29  4930.2  367.37  4936.1  361.28
  4947.4  358.47  4950.0  357.97  4973.2  358.47  5008.3  361.46  5014.0  368.36
  5302.2  365.64  5405.6  367.27  5520.7  367.59  5627.5  367.88  5796.9  378.22
  5965.4  377.88  6444.3  378.53  6595.9  390.58  6666.9  394.82  6768.0  397.79
#Mann=13,-1,0
  3098.7    0.05       0  3151.3    0.12       0  3465.9    0.05       0
  3933.4    0.12       0  4069.8     0.1       0  4146.3    0.12       0
  4947.4    0.07       0  4973.2    0.12       0  5405.6     0.1       0
  5520.7    0.12       0  5965.4     0.1       0  6595.9    0.12       0
  6666.9     0.1       0
Bank Sta=4947.4,4973.2
Exp/Cntr=0.3,0.1