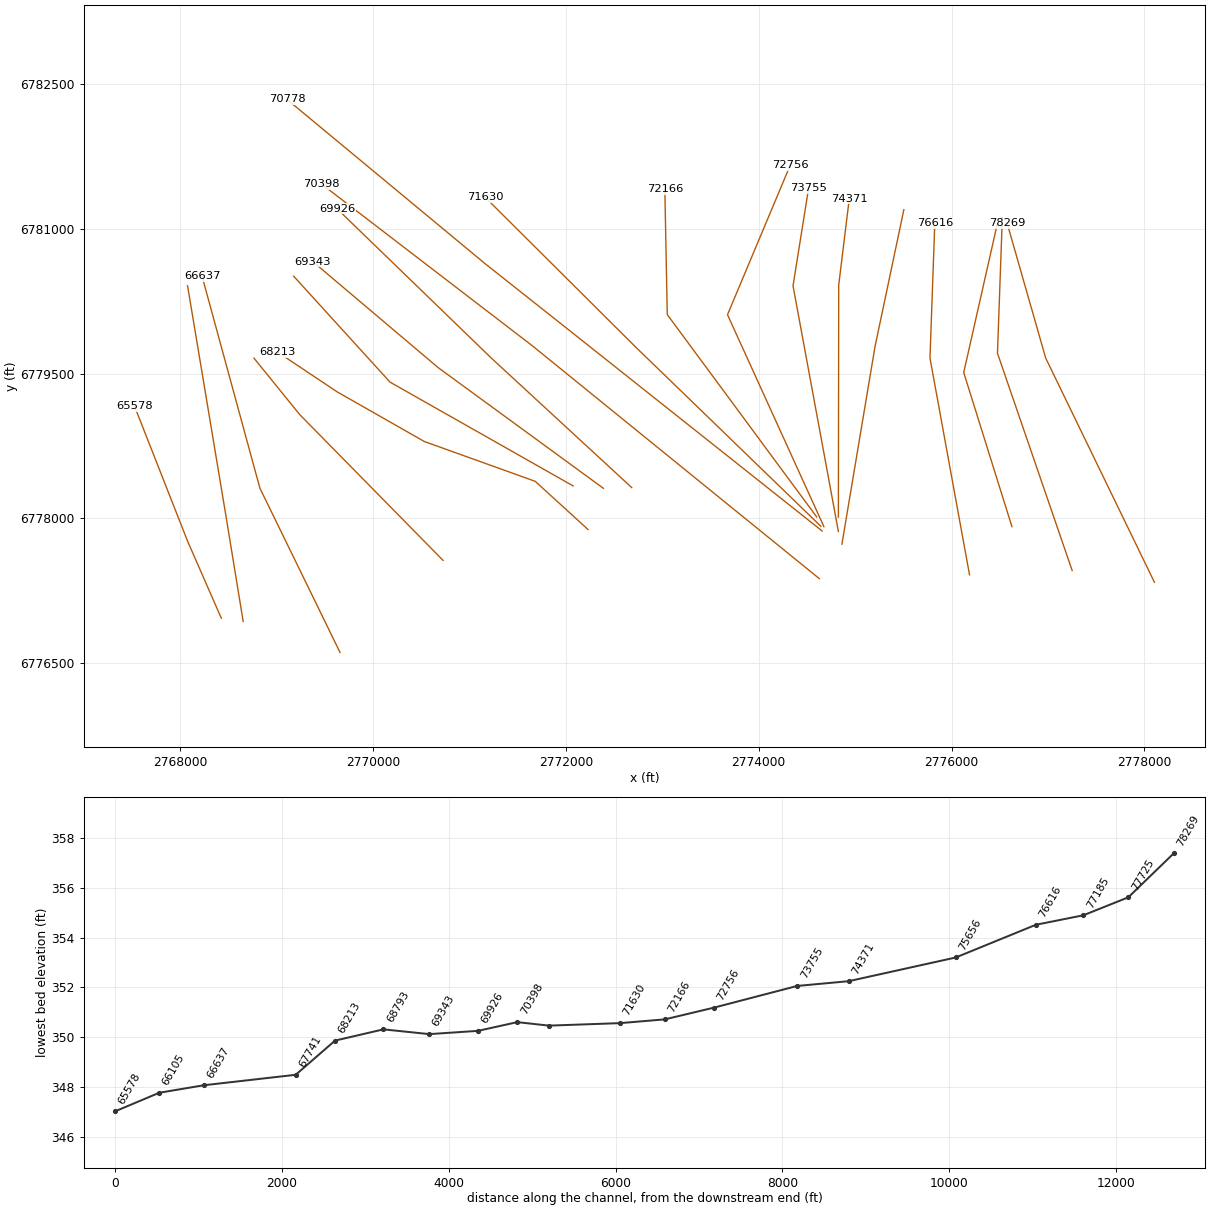
HEC-RAS study Caney Creek.prj: Caney Creek Base Level Engineering

--- Caney Creek.g01 (geometry) --- (continued)

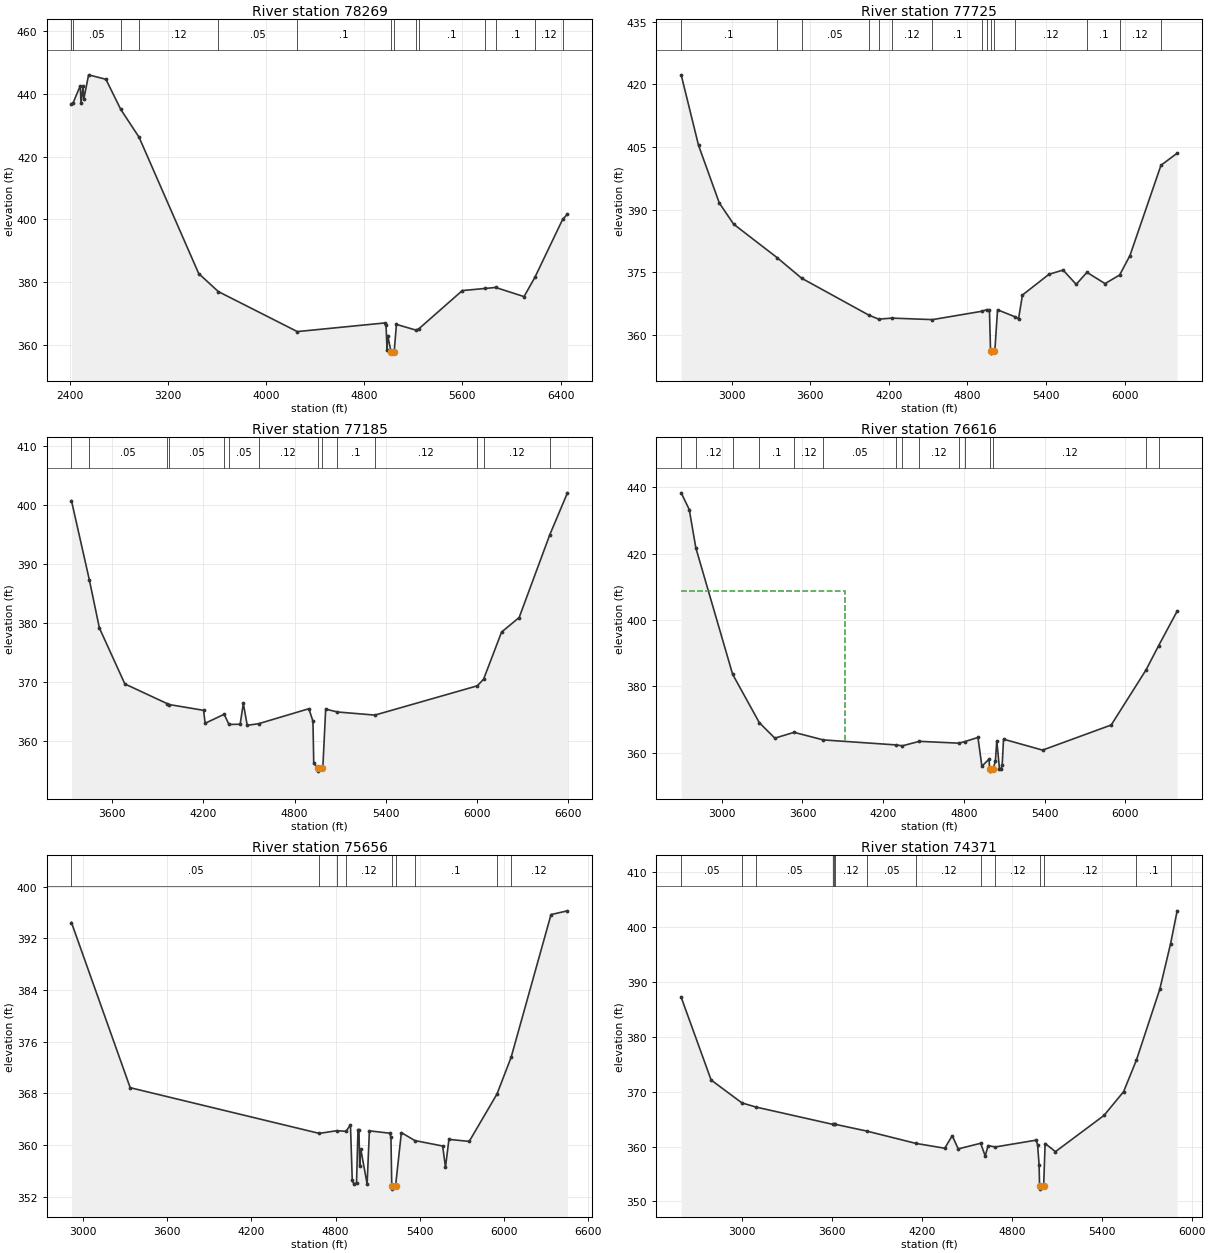
Type RM Length L Ch R = 1,78269,544,544,544
BEGIN DESCRIPTION:
Caney Creek 86.0
END DESCRIPTION:
XS GIS Cut Line= 3
      2778103.82      6777334.08      2776976.00      6779661.00
      2776575.99      6781061.05
#Sta/Elev= 30
  2414.5  436.86  2427.3  437.15  2486.5  442.66  2492.1  437.22  2509.1  442.43
  2514.7  438.34  2554.3  446.13  2695.3  444.70  2816.2  435.10  2965.3  426.24
  3451.4  382.75  3610.9  377.01  4254.9  364.24  4969.2  367.00  4978.1  366.26
  4986.3  358.37  4991.8  362.98  5018.5  357.87  5021.1  357.37  5044.5  357.87
  5062.7  366.54  5222.0  364.71  5245.1  365.12  5599.6  377.32  5785.9  378.00
  5871.4  378.31  6102.7  375.40  6190.9  381.53  6417.5  400.05  6456.4  401.72
#Mann=14,-1,0
  2414.5    0.12       0  2427.3    0.05       0  2816.2     0.1       0
  2965.3    0.12       0  3610.9    0.05       0  4254.9     0.1       0
  5018.5    0.07       0  5044.5     0.1       0  5222.0    0.12       0
  5245.1     0.1       0  5785.9    0.12       0  5871.4     0.1       0
  6190.9    0.12       0  6417.5     0.1       0
Bank Sta=5018.5,5044.5
Exp/Cntr=0.3,0.1

Type RM Length L Ch R = 1,77725,540,540,540
BEGIN DESCRIPTION:
Caney Creek 85.0
END DESCRIPTION:
XS GIS Cut Line= 3
      2777250.67      6777455.75      2776476.00      6779711.00
      2776526.00      6781111.02
#Sta/Elev= 30
  2614.8  422.30  2747.2  405.41  2905.8  391.59  3015.4  386.51  3347.2  378.49
  3533.8  373.57  4046.8  364.72  4121.8  363.76  4224.5  364.00  4532.7  363.64
  4911.3  365.65  4949.7  366.05  4967.7  365.84  4976.1  356.11  4978.6  355.61
  5002.1  356.11  5009.4  356.45  5029.4  365.99  5163.6  364.31  5189.5  363.78
  5219.5  369.53  5422.2  374.51  5529.7  375.51  5629.8  372.09  5711.8  374.97
  5849.9  372.27  5961.5  374.34  6040.1  379.00  6276.7  400.62  6400.3  403.52
#Mann=15,-1,0
  2614.8     0.1       0  3347.2    0.12       0  3533.8    0.05       0
  4046.8    0.12       0  4121.8     0.1       0  4224.5    0.12       0
  4532.7     0.1       0  4911.3    0.12       0  4949.7     0.1       0
  4976.1    0.07       0  5002.1     0.1       0  5163.6    0.12       0
  5711.8     0.1       0  5961.5    0.12       0  6276.7     0.1       0
Bank Sta=4976.1,5002.1
Exp/Cntr=0.3,0.1

Type RM Length L Ch R = 1,77185,569,569,569
BEGIN DESCRIPTION:
Caney Creek 84.0
END DESCRIPTION:
XS GIS Cut Line= 3
      2776626.01      6777910.98      2776126.00      6779511.00
      2776476.01      6781061.05
#Sta/Elev= 30
  3331.1  400.79  3448.4  387.40  3515.0  379.18  3682.6  369.69  3960.0  366.36
  3974.5  366.19  4200.7  365.21  4211.2  363.01  4336.6  364.54  4367.9  362.81
  4441.7  362.85  4462.6  366.37  4488.3  362.66  4563.4  362.94  4893.8  365.48
  4921.0  363.37  4926.2  356.23  4952.5  355.39  4955.1  354.89  4978.5  355.39
  4985.9  355.40  5004.8  365.42  5081.3  364.93  5328.7  364.40  6003.3  369.37
  6044.5  370.50  6162.9  378.49  6278.6  380.96  6480.8  395.04  6596.5  402.12
#Mann=14,-1,0
  3331.1     0.1       0  3448.4    0.05       0  3960.0    0.12       0
  3974.5    0.05       0  4336.6    0.12       0  4367.9    0.05       0
  4563.4    0.12       0  4952.5    0.07       0  4978.5    0.12       0
  5081.3     0.1       0  5328.7    0.12       0  6003.3     0.1       0
  6044.5    0.12       0  6480.8     0.1       0
Bank Sta=4952.5,4978.5
Exp/Cntr=0.3,0.1

Type RM Length L Ch R = 1,76616,960,960,960
BEGIN DESCRIPTION:
Caney Creek 83.0
END DESCRIPTION:
XS GIS Cut Line= 3
      2776186.03      6777411.87      2775776.00      6779661.00
      2775826.00      6781061.01
#Sta/Elev= 30
  2698.5  438.30  2758.6  433.27  2807.4  421.74  3081.2  383.65  3279.4  369.11
  3394.8  364.44  3537.3  366.19  3754.9  363.91  4296.3  362.40  4342.8  362.13
  4469.0  363.48  4761.9  362.93  4805.0  363.38  4904.8  364.65  4933.9  355.98
  4987.2  358.12  4991.7  355.01  4994.3  354.51  5017.7  355.01  5034.7  357.70
  5044.7  363.65  5064.7  355.23  5074.8  355.08  5084.8  356.22  5094.8  364.13
  5385.0  360.84  5895.3  368.40  6153.4  384.93  6248.4  392.33  6385.6  402.68
#Mann=15,-1,0
  2698.5    0.05       0  2807.4    0.12       0  3081.2    0.05       0
  3279.4     0.1       0  3537.3    0.12       0  3754.9    0.05       0
  4296.3    0.12       0  4342.8    0.05       0  4469.0    0.12       0
  4761.9     0.1       0  4805.0    0.12       0  4991.7    0.07       0
  5017.7    0.12       0  6153.4    0.05       0  6248.4    0.12       0
#XS Ineff=2,0
    0.00 3918.60  408.81               0
Permanent Ineff=
       F       F
Bank Sta=4991.7,5017.7
Exp/Cntr=0.3,0.1

Type RM Length L Ch R = 1,75656,1285,1285,1285
BEGIN DESCRIPTION:
Caney Creek 82.0
END DESCRIPTION:
XS GIS Cut Line= 3
      2774862.65      6777729.54      2775206.17      6779781.08
      2775505.04      6781200.55
#Sta/Elev= 30
  2919.9  394.44  3338.0  368.89  4684.0  361.82  4808.9  362.24  4874.8  362.14
  4905.9  363.16  4918.8  354.57  4928.9  354.04  4949.2  354.14  4959.4  362.41
  4966.6  362.27  4971.6  356.80  4979.6  359.37  5024.5  353.99  5040.8  362.21
  5183.9  361.86  5194.1  361.30  5200.0  353.70  5202.7  353.20  5227.0  353.70
  5268.4  361.94  5364.6  360.71  5562.2  359.87  5582.4  356.57  5606.9  360.90
  5751.3  360.58  5949.0  367.91  6049.6  373.59  6333.7  395.67  6450.6  396.25
#Mann=9,-1,0
  2919.9    0.05       0  4684.0    0.12       0  4808.9     0.1       0
  4874.8    0.12       0  5200.0    0.07       0  5227.0    0.12       0
  5364.6     0.1       0  5949.0    0.05       0  6049.6    0.12       0
Bank Sta=5200,5227
Exp/Cntr=0.3,0.1

Type RM Length L Ch R = 1,74371,616,616,616
BEGIN DESCRIPTION:
Caney Creek 81.0
END DESCRIPTION:
XS GIS Cut Line= 3
      2774826.00      6778010.95      2774829.54      6780419.55
      2774939.15      6781316.18
#Sta/Elev= 30
  2591.4  387.16  2791.4  372.10  2997.4  367.93  3091.2  367.18  3607.8  364.01
  3612.0  364.09  3617.2  364.06  3830.6  362.81  4160.3  360.56  4351.4  359.69
  4401.4  361.97  4441.4  359.57  4591.0  360.59  4621.4  358.29  4641.4  360.17
  4688.9  359.92  4961.4  361.16  4971.4  360.33  4981.4  356.66  4984.6  352.75
  4987.3  352.25  5011.8  352.75  5021.6  360.55  5090.8  359.07  5414.5  365.65
  5545.5  369.97  5631.6  375.75  5787.3  388.62  5859.0  396.85  5903.3  402.88
#Mann=14,-1,0
  2591.4    0.05       0  2997.4    0.12       0  3091.2    0.05       0
  3607.8    0.12       0  3612.0    0.05       0  3617.2    0.12       0
  3830.6    0.05       0  4160.3    0.12       0  4591.0     0.1       0
  4688.9    0.12       0  4984.6    0.07       0  5011.8    0.12       0
  5631.6     0.1       0  5859.0    0.12       0
Bank Sta=4984.6,5011.8
Exp/Cntr=0.3,0.1

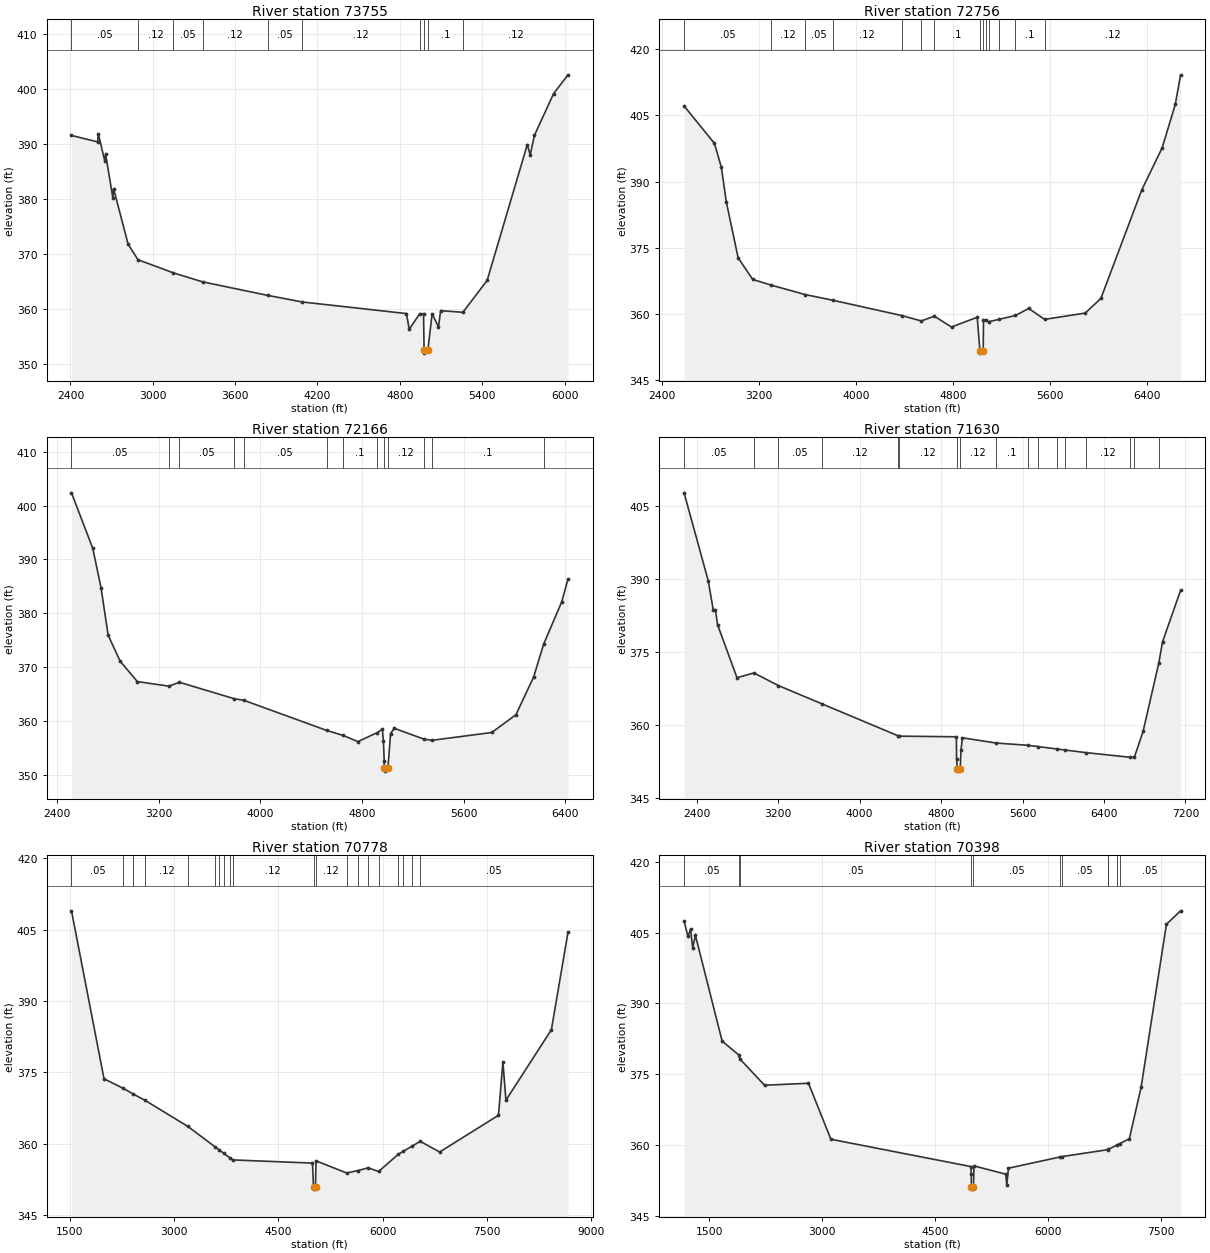
Type RM Length L Ch R = 1,73755,999,999,999
BEGIN DESCRIPTION:
Caney Creek 80.0
END DESCRIPTION:
XS GIS Cut Line= 3
      2774826.01      6777860.96      2774355.61      6780410.43
      2774517.06      6781422.84
#Sta/Elev= 30
  2407.5  391.62  2598.0  390.45  2603.1  391.92  2651.0  386.89  2656.1  388.19
  2709.1  380.26  2714.2  381.96  2820.1  371.86  2891.8  369.04  3150.5  366.64
  3362.2  365.02  3838.2  362.55  4087.9  361.36  4848.0  359.25  4868.4  356.40
  4945.1  359.23  4972.7  359.22  4976.8  352.56  4979.5  352.06  5004.0  352.56
  5035.1  359.21  5081.6  356.82  5097.3  359.78  5259.3  359.48  5436.0  365.26
  5728.7  389.97  5749.9  388.08  5780.3  391.62  5920.1  399.21  6025.2  402.64
#Mann=10,-1,0
  2407.5    0.05       0  2891.8    0.12       0  3150.5    0.05       0
  3362.2    0.12       0  3838.2    0.05       0  4087.9    0.12       0
  4945.1     0.1       0  4976.8    0.07       0  5004.0     0.1       0
  5259.3    0.12       0
Bank Sta=4976.8,5004
Exp/Cntr=0.3,0.1

Type RM Length L Ch R = 1,72756,590,590,590
BEGIN DESCRIPTION:
Caney Creek 79.0
END DESCRIPTION:
XS GIS Cut Line= 3
      2774675.99      6777911.02      2773676.00      6780111.00
      2774326.02      6781661.04
#Sta/Elev= 30
  2583.0  407.13  2833.4  398.66  2890.5  393.25  2931.2  385.45  3028.9  372.76
  3149.8  367.86  3303.4  366.57  3583.4  364.44  3812.3  363.15  4378.1  359.70
  4541.4  358.47  4647.5  359.56  4789.8  357.10  5002.3  359.31  5024.3  351.69
  5027.0  351.19  5051.6  351.69  5053.8  358.65  5074.1  358.63  5095.4  358.29
  5181.4  358.83  5317.8  359.71  5427.1  361.30  5558.3  358.83  5892.9  360.25
  6022.6  363.56  6358.8  388.06  6528.5  397.68  6636.6  407.48  6680.4  414.18
#Mann=14,-1,0
  2583.0    0.05       0  3303.4    0.12       0  3583.4    0.05       0
  3812.3    0.12       0  4378.1    0.05       0  4541.4    0.12       0
  4647.5     0.1       0  5024.3    0.07       0  5051.6     0.1       0
  5074.1    0.12       0  5095.4     0.1       0  5181.4    0.12       0
  5317.8     0.1       0  5558.3    0.12       0
Bank Sta=5024.3,5051.6
Exp/Cntr=0.3,0.1

Type RM Length L Ch R = 1,72166,536,536,536
BEGIN DESCRIPTION:
Caney Creek 78.0
END DESCRIPTION:
XS GIS Cut Line= 3
      2774601.19      6778012.02      2773051.22      6780112.00
      2773026.00      6781411.02
#Sta/Elev= 30
  2511.8  402.37  2679.4  392.06  2744.2  384.79  2800.5  375.94  2894.5  371.14
  3030.2  367.34  3278.1  366.49  3361.7  367.21  3794.6  364.15  3869.6  363.86
  4520.3  358.28  4649.5  357.35  4767.5  356.20  4918.6  357.86  4959.5  358.49
  4967.9  356.32  4974.2  352.64  4974.5  351.22  4977.3  350.72  5003.0  351.22
  5024.3  357.70  5053.5  358.67  5285.7  356.67  5350.7  356.44  5821.0  357.89
  6011.0  361.18  6151.0  368.21  6229.2  374.28  6371.1  382.09  6421.1  386.35
#Mann=13,-1,0
  2511.8    0.05       0  3278.1    0.12       0  3361.7    0.05       0
  3794.6    0.12       0  3869.6    0.05       0  4520.3    0.12       0
  4649.5     0.1       0  4918.6    0.12       0  4974.5    0.07       0
  5003.0    0.12       0  5285.7    0.12       0  5350.7     0.1       0
  6229.2    0.12       0
Bank Sta=4974.5,5003
Exp/Cntr=0.3,0.1

Type RM Length L Ch R = 1,71630,852,852,852
BEGIN DESCRIPTION:
Caney Creek 77.0
END DESCRIPTION:
XS GIS Cut Line= 3
      2774644.43      6777914.58      2772723.63      6779774.98
      2771163.11      6781328.90
#Sta/Elev= 30
  2276.1  407.60  2512.8  389.60  2562.5  383.61  2583.6  383.66  2604.9  380.56
  2795.8  369.71  2962.0  370.69  3201.7  368.11  3630.9  364.35  4372.1  357.86
  4386.1  357.74  4950.2  357.61  4952.7  352.97  4959.7  351.07  4962.5  350.57
  4988.2  351.07  4995.2  354.81  5009.3  357.40  5342.7  356.32  5651.0  355.87
  5749.4  355.61  5937.1  355.11  6020.6  354.89  6223.1  354.36  6652.2  353.42
  6698.5  353.43  6784.1  358.71  6938.3  372.73  6975.1  377.08  7152.4  387.62
#Mann=17,-1,0
  2276.1    0.05       0  2962.0    0.12       0  3201.7    0.05       0
  3630.9    0.12       0  4372.1    0.05       0  4386.1    0.12       0
  4959.7    0.07       0  4988.2    0.12       0  5342.7     0.1       0
  5651.0    0.12       0  5749.4     0.1       0  5937.1    0.12       0
  6020.6     0.1       0  6223.1    0.12       0  6652.2     0.1       0
  6698.5    0.12       0  6938.3    0.05       0
Bank Sta=4959.7,4988.2
Exp/Cntr=0.3,0.1

Type RM Length L Ch R = 1,70778,380,380,380
BEGIN DESCRIPTION:
Caney Creek 76.0
END DESCRIPTION:
XS GIS Cut Line= 4
      2774657.91      6777865.96      2771939.20      6780024.65
      2771164.76      6780638.07      2769105.69      6782346.52
#Sta/Elev= 30
  1528.5  408.95  1996.0  373.65  2271.0  371.66  2413.5  370.47  2584.7  369.14
  3201.3  363.64  3587.7  359.40  3647.4  358.75  3716.4  358.00  3800.4  357.09
  3845.2  356.61  4991.9  355.94  5006.5  350.97  5009.3  350.47  5035.1  350.97
  5042.4  356.41  5483.4  353.86  5647.5  354.38  5789.7  354.94  5942.9  354.18
  6226.1  357.81  6296.7  358.42  6427.9  359.54  6540.5  360.51  6819.6  358.27
  7664.7  365.99  7728.5  377.19  7771.5  369.15  8425.2  383.97  8663.5  404.45
#Mann=20,-1,0
  1528.5    0.05       0  2271.0    0.12       0  2413.5    0.05       0
  2584.7    0.12       0  3201.3    0.05       0  3587.7    0.12       0
  3647.4    0.05       0  3716.4    0.12       0  3800.4    0.05       0
  3845.2    0.12       0  5006.5    0.07       0  5035.1    0.12       0
  5483.4     0.1       0  5647.5     0.1       0  5789.7    0.12       0
  5942.9    0.12       0  6226.1    0.05       0  6296.7    0.12       0
  6427.9    0.12       0  6540.5    0.05       0
Bank Sta=5006.5,5035.1
Exp/Cntr=0.3,0.1

Type RM Length L Ch R = 1,70398,472,472,472
BEGIN DESCRIPTION:
Caney Creek 75.0
END DESCRIPTION:
XS GIS Cut Line= 3
      2774627.86      6777372.07      2771652.69      6779787.62
      2769466.77      6781465.77
#Sta/Elev= 30
  1167.7  407.47  1218.4  404.17  1253.5  405.74  1282.3  401.69  1317.5  404.44
  1672.5  381.98  1891.3  379.08  1906.0  378.24  2234.8  372.63  2818.2  373.05
  3115.5  361.18  4971.1  355.40  4979.0  353.87  4979.1  351.11  4981.9  350.61
  5007.7  351.11  5014.3  355.53  5435.7  353.78  5449.7  351.39  5471.1  355.04
  6153.9  357.42  6179.2  357.50  6789.3  358.97  6795.3  359.02  6916.4  360.00
  6951.3  360.28  7076.0  361.30  7232.1  372.22  7567.7  406.75  7755.8  409.60
#Mann=11,-1,0
  1167.7    0.05       0  1891.3     0.1       0  1906.0    0.05       0
  4979.1    0.05       0  5007.7    0.05       0  6153.9    0.12       0
  6179.2    0.05       0  6789.3    0.12       0  6795.3    0.05       0
  6916.4    0.12       0  6951.3    0.05       0
Bank Sta=4979.1,5007.7
Exp/Cntr=0.3,0.1

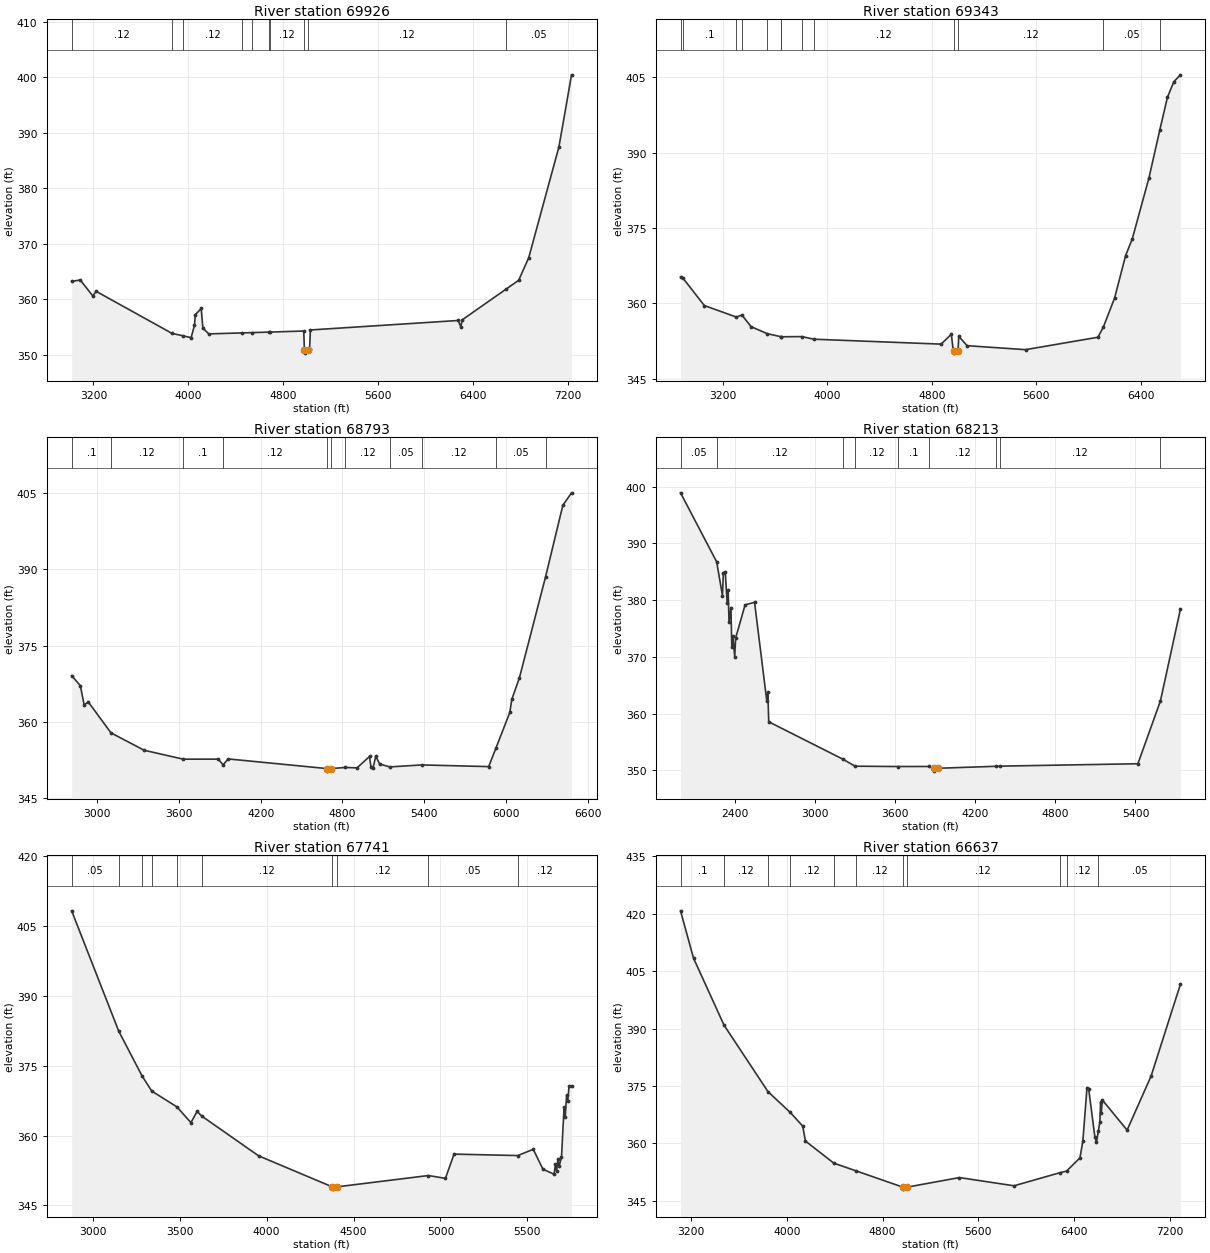
Type RM Length L Ch R = 1,69926,583,583,583
BEGIN DESCRIPTION:
Caney Creek 74.0
END DESCRIPTION:
XS GIS Cut Line= 3
      2772682.97      6778316.35      2771226.00      6779661.00
      2769626.00      6781211.00
#Sta/Elev= 30
  3017.2  363.20  3089.2  363.46  3195.2  360.59  3223.6  361.41  3862.5  353.82
  3952.9  353.40  4023.1  353.05  4051.4  355.26  4058.8  357.19  4108.2  358.32
  4122.3  354.79  4171.7  353.73  4453.1  353.91  4534.7  353.96  4675.5  354.05
  4688.6  354.06  4971.8  354.25  4977.7  350.76  4980.6  350.26  5007.8  350.76
  5021.1  350.97  5028.0  354.44  6272.8  356.15  6294.1  355.03  6308.3  356.29
  6676.7  361.82  6782.0  363.40  6866.7  367.47  7121.4  387.50  7227.5  400.48
#Mann=10,-1,0
  3017.2    0.12       0  3862.5     0.1       0  3952.9    0.12       0
  4453.1     0.1       0  4534.7    0.12       0  4675.5     0.1       0
  4688.6    0.12       0  4977.7    0.07       0  5007.8    0.12       0
  6676.7    0.05       0
Bank Sta=4977.7,5007.8
Exp/Cntr=0.3,0.1

Type RM Length L Ch R = 1,69343,550,550,550
BEGIN DESCRIPTION:
Caney Creek 73.0
END DESCRIPTION:
XS GIS Cut Line= 3
      2772388.80      6778309.03      2770676.00      6779561.00
      2769376.01      6780660.99
#Sta/Elev= 30
  2877.8  365.28  2898.5  364.97  3060.0  359.59  3305.1  357.30  3347.2  357.71
  3417.5  355.40  3539.7  354.01  3646.0  353.39  3646.9  353.38  3807.2  353.42
  3896.3  352.90  4870.8  351.92  4949.8  353.88  4962.7  350.96  4970.8  350.63
  4973.7  350.13  5000.9  350.63  5006.5  353.48  5070.2  351.61  5517.4  350.82
  6071.2  353.29  6112.7  355.32  6198.6  361.08  6283.1  369.54  6333.7  372.82
  6461.2  384.94  6544.8  394.53  6602.9  401.00  6652.3  404.12  6702.3  405.47
#Mann=13,-1,0
  2877.8    0.12       0  2898.5     0.1       0  3305.1    0.12       0
  3347.2     0.1       0  3539.7    0.12       0  3646.0     0.1       0
  3646.9    0.12       0  3807.2     0.1       0  3896.3    0.12       0
  4970.8    0.07       0  5000.9    0.12       0  6112.7    0.05       0
  6544.8    0.12       0
Bank Sta=4970.8,5000.9
Exp/Cntr=0.3,0.1

Type RM Length L Ch R = 1,68793,580,580,580
BEGIN DESCRIPTION:
Caney Creek 72.0
END DESCRIPTION:
XS GIS Cut Line= 3
      2772075.34      6778333.77      2770176.00      6779411.00
      2769175.98      6780511.03
#Sta/Elev= 30
  2812.0  369.10  2875.9  367.13  2903.3  363.38  2935.0  363.89  3101.1  357.84
  3344.7  354.42  3631.7  352.67  3888.5  352.68  3923.9  351.56  3960.9  352.72
  4686.9  350.82  4689.9  350.32  4717.1  350.82  4819.5  351.04  4906.8  350.96
  4998.9  353.20  5009.4  351.16  5023.6  350.84  5045.2  353.27  5073.6  351.71
  5148.4  351.15  5383.6  351.54  5873.7  351.21  5926.3  354.79  6029.1  361.87
  6043.3  364.41  6100.0  368.72  6291.7  388.56  6418.3  402.60  6482.2  405.05
#Mann=11,-1,0
  2812.0     0.1       0  3101.1    0.12       0  3631.7     0.1       0
  3923.9    0.12       0  4686.9    0.07       0  4717.1    0.12       0
  4819.5    0.12       0  5148.4    0.05       0  5383.6    0.12       0
  5926.3    0.05       0  6291.7    0.12       0
Bank Sta=4686.9,4717.1
Exp/Cntr=0.3,0.1

Type RM Length L Ch R = 1,68213,472,472,472
BEGIN DESCRIPTION:
Caney Creek 71.0
END DESCRIPTION:
XS GIS Cut Line= 5
      2772229.60      6777881.37      2771681.75      6778381.64
      2770530.91      6778795.22      2769626.00      6779311.00
      2769012.59      6779720.65
#Sta/Elev= 30
  1992.9  398.89  2263.8  386.72  2306.8  380.80  2313.6  384.72  2327.8  385.01
  2342.0  379.52  2349.4  381.72  2356.2  376.14  2370.3  378.63  2377.1  371.70
  2384.5  373.71  2398.7  370.03  2405.5  373.30  2476.4  379.16  2547.3  379.60
  2639.2  362.19  2646.7  363.79  2653.4  358.56  3211.8  351.94  3299.5  350.74
  3624.4  350.68  3855.3  350.69  3887.6  350.37  3890.5  349.87  3917.8  350.37
  4353.5  350.72  4386.2  350.75  5418.3  351.17  5587.0  362.22  5736.9  378.40
#Mann=9,-1,0
  1992.9    0.05       0  2263.8    0.12       0  3211.8     0.1       0
  3299.5    0.12       0  3624.4     0.1       0  3855.3    0.12       0
  4353.5     0.1       0  4386.2    0.12       0  5587.0    0.05       0
Bank Sta=3887.6,3917.8
Exp/Cntr=0.3,0.1

Type RM Length L Ch R = 1,67741,1104,1104,1104
BEGIN DESCRIPTION:
Caney Creek 70.0
END DESCRIPTION:
XS GIS Cut Line= 3
      2770726.02      6777560.98      2769239.09      6779074.33
      2768764.56      6779660.03
#Sta/Elev= 30
  2878.4  408.28  3149.0  382.45  3283.1  372.83  3339.0  369.57  3483.7  366.17
  3564.4  362.79  3599.7  365.19  3628.4  364.15  3953.3  355.66  4376.6  349.00
  4379.6  348.50  4406.8  349.00  4930.7  351.42  5028.3  350.81  5077.9  356.02
  5444.5  355.71  5533.4  357.05  5589.4  352.77  5653.4  351.71  5661.3  353.94
  5667.8  352.43  5675.7  354.89  5682.1  353.41  5695.9  355.31  5710.9  366.10
  5717.3  363.91  5725.3  368.65  5731.7  367.39  5739.7  370.69  5753.8  370.64
#Mann=10,-1,0
  2878.4    0.05       0  3149.0    0.12       0  3283.1     0.1       0
  3339.0    0.12       0  3483.7     0.1       0  3628.4    0.12       0
  4376.6    0.04       0  4406.8    0.12       0  4930.7    0.05       0
  5444.5    0.12       0
Bank Sta=4376.6,4406.8
Exp/Cntr=0.3,0.1

Type RM Length L Ch R = 1,66637,532,532,532
BEGIN DESCRIPTION:
Caney Creek 69.0
END DESCRIPTION:
XS GIS Cut Line= 3
      2769657.26      6776605.87      2768826.00      6778311.00
      2768226.00      6780510.98
#Sta/Elev= 30
  3111.5  420.74  3220.0  408.38  3475.2  390.88  3842.2  373.54  4028.1  368.11
  4132.5  364.54  4155.1  360.64  4392.0  354.87  4577.1  352.86  4970.8  348.58
  4973.8  348.08  5001.7  348.58  5442.1  351.10  5898.1  348.95  6279.7  352.35
  6337.5  352.79  6449.2  356.25  6473.4  360.57  6508.0  374.53  6521.8  374.35
  6573.6  361.78  6587.4  360.30  6603.3  363.29  6615.1  365.51  6622.0  370.70
  6627.2  367.84  6635.8  371.38  6843.1  363.49  7043.5  377.58  7288.8  401.57
#Mann=11,-1,0
  3111.5     0.1       0  3475.2    0.12       0  3842.2     0.1       0
  4028.1    0.12       0  4392.0     0.1       0  4577.1    0.12       0
  4970.8    0.07       0  5001.7    0.12       0  6279.7    0.05       0
  6337.5    0.12       0  6603.3    0.05       0
Bank Sta=4970.8,5001.7
Exp/Cntr=0.3,0.1

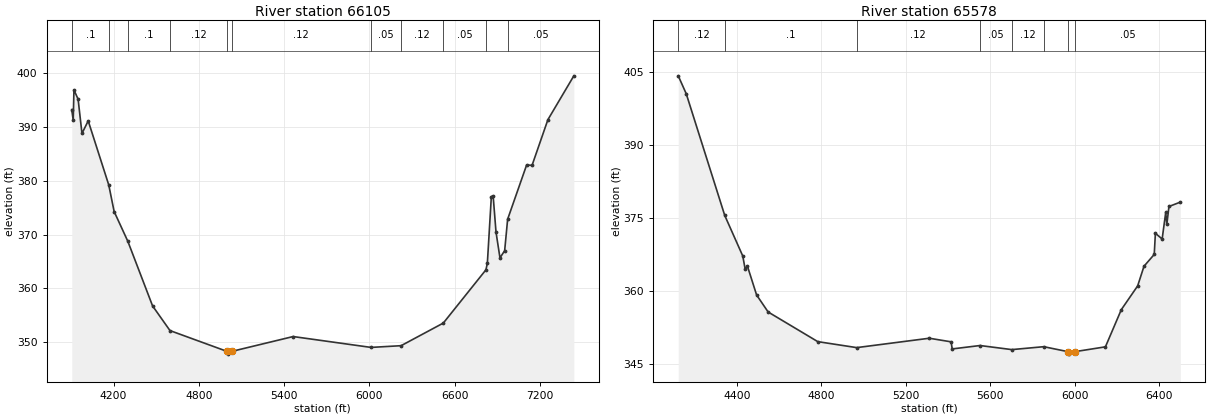
Type RM Length L Ch R = 1,66105,527,527,527
BEGIN DESCRIPTION:
Caney Creek 68.0
END DESCRIPTION:
XS GIS Cut Line= 3
      2768652.82      6776926.92      2768476.00      6778011.00
      2768076.00      6780410.99
#Sta/Elev= 30
  3905.9  393.27  3916.1  391.28  3921.2  396.95  3950.6  395.20  3977.6  388.84
  4021.5  391.18  4165.9  379.27  4203.9  374.31  4300.1  368.78  4474.3  356.75
  4596.7  352.16  4999.0  348.28  5002.0  347.78  5029.9  348.28  5463.0  351.05
  6010.9  349.03  6222.3  349.35  6519.3  353.56  6819.1  363.47  6829.1  364.70
  6857.0  377.05  6869.7  377.25  6890.0  370.47  6917.8  365.69  6950.8  367.03
  6971.7  372.88  7105.4  382.98  7143.4  382.90  7254.9  391.40  7437.4  399.56
#Mann=11,-1,0
  3905.9     0.1       0  4165.9    0.12       0  4300.1     0.1       0
  4596.7    0.12       0  4999.0    0.07       0  5029.9    0.12       0
  6010.9    0.05       0  6222.3    0.12       0  6519.3    0.05       0
  6819.1    0.12       0  6971.7    0.05       0
Bank Sta=4999,5029.9
Exp/Cntr=0.3,0.1

Type RM Length L Ch R = 1,65578,550,550,550
BEGIN DESCRIPTION:
Caney Creek 67.0
END DESCRIPTION:
XS GIS Cut Line= 3
      2768425.99      6776961.02      2768076.00      6777761.00
      2767525.98      6779161.04
#Sta/Elev= 30
  4122.9  404.31  4160.7  400.63  4343.2  375.57  4428.5  367.23  4439.8  364.52
  4450.3  365.18  4494.0  359.21  4548.6  355.71  4783.6  349.61  4967.9  348.38
  5311.8  350.31  5414.9  349.57  5420.2  348.11  5552.0  348.81  5702.5  347.97
  5853.8  348.57  5969.0  347.54  5972.0  347.04  6000.0  347.54  6145.7  348.54
  6220.9  356.19  6298.3  361.08  6328.4  365.13  6376.9  367.56  6382.3  371.91
  6414.3  370.73  6431.2  376.19  6436.5  373.76  6446.5  377.42  6500.3  378.32
#Mann=8,-1,0
  4122.9    0.12       0  4343.2     0.1       0  4967.9    0.12       0
  5552.0    0.05       0  5702.5    0.12       0  5853.8    0.05       0
  5969.0    0.07       0  6000.0    0.05       0
Bank Sta=5969,6000
Exp/Cntr=0.3,0.1