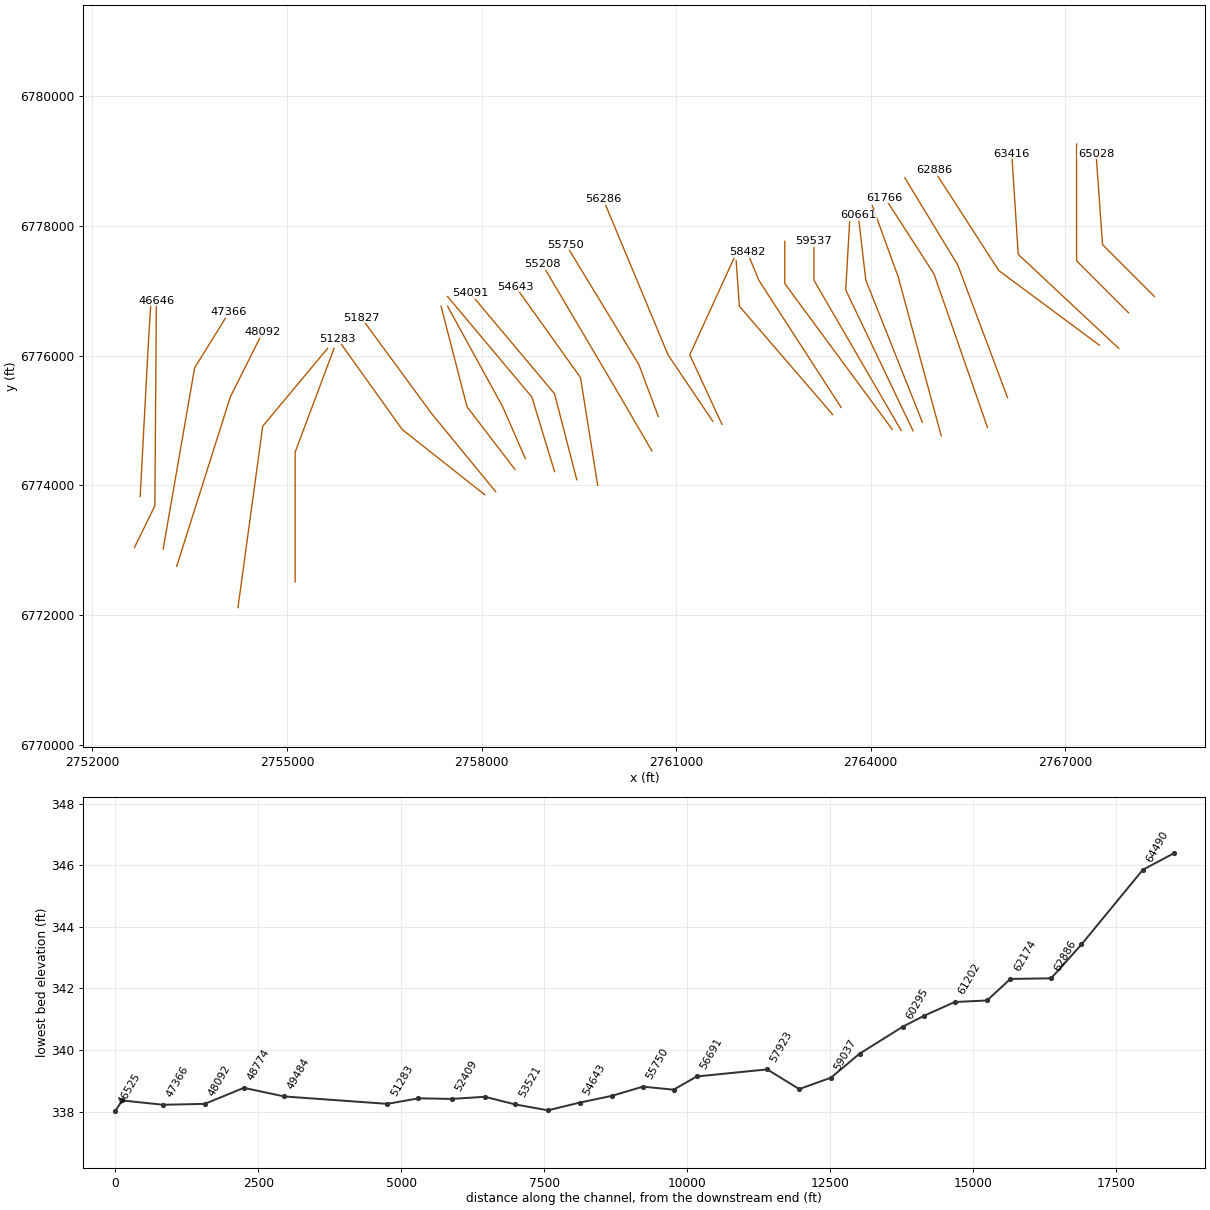
HEC-RAS study Caney Creek.prj: Caney Creek Base Level Engineering

--- Caney Creek.g01 (geometry) --- (continued)

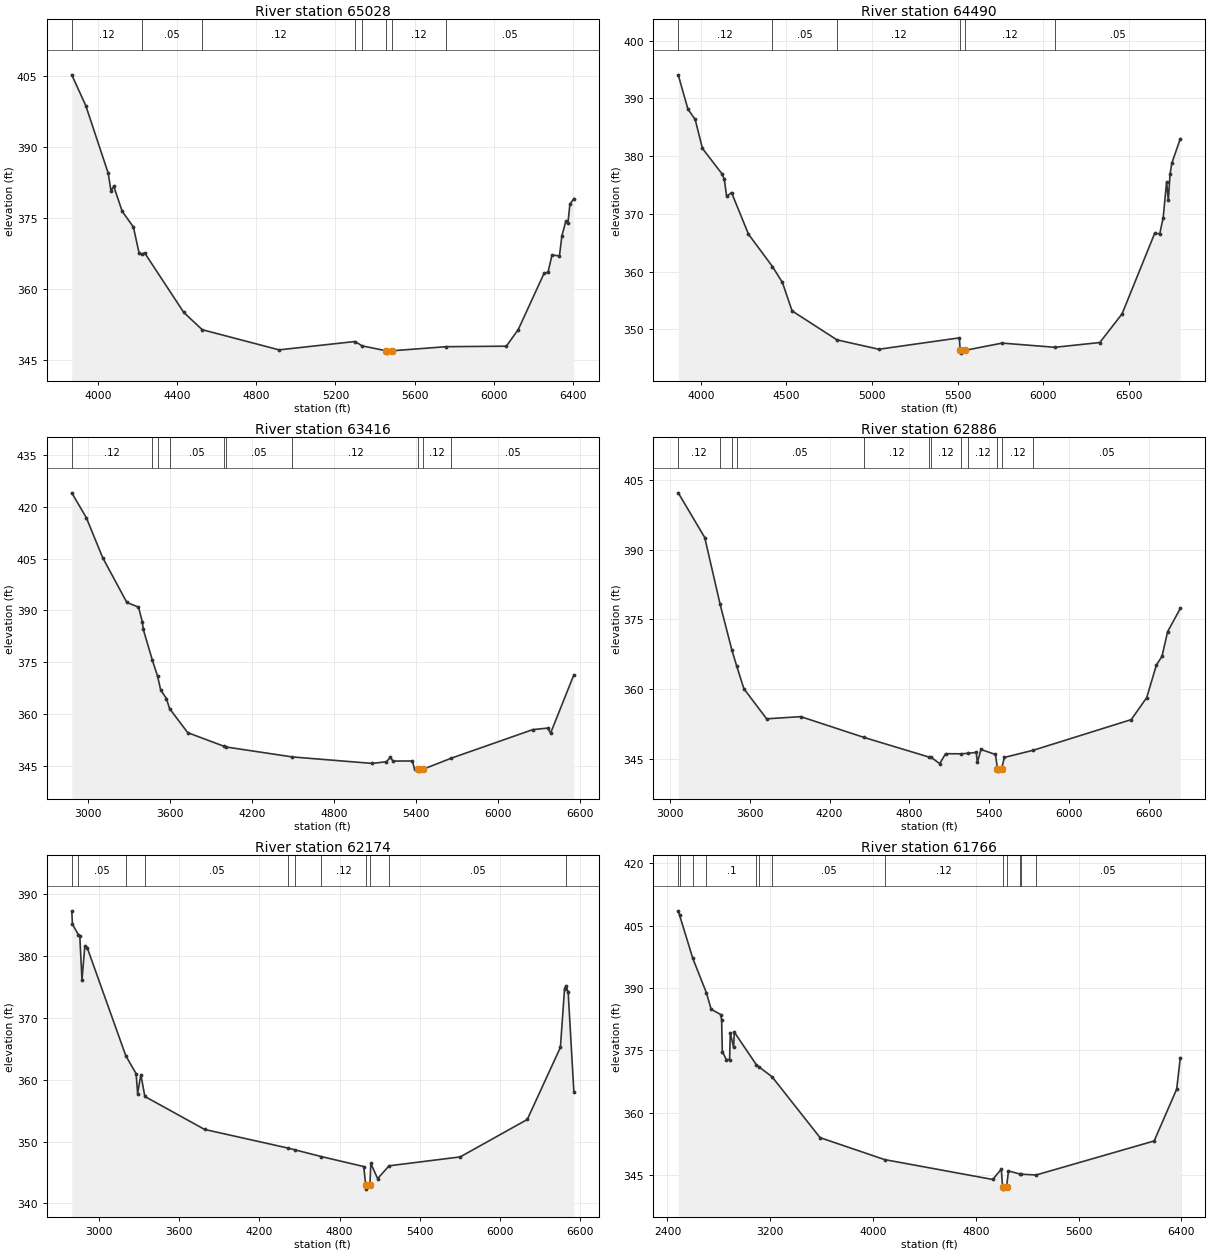
Type RM Length L Ch R = 1,65028,538,538,538
BEGIN DESCRIPTION:
Caney Creek 66.0
END DESCRIPTION:
XS GIS Cut Line= 3
      2768375.99      6776911.01      2767576.00      6777711.00
      2767476.00      6779110.97
#Sta/Elev= 30
  3868.6  405.27  3939.3  398.76  4052.4  384.48  4066.6  380.75  4080.7  381.67
  4123.1  376.40  4179.7  373.08  4208.0  367.65  4221.1  367.32  4236.3  367.61
  4434.3  354.99  4527.2  351.35  4915.1  347.08  5299.0  348.85  5334.2  347.93
  5455.7  346.89  5458.7  346.39  5486.7  346.89  5758.0  347.75  6062.7  347.86
  6122.8  351.38  6253.1  363.27  6273.2  363.52  6293.2  367.14  6330.8  366.97
  6343.4  371.25  6363.4  374.35  6373.5  373.85  6383.5  377.88  6403.5  379.08
#Mann=8,-1,0
  3868.6    0.12       0  4221.1    0.05       0  4527.2    0.12       0
  5299.0    0.05       0  5334.2    0.12       0  5455.7    0.07       0
  5486.7    0.12       0  5758.0    0.05       0
Bank Sta=5455.7,5486.7
Exp/Cntr=0.3,0.1

Type RM Length L Ch R = 1,64490,1074,1074,1074
BEGIN DESCRIPTION:
Caney Creek 65.0
END DESCRIPTION:
XS GIS Cut Line= 3
      2767976.00      6776661.00      2767176.00      6777461.00
      2767176.00      6779261.03
#Sta/Elev= 30
  3868.9  394.10  3925.5  388.15  3967.9  386.36  4010.3  381.34  4123.5  376.97
  4137.6  376.04  4151.7  373.01  4180.0  373.70  4279.0  366.48  4419.1  360.86
  4477.0  358.12  4533.6  353.18  4795.6  348.16  5040.3  346.53  5510.3  348.51
  5514.8  346.36  5517.8  345.86  5545.8  346.36  5760.3  347.60  6068.1  346.87
  6330.3  347.70  6460.3  352.67  6650.3  366.60  6680.3  366.56  6700.3  369.33
  6720.3  375.57  6730.3  372.33  6740.3  376.83  6750.3  378.75  6800.3  383.03
#Mann=6,-1,0
  3868.9    0.12       0  4419.1    0.05       0  4795.6    0.12       0
  5514.8    0.07       0  5545.8    0.12       0  6068.1    0.05       0
Bank Sta=5514.8,5545.8
Exp/Cntr=0.3,0.1

Type RM Length L Ch R = 1,63416,530,530,530
BEGIN DESCRIPTION:
Caney Creek 64.0
END DESCRIPTION:
XS GIS Cut Line= 3
      2767825.97      6776111.03      2766276.00      6777561.00
      2766176.00      6779111.02
#Sta/Elev= 30
  2878.2  424.09  2984.4  416.92  3104.6  405.29  3281.4  392.32  3366.4  390.97
  3394.7  386.74  3401.6  384.52  3468.7  375.53  3506.1  370.98  3529.1  366.99
  3571.6  364.42  3593.8  361.57  3727.2  354.58  3993.5  350.62  4005.3  350.44
  4493.8  347.54  5077.1  345.67  5181.0  346.15  5211.1  347.41  5229.9  346.34
  5371.4  346.38  5387.7  344.05  5416.1  343.93  5419.1  343.43  5447.1  343.93
  5657.1  347.19  6253.3  355.46  6363.5  355.91  6383.5  354.43  6553.9  371.34
#Mann=10,-1,0
  2878.2    0.12       0  3468.7    0.05       0  3506.1    0.12       0
  3593.8    0.05       0  3993.5    0.12       0  4005.3    0.05       0
  4493.8    0.12       0  5416.1    0.07       0  5447.1    0.12       0
  5657.1    0.05       0
Bank Sta=5416.1,5447.1
Exp/Cntr=0.3,0.1

Type RM Length L Ch R = 1,62886,712,712,712
BEGIN DESCRIPTION:
Caney Creek 63.0
END DESCRIPTION:
XS GIS Cut Line= 3
      2767525.97      6776161.02      2765976.00      6777311.00
      2764975.99      6778861.02
#Sta/Elev= 30
  3062.6  402.24  3261.8  392.62  3377.5  378.23  3466.3  368.36  3503.0  364.87
  3556.0  360.08  3727.1  353.59  3984.0  354.06  4457.7  349.60  4949.7  345.34
  4960.2  345.37  5028.3  343.95  5072.8  346.08  5190.2  346.06  5241.9  346.17
  5302.4  346.36  5311.7  344.26  5338.7  346.99  5447.6  345.91  5462.5  342.83
  5465.5  342.33  5493.5  342.83  5514.3  345.28  5732.4  346.83  6468.3  353.42
  6584.7  358.16  6657.3  365.16  6699.6  367.05  6742.0  372.37  6837.2  377.35
#Mann=12,-1,0
  3062.6    0.12       0  3377.5    0.05       0  3466.3    0.12       0
  3503.0    0.05       0  4457.7    0.12       0  4949.7    0.05       0
  4960.2    0.12       0  5190.2    0.05       0  5241.9    0.12       0
  5462.5    0.07       0  5493.5    0.12       0  5732.4    0.05       0
Bank Sta=5462.5,5493.5
Exp/Cntr=0.3,0.1

Type RM Length L Ch R = 1,62174,408,408,408
BEGIN DESCRIPTION:
Mapping XS a5934bf7
END DESCRIPTION:
XS GIS Cut Line= 3
      2766111.89      6775349.38      2765344.04      6777395.74
      2764527.27      6778739.51
#Sta/Elev= 30
  2795.6  387.30  2800.4  385.15  2845.2  383.44  2855.6  383.25  2872.1  376.11
  2893.5  381.65  2910.7  381.37  3200.1  363.87  3277.3  360.97  3288.6  357.76
  3312.9  360.82  3342.6  357.29  3789.9  351.96  4415.6  348.94  4464.8  348.67
  4662.4  347.58  4981.3  345.96  4996.0  342.91  4999.0  342.31  5027.0  342.91
  5034.2  346.46  5085.1  344.01  5170.6  346.08  5703.3  347.52  6205.2  353.57
  6453.2  365.23  6484.2  374.72  6495.3  375.21  6511.3  374.14  6553.8  358.09
#Mann=11,-1,0
  2795.6    0.12       0  2845.2    0.05       0  3200.1    0.12       0
  3342.6    0.05       0  4415.6    0.12       0  4464.8    0.05       0
  4662.4    0.12       0  4996.0    0.07       0  5027.0    0.12       0
  5170.6    0.05       0  6495.3    0.12       0
Bank Sta=4996,5027
Exp/Cntr=0.3,0.1

Type RM Length L Ch R = 1,61766,564,564,564
BEGIN DESCRIPTION:
Caney Creek 62.0
END DESCRIPTION:
XS GIS Cut Line= 3
      2765802.94      6774888.99      2764976.00      6777261.00
      2764218.82      6778434.61
#Sta/Elev= 30
  2483.8  408.53  2494.5  407.45  2597.4  397.08  2702.6  388.87  2740.1  384.85
  2814.2  383.60  2821.7  382.33  2827.0  374.69  2858.1  372.75  2883.8  372.78
  2889.1  379.20  2914.9  375.69  2920.2  379.37  3092.6  371.49  3111.8  371.02
  3214.7  368.61  3588.0  353.99  4090.6  348.71  4932.3  343.93  4998.8  346.43
  5009.0  342.21  5012.0  341.61  5040.0  342.21  5054.9  345.98  5148.2  345.21
  5151.2  345.20  5269.8  345.01  6188.7  353.19  6364.2  365.65  6392.5  373.21
#Mann=13,-1,0
  2483.8    0.12       0  2494.5     0.1       0  2597.4    0.12       0
  2702.6     0.1       0  3092.6    0.12       0  3111.8     0.1       0
  3214.7    0.05       0  4090.6    0.12       0  5009.0    0.07       0
  5040.0    0.12       0  5148.2    0.05       0  5151.2    0.12       0
  5269.8    0.05       0
Bank Sta=5009,5040
Exp/Cntr=0.3,0.1

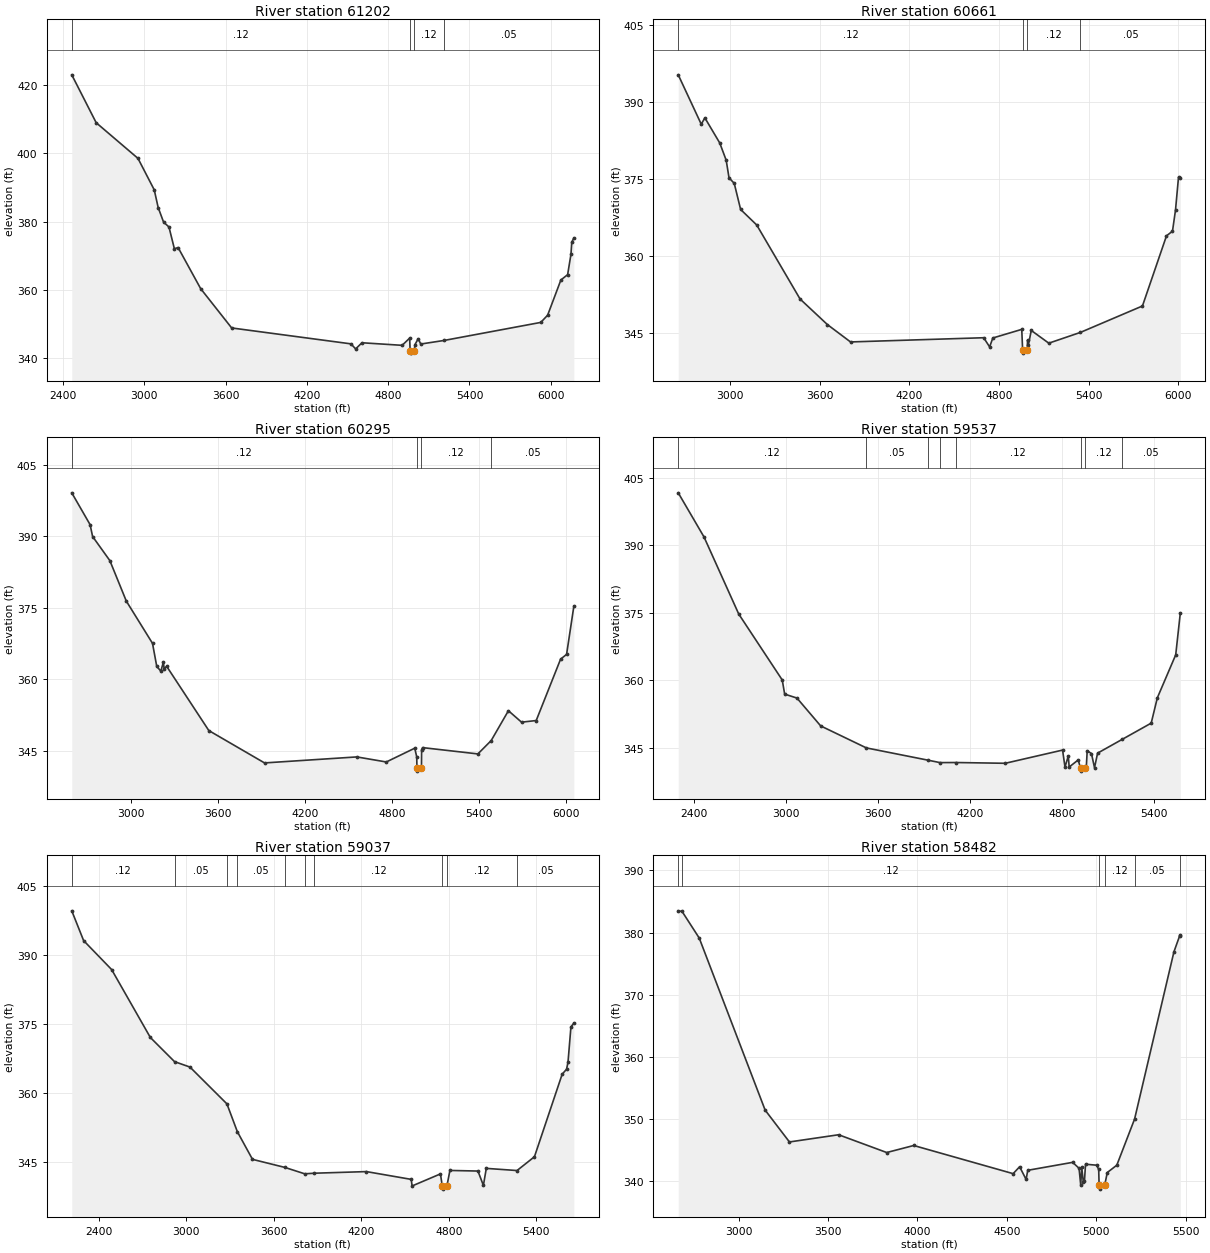
Type RM Length L Ch R = 1,61202,541,541,541
BEGIN DESCRIPTION:
Caney Creek 61.0
END DESCRIPTION:
XS GIS Cut Line= 3
      2765088.37      6774763.22      2764426.00      6777211.00
      2764026.00      6778311.01
#Sta/Elev= 30
  2464.1  422.91  2644.3  408.91  2952.8  398.49  3073.0  389.28  3101.9  384.12
  3141.7  379.87  3181.6  378.43  3221.5  372.07  3249.1  372.42  3415.6  360.41
  3644.4  348.92  4525.0  344.27  4559.6  342.79  4606.3  344.59  4902.9  343.84
  4958.5  345.95  4961.9  342.16  4964.9  341.56  4992.9  342.16  4997.3  344.02
  5021.2  345.76  5040.5  344.22  5213.1  345.27  5926.3  350.54  5976.9  352.65
  6074.6  362.93  6124.5  364.50  6149.1  370.44  6155.1  373.97  6170.4  375.22
#Mann=4,-1,0
  2464.1    0.12       0  4961.9    0.07       0  4992.9    0.12       0
  5213.1    0.05       0
Bank Sta=4961.9,4992.9
Exp/Cntr=0.3,0.1

Type RM Length L Ch R = 1,60661,366,366,366
BEGIN DESCRIPTION:
Caney Creek 60.0
END DESCRIPTION:
XS GIS Cut Line= 3
      2764798.01      6774972.56      2763926.00      6777161.00
      2763809.01      6778163.02
#Sta/Elev= 30
  2650.6  395.35  2804.8  385.73  2829.1  386.96  2928.8  382.07  2972.0  378.70
  2990.9  375.28  3025.9  374.20  3068.7  369.11  3176.4  366.09  3467.0  351.66
  3650.0  346.68  3805.2  343.29  4697.6  344.11  4737.3  342.32  4758.8  344.06
  4952.6  345.74  4958.6  341.71  4961.6  341.11  4989.6  341.71  4991.5  343.67
  4996.9  342.68  5016.4  345.53  5134.0  343.05  5345.9  345.15  5761.5  350.30
  5922.6  363.97  5962.8  364.88  5983.0  369.00  6003.1  375.39  6015.2  375.33
#Mann=4,-1,0
  2650.6    0.12       0  4958.6    0.07       0  4989.6    0.12       0
  5345.9    0.05       0
Bank Sta=4958.6,4989.6
Exp/Cntr=0.3,0.1

Type RM Length L Ch R = 1,60295,758,758,758
BEGIN DESCRIPTION:
Caney Creek 59.0
END DESCRIPTION:
XS GIS Cut Line= 3
      2764654.07      6774839.15      2763616.14      6777011.86
      2763676.00      6778060.95
#Sta/Elev= 30
  2592.1  399.13  2718.4  392.45  2735.6  389.97  2854.5  384.91  2967.9  376.42
  3148.3  367.56  3177.6  362.72  3205.8  361.73  3223.0  363.60  3228.5  362.21
  3245.6  362.75  3536.2  349.27  3920.0  342.48  4555.7  343.74  4758.8  342.68
  4954.7  345.57  4968.4  343.77  4970.1  341.36  4973.1  340.76  5001.1  341.36
  5002.1  345.25  5009.2  345.69  5389.8  344.37  5481.4  347.17  5600.1  353.43
  5690.3  351.03  5791.5  351.37  5959.4  364.24  6000.8  365.25  6050.8  375.33
#Mann=4,-1,0
  2592.1    0.12       0  4970.1    0.07       0  5001.1    0.12       0
  5481.4    0.05       0
Bank Sta=4970.1,5001.1
Exp/Cntr=0.3,0.1

Type RM Length L Ch R = 1,59537,500,500,500
BEGIN DESCRIPTION:
Caney Creek 58.0
END DESCRIPTION:
XS GIS Cut Line= 3
      2764469.88      6774845.50      2763126.00      6777161.00
      2763126.00      6777760.97
#Sta/Elev= 30
  2296.5  401.63  2464.7  391.84  2691.5  374.73  2975.4  360.10  2991.2  356.97
  3071.5  356.09  3226.3  349.91  3524.6  345.03  3923.9  342.33  4005.2  341.77
  4109.0  341.79  4431.0  341.62  4805.2  344.55  4821.0  340.78  4842.5  343.24
  4848.3  340.79  4907.1  342.36  4923.1  340.48  4926.1  339.88  4954.1  340.48
  4960.1  340.76  4965.9  344.41  4993.7  343.78  5013.7  340.64  5033.7  343.87
  5195.0  346.94  5383.7  350.53  5423.7  356.14  5543.7  365.68  5573.7  374.96
#Mann=8,-1,0
  2296.5    0.12       0  3524.6    0.05       0  3923.9    0.12       0
  4005.2    0.05       0  4109.0    0.12       0  4923.1    0.07       0
  4954.1    0.12       0  5195.0    0.05       0
Bank Sta=4923.1,4954.1
Exp/Cntr=0.3,0.1

Type RM Length L Ch R = 1,59037,555,555,555
BEGIN DESCRIPTION:
Caney Creek 57.0
END DESCRIPTION:
XS GIS Cut Line= 3
      2764331.45      6774863.70      2762676.00      6777111.00
      2762676.00      6777760.99
#Sta/Elev= 30
  2216.3  399.59  2297.5  393.12  2489.6  386.82  2754.9  372.06  2920.6  366.81
  3026.4  365.63  3279.7  357.63  3351.2  351.58  3455.0  345.57  3675.5  343.83
  3813.0  342.43  3879.5  342.56  4235.8  342.91  4542.8  341.22  4549.0  339.79
  4743.3  342.41  4756.0  339.70  4759.0  339.10  4787.0  339.70  4808.1  343.16
  5000.2  343.03  5037.5  339.91  5057.5  343.61  5268.1  343.14  5387.5  346.14
  5577.5  364.08  5607.5  365.16  5617.5  366.69  5637.5  374.35  5657.5  375.17
#Mann=10,-1,0
  2216.3    0.12       0  2920.6    0.05       0  3279.7    0.12       0
  3351.2    0.05       0  3675.5    0.12       0  3813.0    0.05       0
  3879.5    0.12       0  4756.0    0.07       0  4787.0    0.12       0
  5268.1    0.05       0
Bank Sta=4756,4787
Exp/Cntr=0.3,0.1

Type RM Length L Ch R = 1,58482,559,559,559
BEGIN DESCRIPTION:
Caney Creek 56.0
END DESCRIPTION:
XS GIS Cut Line= 3
      2763545.92      6775199.20      2762276.00      6777161.00
      2762096.40      6777596.46
#Sta/Elev= 30
  2662.1  383.51  2683.6  383.41  2779.5  379.13  3148.2  351.44  3284.0  346.32
  3559.0  347.48  3828.1  344.62  3979.1  345.75  4535.1  341.22  4571.4  342.33
  4607.7  340.29  4616.9  341.76  4868.0  343.04  4903.8  342.08  4913.0  339.43
  4918.9  342.23  4927.6  339.88  4934.1  340.05  4940.0  342.74  5001.8  342.58
  5013.7  341.91  5016.0  339.33  5019.0  338.73  5047.0  339.33  5061.6  341.40
  5114.9  342.58  5214.4  350.01  5434.5  376.92  5466.7  379.51  5470.1  379.62
#Mann=6,-1,0
  2662.1    0.05       0  2683.6    0.12       0  5016.0    0.07       0
  5047.0    0.12       0  5214.4    0.05       0  5466.7    0.12       0
Bank Sta=5016,5047
Exp/Cntr=0.3,0.1

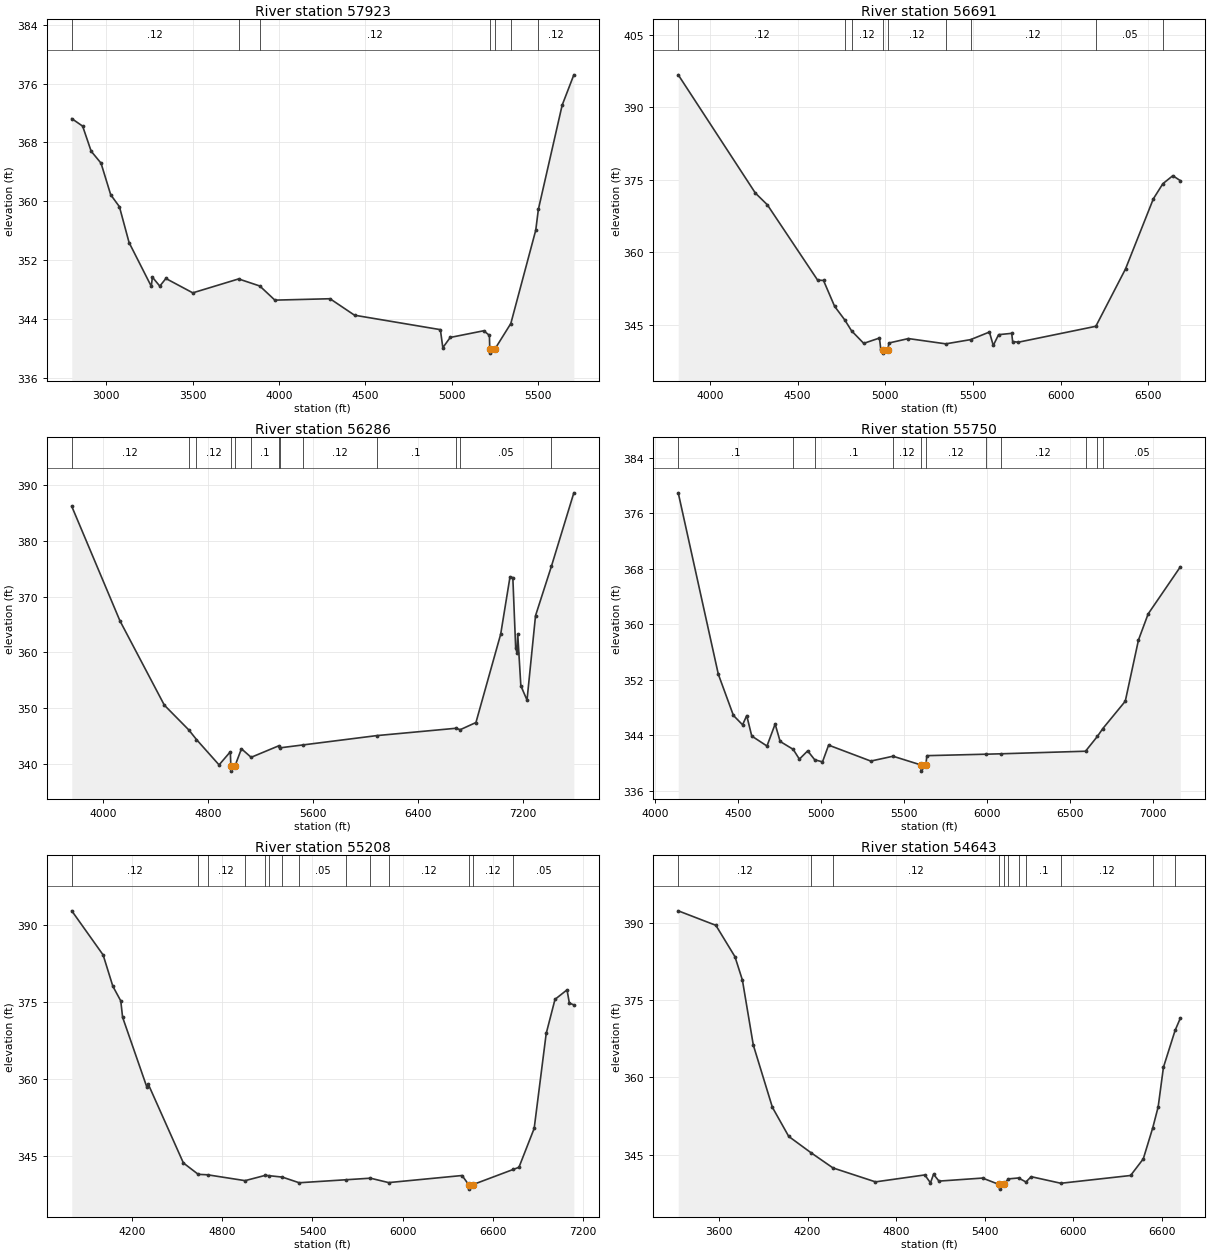
Type RM Length L Ch R = 1,57923,1232,1232,1232
BEGIN DESCRIPTION:
Caney Creek 55.0
END DESCRIPTION:
XS GIS Cut Line= 3
      2763414.20      6775090.83      2761976.00      6776761.00
      2761926.00      6777460.96
#Sta/Elev= 30
  2801.2  371.23  2864.1  370.21  2913.5  366.80  2970.5  365.18  3026.5  360.89
  3077.0  359.26  3132.9  354.39  3261.3  348.45  3267.9  349.69  3310.7  348.47
  3345.8  349.51  3501.6  347.56  3766.7  349.45  3889.4  348.49  3976.7  346.57
  4295.9  346.76  4437.8  344.52  4934.5  342.56  4948.7  340.11  4991.5  341.50
  5185.7  342.41  5218.3  341.78  5220.3  339.97  5223.3  339.37  5251.3  339.97
  5342.2  343.39  5486.5  356.07  5501.7  358.90  5639.4  373.06  5707.0  377.18
#Mann=7,-1,0
  2801.2    0.12       0  3766.7     0.1       0  3889.4    0.12       0
  5220.3    0.07       0  5251.3    0.12       0  5342.2    0.05       0
  5501.7    0.12       0
Bank Sta=5220.3,5251.3
Exp/Cntr=0.3,0.1

Type RM Length L Ch R = 1,56691,405,405,405
BEGIN DESCRIPTION:
Caney Creek 54.0
END DESCRIPTION:
XS GIS Cut Line= 3
      2761707.36      6774940.23      2761210.97      6776011.08
      2761910.63      6777540.76
#Sta/Elev= 30
  3819.7  396.69  4259.4  372.24  4327.6  369.82  4614.1  354.25  4648.0  354.16
  4711.2  348.82  4769.2  346.00  4807.7  343.76  4877.1  341.16  4966.8  342.26
  4974.3  340.02  4984.5  339.84  4987.5  339.14  5015.5  339.84  5020.3  341.23
  5131.9  342.15  5345.0  341.06  5486.3  341.93  5593.7  343.50  5615.7  340.73
  5646.2  342.96  5720.8  343.23  5726.2  341.54  5758.7  341.40  6200.5  344.69
  6369.7  356.55  6528.4  371.05  6582.7  374.18  6639.4  375.83  6682.1  374.81
#Mann=9,-1,0
  3819.7    0.12       0  4769.2     0.1       0  4807.7    0.12       0
  4984.5    0.07       0  5015.5    0.12       0  5345.0     0.1       0
  5486.3    0.12       0  6200.5    0.05       0  6582.7    0.12       0
Bank Sta=4984.5,5015.5
Exp/Cntr=0.3,0.1

Type RM Length L Ch R = 1,56286,536,536,536
BEGIN DESCRIPTION:
Caney Creek 53.0
END DESCRIPTION:
XS GIS Cut Line= 3
      2761564.71      6774988.28      2760876.00      6776011.00
      2759876.00      6778411.01
#Sta/Elev= 30
  3757.9  386.22  4125.7  365.68  4464.6  350.55  4651.1  346.11  4710.0  344.38
  4882.4  339.83  4968.4  342.18  4972.4  339.61  4975.4  338.71  5003.4  339.61
  5053.2  342.72  5127.3  341.19  5338.8  343.26  5351.0  342.90  5519.4  343.40
  6084.7  345.08  6690.4  346.40  6723.7  346.15  6843.4  347.43  7032.4  363.29
  7103.4  373.55  7125.1  373.44  7146.7  360.88  7157.0  359.91  7162.4  363.33
  7186.3  354.02  7233.4  351.46  7298.4  366.61  7419.2  375.43  7590.9  388.65
#Mann=13,-1,0
  3757.9    0.12       0  4651.1     0.1       0  4710.0    0.12       0
  4972.4    0.07       0  5003.4    0.12       0  5127.3     0.1       0
  5338.8    0.12       0  5351.0     0.1       0  5519.4    0.12       0
  6084.7     0.1       0  6690.4    0.12       0  6723.7    0.05       0
  7419.2    0.12       0
Bank Sta=4972.4,5003.4
Exp/Cntr=0.3,0.1

Type RM Length L Ch R = 1,55750,542,542,542
BEGIN DESCRIPTION:
Caney Creek 52.0
END DESCRIPTION:
XS GIS Cut Line= 3
      2760726.01      6775060.99      2760426.00      6775861.00
      2759301.27      6777712.66
#Sta/Elev= 30
  4141.2  378.94  4382.4  352.78  4473.2  346.84  4528.4  345.49  4553.3  346.82
  4583.5  343.87  4675.2  342.43  4724.2  345.60  4754.4  343.09  4832.8  341.95
  4870.1  340.54  4920.0  341.73  4962.7  340.44  5009.2  340.15  5046.0  342.56
  5299.9  340.26  5433.6  340.96  5600.2  339.71  5603.2  338.81  5631.2  339.71
  5637.1  341.04  5991.0  341.25  6084.4  341.31  6591.8  341.68  6663.8  343.84
  6695.9  344.95  6830.9  348.89  6910.4  357.72  6968.6  361.48  7162.1  368.26
#Mann=11,-1,0
  4141.2     0.1       0  4832.8    0.12       0  4962.7     0.1       0
  5433.6    0.12       0  5600.2    0.07       0  5631.2    0.12       0
  5991.0    0.05       0  6084.4    0.12       0  6591.8    0.05       0
  6663.8    0.12       0  6695.9    0.05       0
Bank Sta=5600.2,5631.2
Exp/Cntr=0.3,0.1

Type RM Length L Ch R = 1,55208,565,565,565
BEGIN DESCRIPTION:
Caney Creek 51.0
END DESCRIPTION:
XS GIS Cut Line= 3
      2760628.11      6774528.91      2760026.00      6775561.00
      2758934.96      6777410.14
#Sta/Elev= 30
  3797.7  392.67  4006.5  384.08  4071.0  378.00  4123.9  375.14  4135.9  371.97
  4297.9  358.33  4305.8  359.00  4540.7  343.60  4639.5  341.39  4701.4  341.30
  4951.4  340.16  5087.1  341.20  5109.8  341.13  5199.3  340.85  5311.4  339.75
  5625.9  340.34  5785.7  340.64  5906.9  339.78  6395.6  341.16  6438.7  339.41
  6441.7  338.51  6469.7  339.41  6737.9  342.36  6774.2  342.76  6875.6  350.33
  6955.6  368.80  7014.2  375.44  7094.2  377.29  7109.8  374.71  7139.6  374.37
#Mann=14,-1,0
  3797.7    0.12       0  4639.5    0.05       0  4701.4    0.12       0
  4951.4    0.05       0  5087.1    0.12       0  5109.8    0.05       0
  5199.3    0.12       0  5311.4    0.05       0  5625.9    0.12       0
  5785.7    0.05       0  5906.9    0.12       0  6438.7    0.05       0
  6469.7    0.12       0  6737.9    0.05       0
Bank Sta=6438.7,6469.7
Exp/Cntr=0.3,0.1

Type RM Length L Ch R = 1,54643,552,552,552
BEGIN DESCRIPTION:
Caney Creek 50.0
END DESCRIPTION:
XS GIS Cut Line= 3
      2759790.80      6774001.91      2759526.00      6775661.00
      2758525.97      6777061.04
#Sta/Elev= 30
  3324.2  392.40  3579.1  389.58  3708.4  383.48  3758.7  378.95  3832.6  366.31
  3961.9  354.20  4072.6  348.54  4221.4  345.41  4372.4  342.41  4660.2  339.70
  4994.2  341.05  5032.6  339.51  5053.4  341.18  5090.3  339.85  5385.2  340.44
  5497.6  339.19  5500.6  338.29  5528.6  339.19  5560.7  340.28  5629.3  340.46
  5679.0  339.68  5714.6  340.71  5915.7  339.43  6388.0  340.94  6474.1  344.18
  6538.3  350.23  6574.8  354.28  6610.5  361.98  6689.5  369.15  6724.8  371.52
#Mann=11,-1,0
  3324.2    0.12       0  4221.4     0.1       0  4372.4    0.12       0
  5497.6    0.07       0  5528.6    0.12       0  5560.7    0.05       0
  5629.3    0.12       0  5679.0     0.1       0  5915.7    0.12       0
  6538.3    0.05       0  6689.5     0.1       0
Bank Sta=5497.6,5528.6
Exp/Cntr=0.3,0.1

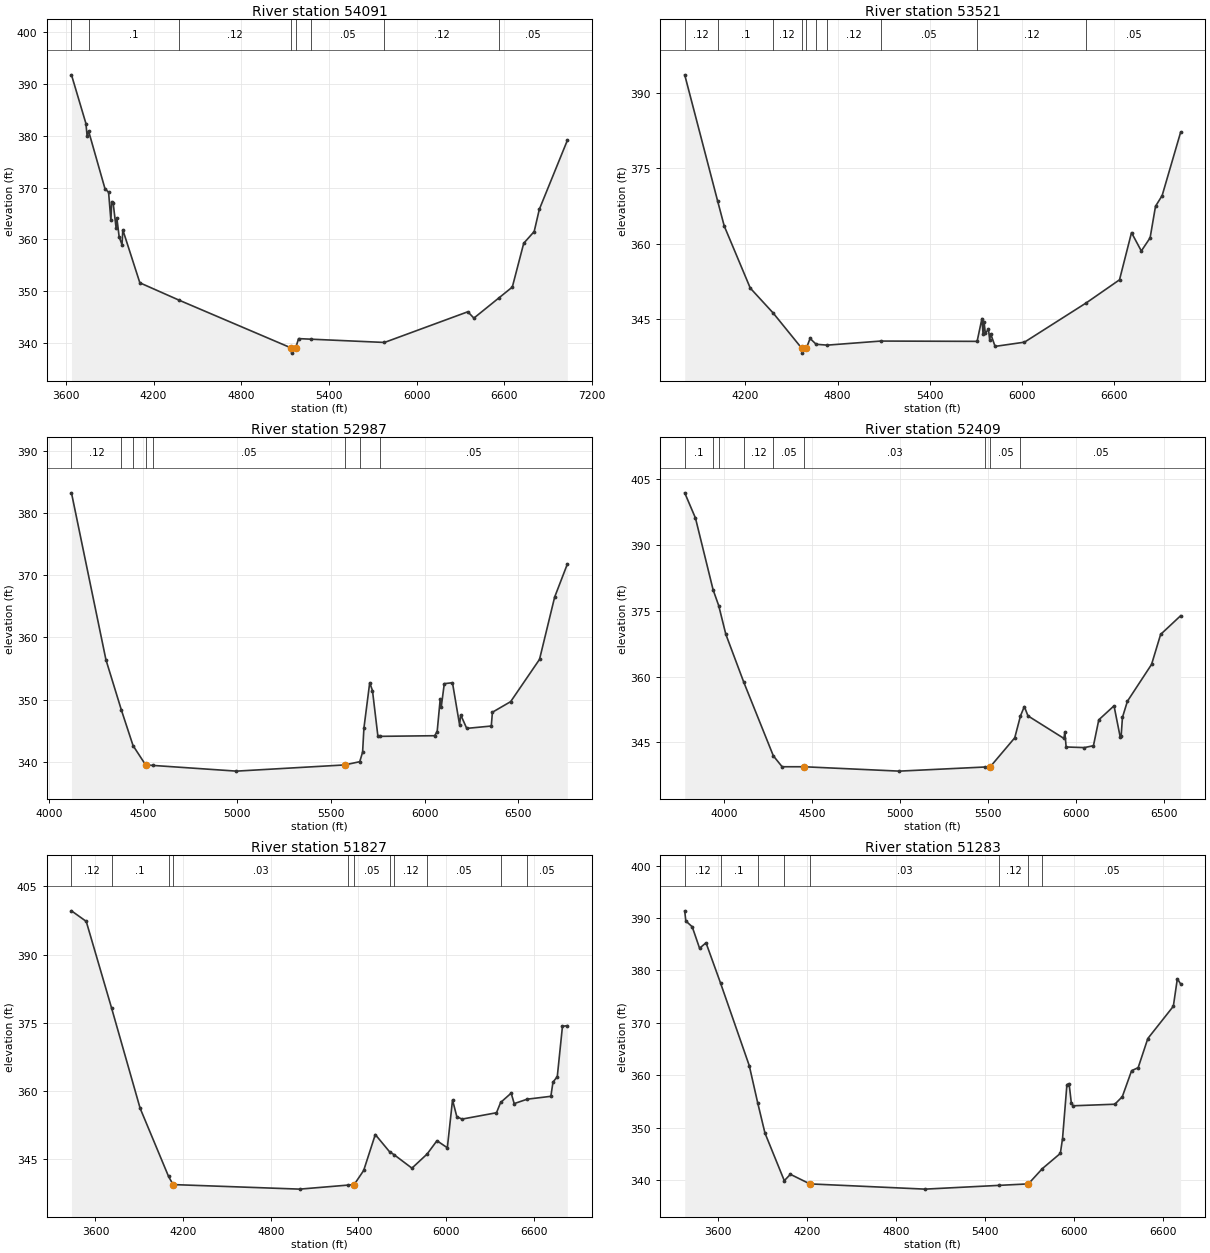
Type RM Length L Ch R = 1,54091,570,570,570
BEGIN DESCRIPTION:
Caney Creek 49.0
END DESCRIPTION:
XS GIS Cut Line= 3
      2759468.57      6774085.06      2759126.00      6775411.00
      2757825.98      6776961.02
#Sta/Elev= 30
  3638.7  391.75  3737.8  382.34  3745.9  379.88  3755.8  380.90  3867.9  369.78
  3892.7  369.08  3908.5  363.65  3913.7  367.27  3923.7  367.07  3944.0  362.21
  3949.2  364.11  3965.0  360.47  3984.6  358.95  3989.8  361.85  4106.6  351.61
  4376.6  348.24  5141.6  339.04  5144.6  338.04  5172.6  339.04  5192.3  340.84
  5278.5  340.73  5779.8  340.10  6350.1  346.02  6391.8  344.80  6563.0  348.70
  6654.6  350.79  6732.6  359.24  6804.2  361.51  6839.3  365.79  7031.2  379.11
#Mann=8,-1,0
  3638.7    0.12       0  3755.8     0.1       0  4376.6    0.12       0
  5141.6    0.07       0  5172.6    0.12       0  5278.5    0.05       0
  5779.8    0.12       0  6563.0    0.05       0
Bank Sta=5141.6,5172.6
Exp/Cntr=0.3,0.1

Type RM Length L Ch R = 1,53521,534,534,534
BEGIN DESCRIPTION:
Caney Creek 48.0
END DESCRIPTION:
XS GIS Cut Line= 3
      2759126.01      6774210.97      2758776.00      6775361.00
      2757476.00      6776910.99
#Sta/Elev= 30
  3805.6  393.57  4020.2  368.42  4062.5  363.52  4232.0  351.16  4380.5  346.22
  4565.9  339.23  4568.9  338.23  4596.9  339.23  4621.0  341.15  4660.3  339.99
  4732.6  339.82  5080.7  340.63  5707.3  340.57  5738.6  345.11  5746.0  342.03
  5752.5  344.43  5760.3  342.24  5781.1  342.93  5788.9  340.90  5795.5  342.05
  5824.1  339.57  6015.3  340.41  6417.9  348.24  6633.3  352.81  6711.3  362.19
  6775.1  358.54  6832.3  361.16  6867.4  367.43  6910.4  369.55  7030.7  382.15
#Mann=10,-1,0
  3805.6    0.12       0  4020.2     0.1       0  4380.5    0.12       0
  4565.9    0.07       0  4596.9    0.12       0  4660.3    0.05       0
  4732.6    0.12       0  5080.7    0.05       0  5707.3    0.12       0
  6417.9    0.05       0
Bank Sta=4565.9,4596.9
Exp/Cntr=0.3,0.1

Type RM Length L Ch R = 1,52987,578,578,578
BEGIN DESCRIPTION:
Caney Creek 47.0
END DESCRIPTION:
XS GIS Cut Line= 3
      2758676.00      6774410.99      2758326.00      6775211.00
      2757475.99      6776761.01
#Sta/Elev= 30
  4119.3  383.28  4302.9  356.41  4384.7  348.36  4447.3  342.59  4514.3  339.48
  4552.6  339.40  4998.0  338.48  5575.1  339.48  5654.6  340.00  5669.8  341.54
  5676.8  345.40  5707.7  352.72  5722.4  351.44  5751.3  344.09  5764.9  344.08
  6053.2  344.18  6066.9  344.84  6083.0  350.05  6088.7  348.81  6104.8  352.56
  6148.4  352.71  6186.3  345.93  6192.1  347.55  6224.3  345.36  6355.1  345.74
  6361.1  347.96  6458.4  349.67  6612.0  356.47  6692.5  366.49  6760.3  371.82
#Mann=8,-1,0
  4119.3    0.12       0  4384.7     0.1       0  4447.3    0.12       0
  4514.3    0.03       0  4552.6    0.05       0  5575.1    0.12       0
  5654.6    0.12       0  5764.9    0.05       0
Bank Sta=4514.3,5575.1
Exp/Cntr=0.3,0.1

Type RM Length L Ch R = 1,52409,582,582,582
BEGIN DESCRIPTION:
Caney Creek 46.0
END DESCRIPTION:
XS GIS Cut Line= 3
      2758515.19      6774243.65      2757776.00      6775211.00
      2757376.01      6776760.98
#Sta/Elev= 30
  3778.3  401.92  3839.4  396.16  3939.5  379.81  3971.6  376.17  4011.8  369.66
  4113.8  358.72  4282.0  341.90  4331.9  339.41  4455.7  339.41  4998.0  338.41
  5485.5  339.35  5514.7  339.41  5653.8  346.01  5686.5  351.02  5708.3  353.15
  5729.0  351.02  5933.3  345.87  5938.5  347.38  5945.9  343.92  6049.2  343.78
  6101.1  344.21  6131.5  350.12  6218.0  353.31  6253.5  346.12  6258.6  346.48
  6266.0  350.68  6294.1  354.36  6431.3  362.76  6482.9  369.61  6596.5  373.87
#Mann=9,-1,0
  3778.3     0.1       0  3939.5    0.12       0  3971.6     0.1       0
  4113.8    0.12       0  4282.0    0.05       0  4455.7    0.03       0
  5485.5    0.12       0  5514.7    0.05       0  5686.5    0.05       0
Bank Sta=4455.7,5514.7
Exp/Cntr=0.3,0.1

Type RM Length L Ch R = 1,51827,544,544,544
BEGIN DESCRIPTION:
Caney Creek 45.0
END DESCRIPTION:
XS GIS Cut Line= 3
      2758217.85      6773901.24      2757226.00      6775111.00
      2756143.69      6776586.54
#Sta/Elev= 30
  3435.6  399.60  3536.7  397.28  3709.9  378.27  3905.5  356.21  4100.3  341.21
  4131.2  339.43  4998.0  338.43  5329.3  339.32  5370.5  339.43  5435.7  342.53
  5515.2  350.43  5612.7  346.65  5642.8  346.02  5766.0  343.04  5869.8  346.14
  5937.3  349.07  6008.3  347.52  6043.9  358.02  6073.2  354.36  6108.7  353.82
  6344.8  355.22  6373.2  357.48  6445.2  359.53  6466.0  357.23  6555.0  358.20
  6716.9  358.83  6731.5  361.96  6760.8  363.14  6796.3  374.22  6829.9  374.36
#Mann=11,-1,0
  3435.6    0.12       0  3709.9     0.1       0  4100.3    0.05       0
  4131.2    0.03       0  5329.3    0.12       0  5370.5    0.05       0
  5612.7    0.05       0  5642.8    0.12       0  5869.8    0.05       0
  6373.2    0.12       0  6555.0    0.05       0
Bank Sta=4131.2,5370.5
Exp/Cntr=0.3,0.1

Type RM Length L Ch R = 1,51283,1799,1799,1799
BEGIN DESCRIPTION:
Caney Creek 44.0
END DESCRIPTION:
XS GIS Cut Line= 3
      2758049.76      6773853.81      2756776.00      6774861.00
      2755776.01      6776260.99
#Sta/Elev= 30
  3376.8  391.38  3384.1  389.45  3427.5  388.33  3477.1  384.23  3520.4  385.28
  3618.5  377.58  3812.2  361.82  3868.8  354.75  3917.9  348.96  4048.4  339.86
  4089.4  341.08  4220.7  339.25  4998.0  338.25  5498.0  338.97  5694.4  339.25
  5788.8  342.17  5910.0  345.07  5924.8  347.91  5954.3  358.19  5969.0  358.40
  5983.8  354.73  5996.1  354.16  6277.5  354.46  6327.9  355.90  6390.5  360.86
  6434.8  361.44  6499.9  367.00  6672.0  373.16  6699.0  378.41  6721.1  377.43
#Mann=8,-1,0
  3376.8    0.12       0  3618.5     0.1       0  3868.8    0.12       0
  4048.4    0.05       0  4220.7    0.03       0  5498.0    0.12       0
  5694.4    0.12       0  5788.8    0.05       0
Bank Sta=4220.7,5694.4
Exp/Cntr=0.3,0.1

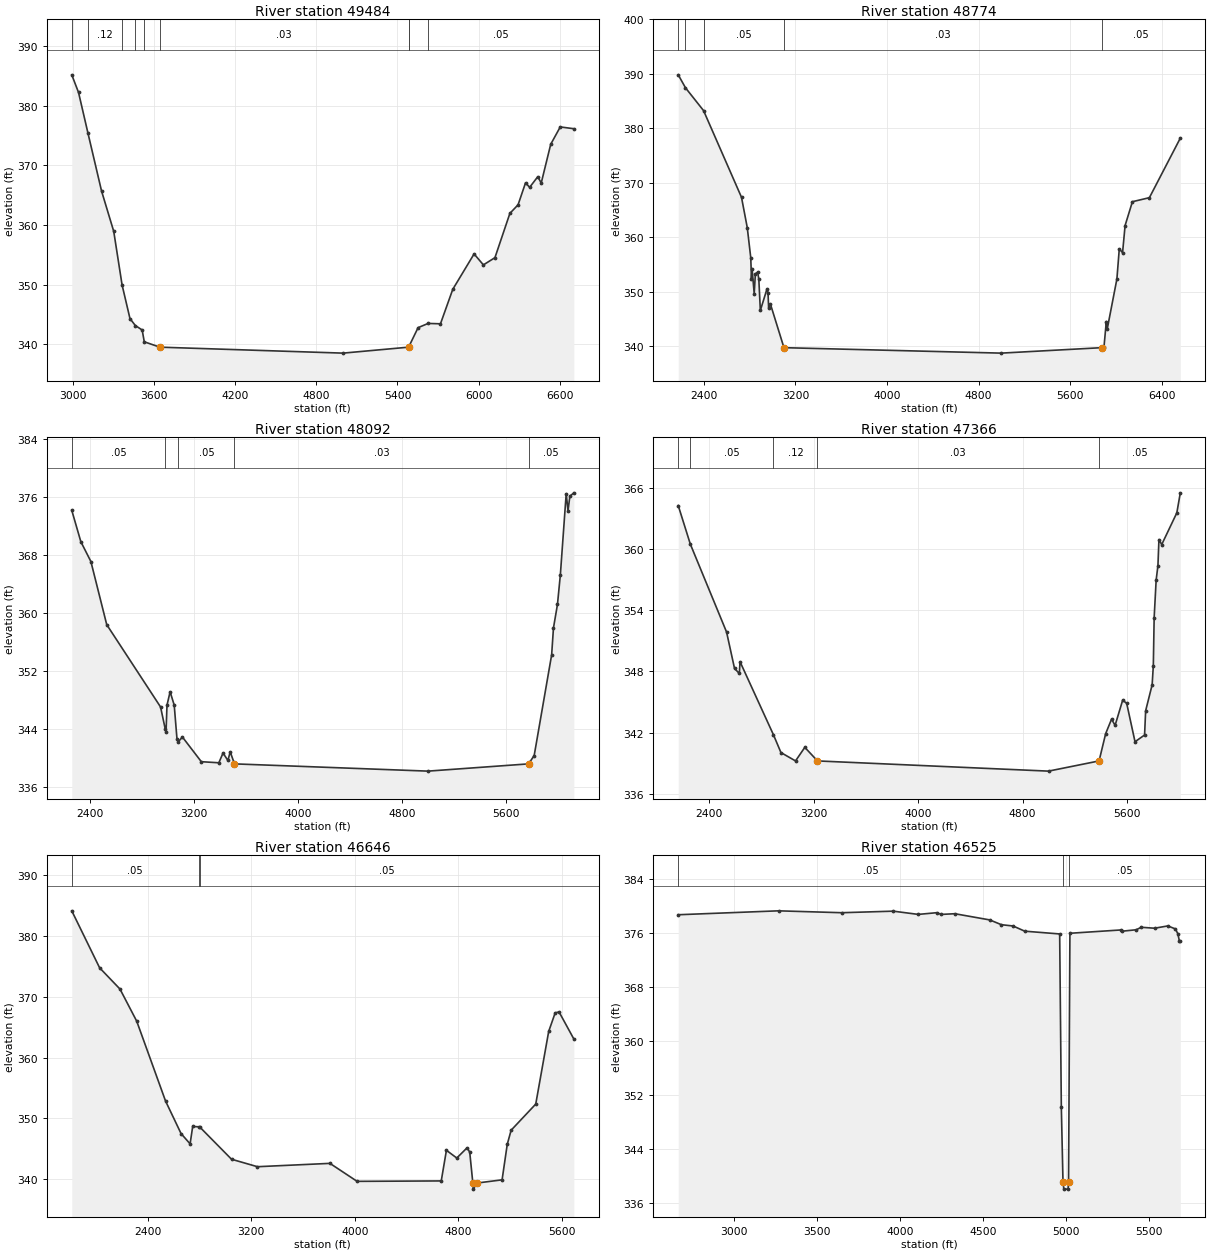
Type RM Length L Ch R = 1,49484,710,710,710
BEGIN DESCRIPTION:
Caney Creek 43.0
END DESCRIPTION:
XS GIS Cut Line= 3
      2755126.00      6772510.95      2755126.00      6774511.00
      2755725.98      6776110.95
#Sta/Elev= 30
  2994.0  385.17  3044.0  382.21  3114.1  375.34  3214.0  365.68  3304.0  358.91
  3365.7  349.92  3424.0  344.28  3463.6  343.12  3514.0  342.37  3529.6  340.39
  3644.8  339.49  4998.0  338.49  5481.9  339.49  5487.0  339.71  5552.1  342.76
  5626.2  343.47  5717.6  343.41  5808.4  349.19  5965.9  355.13  6034.5  353.29
  6119.9  354.50  6230.3  361.93  6290.8  363.37  6346.0  367.06  6376.2  366.30
  6436.7  368.09  6461.7  367.01  6532.0  373.52  6602.3  376.43  6702.8  376.13
#Mann=9,-1,0
  2994.0     0.1       0  3114.1    0.12       0  3365.7    0.05       0
  3463.6    0.12       0  3529.6    0.05       0  3644.8    0.03       0
  5481.9    0.05       0  5487.0    0.12       0  5626.2    0.05       0
Bank Sta=3644.8,5481.9
Exp/Cntr=0.3,0.1

Type RM Length L Ch R = 1,48774,682,682,682
BEGIN DESCRIPTION:
Caney Creek 42.0
END DESCRIPTION:
XS GIS Cut Line= 3
      2754244.32      6772113.46      2754626.00      6774911.00
      2755626.00      6776111.00
#Sta/Elev= 30
  2176.3  389.81  2239.7  387.43  2397.4  383.25  2728.9  367.35  2779.4  361.77
  2809.7  356.27  2816.1  352.45  2821.2  354.26  2839.9  349.69  2850.0  353.29
  2870.2  353.64  2880.3  352.29  2893.5  346.59  2950.9  350.50  2960.7  349.85
  2965.8  347.05  2981.2  347.79  3099.7  339.77  4998.0  338.77  5874.7  339.77
  5894.7  339.81  5915.5  344.57  5923.3  343.17  6007.9  352.37  6028.8  357.91
  6057.4  357.19  6079.5  362.17  6143.3  366.54  6291.7  367.28  6561.8  378.20
#Mann=5,-1,0
  2176.3    0.05       0  2239.7    0.12       0  2397.4    0.05       0
  3099.7    0.03       0  5874.7    0.05       0
Bank Sta=3099.7,5874.7
Exp/Cntr=0.3,0.1

Type RM Length L Ch R = 1,48092,726,726,726
BEGIN DESCRIPTION:
Caney Creek 41.0
END DESCRIPTION:
XS GIS Cut Line= 3
      2753299.59      6772750.91      2754126.00      6775361.00
      2754625.99      6776360.98
#Sta/Elev= 30
  2262.2  374.19  2331.8  369.87  2409.1  367.13  2530.8  358.43  2944.1  347.09
  2979.9  344.06  2986.1  343.59  2993.5  347.34  3017.5  349.19  3049.0  347.34
  3070.0  342.73  3080.2  342.29  3111.9  342.95  3257.1  339.55  3391.6  339.40
  3423.9  340.74  3461.4  339.72  3479.0  340.91  3511.7  339.25  4998.0  338.25
  5770.7  339.25  5813.4  340.40  5947.5  354.27  5961.5  357.98  5992.2  361.22
  6014.6  365.34  6059.3  376.49  6073.3  374.12  6087.3  376.13  6118.0  376.60
#Mann=5,-1,0
  2262.2    0.05       0  2979.9    0.12       0  3080.2    0.05       0
  3511.7    0.03       0  5770.7    0.05       0
Bank Sta=3511.7,5770.7
Exp/Cntr=0.3,0.1

Type RM Length L Ch R = 1,47366,720,720,720
BEGIN DESCRIPTION:
Caney Creek 40.0
END DESCRIPTION:
XS GIS Cut Line= 3
      2753090.74      6773016.46      2753576.00      6775811.00
      2754106.28      6776666.53
#Sta/Elev= 30
  2163.9  364.25  2256.5  360.47  2533.9  351.85  2594.8  348.28  2631.7  347.79
  2636.7  348.95  2892.4  341.79  2950.0  340.04  3061.7  339.22  3132.7  340.55
  3229.7  339.22  4998.0  338.22  5385.0  339.22  5435.6  341.90  5480.5  343.31
  5507.7  342.71  5565.5  345.17  5596.3  344.87  5660.1  341.10  5733.3  341.76
  5741.5  344.14  5791.2  346.68  5800.3  348.57  5806.6  353.26  5821.9  356.95
  5835.6  358.37  5843.2  360.92  5864.5  360.43  5980.2  363.54  6006.8  365.50
#Mann=5,-1,0
  2163.9    0.12       0  2256.5    0.05       0  2892.4    0.12       0
  3229.7    0.03       0  5385.0    0.05       0
Bank Sta=3229.7,5385
Exp/Cntr=0.3,0.1

Type RM Length L Ch R = 1,46646,121,121,121
BEGIN DESCRIPTION:
Mapping XS 031af86b
END DESCRIPTION:
XS GIS Cut Line= 3
      2752647.48      6773040.15      2752962.79      6773681.86
      2752986.29      6776845.28
#Sta/Elev= 30
  1813.3  384.17  2028.4  374.79  2185.8  371.29  2315.1  366.00  2537.4  352.88
  2657.4  347.51  2727.4  345.81  2747.4  348.67  2793.9  348.62  2802.2  348.58
  3047.4  343.28  3247.5  342.05  3807.5  342.60  4017.5  339.64  4667.5  339.71
  4707.5  344.75  4787.5  343.48  4867.5  345.17  4887.5  344.44  4911.6  339.36
  4914.8  338.36  4943.4  339.36  5137.5  339.89  5177.5  345.75  5207.5  348.06
  5397.5  352.36  5497.5  364.32  5547.5  367.37  5577.5  367.53  5691.8  363.07
#Mann=3,-1,0
  1813.3    0.05       0  2793.9    0.12       0  2802.2    0.05       0
Bank Sta=4911.6,4943.4
Exp/Cntr=0.3,0.1

Type RM Length L Ch R = 1,46525,162,162,162
BEGIN DESCRIPTION:
Caney Creek 39.0
END DESCRIPTION:
XS GIS Cut Line= 3
      2752736.21      6773828.30      2752860.95      6776161.06
      2752902.73      6776845.89
#Sta/Elev= 30
  2663.9  378.72  3267.5  379.30  3648.0  379.02  3958.5  379.25  4108.7  378.77
  4218.8  379.02  4247.9  378.77  4329.0  378.87  4539.3  377.95  4609.4  377.24
  4679.5  377.05  4749.6  376.28  4959.9  375.87  4969.9  350.17  4979.9  339.10
  4981.6  339.01  4984.7  338.01  5010.2  338.01  5013.4  339.01  5021.6  375.97
  5327.4  376.46  5332.4  376.27  5420.7  376.49  5450.8  376.86  5530.9  376.72
  5611.1  377.06  5656.9  376.61  5671.2  375.90  5681.1  374.75  5686.1  374.75
#Mann=3,-1,0
  2663.9    0.05       0  4981.6    0.05       0  5013.4    0.05       0
Bank Sta=4981.6,5013.4
Exp/Cntr=0.3,0.1