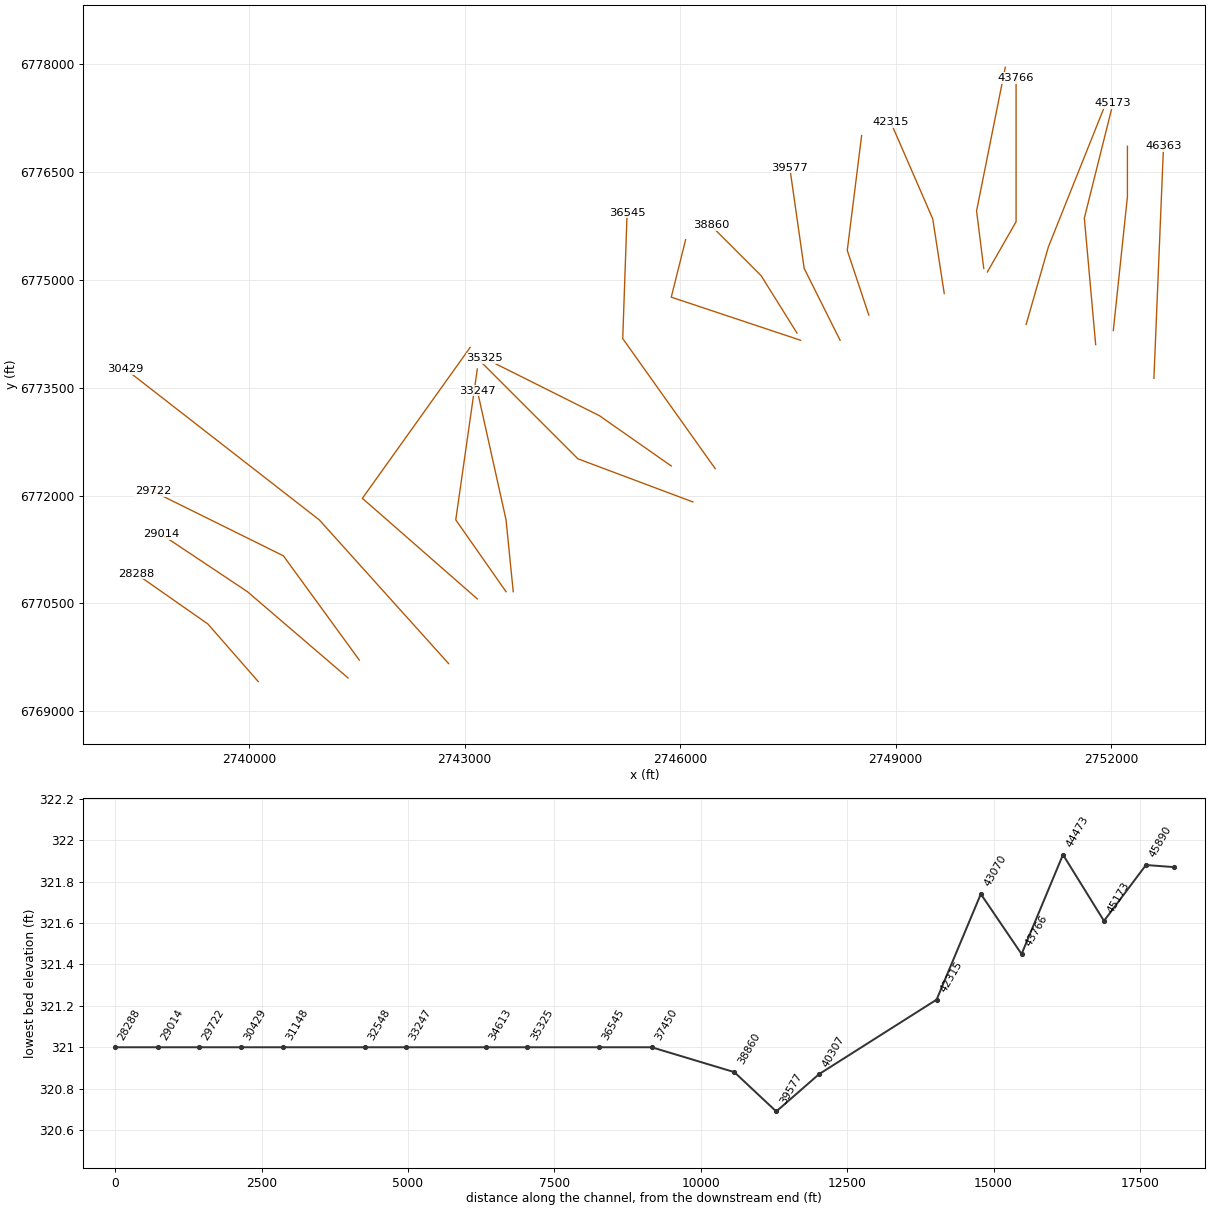
HEC-RAS study Caney Creek.prj: Caney Creek Base Level Engineering

--- Caney Creek.g01 (geometry) --- (continued)

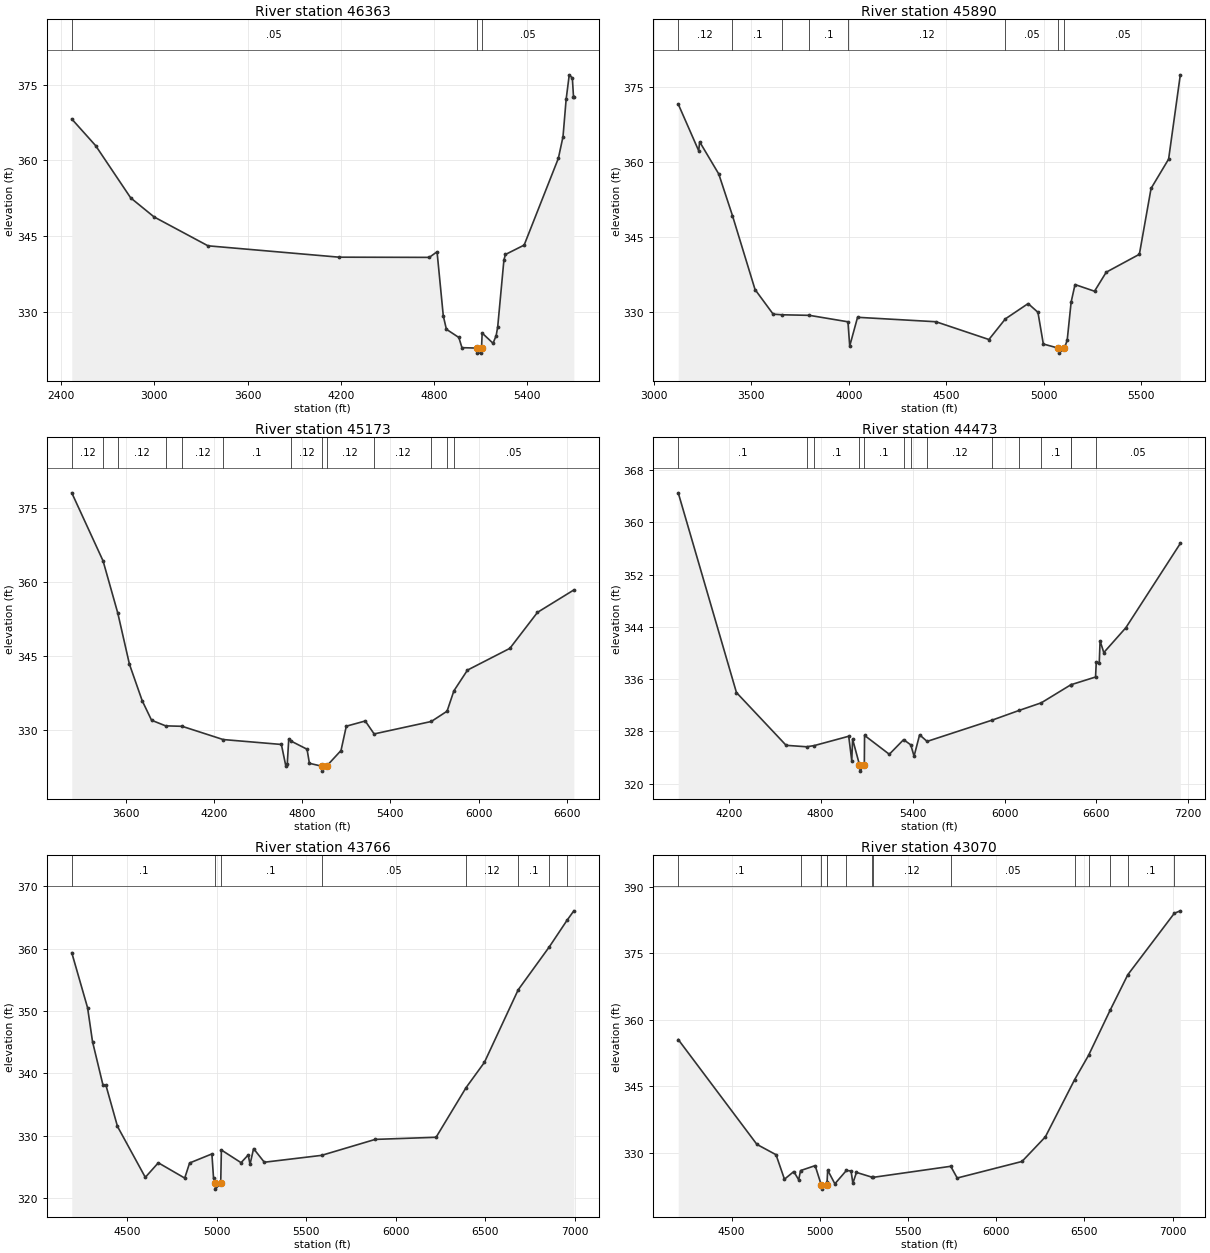
Type RM Length L Ch R = 1,46363,473,473,473
BEGIN DESCRIPTION:
Mapping XS f968f43d
END DESCRIPTION:
XS GIS Cut Line= 2
      2752594.66      6773631.88      2752728.31      6776860.61
#Sta/Elev= 30
  2468.7  368.21  2622.5  362.93  2848.1  352.59  2998.3  348.83  3345.5  343.11
  4189.3  340.86  4769.8  340.82  4819.8  341.93  4859.9  329.24  4879.9  326.59
  4960.0  324.97  4980.0  322.95  5074.2  322.87  5077.3  321.87  5102.8  321.87
  5106.0  322.87  5110.1  325.84  5180.1  323.82  5200.2  325.33  5210.2  327.09
  5250.2  340.33  5260.2  341.40  5380.3  343.25  5600.5  360.42  5630.5  364.72
  5650.5  372.07  5670.6  376.95  5690.6  376.32  5697.9  372.66  5700.2  372.66
#Mann=3,-1,0
  2468.7    0.05       0  5074.2    0.03       0  5106.0    0.05       0
Bank Sta=5074.2,5106
Exp/Cntr=0.3,0.1

Type RM Length L Ch R = 1,45890,717,717,717
BEGIN DESCRIPTION:
Caney Creek 38.0
END DESCRIPTION:
XS GIS Cut Line= 3
      2752029.51      6774296.33      2752226.00      6776161.00
      2752226.00      6776861.01
#Sta/Elev= 30
  3125.0  371.64  3229.9  362.32  3234.9  364.10  3332.9  357.67  3403.0  349.37
  3518.9  334.59  3611.8  329.67  3657.9  329.54  3797.9  329.43  3995.4  328.14
  4004.5  323.31  4044.7  329.04  4446.9  328.15  4718.4  324.60  4803.0  328.73
  4919.5  331.78  4969.8  330.04  4997.5  323.70  5074.1  322.88  5077.2  321.88
  5105.9  322.88  5120.0  324.50  5140.0  332.07  5160.0  335.58  5260.0  334.25
  5320.0  338.05  5490.0  341.63  5550.0  354.79  5640.0  360.65  5700.0  377.49
#Mann=8,-1,0
  3125.0    0.12       0  3403.0     0.1       0  3657.9    0.05       0
  3797.9     0.1       0  3995.4    0.12       0  4803.0    0.05       0
  5074.1    0.03       0  5105.9    0.05       0
Bank Sta=5074.1,5105.9
Exp/Cntr=0.3,0.1

Type RM Length L Ch R = 1,45173,700,700,700
BEGIN DESCRIPTION:
Caney Creek 37.0
END DESCRIPTION:
XS GIS Cut Line= 3
      2751783.99      6774099.94      2751626.00      6775861.00
      2752026.01      6777461.03
#Sta/Elev= 30
  3231.4  378.17  3444.5  364.33  3544.8  353.71  3624.0  343.33  3710.9  335.91
  3774.6  331.95  3870.4  330.81  3982.5  330.72  4261.7  328.03  4658.2  327.03
  4688.3  322.66  4698.3  323.10  4708.4  328.18  4724.4  327.71  4832.8  326.06
  4848.9  323.20  4933.4  322.61  4936.6  321.61  4965.3  322.61  5064.0  325.80
  5100.0  330.74  5228.9  331.80  5289.5  329.17  5678.6  331.70  5785.9  333.79
  5832.2  337.92  5924.7  342.14  6213.3  346.56  6401.4  353.88  6648.8  358.43
#Mann=13,-1,0
  3231.4    0.12       0  3444.5     0.1       0  3544.8    0.12       0
  3870.4    0.05       0  3982.5    0.12       0  4261.7     0.1       0
  4724.4    0.12       0  4933.4    0.05       0  4965.3    0.12       0
  5289.5    0.12       0  5678.6     0.1       0  5785.9    0.12       0
  5832.2    0.05       0
Bank Sta=4933.4,4965.3
Exp/Cntr=0.3,0.1

Type RM Length L Ch R = 1,44473,707,707,707
BEGIN DESCRIPTION:
Caney Creek 36.0
END DESCRIPTION:
XS GIS Cut Line= 3
      2750815.91      6774381.38      2751126.00      6775461.00
      2751925.99      6777460.97
#Sta/Elev= 30
  3870.3  364.54  4250.3  333.96  4574.6  325.88  4708.4  325.66  4758.1  325.84
  4983.2  327.27  5003.0  323.51  5008.4  326.83  5053.0  322.93  5056.2  321.93
  5085.0  322.93  5086.5  327.40  5248.0  324.51  5341.5  326.75  5388.2  325.95
  5409.6  324.22  5445.9  327.49  5494.7  326.48  5920.7  329.75  6096.1  331.23
  6240.2  332.39  6432.3  335.14  6433.0  335.15  6594.3  336.34  6599.1  338.62
  6618.5  338.51  6623.9  341.87  6648.2  340.08  6792.2  343.89  7147.6  356.79
#Mann=14,-1,0
  3870.3     0.1       0  4708.4    0.12       0  4758.1     0.1       0
  5053.0    0.07       0  5085.0     0.1       0  5341.5    0.12       0
  5388.2     0.1       0  5494.7    0.12       0  5920.7     0.1       0
  6096.1    0.12       0  6240.2     0.1       0  6432.3    0.12       0
  6433.0     0.1       0  6599.1    0.05       0
Bank Sta=5053,5085
Exp/Cntr=0.3,0.1

Type RM Length L Ch R = 1,43766,696,696,696
BEGIN DESCRIPTION:
Caney Creek 35.0
END DESCRIPTION:
XS GIS Cut Line= 3
      2750276.00      6775111.01      2750676.00      6775811.00
      2750676.00      6777810.98
#Sta/Elev= 30
  4189.3  359.34  4277.8  350.50  4305.2  345.10  4364.2  338.07  4380.0  338.12
  4444.8  331.50  4600.3  323.34  4673.0  325.67  4820.6  323.22  4847.9  325.64
  4972.5  327.09  4981.8  323.16  4989.2  322.45  4992.6  321.45  5021.8  322.45
  5025.5  327.72  5135.5  325.69  5175.5  326.93  5185.5  325.42  5205.5  327.94
  5265.5  325.76  5585.4  326.86  5885.5  329.42  6225.5  329.76  6393.2  337.72
  6495.5  341.76  6684.4  353.39  6858.7  360.29  6956.6  364.50  6995.5  366.05
#Mann=8,-1,0
  4189.3     0.1       0  4989.2    0.07       0  5021.8     0.1       0
  5585.4    0.05       0  6393.2    0.12       0  6684.4     0.1       0
  6858.7    0.12       0  6956.6     0.1       0
Bank Sta=4989.2,5021.8
Exp/Cntr=0.3,0.1

Type RM Length L Ch R = 1,43070,755,755,755
BEGIN DESCRIPTION:
Caney Creek 34.0
END DESCRIPTION:
XS GIS Cut Line= 3
      2750226.00      6775161.04      2750126.00      6775961.00
      2750526.00      6777961.01
#Sta/Elev= 30
  4198.1  355.55  4644.0  331.85  4752.3  329.52  4800.2  323.98  4853.1  325.71
  4880.8  323.84  4891.5  325.93  4974.1  327.05  5008.4  322.74  5011.7  321.74
  5041.0  322.74  5041.7  323.30  5045.1  326.04  5085.9  322.94  5151.1  325.95
  5177.7  325.85  5187.9  323.06  5208.2  325.52  5295.3  324.45  5302.3  324.40
  5742.7  326.90  5779.3  324.25  6146.5  327.99  6279.0  333.55  6445.2  346.51
  6523.6  351.96  6645.9  362.15  6746.3  370.19  7009.9  384.07  7043.9  384.63
#Mann=14,-1,0
  4198.1     0.1       0  4891.5    0.12       0  5008.4    0.07       0
  5041.0    0.12       0  5041.7     0.1       0  5151.1    0.12       0
  5295.3     0.1       0  5302.3    0.12       0  5742.7    0.05       0
  6445.2    0.12       0  6523.6    0.05       0  6645.9    0.12       0
  6746.3     0.1       0  7009.9    0.05       0
Bank Sta=5008.4,5041
Exp/Cntr=0.3,0.1

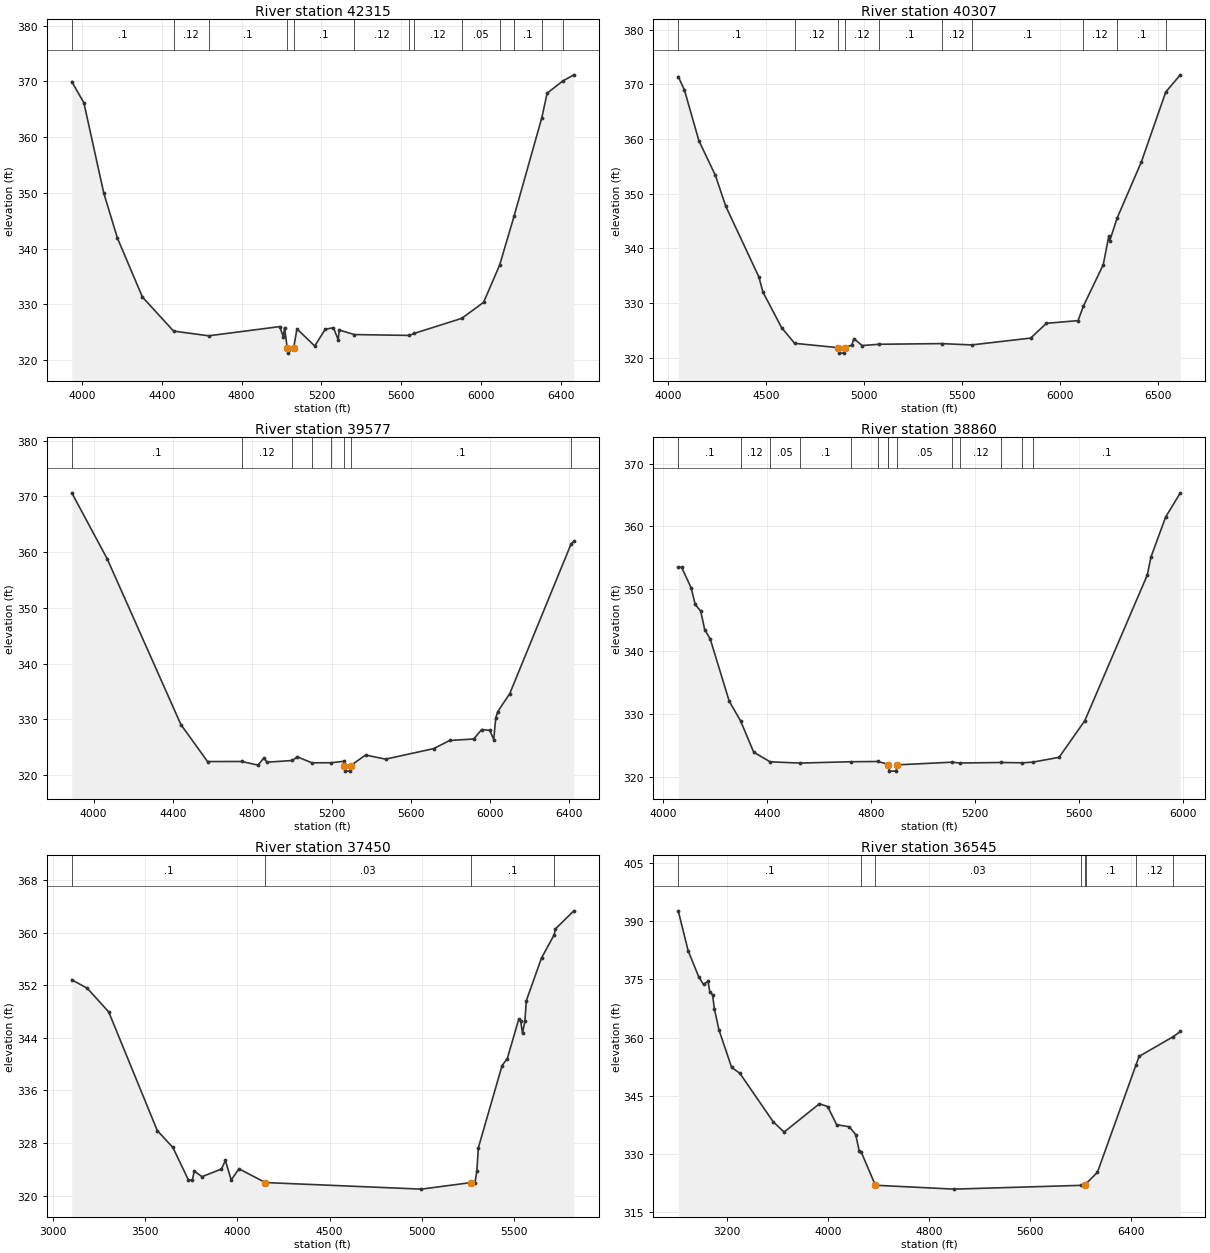
Type RM Length L Ch R = 1,42315,2008,2008,2008
BEGIN DESCRIPTION:
Caney Creek 33.0
END DESCRIPTION:
XS GIS Cut Line= 3
      2749676.00      6774810.99      2749516.00      6775850.04
      2748931.79      6777193.73
#Sta/Elev= 30
  3948.7  369.97  4009.4  366.16  4109.3  349.93  4177.5  341.88  4302.8  331.30
  4458.9  325.19  4634.7  324.34  4990.9  325.99  5009.5  324.10  5015.0  325.81
  5028.4  322.23  5031.7  321.23  5061.0  322.23  5077.4  325.58  5166.5  322.51
  5219.1  325.51  5260.3  325.80  5283.8  323.65  5289.2  325.39  5364.8  324.56
  5640.7  324.41  5666.4  324.79  5903.2  327.47  6012.7  330.34  6093.3  337.04
  6165.8  345.84  6304.7  363.49  6331.4  367.89  6410.4  370.09  6465.2  371.18
#Mann=13,-1,0
  3948.7     0.1       0  4458.9    0.12       0  4634.7     0.1       0
  5028.4    0.07       0  5061.0     0.1       0  5364.8    0.12       0
  5640.7    0.05       0  5666.4    0.12       0  5903.2    0.05       0
  6093.3    0.12       0  6165.8     0.1       0  6304.7    0.12       0
  6410.4    0.05       0
Bank Sta=5028.4,5061
Exp/Cntr=0.3,0.1

Type RM Length L Ch R = 1,40307,730,730,730
BEGIN DESCRIPTION:
Caney Creek 32.0
END DESCRIPTION:
XS GIS Cut Line= 3
      2748625.99      6774511.04      2748326.00      6775411.00
      2748526.00      6777011.01
#Sta/Elev= 30
  4050.8  371.40  4082.4  368.96  4156.2  359.69  4240.5  353.34  4293.2  347.72
  4461.9  334.82  4482.9  332.03  4577.8  325.54  4644.6  322.66  4867.1  321.87
  4870.5  320.87  4896.5  320.87  4899.9  321.87  4936.2  322.35  4946.7  323.52
  4988.9  322.25  5073.3  322.49  5393.9  322.61  5547.5  322.37  5848.5  323.62
  5929.1  326.32  6090.4  326.81  6117.8  329.49  6218.9  337.04  6246.6  342.19
  6251.6  341.36  6289.4  345.54  6412.9  355.79  6537.5  368.58  6611.9  371.73
#Mann=10,-1,0
  4050.8     0.1       0  4644.6    0.12       0  4867.1    0.07       0
  4899.9    0.12       0  5073.3     0.1       0  5393.9    0.12       0
  5547.5     0.1       0  6117.8    0.12       0  6289.4     0.1       0
  6537.5    0.05       0
Bank Sta=4867.1,4899.9
Exp/Cntr=0.3,0.1

Type RM Length L Ch R = 1,39577,717,717,717
BEGIN DESCRIPTION:
Caney Creek 31.0
END DESCRIPTION:
XS GIS Cut Line= 3
      2748226.00      6774160.99      2747726.00      6775161.00
      2747525.99      6776561.04
#Sta/Elev= 30
  3889.7  370.64  4068.6  358.78  4440.3  329.04  4574.5  322.41  4746.5  322.42
  4828.9  321.77  4859.6  323.08  4873.6  322.29  5001.5  322.60  5027.9  323.25
  5100.7  322.18  5199.3  322.20  5260.3  322.45  5264.1  321.69  5267.5  320.69
  5293.5  320.69  5296.9  321.69  5371.4  323.58  5472.4  322.84  5714.9  324.73
  5795.7  326.19  5916.9  326.46  5957.3  328.16  5997.7  328.01  6017.9  326.36
  6028.0  330.17  6038.1  331.37  6098.7  334.60  6408.6  361.51  6422.0  361.92
#Mann=8,-1,0
  3889.7     0.1       0  4746.5    0.12       0  5001.5    0.05       0
  5100.7    0.12       0  5199.3     0.1       0  5264.1    0.07       0
  5296.9     0.1       0  6408.6    0.12       0
Bank Sta=5264.1,5296.9
Exp/Cntr=0.3,0.1

Type RM Length L Ch R = 1,38860,1410,1410,1410
BEGIN DESCRIPTION:
Caney Creek 30.0
END DESCRIPTION:
XS GIS Cut Line= 3
      2747625.98      6774261.03      2747126.00      6775061.00
      2746426.01      6775760.99
#Sta/Elev= 30
  4057.6  353.49  4071.1  353.42  4107.7  350.12  4123.0  347.51  4144.2  346.44
  4159.6  343.48  4180.8  342.00  4253.9  332.06  4297.4  328.93  4348.2  323.91
  4411.2  322.37  4525.0  322.17  4722.4  322.38  4826.1  322.42  4866.4  321.97
  4867.0  321.88  4870.5  320.88  4896.7  320.88  4900.2  321.88  5111.6  322.31
  5142.3  322.18  5301.9  322.26  5382.2  322.21  5423.2  322.32  5524.2  323.09
  5623.2  328.95  5863.6  352.20  5877.8  355.08  5934.3  361.47  5990.9  365.35
#Mann=14,-1,0
  4057.6     0.1       0  4297.4    0.12       0  4411.2    0.05       0
  4525.0     0.1       0  4722.4    0.05       0  4826.1     0.1       0
  4866.4    0.05       0  4867.0    0.03       0  4900.2    0.05       0
  5111.6     0.1       0  5142.3    0.12       0  5301.9    0.05       0
  5382.2    0.12       0  5423.2     0.1       0
Bank Sta=4867,4900.2
Exp/Cntr=0.3,0.1

Type RM Length L Ch R = 1,37450,905,905,905
BEGIN DESCRIPTION:
Caney Creek 29.0
END DESCRIPTION:
XS GIS Cut Line= 3
      2747676.03      6774160.99      2745876.00      6774761.00
      2746076.00      6775560.98
#Sta/Elev= 30
  3102.5  352.83  3186.9  351.53  3302.8  347.94  3566.3  329.89  3650.7  327.33
  3735.0  322.39  3756.1  322.36  3766.6  323.74  3808.8  322.89  3914.2  324.06
  3935.3  325.36  3966.9  322.40  4009.0  324.09  4152.0  322.00  4998.0  321.00
  5267.8  322.00  5288.5  322.00  5298.8  323.76  5306.6  327.27  5435.4  339.79
  5463.7  340.85  5525.6  346.81  5535.9  346.58  5546.2  344.71  5559.1  346.56
  5566.8  349.65  5649.3  356.15  5718.3  359.69  5724.0  360.55  5824.5  363.31
#Mann=4,-1,0
  3102.5     0.1       0  4152.0    0.03       0  5267.8     0.1       0
  5718.3    0.12       0
Bank Sta=4152,5267.8
Exp/Cntr=0.3,0.1

Type RM Length L Ch R = 1,36545,1220,1220,1220
BEGIN DESCRIPTION:
Mapping XS acfb58e4
END DESCRIPTION:
XS GIS Cut Line= 3
      2746487.63      6772373.77      2745200.28      6774184.31
      2745261.41      6775936.98
#Sta/Elev= 30
  2813.6  392.59  2892.0  382.33  2978.1  375.45  3013.8  373.65  3049.4  374.49
  3064.2  371.67  3085.1  371.03  3099.8  367.38  3135.5  362.03  3236.4  352.31
  3301.0  350.82  3566.0  338.31  3652.0  335.68  3931.2  342.95  3996.4  342.25
  4067.7  337.58  4168.6  337.04  4219.0  335.01  4246.0  330.91  4262.5  330.55
  4374.2  322.00  4998.0  321.00  5999.9  321.97  6030.3  322.00  6045.5  322.49
  6132.5  325.32  6437.9  352.92  6462.7  355.15  6732.1  360.21  6788.9  361.55
#Mann=8,-1,0
  2813.6     0.1       0  4262.5    0.05       0  4374.2    0.03       0
  5999.9    0.12       0  6030.3    0.05       0  6045.5     0.1       0
  6437.9    0.12       0  6732.1    0.05       0
Bank Sta=4374.2,6030.3
Exp/Cntr=0.3,0.1

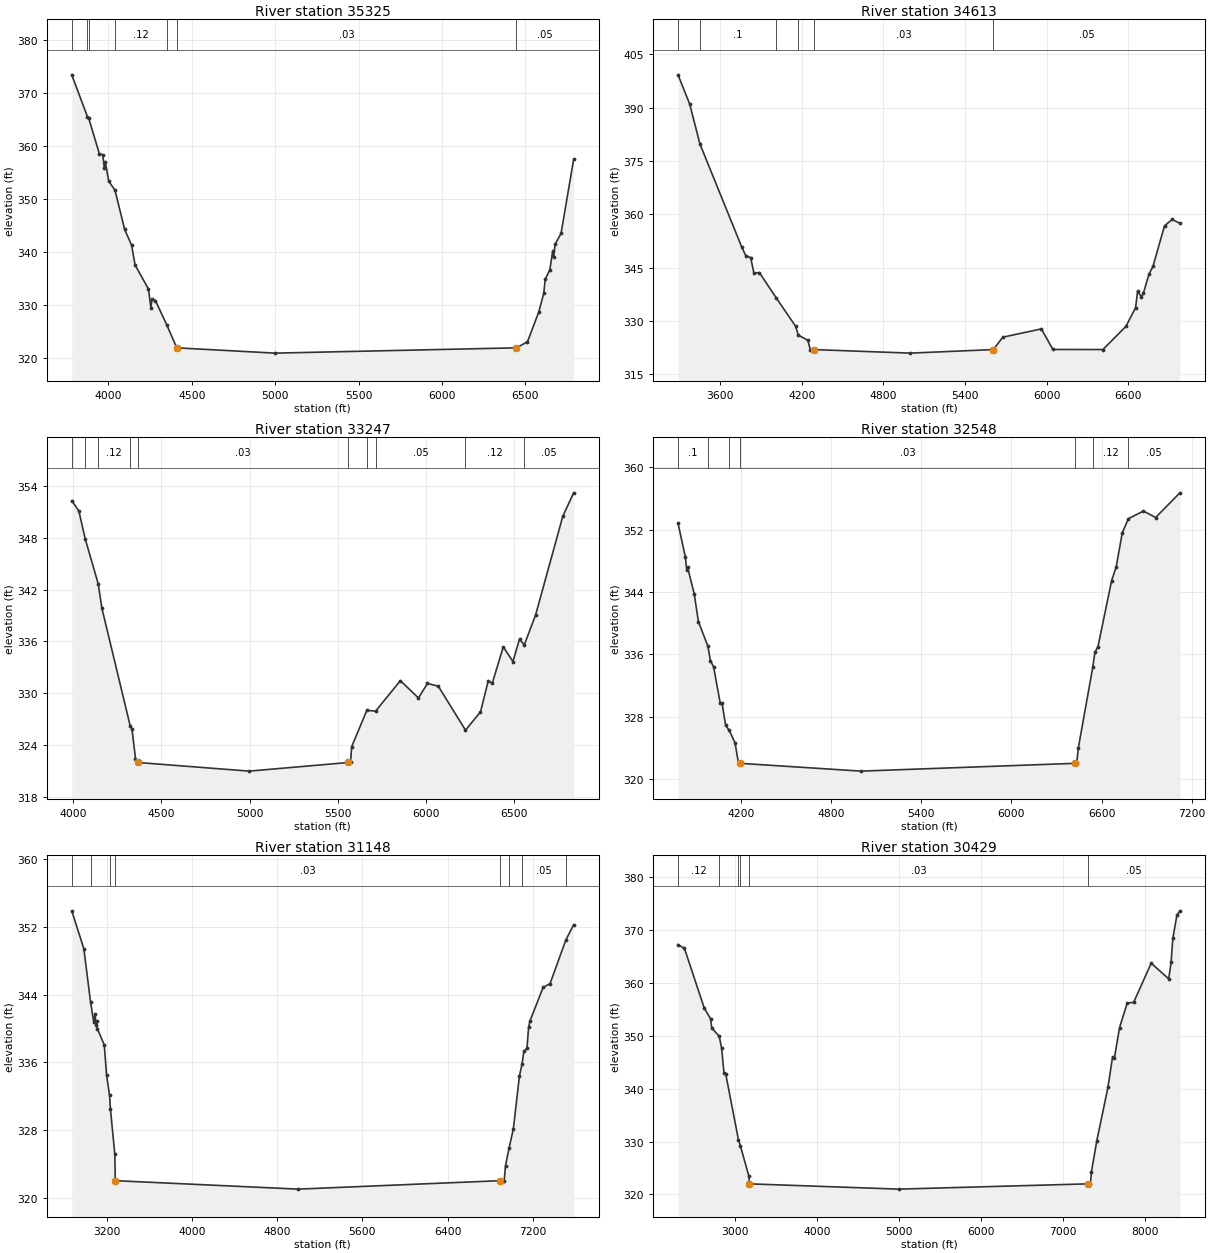
Type RM Length L Ch R = 1,35325,712,712,712
BEGIN DESCRIPTION:
Caney Creek 28.0
END DESCRIPTION:
XS GIS Cut Line= 3
      2745875.96      6772411.03      2744876.00      6773111.00
      2743275.96      6773911.02
#Sta/Elev= 30
  3779.8  373.52  3873.9  365.62  3881.8  365.29  3945.0  358.66  3965.9  358.43
  3974.6  356.02  3980.7  357.15  4001.6  353.43  4039.1  351.74  4096.7  344.37
  4138.5  341.38  4159.5  337.63  4239.7  333.10  4254.5  329.54  4260.6  331.21
  4281.5  330.92  4350.2  326.28  4409.7  322.00  4998.0  321.00  6446.3  322.00
  6512.5  323.14  6579.6  328.71  6610.4  332.32  6618.8  334.94  6646.7  336.72
  6663.5  340.27  6669.1  339.05  6677.5  341.52  6713.8  343.59  6789.3  357.55
#Mann=7,-1,0
  3779.8    0.05       0  3873.9    0.12       0  3881.8    0.05       0
  4039.1    0.12       0  4350.2    0.05       0  4409.7    0.03       0
  6446.3    0.05       0
Bank Sta=4409.7,6446.3
Exp/Cntr=0.3,0.1

Type RM Length L Ch R = 1,34613,1366,1366,1366
BEGIN DESCRIPTION:
Caney Creek 27.0
END DESCRIPTION:
XS GIS Cut Line= 3
      2746176.00      6771911.00      2744576.00      6772511.00
      2743176.00      6773911.00
#Sta/Elev= 30
  3291.2  399.18  3376.6  391.03  3452.5  379.73  3758.4  350.92  3788.7  348.40
  3825.2  347.83  3849.2  343.46  3889.3  343.63  4011.9  336.58  4155.4  328.55
  4175.1  326.07  4246.2  324.57  4263.1  322.00  4291.3  322.00  4998.0  321.00
  5608.1  322.00  5678.8  325.48  5961.7  327.81  6046.5  322.03  6414.2  322.01
  6583.9  328.54  6654.6  333.80  6668.8  338.38  6697.1  336.79  6711.2  337.79
  6753.6  343.27  6781.9  345.34  6866.8  356.76  6923.3  358.54  6979.9  357.47
#Mann=6,-1,0
  3291.2    0.12       0  3452.5     0.1       0  4011.9    0.12       0
  4175.1    0.05       0  4291.3    0.03       0  5608.1    0.05       0
Bank Sta=4291.3,5608.1
Exp/Cntr=0.3,0.1

Type RM Length L Ch R = 1,33247,699,699,699
BEGIN DESCRIPTION:
Caney Creek 26.0
END DESCRIPTION:
XS GIS Cut Line= 3
      2743676.00      6770661.00      2743576.00      6771661.00
      2743176.00      6773461.00
#Sta/Elev= 30
  3990.8  352.29  4031.0  351.11  4066.9  347.89  4141.0  342.67  4161.7  339.86
  4322.7  326.22  4332.5  325.92  4352.6  322.45  4365.6  322.00  4998.0  321.00
  5561.2  322.00  5573.3  322.00  5579.7  323.82  5666.1  328.05  5715.0  327.93
  5856.3  331.47  5958.7  329.46  6009.9  331.14  6071.4  330.83  6225.8  325.74
  6310.9  327.85  6354.4  331.40  6378.7  331.22  6440.2  335.38  6495.2  333.67
  6532.4  336.27  6559.6  335.60  6624.6  339.12  6778.2  350.49  6839.7  353.20
#Mann=10,-1,0
  3990.8    0.12       0  4066.9     0.1       0  4141.0    0.12       0
  4322.7    0.05       0  4365.6    0.03       0  5561.2    0.05       0
  5666.1    0.12       0  5715.0    0.05       0  6225.8    0.12       0
  6559.6    0.05       0
Bank Sta=4365.6,5561.2
Exp/Cntr=0.3,0.1

Type RM Length L Ch R = 1,32548,1400,1400,1400
BEGIN DESCRIPTION:
Caney Creek 25.0
END DESCRIPTION:
XS GIS Cut Line= 3
      2743576.02      6770660.97      2742876.00      6771661.00
      2743176.00      6773760.99
#Sta/Elev= 30
  3779.4  352.82  3828.7  348.48  3837.4  346.83  3843.5  347.15  3888.0  343.69
  3915.0  340.21  3978.1  337.05  3995.2  335.20  4016.2  334.40  4060.2  329.78
  4072.8  329.73  4096.4  326.89  4120.7  326.22  4159.1  324.64  4182.3  322.00
  4194.6  322.00  4998.0  321.00  6420.8  322.00  6434.5  322.00  6444.6  323.92
  6541.2  334.33  6555.7  336.28  6575.9  336.98  6666.8  345.46  6697.1  347.21
  6737.6  351.58  6778.3  353.41  6879.0  354.39  6959.8  353.56  7121.4  356.73
#Mann=7,-1,0
  3779.4     0.1       0  3978.1    0.12       0  4120.7    0.05       0
  4194.6    0.03       0  6420.8    0.05       0  6541.2    0.12       0
  6778.3    0.05       0
Bank Sta=4194.6,6420.8
Exp/Cntr=0.3,0.1

Type RM Length L Ch R = 1,31148,719,719,719
BEGIN DESCRIPTION:
Caney Creek 24.0
END DESCRIPTION:
XS GIS Cut Line= 3
      2743175.98      6770561.02      2741576.00      6771961.00
      2743076.00      6774061.01
#Sta/Elev= 30
  2874.0  353.92  2987.4  349.43  3050.4  343.12  3079.5  340.80  3093.7  341.69
  3100.3  340.36  3107.9  340.88  3114.6  339.97  3179.1  338.05  3200.0  334.51
  3228.5  332.11  3236.6  330.48  3277.8  325.13  3282.0  322.00  4998.0  321.00
  6891.5  322.00  6929.4  322.00  6941.7  323.77  6974.8  325.83  7015.4  328.14
  7071.9  334.35  7096.3  335.75  7113.7  337.29  7143.2  337.65  7158.0  340.12
  7172.7  340.94  7294.4  344.86  7359.5  345.31  7508.8  350.51  7580.7  352.27
#Mann=8,-1,0
  2874.0     0.1       0  3050.4    0.12       0  3236.6    0.05       0
  3282.0    0.03       0  6891.5    0.05       0  6974.8    0.12       0
  7096.3    0.05       0  7508.8    0.12       0
Bank Sta=3282,6891.5
Exp/Cntr=0.3,0.1

Type RM Length L Ch R = 1,30429,707,707,707
BEGIN DESCRIPTION:
Caney Creek 23.0
END DESCRIPTION:
XS GIS Cut Line= 3
      2742775.97      6769661.04      2740976.00      6771661.00
      2738276.00      6773761.00
#Sta/Elev= 30
  2309.3  367.25  2387.4  366.56  2628.0  355.29  2705.8  353.23  2720.0  351.49
  2811.5  349.91  2840.3  347.69  2868.7  343.02  2889.6  342.85  3045.0  330.36
  3069.5  329.15  3172.9  323.41  3177.0  322.00  4998.0  321.00  7306.4  322.00
  7331.0  322.00  7343.7  324.29  7407.9  330.07  7544.6  340.27  7600.7  346.02
  7622.4  345.72  7685.7  351.54  7778.9  356.20  7857.7  356.34  8071.2  363.74
  8284.8  360.78  8313.7  363.95  8334.5  368.44  8384.3  372.82  8420.5  373.65
#Mann=6,-1,0
  2309.3    0.12       0  2811.5     0.1       0  3045.0    0.12       0
  3069.5    0.05       0  3177.0    0.03       0  7306.4    0.05       0
Bank Sta=3177,7306.4
Exp/Cntr=0.3,0.1

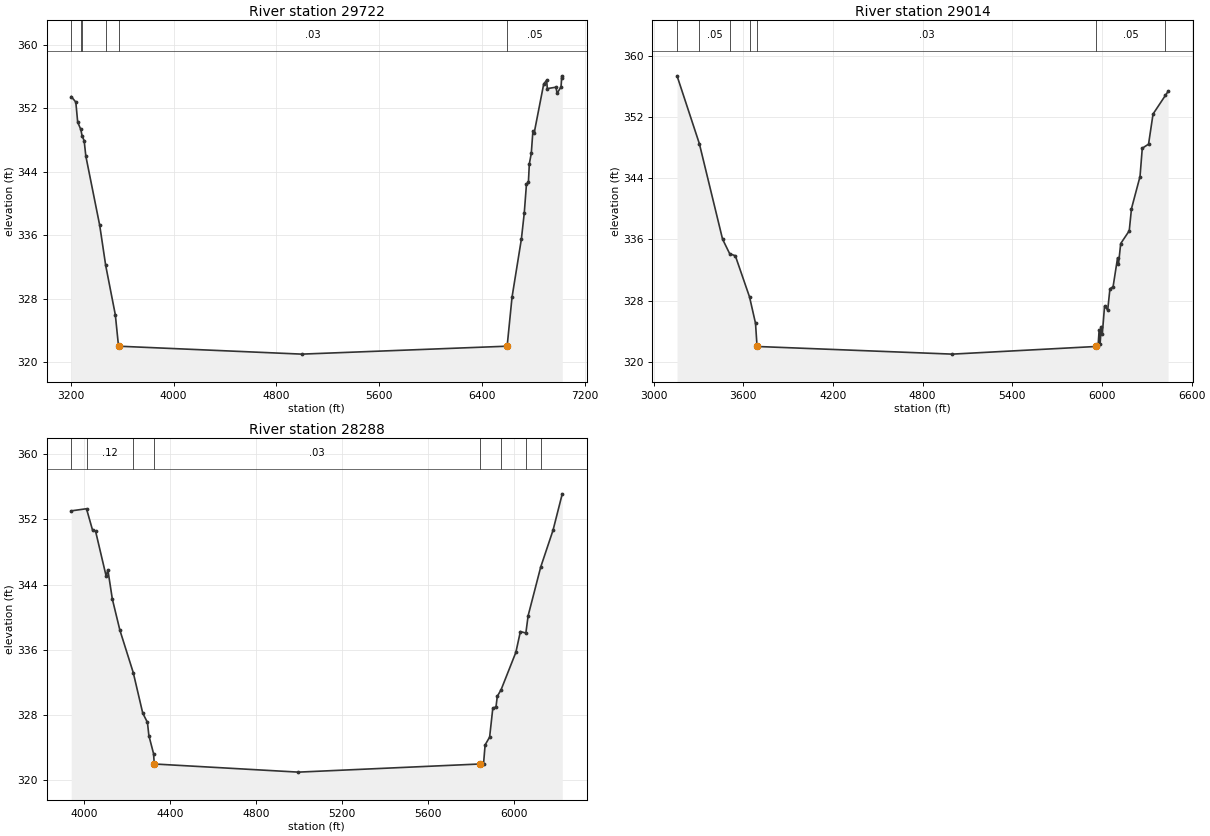
Type RM Length L Ch R = 1,29722,708,708,708
BEGIN DESCRIPTION:
Caney Creek 22.0
END DESCRIPTION:
XS GIS Cut Line= 3
      2741533.52      6769709.11      2740476.00      6771161.00
      2738659.74      6772058.94
#Sta/Elev= 30
  3203.8  353.46  3239.6  352.76  3254.2  350.23  3278.2  349.32  3288.8  348.48
  3304.5  347.90  3317.5  345.96  3425.8  337.21  3472.1  332.18  3547.1  325.96
  3572.0  322.00  4998.0  321.00  6597.0  322.00  6635.1  328.18  6708.0  335.51
  6730.4  338.80  6747.3  342.41  6762.5  342.65  6769.7  344.98  6784.9  346.29
  6797.7  349.15  6807.2  348.85  6881.9  355.06  6904.3  355.50  6909.9  354.46
  6977.2  354.64  6985.7  353.86  7016.5  354.68  7022.1  356.07  7026.1  355.78
#Mann=6,-1,0
  3203.8    0.12       0  3278.2     0.1       0  3288.8    0.12       0
  3472.1    0.05       0  3572.0    0.03       0  6597.0    0.05       0
Bank Sta=3572,6597
Exp/Cntr=0.3,0.1

Type RM Length L Ch R = 1,29014,726,726,726
BEGIN DESCRIPTION:
Caney Creek 21.0
END DESCRIPTION:
XS GIS Cut Line= 3
      2741375.99      6769461.01      2739976.00      6770661.00
      2738776.02      6771460.99
#Sta/Elev= 30
  3156.1  357.37  3305.4  348.51  3460.7  336.03  3508.2  334.13  3546.3  333.85
  3641.3  328.47  3681.3  325.03  3691.6  322.00  4998.0  321.00  5961.0  322.00
  5973.5  322.00  5981.0  324.21  5987.0  322.35  5996.0  324.60  6002.0  323.63
  6017.1  327.28  6038.1  326.76  6053.1  329.54  6074.2  329.81  6104.2  333.59
  6110.2  332.74  6125.2  335.45  6182.3  337.12  6197.3  340.02  6254.4  344.21
  6269.5  347.91  6311.5  348.44  6341.6  352.38  6424.5  354.82  6442.2  355.33
#Mann=7,-1,0
  3156.1    0.12       0  3305.4    0.05       0  3508.2    0.12       0
  3641.3    0.05       0  3691.6    0.03       0  5961.0    0.05       0
  6424.5    0.12       0
Bank Sta=3691.6,5961
Exp/Cntr=0.3,0.1

Type RM Length L Ch R = 1,28288,720,720,720
BEGIN DESCRIPTION:
Caney Creek 20.0
END DESCRIPTION:
XS GIS Cut Line= 3
      2740125.97      6769411.03      2739426.00      6770211.00
      2738426.02      6770910.98
#Sta/Elev= 30
  3941.7  353.06  4012.8  353.32  4040.8  350.70  4055.1  350.55  4104.4  345.02
  4112.0  345.84  4132.9  342.24  4168.0  338.42  4230.2  333.21  4274.3  328.24
  4296.2  327.10  4302.8  325.49  4324.6  323.27  4327.9  322.00  4998.0  321.00
  5844.1  322.00  5859.1  322.00  5866.5  324.34  5887.5  325.30  5902.3  328.85
  5917.1  329.01  5923.2  330.31  5940.6  331.10  6009.5  335.70  6030.5  338.25
  6056.0  338.07  6066.6  340.20  6125.1  346.17  6182.2  350.67  6225.3  355.15
#Mann=8,-1,0
  3941.7    0.05       0  4012.8    0.12       0  4230.2    0.05       0
  4327.9    0.03       0  5844.1    0.05       0  5940.6     0.1       0
  6056.0    0.05       0  6125.1     0.1       0
Bank Sta=4327.9,5844.1
Exp/Cntr=0.3,0.1