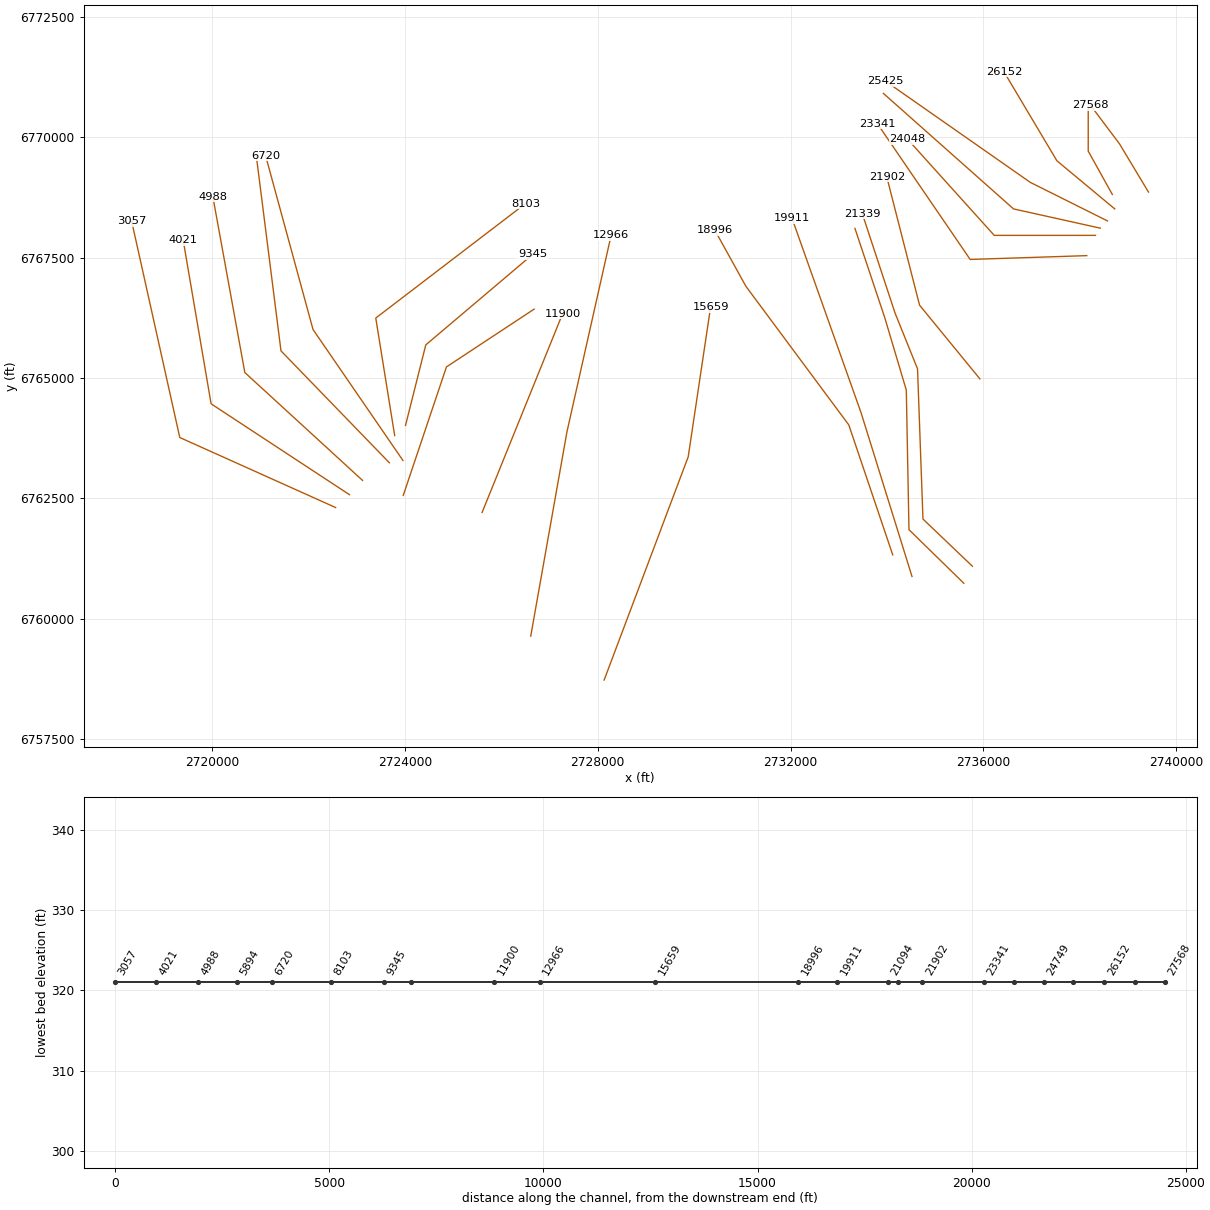
HEC-RAS study Caney Creek.prj: Caney Creek Base Level Engineering

--- Caney Creek.g01 (geometry) --- (continued)

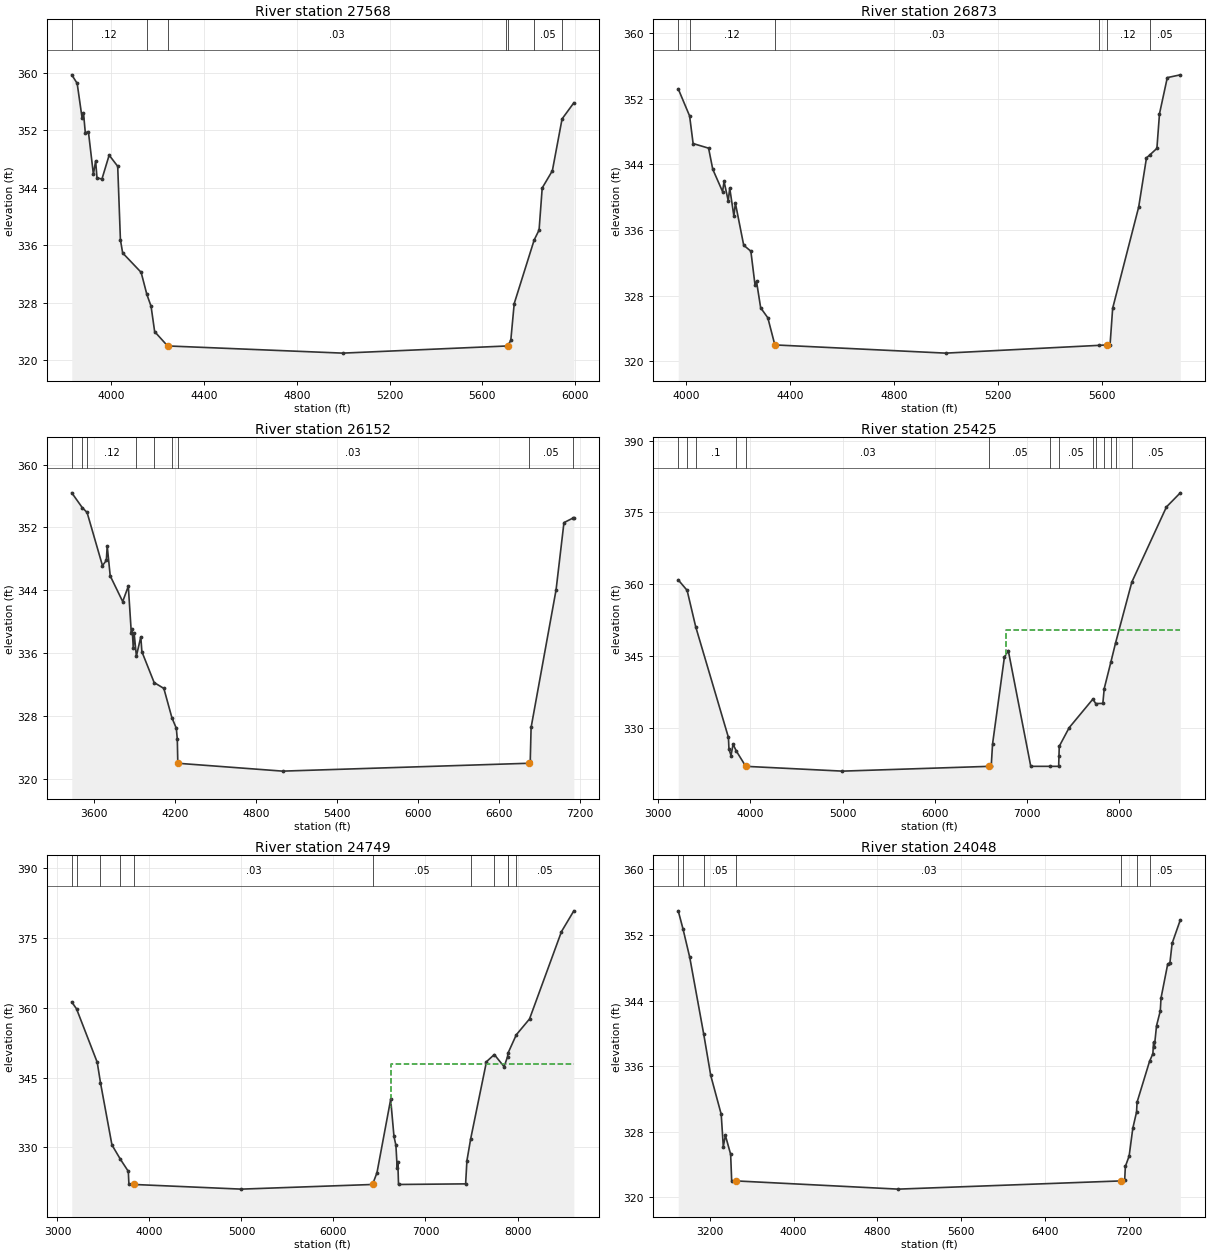
Type RM Length L Ch R = 1,27568,695,695,695
BEGIN DESCRIPTION:
Caney Creek 19.0
END DESCRIPTION:
XS GIS Cut Line= 3
      2739425.99      6768861.02      2738826.00      6769861.00
      2738225.98      6770661.02
#Sta/Elev= 30
  3829.1  359.70  3852.4  358.51  3873.8  353.65  3879.6  354.43  3887.4  351.68
  3901.0  351.76  3922.4  345.87  3932.1  347.72  3937.9  345.37  3959.3  345.21
  3990.4  348.53  4027.3  346.98  4039.0  336.75  4048.7  334.93  4128.4  332.23
  4153.0  329.17  4171.2  327.52  4186.7  323.99  4242.5  322.00  4998.0  321.00
  5703.9  321.99  5711.4  322.00  5723.4  322.82  5738.0  327.89  5824.2  336.74
  5845.3  338.12  5858.8  343.97  5902.6  346.36  5944.5  353.57  5995.3  355.81
#Mann=7,-1,0
  3829.1    0.12       0  4153.0    0.05       0  4242.5    0.03       0
  5703.9    0.12       0  5711.4    0.05       0  5824.2    0.05       0
  5944.5     0.1       0
Bank Sta=4242.5,5711.4
Exp/Cntr=0.3,0.1

Type RM Length L Ch R = 1,26873,721,721,721
BEGIN DESCRIPTION:
Caney Creek 18.0
END DESCRIPTION:
XS GIS Cut Line= 3
      2738675.98      6768811.03      2738176.00      6769711.00
      2738176.00      6770610.98
#Sta/Elev= 30
  3970.4  353.18  4014.1  349.88  4027.6  346.52  4087.0  345.96  4103.1  343.39
  4140.8  340.67  4146.5  341.91  4162.5  339.55  4168.3  341.10  4184.3  337.68
  4190.0  339.27  4222.0  334.14  4249.5  333.41  4265.5  329.30  4271.2  329.74
  4287.2  326.52  4314.7  325.30  4341.7  322.00  4998.0  321.00  5589.0  321.95
  5617.4  322.00  5629.9  322.00  5639.9  326.46  5739.9  338.79  5769.9  344.78
  5782.1  345.12  5809.9  345.93  5819.9  350.15  5849.9  354.55  5899.9  354.89
#Mann=6,-1,0
  3970.4     0.1       0  4014.1    0.12       0  4341.7    0.03       0
  5589.0    0.12       0  5617.4    0.12       0  5782.1    0.05       0
Bank Sta=4341.7,5617.4
Exp/Cntr=0.3,0.1

Type RM Length L Ch R = 1,26152,727,727,727
BEGIN DESCRIPTION:
Caney Creek 17.0
END DESCRIPTION:
XS GIS Cut Line= 3
      2738726.03      6768510.98      2737526.00      6769511.00
      2736426.07      6771363.01
#Sta/Elev= 30
  3437.7  356.40  3514.9  354.53  3551.0  353.90  3664.9  347.14  3693.5  347.80
  3700.0  349.64  3722.2  345.84  3814.6  342.57  3856.2  344.52  3878.4  338.58
  3884.9  339.08  3892.7  336.72  3899.2  338.56  3915.9  335.62  3948.7  338.09
  3956.5  336.20  4047.3  332.27  4119.2  331.52  4178.7  327.80  4211.6  326.45
  4218.8  325.05  4222.6  322.00  4998.0  321.00  6819.1  322.00  6831.2  322.32
  6837.4  326.55  7022.2  344.05  7080.6  352.61  7150.8  353.22  7153.8  353.22
#Mann=9,-1,0
  3437.7    0.12       0  3514.9    0.05       0  3551.0    0.12       0
  3915.9     0.1       0  4047.3    0.12       0  4178.7    0.05       0
  4222.6    0.03       0  6819.1    0.05       0  7150.8     0.1       0
Bank Sta=4222.6,6819.1
Exp/Cntr=0.3,0.1

Type RM Length L Ch R = 1,25425,676,676,676
BEGIN DESCRIPTION:
Caney Creek 16.0
END DESCRIPTION:
XS GIS Cut Line= 3
      2738575.96      6768261.02      2736976.00      6769061.00
      2733975.98      6771161.01
#Sta/Elev= 30
  3215.5  360.91  3311.8  358.73  3405.1  351.13  3760.5  328.03  3766.1  325.62
  3788.4  324.25  3810.8  326.61  3846.2  325.19  3948.5  322.00  4998.0  321.00
  6592.6  322.00  6613.4  322.00  6627.8  326.64  6756.4  344.78  6798.7  346.16
  7042.8  322.00  7252.3  322.00  7345.8  322.00  7348.9  324.12  7351.9  326.18
  7459.1  330.05  7717.4  336.04  7747.8  335.10  7825.3  335.13  7840.2  338.22
  7913.0  343.80  7963.1  347.73  8139.9  360.45  8515.9  376.14  8666.3  379.08
#Mann=14,-1,0
  3215.5    0.12       0  3311.8    0.05       0  3405.1     0.1       0
  3846.2    0.05       0  3948.5    0.03       0  6592.6    0.05       0
  7252.3    0.12       0  7348.9    0.05       0  7717.4    0.12       0
  7747.8    0.05       0  7840.2    0.12       0  7913.0    0.05       0
  7963.1    0.12       0  8139.9    0.05       0
#XS Ineff=2,0
       0                 6769.50    0.00  350.36
Permanent Ineff=
       F       F
Bank Sta=3948.5,6592.6
Exp/Cntr=0.3,0.1

Type RM Length L Ch R = 1,24749,701,701,701
BEGIN DESCRIPTION:
Caney Creek 15.0
END DESCRIPTION:
XS GIS Cut Line= 3
      2738425.97      6768111.01      2736626.00      6768511.00
      2733925.97      6770911.03
#Sta/Elev= 30
  3155.9  361.24  3207.9  359.75  3432.5  348.27  3467.9  343.88  3592.5  330.50
  3685.0  327.40  3770.5  324.82  3776.9  322.00  3833.7  322.00  4998.0  321.00
  6424.7  322.00  6472.8  324.53  6621.6  340.29  6657.6  332.32  6678.5  330.43
  6692.7  325.48  6699.4  326.81  6706.9  322.00  7436.1  322.13  7450.3  327.12
  7490.9  331.79  7662.7  348.40  7747.9  349.94  7854.2  347.32  7891.4  349.44
  7896.7  350.24  7987.1  354.19  8130.6  357.59  8478.0  376.38  8612.3  380.84
#Mann=11,-1,0
  3155.9    0.12       0  3207.9     0.1       0  3467.9    0.12       0
  3685.0    0.05       0  3833.7    0.03       0  6424.7    0.05       0
  7490.9    0.12       0  7747.9     0.1       0  7891.4    0.05       0
  7896.7    0.12       0  7987.1    0.05       0
#XS Ineff=2,0
       0                 6629.70    0.00  347.99
Permanent Ineff=
       F       F
Bank Sta=3833.7,6424.7
Exp/Cntr=0.3,0.1

Type RM Length L Ch R = 1,24048,707,707,707
BEGIN DESCRIPTION:
Caney Creek 14.0
END DESCRIPTION:
XS GIS Cut Line= 3
      2738326.00      6767961.00      2736226.00      6767961.00
      2734426.02      6769960.98
#Sta/Elev= 30
  2900.0  354.94  2945.9  352.71  3010.0  349.25  3143.8  339.86  3210.0  334.87
  3310.0  330.13  3330.0  326.19  3350.0  327.55  3400.0  325.25  3410.0  322.00
  3454.2  322.00  4998.0  321.00  7120.1  322.00  7159.7  322.08  7166.4  323.77
  7202.3  325.03  7237.4  328.42  7273.3  330.41  7278.0  331.60  7397.0  336.58
  7428.8  337.51  7435.5  338.90  7443.0  338.34  7463.9  340.93  7499.8  342.74
  7506.5  344.29  7570.0  348.42  7591.7  348.61  7612.6  350.98  7690.7  353.83
#Mann=7,-1,0
  2900.0    0.12       0  2945.9     0.1       0  3143.8    0.05       0
  3454.2    0.03       0  7120.1    0.05       0  7278.0    0.12       0
  7397.0    0.05       0
Bank Sta=3454.2,7120.1
Exp/Cntr=0.3,0.1

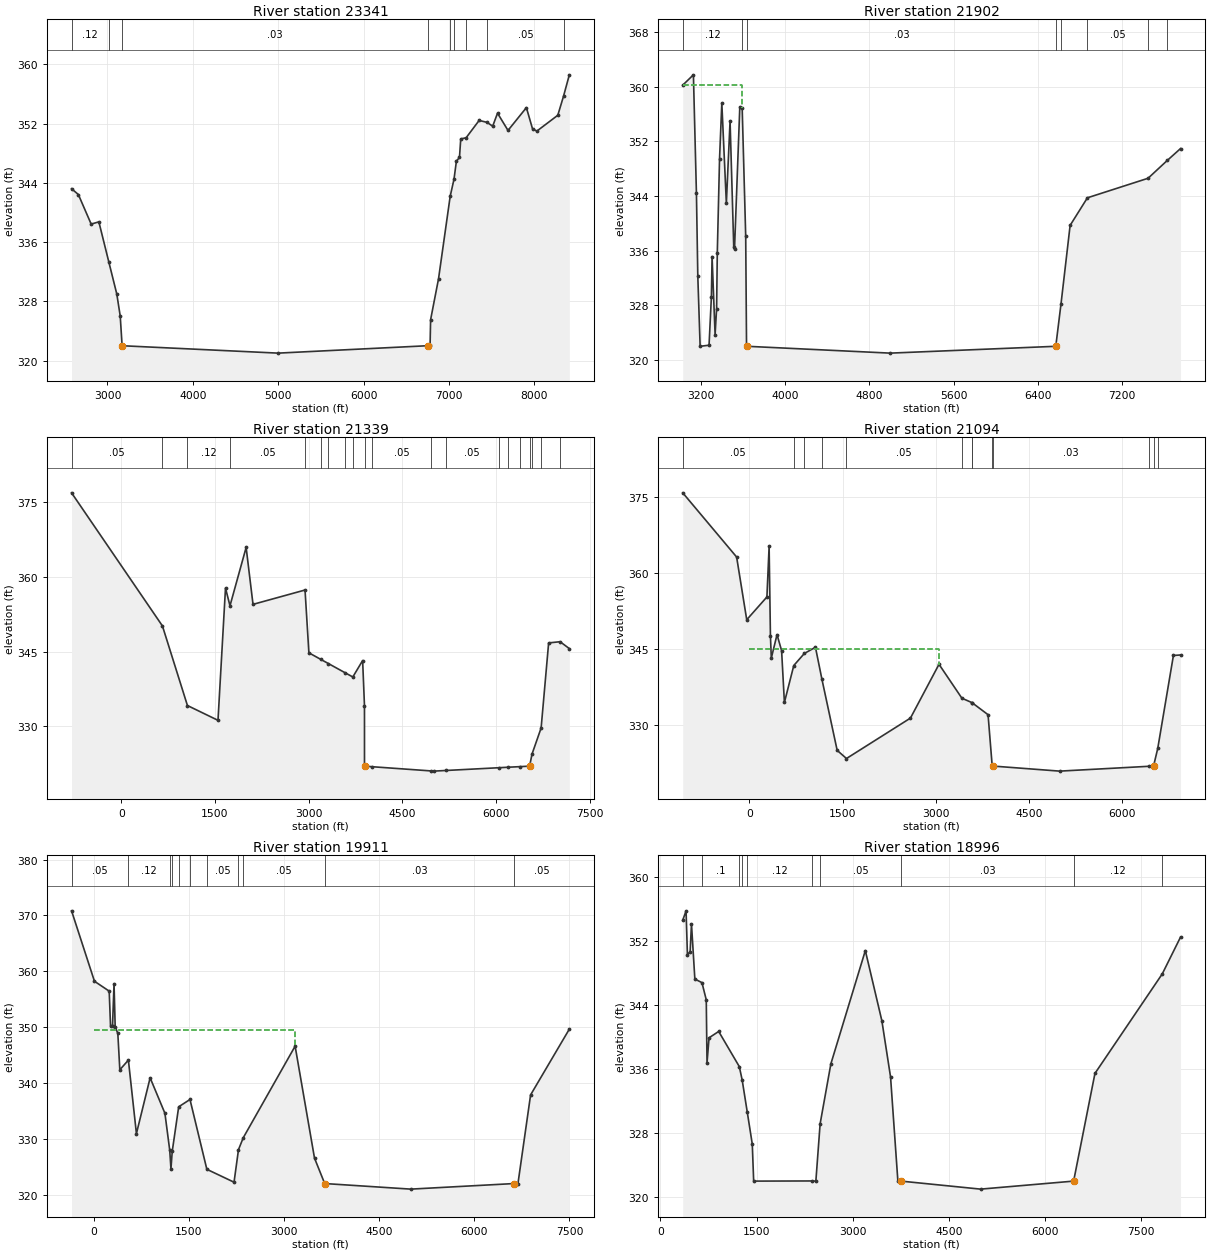
Type RM Length L Ch R = 1,23341,1439,1439,1439
BEGIN DESCRIPTION:
Caney Creek 13.0
END DESCRIPTION:
XS GIS Cut Line= 3
      2738145.62      6767539.94      2735726.00      6767461.00
      2733804.51      6770277.00
#Sta/Elev= 30
  2579.1  343.21  2658.8  342.42  2808.8  338.43  2898.9  338.73  3014.5  333.36
  3109.0  328.98  3149.0  326.02  3171.2  322.00  4998.0  321.00  6748.8  322.00
  6778.3  322.13  6784.4  325.52  6877.1  331.04  7013.7  342.19  7058.3  344.49
  7086.5  346.93  7122.4  347.43  7137.3  349.93  7200.3  350.09  7352.7  352.43
  7445.4  352.17  7511.3  351.65  7568.1  353.41  7690.8  351.08  7906.2  354.16
  7978.1  351.29  8028.8  350.99  8274.1  353.13  8341.8  355.73  8409.1  358.59
#Mann=9,-1,0
  2579.1    0.12       0  3014.5    0.05       0  3171.2    0.03       0
  6748.8    0.05       0  7013.7    0.12       0  7058.3    0.05       0
  7200.3    0.12       0  7445.4    0.05       0  8341.8    0.12       0
Bank Sta=3171.2,6748.8
Exp/Cntr=0.3,0.1

Type RM Length L Ch R = 1,21902,563,563,563
BEGIN DESCRIPTION:
Caney Creek 12.0
END DESCRIPTION:
XS GIS Cut Line= 3
      2735927.29      6764980.23      2734676.00      6766511.00
      2733995.66      6769177.26
#Sta/Elev= 30
  3027.3  360.25  3128.6  361.76  3157.3  344.38  3170.4  332.23  3192.5  322.00
  3277.2  322.16  3299.5  329.29  3305.9  335.15  3334.6  323.71  3349.0  327.53
  3355.4  335.62  3377.0  349.50  3398.5  357.61  3441.6  342.95  3476.8  355.00
  3511.9  336.49  3519.1  336.25  3569.4  357.09  3591.9  356.90  3625.4  338.11
  3633.3  322.00  3639.0  322.00  4998.0  321.00  6571.0  322.00  6620.5  328.18
  6707.3  339.71  6871.5  343.75  7447.8  346.61  7630.1  349.22  7756.1  350.96
#Mann=8,-1,0
  3027.3    0.12       0  3591.9    0.05       0  3639.0    0.03       0
  6571.0    0.12       0  6620.5    0.12       0  6871.5    0.05       0
  7447.8    0.12       0  7630.1    0.05       0
#XS Ineff=2,0
    0.00 3590.50  360.22               0
Permanent Ineff=
       F       F
Bank Sta=3639,6571
Exp/Cntr=0.3,0.1

Type RM Length L Ch R = 1,21339,245,245,245
BEGIN DESCRIPTION:
Caney Creek 11.0
END DESCRIPTION:
XS GIS Cut Line= 5
      2735772.19      6761086.80      2734746.91      6762066.59
      2734634.06      6765187.92      2734166.37      6766350.11
      2733487.96      6768411.97
#Sta/Elev= 30
  -794.3  376.87   659.7  350.15  1059.8  334.17  1548.9  331.20  1669.0  357.75
  1740.6  354.19  1999.2  365.91  2109.2  354.48  2941.6  357.36  3003.3  344.75
  3191.2  343.45  3314.5  342.60  3583.9  340.74  3706.2  339.90  3863.2  343.20
  3892.7  334.13  3893.1  322.00  4009.6  321.89  4958.4  321.04  4998.0  321.00
  5197.9  321.13  6037.9  321.68  6187.1  321.78  6379.2  321.90  6534.9  322.00
  6573.6  324.42  6719.3  329.67  6839.4  346.74  7022.7  346.98  7170.6  345.60
#Mann=20,-1,0
  -794.3    0.05       0   659.7    0.05       0  1059.8    0.12       0
  1740.6    0.05       0  2941.6     0.1       0  3191.2     0.1       0
  3314.5    0.05       0  3583.9   0.075       0  3706.2    0.05       0
  3893.1    0.07       0  4009.6    0.05       0  4958.4     0.1       0
  5197.9    0.05       0  6037.9     0.1       0  6187.1    0.05       0
  6379.2   0.075       0  6534.9     0.1       0  6573.6   0.075       0
  6719.3    0.05       0  7022.7   0.075       0
Bank Sta=3893.1,6534.9
Exp/Cntr=0.3,0.1

Type RM Length L Ch R = 1,21094,1183,1183,1183
BEGIN DESCRIPTION:
Caney Creek 10.0
END DESCRIPTION:
XS GIS Cut Line= 5
      2735594.67      6760732.24      2734456.48      6761845.91
      2734401.11      6764746.82      2733951.00      6766261.00
      2733335.21      6768105.95
#Sta/Elev= 30
 -1073.5  375.89  -205.6  363.23   -42.8  350.86   282.3  355.35   317.8  365.33
   338.9  347.72   353.1  343.28   445.1  347.92   518.9  344.77   564.0  334.54
   715.2  341.83   885.6  344.21  1064.1  345.43  1168.3  339.13  1414.2  325.09
  1564.0  323.49  2594.4  331.46  3054.5  342.07  3423.2  335.38  3584.1  334.52
  3588.9  334.48  3844.5  332.13  3911.3  322.02  3921.9  322.00  4998.0  321.00
  6444.7  321.96  6510.5  322.00  6578.1  325.48  6830.5  343.81  6945.0  343.91
#Mann=13,-1,0
 -1073.5    0.05       0   715.2    0.12       0   885.6    0.05       0
  1168.3    0.12       0  1564.0    0.05       0  3423.2   0.075       0
  3584.1    0.05       0  3588.9   0.075       0  3911.3    0.05       0
  3921.9    0.03       0  6444.7   0.075       0  6510.5    0.12       0
  6578.1    0.05       0
#XS Ineff=2,0
    0.00 3059.00  345.02               0
Permanent Ineff=
       F       F
Bank Sta=3921.9,6510.5
Exp/Cntr=0.3,0.1

Type RM Length L Ch R = 1,19911,915,915,915
BEGIN DESCRIPTION:
Mapping XS 8335b49f
END DESCRIPTION:
XS GIS Cut Line= 3
      2734519.03      6760874.13      2733464.54      6764269.04
      2732029.31      6768316.82
#Sta/Elev= 30
  -351.3  370.83     9.8  358.22   242.3  356.45   263.2  350.24   294.6  350.17
   318.6  357.80   336.5  350.09   378.4  348.87   409.8  342.37   545.1  344.10
   671.6  330.94   887.8  340.93  1121.0  334.58  1197.2  327.93  1216.1  324.63
  1236.3  327.77  1338.1  335.74  1516.2  337.05  1782.2  324.55  2210.9  322.24
  2281.2  328.07  2356.3  330.20  3174.2  346.60  3479.9  326.55  3640.5  322.00
  4998.0  321.00  6630.5  322.00  6688.2  322.00  6887.4  337.87  7498.3  349.65
#Mann=11,-1,0
  -351.3    0.05       0   545.1    0.12       0  1197.2     0.1       0
  1236.3    0.12       0  1338.1     0.1       0  1516.2    0.12       0
  1782.2    0.05       0  2281.2    0.12       0  2356.3    0.05       0
  3640.5    0.03       0  6630.5    0.05       0
#XS Ineff=2,0
    0.00 3171.30  349.47               0
Permanent Ineff=
       F       F
Bank Sta=3640.5,6630.5
Exp/Cntr=0.3,0.1

Type RM Length L Ch R = 1,18996,3337,3337,3337
BEGIN DESCRIPTION:
Mapping XS 7412aad1
END DESCRIPTION:
XS GIS Cut Line= 4
      2734119.70      6761321.88      2733207.86      6764022.81
      2731072.81      6766902.84      2730426.97      6768072.24
#Sta/Elev= 30
   347.8  354.55   399.6  355.72   420.8  350.23   463.0  350.62   484.1  354.08
   536.9  347.21   647.8  346.76   714.9  344.62   726.8  336.76   758.5  339.88
   909.0  340.67  1230.6  336.29  1275.5  334.62  1354.9  330.62  1433.3  326.62
  1455.1  322.00  2362.8  322.02  2426.1  322.00  2492.7  329.15  2660.4  336.63
  3198.5  350.76  3456.7  342.00  3592.3  334.99  3706.6  322.00  3755.8  322.00
  4998.0  321.00  6450.5  322.00  6783.6  335.44  7834.3  347.85  8119.5  352.44
#Mann=10,-1,0
   347.8    0.05       0   647.8     0.1       0  1230.6    0.12       0
  1275.5     0.1       0  1354.9    0.12       0  2362.8    0.12       0
  2492.7    0.05       0  3755.8    0.03       0  6450.5    0.12       0
  7834.3    0.12       0
#XS Ineff=2,0
    0.00 3224.80  348.57               0
Permanent Ineff=
       F       F
Bank Sta=3755.8,6450.5
Exp/Cntr=0.3,0.1

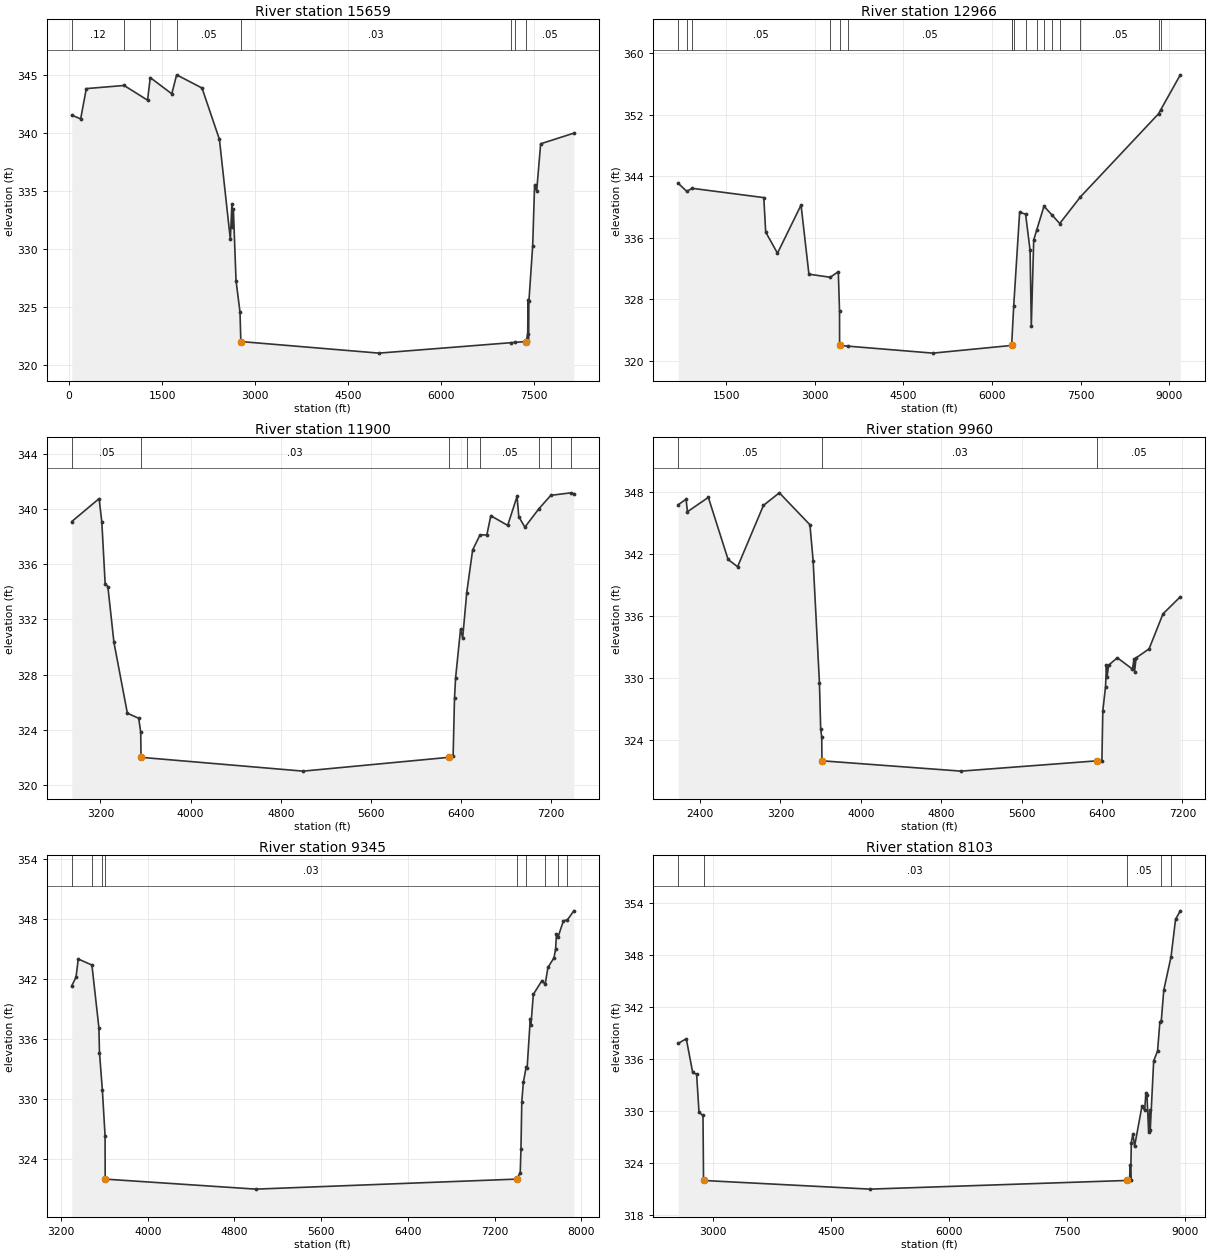
Type RM Length L Ch R = 1,15659,2693,2693,2693
BEGIN DESCRIPTION:
Caney Creek 9.0
END DESCRIPTION:
XS GIS Cut Line= 3
      2728130.99      6758721.19      2729876.00      6763360.99
      2730339.72      6766467.47
#Sta/Elev= 30
    42.9  341.57   186.0  341.24   277.7  343.86   887.0  344.13  1265.2  342.86
  1308.9  344.81  1656.0  343.41  1734.4  345.05  2143.6  343.91  2424.5  339.47
  2600.5  330.83  2625.4  333.85  2630.8  331.94  2649.6  333.43  2692.3  327.26
  2756.4  324.55  2769.7  322.00  4998.0  321.00  7122.6  321.90  7189.1  321.93
  7370.1  322.00  7396.3  322.65  7402.9  325.62  7408.0  322.06  7416.5  325.52
  7477.2  330.29  7507.5  335.50  7541.4  335.02  7605.6  339.09  8140.9  340.01
#Mann=8,-1,0
    42.9    0.12       0   887.0     0.1       0  1308.9    0.12       0
  1734.4    0.05       0  2769.7    0.03       0  7122.6   0.075       0
  7189.1    0.05       0  7370.1    0.05       0
Bank Sta=2769.7,7370.1
Exp/Cntr=0.3,0.1

Type RM Length L Ch R = 1,12966,1066,1066,1066
BEGIN DESCRIPTION:
Caney Creek 8.0
END DESCRIPTION:
XS GIS Cut Line= 3
      2726608.08      6759633.79      2727359.43      6763877.90
      2728276.00      6767960.98
#Sta/Elev= 30
   689.9  343.09   836.2  342.03   922.8  342.44  2137.5  341.23  2169.8  336.74
  2369.0  334.00  2767.8  340.26  2901.0  331.27  3261.3  330.87  3398.2  331.59
  3418.9  326.45  3420.2  322.00  3556.7  321.91  4998.0  321.00  6330.2  322.00
  6330.8  322.00  6365.5  327.07  6465.9  339.32  6567.0  339.08  6643.0  334.37
  6663.5  324.50  6704.5  335.72  6755.9  337.04  6878.4  340.11  7018.4  338.93
  7144.6  337.86  7495.2  341.33  8815.8  352.13  8854.0  352.66  9184.7  357.20
#Mann=17,-1,0
   689.9    0.05       0   836.2    0.12       0   922.8    0.05       0
  3261.3    0.12       0  3420.2    0.03       0  3556.7    0.05       0
  6330.2    0.12       0  6330.8    0.12       0  6365.5    0.05       0
  6567.0    0.12       0  6755.9    0.05       0  6878.4    0.12       0
  7018.4    0.05       0  7144.6    0.12       0  7495.2    0.05       0
  8815.8    0.12       0  8854.0    0.05       0
Bank Sta=3420.2,6330.2
Exp/Cntr=0.3,0.1

Type RM Length L Ch R = 1,11900,1940,1940,1940
BEGIN DESCRIPTION:
Mapping XS b82788d8
END DESCRIPTION:
XS GIS Cut Line= 2
      2725598.95      6762203.73      2727269.60      6766334.04
#Sta/Elev= 30
  2945.4  339.09  3188.0  340.75  3212.1  339.05  3241.7  334.59  3265.8  334.37
  3319.4  330.34  3438.7  325.20  3539.4  324.83  3557.3  323.81  3559.8  322.00
  4998.0  321.00  6291.8  322.00  6329.6  322.13  6341.8  326.29  6351.2  327.74
  6395.4  331.28  6414.1  330.64  6450.0  333.91  6502.7  337.03  6568.3  338.12
  6628.7  338.12  6664.0  339.51  6813.7  338.81  6896.9  340.91  6912.1  339.45
  6966.0  338.68  7090.1  340.01  7196.8  340.99  7374.7  341.17  7400.8  341.11
#Mann=8,-1,0
  2945.4    0.05       0  3559.8    0.03       0  6291.8    0.05       0
  6450.0    0.12       0  6568.3    0.05       0  7090.1    0.12       0
  7196.8    0.05       0  7374.7    0.12       0
Bank Sta=3559.8,6291.8
Exp/Cntr=0.3,0.1

Type RM Length L Ch R = 1,9960,615,615,615
BEGIN DESCRIPTION:
Caney Creek 7.0
END DESCRIPTION:
XS GIS Cut Line= 3
      2723962.51      6762557.11      2724859.33      6765227.65
      2726678.41      6766428.49
#Sta/Elev= 30
  2182.9  346.78  2260.8  347.31  2274.5  346.10  2482.4  347.49  2679.1  341.48
  2773.7  340.78  3031.2  346.72  3189.1  347.93  3493.6  344.84  3525.2  341.38
  3588.2  329.55  3600.5  325.09  3611.1  324.28  3613.1  322.00  4998.0  321.00
  6354.1  322.00  6399.3  322.00  6408.4  326.83  6435.4  329.17  6444.5  331.23
  6450.5  330.06  6465.6  331.25  6552.9  331.97  6703.4  330.87  6718.4  331.81
  6724.4  330.64  6739.5  331.96  6868.9  332.83  7007.4  336.22  7179.7  337.87
#Mann=3,-1,0
  2182.9    0.05       0  3613.1    0.03       0  6354.1    0.05       0
Bank Sta=3613.1,6354.1
Exp/Cntr=0.3,0.1

Type RM Length L Ch R = 1,9345,1242,1242,1242
BEGIN DESCRIPTION:
Mapping XS cb67e05d
END DESCRIPTION:
XS GIS Cut Line= 3
      2724010.00      6764013.03      2724430.51      6765685.30
      2726648.28      6767565.73
#Sta/Elev= 30
  3299.4  341.30  3338.6  342.15  3359.2  343.97  3485.2  343.37  3549.7  337.11
  3555.1  334.63  3581.5  330.92  3606.6  326.32  3607.7  322.00  4998.0  321.00
  7403.5  322.00  7436.9  322.65  7443.4  324.97  7451.2  329.72  7465.5  331.66
  7491.4  333.17  7500.6  333.12  7529.2  337.97  7535.7  337.41  7557.7  340.44
  7635.7  341.79  7667.1  341.47  7692.4  343.13  7748.8  344.10  7763.1  344.98
  7770.9  346.43  7787.0  346.20  7834.6  347.77  7872.6  347.89  7931.4  348.78
#Mann=9,-1,0
  3299.4    0.05       0  3485.2    0.12       0  3581.5    0.05       0
  3607.7    0.03       0  7403.5    0.05       0  7491.4    0.12       0
  7667.1    0.05       0  7787.0    0.12       0  7872.6    0.05       0
Bank Sta=3607.7,7403.5
Exp/Cntr=0.3,0.1

Type RM Length L Ch R = 1,8103,1383,1383,1383
BEGIN DESCRIPTION:
Mapping XS b4899b73
END DESCRIPTION:
XS GIS Cut Line= 3
      2723785.24      6763799.93      2723392.72      6766243.05
      2726499.97      6768622.14
#Sta/Elev= 30
  2558.0  337.84  2660.4  338.37  2741.4  334.50  2792.0  334.25  2822.4  329.86
  2873.1  329.51  2879.9  322.00  4998.0  321.00  8261.5  322.00  8299.6  322.00
  8307.8  323.78  8314.1  322.00  8322.3  326.37  8343.1  327.41  8364.0  325.95
  8457.4  330.55  8492.7  330.13  8507.3  332.06  8521.8  331.85  8542.6  327.63
  8557.1  330.12  8563.4  327.82  8607.0  335.81  8656.8  336.97  8685.9  340.32
  8703.2  340.38  8735.7  344.00  8828.0  347.84  8885.3  352.17  8945.9  353.15
#Mann=5,-1,0
  2558.0    0.05       0  2879.9    0.03       0  8261.5    0.05       0
  8703.2    0.12       0  8828.0    0.05       0
Bank Sta=2879.9,8261.5
Exp/Cntr=0.3,0.1

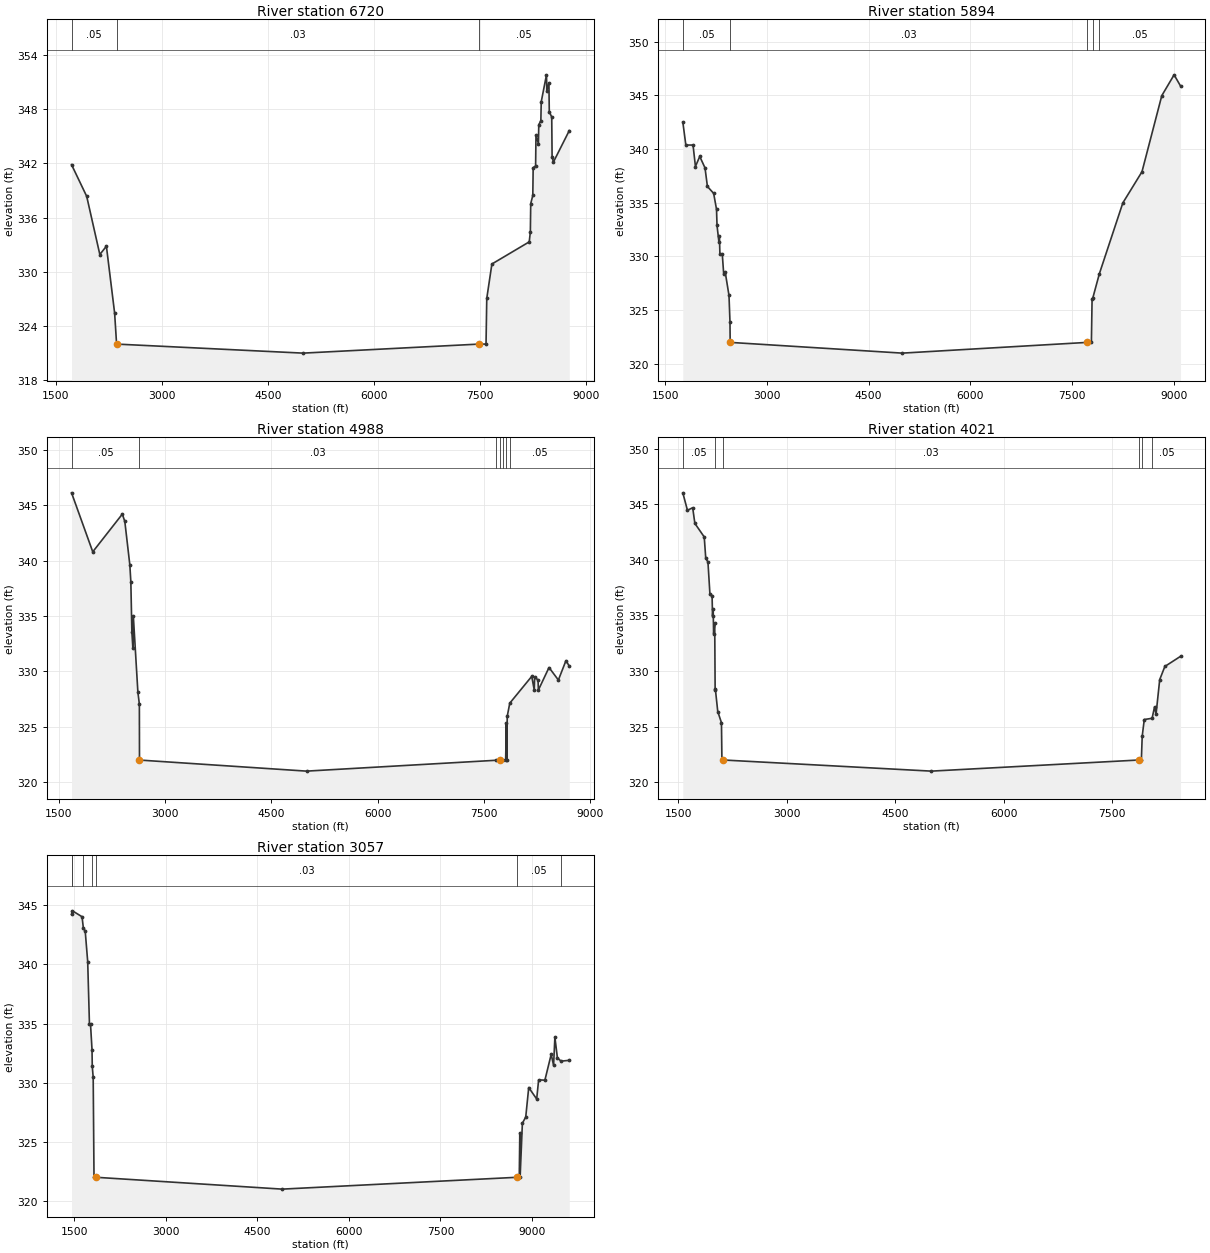
Type RM Length L Ch R = 1,6720,826,826,826
BEGIN DESCRIPTION:
Mapping XS b9cf0343
END DESCRIPTION:
XS GIS Cut Line= 3
      2723956.27      6763284.36      2722090.73      6766005.01
      2721106.28      6769617.46
#Sta/Elev= 30
  1722.3  341.85  1936.5  338.35  2122.5  331.91  2215.4  332.83  2331.7  325.44
  2359.7  322.00  4998.0  321.00  7488.3  322.00  7587.4  322.00  7597.8  327.05
  7670.3  330.86  8198.9  333.31  8214.7  334.43  8219.9  337.54  8249.2  338.44
  8254.4  341.51  8289.0  341.72  8294.2  345.08  8328.7  344.19  8333.9  346.27
  8363.3  346.71  8368.5  348.80  8442.8  351.79  8448.0  350.05  8477.3  350.88
  8482.5  347.70  8517.1  347.12  8522.3  342.72  8541.0  342.14  8765.3  345.62
#Mann=3,-1,0
  1722.3    0.05       0  2359.7    0.03       0  7488.3    0.05       0
Bank Sta=2359.7,7488.3
Exp/Cntr=0.3,0.1

Type RM Length L Ch R = 1,5894,906,906,906
BEGIN DESCRIPTION:
Caney Creek 6.0
END DESCRIPTION:
XS GIS Cut Line= 3
      2723674.60      6763236.32      2721426.00      6765561.00
      2720911.15      6769635.25
#Sta/Elev= 30
  1761.0  342.53  1805.8  340.38  1911.8  340.38  1947.3  338.38  2010.8  339.32
  2088.5  338.25  2124.0  336.52  2215.9  335.88  2258.3  334.39  2265.5  332.89
  2293.8  331.33  2300.8  331.90  2308.0  330.27  2343.2  330.22  2364.5  328.33
  2385.6  328.58  2442.2  326.37  2456.4  323.94  2459.7  322.00  4998.0  321.00
  7726.1  322.00  7787.3  322.00  7797.4  326.06  7806.2  326.09  7904.6  328.39
  8250.9  334.99  8533.2  337.89  8825.5  344.98  9006.9  346.92  9101.9  345.88
#Mann=5,-1,0
  1761.0    0.05       0  2459.7    0.03       0  7726.1    0.05       0
  7806.2    0.12       0  7904.6    0.05       0
Bank Sta=2459.7,7726.1
Exp/Cntr=0.3,0.1

Type RM Length L Ch R = 1,4988,967,967,967
BEGIN DESCRIPTION:
Caney Creek 5.0
END DESCRIPTION:
XS GIS Cut Line= 3
      2723117.67      6762870.06      2720676.00      6765111.00
      2720012.66      6768762.39
#Sta/Elev= 30
  1681.4  346.14  1980.7  340.81  2398.2  344.22  2433.3  343.55  2504.2  339.62
  2518.4  338.08  2532.6  333.60  2546.8  332.13  2553.5  335.00  2617.7  328.13
  2638.6  327.05  2640.3  322.00  4998.0  321.00  7671.8  321.98  7735.6  322.00
  7767.9  322.00  7808.7  322.00  7818.4  325.31  7823.5  322.00  7831.2  325.96
  7867.0  327.14  8176.8  329.56  8212.4  328.33  8217.5  329.46  8265.8  329.25
  8270.9  328.33  8420.7  330.36  8553.0  329.23  8659.8  330.98  8706.7  330.49
#Mann=7,-1,0
  1681.4    0.05       0  2640.3    0.03       0  7671.8   0.075       0
  7735.6    0.05       0  7767.9    0.05       0  7808.7   0.075       0
  7867.0    0.05       0
Bank Sta=2640.3,7735.6
Exp/Cntr=0.3,0.1

Type RM Length L Ch R = 1,4021,964,964,964
BEGIN DESCRIPTION:
Caney Creek 4.0
END DESCRIPTION:
XS GIS Cut Line= 3
      2722847.67      6762572.68      2719976.00      6764461.00
      2719397.61      6767854.57
#Sta/Elev= 30
  1563.1  346.02  1627.3  344.45  1699.6  344.68  1729.8  343.27  1859.3  342.05
  1880.4  340.12  1910.6  339.80  1937.6  336.95  1967.8  336.76  1973.8  334.94
  1982.9  335.55  1988.9  333.35  2004.0  334.29  2009.9  328.36  2014.0  328.32
  2046.1  326.36  2097.3  325.35  2103.7  322.00  2123.9  322.00  4998.0  321.00
  7870.0  322.00  7901.2  322.00  7912.8  324.14  7941.5  325.64  8049.5  325.75
  8083.8  326.79  8104.1  326.12  8154.8  329.23  8225.9  330.41  8442.5  331.32
#Mann=6,-1,0
  1563.1    0.05       0  2014.0    0.12       0  2123.9    0.03       0
  7870.0    0.12       0  7912.8   0.075       0  8049.5    0.05       0
Bank Sta=2123.9,7870
Exp/Cntr=0.3,0.1

Type RM Length L Ch R = 1,3057,0,0,0
BEGIN DESCRIPTION:
Caney Creek 3.0
END DESCRIPTION:
XS GIS Cut Line= 3
      2722559.36      6762306.21      2719326.00      6763761.00
      2718326.01      6768260.96
#Sta/Elev= 30
  1454.7  344.23  1468.8  344.53  1626.6  344.03  1648.8  343.05  1678.4  342.82
  1719.2  340.24  1747.8  334.99  1765.4  334.94  1790.2  332.78  1794.1  331.38
  1809.3  330.45  1822.7  322.00  1858.6  322.00  4905.8  321.00  8750.5  322.00
  8790.5  322.00  8799.5  325.76  8804.6  322.00  8841.7  326.57  8896.8  327.10
  8945.5  329.59  9076.1  328.62  9108.1  330.24  9210.5  330.21  9314.2  332.40
  9352.7  331.47  9374.4  333.84  9415.4  332.10  9474.7  331.82  9610.0  331.89
#Mann=7,-1,0
  1454.7    0.12       0  1468.8    0.05       0  1648.8    0.12       0
  1790.2    0.05       0  1858.6    0.03       0  8750.5    0.05       0
  9474.7    0.12       0
Bank Sta=1858.6,8750.5
Exp/Cntr=0.3,0.1

Chan Stop Cuts=-1