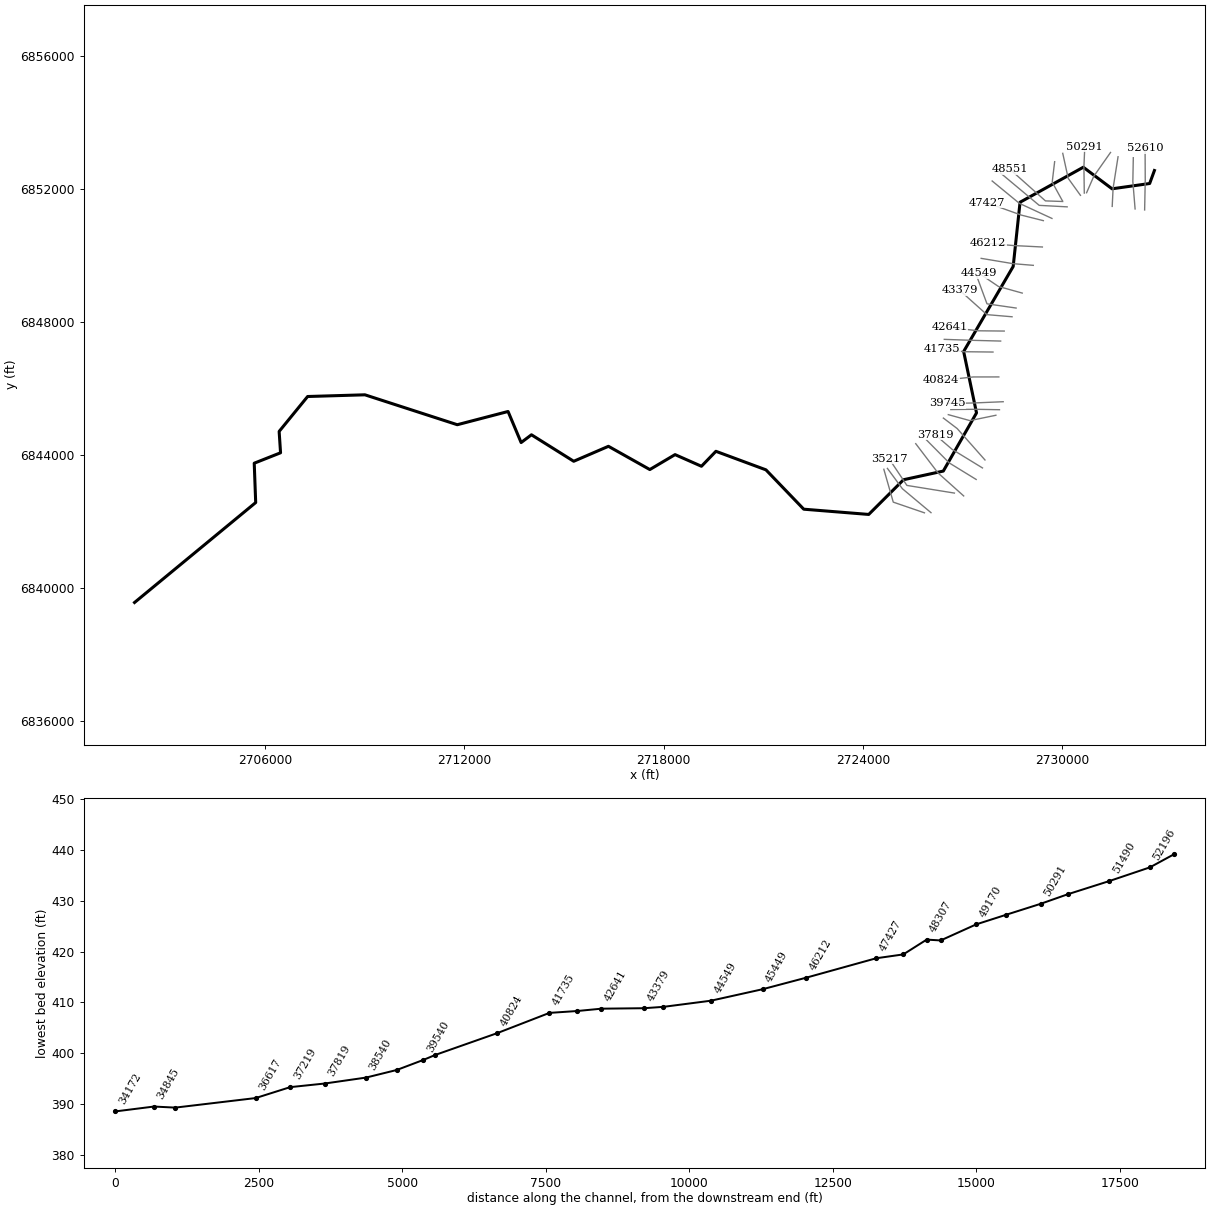
--- Caney Creek.prj (project) ---

Proj Title=Caney Creek Base Level Engineering
Current Plan=p01
Default Exp/Contr=0.3,0.1
English Units
Geom File=g01
Flow File=f01
Plan File=p01
Y Axis Title=Elevation
X Axis Title(PF)=Main Channel Distance
X Axis Title(XS)=Station
BEGIN DESCRIPTION:
Caney Creek
END DESCRIPTION:
DSS Export Rating Curves= 0
DSS Export Rating Curve Sorted= 0
DSS Export Volume Flow Curves= 0
DXF OffsetX= 0
DXF OffsetY= 0
DXF ScaleX= 1
DXF ScaleY= 10

--- Caney Creek.p01 (plan) ---

Plan Title=Multiple Run
Short Identifier=Multiple
Geom File=g01
Flow File=f01
Subcritical Flow
K Sum by GR= 0
Std Step Tol= 0.01
Critical Tol= 0.01
Num of Std Step Trials= 20
Max Error Tol= 0.3
Flow Tol Ratio= 0.001
Split Flow NTrial= 30
Split Flow Tol= 0.02
Split Flow Ratio= 0.02
Log Output Level= 0
Friction Slope Method= 1
Unsteady Friction Slope Method= 2
Unsteady Bridges Friction Slope Method= 1
Parabolic Critical Depth
Global Vel Dist=  1 , 1 , 1
Global Log Level= 0
CheckData=True
Encroach Param= -1, 0, 0, 0
BEGIN DESCRIPTION:
Multiple Run
END DESCRIPTION:

--- Caney Creek.f01 (steady flow) ---

Flow Title=Multiple
Number of Profiles=7
Profile Names=10-year,25-year,50-year,1pct_min,100-year,1pct_plu,500-year
River Rch & RM= Caney Creek,Reach-1,52610
     663     888    1069     639    1275    2543    1808
River Rch & RM= Caney Creek,Reach-1,50766
     741     994    1199     716    1429    2852    2030
River Rch & RM= Caney Creek,Reach-1,48551
    1390    1919    2359    1432    2858    5702    4196
River Rch & RM= Caney Creek,Reach-1,43722
    1401    1932    2371    1438    2868    5723    4200
River Rch & RM= Caney Creek,Reach-1,38540
    1789    2498    3091    1888    3767    7516    5601
River Rch & RM= Caney Creek,Reach-1,34845
    1847    2581    3196    1953    3897    7776    5799
River Rch & RM= Caney Creek,Reach-1,33570
    2013    2824    3506    2148    4285    8550    6407
River Rch & RM= Caney Creek,Reach-1,32823
    2047    2872    3565    2183    4356    8692    6510
River Rch & RM= Caney Creek,Reach-1,30806
    2019    2819    3487    2128    4246    8471    6298
River Rch & RM= Caney Creek,Reach-1,27619
    2139    2990    3702    2261    4511    9000    6701
River Rch & RM= Caney Creek,Reach-1,25857
    2448    3458    4313    2652    5292   10559    7975
River Rch & RM= Caney Creek,Reach-1,22097
    2929    4163    5212    3217    6418   12806    9740
River Rch & RM= Caney Creek,Reach-1,17442
    2900    4111    5138    3165    6314   12599    9545
River Rch & RM= Caney Creek,Reach-1,12521
    2988    4241    5306    3271    6526   13021    9881
Boundary for River Rch & Prof#=Caney Creek,Reach-1,1
Up Type=0
Dn Type=3
Dn Slope=0.005
Boundary for River Rch & Prof#=Caney Creek,Reach-1,2
Up Type=0
Dn Type=3
Dn Slope=0.005
Boundary for River Rch & Prof#=Caney Creek,Reach-1,3
Up Type=0
Dn Type=3
Dn Slope=0.005
Boundary for River Rch & Prof#=Caney Creek,Reach-1,4
Up Type=0
Dn Type=3
Dn Slope=0.005
Boundary for River Rch & Prof#=Caney Creek,Reach-1,5
Up Type=0
Dn Type=3
Dn Slope=0.005
Boundary for River Rch & Prof#=Caney Creek,Reach-1,6
Up Type=0
Dn Type=3
Dn Slope=0.005
Boundary for River Rch & Prof#=Caney Creek,Reach-1,7
Up Type=0
Dn Type=3
Dn Slope=0.005

--- Caney Creek.g01 (geometry) ---

Geom Title=Existing Conditions
Program Version=4.10

River Reach=Caney Creek     ,Reach-1
Reach XY= 30
        2732776.        6852561.      2732632.69      6852169.95
      2731500.96      6852010.49      2730635.66      6852659.65
      2728731.28       6851606.1      2728524.37      6849672.81
      2727033.58      6847114.35       2727420.9      6845266.69
      2726421.34      6843516.26      2725223.53      6843255.54
        2724176.        6842211.      2722219.84       6842368.9
      2721082.14      6843553.13        2719576.        6844111.
       2719141.2      6843660.51      2718346.13      6844011.33
      2717586.78      6843561.69      2716341.18      6844261.44
      2715296.03      6843811.07      2714023.91      6844608.07
      2713712.76      6844374.11      2713319.88      6845309.18
      2711791.42      6844911.03      2709010.79       6845811.1
      2707286.43      6845759.95      2706428.92      6844709.27
      2706471.35      6844066.26      2705678.78      6843752.82
      2705722.92      6842568.62        2702076.        6839561.

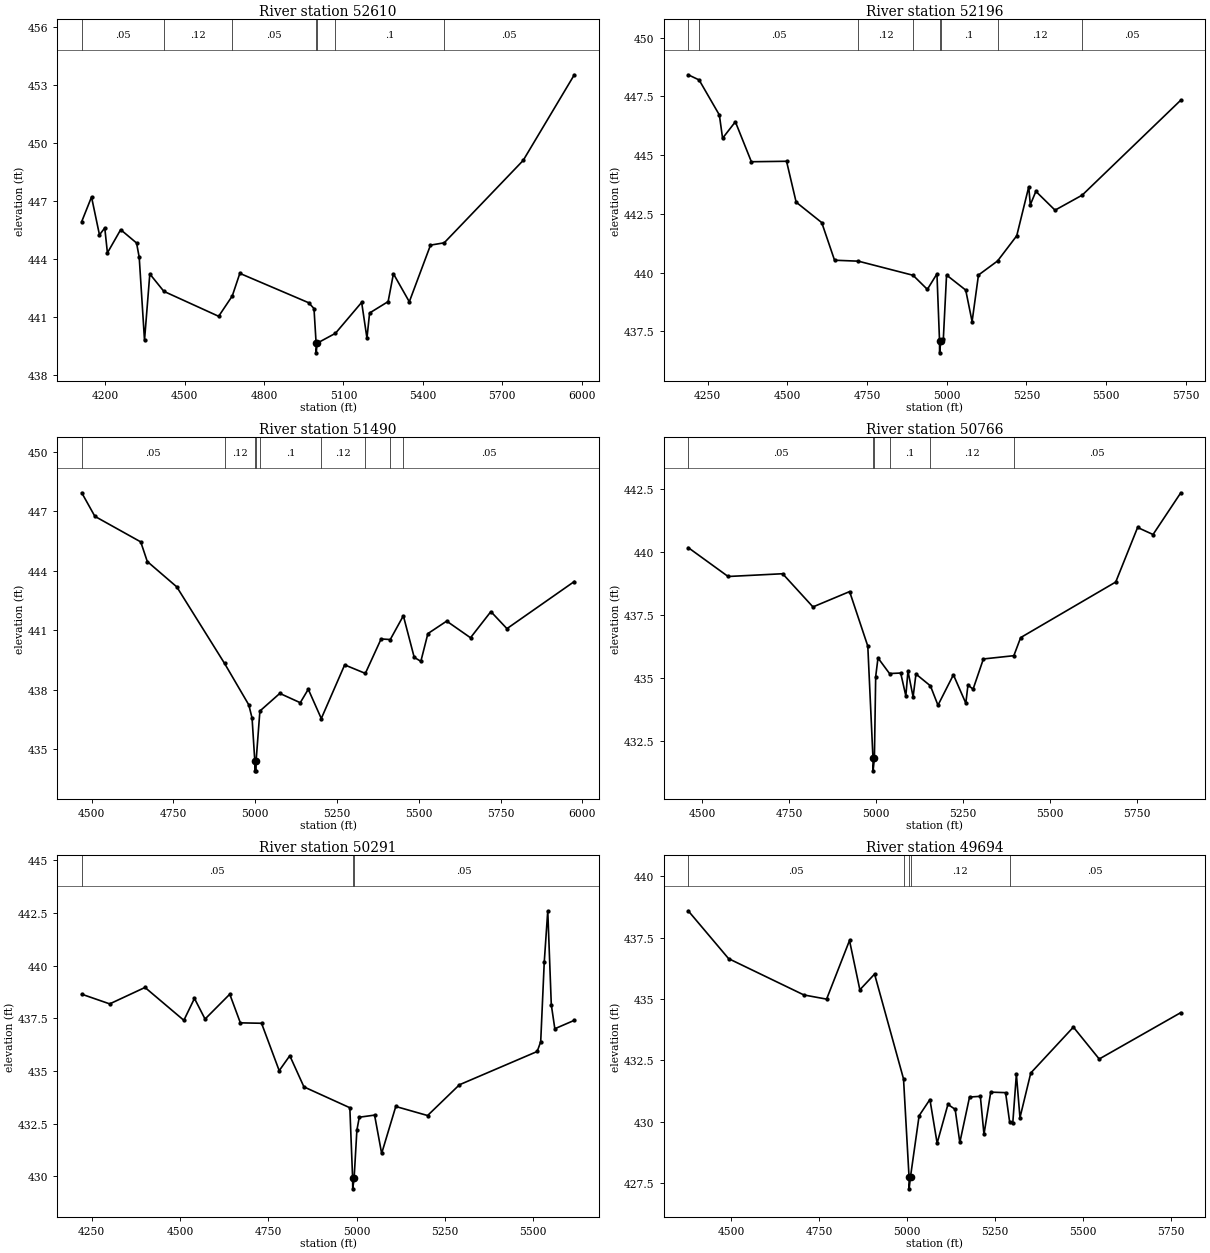
Type RM Length L Ch R = 1 ,52610   ,414,414,414
BEGIN DESCRIPTION:
Caney Creek 860
END DESCRIPTION:
XS GIS Cut Line= 3
      2732481.39      6851373.98      2732499.84      6852273.18
       2732494.8      6853234.18
#Sta/Elev= 30
  4111.8  445.92  4148.8  447.19  4178.8  445.23  4198.8  445.59  4208.8   444.3
  4258.9   445.5  4318.9  444.81  4328.9  444.07  4348.9  439.78  4368.9  443.21
    4422  442.31  4628.9  441.02  4680.3  442.07  4708.9  443.24    4969  441.72
    4989  441.42    4997  439.63  4997.3  439.13    5001  439.63    5070  440.14
    5169  441.74    5189  439.89    5199  441.19    5269  441.78    5289  443.22
    5349  441.77    5429   444.7  5480.8  444.82    5779  449.08  5972.2  453.51
#Mann= 7 ,-1 , 0
  4111.8     .05       0    4422     .12       0  4680.3     .05       0
    4997     .05       0    5001     .05       0    5070      .1       0
  5480.8     .05       0
Bank Sta=4997,5001
XS Rating Curve= 0 ,0
Exp/Cntr=0.3,0.1

Type RM Length L Ch R = 1 ,52196   ,706,706,706
BEGIN DESCRIPTION:
Caney Creek 862
END DESCRIPTION:
XS GIS Cut Line= 3
      2732194.32      6851403.59       2732126.3       6852233.2
      2732140.36      6852945.27
#Sta/Elev= 30
  4189.2  448.42  4223.4   448.2  4286.9  446.71    4297  445.72  4337.1  446.42
  4387.3  444.72  4497.6  444.74  4527.7     443    4608  442.13  4648.1  440.53
  4722.8  440.49  4894.2  439.89  4939.1  439.29  4969.2  439.95  4977.3  437.09
  4977.5  436.59  4981.3  437.09  4989.3   437.2  4999.3   439.9  5059.4  439.26
  5079.4  437.92  5099.4   439.9  5159.4   440.5  5219.4  441.57    5257  443.65
    5262  442.89  5279.4  443.46  5339.5  442.66  5424.7   443.3  5733.8  447.34
#Mann= 8 ,-1 , 0
  4189.2     .12       0  4223.4     .05       0  4722.8     .12       0
  4894.2      .1       0  4977.3     .07       0  4981.3      .1       0
  5159.4     .12       0  5424.7     .05       0
Bank Sta=4977.3,4981.3
XS Rating Curve= 0 ,0
Exp/Cntr=0.3,0.1

Type RM Length L Ch R = 1 ,51490   ,724,724,724
BEGIN DESCRIPTION:
Caney Creek 861
END DESCRIPTION:
XS GIS Cut Line= 3
      2731505.21      6851480.86      2731531.99      6852026.97
      2731681.22      6852974.52
#Sta/Elev= 30
  4469.5  447.94  4509.7  446.75  4649.9  445.46  4669.9  444.47    4760  443.19
  4906.3  439.32  4980.3  437.23  4990.3  436.56  4998.6   434.4  4998.9   433.9
  5002.4   433.9  5002.6   434.4  5014.2  436.92  5075.1  437.81  5137.6  437.34
  5162.1  438.02  5201.9  436.54  5273.4  439.25  5336.6  438.82  5384.8  440.56
  5412.8  440.53  5452.8  441.73    5486  439.63  5506.3  439.43  5527.8  440.83
  5585.3  441.46  5658.1  440.62  5720.4  441.94  5769.5  441.08  5975.5  443.46
#Mann= 9 ,-1 , 0
  4469.5     .05       0  4906.3     .12       0  4998.6     .07       0
  5002.6     .12       0  5014.2      .1       0  5201.9     .12       0
  5336.6      .1       0  5412.8     .12       0  5452.8     .05       0
Bank Sta=4998.6,5002.6
XS Rating Curve= 0 ,0
Exp/Cntr=0.3,0.1

Type RM Length L Ch R = 1 ,50766   ,475,475,475
BEGIN DESCRIPTION:
Caney Creek 847
END DESCRIPTION:
XS GIS Cut Line= 3
      2730734.44      6851892.17      2730950.43      6852386.48
      2731454.88      6853104.08
#Sta/Elev= 30
  4460.4  440.18  4575.2  439.03    4732  439.14  4819.2  437.82  4924.6  438.43
  4976.9  436.26  4991.8   431.8  4992.1   431.3  4995.9   431.8  4999.6  435.05
  5006.2  435.79  5039.4  435.17  5071.5  435.19  5086.3  434.28  5092.4  435.27
  5107.2  434.24  5115.4  435.15    5157  434.68  5178.7  433.91  5223.1  435.12
  5258.8  433.99  5264.9  434.71  5279.7  434.55  5309.3  435.75  5396.9  435.88
  5416.5   436.6  5689.9  438.81  5752.8  440.98  5797.2   440.7    5877  442.36
#Mann= 6 ,-1 , 0
  4460.4     .05       0  4991.8     .04       0  4995.9     .05       0
  5039.4      .1       0    5157     .12       0  5396.9     .05       0
Bank Sta=4991.8,4995.9
XS Rating Curve= 0 ,0
Exp/Cntr=0.3,0.1

Type RM Length L Ch R = 1 ,50291   ,597,597,597
BEGIN DESCRIPTION:
Caney Creek 846
END DESCRIPTION:
XS GIS Cut Line= 3
      2730664.92      6851881.85      2730653.73      6852669.57
      2730679.84      6853276.11
#Sta/Elev= 30
  4221.8  438.65    4301  438.19    4401  438.97    4511  437.41    4541  438.45
    4571  437.47    4641  438.65    4671  437.29    4731  437.27    4781  435.02
    4811  435.73    4851  434.25    4981  433.26  4988.9  429.91  4989.2  429.41
  4993.1  429.91    5001   432.2  5007.8  432.81  5051.1  432.91  5071.1  431.09
  5111.1  433.32  5201.2  432.89  5291.3  434.35  5511.5  435.93  5521.5  436.39
  5531.5  440.16  5541.5  442.61  5551.5  438.15  5561.5  437.01  5616.7  437.41
#Mann= 3 ,-1 , 0
  4221.8     .05       0  4988.9     .04       0  4993.1     .05       0
Bank Sta=4988.9,4993.1
XS Rating Curve= 0 ,0
Exp/Cntr=0.3,0.1

Type RM Length L Ch R = 1 ,49694   ,524,524,524
BEGIN DESCRIPTION:
Caney Creek 845
END DESCRIPTION:
XS GIS Cut Line= 3
      2730549.03      6851814.21      2730180.89      6852325.09
      2730016.63      6853077.47
#Sta/Elev= 30
  4377.4   438.6  4492.2  436.65  4706.2  435.17  4770.7     435  4835.8  437.39
  4865.2  435.38    4907  436.02  4989.3  431.75  5004.9  427.77  5005.2  427.27
  5009.2  427.77  5033.6  430.25  5064.3  430.91  5084.8  429.13  5115.5  430.71
    5136  430.51  5149.3  429.16  5176.9  431.01  5207.6  431.04  5217.9  429.49
  5237.1  431.21  5279.3  431.19  5290.8     430  5299.7  429.94    5310  431.94
  5320.2  430.17  5350.9  431.99    5472  433.86  5545.4  432.56  5777.2  434.45
#Mann= 5 ,-1 , 0
  4377.4     .05       0  4989.3     .12       0  5004.9     .07       0
  5009.2     .12       0  5290.8     .05       0
Bank Sta=5004.9,5009.2
XS Rating Curve= 0 ,0
Exp/Cntr=0.3,0.1

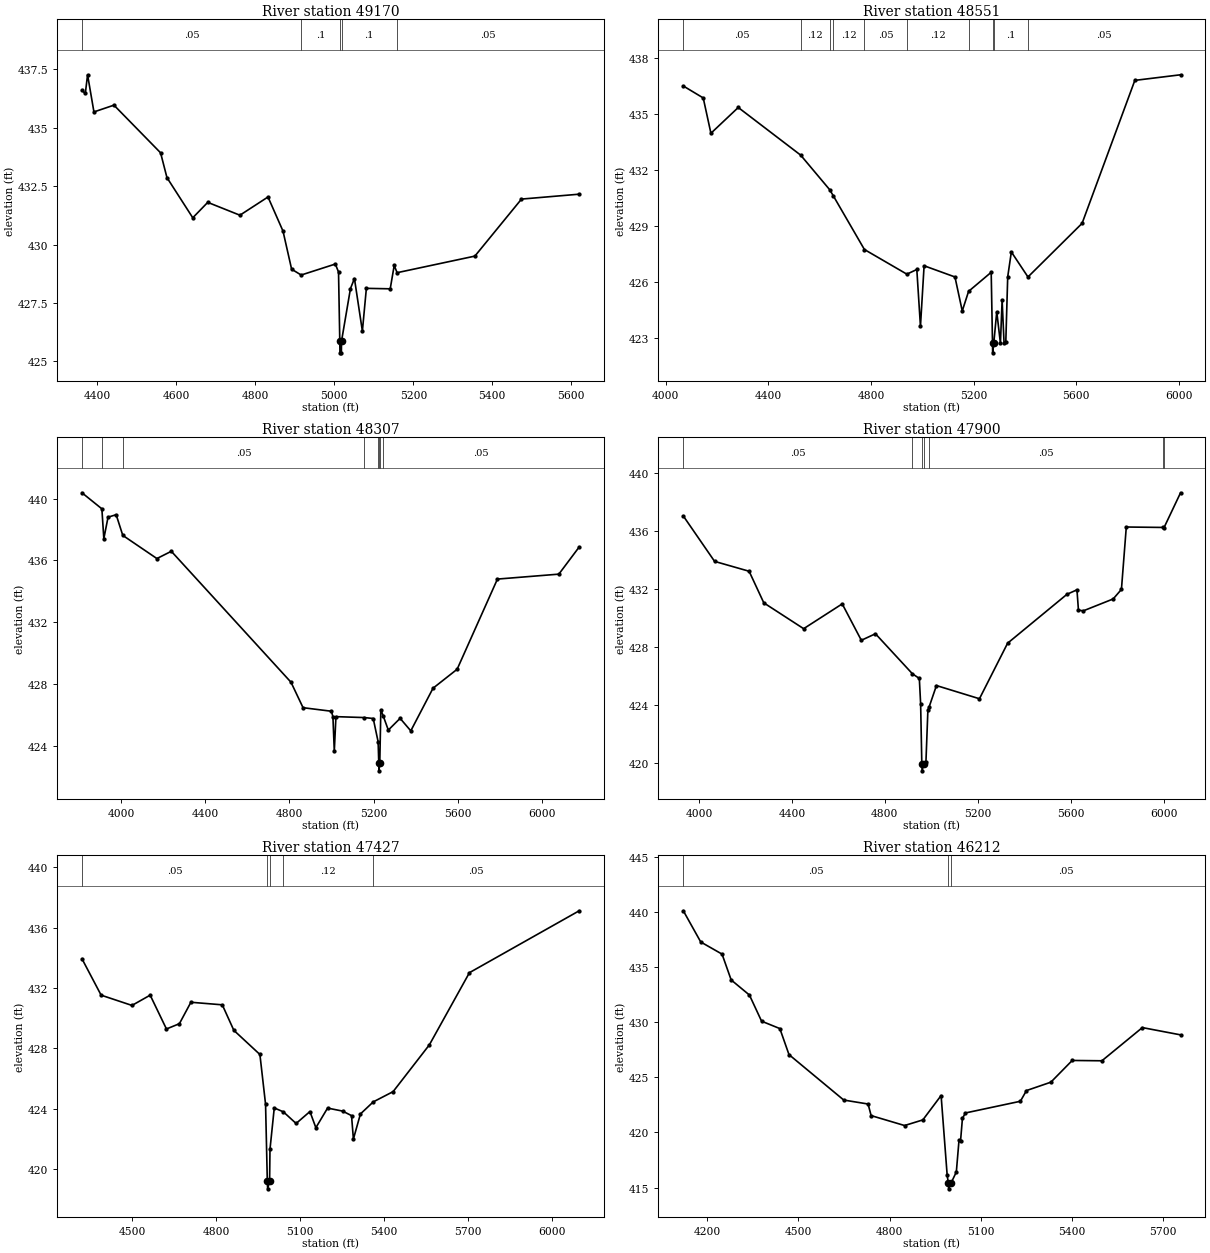
Type RM Length L Ch R = 1 ,49170   ,619,619,619
BEGIN DESCRIPTION:
Caney Creek 844
END DESCRIPTION:
XS GIS Cut Line= 3
      2730005.84      6851649.93      2729698.98      6852209.86
      2729772.59      6852826.18
#Sta/Elev= 30
  4360.9   436.6  4369.4  436.47  4375.1  437.27  4391.2  435.68  4441.9  435.97
    4560  433.93  4576.1  432.87  4641.5  431.15  4679.4  431.81  4760.9  431.26
    4832  432.04    4870  430.58  4891.8  428.95    4916   428.7  5002.5  429.17
  5010.6  428.83  5013.8  425.87  5014.2  425.37  5017.8  425.37  5018.2  425.87
  5040.8  428.12  5050.9  428.55    5071   426.3  5081.1  428.13  5141.5  428.11
  5151.6  429.11  5158.9   428.8  5355.9  429.51  5473.9  431.95  5620.1  432.16
#Mann= 5 ,-1 , 0
  4360.9     .05       0    4916      .1       0  5013.8     .07       0
  5018.2      .1       0  5158.9     .05       0
Bank Sta=5013.8,5018.2
XS Rating Curve= 0 ,0
Exp/Cntr=0.3,0.1

Type RM Length L Ch R = 1 ,48551   ,244,244,244
BEGIN DESCRIPTION:
Caney Creek 849
END DESCRIPTION:
XS GIS Cut Line= 3
      2730013.66      6851628.45       2729495.6      6851646.58
       2728434.4      6852591.49
#Sta/Elev= 30
    4068  436.49  4145.7  435.85  4175.7  433.96  4282.3  435.34  4525.7  432.79
  4638.9  430.94  4653.1  430.61  4774.3  427.74  4939.9  426.42  4978.7  426.67
  4992.9  423.63  5007.1  426.87  5127.5  426.27  5155.9  424.45  5180.6   425.5
  5268.8  426.52  5273.9  422.71  5274.5  422.21  5278.7  422.71  5290.5  424.41
  5304.8  422.72  5311.4  425.02    5319  422.73  5325.7  422.77  5333.2  426.28
  5347.4  427.61  5412.2  426.27  5623.3  429.14    5829  436.79  6007.3  437.09
#Mann= 10 ,-1 , 0
    4068     .05       0  4525.7     .12       0  4638.9     .05       0
  4653.1     .12       0  4774.3     .05       0  4939.9     .12       0
  5180.6      .1       0  5273.9     .07       0  5278.7      .1       0
  5412.2     .05       0
Bank Sta=5273.9,5278.7
XS Rating Curve= 0 ,0
Exp/Cntr=0.3,0.1

Type RM Length L Ch R = 1 ,48307   ,407,407,407
BEGIN DESCRIPTION:
Caney Creek 848
END DESCRIPTION:
XS GIS Cut Line= 3
      2730149.63      6851467.13      2729307.84      6851512.29
      2728143.25      6852485.03
#Sta/Elev= 30
    3815  440.38  3909.5  439.34  3918.8  437.41  3938.8   438.8  3977.3  438.96
  4008.8  437.62  4170.7  436.12  4239.2  436.59  4807.2  428.11  4864.5  426.46
  4999.2  426.23  5006.3  425.87  5012.8  423.65  5020.6  425.88    5156  425.82
  5197.6  425.76  5220.9  424.25  5223.9  422.87  5224.4  422.37  5228.7  422.87
  5233.7  426.33  5244.7  425.94  5269.2  425.01  5325.2  425.77  5375.9  424.96
  5481.4  427.72  5595.9  428.95  5787.2  434.79  6078.7  435.11  6175.4  436.87
#Mann= 8 ,-1 , 0
    3815     .05       0  3909.5     .12       0  4008.8     .05       0
    5156      .1       0  5220.9     .12       0  5223.9     .04       0
  5228.7     .12       0  5244.7     .05       0
Bank Sta=5223.9,5228.7
XS Rating Curve= 0 ,0
Exp/Cntr=0.3,0.1

Type RM Length L Ch R = 1 ,47900   ,473,473,473
BEGIN DESCRIPTION:
Caney Creek 843
END DESCRIPTION:
XS GIS Cut Line= 3
       2729691.6      6851118.65      2728711.67       6851571.9
      2727891.81       6852245.4
#Sta/Elev= 30
  3932.6  437.03  4067.3   433.9  4215.9  433.22  4279.2  431.04  4450.7  429.26
  4616.7  430.97    4699  428.46  4759.8  428.91    4919  426.15  4948.7  425.83
  4954.3  424.09  4959.4  419.96  4960.6  419.46  4967.4  419.96  4977.2   420.1
  4985.5  423.62  4991.2  423.88  5022.4  425.34  5207.5  424.43  5328.8  428.26
  5584.2  431.63  5627.3  431.94  5633.7  430.54  5654.6  430.49  5783.2  431.31
  5818.8  431.97  5839.7  436.27  5998.2  436.24  6001.6  436.21  6073.3  438.63
#Mann= 7 ,-1 , 0
  3932.6     .05       0    4919     .12       0  4959.4     .04       0
  4967.4     .12       0  4991.2     .05       0  5998.2     .12       0
  6001.6     .05       0
Bank Sta=4959.4,4967.4
XS Rating Curve= 0 ,0
Exp/Cntr=0.3,0.1

Type RM Length L Ch R = 1 ,47427   ,1215,1215,1215
BEGIN DESCRIPTION:
Caney Creek 842
END DESCRIPTION:
XS GIS Cut Line= 3
      2729432.47      6851051.96      2728771.37      6851218.28
      2727739.67      6851587.57
#Sta/Elev= 30
  4320.4  433.94  4388.9  431.53  4499.1  430.85  4564.2  431.53  4622.4  429.29
  4668.7  429.64  4709.8  431.06    4822  430.89  4863.3   429.2  4956.5   427.6
  4976.7   424.3    4983   419.2  4984.2   418.7  4991.1   419.2  4992.5  421.32
  5007.8  424.06  5040.4   423.8  5085.9  423.03  5135.3  423.82  5156.5  422.75
  5198.4  424.05  5252.1  423.85    5284  423.55  5290.7     422  5315.8  423.66
  5361.7  424.46  5432.7  425.14  5562.3  428.24  5705.5  433.02  6097.9  437.12
#Mann= 5 ,-1 , 0
  4320.4     .05       0    4983     .04       0  4991.1     .05       0
  5040.4     .12       0  5361.7     .05       0
Bank Sta=4983,4991.1
XS Rating Curve= 0 ,0
Exp/Cntr=0.3,0.1

Type RM Length L Ch R = 1 ,46212   ,763,763,763
BEGIN DESCRIPTION:
Caney Creek 841
END DESCRIPTION:
XS GIS Cut Line= 3
      2729403.32      6850258.99      2728524.81      6850303.32
      2727770.79      6850367.88
#Sta/Elev= 30
  4121.1   440.1  4178.5  437.27  4248.6  436.17  4278.6  433.83  4338.7  432.46
  4378.7  430.09  4438.8  429.42  4468.9  427.06  4649.1  422.94  4729.2  422.58
  4739.2  421.53  4849.3  420.63  4909.4  421.14  4969.5  423.35  4989.5  416.11
  4993.4  415.39  4994.6  414.89  5001.8  415.39  5019.6  416.42  5028.4  419.29
  5033.4  419.21  5039.7  421.28  5049.7  421.77  5230.4  422.83  5250.4   423.8
  5330.7  424.56    5401  426.53  5498.7   426.5  5631.8  429.51  5757.5  428.85
#Mann= 3 ,-1 , 0
  4121.1     .05       0  4993.4     .04       0  5001.8     .05       0
Bank Sta=4993.4,5001.8
XS Rating Curve= 0 ,0
Exp/Cntr=0.3,0.1

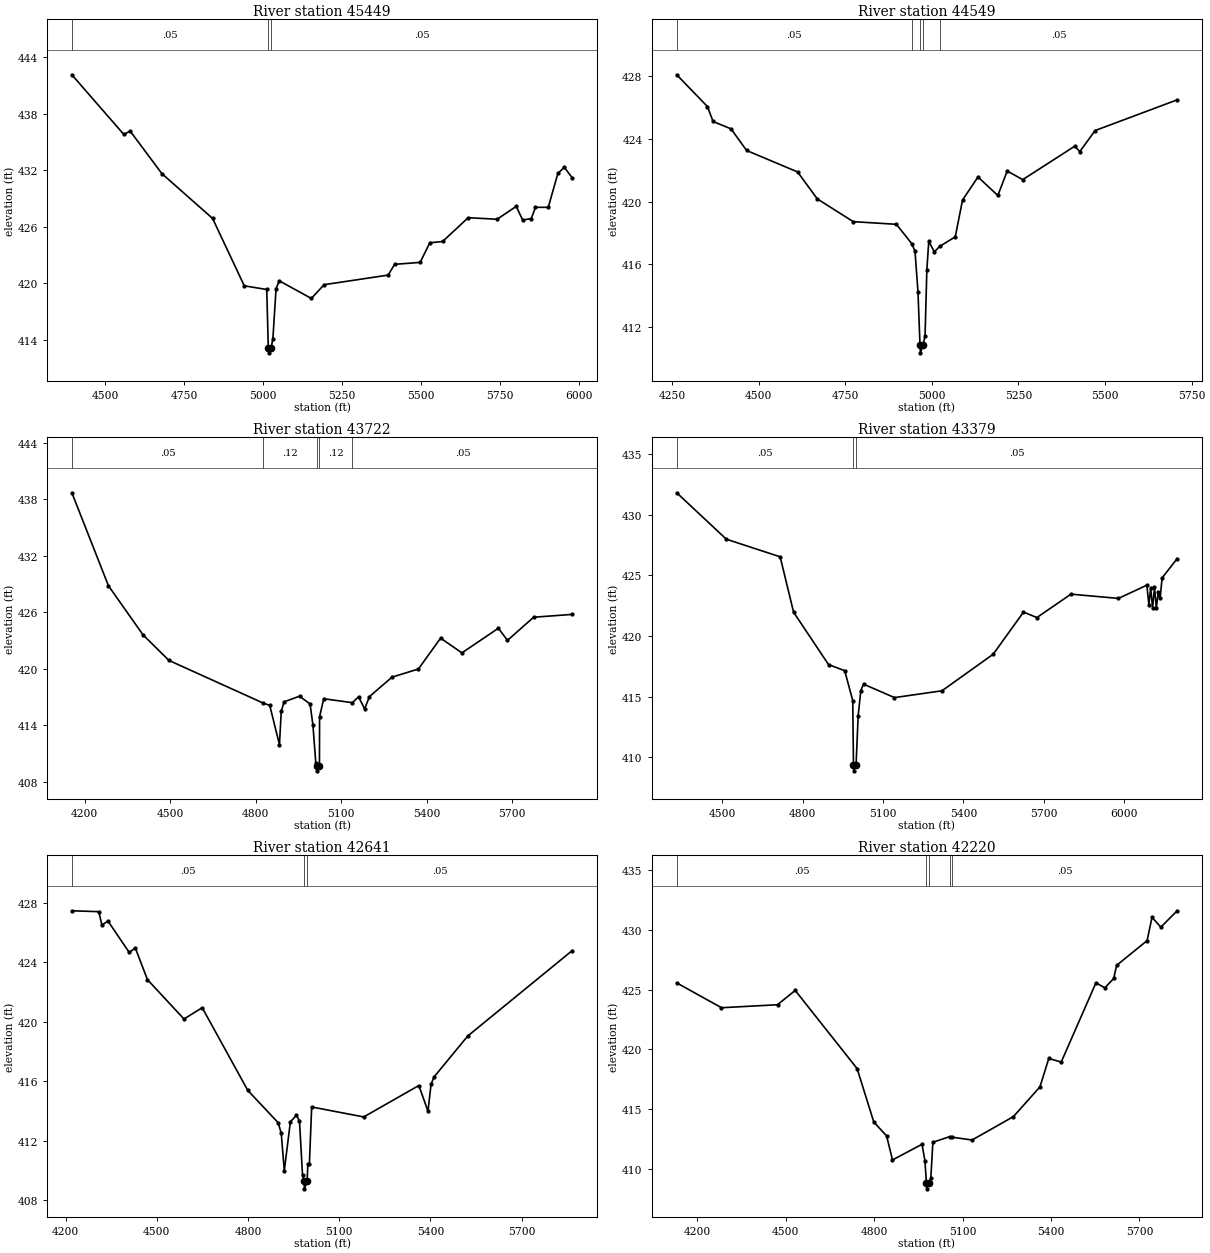
Type RM Length L Ch R = 1 ,45449   ,900,900,900
BEGIN DESCRIPTION:
Caney Creek 840
END DESCRIPTION:
XS GIS Cut Line= 3
       2729129.9      6849707.07      2728519.25      6849757.68
      2727560.95      6849917.04
#Sta/Elev= 30
  4394.4  442.15  4558.9  435.81  4578.9  436.17  4679.3  431.65  4839.8  426.89
  4940.2  419.73  5011.3  419.34  5016.2  413.11  5017.5  412.61  5024.9  413.11
  5030.7   414.1  5040.8  419.44    5051  420.26  5152.4  418.39  5192.9  419.85
  5395.7  420.87  5415.9  422.01    5497  422.22  5527.4   424.3    5568  424.44
  5649.1  426.97  5740.3   426.8  5801.1  428.17  5821.4  426.72  5848.6  426.87
    5862  428.07  5902.5  428.07  5932.9  431.67  5953.2  432.32  5978.6  431.19
#Mann= 3 ,-1 , 0
  4394.4     .05       0  5016.2     .04       0  5024.9     .05       0
Bank Sta=5016.2,5024.9
XS Rating Curve= 0 ,0
Exp/Cntr=0.3,0.1

Type RM Length L Ch R = 1 ,44549   ,827,827,827
BEGIN DESCRIPTION:
Caney Creek 839
END DESCRIPTION:
XS GIS Cut Line= 3
      2728797.02      6848872.33      2728080.04      6849071.98
      2727499.54       6849464.3
#Sta/Elev= 30
  4263.3  428.09  4352.1  426.06  4368.2  425.11  4420.1  424.64  4465.1  423.26
  4612.3  421.89  4669.2  420.17    4773  418.72  4897.6  418.55  4942.1  417.31
  4951.3  416.83  4959.9  414.22  4965.7  410.85    4967  410.35  4974.7  410.85
  4980.3  411.45  4985.5  415.64    4991  417.47  5007.1  416.79  5022.4  417.14
  5067.5  417.75  5088.5   420.1  5133.1  421.57  5190.4  420.39  5217.6  421.95
  5262.3   421.4  5412.2  423.53  5427.2  423.19  5471.1  424.53  5708.2  426.49
#Mann= 5 ,-1 , 0
  4263.3     .05       0  4942.1     .12       0  4965.7     .07       0
  4974.7     .12       0  5022.4     .05       0
Bank Sta=4965.7,4974.7
XS Rating Curve= 0 ,0
Exp/Cntr=0.3,0.1

Type RM Length L Ch R = 1 ,43722   ,343,343,343
BEGIN DESCRIPTION:
Caney Creek 838
END DESCRIPTION:
XS GIS Cut Line= 3
      2728612.97      6848422.08      2727736.15      6848548.72
      2727434.32      6849364.24
#Sta/Elev= 30
  4155.4  438.68  4283.7   428.8  4404.9  423.59  4495.9  420.87  4827.2  416.33
  4849.5   416.1  4883.6  411.92  4889.9  415.48    4900  416.47    4954  417.07
    4991  416.24  5001.1  413.97  5011.2  409.92  5014.5  409.64  5015.8  409.14
  5023.9  409.64  5024.3  414.89  5038.9   416.8  5139.6  416.38    5161  417.01
  5182.4  415.72  5199.3  417.03  5278.3  419.09    5371  419.96  5448.9  423.24
  5523.6  421.67  5651.5  424.29  5683.5     423  5775.3  425.46  5910.9  425.76
#Mann= 5 ,-1 , 0
  4155.4     .05       0  4827.2     .12       0  5014.5     .07       0
  5023.9     .12       0  5139.6     .05       0
Bank Sta=5014.5,5023.9
XS Rating Curve= 0 ,0
Exp/Cntr=0.3,0.1

Type RM Length L Ch R = 1 ,43379   ,738,738,738
BEGIN DESCRIPTION:
Caney Creek 837
END DESCRIPTION:
XS GIS Cut Line= 3
      2728490.65      6848159.44      2727732.74      6848223.93
       2726907.7      6848962.23
#Sta/Elev= 30
  4329.9   431.8  4515.2  427.97  4715.9  426.52  4766.1  421.95  4896.6  417.63
  4956.8  417.13  4986.9  414.66  4989.6  409.37    4991  408.87  4999.3  409.37
    5007  413.39    5017  415.49  5027.1  416.02  5142.6  414.91  5319.8  415.47
  5511.2  418.49  5624.1  421.96  5674.2  421.51  5801.3  423.44  5978.5  423.09
  6084.6  424.18  6092.1  422.55  6098.9  423.97    6106  422.29  6113.1  424.03
  6119.8  422.32  6127.3   423.6    6134  423.09  6141.5  424.78  6197.7  426.37
#Mann= 3 ,-1 , 0
  4329.9     .05       0  4989.6     .04       0  4999.3     .05       0
Bank Sta=4989.6,4999.3
XS Rating Curve= 0 ,0
Exp/Cntr=0.3,0.1

Type RM Length L Ch R = 1 ,42641   ,421,421,421
BEGIN DESCRIPTION:
Caney Creek 836
END DESCRIPTION:
XS GIS Cut Line= 3
       2728254.7      6847729.62       2727476.1      6847737.35
      2726614.55      6847838.41
#Sta/Elev= 30
  4220.5  427.46  4309.2   427.4  4319.2   426.5  4339.2  426.77  4409.2  424.66
  4429.2  424.96  4469.2  422.83  4589.2  420.19  4649.2  420.95  4799.2  415.39
  4899.2  413.22  4909.2  412.51  4919.2     410  4939.2  413.28  4959.2  413.72
  4969.2  413.33  4979.2  409.69  4984.2  409.28  4985.6  408.78  4994.2  409.28
  4996.7  410.44  5001.7  410.44  5009.3  414.28  5180.5  413.61  5361.7  415.72
  5391.9     414    5402  415.81  5411.9   416.3  5522.8  419.05  5866.6  424.79
#Mann= 3 ,-1 , 0
  4220.5     .05       0  4984.2     .04       0  4994.2     .05       0
Bank Sta=4984.2,4994.2
XS Rating Curve= 0 ,0
Exp/Cntr=0.3,0.1

Type RM Length L Ch R = 1 ,42220   ,485,485,485
BEGIN DESCRIPTION:
Caney Creek 835
END DESCRIPTION:
XS GIS Cut Line= 3
       2728147.9      6847428.39      2727277.17      6847451.28
      2726450.68      6847479.54
#Sta/Elev= 30
  4130.2  425.57  4282.1  423.49  4472.2  423.74  4532.2  424.94  4742.3  418.39
  4798.8  413.92  4842.3  412.75  4862.3  410.74  4962.4  412.05  4972.4  410.67
  4977.3  408.82  4978.7  408.32  4987.4  408.82  4992.4  409.23  4999.3  412.22
    5056  412.69    5064  412.65  5132.5  412.41  5272.6  414.37  5362.6  416.86
  5392.6  419.24  5434.8  418.94  5552.7  425.58  5582.7  425.15  5612.8  425.94
  5622.8  427.04  5726.2  429.11  5742.8  431.06  5772.8  430.24  5828.2  431.61
#Mann= 5 ,-1 , 0
  4130.2     .05       0  4977.3     .04       0  4987.4     .05       0
    5056     .12       0    5064     .05       0
Bank Sta=4977.3,4987.4
XS Rating Curve= 0 ,0
Exp/Cntr=0.3,0.1

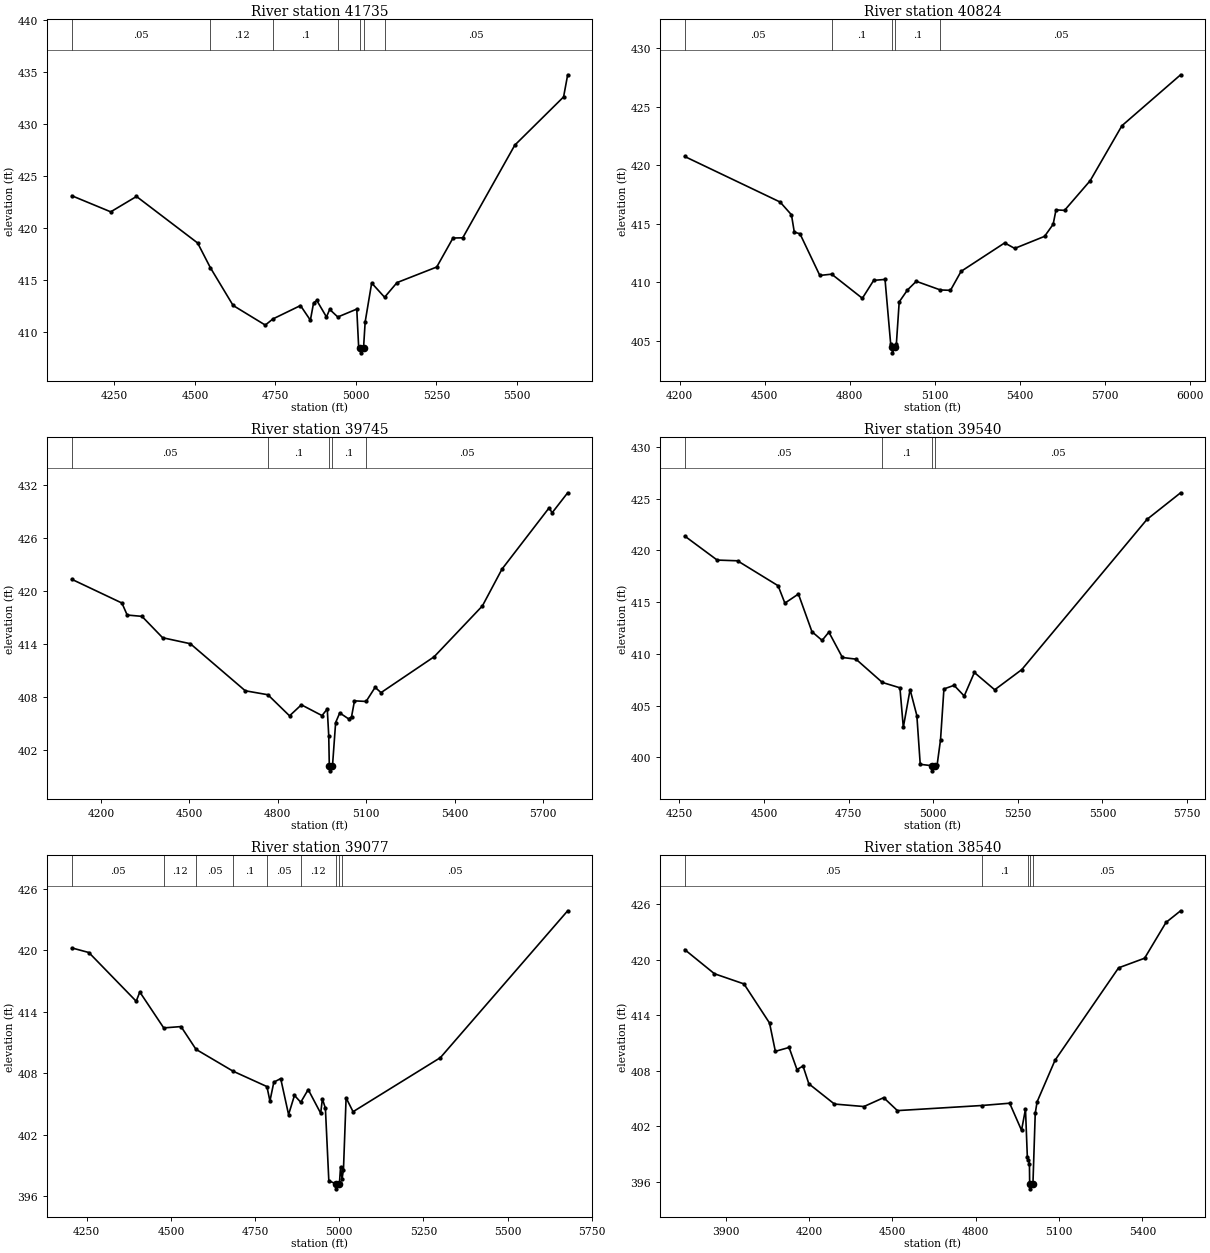
Type RM Length L Ch R = 1 ,41735   ,911,911,911
BEGIN DESCRIPTION:
Caney Creek 833
END DESCRIPTION:
XS GIS Cut Line= 3
      2727917.02      6847098.27      2727031.85      6847107.84
      2726383.42      6847200.91
#Sta/Elev= 30
  4117.4  423.07  4238.4  421.52  4318.4     423  4508.4  418.52  4547.6  416.16
  4618.5  412.51  4718.5  410.62    4742  411.21  4827.8   412.5  4858.5  411.09
  4868.5  412.76  4878.5  412.99  4908.5   411.4  4918.5  412.13  4943.7   411.4
  5002.6  412.16  5008.5   408.5  5013.6  408.45    5015  407.95  5023.7  408.45
  5028.7  410.93  5048.9  414.67    5089   413.3  5127.6  414.71    5251  416.21
  5301.5     419  5331.8  419.02  5493.5  427.94    5645  432.58  5657.7  434.71
#Mann= 7 ,-1 , 0
  4117.4     .05       0  4547.6     .12       0    4742      .1       0
  4943.7     .12       0  5013.6     .07       0  5023.7     .12       0
    5089     .05       0
Bank Sta=5013.6,5023.7
XS Rating Curve= 0 ,0
Exp/Cntr=0.3,0.1

Type RM Length L Ch R = 1 ,40824   ,1079,1079,1079
BEGIN DESCRIPTION:
Caney Creek 834
END DESCRIPTION:
XS GIS Cut Line= 3
      2728092.46      6846349.06      2727325.03       6846348.4
      2726348.99      6846243.46
#Sta/Elev= 30
  4217.7  420.73  4554.2  416.84  4594.2  415.75  4604.2  414.27  4624.2  414.13
  4694.2  410.57  4736.1  410.68  4844.2  408.62  4884.2  410.15  4924.2  410.23
  4944.2   404.7  4948.9  404.46  4950.4  403.96  4959.4  404.46  4964.2  404.71
  4974.2  408.31  5003.4  409.33  5034.4  410.07  5119.5  409.33  5155.1   409.3
  5192.5  410.92  5346.2  413.35  5381.6  412.88    5487  413.91  5517.2  414.94
  5527.3  416.17  5557.4  416.13    5648  418.67  5759.8  423.36  5966.8  427.71
#Mann= 5 ,-1 , 0
  4217.7     .05       0  4736.1      .1       0  4948.9     .07       0
  4959.4      .1       0  5119.5     .05       0
Bank Sta=4948.9,4959.4
XS Rating Curve= 0 ,0
Exp/Cntr=0.3,0.1

Type RM Length L Ch R = 1 ,39745   ,205,205,205
BEGIN DESCRIPTION:
Caney Creek 832
END DESCRIPTION:
XS GIS Cut Line= 3
      2728223.75      6845603.14      2727328.69      6845564.85
       2726543.2       6845550.8
#Sta/Elev= 30
  4101.5  421.37  4271.5  418.68  4289.4  417.32  4339.5  417.17  4409.5  414.75
  4503.6  414.07  4689.8  408.74  4766.5  408.29  4839.9   405.9    4880  407.15
    4950  405.93  4967.8  406.68  4972.8  403.66  4974.8  400.17  4976.2  399.67
  4985.4  400.17  4996.2  405.14  5010.1  406.23  5040.1  405.56  5050.1  405.79
  5060.1   407.6  5099.5  407.53  5130.1  409.13  5150.1  408.53  5330.1  412.59
  5493.8  418.35  5560.2  422.52  5720.2  429.47  5730.2   428.9    5783  431.17
#Mann= 5 ,-1 , 0
  4101.5     .05       0  4766.5      .1       0  4974.8     .07       0
  4985.4      .1       0  5099.5     .05       0
Bank Sta=4974.8,4985.4
XS Rating Curve= 0 ,0
Exp/Cntr=0.3,0.1

Type RM Length L Ch R = 1 ,39540   ,463,463,463
BEGIN DESCRIPTION:
Caney Creek 831
END DESCRIPTION:
XS GIS Cut Line= 3
      2728111.93       6845362.4      2727373.51      6845375.41
      2726646.59      6845367.05
#Sta/Elev= 30
  4265.6  421.38  4361.5  419.06  4421.6  418.99  4541.6  416.58  4561.6   414.9
  4601.6  415.78  4641.6  412.14  4671.6   411.3  4691.6   412.1  4731.6  409.65
  4771.6  409.49  4849.5  407.24  4901.6  406.72  4911.6   402.9  4931.6  406.55
  4951.6  404.04  4961.6  399.33    4995   399.2  4996.5   398.7  5005.7   399.2
  5011.6  399.29  5021.6  401.71  5031.6  406.61  5061.6  406.96  5091.6  405.93
  5121.6   408.2  5181.7  406.53  5261.7  408.48  5631.7  422.99  5731.1  425.56
#Mann= 4 ,-1 , 0
  4265.6     .05       0  4849.5      .1       0    4995     .07       0
  5005.7     .05       0
Bank Sta=4995,5005.7
XS Rating Curve= 0 ,0
Exp/Cntr=0.3,0.1

Type RM Length L Ch R = 1 ,39077   ,537,537,537
BEGIN DESCRIPTION:
Caney Creek 812
END DESCRIPTION:
XS GIS Cut Line= 3
      2728003.96      6845195.56      2727221.91      6845034.38
      2726571.44      6845213.97
#Sta/Elev= 30
  4205.4  420.21  4256.1  419.76  4396.8  415.01  4407.5  415.91  4478.6  412.41
    4530  412.54  4574.5  410.32  4684.6  408.19  4785.2  406.69  4794.1  405.28
  4805.7  407.12  4826.1  407.47  4849.5  403.96    4867  405.83  4885.7  405.16
  4907.8   406.4  4944.9  404.09    4950  405.49  4958.9  404.58  4969.1   397.5
  4989.8  397.22  4991.3  396.72  5000.6  397.22  5003.9  398.86  5008.4  397.68
  5012.6   398.6  5020.4  405.59  5041.1  404.24  5300.5  409.51  5678.7  423.83
#Mann= 9 ,-1 , 0
  4205.4     .05       0  4478.6     .12       0  4574.5     .05       0
  4684.6      .1       0  4785.2     .05       0  4885.7     .12       0
  4989.8     .07       0  5000.6     .12       0  5008.4     .05       0
Bank Sta=4989.8,5000.6
XS Rating Curve= 0 ,0
Exp/Cntr=0.3,0.1

Type RM Length L Ch R = 1 ,38540   ,721,721,721
BEGIN DESCRIPTION:
Caney Creek 811
END DESCRIPTION:
XS GIS Cut Line= 3
      2727675.63      6843850.07      2726838.24      6844795.94
      2726423.24      6845110.95
#Sta/Elev= 30
  3753.2  421.09  3860.2  418.48  3966.4  417.38  4058.4  413.15  4079.3  410.09
  4128.7  410.51  4157.1  408.12  4178.9   408.5  4199.8  406.58  4291.8  404.39
    4398  404.12  4469.1  405.08  4518.4  403.68  4821.2  404.23  4922.4  404.48
  4965.1  401.55  4979.3  403.84    4986  398.66  4989.1  398.37  4993.5  397.95
  4994.4  395.72    4996  395.22  5006.1  395.72  5014.4  403.39  5021.1  404.63
  5085.5  409.12  5314.3  419.12  5407.9  420.16  5484.9  424.03  5537.5  425.29
#Mann= 5 ,-1 , 0
  3753.2     .05       0  4821.2      .1       0  4989.1     .12       0
  4994.4     .05       0  5006.1     .05       0
Bank Sta=4994.4,5006.1
XS Rating Curve= 0 ,0
Exp/Cntr=0.3,0.1

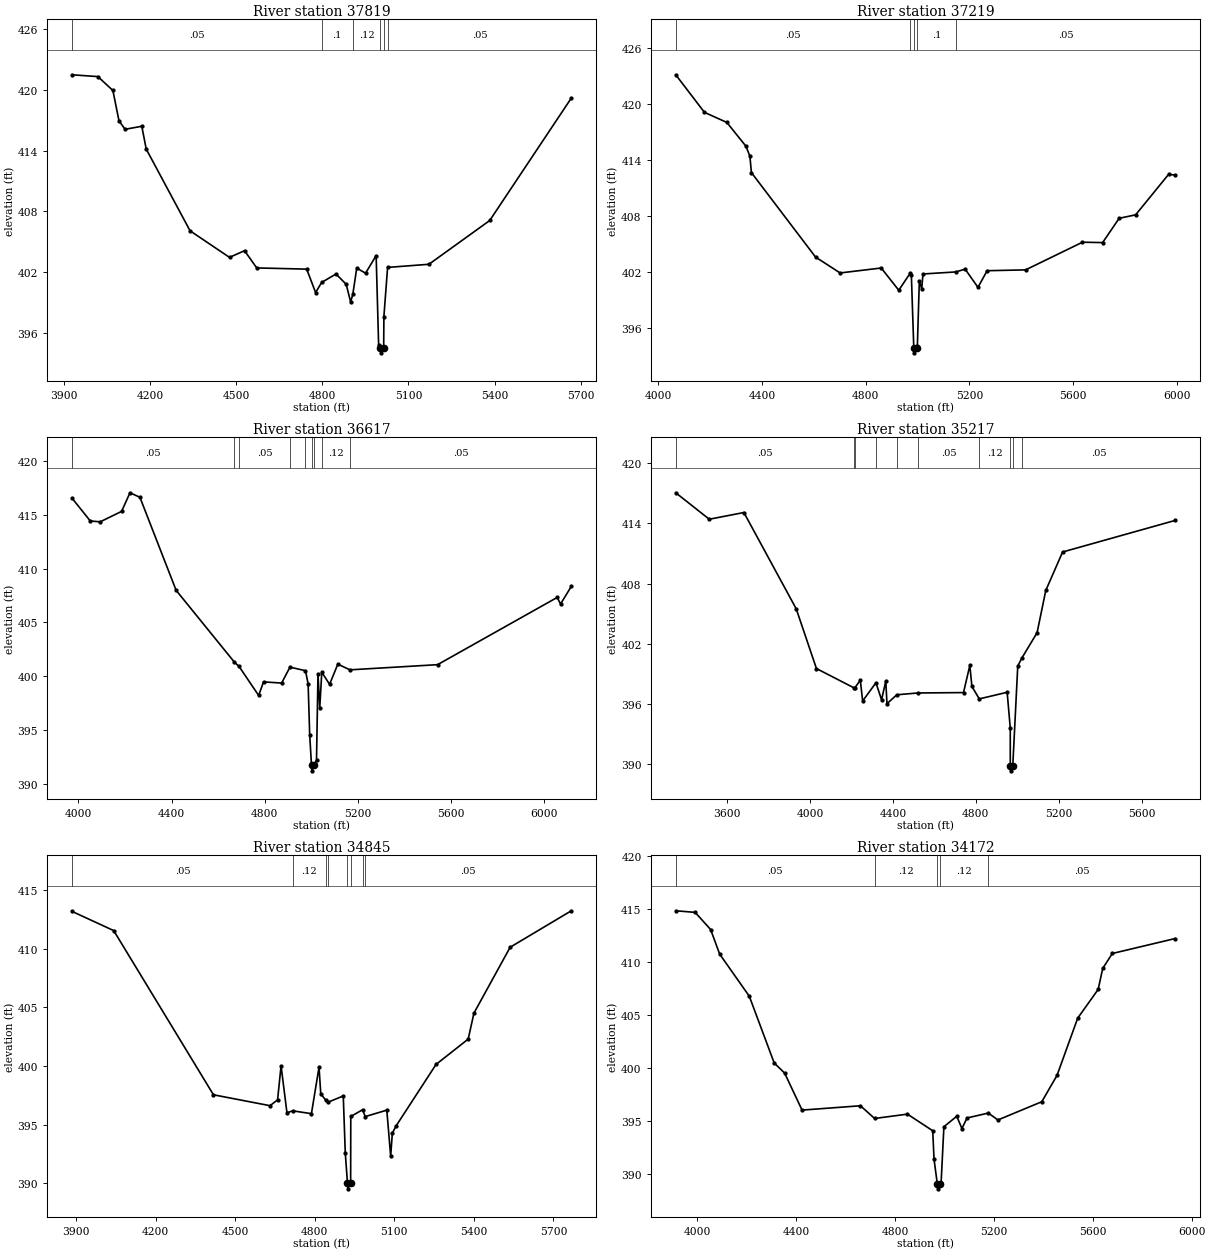
Type RM Length L Ch R = 1 ,37819   ,600,600,600
BEGIN DESCRIPTION:
Caney Creek 809
END DESCRIPTION:
XS GIS Cut Line= 3
      2727600.45       6843610.2      2726687.66      6844168.97
      2726180.25      6844605.37
#Sta/Elev= 30
    3928  421.49  4018.4  421.31  4070.6  419.94  4091.9  416.94  4113.2  416.11
  4171.3  416.41  4186.7  414.16  4339.5  406.09  4476.9  403.47  4529.1  404.13
  4571.7  402.43  4745.8  402.31  4776.7     400  4797.9     401  4847.8  401.83
  4883.2  400.82  4898.7  399.08  4906.3  399.81    4920  402.41  4950.8  401.91
  4987.6  403.65  4996.3  394.84  5002.1  394.55  5003.8  394.05  5013.9  394.55
  5014.6  397.62  5027.5  402.48  5171.5  402.79  5383.3  407.11  5667.5  419.19
#Mann= 6 ,-1 , 0
    3928     .05       0  4797.9      .1       0  4906.3     .12       0
  5002.1     .07       0  5013.9     .12       0  5027.5     .05       0
Bank Sta=5002.1,5013.9
XS Rating Curve= 0 ,0
Exp/Cntr=0.3,0.1

Type RM Length L Ch R = 1 ,37219   ,602,602,602
BEGIN DESCRIPTION:
Caney Creek 810
END DESCRIPTION:
XS GIS Cut Line= 3
      2727410.25      6843263.72      2726601.75        6843760.
      2725913.51      6844453.92
#Sta/Elev= 30
  4067.3   423.1  4177.9  419.08  4264.3     418  4337.8  415.46  4353.2  414.39
  4359.1  412.63  4606.5  403.59  4701.2  401.89  4859.8  402.42  4927.4  400.04
  4972.1  401.89  4975.9  401.72  4985.4  393.84    4987  393.34  4997.2  393.84
  4999.2  394.09  5006.7  401.03    5016  400.19  5020.7  401.78  5147.4     402
  5183.4   402.3  5232.9  400.35  5268.2  402.13  5416.7  402.22  5635.9  405.18
  5713.7  405.14  5777.4  407.74    5841  408.11  5968.3  412.45  5993.3  412.36
#Mann= 5 ,-1 , 0
  4067.3     .05       0  4972.1      .1       0  4985.4     .07       0
  4997.2      .1       0  5147.4     .05       0
Bank Sta=4985.4,4997.2
XS Rating Curve= 0 ,0
Exp/Cntr=0.3,0.1

Type RM Length L Ch R = 1 ,36617   ,1400,1400,1400
BEGIN DESCRIPTION:
Caney Creek 753
END DESCRIPTION:
XS GIS Cut Line= 3
      2727034.44      6842767.85      2726261.73      6843459.81
      2725591.18       6844340.3
#Sta/Elev= 30
  3971.9  416.55  4050.6  414.42  4093.2  414.34  4185.1  415.31    4221  417.04
  4263.7  416.62  4419.2  407.97  4669.5  401.29  4689.5  400.89  4773.5   398.2
  4794.5  399.46  4872.2  399.35  4907.9  400.83  4974.6   400.5  4985.9  399.27
  4992.6  394.56  5000.4  391.69    5002  391.19  5012.2  391.69  5021.9  392.19
  5028.2  400.19  5035.8  397.02  5044.5  400.36  5078.1  399.23  5113.4  401.11
  5165.3  400.58  5541.7  401.06  6055.2  407.31  6069.7   406.7  6115.9  408.34
#Mann= 9 ,-1 , 0
  3971.9     .05       0  4669.5      .1       0  4689.5     .05       0
  4907.9     .12       0  4974.6      .1       0  5000.4     .07       0
  5012.2      .1       0  5044.5     .12       0  5165.3     .05       0
Bank Sta=5000.4,5012.2
XS Rating Curve= 0 ,0
Exp/Cntr=0.3,0.1

Type RM Length L Ch R = 1 ,35217   ,372,372,372
BEGIN DESCRIPTION:
Caney Creek 750
END DESCRIPTION:
XS GIS Cut Line= 3
      2726755.58      6842853.75      2725325.31      6843084.41
       2724792.6      6843881.55
#Sta/Elev= 30
  3353.3  417.06  3514.9  414.42  3681.8  415.09    3934  405.48  4031.5  399.52
  4211.7   397.6  4217.7  397.62    4243  398.36  4254.4  396.28  4318.4   398.1
  4345.5   396.4  4365.8  398.26  4371.6  396.01    4419   396.9  4519.7  397.08
  4740.6  397.12    4771  399.83  4781.1  397.73  4816.6  396.49    4951  397.15
    4966  393.58  4966.1  389.81  4967.7  389.31  4978.1  389.81  5002.1  399.77
  5022.2  400.58  5095.2  403.09  5137.2  407.31  5218.3  411.15  5760.8   414.3
#Mann= 10 ,-1 , 0
  3353.3     .05       0  4211.7     .12       0  4217.7     .05       0
  4318.4      .1       0    4419     .12       0  4519.7     .05       0
  4816.6     .12       0  4966.1     .07       0  4978.1     .12       0
  5022.2     .05       0
Bank Sta=4966.1,4978.1
XS Rating Curve= 0 ,0
Exp/Cntr=0.3,0.1

Type RM Length L Ch R = 1 ,34845   ,673,673,673
BEGIN DESCRIPTION:
Caney Creek 751
END DESCRIPTION:
XS GIS Cut Line= 3
      2726050.98      6842264.28      2725189.49       6842984.5
      2724738.67      6843596.73
#Sta/Elev= 30
  3884.3  413.18  4041.8  411.54  4417.9  397.54  4631.3  396.61  4659.8  397.11
  4672.9  400.01  4695.1  396.01  4717.3  396.17  4787.4  395.93  4816.1   399.9
  4822.6  397.62  4841.8  397.07    4849   396.9  4907.5  397.44    4915  392.61
  4923.3  390.02  4924.9  389.52  4935.3  390.02  4935.8  395.69  4980.6  396.27
  4990.2  395.68  5071.6  396.23  5086.3  392.31  5092.5  394.27  5107.1   394.9
  5257.4  400.13  5378.6  402.29  5400.2   404.5  5536.8  410.12  5767.5  413.23
#Mann= 8 ,-1 , 0
  3884.3     .05       0  4717.3     .12       0  4841.8     .05       0
    4849      .1       0  4923.3     .05       0  4935.3      .1       0
  4980.6     .12       0  4990.2     .05       0
Bank Sta=4923.3,4935.3
XS Rating Curve= 0 ,0
Exp/Cntr=0.3,0.1

Type RM Length L Ch R = 1 ,34172   ,602,602,602
BEGIN DESCRIPTION:
Caney Creek 749
END DESCRIPTION:
XS GIS Cut Line= 3
      2725852.81      6842259.64      2724914.73      6842581.27
      2724630.95      6843570.29
#Sta/Elev= 30
  3912.6   414.8  3991.2  414.65  4053.7  413.03  4090.3  410.71  4210.1  406.74
  4310.9  400.44  4353.2  399.48  4423.7  395.99  4659.8   396.4  4717.3   395.2
  4850.1  395.61  4952.4  394.04  4957.6  391.38  4970.7  389.06  4972.4  388.56
  4982.9  389.06  4986.2  389.09  4997.6  394.42  5049.6  395.41  5070.5  394.25
  5091.3  395.25  5177.3  395.71  5216.1  395.06  5393.7  396.78  5455.4  399.27
    5539  404.67  5621.8  407.38  5640.2  409.36  5679.1  410.77  5933.2  412.18
#Mann= 5 ,-1 , 0
  3912.6     .05       0  4717.3     .12       0  4970.7     .07       0
  4982.9     .12       0  5177.3     .05       0
Bank Sta=4970.7,4982.9
XS Rating Curve= 0 ,0
Exp/Cntr=0.3,0.1