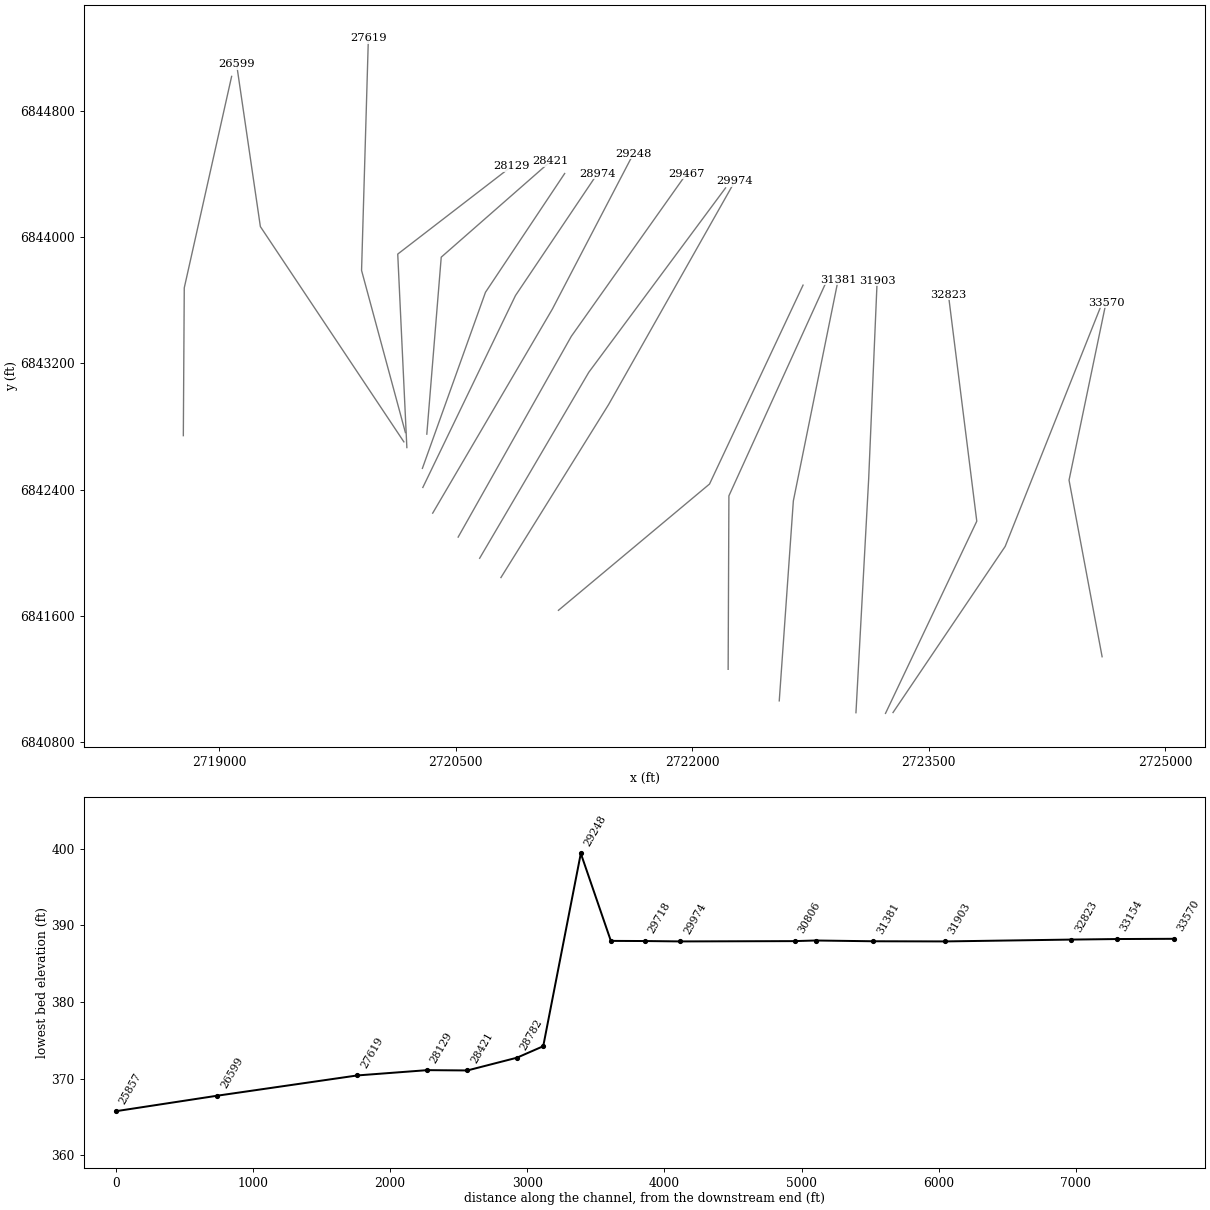
HEC-RAS study Caney Creek.prj: Caney Creek Base Level Engineering

--- Caney Creek.g01 (geometry) --- (continued)

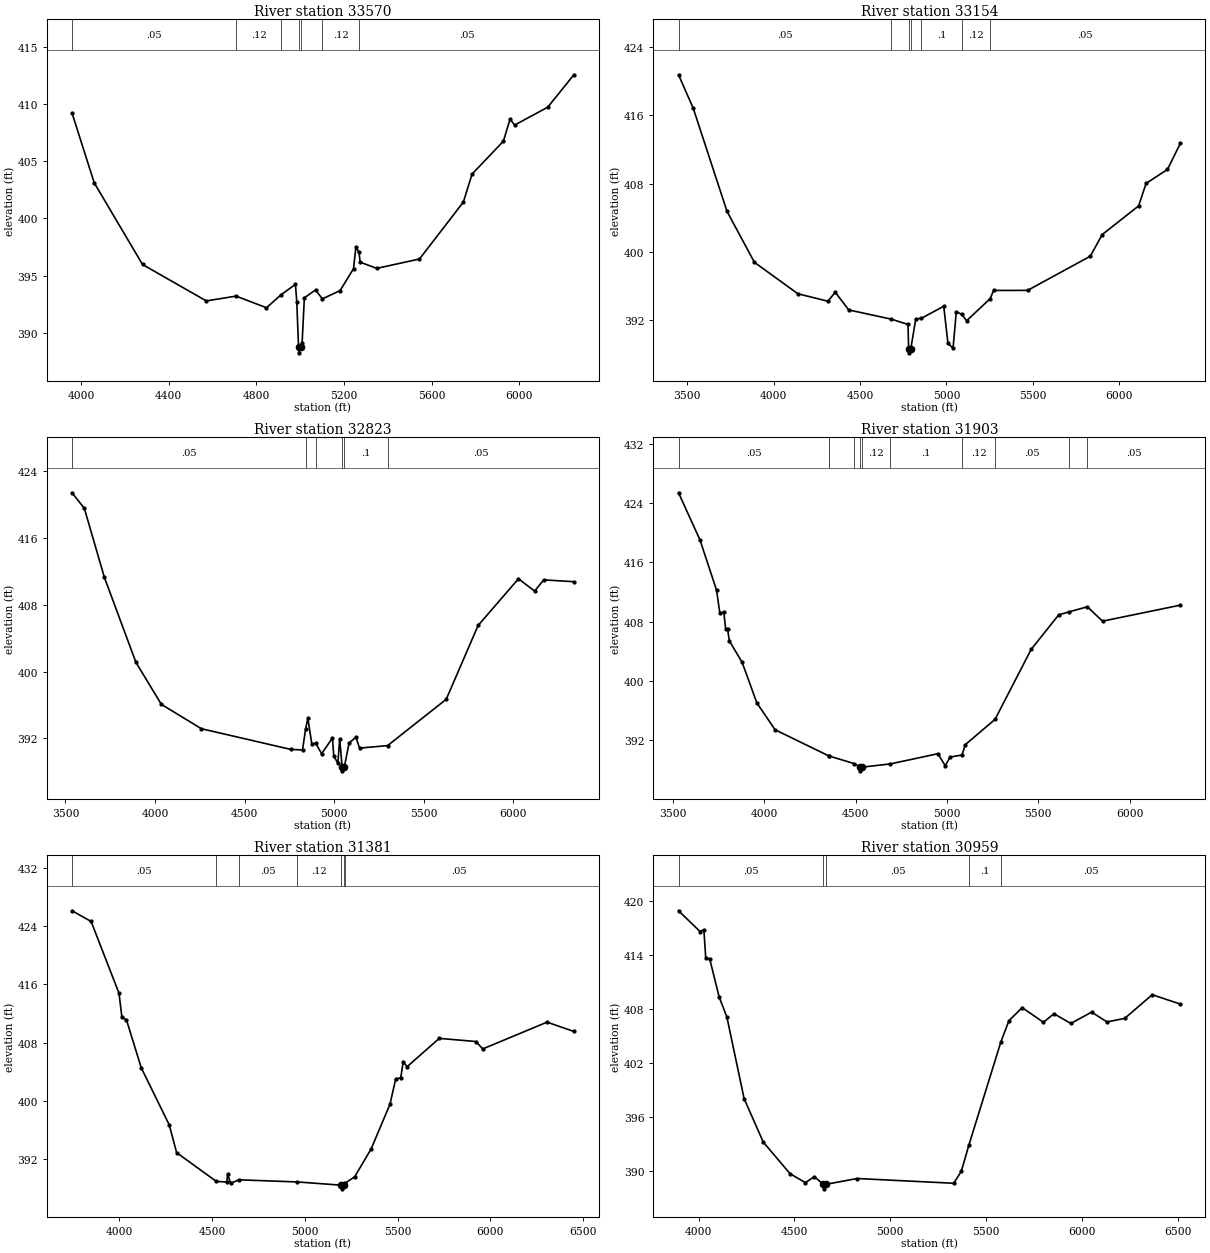
Type RM Length L Ch R = 1 ,33570   ,416,416,416
BEGIN DESCRIPTION:
Caney Creek 752
END DESCRIPTION:
XS GIS Cut Line= 3
      2724599.92      6841338.51      2724390.15       6842459.3
      2724624.59      6843586.01
#Sta/Elev= 30
  3958.7  409.23  4059.7  403.13  4280.3  395.97  4571.7  392.78  4707.7   393.2
  4846.3  392.18  4914.4  393.34  4978.6  394.23  4984.7   392.7  4992.8  388.73
  4994.5  388.23    5005  388.73  5009.1  389.11  5019.3  393.05  5070.2  393.74
  5101.5  392.96  5182.4  393.68  5243.7   395.6  5254.7   397.5  5268.6  397.05
  5274.3  396.17  5349.8  395.63    5545  396.45  5745.3  401.44    5785  403.89
    5928  406.77  5958.7  408.72  5979.1  408.18  6130.6  409.75  6249.8  412.59
#Mann= 7 ,-1 , 0
  3958.7     .05       0  4707.7     .12       0  4914.4      .1       0
  4992.8     .07       0    5005      .1       0  5101.5     .12       0
  5268.6     .05       0
Bank Sta=4992.8,5005
XS Rating Curve= 0 ,0
Exp/Cntr=0.3,0.1

Type RM Length L Ch R = 1 ,33154   ,331,331,331
BEGIN DESCRIPTION:
Caney Creek 747
END DESCRIPTION:
XS GIS Cut Line= 3
      2723273.63      6840984.43      2723984.97      6842038.56
       2724588.6      6843554.94
#Sta/Elev= 30
    3450  420.74  3535.5   416.8  3730.4  404.76  3889.2  398.79    4141  395.11
  4314.5  394.24  4356.9  395.29  4435.1  393.22  4681.9  392.14  4778.1  391.52
  4781.4   388.7  4783.2   388.2  4794.2   388.7  4822.8  392.17    4855  392.24
  4984.7  393.65    5009  389.32  5038.6  388.74  5057.5  393.02  5089.8  392.69
  5116.9  391.95  5253.2  394.54  5273.2   395.5  5470.2  395.51  5832.9  399.51
  5901.8  402.04  6112.2  405.39  6155.8  408.03  6279.4  409.66  6353.8  412.71
#Mann= 7 ,-1 , 0
    3450     .05       0  4681.9     .12       0  4781.4     .07       0
  4794.2     .12       0    4855      .1       0  5089.8     .12       0
  5253.2     .05       0
Bank Sta=4781.4,4794.2
XS Rating Curve= 0 ,0
Exp/Cntr=0.3,0.1

Type RM Length L Ch R = 1 ,32823   ,920,920,920
BEGIN DESCRIPTION:
Caney Creek 748
END DESCRIPTION:
XS GIS Cut Line= 4
      2723226.03      6840979.02      2723804.95      6842198.88
      2723651.52      6843424.86      2723624.88      6843637.79
#Sta/Elev= 30
    3537   421.4  3605.6  419.53  3716.8  411.31  3893.2  401.12  4035.1  396.09
  4258.7  393.17  4756.3   390.7  4823.2  390.63  4840.3  393.14  4852.8   394.4
  4875.5  391.29    4896  391.45  4929.7  390.18  4990.2  392.06  4997.4  389.93
  5020.4  389.03  5030.5  391.94  5044.2  388.63    5046  388.13    5057  388.63
    5083  391.47  5121.2  392.15  5141.4  390.85  5297.9  391.15  5625.1  396.69
  5803.2  405.53  6028.2  411.11  6118.3  409.64  6169.3  410.98  6337.4  410.76
#Mann= 6 ,-1 , 0
    3537     .05       0  4840.3     .12       0    4896      .1       0
  5044.2     .07       0    5057      .1       0  5297.9     .05       0
Bank Sta=5044.2,5057
XS Rating Curve= 0 ,0
Exp/Cntr=0.3,0.1

Type RM Length L Ch R = 1 ,31903   ,522,522,522
BEGIN DESCRIPTION:
Caney Creek 746
END DESCRIPTION:
XS GIS Cut Line= 3
       2723038.6      6840983.25      2723119.27      6842468.65
      2723173.02      6843726.52
#Sta/Elev= 30
  3530.5  425.38  3648.4  418.99  3738.6  412.24  3756.3  409.21  3778.6  409.24
  3788.6  406.99  3798.6  407.04  3808.7  405.41  3878.8  402.51  3958.9  397.06
    4059  393.43  4351.6  389.92  4355.9  389.88  4492.8  388.86  4523.3  388.39
  4525.1  387.89  4536.2  388.39  4689.1  388.82  4950.3   390.2  4990.4  388.57
  5016.8  389.75  5081.8  390.02  5100.5  391.43    5263  394.83  5460.8  404.27
    5611  408.91  5665.8  409.31  5768.5  410.01  5851.2  408.07  6277.1  410.23
#Mann= 11 ,-1 , 0
  3530.5     .05       0  4351.6     .12       0  4355.9     .05       0
  4492.8     .12       0  4523.3     .07       0  4536.2     .12       0
  4689.1      .1       0  5081.8     .12       0    5263     .05       0
  5665.8     .12       0  5768.5     .05       0
Bank Sta=4523.3,4536.2
XS Rating Curve= 0 ,0
Exp/Cntr=0.3,0.1

Type RM Length L Ch R = 1 ,31381   ,422,422,422
BEGIN DESCRIPTION:
Caney Creek 745
END DESCRIPTION:
XS GIS Cut Line= 4
      2722552.07      6841058.53      2722641.46      6842327.65
      2722792.98      6843075.83      2722925.99      6843732.66
#Sta/Elev= 30
  3744.3  426.11    3847  424.64  3997.4  414.78  4013.1  411.46  4037.5  411.13
  4117.7  404.51  4268.1  396.71  4308.2  392.88  4522.3  388.93  4578.4  388.85
  4583.4  389.93  4598.9  388.68  4644.6  389.15  4957.3  388.86  5197.1  388.41
    5199  387.91  5210.1  388.41  5214.7  388.65    5268  389.56  5356.7  393.38
  5458.7  399.54  5489.3     403  5516.4  403.17  5530.1  405.37  5550.5  404.68
  5724.3  408.58    5922  408.15  5958.7  407.13  6305.6  410.81  6450.1  409.53
#Mann= 7 ,-1 , 0
  3744.3     .05       0  4522.3     .12       0  4644.6     .05       0
  4957.3     .12       0  5197.1     .07       0  5210.1     .12       0
  5214.7     .05       0
Bank Sta=5197.1,5210.1
XS Rating Curve= 0 ,0
Exp/Cntr=0.3,0.1

Type RM Length L Ch R = 1 ,30959   ,153,153,153
BEGIN DESCRIPTION:
Caney Creek 719
END DESCRIPTION:
XS GIS Cut Line= 4
       2722227.9      6841258.78      2722232.71       6842359.7
      2722634.47      6843243.59      2722860.71      6843741.34
#Sta/Elev= 30
  3895.4  418.96  4007.6  416.65  4027.6  416.86  4037.6  413.66  4057.6  413.64
  4107.6  409.35  4147.6  407.14  4237.6  398.05  4337.6  393.21  4477.6  389.69
  4557.6   388.7    4604  389.36  4651.1  388.51    4653  388.01  4664.1  388.51
  4827.6  389.16  5331.7  388.63  5371.2  389.97  5411.1  392.92  5577.2  404.34
  5619.5  406.72  5688.7  408.18  5799.6  406.55  5854.6   407.5  5942.4  406.42
  6051.2  407.68  6131.3  406.59  6223.6  406.98  6367.5  409.62    6514  408.57
#Mann= 5 ,-1 , 0
  3895.4     .05       0  4651.1     .03       0  4664.1     .05       0
  5411.1      .1       0  5577.2     .05       0
Bank Sta=4651.1,4664.1
XS Rating Curve= 0 ,0
Exp/Cntr=0.3,0.1

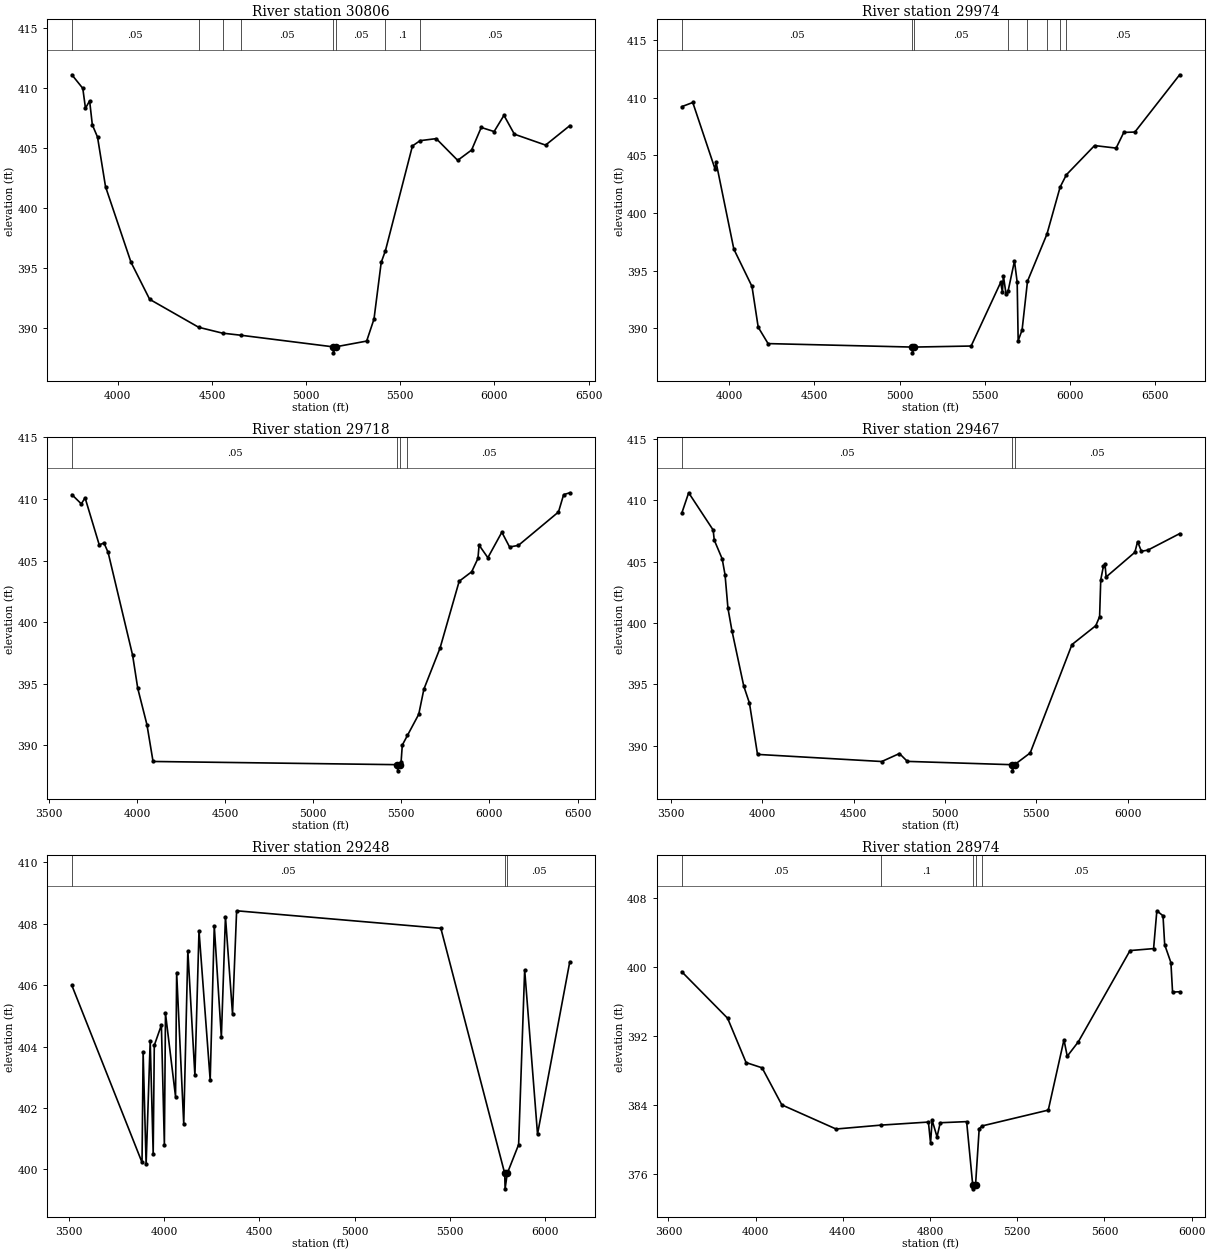
Type RM Length L Ch R = 1 ,30806   ,832,832,832
BEGIN DESCRIPTION:
Caney Creek 720
END DESCRIPTION:
XS GIS Cut Line= 3
       2721151.5      6841633.19      2722109.77      6842434.77
        2722703.      6843697.32
#Sta/Elev= 30
  3755.8   411.1  3813.8  409.97    3828  408.31  3850.1  408.93  3864.4  406.93
    3892  405.91  3934.6  401.77    4070  395.47  4168.9  392.39  4429.2  390.06
  4555.8  389.57  4651.6   389.4  5143.1  388.43  5144.9  387.93  5156.2  388.43
  5321.4  388.91  5360.4  390.75  5398.7  395.47  5421.2  396.45  5564.5  405.17
  5605.2  405.61  5690.7  405.78  5804.8  403.97  5878.7  404.83  5929.8  406.71
  5998.3  406.37  6050.6  407.72  6105.8  406.15  6271.6  405.24  6400.1  406.86
#Mann= 8 ,-1 , 0
  3755.8     .05       0  4429.2     .12       0  4555.8      .1       0
  4651.6     .05       0  5143.1     .03       0  5156.2     .05       0
  5421.2      .1       0  5605.2     .05       0
Bank Sta=5143.1,5156.2
XS Rating Curve= 0 ,0
Exp/Cntr=0.3,0.1

Type RM Length L Ch R = 1 ,29974   ,256,256,256
BEGIN DESCRIPTION:
Caney Creek 718
END DESCRIPTION:
XS GIS Cut Line= 3
      2720786.77      6841841.19      2721469.06      6842938.31
      2722269.75      6844355.37
#Sta/Elev= 30
  3722.8  409.21  3787.5  409.57  3918.5  403.79  3924.4  404.38  4028.3  396.87
  4134.7  393.64  4171.1  390.11    4229  388.69  5073.8  388.39  5075.7  387.89
    5087  388.39  5419.7  388.48  5592.9  393.99  5603.1  393.16  5608.8  394.57
  5624.7  392.95  5636.2  393.22  5673.8  395.84  5689.7  394.01  5695.5  388.94
  5718.5  389.87  5750.2  394.09  5864.2  398.17  5941.4  402.24  5978.2  403.31
  6143.5  405.84  6269.8  405.62  6314.9  406.98  6379.8  407.01  6642.4  411.97
#Mann= 8 ,-1 , 0
  3722.8     .05       0  5073.8     .03       0    5087     .05       0
  5636.2      .1       0  5750.2     .12       0  5864.2     .05       0
  5941.4      .1       0  5978.2     .05       0
Bank Sta=5073.8,5087
XS Rating Curve= 0 ,0
Exp/Cntr=0.3,0.1

Type RM Length L Ch R = 1 ,29718   ,251,251,251
BEGIN DESCRIPTION:
Caney Creek 717
END DESCRIPTION:
XS GIS Cut Line= 3
      2720651.74      6841963.64      2721344.12      6843144.32
      2722211.45      6844314.39
#Sta/Elev= 30
  3630.6  410.36  3684.1  409.61  3705.6   410.1  3785.7  406.29    3813  406.43
  3836.2  405.67  3975.3  397.32  4004.5  394.63  4056.5  391.69  4091.2   388.7
  5477.4  388.44  5479.2  387.94  5490.6  388.44  5498.6  388.65  5505.5  390.03
  5534.9  390.82  5598.8  392.53    5628  394.57  5719.8  397.91  5828.3  403.33
  5899.3   404.1  5934.7  405.18  5941.2  406.26    5991  405.24  6070.4  407.31
  6114.2  406.11  6164.3  406.24  6391.7  408.95    6421  410.36  6455.8  410.51
#Mann= 4 ,-1 , 0
  3630.6     .05       0  5477.4     .03       0  5490.6     .05       0
  5534.9     .05       0
Bank Sta=5477.4,5490.6
XS Rating Curve= 0 ,0
Exp/Cntr=0.3,0.1

Type RM Length L Ch R = 1 ,29467   ,219,219,219
BEGIN DESCRIPTION:
Caney Creek 625
END DESCRIPTION:
XS GIS Cut Line= 3
       2720515.4      6842097.94      2721232.95      6843372.12
      2721963.79      6844404.48
#Sta/Elev= 30
  3558.3  408.95  3596.2  410.62  3730.5  407.58  3736.2  406.77  3779.9  405.23
  3795.5  403.93  3811.4  401.21  3833.1  399.39  3898.1  394.86  3929.1  393.48
  3973.3   389.3  4653.8  388.72  4750.7  389.37    4794  388.73    5368  388.46
  5369.8  387.96  5381.2  388.46  5466.9  389.42  5695.7  398.25  5826.2  399.79
  5847.1  400.53  5853.3  403.53    5868  404.64  5876.7  404.81  5882.8  403.76
  6040.3  405.77  6055.1  406.64    6076  405.85  6111.7  405.95  6285.5  407.29
#Mann= 3 ,-1 , 0
  3558.3     .05       0    5368     .03       0  5381.2     .05       0
Bank Sta=5368,5381.2
XS Rating Curve= 0 ,0
Exp/Cntr=0.3,0.1

Type RM Length L Ch R = 1 ,29248   ,274,274,274
BEGIN DESCRIPTION:
Caney Creek 626
END DESCRIPTION:
XS GIS Cut Line= 3
      2720353.95      6842250.04       2721112.9      6843545.21
      2721626.69      6844530.88
#Sta/Elev= 30
  3515.6  405.99  3883.7  400.23  3889.5  403.81  3905.2  400.17  3926.6  404.19
  3942.3  400.51  3948.1  404.04  3985.3   404.7    4001   400.8  4006.8  405.08
  4059.6  402.37  4065.4  406.41  4102.6  401.48  4124.1  407.12  4161.2  403.06
  4182.7  407.77  4241.4  402.91  4262.8  407.93    4300   404.3  4321.5  408.23
  4358.6  405.06  4380.1  408.42  5451.8  407.85    5787  399.87  5788.9  399.37
  5800.2  399.87  5859.9  400.81  5891.6   406.5  5959.1  401.15  6128.3  406.76
#Mann= 3 ,-1 , 0
  3515.6     .05       0    5787     .04       0  5800.2     .05       0
Bank Sta=5787,5800.2
XS Rating Curve= 0 ,0
Exp/Cntr=0.3,0.1

Type RM Length L Ch R = 1 ,28974   ,192,192,192
BEGIN DESCRIPTION:
Caney Creek 624
END DESCRIPTION:
XS GIS Cut Line= 3
      2720291.38      6842413.05      2720878.85      6843630.97
      2721398.27      6844404.33
#Sta/Elev= 30
  3661.3  399.48  3871.6  394.07  3956.4  388.91  4029.8   388.3  4120.3  383.99
    4369  381.18  4573.5  381.63  4792.7  381.99  4802.6  379.53  4809.7  382.21
  4832.3  380.27    4847  381.91    4968  382.04  4995.8  374.72  4997.7  374.22
    5009  374.72  5025.6   381.2  5039.2  381.54  5342.5  383.38  5414.5  391.56
  5429.5  389.65  5480.5  391.33  5717.5  401.94  5825.6  402.17  5840.5  406.57
  5868.8  405.99  5876.5  402.62    5905  400.54  5912.6  397.11  5945.1  397.15
#Mann= 5 ,-1 , 0
  3661.3     .05       0  4573.5      .1       0  4995.8     .07       0
    5009      .1       0  5039.2     .05       0
Bank Sta=4995.8,5009
XS Rating Curve= 0 ,0
Exp/Cntr=0.3,0.1

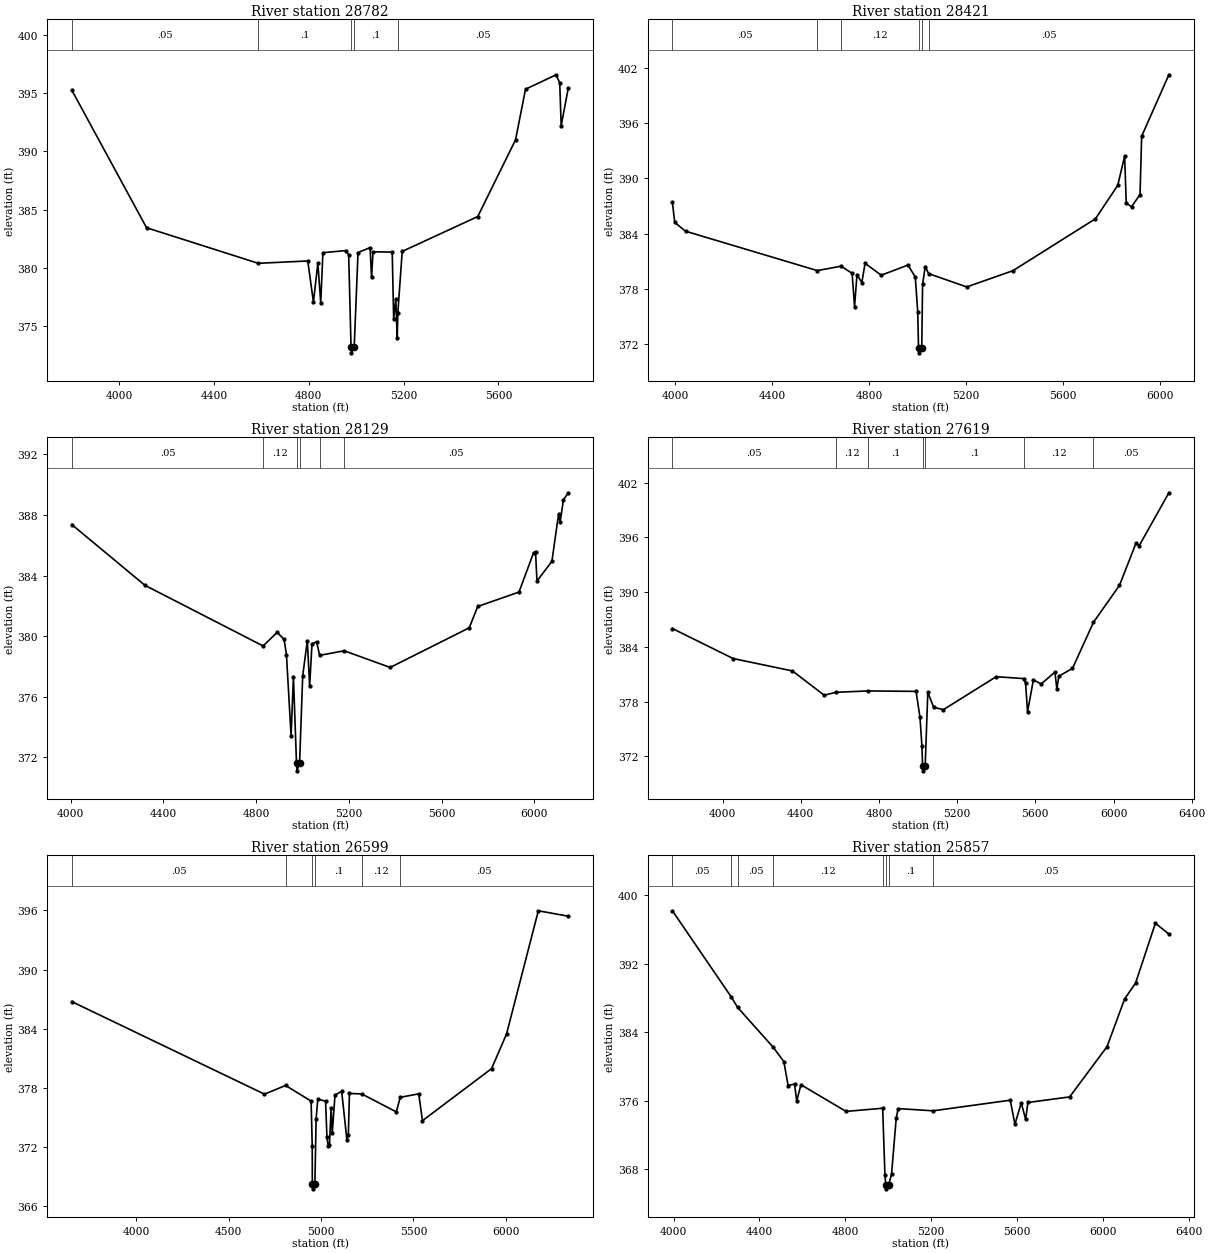
Type RM Length L Ch R = 1 ,28782   ,361,361,361
BEGIN DESCRIPTION:
Caney Creek 627
END DESCRIPTION:
XS GIS Cut Line= 3
       2720288.6      6842534.29      2720688.65      6843651.86
      2721191.01      6844405.92
#Sta/Elev= 30
  3801.2  395.25  4116.4  383.45  4587.3   380.4  4796.1   380.6  4819.9  377.08
  4838.6  380.43  4850.7     377  4859.8  381.31  4955.4  381.49  4968.5  381.13
  4978.5  373.22  4980.4  372.72  4991.8  373.22  5007.9  381.32  5058.9  381.75
  5064.9   379.2  5071.3  381.39  5152.1  381.36  5158.1  375.66  5167.1   377.3
  5173.1  373.97  5175.8  376.17  5194.2  381.42  5512.7  384.41    5672  390.99
    5714  395.33  5843.2  396.57  5858.3  395.87  5864.4  392.21  5894.3  395.42
#Mann= 5 ,-1 , 0
  3801.2     .05       0  4587.3      .1       0  4978.5     .07       0
  4991.8      .1       0  5175.8     .05       0
Bank Sta=4978.5,4991.8
XS Rating Curve= 0 ,0
Exp/Cntr=0.3,0.1

Type RM Length L Ch R = 1 ,28421   ,292,292,292
BEGIN DESCRIPTION:
Caney Creek 3525
END DESCRIPTION:
XS GIS Cut Line= 3
       2720316.6      6842751.41      2720408.05      6843874.81
      2721101.86      6844483.37
#Sta/Elev= 30
  3988.4  387.39    3998   385.2  4042.9  384.25  4586.7  379.98  4685.2  380.46
  4730.4  379.68  4740.5  376.08  4750.5  379.54  4770.6  378.68  4783.9  380.77
  4850.8  379.48  4961.2  380.58  4991.3  379.28  5001.3  375.54  5004.7  371.56
  5006.6  371.06    5018  371.56  5021.4  378.52  5032.5  380.42  5046.2  379.65
  5203.8  378.21  5394.5  379.97  5735.2   385.6  5827.3  389.23  5855.7  392.39
  5862.4  387.29  5884.2  386.91  5919.3  388.23    5926  394.56  6038.4  401.22
#Mann= 6 ,-1 , 0
  3988.4     .05       0  4586.7      .1       0  4685.2     .12       0
  5004.7     .07       0    5018     .12       0  5046.2     .05       0
Bank Sta=5004.7,5018
XS Rating Curve= 0 ,0
Exp/Cntr=0.3,0.1

Type RM Length L Ch R = 1 ,28129   ,510,510,510
BEGIN DESCRIPTION:
Caney Creek 628
END DESCRIPTION:
XS GIS Cut Line= 3
      2720190.04      6842666.21      2720132.18      6843894.39
      2720854.31      6844451.18
#Sta/Elev= 30
  4004.6  387.37  4319.7  383.36  4829.7  379.35  4890.4  380.25  4920.4  379.78
  4930.4  378.78  4950.4  373.42  4960.5  377.33  4973.8   371.6  4975.7   371.1
  4987.1   371.6  5000.5  377.38  5020.5   379.7  5030.5   376.7  5040.5  379.48
  5060.6  379.63  5073.6  378.73  5179.5  379.03  5377.9  377.93  5718.8  380.55
  5755.6  381.96  5933.5  382.91  5996.6  385.52  6004.7  385.59    6011  383.64
  6075.4  384.94  6104.4  388.09  6110.7  387.51  6125.2     389    6146  389.47
#Mann= 6 ,-1 , 0
  4004.6     .05       0  4829.7     .12       0  4973.8     .07       0
  4987.1     .12       0  5073.6      .1       0  5179.5     .05       0
Bank Sta=4973.8,4987.1
XS Rating Curve= 0 ,0
Exp/Cntr=0.3,0.1

Type RM Length L Ch R = 1 ,27619   ,1020,1020,1020
BEGIN DESCRIPTION:
Caney Creek 630
END DESCRIPTION:
XS GIS Cut Line= 3
      2720180.75       6842761.4      2719902.71      6843790.72
       2719945.9      6845263.88
#Sta/Elev= 30
  3743.1  386.01  4053.8  382.72  4357.4  381.36  4519.6   378.7  4579.9  379.02
  4745.2  379.17  4989.7  379.12  5009.7  376.27  5019.7  373.13    5023  370.91
  5024.9  370.41  5036.3  370.91  5049.7  379.02  5079.7  377.37  5129.7  377.12
  5399.8  380.73  5540.6  380.52  5549.9  380.04  5559.9  376.87  5589.9  380.38
  5629.9  379.93    5700  381.23    5710   379.4    5720  380.79    5790  381.64
  5897.2  386.69  6030.1  390.73  6115.5   395.4  6130.2  395.05  6283.1  400.89
#Mann= 7 ,-1 , 0
  3743.1     .05       0  4579.9     .12       0  4745.2      .1       0
    5023     .07       0  5036.3      .1       0  5540.6     .12       0
  5897.2     .05       0
Bank Sta=5023,5036.3
XS Rating Curve= 0 ,0
Exp/Cntr=0.3,0.1

Type RM Length L Ch R = 1 ,26599   ,742,742,742
BEGIN DESCRIPTION:
Caney Creek 629
END DESCRIPTION:
XS GIS Cut Line= 3
      2720171.06      6842702.58      2719260.87      6844068.97
      2719109.88      6845101.19
#Sta/Elev= 30
  3652.5  386.75  4694.4  377.37    4809  378.25  4946.8  376.66  4952.8  372.08
  4953.3  368.27  4955.3  367.77  4967.2  368.27  4973.8  374.86  4982.9  376.86
  5024.9  376.66  5032.4  372.98    5040  372.08    5046  372.21    5055  375.99
    5061  373.39    5076  377.29  5112.1  377.64  5140.5  372.69  5148.1  373.27
  5154.1  377.44  5220.8  377.39  5407.5  375.57  5428.9  377.05  5528.8   377.4
    5549  374.68  5922.9  379.96  6003.8  383.48  6175.6  395.96  6337.5  395.41
#Mann= 6 ,-1 , 0
  3652.5     .05       0    4809      .1       0  4953.3     .07       0
  4967.2      .1       0  5220.8     .12       0  5428.9     .05       0
Bank Sta=4953.3,4967.2
XS Rating Curve= 0 ,0
Exp/Cntr=0.3,0.1

Type RM Length L Ch R = 1 ,25857   ,284,284,284
BEGIN DESCRIPTION:
Caney Creek 622
END DESCRIPTION:
XS GIS Cut Line= 3
      2718772.22      6842741.85      2718778.13      6843679.98
      2719078.56      6845022.32
#Sta/Elev= 30
  3994.4  398.17  4268.6  388.12  4298.6  386.89  4464.5  382.24  4513.6  380.59
  4533.6  377.79  4563.6  377.96  4573.6  376.01  4593.6  377.88  4803.6  374.77
  4974.3  375.14  4984.8  367.38  4988.7  366.24  4990.7  365.74    5003  366.24
  5015.6  367.45  5037.3  373.95  5046.3   375.1  5209.5  374.84  5568.9  376.08
  5590.6  373.27  5620.2  375.77  5640.7  373.83  5650.9  375.81  5845.6  376.46
  6019.8  382.32  6101.8  387.88    6153  389.75  6245.3  396.72  6308.1  395.45
#Mann= 8 ,-1 , 0
  3994.4     .05       0  4268.6     .12       0  4298.6     .05       0
  4464.5     .12       0  4974.3      .1       0  4988.7     .07       0
    5003      .1       0  5209.5     .05       0
Bank Sta=4988.7,5003
XS Rating Curve= 0 ,0
Exp/Cntr=0.3,0.1