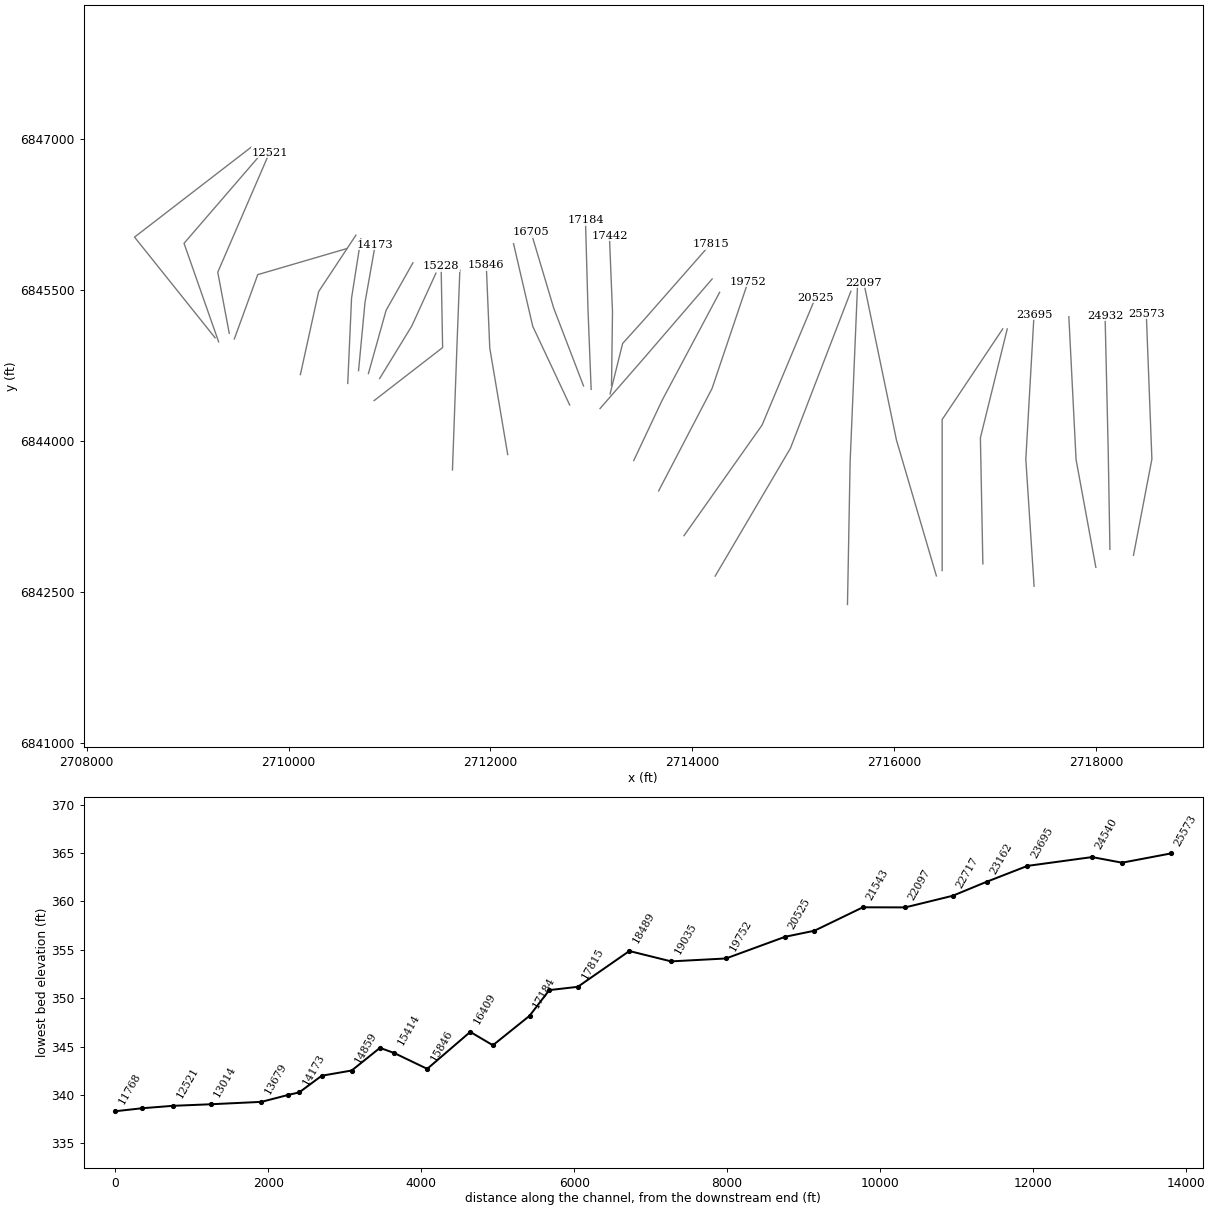
HEC-RAS study Caney Creek.prj: Caney Creek Base Level Engineering

--- Caney Creek.g01 (geometry) --- (continued)

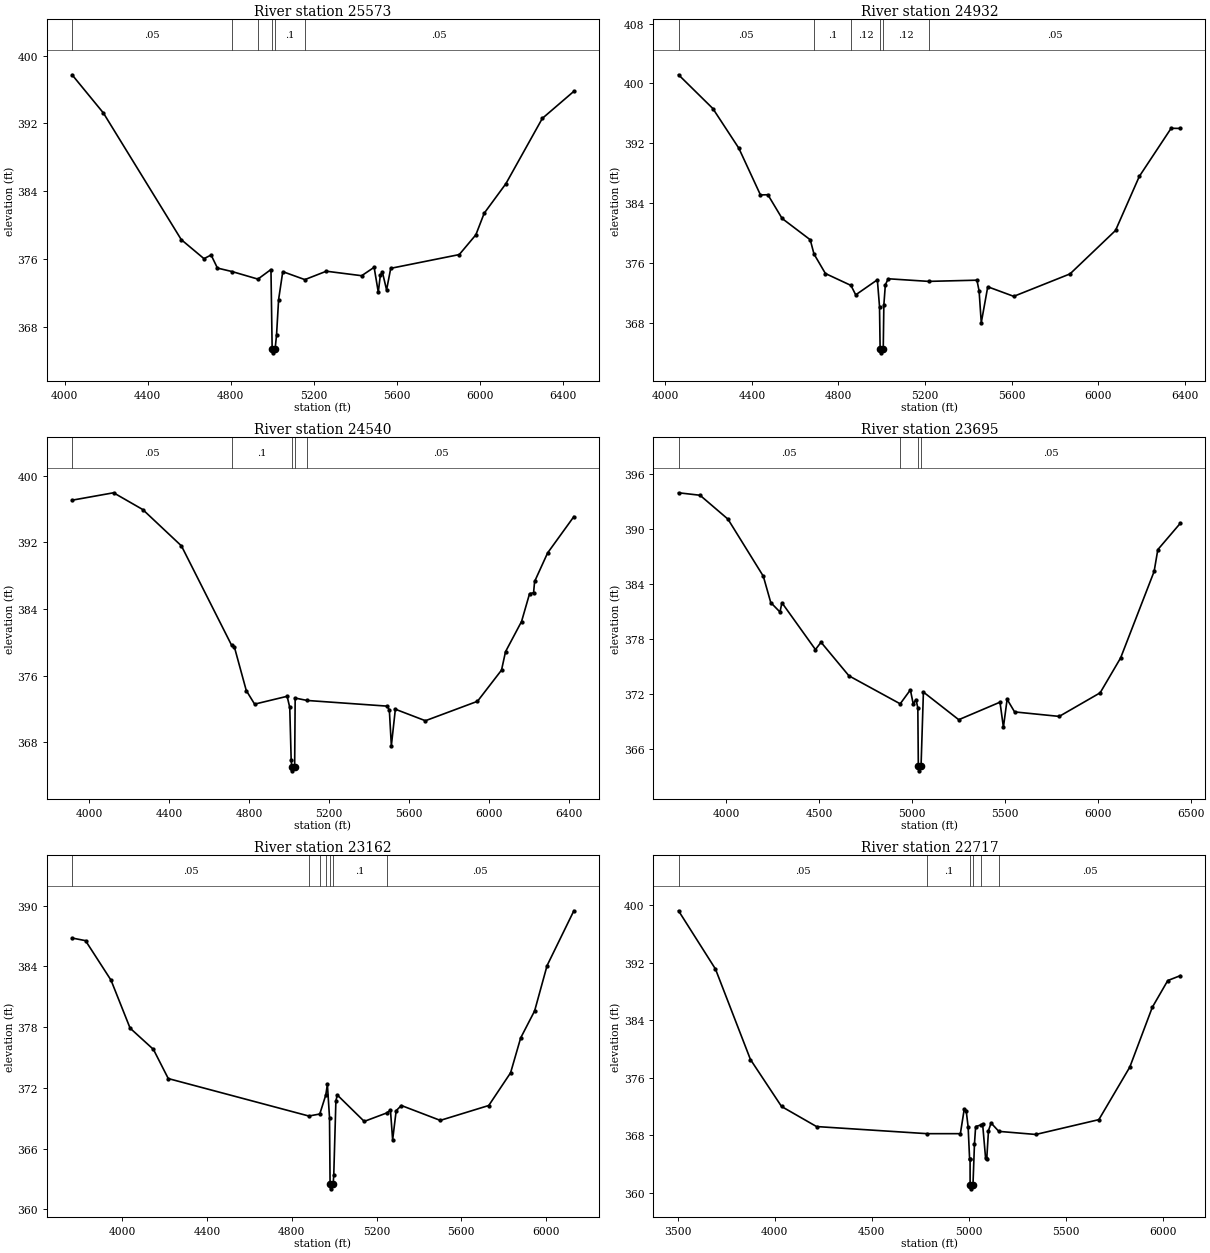
Type RM Length L Ch R = 1 ,25573   ,641,641,641
BEGIN DESCRIPTION:
Caney Creek 621
END DESCRIPTION:
XS GIS Cut Line= 3
      2718371.59      6842862.82      2718553.93       6843818.1
      2718498.39      6845262.91
#Sta/Elev= 30
    4035  397.73  4185.9  393.23  4561.3   378.3  4670.7  376.06  4705.1  376.49
  4735.6  374.95  4805.9  374.54  4930.7  373.65  4993.6  374.78  4999.3  365.46
  5001.3  364.96  5013.7  365.46  5020.4  367.04  5030.4  371.24  5050.5  374.53
  5156.8  373.59  5260.6  374.58  5430.7  374.05  5490.8  375.04  5510.8  372.11
  5520.8  374.12  5530.8  374.45  5550.8  372.38  5570.8  374.92  5901.1  376.54
  5981.1  378.87  6021.2  381.41  6125.7  384.89  6301.4  392.59  6453.4  395.78
#Mann= 6 ,-1 , 0
    4035     .05       0  4805.9     .12       0  4930.7      .1       0
  4999.3     .07       0  5013.7      .1       0  5156.8     .05       0
Bank Sta=4999.3,5013.7
XS Rating Curve= 0 ,0
Exp/Cntr=0.3,0.1

Type RM Length L Ch R = 1 ,24932   ,392,392,392
BEGIN DESCRIPTION:
Caney Creek 620
END DESCRIPTION:
XS GIS Cut Line= 3
      2718138.15      6842922.55      2718121.54      6843879.75
      2718090.06      6845240.44
#Sta/Elev= 30
  4061.2  401.16  4219.7  396.65  4339.7  391.35  4439.7   385.1    4474  385.13
  4539.7  381.96  4669.7  379.11    4687  377.21  4739.8   374.6  4857.8  373.01
  4879.8  371.75  4979.8  373.76  4989.8  370.19  4992.6   364.5  4994.6     364
    5007   364.5  5009.8  370.38  5016.7  373.08  5029.8   373.9  5216.3  373.55
  5439.9  373.71  5449.9  372.27  5459.9  368.02  5489.9  372.83    5610  371.55
    5870  374.55  6080.1  380.35  6190.1  387.58  6337.1  394.01  6379.6  393.99
#Mann= 6 ,-1 , 0
  4061.2     .05       0    4687      .1       0  4857.8     .12       0
  4992.6     .07       0    5007     .12       0  5216.3     .05       0
Bank Sta=4992.6,5007
XS Rating Curve= 0 ,0
Exp/Cntr=0.3,0.1

Type RM Length L Ch R = 1 ,24540   ,845,845,845
BEGIN DESCRIPTION:
Caney Creek 623
END DESCRIPTION:
XS GIS Cut Line= 3
      2717998.64      6842743.47       2717802.6      6843813.75
      2717731.13      6845232.16
#Sta/Elev= 30
  3914.8  397.04  4122.2  397.93  4268.1  395.92  4461.5  391.56  4712.1  379.65
  4725.6  379.48  4785.6  374.21  4827.3  372.58  4989.9  373.52  5002.9  372.18
  5010.1  365.84    5013  365.08    5015  364.58  5027.4  365.08    5030  373.31
  5090.1  373.02  5490.8  372.34  5500.8  371.85  5510.8  367.59  5530.8  371.97
    5681  370.59  5941.3  372.92  6061.5  376.66  6081.5  378.87  6161.6  382.49
  6201.7  385.83  6221.7  385.94  6226.9  387.29  6291.8  390.71  6423.1  395.07
#Mann= 5 ,-1 , 0
  3914.8     .05       0  4712.1      .1       0    5013     .07       0
  5027.4      .1       0  5090.1     .05       0
Bank Sta=5013,5027.4
XS Rating Curve= 0 ,0
Exp/Cntr=0.3,0.1

Type RM Length L Ch R = 1 ,23695   ,533,533,533
BEGIN DESCRIPTION:
Caney Creek 586
END DESCRIPTION:
XS GIS Cut Line= 3
      2717386.74      6842555.53      2717304.74      6843816.05
      2717386.14      6845251.86
#Sta/Elev= 30
  3741.9  393.96  3857.6  393.69  4007.9  391.09  4198.3  384.87  4238.4     382
    4288  380.97  4298.5  381.98  4478.9  376.88    4509  377.68  4659.3  374.02
  4935.2  370.97    4990  372.49  5005.1  370.97  5020.1  371.43  5030.1  370.53
  5032.8  364.17  5034.8  363.67  5047.4  364.17  5060.1  372.25  5250.4  369.24
  5472.4  371.15  5490.8  368.42  5510.8  371.46  5550.9  370.09  5791.3   369.6
  6011.6  372.17  6121.8  375.97  6302.1  385.39  6322.1  387.77  6443.2  390.64
#Mann= 4 ,-1 , 0
  3741.9     .05       0  4935.2     .12       0  5032.8     .07       0
  5047.4     .05       0
Bank Sta=5032.8,5047.4
XS Rating Curve= 0 ,0
Exp/Cntr=0.3,0.1

Type RM Length L Ch R = 1 ,23162   ,445,445,445
BEGIN DESCRIPTION:
Caney Creek 587
END DESCRIPTION:
XS GIS Cut Line= 3
      2716879.24      6842777.58      2716854.74      6844029.06
      2717120.61      6845110.65
#Sta/Elev= 30
  3764.8   386.8  3828.2  386.54  3948.3  382.64  4038.3   377.9  4148.3   375.8
  4218.3  372.92  4881.1  369.22  4932.5  369.42  4960.8  371.29  4968.4  372.35
  4978.4  369.07  4981.1  362.53  4983.1  362.03  4995.7  362.53  4998.5  363.44
  5008.5  370.71    5015   371.3  5142.1  368.69  5247.6  369.52  5265.7   369.8
    5276  366.87  5292.7  369.75  5317.1  370.26  5500.5  368.79  5729.1  370.26
    5832  373.49  5879.5  376.93  5945.3   379.6  6004.1  384.08  6130.3  389.49
#Mann= 7 ,-1 , 0
  3764.8     .05       0  4881.1      .1       0  4932.5     .05       0
  4960.8      .1       0  4981.1     .07       0  4995.7      .1       0
  5247.6     .05       0
Bank Sta=4981.1,4995.7
XS Rating Curve= 0 ,0
Exp/Cntr=0.3,0.1

Type RM Length L Ch R = 1 ,22717   ,620,620,620
BEGIN DESCRIPTION:
Caney Creek 28
END DESCRIPTION:
XS GIS Cut Line= 3
        2716476.      6842710.97        2716476.        6844211.
        2717076.      6845111.01
#Sta/Elev= 30
  3505.3  399.24  3695.3  391.14  3875.3  378.56  4035.3  372.03  4215.3  369.24
  4783.9  368.25  4955.3  368.25  4975.3  371.67  4985.3  371.44  4995.3  369.19
  5002.8  364.73  5005.3  364.73  5005.5  361.08  5007.5  360.58  5020.1  361.08
  5027.9  366.84  5033.9  369.24  5059.2  369.45  5069.9  369.56  5084.9   364.9
    5091  364.72    5100  368.69  5113.5  369.73  5153.1  368.57  5343.3  368.14
  5667.8   370.2  5827.1  377.51  5942.8  385.82  6022.4  389.54    6087  390.22
#Mann= 6 ,-1 , 0
  3505.3     .05       0  4783.9      .1       0  5005.5     .07       0
  5020.1      .1       0  5059.2     .12       0  5153.1     .05       0
Bank Sta=5005.5,5020.1
XS Rating Curve= 0 ,0
Exp/Cntr=0.3,0.1

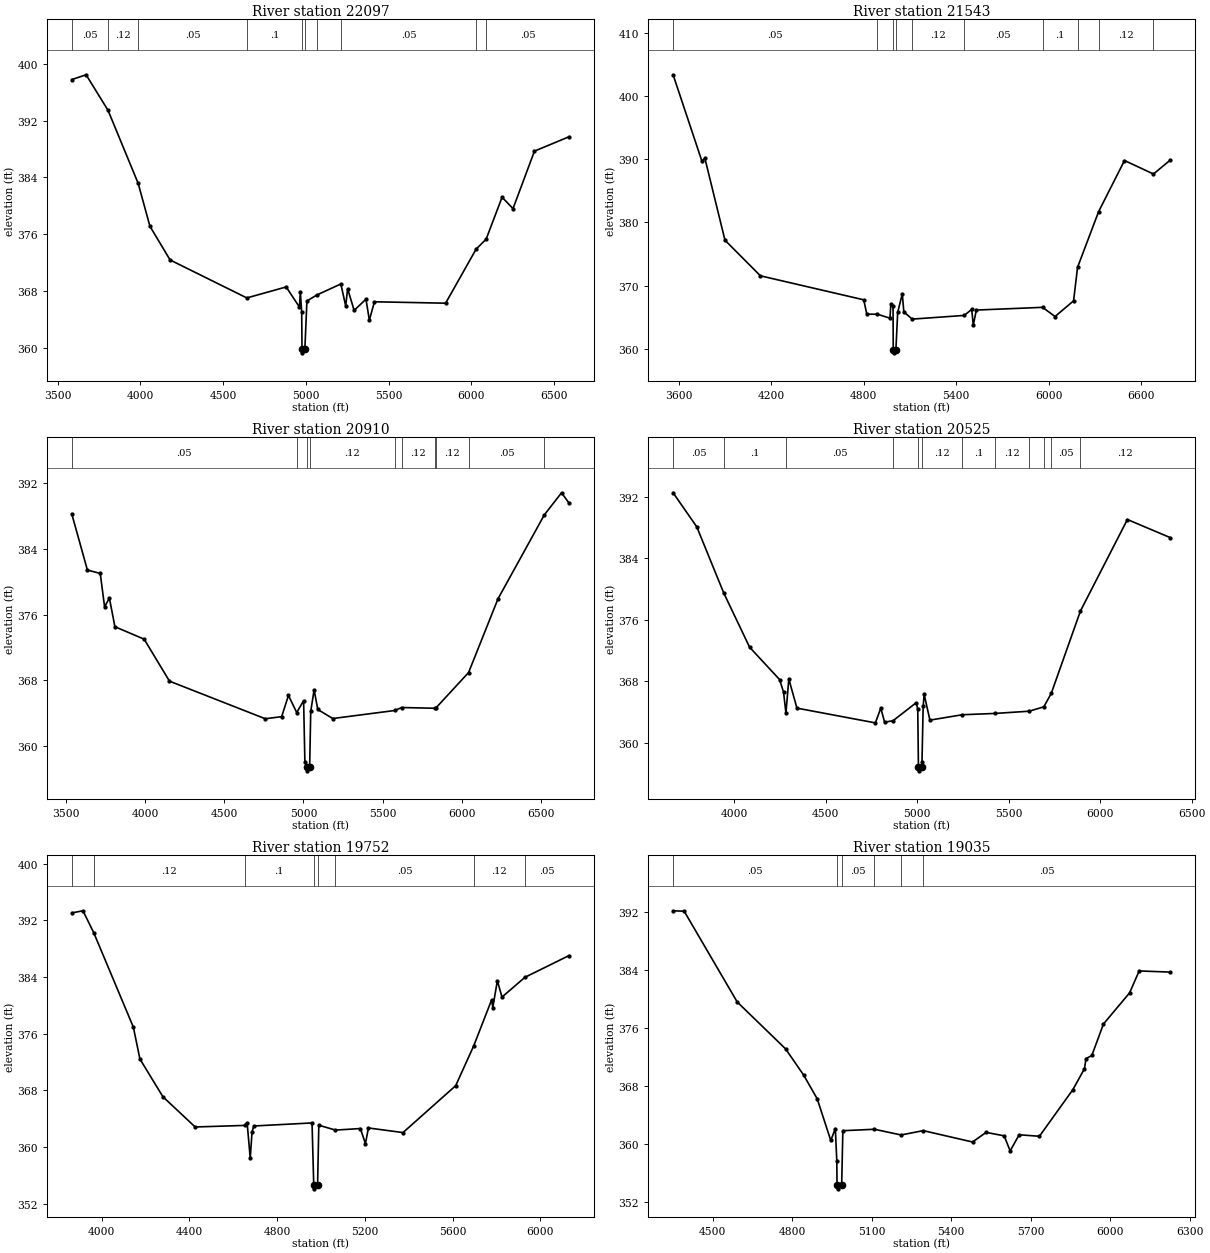
Type RM Length L Ch R = 1 ,22097   ,554,554,554
BEGIN DESCRIPTION:
Caney Creek 504
END DESCRIPTION:
XS GIS Cut Line= 3
      2716418.58      6842658.17      2716023.17      6844006.78
      2715699.19      6845571.71
#Sta/Elev= 30
  3585.8  397.75  3672.1  398.42  3804.5  393.43  3986.7  383.17  4057.7  377.15
  4179.5  372.42  4643.2  367.09    4881  368.63  4961.2   365.8  4966.4  367.97
  4974.7  365.11  4976.6  359.88  4978.6  359.38  4993.8  359.88  5006.3  366.66
  5065.4  367.49  5211.2  369.05  5240.6  365.97  5252.2  368.38  5291.6  365.34
  5363.1  366.91  5383.6  363.97  5414.2  366.55  5844.3  366.35  6028.9  373.95
  6089.2  375.34  6185.5  381.23  6251.6  379.63  6381.1   387.7  6589.3  389.71
#Mann= 10 ,-1 , 0
  3585.8     .05       0  3804.5     .12       0  3986.7     .05       0
  4643.2      .1       0  4976.6     .07       0  4993.8      .1       0
  5065.4     .12       0  5211.2     .05       0  6028.9      .1       0
  6089.2     .05       0
Bank Sta=4976.6,4993.8
XS Rating Curve= 0 ,0
Exp/Cntr=0.3,0.1

Type RM Length L Ch R = 1 ,21543   ,633,633,633
BEGIN DESCRIPTION:
Caney Creek 505
END DESCRIPTION:
XS GIS Cut Line= 3
      2715537.86      6842374.69      2715564.03      6843788.39
      2715639.78      6845597.06
#Sta/Elev= 30
  3563.7  403.33    3750  389.72    3770  390.12  3900.1  377.19  4130.1  371.56
  4800.2  367.77  4820.2   365.5  4889.1  365.49  4970.2  364.87  4976.4  367.11
  4990.3  366.76  4991.7  359.89  4993.7  359.39  5008.9  359.89  5020.3  365.77
  5050.3  368.71  5060.3  365.86  5114.5  364.72  5451.7   365.3  5500.7  366.26
  5510.7  363.77  5530.7  366.15  5959.9  366.58  6041.2  365.13  6161.3  367.61
  6187.1   372.9    6324  381.72  6491.6  389.78  6679.5  387.65  6787.9  389.84
#Mann= 10 ,-1 , 0
  3563.7     .05       0  4889.1      .1       0  4991.7     .07       0
  5008.9      .1       0  5114.5     .12       0  5451.7     .05       0
  5959.9      .1       0  6187.1     .05       0    6324     .12       0
  6679.5     .05       0
Bank Sta=4991.7,5008.9
XS Rating Curve= 0 ,0
Exp/Cntr=0.3,0.1

Type RM Length L Ch R = 1 ,20910   ,385,385,385
BEGIN DESCRIPTION:
Caney Creek 502
END DESCRIPTION:
XS GIS Cut Line= 3
      2714226.94      6842656.17      2714973.28      6843927.17
      2715571.46      6845484.51
#Sta/Elev= 30
    3536  388.23  3634.4  381.42  3715.6  381.01    3743  376.95  3773.5     378
  3808.3  374.52  3993.2     373  4153.3  367.89  4759.2  363.31  4862.5  363.57
  4905.4  366.15  4957.5  364.07  5001.2  365.51  5009.3  357.99  5022.1  357.47
  5024.1  356.97  5039.4  357.47  5046.2  364.21  5067.6  366.83  5090.8  364.44
  5185.4  363.34  5578.2  364.32  5620.6  364.68  5832.3  364.59  5838.1  364.64
    6044  368.94  6230.3  377.93  6522.9  388.14  6631.6  390.83  6678.2   389.6
#Mann= 10 ,-1 , 0
    3536     .05       0  4957.5     .12       0  5022.1     .07       0
  5039.4     .12       0  5578.2     .05       0  5620.6     .12       0
  5832.3     .05       0  5838.1     .12       0    6044     .05       0
  6522.9     .12       0
Bank Sta=5022.1,5039.4
XS Rating Curve= 0 ,0
Exp/Cntr=0.3,0.1

Type RM Length L Ch R = 1 ,20525   ,773,773,773
BEGIN DESCRIPTION:
Caney Creek 503
END DESCRIPTION:
XS GIS Cut Line= 3
      2713918.05      6843057.77      2714691.86      6844156.21
      2715220.86       6845422.2
#Sta/Elev= 30
  3666.9  392.52  3796.4  388.08  3943.2   379.5  4084.7  372.43  4248.5  368.22
  4270.2  366.59  4283.4  363.85    4299   368.3  4343.4   364.5  4771.9  362.58
  4801.5   364.5  4822.4  362.67  4868.4  362.86  4994.9   365.2  5003.5  364.39
  5007.2  356.84  5009.2  356.34  5024.5  356.84  5026.6  357.51  5033.1  364.72
  5038.5   366.3  5069.9  362.94  5247.2  363.64  5426.8  363.81  5612.4   364.1
  5692.3  364.67  5732.9  366.42  5892.4  377.14  6148.9  389.04  6382.6  386.69
#Mann= 12 ,-1 , 0
  3666.9     .05       0  3943.2      .1       0  4283.4     .05       0
  4868.4     .12       0  5007.2     .07       0  5024.5     .12       0
  5247.2      .1       0  5426.8     .12       0  5612.4      .1       0
  5692.3     .12       0  5732.9     .05       0  5892.4     .12       0
Bank Sta=5007.2,5024.5
XS Rating Curve= 0 ,0
Exp/Cntr=0.3,0.1

Type RM Length L Ch R = 1 ,19752   ,717,717,717
BEGIN DESCRIPTION:
Caney Creek 501
END DESCRIPTION:
XS GIS Cut Line= 3
      2713666.93      6843502.26      2714195.84      6844518.85
      2714553.32        6845580.
#Sta/Elev= 30
  3864.3  393.04    3915  393.34  3964.1  390.25  4144.7  376.92  4174.7  372.42
  4279.6  367.09  4426.5  362.83  4652.9  363.05  4663.2  363.44  4677.5  358.43
  4685.8  362.16  4693.9  362.97  4959.2   363.4    4967   354.6    4969   354.1
  4984.4   354.6  4990.1  363.08  5066.1  362.39  5179.6  362.61  5202.5  360.48
  5216.3  362.69  5373.8  362.04    5614  368.66  5696.3  374.29  5777.9  380.78
  5783.1  379.69  5803.9  383.47    5825  381.16  5929.5  383.95    6130  387.01
#Mann= 8 ,-1 , 0
  3864.3     .05       0  3964.1     .12       0  4652.9      .1       0
    4967     .07       0  4984.4      .1       0  5066.1     .05       0
  5696.3     .12       0  5929.5     .05       0
Bank Sta=4967,4984.4
XS Rating Curve= 0 ,0
Exp/Cntr=0.3,0.1

Type RM Length L Ch R = 1 ,19035   ,546,546,546
BEGIN DESCRIPTION:
Caney Creek 499
END DESCRIPTION:
XS GIS Cut Line= 3
      2713419.86      6843803.14      2713701.33      6844401.84
      2714271.28      6845474.34
#Sta/Elev= 30
  4350.8  392.21  4392.6  392.15  4592.8  379.61  4775.2  373.14  4843.6  369.51
  4894.7  366.24  4945.9  360.48  4963.1  362.12  4968.7   357.6  4969.5   354.3
  4971.5   353.8    4987   354.3  4991.5  361.83  5110.7  362.03  5211.1  361.24
  5294.9  361.84  5480.9  360.27  5532.3   361.6  5600.3  361.12  5622.9  359.04
  5656.9  361.27  5733.3  361.06  5859.6   367.5  5903.5   370.4  5909.2  371.79
  5931.2  372.22  5975.1  376.57  6073.7  380.87  6109.9   383.9  6226.9  383.74
#Mann= 6 ,-1 , 0
  4350.8     .05       0  4969.5     .07       0    4987     .05       0
  5110.7     .05       0  5211.1     .12       0  5294.9     .05       0
Bank Sta=4969.5,4987
XS Rating Curve= 0 ,0
Exp/Cntr=0.3,0.1

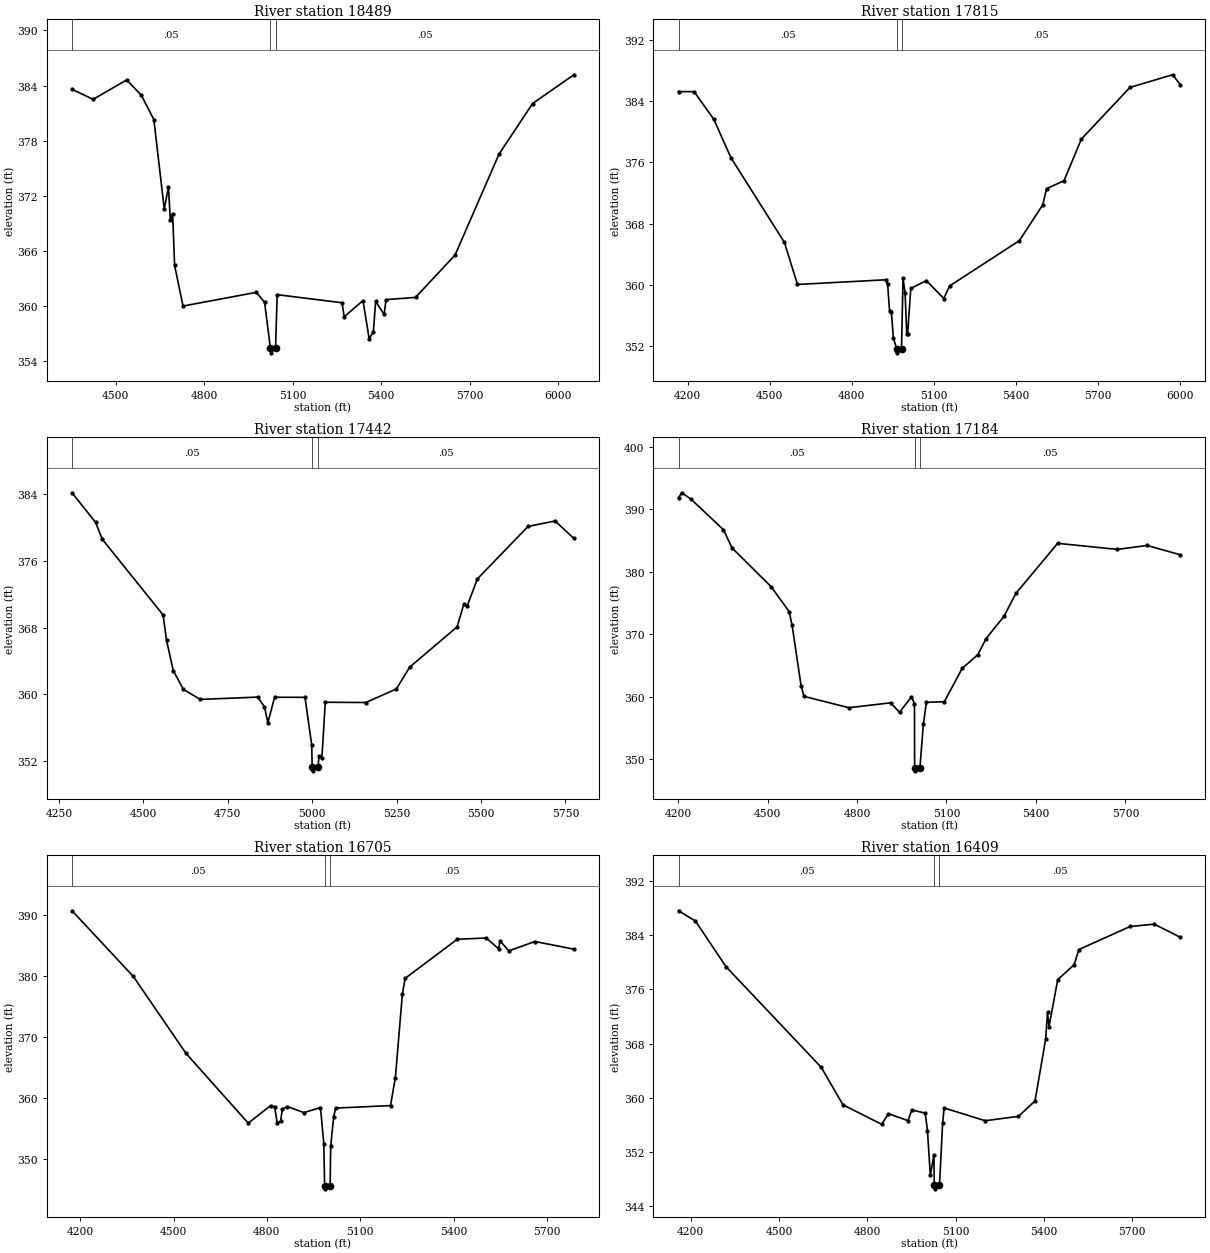
Type RM Length L Ch R = 1 ,18489   ,674,674,674
BEGIN DESCRIPTION:
Caney Creek 498
END DESCRIPTION:
XS GIS Cut Line= 3
      2713086.27      6844320.15      2713519.89      6844818.48
      2714197.02      6845607.09
#Sta/Elev= 30
  4352.5  383.59  4423.6  382.49  4537.5  384.61  4586.9  382.95  4629.6  380.29
  4664.8  370.54    4679  372.91  4685.6   369.3  4693.2  370.05  4699.9  364.39
  4728.4  359.97  4976.6  361.46  5004.7  360.38  5024.4  355.37  5026.4  354.87
  5041.9  355.37  5047.4  361.21  5266.9  360.33  5274.6   358.8  5338.2  360.57
  5359.1  356.39  5373.3  357.18    5381  360.48  5409.6  359.05  5416.1  360.67
    5516  360.91  5649.9  365.52  5799.1  376.53  5912.7  382.04  6052.5  385.17
#Mann= 3 ,-1 , 0
  4352.5     .05       0  5024.4     .04       0  5041.9     .05       0
Bank Sta=5024.4,5041.9
XS Rating Curve= 0 ,0
Exp/Cntr=0.3,0.1

Type RM Length L Ch R = 1 ,17815   ,373,373,373
BEGIN DESCRIPTION:
Caney Creek 521
END DESCRIPTION:
XS GIS Cut Line= 4
      2713185.89      6844465.74      2713310.24      6844966.44
      2713525.08      6845205.16      2714182.06      6845954.72
#Sta/Elev= 30
  4166.7  385.22  4223.6  385.21  4295.8   381.6  4358.3  376.59  4553.4  365.58
  4601.3  360.08  4923.6  360.69  4930.9  360.08  4937.8  356.68  4944.5  356.44
    4952  353.11  4964.1  351.67  4966.1  351.17  4981.6  351.67  4987.1  360.87
  4994.6  359.03  5000.7  353.65  5003.8  353.65  5015.5  359.57  5072.4  360.58
    5136  358.25  5157.8   359.9  5412.2  365.79  5497.6  370.45  5511.8  372.57
  5575.4   373.6    5639  379.04  5816.4  385.76  5972.1  387.41  6000.5  386.14
#Mann= 3 ,-1 , 0
  4166.7     .05       0  4964.1     .04       0  4981.6     .05       0
Bank Sta=4964.1,4981.6
XS Rating Curve= 0 ,0
Exp/Cntr=0.3,0.1

Type RM Length L Ch R = 1 ,17442   ,258,258,258
BEGIN DESCRIPTION:
Caney Creek 496
END DESCRIPTION:
XS GIS Cut Line= 3
      2713199.95       6844551.4      2713209.67      6845278.93
      2713179.05      6846036.42
#Sta/Elev= 30
  4289.1  384.16  4358.7  380.61  4378.7  378.58  4558.7  369.51  4568.7  366.49
  4588.7  362.85  4618.7  360.59  4668.7  359.39  4838.7  359.67  4858.8   358.5
  4868.8  356.59  4888.8  359.65  4978.8  359.64  4998.8  353.88  4999.9  351.33
  5001.9  350.83  5017.6  351.33  5020.2  352.64  5028.8  352.41  5038.8  359.05
  5158.9  359.02    5249  360.64    5289  363.27  5429.1  368.09  5449.1  370.83
  5459.1  370.61  5489.2  373.84  5639.3  380.13  5719.3  380.78  5774.8  378.69
#Mann= 3 ,-1 , 0
  4289.1     .05       0  4999.9     .04       0  5017.6     .05       0
Bank Sta=4999.9,5017.6
XS Rating Curve= 0 ,0
Exp/Cntr=0.3,0.1

Type RM Length L Ch R = 1 ,17184   ,479,479,479
BEGIN DESCRIPTION:
Caney Creek 495
END DESCRIPTION:
XS GIS Cut Line= 3
      2712998.19      6844510.33      2712966.48       6845314.9
      2712941.92      6846192.36
#Sta/Elev= 30
  4201.3   391.8    4212  392.61    4242  391.64  4352.1   386.7  4380.5  383.81
  4512.2  377.58  4572.3  373.62  4582.3  371.41  4612.3  361.78  4622.3  360.07
  4772.4  358.26  4912.5  359.04  4942.5  357.53  4982.6     360  4992.6  358.91
  4993.2  348.67  4995.2  348.17  5010.9  348.67  5022.6  355.68  5032.6  359.12
  5092.6  359.21  5152.7  364.55  5205.1  366.73  5232.7   369.3  5292.7  372.85
  5332.7  376.52  5472.8  384.53  5672.9  383.56  5772.9  384.19  5884.3   382.7
#Mann= 3 ,-1 , 0
  4201.3     .05       0  4993.2     .04       0  5010.9     .05       0
Bank Sta=4993.2,5010.9
XS Rating Curve= 0 ,0
Exp/Cntr=0.3,0.1

Type RM Length L Ch R = 1 ,16705   ,296,296,296
BEGIN DESCRIPTION:
Caney Creek 500
END DESCRIPTION:
XS GIS Cut Line= 3
      2712922.47      6844545.02      2712627.13       6845317.5
      2712402.72      6846070.88
#Sta/Elev= 30
  4173.8  390.72  4370.7  379.95  4540.4  367.32  4740.1   355.9  4811.9  358.77
  4824.9  358.57  4833.3  355.96    4844  356.21  4849.6  358.15  4865.4  358.63
  4918.9  357.63  4972.4  358.45  4983.1  352.52  4985.7  345.63  4987.7  345.13
  5003.4  345.63  5005.2  352.19  5014.9  356.96  5021.2  358.37  5197.5  358.78
  5213.1  363.38  5235.8  377.14  5244.5  379.64  5412.1  386.05  5505.3  386.26
  5544.8  384.49    5550  385.76  5577.9  384.15  5661.8  385.68  5786.9  384.43
#Mann= 3 ,-1 , 0
  4173.8     .05       0  4985.7     .04       0  5003.4     .05       0
Bank Sta=4985.7,5003.4
XS Rating Curve= 0 ,0
Exp/Cntr=0.3,0.1

Type RM Length L Ch R = 1 ,16409   ,563,563,563
BEGIN DESCRIPTION:
Caney Creek 497
END DESCRIPTION:
XS GIS Cut Line= 3
      2712785.83      6844354.83      2712419.78       6845136.1
      2712229.27      6845956.91
#Sta/Elev= 30
  4158.6  387.63  4216.1  386.11    4320  379.36  4643.6  364.48  4717.6  358.93
    4849  356.05  4871.9  357.62  4938.4   356.6  4951.4  358.17  4997.1  357.71
  5004.7   355.1  5014.4  348.49  5026.5  351.53  5027.8  347.01  5029.8  346.51
  5045.5  347.01  5056.1  356.19  5061.3  358.47  5200.9  356.58  5313.8  357.23
  5370.1   359.5  5406.2  368.61  5412.7  372.59  5417.8  370.51  5447.3  377.44
  5503.1  379.65  5519.2   381.9  5693.7  385.31  5775.8  385.65    5864  383.71
#Mann= 3 ,-1 , 0
  4158.6     .05       0  5027.8     .04       0  5045.5     .05       0
Bank Sta=5027.8,5045.5
XS Rating Curve= 0 ,0
Exp/Cntr=0.3,0.1

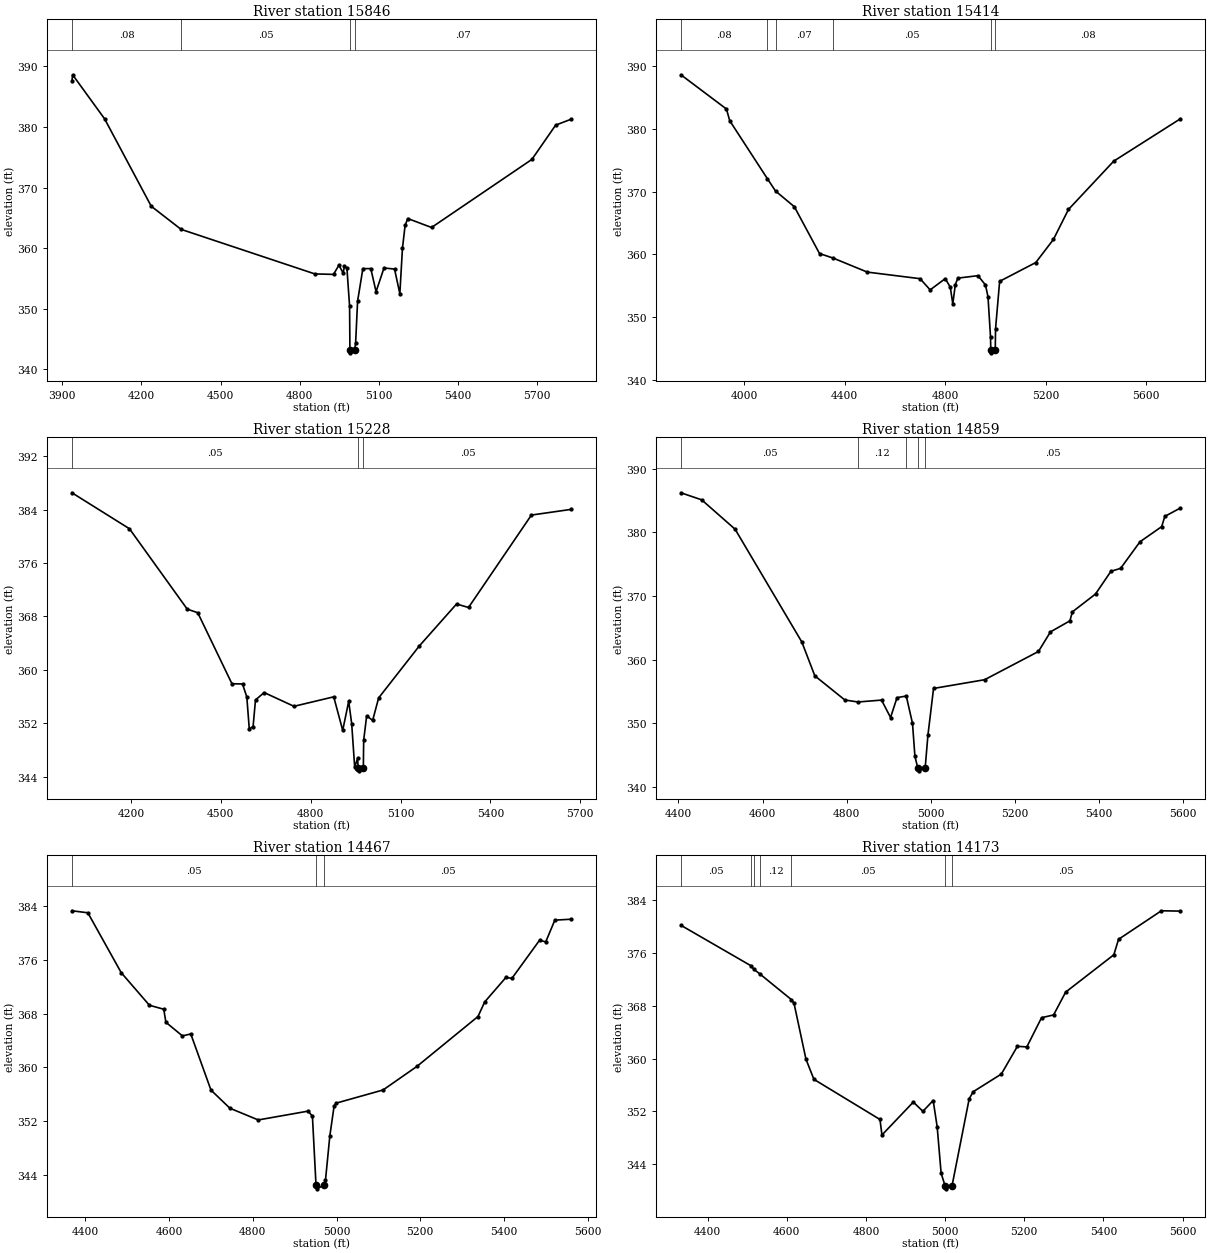
Type RM Length L Ch R = 1 ,15846   ,432,432,432
BEGIN DESCRIPTION:
Caney Creek 520
END DESCRIPTION:
XS GIS Cut Line= 3
      2712171.39      6843863.35      2711993.75        6844921.
      2711959.21      6845740.91
#Sta/Elev= 30
  3936.7  387.53  3939.2  388.63  4060.4  381.35  4237.2  366.91  4350.3  363.09
  4857.1  355.73    4928  355.65  4948.3  357.17  4964.5  355.88  4969.5  357.04
  4978.7  356.71  4988.9  350.39  4990.1  343.19  4992.1  342.69  5007.9  343.19
  5011.7  344.25  5019.2  351.23  5039.2   356.6  5069.2  356.61  5089.2   352.8
  5119.3  356.71  5159.3  356.53  5179.3  352.46  5189.3  360.01  5199.3  363.73
  5209.3  364.88  5299.4   363.4  5679.8  374.65  5769.8  380.31  5829.8  381.31
#Mann= 4 ,-1 , 0
  3936.7     .08       0  4350.3     .05       0  4990.1     .05       0
  5007.9     .07       0
Bank Sta=4990.1,5007.9
XS Rating Curve= 0 ,0
Exp/Cntr=0.3,0.1

Type RM Length L Ch R = 1 ,15414   ,186,186,186
BEGIN DESCRIPTION:
Caney Creek 493
END DESCRIPTION:
XS GIS Cut Line= 3
      2711624.06       6843709.9      2711669.88      6844978.62
      2711697.49      6845696.14
#Sta/Elev= 30
  3748.6  388.58  3929.8  383.13  3942.8  381.27  4092.7  372.04  4125.1  370.08
    4200  367.58  4300.1  360.13  4353.7  359.42  4490.1  357.18  4700.3  356.13
  4740.3  354.35  4800.4  356.14  4820.4  354.79  4830.4  352.12  4840.4  355.16
  4850.4  356.22  4930.5  356.61  4960.5  355.13  4970.5  353.24  4980.5  346.86
  4981.6  344.83  4983.6  344.33  4999.4  344.83  5000.5  348.15  5016.8  355.71
  5160.6   358.7  5230.7  362.37  5290.7  367.15  5470.9  374.84  5736.2  381.58
#Mann= 6 ,-1 , 0
  3748.6     .08       0  4092.7      .1       0  4125.1     .07       0
  4353.7     .05       0  4981.6     .03       0  4999.4     .08       0
Bank Sta=4981.6,4999.4
XS Rating Curve= 0 ,0
Exp/Cntr=0.3,0.1

Type RM Length L Ch R = 1 ,15228   ,369,369,369
BEGIN DESCRIPTION:
Caney Creek 494
END DESCRIPTION:
XS GIS Cut Line= 3
      2710848.26      6844399.09      2711526.54      6844925.49
      2711511.66      6845734.77
#Sta/Elev= 30
  4002.8  386.53  4194.8  381.14  4387.6   369.1  4422.9  368.55    4537  357.91
  4572.3  357.88  4586.7  355.93  4594.9  351.15  4607.6  351.49  4615.7  355.49
  4644.7  356.59  4744.2  354.53  4876.9  355.95  4906.9  350.93  4926.9  355.27
  4936.9  351.92  4946.9  345.39  4956.9  346.78    4958  345.36    4960  344.86
  4975.8  345.36  4976.9  349.45  4986.9   353.1  5006.9  352.42  5026.9  355.79
  5162.4  363.56    5287  369.86    5327  369.34    5537  383.19  5670.8  384.05
#Mann= 3 ,-1 , 0
  4002.8     .05       0    4958     .04       0  4975.8     .05       0
Bank Sta=4958,4975.8
XS Rating Curve= 0 ,0
Exp/Cntr=0.3,0.1

Type RM Length L Ch R = 1 ,14859   ,392,392,392
BEGIN DESCRIPTION:
Caney Creek 492
END DESCRIPTION:
XS GIS Cut Line= 3
       2710902.6      6844618.16      2711221.13      6845139.78
      2711460.27       6845664.8
#Sta/Elev= 30
  4405.8  386.22  4455.2  385.11  4534.6   380.5  4693.4  362.77  4724.3  357.45
  4795.8  353.65  4827.1  353.34    4883  353.64  4904.4   350.9  4919.8  354.02
  4941.8  354.28  4956.6  349.99  4962.4  344.79    4969  343.02    4971  342.52
  4986.8  343.02  4993.3  348.12  5006.7  355.47  5128.2  356.84  5256.2  361.28
  5284.8  364.36  5330.9  366.09    5337  367.51  5391.9  370.31  5428.6  373.88
  5451.6  374.34  5497.7  378.52  5549.3   380.9  5556.8  382.51  5593.9  383.83
#Mann= 5 ,-1 , 0
  4405.8     .05       0  4827.1     .12       0  4941.8     .05       0
    4969     .04       0  4986.8     .05       0
Bank Sta=4969,4986.8
XS Rating Curve= 0 ,0
Exp/Cntr=0.3,0.1

Type RM Length L Ch R = 1 ,14467   ,294,294,294
BEGIN DESCRIPTION:
Caney Creek 491
END DESCRIPTION:
XS GIS Cut Line= 3
      2710791.29      6844667.51      2710966.41      6845294.99
      2711232.42      6845767.38
#Sta/Elev= 30
  4367.7  383.27  4405.7  382.97  4485.5  374.07  4552.8  369.24    4587  368.65
  4592.2  366.71  4631.6  364.69  4651.6  364.98  4699.9  356.64  4745.1  353.95
  4812.8  352.21    4932  353.52  4942.3  352.76  4950.9  342.48  4952.9  341.98
  4968.8  342.48  4973.5  343.27  4983.9  349.85  4994.1  354.28  4999.2  354.71
  5111.1  356.66    5192  360.16  5337.9  367.57  5353.9  369.73  5404.8  373.38
  5418.9  373.23  5485.1   378.9  5499.8  378.65  5521.5  381.88  5561.3  382.02
#Mann= 3 ,-1 , 0
  4367.7     .05       0  4950.9     .04       0  4968.8     .05       0
Bank Sta=4950.9,4968.8
XS Rating Curve= 0 ,0
Exp/Cntr=0.3,0.1

Type RM Length L Ch R = 1 ,14173   ,148,148,148
BEGIN DESCRIPTION:
Caney Creek 490
END DESCRIPTION:
XS GIS Cut Line= 3
      2710693.69      6844696.47      2710757.51      6845373.33
      2710858.84      6845946.58
#Sta/Elev= 30
  4332.7  380.24  4510.5  374.07  4516.8  373.57  4531.5  372.89  4611.7  368.97
  4618.5  368.39  4648.6  359.93  4668.7  356.87  4835.6  350.78  4840.6  348.43
  4919.8  353.42  4944.1  352.02    4970  353.66  4980.1  349.68  4990.1  342.62
  4999.9  340.76  5001.9  340.26  5017.8  340.76    5061  353.92  5071.1  354.99
  5142.2  357.67  5182.8  361.88  5206.6  361.79  5243.8  366.22  5274.2  366.64
  5304.7   370.1  5426.5  375.77  5438.3  378.11  5546.5  382.44  5594.7  382.39
#Mann= 7 ,-1 , 0
  4332.7     .05       0  4510.5     .12       0  4516.8     .05       0
  4531.5     .12       0  4611.7     .05       0  4999.9     .04       0
  5017.8     .05       0
Bank Sta=4999.9,5017.8
XS Rating Curve= 0 ,0
Exp/Cntr=0.3,0.1

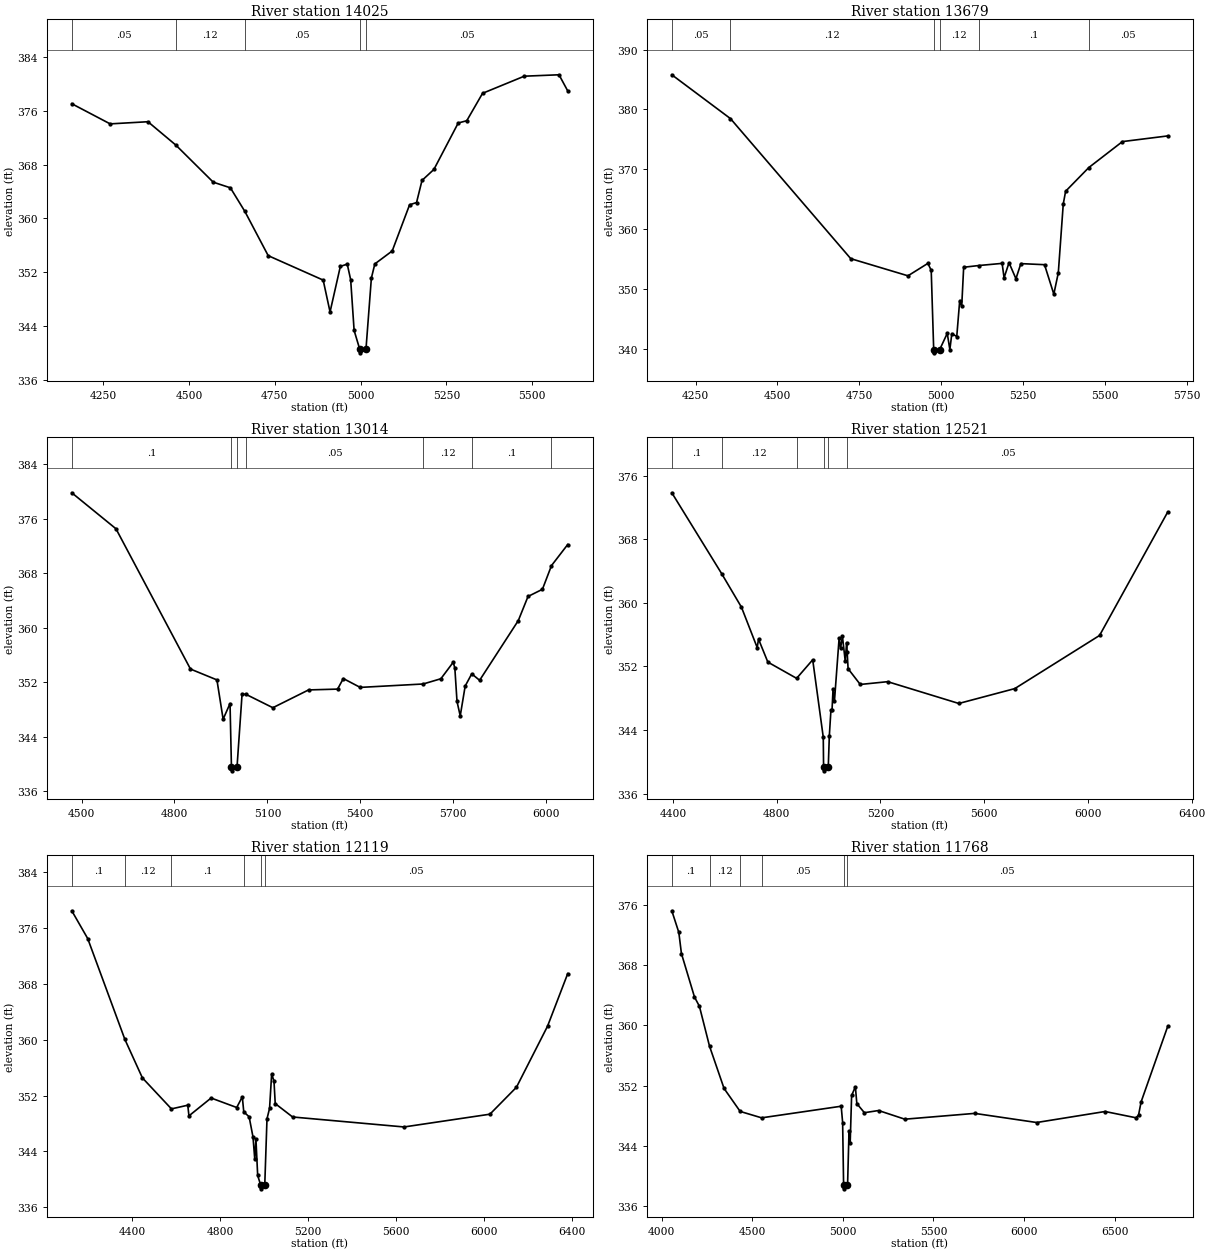
Type RM Length L Ch R = 1 ,14025   ,346,346,346
BEGIN DESCRIPTION:
Caney Creek 489
END DESCRIPTION:
XS GIS Cut Line= 3
      2710586.44      6844569.34      2710624.32      6845417.04
      2710716.56      6846006.12
#Sta/Elev= 30
  4158.5  377.08  4270.3  374.08  4380.4   374.4  4461.7  370.92  4570.6   365.4
  4620.6  364.56  4662.8  361.04  4730.7  354.46  4890.9  350.82  4910.9  346.08
  4940.9  352.86    4961   353.2    4971  350.87    4981  343.33  4997.6  340.49
  4999.6  339.99  5015.5  340.49  5031.3  351.12  5041.4  353.23    5092  355.16
  5142.6  362.03  5162.9  362.37  5178.8  365.66  5213.5   367.3  5284.3  374.21
  5309.2  374.55  5355.2  378.63  5476.7  381.18  5577.9  381.39  5603.3  378.99
#Mann= 5 ,-1 , 0
  4158.5     .05       0  4461.7     .12       0  4662.8     .05       0
  4997.6     .04       0  5015.5     .05       0
Bank Sta=4997.6,5015.5
XS Rating Curve= 0 ,0
Exp/Cntr=0.3,0.1

Type RM Length L Ch R = 1 ,13679   ,665,665,665
BEGIN DESCRIPTION:
Caney Creek 488
END DESCRIPTION:
XS GIS Cut Line= 3
      2710117.34      6844657.33      2710298.35      6845481.82
      2710667.28      6846041.43
#Sta/Elev= 30
  4177.6  385.81  4356.8  378.47    4724  355.04  4898.7  352.17  4959.5  354.25
  4969.7  353.09  4977.3  339.78  4979.3  339.28  4995.2  339.78  5018.7  342.54
  5026.6  339.82  5032.7   342.5  5047.7  342.01  5056.7  348.02  5062.8  347.04
  5068.8   353.6  5114.8  353.89  5186.2  354.25  5192.2  351.84  5207.3  354.36
  5228.4  351.68  5243.4  354.21  5315.7  354.03  5344.1   349.1  5357.8  352.68
  5372.9  364.18  5380.1  366.32  5450.8  370.28  5553.6  374.63    5692  375.58
#Mann= 6 ,-1 , 0
  4177.6     .05       0  4356.8     .12       0  4977.3     .07       0
  4995.2     .12       0  5114.8      .1       0  5450.8     .05       0
Bank Sta=4977.3,4995.2
XS Rating Curve= 0 ,0
Exp/Cntr=0.3,0.1

Type RM Length L Ch R = 1 ,13014   ,493,493,493
BEGIN DESCRIPTION:
Caney Creek 487
END DESCRIPTION:
XS GIS Cut Line= 3
      2709462.71       6845010.7      2709694.86      6845649.85
      2710579.04      6845909.07
#Sta/Elev= 30
  4468.4  379.82  4611.1  374.54  4851.7  353.96  4937.1  352.37  4957.1  346.61
  4979.4   348.9    4984  339.53    4986  339.03  5001.9  339.53  5018.3  350.29
  5031.4  350.24  5117.7  348.29    5233   350.9  5326.7  351.02  5345.2  352.57
  5399.7  351.27    5603  351.77  5660.2  352.54  5700.1  354.96  5705.3  354.11
  5712.3  349.21  5722.7  347.09  5738.7  351.47  5759.9  353.26  5785.3  352.31
  5910.3  361.08  5941.6  364.61  5988.1  365.66  6017.4  369.14  6069.8  372.23
#Mann= 7 ,-1 , 0
  4468.4      .1       0    4984     .07       0  5001.9      .1       0
  5031.4     .05       0    5603     .12       0  5759.9      .1       0
  6017.4     .05       0
Bank Sta=4984,5001.9
XS Rating Curve= 0 ,0
Exp/Cntr=0.3,0.1

Type RM Length L Ch R = 1 ,12521   ,402,402,402
BEGIN DESCRIPTION:
Caney Creek 481
END DESCRIPTION:
XS GIS Cut Line= 3
      2709412.48      6845067.16      2709298.71      6845674.18
      2709811.52      6846862.35
#Sta/Elev= 30
  4395.9  373.83  4587.9  363.67  4664.3  359.45    4725  354.37  4730.1  355.43
  4766.1  352.54    4877   350.5    4939  352.83  4979.7   343.1  4980.9  339.37
  4982.9  338.87    4999  339.37  5003.1  343.28  5009.3  346.52  5013.5  346.52
  5017.4  349.16  5022.8  347.63  5040.9  355.59  5046.3  354.26  5053.6  355.77
  5064.4  352.67  5069.8     355  5071.9  353.77  5075.4  351.71  5122.3  349.73
  5227.9  350.08  5502.2  347.34    5718  349.21  6044.7  355.89  6307.6  371.42
#Mann= 6 ,-1 , 0
  4395.9      .1       0  4587.9     .12       0    4877      .1       0
  4980.9     .07       0    4999      .1       0  5071.9     .05       0
Bank Sta=4980.9,4999
XS Rating Curve= 0 ,0
Exp/Cntr=0.3,0.1

Type RM Length L Ch R = 1 ,12119   ,351,351,351
BEGIN DESCRIPTION:
Caney Creek 477
END DESCRIPTION:
XS GIS Cut Line= 3
      2709307.13      6844982.54      2708964.59      6845960.74
      2709760.57      6846886.04
#Sta/Elev= 30
  4124.7  378.48  4197.2   374.5  4366.4  360.04    4446  354.53  4578.3  350.08
  4652.6  350.61  4657.9  349.08  4758.8  351.64  4875.3  350.28  4900.8  351.81
  4907.4  349.65  4931.8  348.95  4949.5  346.04  4957.5  342.85  4962.8  345.75
  4970.7  340.54  4984.8  339.12  4986.8  338.62  5002.9  339.12  5013.1  348.66
  5024.8  350.16  5034.3  355.06  5044.9   354.1  5050.6  350.84  5129.6  348.92
    5637  347.49  6027.6  349.32  6148.3  353.18  6289.8  361.93  6381.7  369.47
#Mann= 6 ,-1 , 0
  4124.7      .1       0  4366.4     .12       0  4578.3      .1       0
  4907.4     .05       0  4984.8     .04       0  5002.9     .05       0
Bank Sta=4984.8,5002.9
XS Rating Curve= 0 ,0
Exp/Cntr=0.3,0.1

Type RM Length L Ch R = 1 ,11768   ,0,0,0
BEGIN DESCRIPTION:
Caney Creek 480
END DESCRIPTION:
XS GIS Cut Line= 3
       2709272.5      6845022.42      2708474.11      6846022.47
      2709628.75      6846914.76
#Sta/Elev= 30
    4055   375.2  4093.7  372.33  4108.1  369.53  4180.2  363.76  4207.4  362.53
  4263.2  357.24  4343.5  351.63  4432.5  348.58  4550.9  347.73  4990.4  349.27
  4998.4  347.11  5003.7  338.81  5005.7  338.31  5021.8  338.81  5025.7  338.86
  5033.6  345.96    5040  344.35    5048   350.7  5068.8  351.85  5076.8  349.62
  5118.5  348.41  5196.9   348.7  5341.9  347.55  5727.7  348.32    6070  347.11
  6447.7  348.57  6617.9  347.74  6632.4  348.08  6646.9  349.86  6793.9  359.88
#Mann= 6 ,-1 , 0
    4055      .1       0  4263.2     .12       0  4432.5      .1       0
  4550.9     .05       0  5003.7     .04       0  5021.8     .05       0
Bank Sta=5003.7,5021.8
XS Rating Curve= 0 ,0
Exp/Cntr=0.3,0.1

Chan Stop Cuts=-1
Use User Specified Reach Order=0
Composite Channel Slope=5