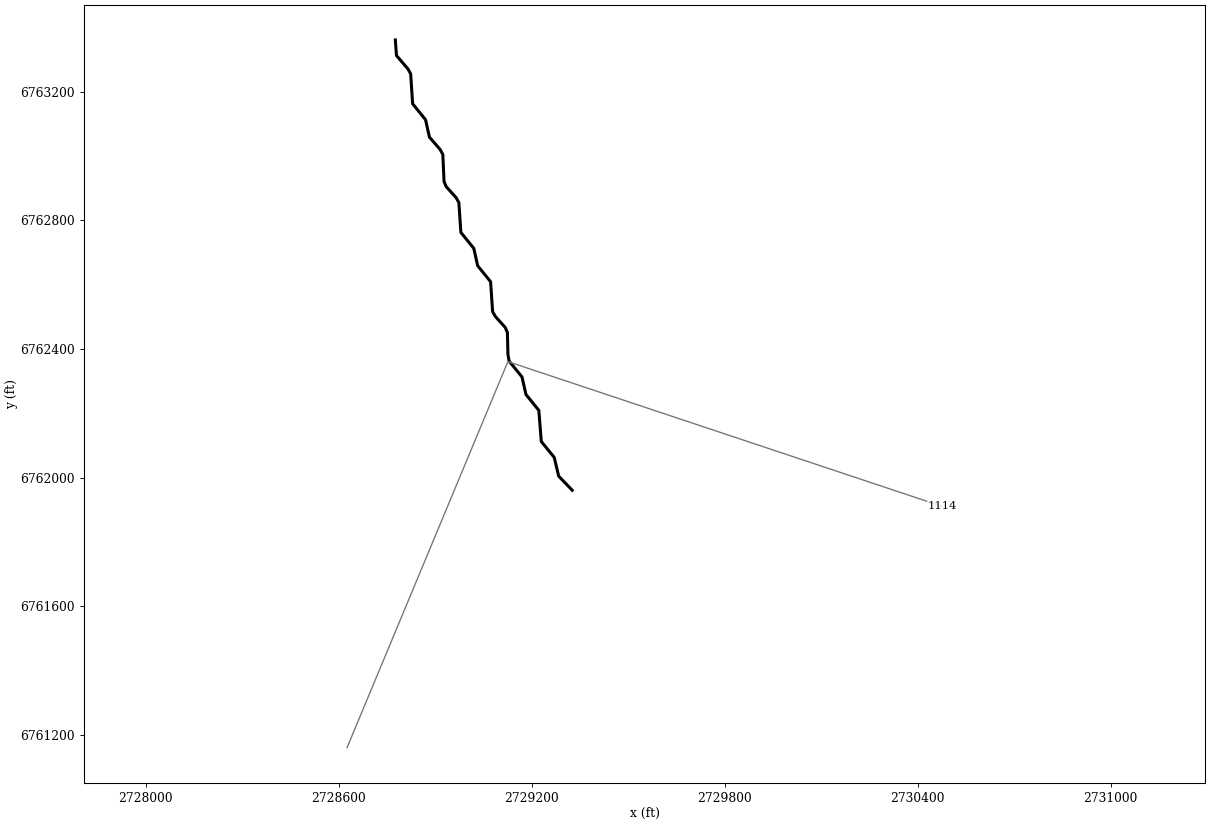
--- Caney Creek T 1.prj (project) ---

Proj Title=Caney Creek T 1 Base Level Engineering
Current Plan=p01
Default Exp/Contr=0.3,0.1
English Units
Geom File=g01
Flow File=f01
Plan File=p01
BEGIN DESCRIPTION:
Caney Creek T 1
END DESCRIPTION:

--- Caney Creek T 1.p01 (plan) ---

Plan Title=Multiple Run
Short Identifier=Multiple
Geom File=g01
Flow File=f01
Subcritical Flow
K Sum by GR= 0
Std Step Tol= 0.01
Critical Tol= 0.01
Num of Std Step Trials= 20
Max Error Tol= 0.3
Flow Tol Ratio= 0.001
Split Flow NTrial= 30
Split Flow Tol= 0.02
Split Flow Ratio= 0.02
Log Output Level= 0
Friction Slope Method= 1
Unsteady Friction Slope Method= 2
Unsteady Bridges Friction Slope Method= 1
Parabolic Critical Depth
Global Vel Dist=  1 , 1 , 1
Global Log Level= 0
CheckData=True
Encroach Param= -1, 0, 0, 0
BEGIN DESCRIPTION:
Multiple Run
END DESCRIPTION:

--- Caney Creek T 1.f01 (steady flow) ---

Flow Title=Multiple
Number of Profiles=7
Profile Names=10-year,25-year,50-year,1pct_min,100-year,1pct_plu,500-year
River Rch & RM= Caney Creek T 1,Reach-1,1114
     402     522     616     361     721    1438     985
Boundary for River Rch & Prof#=Caney Creek T 1,Reach-1,1
Up Type=0
Dn Type=3
Dn Slope=0.005
Boundary for River Rch & Prof#=Caney Creek T 1,Reach-1,2
Up Type=0
Dn Type=3
Dn Slope=0.005
Boundary for River Rch & Prof#=Caney Creek T 1,Reach-1,3
Up Type=0
Dn Type=3
Dn Slope=0.005
Boundary for River Rch & Prof#=Caney Creek T 1,Reach-1,4
Up Type=0
Dn Type=3
Dn Slope=0.005
Boundary for River Rch & Prof#=Caney Creek T 1,Reach-1,5
Up Type=0
Dn Type=3
Dn Slope=0.005
Boundary for River Rch & Prof#=Caney Creek T 1,Reach-1,6
Up Type=0
Dn Type=3
Dn Slope=0.005
Boundary for River Rch & Prof#=Caney Creek T 1,Reach-1,7
Up Type=0
Dn Type=3
Dn Slope=0.005

--- Caney Creek T 1.g01 (geometry) ---

Geom Title=Existing Conditions

River Reach=Caney Creek T 1,Reach-1
Reach XY= 30
      2729326.00      6761961.00      2729283.91      6762004.85
      2729269.97      6762063.22      2729229.82      6762112.58
      2729222.17      6762209.42      2729182.11      6762258.82
      2729169.89      6762313.18      2729129.83      6762362.58
      2729126.08      6762383.76      2729124.51      6762451.29
      2729117.81      6762467.04      2729086.89      6762501.37
      2729078.47      6762516.57      2729072.17      6762609.42
      2729032.11      6762658.82      2729019.89      6762713.18
      2728979.83      6762762.58      2728973.53      6762855.43
      2728965.11      6762870.63      2728934.19      6762904.96
      2728927.49      6762920.71      2728923.67      6763005.03
      2728915.16      6763020.65      2728882.11      6763058.82
      2728869.89      6763113.18      2728829.82      6763162.58
      2728823.66      6763255.49      2728815.39      6763270.75
      2728779.64      6763312.51      2728776.00      6763361.00

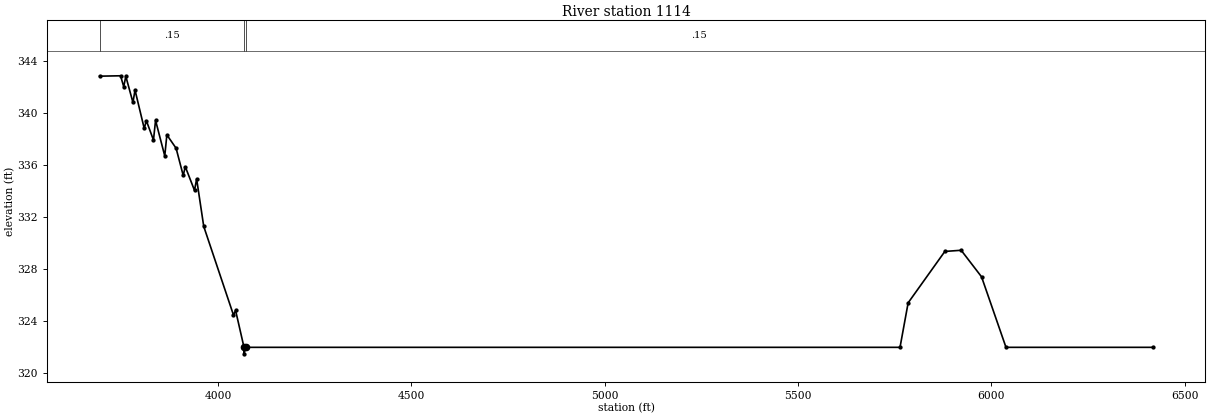
Type RM Length L Ch R = 1,1114,0,0,0
BEGIN DESCRIPTION:
Caney Creek T 1 1.0
END DESCRIPTION:
XS GIS Cut Line= 3
      2728626.01      6761161.03      2729126.00      6762361.00
      2730476.01      6761911.00
#Sta/Elev= 30
  3694.2  342.84  3748.3  342.87  3756.5  342.03  3761.9  342.83  3780.3  340.82
  3785.7  341.77  3809.5  338.82  3815.0  339.42  3833.4  337.93  3838.8  339.44
  3862.6  336.71  3868.0  338.33  3891.9  337.30  3910.3  335.21  3915.7  335.88
  3939.5  334.06  3945.0  334.94  3963.4  331.29  4040.3  324.48  4045.7  324.84
  4067.5  322.00  4067.8  321.50  4071.5  322.00  5763.7  322.00  5784.7  325.42
  5879.6  329.37  5921.8  329.46  5974.5  327.42  6037.7  322.00  6417.2  322.00
#Mann=3,-1,0
  3694.2    0.15       0  4067.5    0.05       0  4071.5    0.15       0
Bank Sta=4067.5,4071.5
Exp/Cntr=0.3,0.1

Chan Stop Cuts=-1