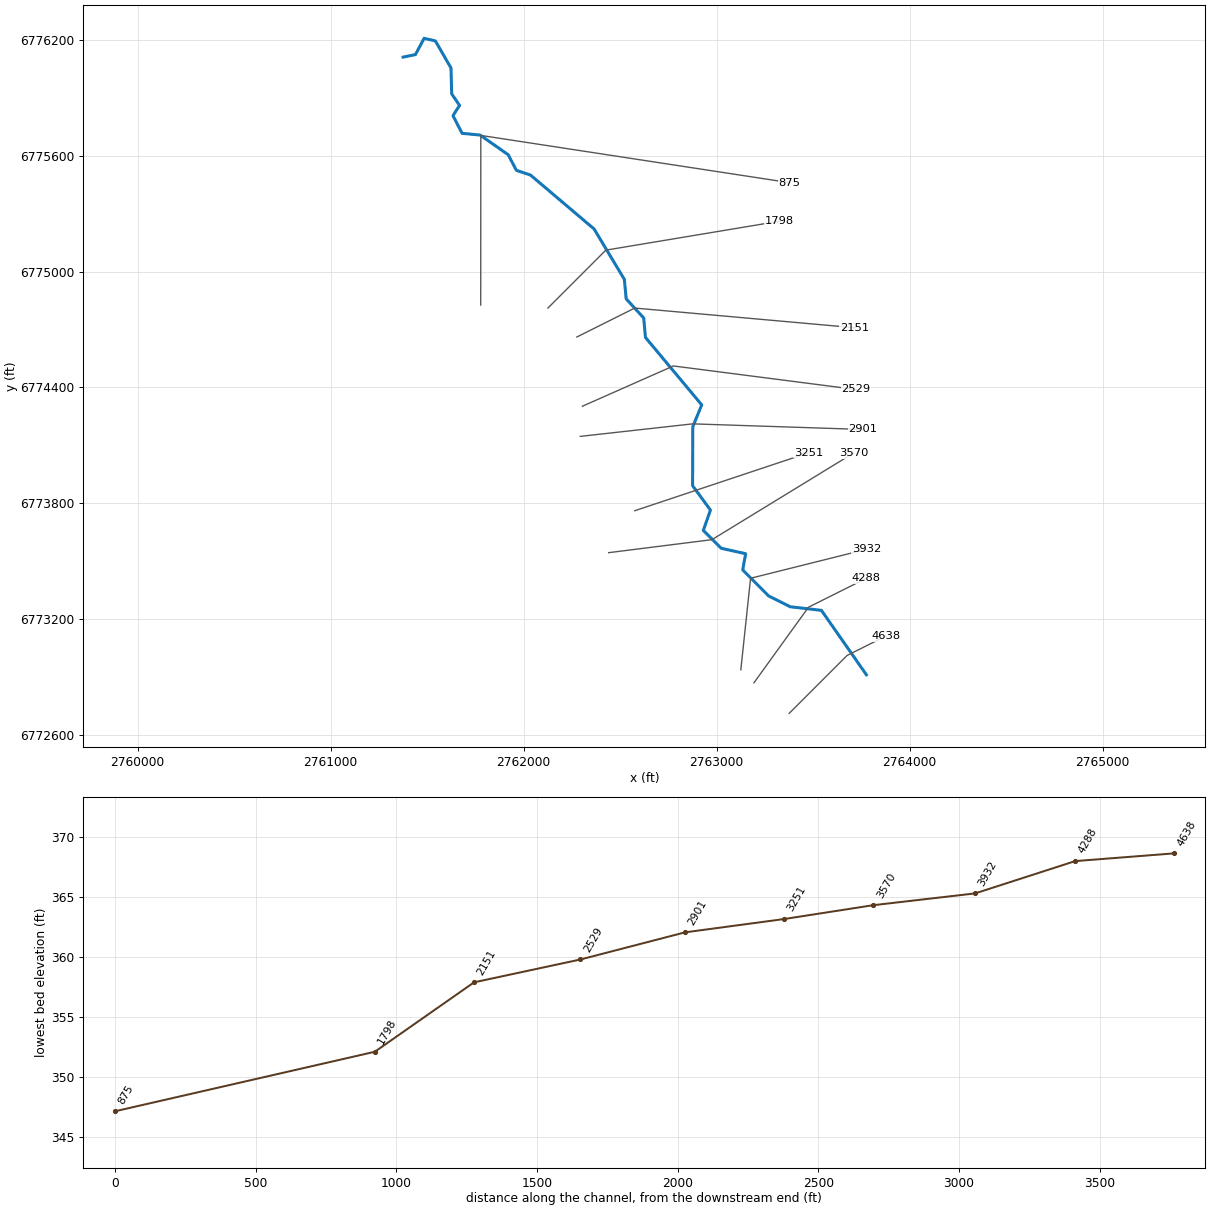
--- Caney Creek T 10.prj (project) ---

Proj Title=Caney Creek T 10 Base Level Engineering
Current Plan=p01
Default Exp/Contr=0.3,0.1
English Units
Geom File=g01
Flow File=f01
Plan File=p01
BEGIN DESCRIPTION:
Caney Creek T 10
END DESCRIPTION:

--- Caney Creek T 10.p01 (plan) ---

Plan Title=Multiple Run
Short Identifier=Multiple
Geom File=g01
Flow File=f01
Subcritical Flow
K Sum by GR= 0
Std Step Tol= 0.01
Critical Tol= 0.01
Num of Std Step Trials= 20
Max Error Tol= 0.3
Flow Tol Ratio= 0.001
Split Flow NTrial= 30
Split Flow Tol= 0.02
Split Flow Ratio= 0.02
Log Output Level= 0
Friction Slope Method= 1
Unsteady Friction Slope Method= 2
Unsteady Bridges Friction Slope Method= 1
Parabolic Critical Depth
Global Vel Dist=  1 , 1 , 1
Global Log Level= 0
CheckData=True
Encroach Param= -1, 0, 0, 0
BEGIN DESCRIPTION:
Multiple Run
END DESCRIPTION:

--- Caney Creek T 10.f01 (steady flow) ---

Flow Title=Multiple
Number of Profiles=7
Profile Names=10-year,25-year,50-year,1pct_min,100-year,1pct_plu,500-year
River Rch & RM= Caney Creek T 10,Reach-1,4638
     603     820     998     605    1207    2409    1768
Boundary for River Rch & Prof#=Caney Creek T 10,Reach-1,1
Up Type=0
Dn Type=3
Dn Slope=0.005
Boundary for River Rch & Prof#=Caney Creek T 10,Reach-1,2
Up Type=0
Dn Type=3
Dn Slope=0.005
Boundary for River Rch & Prof#=Caney Creek T 10,Reach-1,3
Up Type=0
Dn Type=3
Dn Slope=0.005
Boundary for River Rch & Prof#=Caney Creek T 10,Reach-1,4
Up Type=0
Dn Type=3
Dn Slope=0.005
Boundary for River Rch & Prof#=Caney Creek T 10,Reach-1,5
Up Type=0
Dn Type=3
Dn Slope=0.005
Boundary for River Rch & Prof#=Caney Creek T 10,Reach-1,6
Up Type=0
Dn Type=3
Dn Slope=0.005
Boundary for River Rch & Prof#=Caney Creek T 10,Reach-1,7
Up Type=0
Dn Type=3
Dn Slope=0.005

--- Caney Creek T 10.g01 (geometry) ---

Geom Title=Existing Conditions

River Reach=Caney Creek T 10,Reach-1
Reach XY= 30
      2763776.00      6772911.00      2763543.14      6773244.72
      2763381.52      6773263.36      2763269.94      6773319.14
      2763135.31      6773454.34      2763150.41      6773538.12
      2763023.56      6773566.52      2762931.11      6773658.70
      2762968.16      6773764.40      2762875.57      6773890.82
      2762876.54      6774195.79      2762922.87      6774309.37
      2762631.52      6774658.57      2762622.37      6774759.50
      2762531.54      6774858.58      2762522.17      6774959.41
      2762365.23      6775220.70      2762035.66      6775500.22
      2761962.47      6775524.55      2761920.37      6775605.35
      2761774.43      6775707.35      2761681.41      6775716.26
      2761634.22      6775807.73      2761668.20      6775860.90
      2761627.55      6775920.59      2761623.75      6776055.07
      2761542.86      6776195.03      2761484.52      6776208.44
      2761439.74      6776124.38      2761376.00      6776111.00

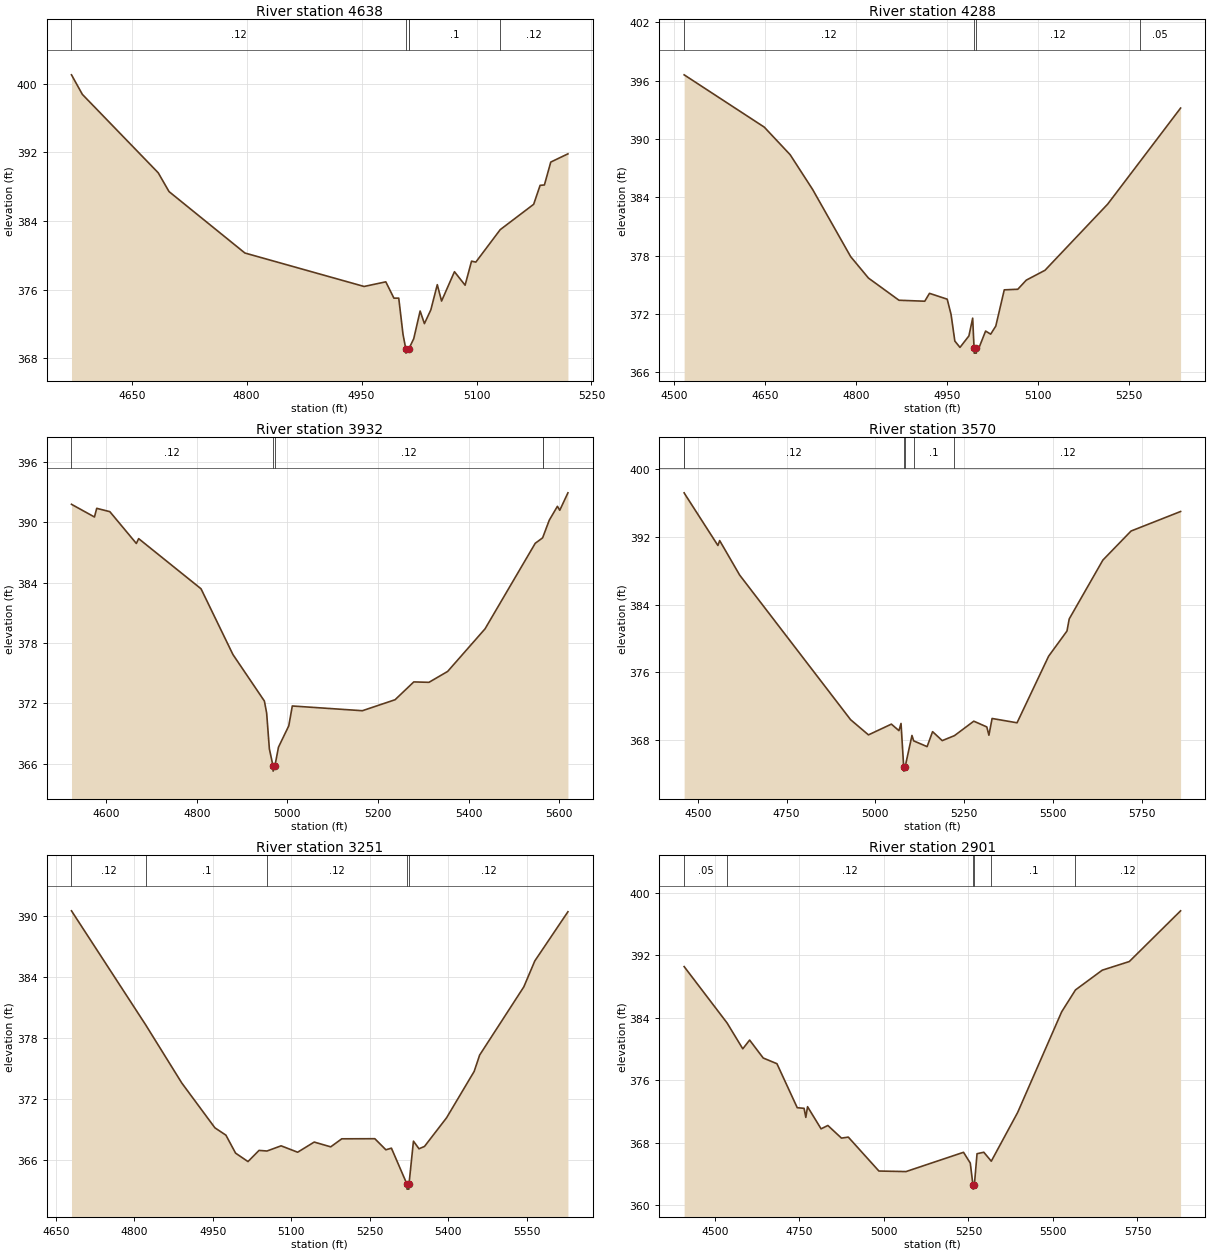
Type RM Length L Ch R = 1,4638,350,350,350
BEGIN DESCRIPTION:
Caney Creek T 10 10.0
END DESCRIPTION:
XS GIS Cut Line= 3
      2763375.98      6772710.98      2763676.00      6773011.00
      2763876.00      6773111.00
#Sta/Elev= 30
  4571.4  401.04  4585.6  398.76  4684.6  389.62  4698.7  387.43  4797.7  380.27
  4953.3  376.37  4981.6  376.91  4992.2  375.01  4998.5  375.01  5004.1  370.77
  5007.7  369.10  5007.9  368.60  5011.7  369.10  5012.0  369.16  5018.1  370.29
  5026.4  373.51  5032.0  372.04  5040.4  373.65  5048.8  376.58  5054.4  374.67
  5071.2  378.09  5085.1  376.52  5093.5  379.32  5099.1  379.21  5130.9  382.99
  5174.6  385.95  5183.0  388.16  5188.6  388.20  5196.9  390.87  5219.3  391.83
#Mann=5,-1,0
  4571.4    0.12       0  5007.7    0.07       0  5011.7    0.12       0
  5012.0     0.1       0  5130.9    0.12       0
Bank Sta=5007.7,5011.7
Exp/Cntr=0.3,0.1

Type RM Length L Ch R = 1,4288,356,356,356
BEGIN DESCRIPTION:
Caney Creek T 10 9.0
END DESCRIPTION:
XS GIS Cut Line= 3
      2763193.40      6772869.24      2763476.00      6773261.00
      2763776.03      6773411.02
#Sta/Elev= 30
  4516.1  396.59  4648.2  391.21  4690.9  388.37  4727.9  384.80  4790.6  377.89
  4820.0  375.68  4870.3  373.40  4912.8  373.30  4920.6  374.11  4949.8  373.51
  4956.2  371.93  4962.4  369.20  4970.9  368.55  4985.6  369.73  4991.8  371.56
  4994.1  368.46  4994.3  367.96  4997.8  367.96  4998.1  368.46  5001.9  368.46
  5013.1  370.23  5021.5  369.91  5029.9  370.74  5043.9  374.47  5066.2  374.53
  5080.2  375.47  5111.0  376.48  5214.4  383.29  5267.6  387.66  5334.6  393.17
#Mann=4,-1,0
  4516.1    0.12       0  4994.1    0.07       0  4998.1    0.12       0
  5267.6    0.05       0
Bank Sta=4994.1,4998.1
Exp/Cntr=0.3,0.1

Type RM Length L Ch R = 1,3932,362,362,362
BEGIN DESCRIPTION:
Caney Creek T 10 8.0
END DESCRIPTION:
XS GIS Cut Line= 3
      2763125.51      6772936.83      2763176.00      6773411.00
      2763775.99      6773561.00
#Sta/Elev= 30
  4523.6  391.77  4574.3  390.51  4579.3  391.37  4608.2  391.04  4666.7  387.88
  4671.8  388.36  4809.4  383.38  4879.8  376.85  4949.2  372.23  4954.2  371.03
  4960.2  367.48  4968.3  365.77  4968.5  365.27  4972.3  365.77  4980.3  367.65
  5003.0  369.77  5010.8  371.74  5165.4  371.27  5237.5  372.36  5278.8  374.13
  5312.3  374.09  5353.5  375.17  5436.0  379.40  5546.8  387.90  5562.8  388.43
  5563.4  388.48  5577.7  390.19  5595.7  391.57  5600.9  391.18  5618.9  392.91
#Mann=5,-1,0
  4523.6    0.12       0  4968.3    0.07       0  4972.3    0.12       0
  5562.8     0.1       0  5563.4    0.12       0
Bank Sta=4968.3,4972.3
Exp/Cntr=0.3,0.1

Type RM Length L Ch R = 1,3570,319,319,319
BEGIN DESCRIPTION:
Caney Creek T 10 7.0
END DESCRIPTION:
XS GIS Cut Line= 3
      2762440.79      6773543.60      2762976.00      6773611.00
      2763709.01      6774059.55
#Sta/Elev= 30
  4461.2  397.22  4461.4  397.19  4556.3  390.99  4561.3  391.57  4617.6  387.49
  4930.1  370.38  4980.5  368.58  5045.1  369.85  5066.4  369.08  5072.3  369.93
  5079.8  364.79  5080.1  364.29  5083.8  364.79  5103.1  368.51  5107.9  367.87
  5145.8  367.19  5161.2  368.96  5188.4  367.90  5222.9  368.49  5277.3  370.20
  5314.0  369.52  5319.9  368.54  5328.9  370.52  5399.2  370.01  5488.2  377.89
  5539.9  380.87  5546.2  382.30  5641.0  389.26  5720.4  392.70  5860.0  395.01
#Mann=6,-1,0
  4461.2    0.05       0  4461.4    0.12       0  5079.8    0.07       0
  5083.8    0.12       0  5107.9     0.1       0  5222.9    0.12       0
Bank Sta=5079.8,5083.8
Exp/Cntr=0.3,0.1

Type RM Length L Ch R = 1,3251,350,350,350
BEGIN DESCRIPTION:
Caney Creek T 10 6.0
END DESCRIPTION:
XS GIS Cut Line= 3
      2762576.00      6773761.00      2762876.00      6773861.00
      2763476.02      6774061.01
#Sta/Elev= 30
  4679.9  390.51  4821.7  379.29  4890.7  373.57  4954.0  369.16  4975.0  368.44
  4993.5  366.67  5017.2  365.84  5038.3  366.94  5053.5  366.88  5080.5  367.39
  5112.1  366.76  5143.7  367.76  5175.3  367.29  5196.4  368.08  5259.6  368.09
  5280.7  367.00  5291.3  367.16  5320.9  363.63  5321.1  363.13  5324.6  363.13
  5324.9  363.63  5333.4  367.85  5344.0  367.10  5354.5  367.33  5396.7  370.15
  5449.4  374.71  5459.9  376.32  5544.3  383.03  5565.3  385.58  5628.6  390.42
#Mann=5,-1,0
  4679.9    0.12       0  4821.7     0.1       0  5053.5    0.12       0
  5320.9    0.07       0  5324.9    0.12       0
Bank Sta=5320.9,5324.9
Exp/Cntr=0.3,0.1

Type RM Length L Ch R = 1,2901,372,372,372
BEGIN DESCRIPTION:
Caney Creek T 10 5.0
END DESCRIPTION:
XS GIS Cut Line= 3
      2762293.62      6774146.15      2762876.00      6774211.00
      2763757.55      6774181.96
#Sta/Elev= 30
  4409.5  390.56  4536.5  383.33  4582.9  380.02  4603.1  381.14  4643.3  378.84
  4683.9  378.11  4743.9  372.47  4764.1  372.39  4769.3  371.23  4774.4  372.60
  4814.4  369.76  4834.5  370.19  4874.7  368.57  4894.9  368.70  4985.4  364.35
  5065.5  364.28  5235.6  366.75  5255.6  365.37  5263.6  362.53  5263.9  362.03
  5267.6  362.53  5275.6  366.57  5295.6  366.76  5317.7  365.61  5395.7  371.86
  5525.8  384.76  5566.7  387.57  5645.8  390.10  5725.9  391.21  5877.5  397.71
#Mann=6,-1,0
  4409.5    0.05       0  4536.5    0.12       0  5263.6    0.07       0
  5267.6    0.12       0  5317.7     0.1       0  5566.7    0.12       0
Bank Sta=5263.6,5267.6
Exp/Cntr=0.3,0.1

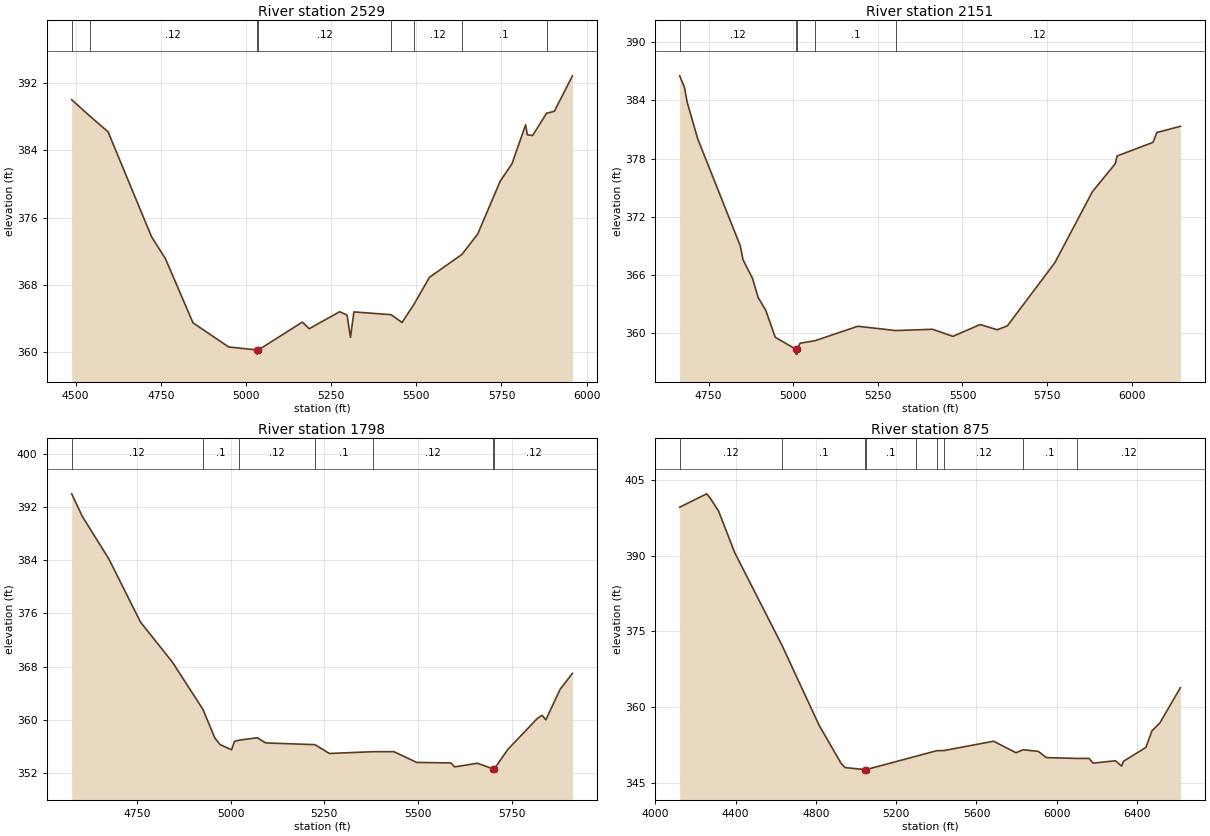
Type RM Length L Ch R = 1,2529,378,378,378
BEGIN DESCRIPTION:
Caney Creek T 10 4.0
END DESCRIPTION:
XS GIS Cut Line= 3
      2762304.52      6774302.28      2762776.00      6774511.00
      2763721.96      6774389.07
#Sta/Elev= 30
  4488.7  390.03  4541.3  388.11  4595.5  386.21  4722.8  373.75  4763.7  371.13
  4844.7  363.49  4949.6  360.62  5032.6  360.27  5032.8  359.77  5036.6  360.27
  5165.6  363.58  5185.8  362.79  5274.8  364.81  5296.7  364.43  5306.8  361.76
  5316.9  364.79  5426.2  364.46  5458.0  363.53  5492.4  365.64  5538.7  368.91
  5633.6  371.62  5679.9  374.03  5746.4  380.36  5780.7  382.40  5820.8  387.05
  5825.9  385.85  5841.2  385.77  5882.1  388.41  5905.3  388.66  5958.1  392.87
#Mann=8,-1,0
  4488.7    0.05       0  4541.3    0.12       0  5032.6    0.07       0
  5036.6    0.12       0  5426.2     0.1       0  5492.4    0.12       0
  5633.6     0.1       0  5882.1    0.12       0
Bank Sta=5032.6,5036.6
Exp/Cntr=0.3,0.1

Type RM Length L Ch R = 1,2151,353,353,353
BEGIN DESCRIPTION:
Caney Creek T 10 3.0
END DESCRIPTION:
XS GIS Cut Line= 3
      2762276.00      6774661.00      2762576.00      6774811.00
      2763715.14      6774709.13
#Sta/Elev= 30
  4664.6  386.54  4678.6  385.37  4687.0  383.80  4717.7  380.07  4843.5  369.04
  4851.9  367.58  4879.8  365.67  4896.6  363.69  4919.0  362.38  4946.9  359.61
  5008.1  358.37  5008.3  357.87  5011.8  357.87  5012.1  358.37  5020.1  358.99
  5065.1  359.26  5190.8  360.74  5302.6  360.30  5411.6  360.43  5471.9  359.70
  5552.2  360.92  5602.4  360.38  5632.5  360.78  5773.1  367.30  5883.5  374.59
  5951.6  377.50  5956.6  378.28  6062.9  379.69  6074.3  380.70  6143.7  381.34
#Mann=5,-1,0
  4664.6    0.12       0  5008.1    0.07       0  5012.1    0.12       0
  5065.1     0.1       0  5302.6    0.12       0
Bank Sta=5008.1,5012.1
Exp/Cntr=0.3,0.1

Type RM Length L Ch R = 1,1798,923,923,923
BEGIN DESCRIPTION:
Caney Creek T 10 2.0
END DESCRIPTION:
XS GIS Cut Line= 3
      2762125.98      6774810.98      2762426.00      6775111.00
      2763325.99      6775261.00
#Sta/Elev= 30
  4575.7  394.02  4604.0  390.63  4674.7  384.23  4759.6  374.68  4844.4  368.68
  4926.0  361.55  4957.6  357.26  4971.7  356.25  5002.5  355.45  5010.1  356.71
  5022.3  356.90  5071.0  357.27  5093.8  356.49  5225.1  356.23  5263.6  354.90
  5381.3  355.17  5435.9  355.17  5496.8  353.55  5588.0  353.48  5598.1  352.88
  5659.0  353.43  5700.0  352.59  5700.3  352.09  5704.0  352.59  5740.1  355.51
  5818.6  360.17  5831.3  360.66  5841.4  359.97  5879.5  364.56  5912.4  366.97
#Mann=7,-1,0
  4575.7    0.12       0  4926.0     0.1       0  5022.3    0.12       0
  5225.1     0.1       0  5381.3    0.12       0  5700.0    0.07       0
  5704.0    0.12       0
Bank Sta=5700,5704
Exp/Cntr=0.3,0.1

Type RM Length L Ch R = 1,875,0,0,0
BEGIN DESCRIPTION:
Caney Creek T 10 1.0
END DESCRIPTION:
XS GIS Cut Line= 3
      2761777.87      6774826.74      2761778.36      6775705.44
      2763375.97      6775461.00
#Sta/Elev= 30
  4121.3  399.59  4255.6  402.24  4275.6  401.27  4315.6  398.79  4395.6  390.60
  4632.5  372.14  4815.6  356.46  4925.6  348.88  4945.6  348.04  5046.2  347.64
  5046.4  347.14  5050.2  347.64  5296.6  350.26  5401.9  351.38  5439.4  351.42
  5685.5  353.26  5796.8  350.98  5832.6  351.57  5908.1  351.25  5948.5  350.02
  6100.9  349.85  6161.0  349.86  6181.2  348.92  6292.5  349.39  6323.3  348.34
  6333.0  349.30  6444.3  352.03  6474.6  355.31  6513.5  356.85  6616.2  363.86
#Mann=9,-1,0
  4121.3    0.12       0  4632.5     0.1       0  5046.2    0.07       0
  5050.2     0.1       0  5296.6    0.12       0  5401.9     0.1       0
  5439.4    0.12       0  5832.6     0.1       0  6100.9    0.12       0
Bank Sta=5046.2,5050.2
Exp/Cntr=0.3,0.1

Chan Stop Cuts=-1