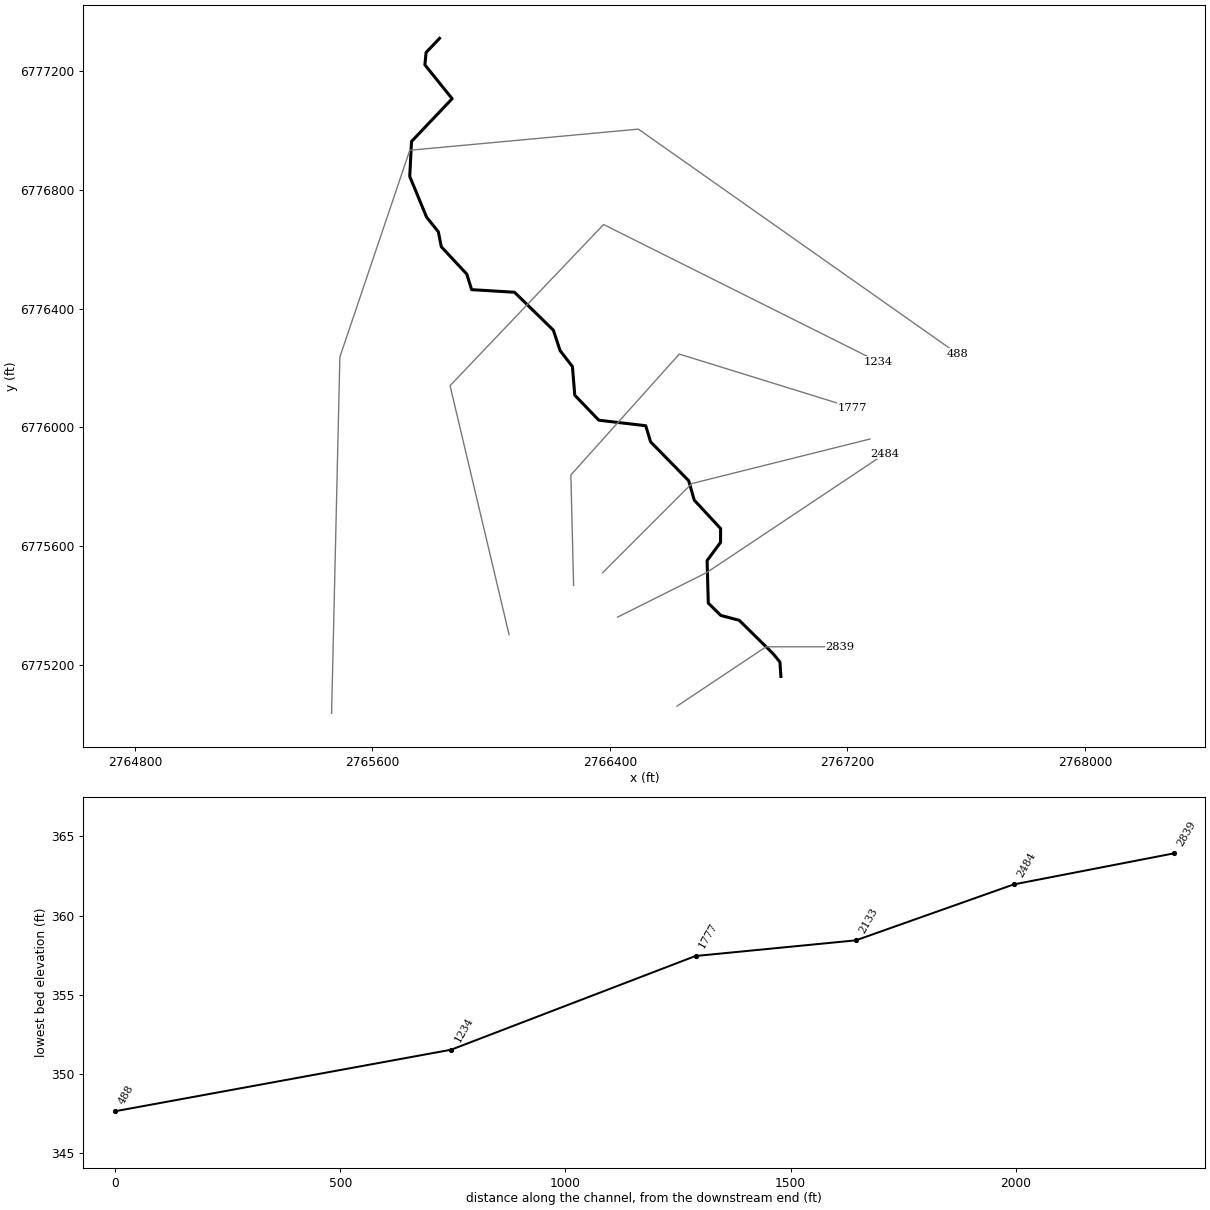
--- Caney Creek T 11.prj (project) ---

Proj Title=Caney Creek T 11 Base Level Engineering
Current Plan=p01
Default Exp/Contr=0.3,0.1
English Units
Geom File=g01
Flow File=f01
Plan File=p01
BEGIN DESCRIPTION:
Caney Creek T 11
END DESCRIPTION:

--- Caney Creek T 11.p01 (plan) ---

Plan Title=Multiple Run
Short Identifier=Multiple
Geom File=g01
Flow File=f01
Subcritical Flow
K Sum by GR= 0
Std Step Tol= 0.01
Critical Tol= 0.01
Num of Std Step Trials= 20
Max Error Tol= 0.3
Flow Tol Ratio= 0.001
Split Flow NTrial= 30
Split Flow Tol= 0.02
Split Flow Ratio= 0.02
Log Output Level= 0
Friction Slope Method= 1
Unsteady Friction Slope Method= 2
Unsteady Bridges Friction Slope Method= 1
Parabolic Critical Depth
Global Vel Dist=  1 , 1 , 1
Global Log Level= 0
CheckData=True
Encroach Param= -1, 0, 0, 0
BEGIN DESCRIPTION:
Multiple Run
END DESCRIPTION:

--- Caney Creek T 11.f01 (steady flow) ---

Flow Title=Multiple
Number of Profiles=7
Profile Names=10-year,25-year,50-year,1pct_min,100-year,1pct_plu,500-year
River Rch & RM= Caney Creek T 11,Reach-1,2839
     624     851    1039     632    1260    2514    1855
Boundary for River Rch & Prof#=Caney Creek T 11,Reach-1,1
Up Type=0
Dn Type=3
Dn Slope=0.005
Boundary for River Rch & Prof#=Caney Creek T 11,Reach-1,2
Up Type=0
Dn Type=3
Dn Slope=0.005
Boundary for River Rch & Prof#=Caney Creek T 11,Reach-1,3
Up Type=0
Dn Type=3
Dn Slope=0.005
Boundary for River Rch & Prof#=Caney Creek T 11,Reach-1,4
Up Type=0
Dn Type=3
Dn Slope=0.005
Boundary for River Rch & Prof#=Caney Creek T 11,Reach-1,5
Up Type=0
Dn Type=3
Dn Slope=0.005
Boundary for River Rch & Prof#=Caney Creek T 11,Reach-1,6
Up Type=0
Dn Type=3
Dn Slope=0.005
Boundary for River Rch & Prof#=Caney Creek T 11,Reach-1,7
Up Type=0
Dn Type=3
Dn Slope=0.005

--- Caney Creek T 11.g01 (geometry) ---

Geom Title=Existing Conditions

River Reach=Caney Creek T 11,Reach-1
Reach XY= 30
      2766976.00      6775161.00      2766972.73      6775209.64
      2766949.65      6775237.80      2766835.66      6775350.21
      2766773.42      6775366.74      2766731.35      6775408.30
      2766727.39      6775551.34      2766772.66      6775612.75
      2766772.86      6775659.36      2766684.18      6775754.96
      2766665.22      6775820.68      2766536.91      6775951.63
      2766520.56      6776005.81      2766362.66      6776024.36
      2766281.52      6776108.56      2766273.67      6776205.03
      2766232.14      6776258.83      2766209.36      6776327.68
      2766078.44      6776455.53      2765934.01      6776464.24
      2765917.68      6776516.69      2765831.85      6776608.71
      2765821.81      6776659.26      2765782.08      6776708.80
      2765725.52      6776845.84      2765731.45      6776963.45
      2765868.40      6777107.66      2765776.51      6777221.55
      2765780.57      6777263.35      2765826.00      6777311.00

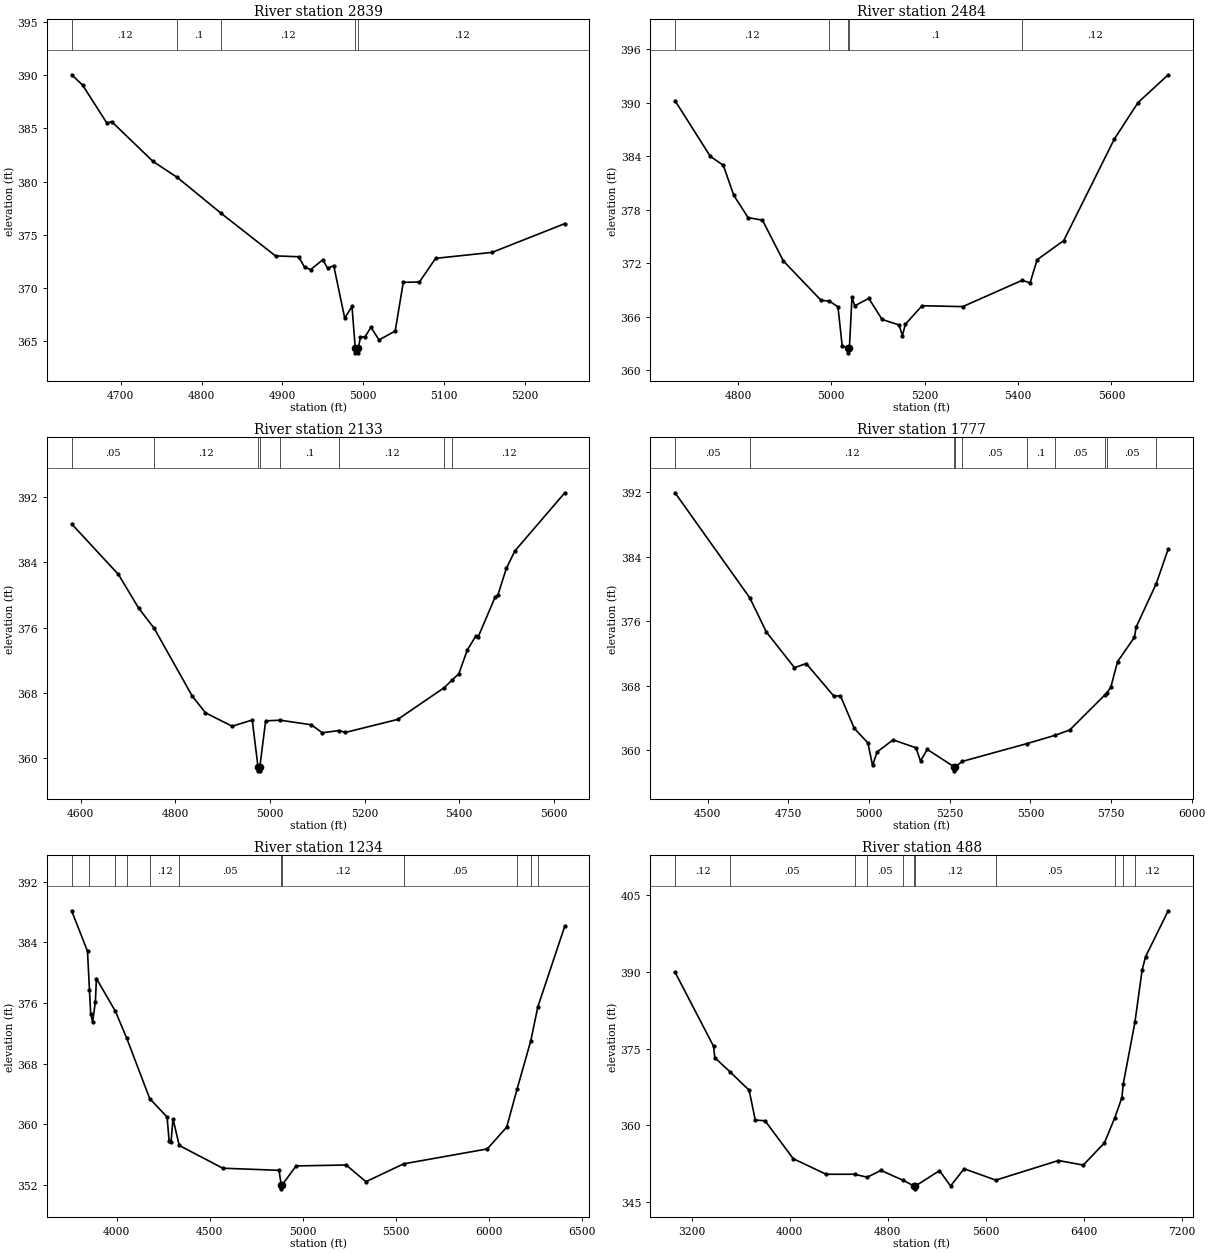
Type RM Length L Ch R = 1,2839,355,355,355
BEGIN DESCRIPTION:
Caney Creek T 11 4.0
END DESCRIPTION:
XS GIS Cut Line= 3
      2766625.96      6775060.97      2766926.00      6775261.00
      2767176.00      6775261.00
#Sta/Elev= 30
  4639.1  390.03  4652.7  389.06  4682.7  385.50  4688.7  385.63  4739.8  381.90
  4770.0  380.39  4824.1  377.03  4891.5  373.03  4920.1  372.95  4927.6  371.96
  4935.1  371.75  4950.1  372.67  4956.1  371.86  4963.6  372.12  4977.2  367.18
  4986.2  368.29  4990.2  364.43  4990.4  363.93  4993.9  363.93  4994.2  364.43
  4996.7  365.42  5002.2  365.42  5009.7  366.32  5019.7  365.14  5039.7  365.98
  5049.7  370.55  5069.7  370.58  5089.7  372.80  5159.7  373.36  5249.7  376.06
#Mann=5,-1,0
  4639.1    0.12       0  4770.0     0.1       0  4824.1    0.12       0
  4990.2    0.07       0  4994.2    0.12       0
Bank Sta=4990.2,4994.2
Exp/Cntr=0.3,0.1

Type RM Length L Ch R = 1,2484,351,351,351
BEGIN DESCRIPTION:
Caney Creek T 11 3.0
END DESCRIPTION:
XS GIS Cut Line= 3
      2766425.98      6775360.99      2766726.00      6775511.00
      2767325.96      6775910.97
#Sta/Elev= 30
  4665.1  390.23  4740.6  383.99  4768.5  382.99  4790.9  379.63  4821.6  377.12
  4852.4  376.84  4897.1  372.27  4978.2  367.84  4995.4  367.78  5014.1  367.13
  5023.1  362.79  5034.6  362.47  5034.8  361.97  5038.6  362.47  5044.1  368.18
  5050.1  367.24  5080.2  368.07  5108.7  365.71  5144.8  365.10  5152.3  363.90
  5158.3  365.16  5194.3  367.25  5281.5  367.15  5408.8  370.10  5425.7  369.80
  5440.7  372.40  5497.8  374.55  5606.0  385.91  5657.0  390.02  5721.6  393.13
#Mann=5,-1,0
  4665.1    0.12       0  4995.4     0.1       0  5034.6    0.07       0
  5038.6     0.1       0  5408.8    0.12       0
Bank Sta=5034.6,5038.6
Exp/Cntr=0.3,0.1

Type RM Length L Ch R = 1,2133,356,356,356
BEGIN DESCRIPTION:
Caney Creek T 11 2.0
END DESCRIPTION:
XS GIS Cut Line= 3
      2766375.98      6775510.98      2766676.00      6775811.00
      2767276.04      6775961.01
#Sta/Elev= 30
  4580.5  388.71  4679.5  382.51  4722.0  378.40  4755.1  375.90  4835.1  367.64
  4863.4  365.55  4919.9  363.90  4962.4  364.66  4974.5  358.93  4974.8  358.43
  4978.3  358.43  4978.5  358.93  4990.7  364.56  5021.2  364.64  5087.3  364.08
  5110.5  363.10  5146.0  363.37  5159.4  363.14  5270.2  364.74  5368.5  368.64
  5385.3  369.59  5399.1  370.32  5417.1  373.25  5435.1  374.96  5440.3  374.88
  5476.4  379.80  5481.5  379.94  5499.6  383.25  5517.6  385.39  5623.3  392.53
#Mann=8,-1,0
  4580.5    0.05       0  4755.1    0.12       0  4974.5    0.07       0
  4978.5    0.12       0  5021.2     0.1       0  5146.0    0.12       0
  5368.5    0.05       0  5385.3    0.12       0
Bank Sta=4974.5,4978.5
Exp/Cntr=0.3,0.1

Type RM Length L Ch R = 1,1777,543,543,543
BEGIN DESCRIPTION:
Mapping XS 617a20f2
END DESCRIPTION:
XS GIS Cut Line= 4
      2766277.55      6775467.71      2766268.40      6775839.86
      2766633.78      6776247.16      2767216.00      6776066.64
#Sta/Elev= 30
  4398.3  391.96  4630.2  378.91  4681.7  374.66  4768.6  370.25  4805.0  370.76
  4890.3  366.73  4911.2  366.74  4953.8  362.73  4996.4  360.89  5010.6  358.11
  5024.8  359.78  5074.2  361.29  5145.2  360.30  5159.4  358.66  5180.3  360.10
  5263.5  357.94  5263.8  357.44  5267.5  357.94  5288.8  358.61  5490.1  360.83
  5577.0  361.86  5622.0  362.51  5730.9  366.86  5737.0  367.13  5749.3  367.81
  5770.3  371.01  5822.6  374.02  5828.0  375.30  5890.1  380.67  5927.3  384.98
#Mann=10,-1,0
  4398.3    0.05       0  4630.2    0.12       0  5263.5    0.07       0
  5267.5    0.12       0  5288.8    0.05       0  5490.1     0.1       0
  5577.0    0.05       0  5730.9    0.12       0  5737.0    0.05       0
  5890.1    0.12       0
Bank Sta=5263.5,5267.5
Exp/Cntr=0.3,0.1

Type RM Length L Ch R = 1,1234,746,746,746
BEGIN DESCRIPTION:
Mapping XS 71af8f27
END DESCRIPTION:
XS GIS Cut Line= 4
      2766060.29      6775301.48      2765861.31      6776140.69
      2766378.59      6776683.72      2767305.13      6776220.57
#Sta/Elev= 30
  3758.8  388.15  3844.0  382.82  3854.4  377.76  3861.1  374.60  3871.4  373.48
  3886.3  376.16  3891.9  379.22  3994.2  374.89  4054.6  371.36  4178.2  363.39
  4271.4  360.97  4282.4  357.76  4292.7  357.73  4303.0  360.74  4336.5  357.23
  4570.2  354.23  4872.3  353.95  4884.4  352.01  4884.7  351.51  4888.4  352.01
  4964.4  354.53  5233.0  354.65  5339.4  352.45  5540.9  354.80  5990.6  356.77
  6095.0  359.64  6150.3  364.60  6224.5  371.04  6262.3  375.50  6407.1  386.14
#Mann=12,-1,0
  3758.8    0.12       0  3854.4    0.05       0  3994.2    0.12       0
  4054.6    0.05       0  4178.2    0.12       0  4336.5    0.05       0
  4884.4    0.07       0  4888.4    0.12       0  5540.9    0.05       0
  6150.3    0.12       0  6224.5    0.05       0  6262.3    0.12       0
Bank Sta=4884.4,4888.4
Exp/Cntr=0.3,0.1

Type RM Length L Ch R = 1,488,0,0,0
BEGIN DESCRIPTION:
Caney Creek T 11 1.0
END DESCRIPTION:
XS GIS Cut Line= 5
      2765462.18      6775036.63      2765490.13      6776237.44
      2765725.60      6776933.87      2766495.82      6777005.10
      2767570.17      6776248.72
#Sta/Elev= 30
  3063.7  389.92  3378.2  375.45  3388.2  373.22  3513.1  370.45  3668.2  366.87
  3718.3  361.05  3798.3  360.91  4028.3  353.50  4296.9  350.46  4528.4  350.47
  4631.8  349.89  4743.6  351.22  4926.3  349.27  5017.3  348.12  5017.6  347.62
  5021.3  348.12  5221.3  351.17  5311.7  348.18  5422.2  351.54  5680.6  349.32
  6192.2  353.15  6394.3  352.26  6566.8  356.58  6651.2  361.48  6709.6  365.42
  6720.8  368.12  6815.8  380.15  6874.4  390.34  6903.0  392.97  7087.4  401.91
#Mann=11,-1,0
  3063.7    0.12       0  3513.1    0.05       0  4528.4    0.12       0
  4631.8    0.05       0  4926.3    0.12       0  5017.3    0.07       0
  5021.3    0.12       0  5680.6    0.05       0  6651.2    0.12       0
  6720.8    0.05       0  6815.8    0.12       0
Bank Sta=5017.3,5021.3
Exp/Cntr=0.3,0.1

Chan Stop Cuts=-1