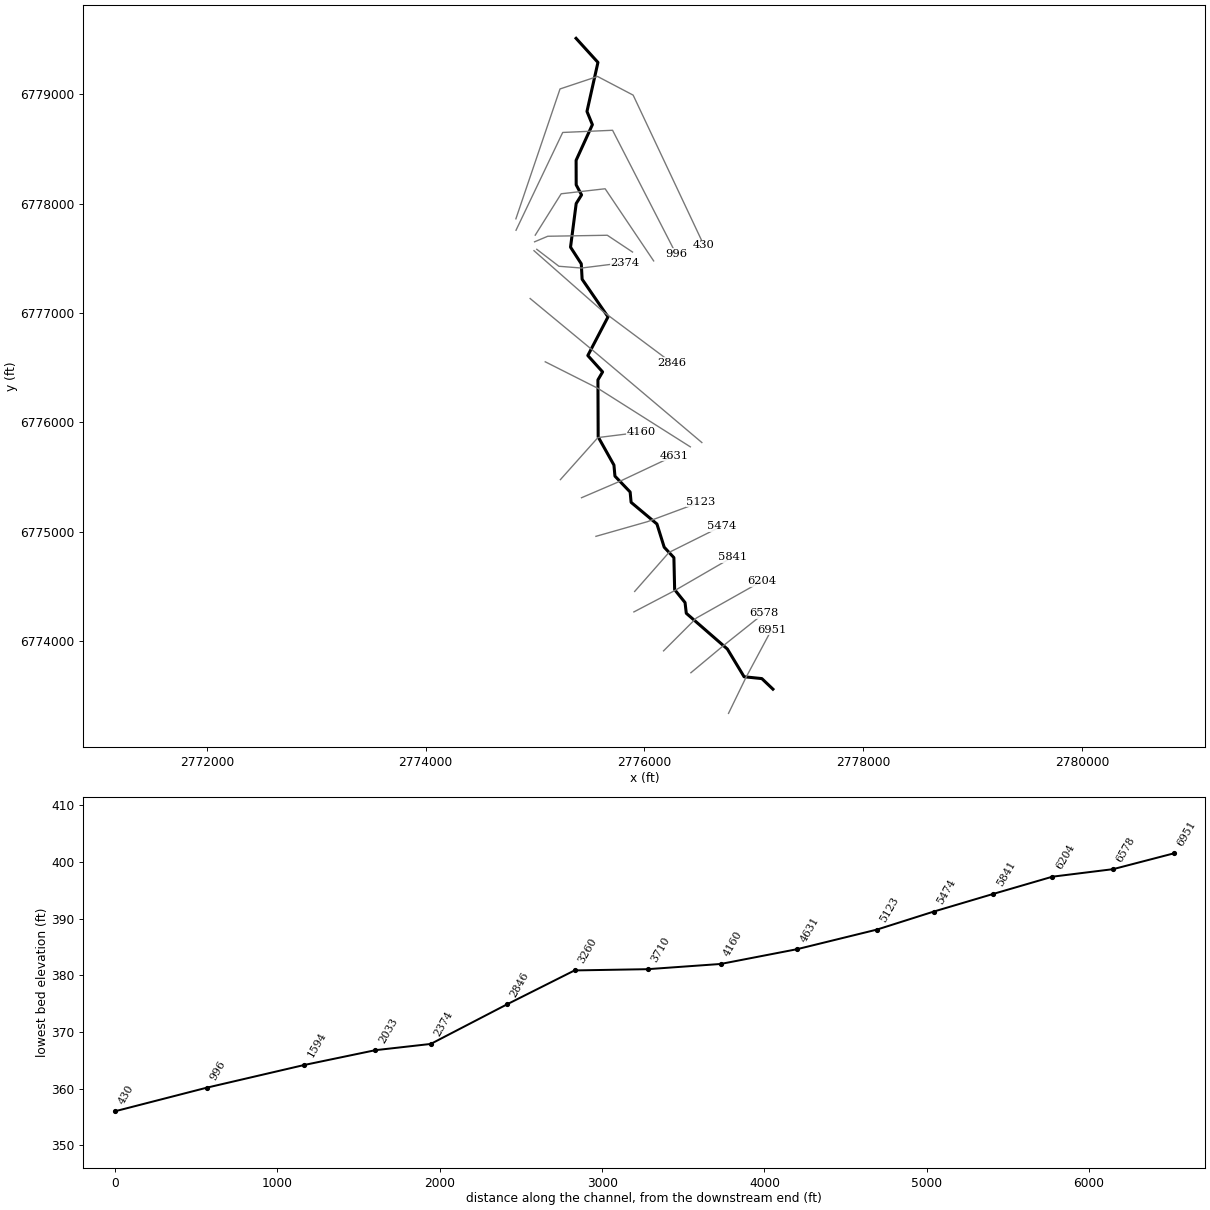
--- Caney Creek T 12.prj (project) ---

Proj Title=Caney Creek T 12 Base Level Engineering
Current Plan=p01
Default Exp/Contr=0.3,0.1
English Units
Geom File=g01
Flow File=f01
Plan File=p01
BEGIN DESCRIPTION:
Caney Creek T 12
END DESCRIPTION:

--- Caney Creek T 12.p01 (plan) ---

Plan Title=Multiple Run
Short Identifier=Multiple
Geom File=g01
Flow File=f01
Subcritical Flow
K Sum by GR= 0
Std Step Tol= 0.01
Critical Tol= 0.01
Num of Std Step Trials= 20
Max Error Tol= 0.3
Flow Tol Ratio= 0.001
Split Flow NTrial= 30
Split Flow Tol= 0.02
Split Flow Ratio= 0.02
Log Output Level= 0
Friction Slope Method= 1
Unsteady Friction Slope Method= 2
Unsteady Bridges Friction Slope Method= 1
Parabolic Critical Depth
Global Vel Dist=  1 , 1 , 1
Global Log Level= 0
CheckData=True
Encroach Param= -1, 0, 0, 0
BEGIN DESCRIPTION:
Multiple Run
END DESCRIPTION:

--- Caney Creek T 12.f01 (steady flow) ---

Flow Title=Multiple
Number of Profiles=7
Profile Names=10-year,25-year,50-year,1pct_min,100-year,1pct_plu,500-year
River Rch & RM= Caney Creek T 12,Reach-1,6951
     661     905    1107     674    1345    2684    1989
River Rch & RM= Caney Creek T 12,Reach-1,5123
     746    1023    1253     763    1522    3037    2252
Boundary for River Rch & Prof#=Caney Creek T 12,Reach-1,1
Up Type=0
Dn Type=3
Dn Slope=0.005
Boundary for River Rch & Prof#=Caney Creek T 12,Reach-1,2
Up Type=0
Dn Type=3
Dn Slope=0.005
Boundary for River Rch & Prof#=Caney Creek T 12,Reach-1,3
Up Type=0
Dn Type=3
Dn Slope=0.005
Boundary for River Rch & Prof#=Caney Creek T 12,Reach-1,4
Up Type=0
Dn Type=3
Dn Slope=0.005
Boundary for River Rch & Prof#=Caney Creek T 12,Reach-1,5
Up Type=0
Dn Type=3
Dn Slope=0.005
Boundary for River Rch & Prof#=Caney Creek T 12,Reach-1,6
Up Type=0
Dn Type=3
Dn Slope=0.005
Boundary for River Rch & Prof#=Caney Creek T 12,Reach-1,7
Up Type=0
Dn Type=3
Dn Slope=0.005

--- Caney Creek T 12.g01 (geometry) ---

Geom Title=Existing Conditions

River Reach=Caney Creek T 12,Reach-1
Reach XY= 30
      2777176.00      6773561.00      2777074.55      6773657.51
      2776912.33      6773674.23      2776759.36      6773927.71
      2776383.76      6774254.59      2776372.50      6774352.52
      2776277.35      6774470.64      2776270.53      6774763.45
      2776181.85      6774858.71      2776115.48      6775070.79
      2775879.33      6775269.05      2775870.45      6775363.37
      2775731.52      6775508.57      2775722.37      6775609.50
      2775578.26      6775866.94      2775576.01      6776388.36
      2775618.74      6776461.30      2775483.52      6776610.96
      2775668.22      6776964.40      2775431.48      6777308.56
      2775423.84      6777449.73      2775325.54      6777601.72
      2775377.24      6778000.50      2775426.18      6778079.43
      2775377.24      6778171.50      2775376.52      6778395.78
      2775525.25      6778721.69      2775475.83      6778842.57
      2775576.06      6779291.01      2775376.00      6779511.00

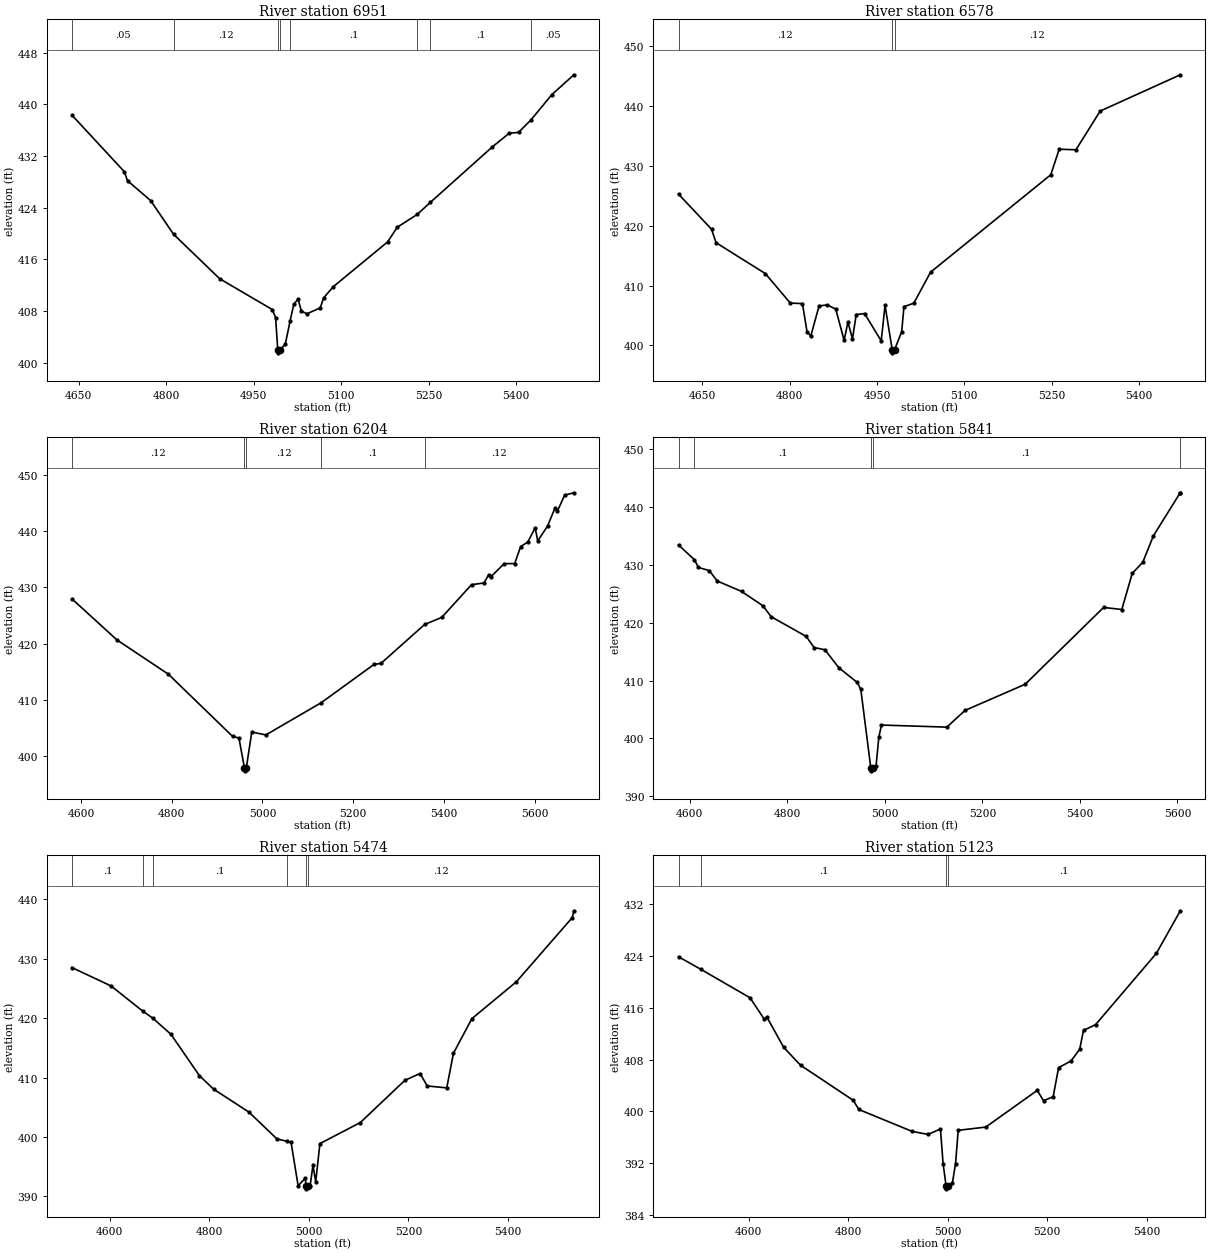
Type RM Length L Ch R = 1,6951,373,373,373
BEGIN DESCRIPTION:
Caney Creek T 12 13.0
END DESCRIPTION:
XS GIS Cut Line= 3
      2776769.96      6773339.49      2776926.00      6773661.00
      2777163.15      6774104.39
#Sta/Elev= 30
  4638.9  438.33  4728.4  429.60  4734.0  428.19  4773.5  425.13  4812.9  419.90
  4891.9  413.02  4982.2  408.24  4987.8  406.99  4991.5  402.04  4991.7  401.54
  4995.5  402.04  5004.4  402.87  5012.8  406.54  5019.0  409.06  5026.3  409.86
  5032.0  408.00  5041.6  407.59  5064.3  408.50  5070.2  410.05  5086.5  411.77
  5179.9  418.72  5196.2  420.98  5230.8  422.99  5253.2  424.85  5359.2  433.42
  5388.0  435.53  5404.3  435.69  5425.5  437.60  5461.2  441.51  5499.1  444.60
#Mann=8,-1,0
  4638.9    0.05       0  4812.9    0.12       0  4991.5    0.07       0
  4995.5    0.12       0  5012.8     0.1       0  5230.8    0.12       0
  5253.2     0.1       0  5425.5    0.05       0
Bank Sta=4991.5,4995.5
Exp/Cntr=0.3,0.1

Type RM Length L Ch R = 1,6578,374,374,374
BEGIN DESCRIPTION:
Caney Creek T 12 12.0
END DESCRIPTION:
XS GIS Cut Line= 3
      2776425.97      6773710.98      2776726.00      6773961.00
      2777094.61      6774255.08
#Sta/Elev= 30
  4609.0  425.26  4665.7  419.40  4673.5  417.15  4758.1  412.00  4801.0  407.07
  4821.9  406.98  4829.7  402.32  4836.2  401.55  4850.5  406.61  4864.8  406.75
  4879.1  406.06  4893.5  400.84  4900.0  403.90  4907.8  401.11  4914.3  405.15
  4928.6  405.32  4957.2  400.76  4963.8  406.68  4976.1  399.26  4976.3  398.76
  4980.1  399.26  4992.4  402.30  4996.3  406.47  5013.2  407.05  5042.0  412.23
  5248.5  428.49  5263.0  432.76  5291.8  432.67  5333.4  439.13  5471.1  445.19
#Mann=3,-1,0
  4609.0    0.12       0  4976.1    0.07       0  4980.1    0.12       0
Bank Sta=4976.1,4980.1
Exp/Cntr=0.3,0.1

Type RM Length L Ch R = 1,6204,363,363,363
BEGIN DESCRIPTION:
Caney Creek T 12 11.0
END DESCRIPTION:
XS GIS Cut Line= 3
      2776175.99      6773910.99      2776476.00      6774211.00
      2777069.71      6774545.42
#Sta/Elev= 30
  4580.4  427.95  4679.4  420.67  4792.5  414.60  4934.0  403.56  4948.1  403.25
  4960.3  397.93  4960.5  397.43  4964.3  397.93  4976.4  404.32  5007.5  403.81
  5129.2  409.52  5245.7  416.33  5261.1  416.51  5357.2  423.42  5394.9  424.67
  5460.6  430.49  5488.0  430.79  5498.2  432.22  5503.9  431.94  5532.6  434.23
  5555.6  434.23  5568.9  437.26  5584.8  438.08  5600.8  440.61  5606.5  438.26
  5628.2  440.91  5644.1  444.03  5649.8  443.55  5665.8  446.39  5686.1  446.81
#Mann=5,-1,0
  4580.4    0.12       0  4960.3    0.07       0  4964.3    0.12       0
  5129.2     0.1       0  5357.2    0.12       0
Bank Sta=4960.3,4964.3
Exp/Cntr=0.3,0.1

Type RM Length L Ch R = 1,5841,367,367,367
BEGIN DESCRIPTION:
Caney Creek T 12 10.0
END DESCRIPTION:
XS GIS Cut Line= 3
      2775904.82      6774267.06      2776276.00      6774461.00
      2776803.86      6774766.73
#Sta/Elev= 30
  4577.1  433.46  4609.6  430.92  4618.0  429.57  4640.0  429.04  4656.5  427.23
  4706.3  425.43  4750.4  422.93  4766.9  421.06  4838.8  417.65  4855.2  415.72
  4877.3  415.34  4905.6  412.24  4943.5  409.69  4950.8  408.49  4971.3  394.90
  4971.6  394.40  4975.3  394.90  4982.0  395.17  4987.7  400.19  4993.1  402.32
  5127.2  401.96  5164.5  404.85  5287.9  409.38  5448.6  422.66  5485.9  422.30
  5507.4  428.56  5528.9  430.47  5550.6  435.03  5604.8  442.38  5605.9  442.49
#Mann=5,-1,0
  4577.1    0.12       0  4609.6     0.1       0  4971.3    0.07       0
  4975.3     0.1       0  5604.8    0.12       0
Bank Sta=4971.3,4975.3
Exp/Cntr=0.3,0.1

Type RM Length L Ch R = 1,5474,351,351,351
BEGIN DESCRIPTION:
Caney Creek T 12 9.0
END DESCRIPTION:
XS GIS Cut Line= 3
      2775911.95      6774454.30      2776226.00      6774811.00
      2776702.45      6775048.24
#Sta/Elev= 30
  4524.7  428.51  4602.9  425.43  4666.9  421.17  4687.2  419.98  4723.4  417.27
  4780.3  410.34  4808.8  408.06  4879.9  404.19  4935.9  399.69  4956.4  399.27
  4964.4  399.11  4978.6  391.79  4992.8  393.06  4994.6  391.78  4994.9  391.28
  4998.6  391.78  5002.7  391.78  5008.4  395.27  5013.9  392.46  5022.3  398.89
  5103.5  402.44  5193.0  409.55  5223.4  410.69  5237.8  408.60  5277.0  408.27
  5290.4  414.10  5327.4  419.92  5416.9  426.14  5528.9  436.92  5532.2  438.08
#Mann=6,-1,0
  4524.7     0.1       0  4666.9    0.12       0  4687.2     0.1       0
  4956.4    0.12       0  4994.6    0.07       0  4998.6    0.12       0
Bank Sta=4994.6,4998.6
Exp/Cntr=0.3,0.1

Type RM Length L Ch R = 1,5123,492,492,492
BEGIN DESCRIPTION:
Caney Creek T 12 8.0
END DESCRIPTION:
XS GIS Cut Line= 3
      2775557.87      6774958.11      2776027.72      6775091.77
      2776515.80      6775272.89
#Sta/Elev= 30
  4458.7  423.83  4503.2  421.91  4602.4  417.52  4631.0  414.23  4636.2  414.56
  4670.1  409.89  4704.0  407.13  4810.2  401.71  4821.2  400.31  4928.0  396.95
  4960.4  396.47  4985.4  397.31  4990.7  391.97  4996.7  388.59  4996.9  388.09
  5000.7  388.59  5009.4  388.99  5015.8  391.98  5021.1  397.10  5076.5  397.60
  5180.0  403.25  5192.7  401.67  5212.0  402.26  5223.0  406.75  5248.1  407.79
  5265.4  409.59  5273.1  412.49  5297.4  413.38  5419.6  424.35  5467.8  430.91
#Mann=4,-1,0
  4458.7    0.12       0  4503.2     0.1       0  4996.7    0.07       0
  5000.7     0.1       0
Bank Sta=4996.7,5000.7
Exp/Cntr=0.3,0.1

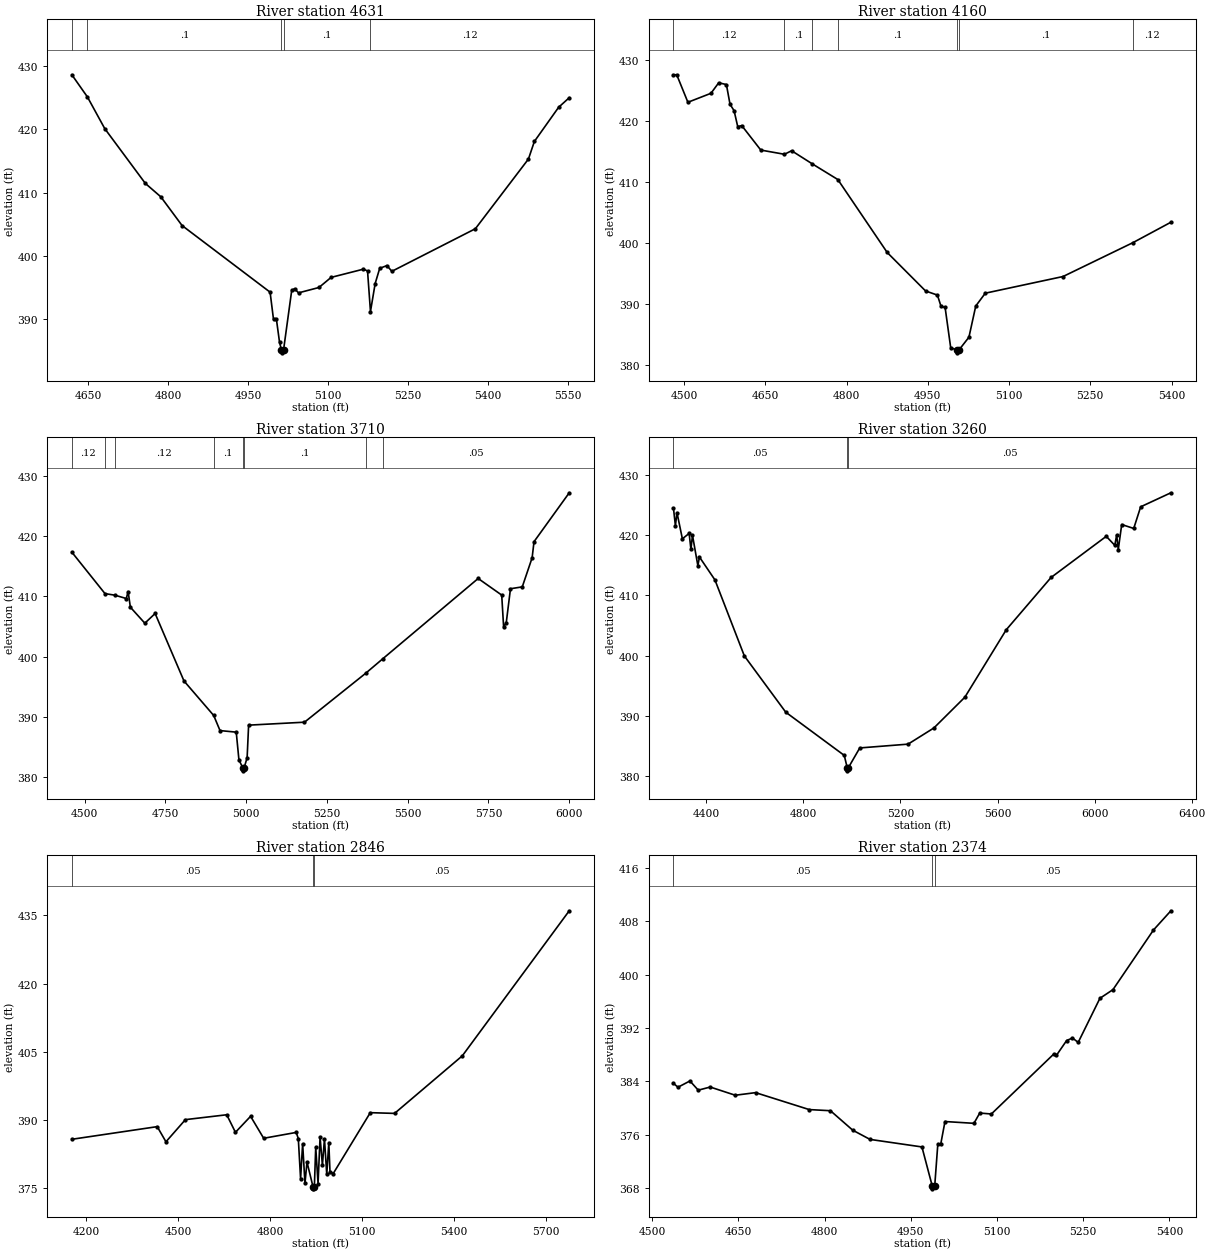
Type RM Length L Ch R = 1,4631,471,471,471
BEGIN DESCRIPTION:
Caney Creek T 12 7.0
END DESCRIPTION:
XS GIS Cut Line= 3
      2775425.99      6775311.00      2775776.00      6775461.00
      2776275.17      6775696.21
#Sta/Elev= 30
  4619.5  428.63  4648.7  425.12  4681.2  420.11  4757.3  411.44  4786.3  409.32
  4826.2  404.77  4991.2  394.23  4997.6  389.91  5003.1  389.91  5008.9  386.30
  5012.4  385.13  5012.7  384.63  5016.5  385.13  5031.7  394.50  5037.2  394.77
  5044.5  394.12  5082.8  394.97  5105.6  396.57  5166.1  397.87  5173.9  397.59
  5179.4  391.17  5188.2  395.60  5196.7  398.00  5210.3  398.44  5219.5  397.53
  5376.1  404.27  5475.6  415.30  5486.7  418.08  5532.3  423.50  5552.1  425.00
#Mann=5,-1,0
  4619.5    0.12       0  4648.7     0.1       0  5012.4    0.07       0
  5016.5     0.1       0  5179.4    0.12       0
Bank Sta=5012.4,5016.5
Exp/Cntr=0.3,0.1

Type RM Length L Ch R = 1,4160,450,450,450
BEGIN DESCRIPTION:
Caney Creek T 12 6.0
END DESCRIPTION:
XS GIS Cut Line= 3
      2775232.92      6775476.55      2775576.00      6775861.00
      2775976.02      6775911.00
#Sta/Elev= 30
  4480.4  427.52  4486.4  427.52  4507.0  423.02  4549.6  424.49  4563.9  426.21
  4578.1  425.92  4584.8  422.69  4592.3  421.64  4599.0  419.04  4606.5  419.20
  4641.6  415.20  4685.3  414.51  4698.5  415.09  4736.9  412.93  4783.8  410.38
  4875.0  398.44  4945.9  392.14  4967.7  391.47  4974.4  389.62  4981.9  389.45
  4992.3  382.82  5003.7  382.52  5004.0  382.02  5007.8  382.52  5025.9  384.58
  5038.5  389.68  5056.1  391.78  5199.7  394.51  5328.7  400.05  5398.8  403.39
#Mann=7,-1,0
  4480.4    0.12       0  4685.3     0.1       0  4736.9    0.12       0
  4783.8     0.1       0  5003.7    0.07       0  5007.8     0.1       0
  5328.7    0.12       0
Bank Sta=5003.7,5007.8
Exp/Cntr=0.3,0.1

Type RM Length L Ch R = 1,3710,450,450,450
BEGIN DESCRIPTION:
Caney Creek T 12 5.0
END DESCRIPTION:
XS GIS Cut Line= 3
      2775094.30      6776553.73      2775576.00      6776311.00
      2776420.77      6775776.24
#Sta/Elev= 30
  4460.7  417.33  4563.3  410.46  4594.2  410.20  4629.2  409.65  4634.8  410.81
  4641.8  408.21  4686.6  405.56  4718.4  407.17  4807.7  395.99  4899.7  390.27
  4919.2  387.77  4969.4  387.51  4977.7  382.93  4989.6  381.60  4989.9  381.10
  4993.8  381.60  5003.1  383.28  5007.7  388.67  5180.6  389.16  5369.6  397.25
  5422.7  399.66  5718.0  412.97  5790.9  410.22  5796.8  404.94  5804.9  405.62
  5818.0  411.27  5854.5  411.58  5885.0  416.40  5890.9  419.07  5999.9  427.17
#Mann=8,-1,0
  4460.7    0.12       0  4563.3     0.1       0  4594.2    0.12       0
  4899.7     0.1       0  4989.6    0.07       0  4993.8     0.1       0
  5369.6    0.12       0  5422.7    0.05       0
Bank Sta=4989.6,4993.8
Exp/Cntr=0.3,0.1

Type RM Length L Ch R = 1,3260,414,414,414
BEGIN DESCRIPTION:
Caney Creek T 12 4.0
END DESCRIPTION:
XS GIS Cut Line= 3
      2774956.27      6777132.20      2775526.00      6776661.00
      2776526.14      6775815.62
#Sta/Elev= 30
  4265.3  424.45  4273.2  421.56  4279.7  423.73  4301.9  419.39  4329.8  420.29
  4337.1  417.65  4343.5  419.98  4365.7  414.93  4372.2  416.37  4436.0  412.57
  4557.2  399.95  4727.8  390.61  4968.8  383.44  4981.0  381.38  4981.3  380.88
  4985.3  381.38  5032.6  384.68  5231.5  385.31  5338.1  388.00  5465.5  393.10
  5635.9  404.29  5820.5  412.97  6047.9  419.80  6083.1  418.31  6090.8  420.02
  6097.4  417.60  6111.6  421.76  6161.1  421.11  6189.7  424.70  6314.2  427.03
#Mann=3,-1,0
  4265.3    0.05       0  4981.0    0.05       0  4985.3    0.05       0
Bank Sta=4981,4985.3
Exp/Cntr=0.3,0.1

Type RM Length L Ch R = 1,2846,472,472,472
BEGIN DESCRIPTION:
Caney Creek T 12 3.0
END DESCRIPTION:
XS GIS Cut Line= 3
      2774991.38      6777569.53      2775626.00      6777011.00
      2776248.93      6776546.07
#Sta/Elev= 30
  4153.5  385.81  4432.0  388.59  4460.5  385.26  4524.0  390.13  4658.8  391.20
  4687.2  387.34  4736.6  390.86  4779.3  386.03  4885.5  387.32  4892.3  385.95
  4899.7  377.14  4906.4  384.84  4914.0  376.14  4920.6  380.81  4940.1  375.42
  4940.6  374.92  4944.7  375.42  4949.1  384.07  4956.7  376.07  4963.3  386.31
  4970.9  380.10  4977.6  385.90  4985.1  378.09  4991.8  385.09  4995.6  378.69
  5006.2  378.28  5127.1  391.66  5206.3  391.50  5427.3  404.15  5776.2  436.03
#Mann=3,-1,0
  4153.5    0.05       0  4940.1    0.03       0  4944.7    0.05       0
Bank Sta=4940.1,4944.7
Exp/Cntr=0.3,0.1

Type RM Length L Ch R = 1,2374,341,341,341
BEGIN DESCRIPTION:
Caney Creek T 12 2.0
END DESCRIPTION:
XS GIS Cut Line= 4
      2775016.85      6777582.26      2775219.40      6777427.12
      2775426.00      6777411.00      2775826.02      6777461.00
#Sta/Elev= 30
  4537.2  383.71  4545.0  383.13  4565.8  384.07  4580.3  382.69  4601.1  383.16
  4644.7  381.93  4680.0  382.32  4773.4  379.78  4810.3  379.61  4849.1  376.69
  4879.2  375.31  4969.5  374.18  4987.2  368.40  4987.7  367.90  4991.8  368.40
  4997.1  374.55  5002.1  374.55  5009.6  377.99  5060.0  377.72  5070.1  379.26
  5090.3  379.12  5198.6  388.08  5203.6  387.92  5221.3  390.13  5231.4  390.51
  5241.4  389.85  5279.2  396.46  5301.9  397.76  5372.4  406.70  5402.7  409.58
#Mann=3,-1,0
  4537.2    0.05       0  4987.2    0.03       0  4991.8    0.05       0
Bank Sta=4987.2,4991.8
Exp/Cntr=0.3,0.1

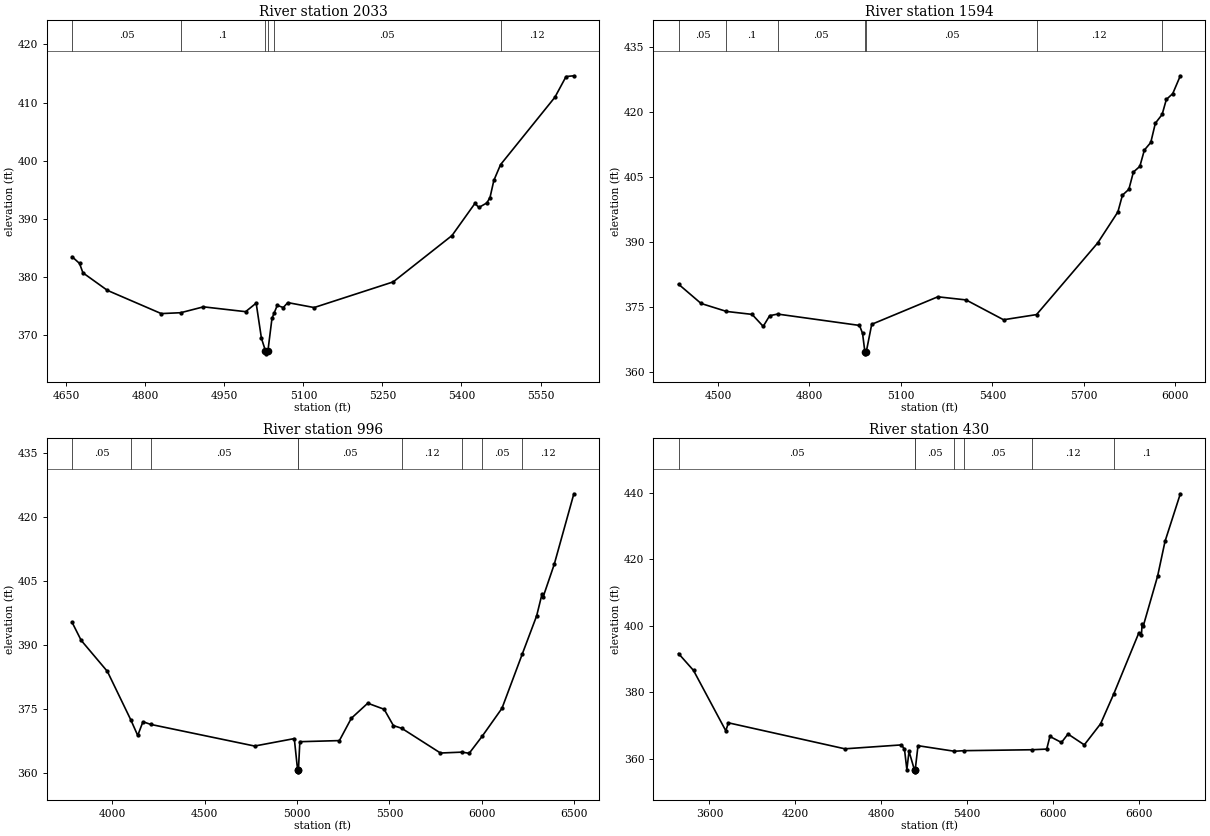
Type RM Length L Ch R = 1,2033,439,439,439
BEGIN DESCRIPTION:
Mapping XS e69ac7d6
END DESCRIPTION:
XS GIS Cut Line= 4
      2774996.99      6777650.87      2775117.21      6777701.49
      2775661.63      6777710.69      2775892.35      6777557.12
#Sta/Elev= 30
  4661.1  383.50  4675.3  382.34  4681.7  380.73  4728.2  377.71  4830.3  373.72
  4867.2  373.87  4910.4  374.88  4990.4  374.05  5010.4  375.52  5020.4  369.48
  5028.1  367.30  5028.5  366.80  5032.7  367.30  5040.4  372.89  5044.6  373.83
  5050.4  375.13  5061.9  374.76  5070.4  375.61  5120.4  374.76  5270.4  379.17
  5382.0  387.14  5425.4  392.65  5433.1  391.97  5448.1  392.75  5454.1  393.68
  5461.4  396.62  5474.1  399.33  5577.3  410.93  5598.4  414.48  5613.2  414.61
#Mann=6,-1,0
  4661.1    0.05       0  4867.2     0.1       0  5028.1    0.07       0
  5032.7     0.1       0  5044.6    0.05       0  5474.1    0.12       0
Bank Sta=5028.1,5032.7
Exp/Cntr=0.3,0.1

Type RM Length L Ch R = 1,1594,598,598,598
BEGIN DESCRIPTION:
Mapping XS c5603737
END DESCRIPTION:
XS GIS Cut Line= 4
      2775002.88      6777711.65      2775240.05      6778089.88
      2775641.89      6778135.73      2776085.41      6777476.17
#Sta/Elev= 30
  4370.5  380.26  4444.4  375.81  4527.8  373.97  4611.7  373.29  4648.2  370.52
  4669.4  372.99  4695.7  373.36  4964.0  370.74  4973.9  368.93  4981.6  364.68
  4982.1  364.18  4986.3  364.68  5004.1  371.00  5220.9  377.35  5313.4  376.63
  5436.4  372.05  5544.6  373.24  5745.4  389.80  5811.4  396.94  5826.3  400.81
  5847.4  402.17  5862.3  406.15  5883.4  407.46  5898.3  411.23  5919.3  412.98
  5934.3  417.43  5956.5  419.44  5970.3  422.91  5991.3  424.26  6016.2  428.38
#Mann=7,-1,0
  4370.5    0.05       0  4527.8     0.1       0  4695.7    0.05       0
  4981.6    0.05       0  4986.3    0.05       0  5544.6    0.12       0
  5956.5    0.05       0
Bank Sta=4981.6,4986.3
Exp/Cntr=0.3,0.1

Type RM Length L Ch R = 1,996,566,566,566
BEGIN DESCRIPTION:
Mapping XS ebd739a1
END DESCRIPTION:
XS GIS Cut Line= 4
      2774827.23      6777756.61      2775253.99      6778650.46
      2775709.81      6778670.45      2776289.87      6777541.84
#Sta/Elev= 30
  3782.5  395.32  3831.7  391.08  3973.6  383.78  4100.9  372.35  4137.9  368.73
  4166.1  371.96  4208.5  371.33  4770.5  366.25  4985.2  368.00  5002.9  360.69
  5003.4  360.19  5007.6  360.69  5015.2  367.27  5229.3  367.53  5294.0  372.78
  5382.7  376.31  5471.4  374.89  5521.4  371.06  5567.0  370.41  5776.3  364.61
  5893.4  364.82  5931.6  364.54  6002.2  368.56  6109.1  375.11  6219.8  387.96
  6296.8  396.83  6325.3  401.86  6330.9  401.15  6391.8  408.91  6498.2  425.51
#Mann=9,-1,0
  3782.5    0.05       0  4100.9     0.1       0  4208.5    0.05       0
  5002.9    0.05       0  5007.6    0.05       0  5567.0    0.12       0
  5893.4     0.1       0  6002.2    0.05       0  6219.8    0.12       0
Bank Sta=5002.9,5007.6
Exp/Cntr=0.3,0.1

Type RM Length L Ch R = 1,430,0,0,0
BEGIN DESCRIPTION:
Caney Creek T 12 1.0
END DESCRIPTION:
XS GIS Cut Line= 5
      2774825.99      6777860.96      2775229.39      6779048.18
      2775572.23      6779162.57      2775898.00      6778991.78
      2776545.61      6777617.44
#Sta/Elev= 30
  3384.7  391.62  3489.3  386.54  3714.3  368.40  3733.3  370.77  4545.8  362.95
  4940.7  364.13  4961.8  362.81  4978.4  356.69  4993.4  362.21  5031.7  356.52
  5032.2  356.02  5036.4  356.52  5056.1  363.89  5309.5  362.22  5377.3  362.39
  5852.6  362.67  5954.6  362.87  5976.7  366.67  6057.4  364.86  6103.0  367.40
  6216.9  364.14  6330.4  370.47  6423.0  379.53  6598.0  397.90  6615.3  397.07
  6620.8  400.64  6628.9  400.00  6728.4  414.91  6780.3  425.40  6887.1  439.72
#Mann=7,-1,0
  3384.7    0.05       0  5031.7    0.05       0  5036.4    0.05       0
  5309.5    0.12       0  5377.3    0.05       0  5852.6    0.12       0
  6423.0     0.1       0
Bank Sta=5031.7,5036.4
Exp/Cntr=0.3,0.1

Chan Stop Cuts=-1