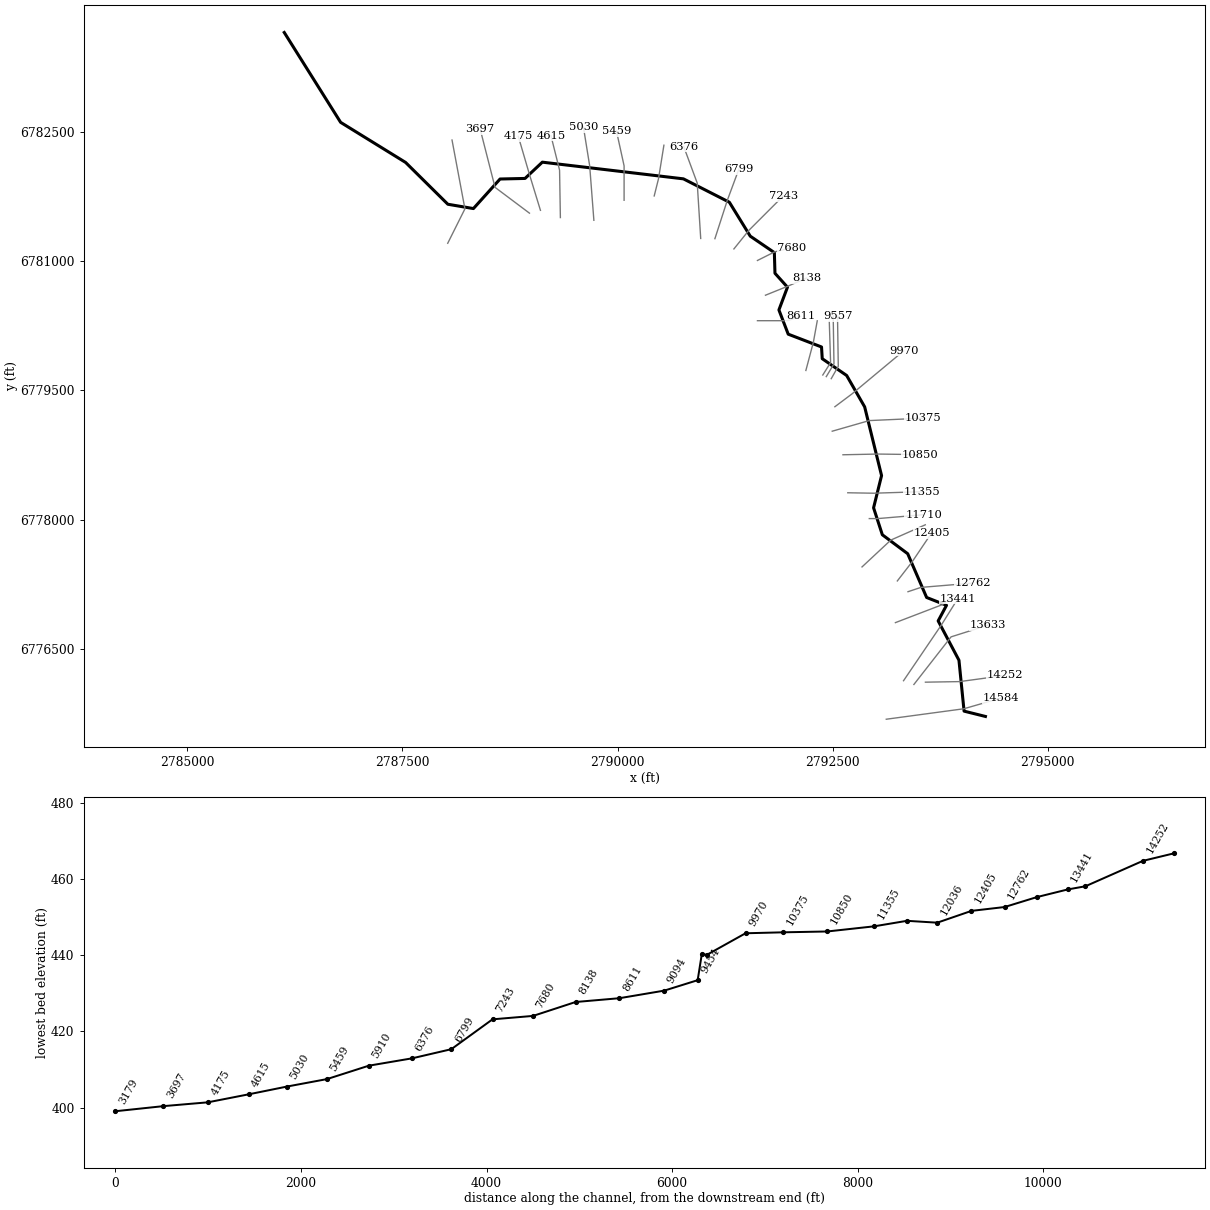
--- Caney Creek T 13.prj (project) ---

Proj Title=Caney Creek T 13 Base Level Engineering
Current Plan=p01
Default Exp/Contr=0.3,0.1
English Units
Geom File=g01
Flow File=f01
Plan File=p01
BEGIN DESCRIPTION:
Caney Creek T 13
END DESCRIPTION:

--- Caney Creek T 13.p01 (plan) ---

Plan Title=Multiple Run
Short Identifier=Multiple
Geom File=g01
Flow File=f01
Subcritical Flow
K Sum by GR= 0
Std Step Tol= 0.01
Critical Tol= 0.01
Num of Std Step Trials= 20
Max Error Tol= 0.3
Flow Tol Ratio= 0.001
Split Flow NTrial= 30
Split Flow Tol= 0.02
Split Flow Ratio= 0.02
Log Output Level= 0
Friction Slope Method= 1
Unsteady Friction Slope Method= 2
Unsteady Bridges Friction Slope Method= 1
Parabolic Critical Depth
Global Vel Dist=  1 , 1 , 1
Global Log Level= 0
CheckData=True
Encroach Param= -1, 0, 0, 0
BEGIN DESCRIPTION:
Multiple Run
END DESCRIPTION:

--- Caney Creek T 13.f01 (steady flow) ---

Flow Title=Multiple
Number of Profiles=7
Profile Names=10-year,25-year,50-year,1pct_min,100-year,1pct_plu,500-year
River Rch & RM= Caney Creek T 13,Reach-1,14584
     468     628     759     457     911    1818    1317
River Rch & RM= Caney Creek T 13,Reach-1,13633
     614     836    1020     619    1235    2464    1814
River Rch & RM= Caney Creek T 13,Reach-1,11355
     732    1003    1228     747    1491    2976    2203
River Rch & RM= Caney Creek T 13,Reach-1,9454
     938    1296    1595     974    1944    3879    2896
River Rch & RM= Caney Creek T 13,Reach-1,3179
    1067    1480    1825    1117    2228    4445    3328
Boundary for River Rch & Prof#=Caney Creek T 13,Reach-1,1
Up Type=0
Dn Type=3
Dn Slope=0.005
Boundary for River Rch & Prof#=Caney Creek T 13,Reach-1,2
Up Type=0
Dn Type=3
Dn Slope=0.005
Boundary for River Rch & Prof#=Caney Creek T 13,Reach-1,3
Up Type=0
Dn Type=3
Dn Slope=0.005
Boundary for River Rch & Prof#=Caney Creek T 13,Reach-1,4
Up Type=0
Dn Type=3
Dn Slope=0.005
Boundary for River Rch & Prof#=Caney Creek T 13,Reach-1,5
Up Type=0
Dn Type=3
Dn Slope=0.005
Boundary for River Rch & Prof#=Caney Creek T 13,Reach-1,6
Up Type=0
Dn Type=3
Dn Slope=0.005
Boundary for River Rch & Prof#=Caney Creek T 13,Reach-1,7
Up Type=0
Dn Type=3
Dn Slope=0.005

--- Caney Creek T 13.g01 (geometry) ---

Geom Title=Existing Conditions

River Reach=Caney Creek T 13,Reach-1
Reach XY= 30
      2794276.00      6775711.00      2794027.73      6775772.85
      2793968.20      6776364.42      2793726.56      6776821.64
      2793823.54      6777002.83      2793592.49      6777093.94
      2793372.45      6777602.50      2793077.64      6777822.83
      2792975.77      6778136.00      2793068.67      6778510.90
      2792872.18      6779309.42      2792662.86      6779674.21
      2792379.08      6779869.29      2792370.82      6780005.58
      2791983.68      6780154.48      2791875.42      6780436.00
      2791974.96      6780700.56      2791829.54      6780862.46
      2791822.60      6781102.56      2791542.27      6781293.79
      2791299.47      6781687.99      2790765.50      6781959.78
      2789125.91      6782153.71      2788924.54      6781964.54
      2788634.28      6781957.94      2788324.61      6781614.37
      2788027.47      6781664.54      2787536.12      6782150.65
      2786781.26      6782616.47      2786126.00      6783661.00

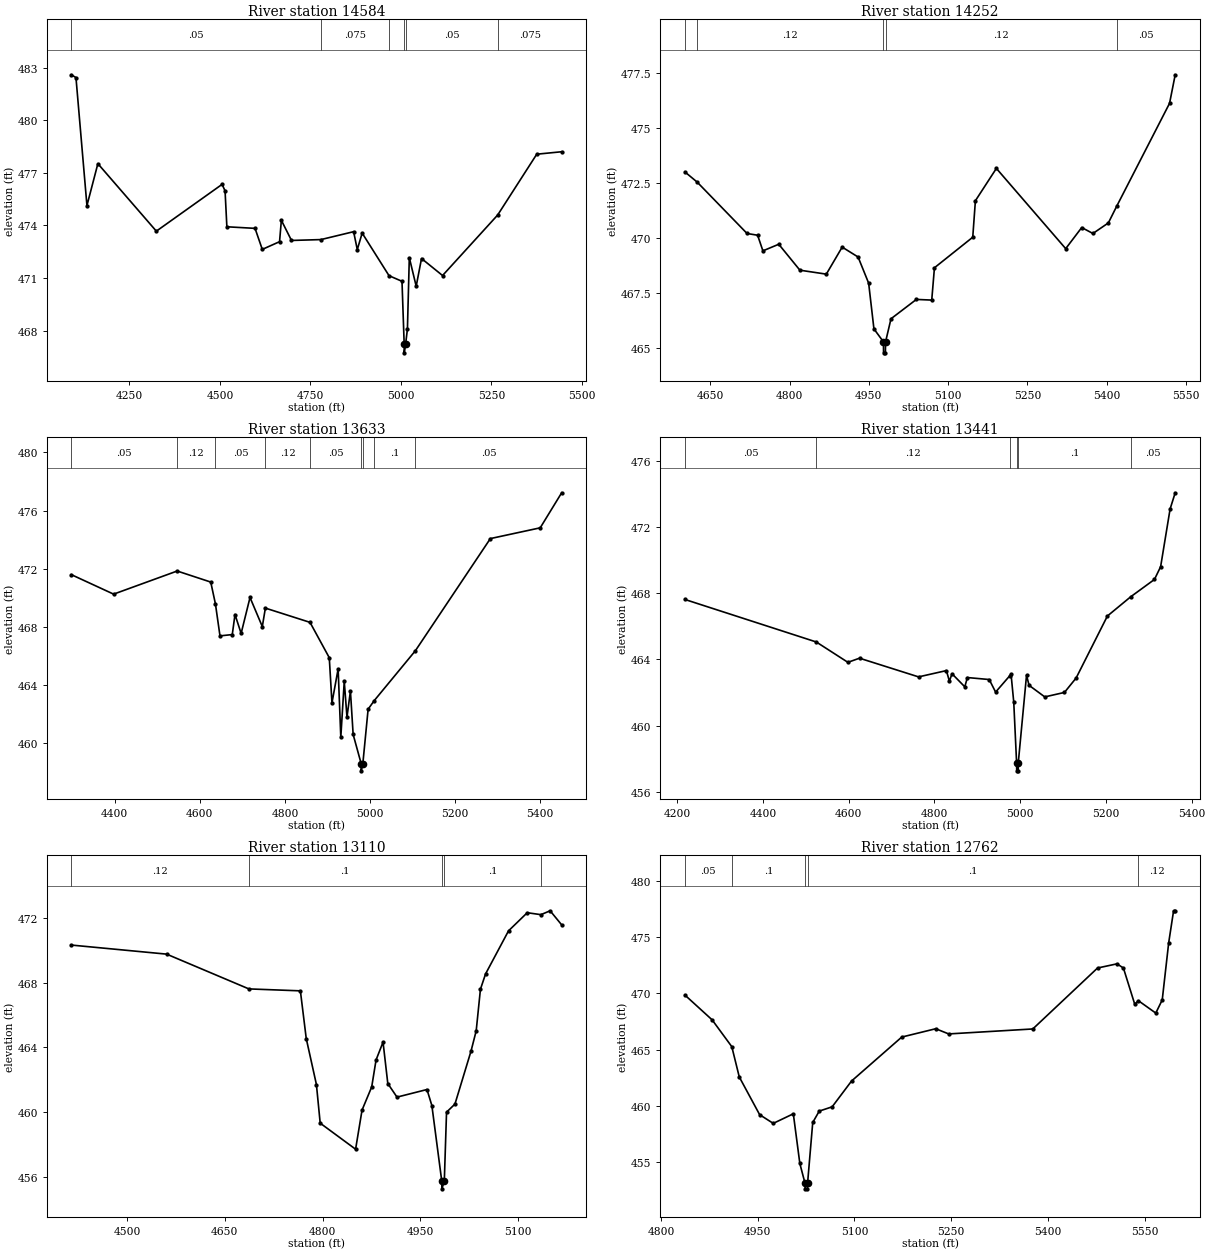
Type RM Length L Ch R = 1,14584,332,332,332
BEGIN DESCRIPTION:
Caney Creek T 13 32.0
END DESCRIPTION:
XS GIS Cut Line= 3
      2793123.43      6775678.84      2794025.66      6775800.54
      2794452.06      6775923.60
#Sta/Elev= 30
  4089.6  482.59  4102.3  482.43  4132.6  475.13  4162.8  477.52  4324.3  473.67
  4505.9  476.34  4514.1  475.97  4519.1  473.92  4596.9  473.83  4616.9  472.63
  4664.6  473.07  4669.6  474.29  4697.6  473.14  4778.9  473.19  4869.2  473.64
  4879.3  472.62  4892.8  473.56  4967.0  471.13  5002.8  470.81  5008.8  467.23
  5009.0  466.73  5012.8  467.23  5017.8  468.09  5023.0  472.16  5042.0  470.53
  5056.7  472.11  5114.8  471.14  5267.0  474.59  5375.0  478.06  5443.8  478.20
#Mann=6,-1,0
  4089.6    0.05       0  4778.9   0.075       0  4967.0    0.05       0
  5008.8    0.04       0  5012.8    0.05       0  5267.0   0.075       0
Bank Sta=5008.8,5012.8
Exp/Cntr=0.3,0.1

Type RM Length L Ch R = 1,14252,619,619,619
BEGIN DESCRIPTION:
Caney Creek T 13 31.0
END DESCRIPTION:
XS GIS Cut Line= 3
      2793578.39      6776109.51      2793976.44      6776116.18
      2794501.32      6776187.48
#Sta/Elev= 30
  4601.9  473.00  4625.0  472.54  4719.5  470.20  4739.5  470.12  4749.5  469.41
  4779.5  469.71  4819.5  468.53  4869.5  468.35  4899.5  469.58  4929.6  469.13
  4949.6  467.94  4959.6  465.86  4977.6  465.27  4977.8  464.77  4981.3  464.77
  4981.6  465.27  4991.9  466.32  5039.9  467.20  5069.0  467.17  5074.1  468.64
  5146.6  470.03  5151.6  471.69  5191.3  473.16  5322.5  469.51  5352.8  470.47
  5374.0  470.20  5403.2  470.68  5419.0  471.44  5519.0  476.12  5529.7  477.42
#Mann=5,-1,0
  4601.9    0.05       0  4625.0    0.12       0  4977.6    0.07       0
  4981.6    0.12       0  5419.0    0.05       0
Bank Sta=4977.6,4981.6
Exp/Cntr=0.3,0.1

Type RM Length L Ch R = 1,13633,192,192,192
BEGIN DESCRIPTION:
Caney Creek T 13 30.0
END DESCRIPTION:
XS GIS Cut Line= 3
      2793444.44      6776082.76      2793876.34      6776636.04
      2794305.75      6776772.26
#Sta/Elev= 30
  4298.1  471.59  4397.4  470.25  4546.8  471.84  4625.7  471.08  4636.7  469.58
  4647.4  467.38  4676.3  467.47  4682.7  468.85  4697.1  467.55  4718.0  470.02
  4746.9  468.02  4754.1  469.29  4859.0  468.31  4904.3  465.88  4910.6  462.77
  4925.1  465.11  4931.4  460.41  4939.5  464.26  4945.9  461.79  4954.0  463.59
  4960.4  460.60  4979.2  458.60  4979.4  458.10  4983.2  458.60  4995.6  462.34
  5010.0  462.93  5106.7  466.36  5282.9  474.07  5400.1  474.81  5450.5  477.22
#Mann=9,-1,0
  4298.1    0.05       0  4546.8    0.12       0  4636.7    0.05       0
  4754.1    0.12       0  4859.0    0.05       0  4979.2    0.05       0
  4983.2    0.05       0  5010.0     0.1       0  5106.7    0.05       0
Bank Sta=4979.2,4983.2
Exp/Cntr=0.3,0.1

Type RM Length L Ch R = 1,13441,331,331,331
BEGIN DESCRIPTION:
Caney Creek T 13 29.0
END DESCRIPTION:
XS GIS Cut Line= 3
      2793324.07      6776126.45      2793763.15      6776773.43
      2793954.93      6777079.86
#Sta/Elev= 30
  4218.1  467.62  4524.5  465.05  4598.2  463.82  4625.3  464.07  4763.0  462.94
  4827.9  463.32  4834.9  462.68  4841.0  463.13  4870.8  462.34  4876.9  462.90
  4927.8  462.78  4942.7  462.02  4976.1  463.02  4978.7  463.10  4985.0  461.41
  4991.6  457.76  4991.9  457.26  4995.4  457.26  4995.6  457.76  5014.8  463.04
  5020.7  462.43  5057.3  461.73  5103.2  462.00  5130.4  462.87  5203.4  466.62
  5257.6  467.78  5313.1  468.83  5327.5  469.60  5349.6  473.09  5361.5  474.07
#Mann=6,-1,0
  4218.1    0.05       0  4524.5    0.12       0  4976.1     0.1       0
  4991.6    0.07       0  4995.6     0.1       0  5257.6    0.05       0
Bank Sta=4991.6,4995.6
Exp/Cntr=0.3,0.1

Type RM Length L Ch R = 1,13110,348,348,348
BEGIN DESCRIPTION:
Caney Creek T 13 28.0
END DESCRIPTION:
XS GIS Cut Line= 3
      2793229.59      6776801.62      2793776.00      6777011.00
      2793905.16      6777116.78
#Sta/Elev= 30
  4414.6  470.33  4560.7  469.77  4686.9  467.62  4765.9  467.50  4774.9  464.55
  4790.5  461.71  4796.3  459.32  4850.6  457.71  4860.5  460.13  4875.3  461.56
  4882.0  463.23  4892.7  464.33  4900.0  461.77  4914.1  460.93  4960.1  461.40
  4967.6  460.41  4982.7  455.76  4983.0  455.26  4986.7  455.76  4990.1  460.00
  5003.0  460.50  5027.7  463.78  5035.6  465.03  5042.1  467.60  5050.0  468.55
  5085.2  471.21  5113.9  472.33  5134.9  472.21  5149.0  472.45  5166.7  471.58
#Mann=5,-1,0
  4414.6    0.12       0  4686.9     0.1       0  4982.7    0.07       0
  4986.7     0.1       0  5134.9    0.05       0
Bank Sta=4982.7,4986.7
Exp/Cntr=0.3,0.1

Type RM Length L Ch R = 1,12762,357,357,357
BEGIN DESCRIPTION:
Caney Creek T 13 27.0
END DESCRIPTION:
XS GIS Cut Line= 3
      2793376.01      6777161.00      2793526.00      6777211.00
      2794126.02      6777261.00
#Sta/Elev= 30
  4837.1  469.85  4879.3  467.65  4909.8  465.27  4921.4  462.58  4953.0  459.23
  4974.1  458.46  5005.2  459.31  5015.3  454.90  5023.3  453.15  5023.6  452.65
  5027.1  452.65  5027.3  453.15  5035.3  458.54  5045.4  459.55  5065.4  459.93
  5095.5  462.22  5173.3  466.12  5226.0  466.86  5246.1  466.40  5376.5  466.84
  5476.9  472.25  5507.0  472.62  5517.0  472.25  5534.6  469.03  5540.2  469.35
  5567.2  468.25  5577.2  469.42  5587.2  474.49  5594.8  477.33  5597.3  477.33
#Mann=5,-1,0
  4837.1    0.05       0  4909.8     0.1       0  5023.3    0.07       0
  5027.3     0.1       0  5540.2    0.12       0
Bank Sta=5023.3,5027.3
Exp/Cntr=0.3,0.1

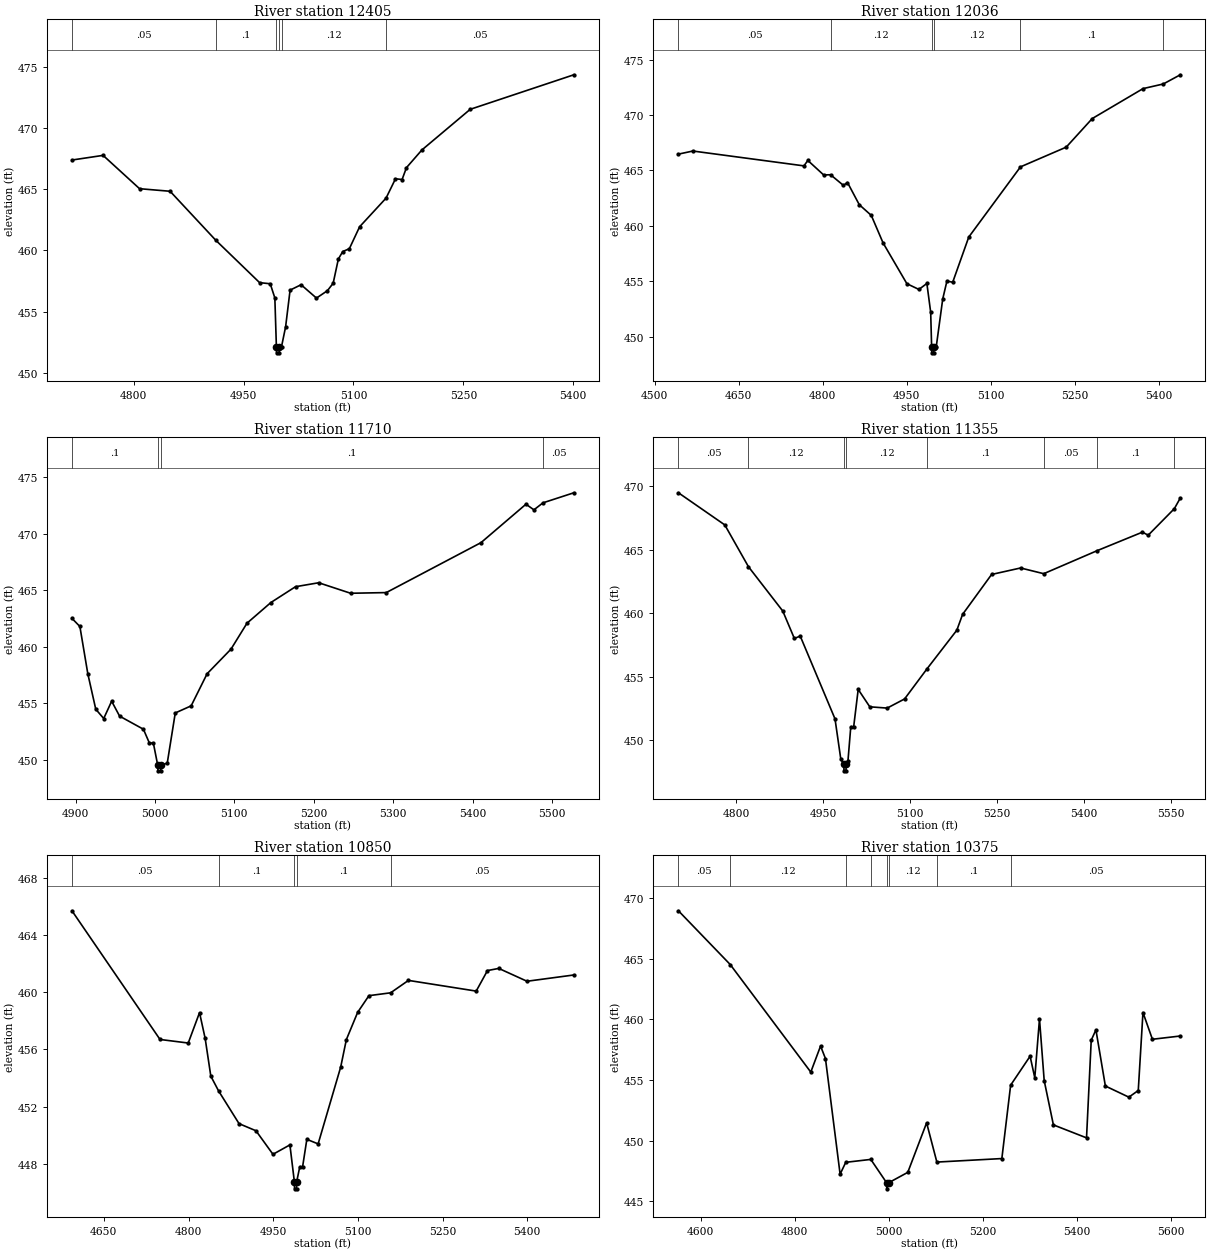
Type RM Length L Ch R = 1,12405,369,369,369
BEGIN DESCRIPTION:
Caney Creek T 13 26.0
END DESCRIPTION:
XS GIS Cut Line= 3
      2793251.93      6777286.28      2793426.00      6777511.00
      2793649.91      6777843.60
#Sta/Elev= 30
  4715.7  467.38  4758.2  467.76  4808.0  465.04  4849.7  464.83  4911.9  460.84
  4971.9  457.37  4986.4  457.28  4992.7  456.12  4994.8  452.14  4995.0  451.64
  4998.5  451.64  4998.8  452.14  5001.8  452.14  5007.4  453.77  5013.5  456.76
  5028.5  457.20  5049.5  456.11  5064.4  456.71  5072.3  457.32  5079.4  459.30
  5085.4  459.91  5094.4  460.14  5108.4  461.93  5144.5  464.27  5157.4  465.85
  5166.4  465.79  5172.4  466.76  5193.4  468.20  5259.4  471.52  5400.9  474.34
#Mann=6,-1,0
  4715.7    0.05       0  4911.9     0.1       0  4994.8    0.07       0
  4998.8     0.1       0  5001.8    0.12       0  5144.5    0.05       0
Bank Sta=4994.8,4998.8
Exp/Cntr=0.3,0.1

Type RM Length L Ch R = 1,12036,326,326,326
BEGIN DESCRIPTION:
Caney Creek T 13 25.0
END DESCRIPTION:
XS GIS Cut Line= 3
      2792841.49      6777449.03      2793176.00      6777761.00
      2793576.85      6777938.76
#Sta/Elev= 30
  4542.4  466.47  4568.2  466.75  4766.5  465.41  4773.4  465.90  4801.7  464.59
  4814.0  464.61  4836.9  463.65  4844.2  463.91  4865.2  461.91  4886.7  460.94
  4907.7  458.46  4950.2  454.78  4971.7  454.26  4985.9  454.80  4992.7  452.20
  4994.4  449.04  4994.6  448.54  4998.1  448.54  4998.4  449.04  5002.5  449.04
  5014.2  453.40  5021.7  455.02  5032.0  454.91  5060.7  458.99  5153.0  465.32
  5234.6  467.10  5281.1  469.68  5371.7  472.38  5407.9  472.80  5438.3  473.63
#Mann=6,-1,0
  4542.4    0.05       0  4814.0    0.12       0  4994.4    0.07       0
  4998.4    0.12       0  5153.0     0.1       0  5407.9    0.05       0
Bank Sta=4994.4,4998.4
Exp/Cntr=0.3,0.1

Type RM Length L Ch R = 1,11710,355,355,355
BEGIN DESCRIPTION:
Caney Creek T 13 24.0
END DESCRIPTION:
XS GIS Cut Line= 3
      2792926.03      6778011.00      2793026.00      6778011.00
      2793556.13      6778056.00
#Sta/Elev= 30
  4895.5  462.52  4905.5  461.80  4915.5  457.61  4925.5  454.48  4935.5  453.66
  4945.5  455.19  4955.5  453.87  4985.5  452.71  4993.0  451.49  4998.0  451.49
  5003.5  449.53  5003.8  449.03  5007.3  449.03  5007.5  449.53  5015.5  449.71
  5025.6  454.15  5045.6  454.78  5065.7  457.62  5095.8  459.80  5115.9  462.09
  5146.0  463.92  5177.0  465.32  5206.2  465.67  5246.4  464.74  5291.3  464.80
  5410.6  469.22  5467.2  472.62  5477.2  472.12  5488.6  472.74  5527.5  473.63
#Mann=4,-1,0
  4895.5     0.1       0  5003.5    0.07       0  5007.5     0.1       0
  5488.6    0.05       0
Bank Sta=5003.5,5007.5
Exp/Cntr=0.3,0.1

Type RM Length L Ch R = 1,11355,505,505,505
BEGIN DESCRIPTION:
Caney Creek T 13 23.0
END DESCRIPTION:
XS GIS Cut Line= 3
      2792675.98      6778311.00      2792975.54      6778305.83
      2793541.36      6778323.65
#Sta/Elev= 30
  4700.4  469.47  4780.4  466.94  4821.2  463.65  4880.4  460.16  4900.4  458.00
  4910.5  458.19  4970.5  451.67  4980.5  448.50  4985.7  448.08  4986.0  447.58
  4989.5  447.58  4989.7  448.08  4992.8  448.34  4997.7  451.05  5002.7  451.05
  5010.5  453.99  5030.5  452.62  5060.5  452.52  5090.5  453.24  5129.0  455.60
  5180.6  458.65  5190.6  459.90  5240.6  463.04  5290.6  463.55  5330.5  463.10
  5423.0  464.92  5500.7  466.37  5510.7  466.13  5555.8  468.22  5566.1  469.06
#Mann=8,-1,0
  4700.4    0.05       0  4821.2    0.12       0  4985.7    0.07       0
  4989.7    0.12       0  5129.0     0.1       0  5330.5    0.05       0
  5423.0     0.1       0  5555.8    0.05       0
Bank Sta=4985.7,4989.7
Exp/Cntr=0.3,0.1

Type RM Length L Ch R = 1,10850,475,475,475
BEGIN DESCRIPTION:
Caney Creek T 13 22.0
END DESCRIPTION:
XS GIS Cut Line= 3
      2792620.02      6778752.70      2793026.00      6778761.00
      2793508.99      6778754.49
#Sta/Elev= 30
  4593.5  465.72  4749.5  456.70  4799.5  456.45  4819.5  458.58  4829.5  456.77
  4839.5  454.13  4853.3  453.09  4889.5  450.80  4919.5  450.30  4949.6  448.65
  4979.6  449.31  4987.5  446.73  4987.8  446.23  4991.3  446.23  4991.6  446.73
  4997.1  447.78  5002.1  447.78  5009.6  449.70  5029.6  449.38  5069.6  454.77
  5079.6  456.69  5099.6  458.60  5119.6  459.77  5158.0  459.97  5189.6  460.84
  5309.6  460.09  5329.6  461.53  5349.6  461.68  5399.6  460.78  5482.6  461.22
#Mann=5,-1,0
  4593.5    0.05       0  4853.3     0.1       0  4987.5    0.07       0
  4991.6     0.1       0  5158.0    0.05       0
Bank Sta=4987.5,4991.6
Exp/Cntr=0.3,0.1

Type RM Length L Ch R = 1,10375,405,405,405
BEGIN DESCRIPTION:
Caney Creek T 13 21.0
END DESCRIPTION:
XS GIS Cut Line= 3
      2792495.24      6779026.63      2792925.31      6779149.95
      2793545.38      6779177.99
#Sta/Elev= 30
  4552.6  468.97  4662.9  464.53  4834.3  455.65  4855.1  457.80  4865.5  456.77
  4896.7  447.22  4908.7  448.20  4962.0  448.44  4995.7  446.51  4996.0  446.01
  4999.9  446.51  5040.7  447.37  5080.8  451.46  5102.6  448.22  5240.9  448.51
  5259.6  454.57  5301.0  456.96  5311.0  455.18  5321.0  460.04  5331.0  454.95
  5350.6  451.29  5421.1  450.22  5431.1  458.28  5441.1  459.14  5461.2  454.50
  5511.2  453.58  5531.2  454.13  5541.2  460.57  5561.3  458.36  5620.7  458.63
#Mann=8,-1,0
  4552.6    0.05       0  4662.9    0.12       0  4908.7     0.1       0
  4962.0    0.12       0  4995.7    0.07       0  4999.9    0.12       0
  5102.6     0.1       0  5259.6    0.05       0
Bank Sta=4995.7,4999.9
Exp/Cntr=0.3,0.1

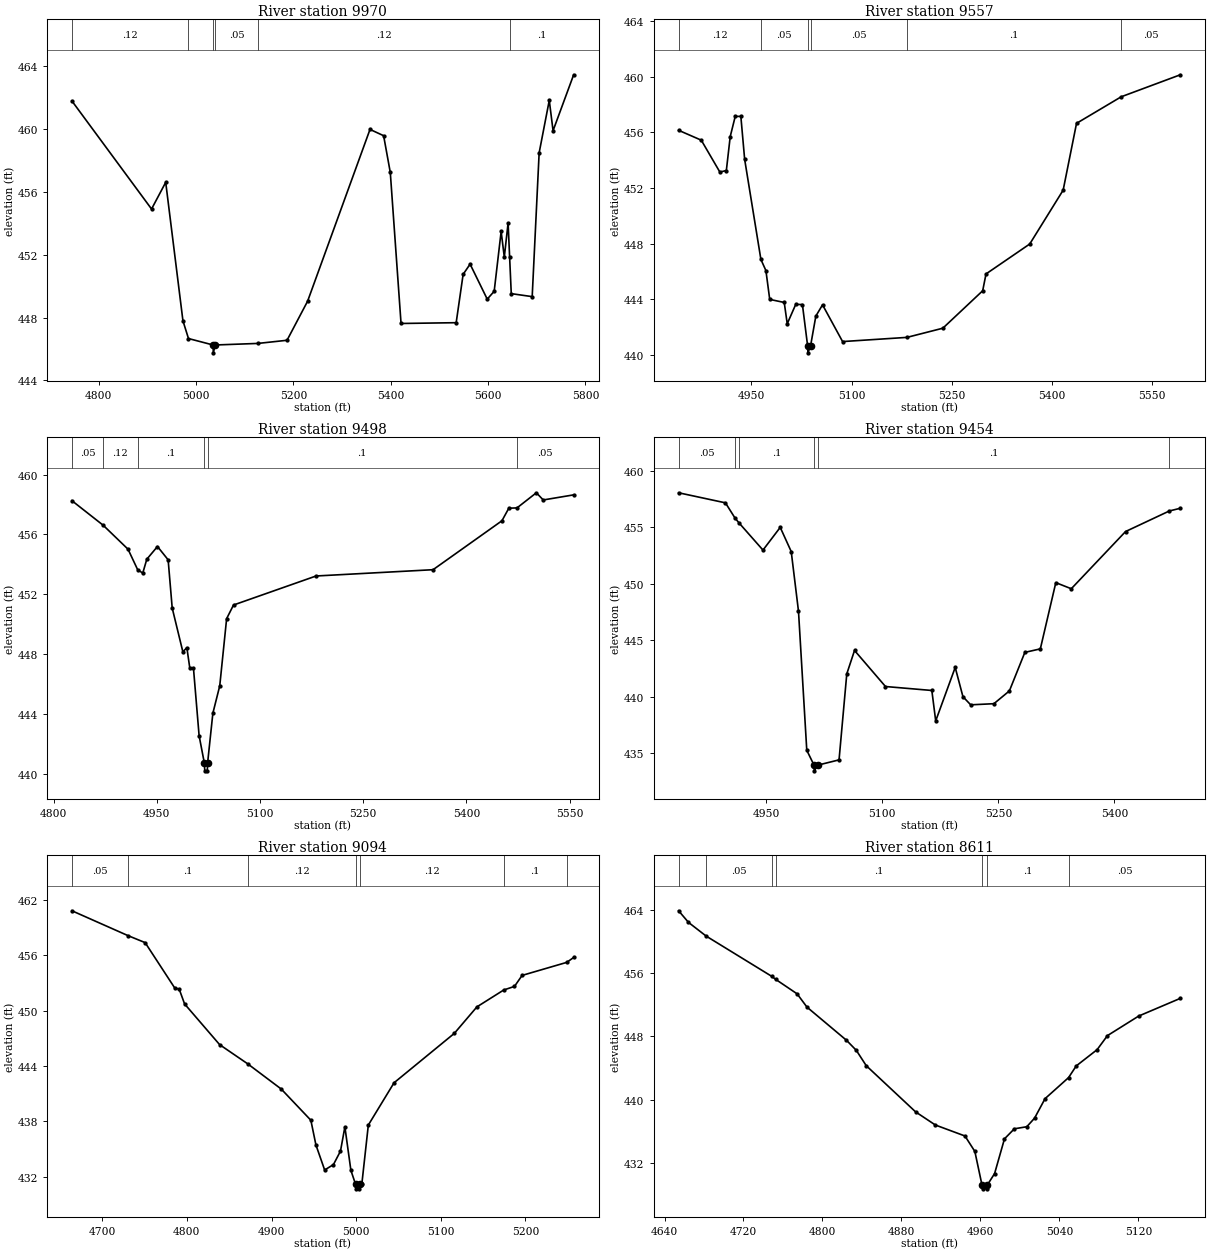
Type RM Length L Ch R = 1,9970,413,413,413
BEGIN DESCRIPTION:
Caney Creek T 13 20.0
END DESCRIPTION:
XS GIS Cut Line= 3
      2792525.99      6779310.99      2792726.00      6779461.00
      2793325.97      6779960.97
#Sta/Elev= 30
  4744.9  461.80  4908.5  454.92  4937.6  456.62  4973.0  447.80  4984.4  446.67
  5035.0  446.26  5035.4  445.76  5039.4  446.26  5127.2  446.36  5186.9  446.56
  5229.2  449.05  5357.4  459.99  5385.4  459.59  5399.1  457.25  5421.2  447.63
  5534.5  447.68  5548.8  450.76  5563.1  451.41  5598.3  449.18  5612.6  449.68
  5626.9  453.49  5633.4  451.86  5641.2  454.03  5644.3  451.88  5647.7  449.53
  5690.7  449.34  5705.0  458.50  5725.8  461.84  5733.6  459.91  5775.9  463.47
#Mann=6,-1,0
  4744.9    0.12       0  4984.4    0.05       0  5035.0    0.04       0
  5039.4    0.05       0  5127.2    0.12       0  5644.3     0.1       0
Bank Sta=5035,5039.4
Exp/Cntr=0.3,0.1

Type RM Length L Ch R = 1,9557,59,59,59
BEGIN DESCRIPTION:
Mapping XS fb656c15
END DESCRIPTION:
XS GIS Cut Line= 3
      2792483.80      6779637.31      2792565.50      6779781.36
      2792556.54      6780366.29
#Sta/Elev= 30
  4841.3  456.14  4875.2  455.43  4903.0  453.14  4912.7  453.25  4918.5  455.69
  4926.0  457.14  4934.4  457.14  4940.1  454.05  4964.4  446.86  4971.9  446.06
  4977.6  443.99  4999.3  443.77  5003.8  442.24  5016.5  443.63  5026.5  443.62
  5034.3  440.65  5034.7  440.15  5038.7  440.65  5046.6  442.79  5056.6  443.60
  5086.6  440.96  5182.8  441.26  5236.6  441.92  5296.2  444.61  5301.2  445.82
  5366.6  447.97  5416.6  451.84  5436.6  456.64  5503.5  458.55  5591.9  460.13
#Mann=6,-1,0
  4841.3    0.12       0  4964.4    0.05       0  5034.3    0.03       0
  5038.7    0.05       0  5182.8     0.1       0  5503.5    0.05       0
Bank Sta=5034.3,5038.7
Exp/Cntr=0.3,0.1

Type RM Length L Ch R = 1,9498,44,44,44
BEGIN DESCRIPTION:
Caney Creek T 13 19.0
END DESCRIPTION:
XS GIS Cut Line= 3
      2792426.01      6779661.01      2792515.37      6779809.49
      2792506.53      6780365.22
#Sta/Elev= 30
  4826.7  458.25  4872.1  456.61  4908.2  455.01  4922.1  453.65  4929.6  453.41
  4935.5  454.34  4951.0  455.19  4966.5  454.30  4972.4  451.08  4987.9  448.15
  4993.7  448.43  4998.0  447.06  5003.3  447.06  5011.5  442.55  5019.2  440.70
  5019.7  440.20  5023.4  440.20  5023.8  440.70  5031.5  444.05  5041.5  445.88
  5051.5  450.37  5061.5  451.28  5181.5  453.22  5351.5  453.64  5451.6  456.91
  5461.6  457.75  5473.5  457.77  5501.6  458.78  5511.6  458.30  5555.8  458.64
#Mann=6,-1,0
  4826.7    0.05       0  4872.1    0.12       0  4922.1     0.1       0
  5019.2    0.07       0  5023.8     0.1       0  5473.5    0.05       0
Bank Sta=5019.2,5023.8
Exp/Cntr=0.3,0.1

Type RM Length L Ch R = 1,9454,360,360,360
BEGIN DESCRIPTION:
Mapping XS dae25dd4
END DESCRIPTION:
XS GIS Cut Line= 3
      2792385.53      6779679.78      2792476.10      6779824.12
      2792461.03      6780301.78
#Sta/Elev= 30
  4836.8  458.04  4897.3  457.15  4909.7  455.80  4914.9  455.37  4945.8  452.97
  4968.1  454.98  4982.3  452.84  4991.7  447.56  5002.4  435.26  5011.8  433.94
  5012.2  433.44  5016.4  433.94  5044.1  434.41  5054.1  442.02  5064.1  444.09
  5104.1  440.90  5164.0  440.55  5169.0  437.86  5194.2  442.59  5204.2  440.00
  5214.2  439.28  5244.2  439.38  5264.2  440.51  5284.2  443.92  5304.2  444.23
  5324.2  450.09  5344.2  449.55  5414.3  454.61  5470.9  456.43  5485.1  456.67
#Mann=6,-1,0
  4836.8    0.05       0  4909.7    0.12       0  4914.9     0.1       0
  5011.8    0.07       0  5016.4     0.1       0  5470.9    0.05       0
Bank Sta=5011.8,5016.4
Exp/Cntr=0.3,0.1

Type RM Length L Ch R = 1,9094,483,483,483
BEGIN DESCRIPTION:
Caney Creek T 13 18.0
END DESCRIPTION:
XS GIS Cut Line= 3
      2792188.85      6779732.37      2792276.00      6780061.00
      2792321.19      6780309.74
#Sta/Elev= 30
  4664.2  460.82  4730.4  458.13  4750.7  457.37  4785.7  452.45  4790.9  452.34
  4797.3  450.73  4838.7  446.32  4871.9  444.24  4911.5  441.51  4946.5  438.13
  4952.5  435.45  4962.8  432.74  4973.2  433.33  4981.5  434.79  4986.7  437.41
  4993.8  432.70  4999.3  431.20  4999.8  430.70  5003.5  430.70  5004.0  431.20
  5006.7  431.20  5014.4  437.61  5044.8  442.19  5116.0  447.54  5142.7  450.41
  5174.4  452.24  5187.1  452.63  5196.1  453.82  5248.8  455.23  5257.0  455.76
#Mann=7,-1,0
  4664.2    0.05       0  4730.4     0.1       0  4871.9    0.12       0
  4999.3    0.07       0  5004.0    0.12       0  5174.4     0.1       0
  5248.8    0.05       0
Bank Sta=4999.3,5004
Exp/Cntr=0.3,0.1

Type RM Length L Ch R = 1,8611,473,473,473
BEGIN DESCRIPTION:
Caney Creek T 13 17.0
END DESCRIPTION:
XS GIS Cut Line= 3
      2791626.02      6780311.00      2791976.00      6780311.00
      2792126.00      6780361.00
#Sta/Elev= 30
  4654.3  463.86  4664.3  462.39  4682.2  460.66  4748.5  455.58  4752.6  455.19
  4774.3  453.36  4784.3  451.68  4824.3  447.49  4834.3  446.21  4844.3  444.28
  4894.3  438.44  4914.3  436.78  4944.3  435.39  4954.3  433.44  4961.5  429.21
  4962.3  428.71  4966.2  428.71  4967.0  429.21  4974.3  430.64  4984.3  435.03
  4994.3  436.30  5006.9  436.56  5014.8  437.65  5025.4  440.11  5049.2  442.77
  5057.0  444.25  5078.1  446.30  5088.6  448.08  5120.2  450.55  5162.4  452.79
#Mann=7,-1,0
  4654.3    0.12       0  4682.2    0.05       0  4748.5    0.12       0
  4752.6     0.1       0  4961.5    0.07       0  4967.0     0.1       0
  5049.2    0.05       0
Bank Sta=4961.5,4967
Exp/Cntr=0.3,0.1

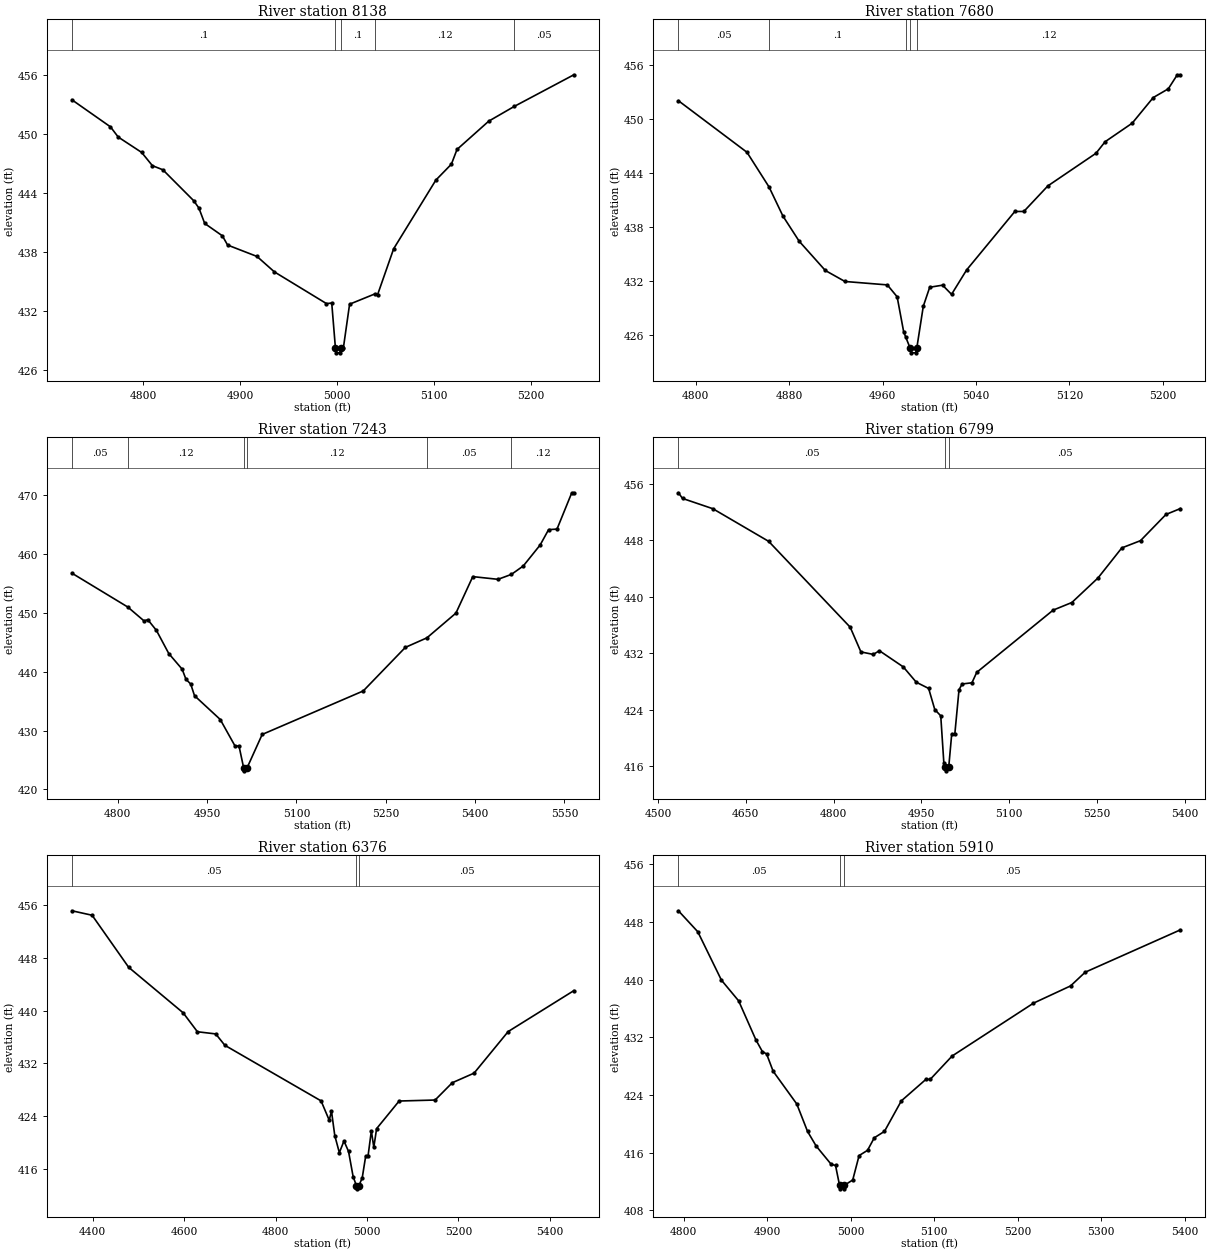
Type RM Length L Ch R = 1,8138,458,458,458
BEGIN DESCRIPTION:
Caney Creek T 13 16.0
END DESCRIPTION:
XS GIS Cut Line= 3
      2791719.16      6780607.19      2791976.00      6780711.00
      2792196.51      6780806.18
#Sta/Elev= 30
  4726.8  453.46  4766.5  450.71  4774.5  449.67  4798.6  448.11  4809.7  446.76
  4820.5  446.34  4852.2  443.20  4857.6  442.45  4863.6  440.88  4881.8  439.62
  4887.2  438.68  4917.5  437.52  4935.4  435.95  4989.1  432.72  4994.5  432.78
  4998.3  428.21  4999.2  427.71  5003.1  427.71  5003.9  428.21  5006.5  428.21
  5012.9  432.66  5038.8  433.70  5041.8  433.64  5058.3  438.30  5101.8  445.29
  5117.8  446.91  5123.6  448.41  5156.3  451.29  5182.6  452.79  5244.0  456.01
#Mann=5,-1,0
  4726.8     0.1       0  4998.3    0.07       0  5003.9     0.1       0
  5038.8    0.12       0  5182.6    0.05       0
Bank Sta=4998.3,5003.9
Exp/Cntr=0.3,0.1

Type RM Length L Ch R = 1,7680,437,437,437
BEGIN DESCRIPTION:
Caney Creek T 13 15.0
END DESCRIPTION:
XS GIS Cut Line= 3
      2791625.97      6781010.99      2791826.00      6781111.00
      2792026.01      6781161.00
#Sta/Elev= 30
  4785.2  452.04  4843.9  446.32  4862.8  442.47  4874.7  439.24  4888.6  436.45
  4911.0  433.20  4927.8  431.98  4964.1  431.60  4972.5  430.28  4978.1  426.39
  4979.8  425.83  4983.7  424.56  4984.5  424.06  4988.4  424.06  4989.3  424.56
  4994.9  429.23  5000.4  431.34  5011.4  431.57  5019.1  430.55  5032.0  433.26
  5073.3  439.75  5081.0  439.75  5101.6  442.59  5142.8  446.21  5150.6  447.49
  5173.8  449.55  5191.8  452.39  5204.7  453.36  5212.4  454.92  5215.0  454.92
#Mann=5,-1,0
  4785.2    0.05       0  4862.8     0.1       0  4979.8    0.12       0
  4983.7    0.07       0  4989.3    0.12       0
Bank Sta=4983.7,4989.3
Exp/Cntr=0.3,0.1

Type RM Length L Ch R = 1,7243,444,444,444
BEGIN DESCRIPTION:
Caney Creek T 13 14.0
END DESCRIPTION:
XS GIS Cut Line= 3
      2791352.33      6781145.21      2791526.00      6781361.00
      2791926.01      6781761.01
#Sta/Elev= 30
  4723.1  456.73  4816.9  450.98  4844.1  448.63  4850.5  448.83  4864.9  447.02
  4885.7  443.08  4908.1  440.43  4914.5  438.72  4922.5  437.90  4928.9  435.92
  4972.1  431.88  4996.9  427.38  5003.6  427.38  5011.4  423.66  5012.3  423.16
  5017.1  423.66  5042.5  429.34  5212.2  436.73  5282.9  444.13  5319.1  445.75
  5367.8  449.95  5396.1  456.15  5438.5  455.69  5461.0  456.53  5480.9  457.96
  5509.2  461.52  5523.4  464.13  5537.5  464.22  5562.3  470.39  5565.8  470.39
#Mann=6,-1,0
  4723.1    0.05       0  4816.9    0.12       0  5011.4    0.07       0
  5017.1    0.12       0  5319.1    0.05       0  5461.0    0.12       0
Bank Sta=5011.4,5017.1
Exp/Cntr=0.3,0.1

Type RM Length L Ch R = 1,6799,423,423,423
BEGIN DESCRIPTION:
Caney Creek T 13 13.0
END DESCRIPTION:
XS GIS Cut Line= 3
      2791131.45      6781264.30      2791276.00      6781711.00
      2791411.08      6782074.72
#Sta/Elev= 30
  4534.8  454.70  4541.8  453.90  4593.7  452.44  4689.0  447.82  4828.3  435.66
  4846.6  432.16  4867.7  431.81  4878.2  432.33  4919.0  430.04  4941.2  427.87
  4962.3  426.99  4972.8  424.00  4983.0  423.11  4988.3  416.42  4990.9  415.82
  4991.8  415.32  4996.6  415.82  5001.7  420.51  5007.0  420.51  5014.2  426.80
  5019.5  427.62  5036.3  427.79  5044.5  429.27  5175.0  438.08  5207.0  439.16
  5251.7  442.64  5292.3  446.89  5324.3  447.92  5367.8  451.63  5392.3  452.46
#Mann=3,-1,0
  4534.8    0.05       0  4990.9    0.04       0  4996.6    0.05       0
Bank Sta=4990.9,4996.6
Exp/Cntr=0.3,0.1

Type RM Length L Ch R = 1,6376,466,466,466
BEGIN DESCRIPTION:
Caney Creek T 13 12.0
END DESCRIPTION:
XS GIS Cut Line= 3
      2790966.52      6781267.01      2790926.00      6781911.00
      2790768.73      6782335.76
#Sta/Elev= 30
  4354.4  455.19  4398.5  454.51  4478.6  446.59  4597.7  439.68  4628.9  436.80
  4669.0  436.47  4689.0  434.74  4899.5  426.29  4917.3  423.36  4922.3  424.72
  4929.5  421.01  4939.5  418.42  4949.6  420.19  4959.6  418.61  4969.6  414.79
  4976.7  413.42  4977.6  412.92  4982.5  413.42  4989.6  414.61  4997.2  417.93
  5002.3  417.93  5009.5  421.73  5014.9  419.24  5021.0  422.07  5070.3  426.27
  5149.0  426.42  5186.6  429.05  5234.3  430.51  5308.9  436.83  5452.6  443.05
#Mann=3,-1,0
  4354.4    0.05       0  4976.7    0.04       0  4982.5    0.05       0
Bank Sta=4976.7,4982.5
Exp/Cntr=0.3,0.1

Type RM Length L Ch R = 1,5910,451,451,451
BEGIN DESCRIPTION:
Caney Creek T 13 11.0
END DESCRIPTION:
XS GIS Cut Line= 3
      2790426.00      6781761.02      2790476.00      6781961.00
      2790538.73      6782350.75
#Sta/Elev= 30
  4793.9  449.55  4817.1  446.64  4845.4  439.93  4866.0  437.06  4886.7  431.64
  4894.4  430.03  4899.5  429.69  4907.3  427.30  4935.6  422.76  4948.5  418.95
  4958.8  416.93  4976.8  414.39  4982.0  414.23  4986.8  411.49  4987.7  410.99
  4991.7  410.99  4992.7  411.49  5002.6  412.22  5010.2  415.60  5020.3  416.33
  5028.4  418.07  5040.6  418.96  5060.8  423.19  5090.3  426.18  5095.3  426.16
  5121.6  429.41  5219.0  436.74  5263.4  439.13  5280.9  441.03  5394.8  446.90
#Mann=3,-1,0
  4793.9    0.05       0  4986.8    0.04       0  4992.7    0.05       0
Bank Sta=4986.8,4992.7
Exp/Cntr=0.3,0.1

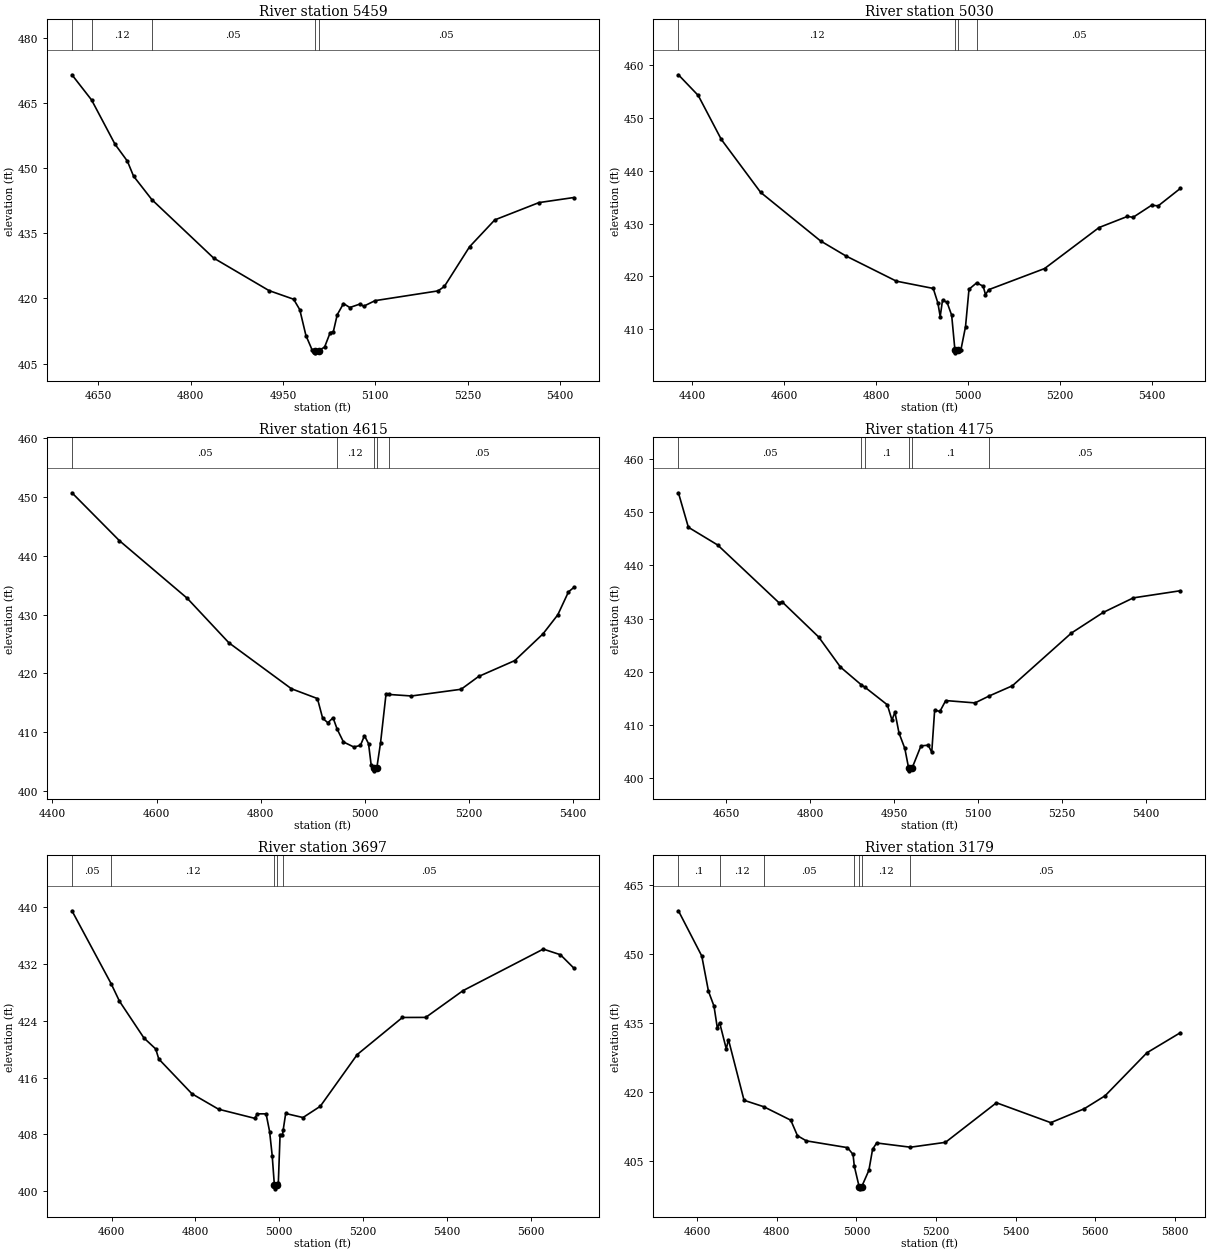
Type RM Length L Ch R = 1,5459,429,429,429
BEGIN DESCRIPTION:
Caney Creek T 13 10.0
END DESCRIPTION:
XS GIS Cut Line= 3
      2790076.00      6781710.96      2790076.00      6782111.00
      2789987.11      6782516.42
#Sta/Elev= 30
  4607.3  471.47  4639.2  465.67  4677.3  455.47  4697.3  451.60  4707.3  448.15
  4737.1  442.73  4837.3  429.30  4927.3  421.80  4967.3  419.81  4977.3  417.40
  4987.3  411.45  4997.3  408.15  5001.8  407.97  5002.8  407.47  5007.8  407.97
  5017.6  408.80  5026.7  412.13  5031.8  412.35  5038.1  416.23  5048.3  418.82
  5058.5  417.90  5075.6  418.73  5080.8  418.18  5099.5  419.48  5201.9  421.73
  5212.1  422.75  5253.0  431.88  5294.0  438.07  5365.7  442.05  5422.4  443.22
#Mann=5,-1,0
  4607.3    0.05       0  4639.2    0.12       0  4737.1    0.05       0
  5001.8    0.04       0  5007.8    0.05       0
Bank Sta=5001.8,5007.8
Exp/Cntr=0.3,0.1

Type RM Length L Ch R = 1,5030,415,415,415
BEGIN DESCRIPTION:
Caney Creek T 13 9.0
END DESCRIPTION:
XS GIS Cut Line= 3
      2789724.80      6781478.02      2789676.00      6782111.00
      2789603.17      6782562.60
#Sta/Elev= 30
  4369.9  458.24  4413.0  454.32  4463.2  445.99  4548.9  435.94  4679.2  426.74
  4734.0  423.91  4844.3  419.11  4924.5  417.73  4934.6  414.96  4939.6  412.40
  4944.7  415.51  4954.6  415.09  4964.6  412.64  4971.7  406.02  4972.7  405.52
  4977.7  406.02  4984.7  406.10  4994.7  410.46  5002.3  417.58  5019.0  418.79
  5033.1  418.16  5038.2  416.57  5045.3  417.50  5166.8  421.50  5285.4  429.28
  5347.2  431.39  5359.3  431.21  5399.8  433.51  5414.0  433.38  5462.2  436.69
#Mann=4,-1,0
  4369.9    0.12       0  4971.7    0.07       0  4977.7    0.12       0
  5019.0    0.05       0
Bank Sta=4971.7,4977.7
Exp/Cntr=0.3,0.1

Type RM Length L Ch R = 1,4615,440,440,440
BEGIN DESCRIPTION:
Caney Creek T 13 8.0
END DESCRIPTION:
XS GIS Cut Line= 3
      2789335.42      6781509.77      2789326.00      6782061.00
      2789226.01      6782460.98
#Sta/Elev= 30
  4437.5  450.68  4528.7  442.54  4658.8  432.77  4738.8  425.21  4858.8  417.41
  4908.8  415.74  4918.8  412.41  4928.8  411.63  4938.8  412.48  4946.7  410.54
  4958.8  408.37  4978.8  407.51  4991.4  407.80  4999.1  409.44  5006.9  408.09
  5012.0  404.44  5016.7  403.97  5017.7  403.47  5022.8  403.97  5030.0  408.25
  5040.4  416.45  5046.0  416.44  5089.3  416.18  5184.7  417.32  5218.2  419.49
  5287.7  422.19  5341.9  426.73  5370.2  429.95  5390.8  433.86  5401.1  434.61
#Mann=5,-1,0
  4437.5    0.05       0  4946.7    0.12       0  5016.7    0.07       0
  5022.8    0.12       0  5046.0    0.05       0
Bank Sta=5016.7,5022.8
Exp/Cntr=0.3,0.1

Type RM Length L Ch R = 1,4175,478,478,478
BEGIN DESCRIPTION:
Caney Creek T 13 7.0
END DESCRIPTION:
XS GIS Cut Line= 3
      2789103.68      6781593.99      2788976.00      6782011.00
      2788846.47      6782453.41
#Sta/Elev= 30
  4564.2  453.68  4582.0  447.19  4634.3  443.86  4744.1  432.98  4749.3  433.19
  4814.9  426.55  4853.9  420.88  4891.1  417.55  4898.2  417.05  4937.6  413.79
  4945.9  410.92  4951.2  412.41  4958.5  408.47  4968.9  405.58  4975.7  401.87
  4976.7  401.37  4981.8  401.87  4997.7  406.06  5010.7  406.20  5017.0  404.87
  5022.2  412.79  5031.6  412.55  5042.0  414.59  5094.3  414.15  5120.0  415.47
  5161.1  417.37  5266.6  427.29  5323.3  431.16  5377.3  433.91  5461.3  435.25
#Mann=6,-1,0
  4564.2    0.05       0  4891.1    0.12       0  4898.2     0.1       0
  4975.7    0.07       0  4981.8     0.1       0  5120.0    0.05       0
Bank Sta=4975.7,4981.8
Exp/Cntr=0.3,0.1

Type RM Length L Ch R = 1,3697,518,518,518
BEGIN DESCRIPTION:
Caney Creek T 13 6.0
END DESCRIPTION:
XS GIS Cut Line= 3
      2788975.98      6781561.01      2788576.00      6781861.00
      2788403.16      6782537.60
#Sta/Elev= 30
  4505.1  439.41  4598.5  429.19  4618.6  426.71  4677.0  421.55  4705.1  420.01
  4712.4  418.60  4791.5  413.72  4855.1  411.55  4941.5  410.27  4947.8  410.90
  4968.6  410.90  4977.0  408.42  4983.2  405.03  4988.4  400.87  4989.5  400.37
  4994.6  400.87  4997.8  401.14  5002.0  407.96  5007.7  407.96  5009.4  408.62
  5015.4  410.95  5056.7  410.38  5098.0  411.96  5186.3  419.23  5294.1  424.43
  5349.7  424.44  5438.6  428.19  5630.4  434.03  5671.3  433.24  5703.4  431.36
#Mann=5,-1,0
  4505.1    0.05       0  4598.5    0.12       0  4988.4    0.07       0
  4994.6    0.12       0  5009.4    0.05       0
Bank Sta=4988.4,4994.6
Exp/Cntr=0.3,0.1

Type RM Length L Ch R = 1,3179,428,428,428
BEGIN DESCRIPTION:
Caney Creek T 13 5.0
END DESCRIPTION:
XS GIS Cut Line= 3
      2788026.01      6781211.01      2788226.00      6781611.00
      2788076.01      6782410.96
#Sta/Elev= 30
  4552.8  459.41  4611.5  449.59  4628.3  441.94  4642.2  438.70  4650.6  433.96
  4656.3  435.13  4673.0  429.44  4678.6  431.42  4717.7  418.26  4767.2  416.86
  4835.1  413.94  4851.9  410.57  4874.2  409.45  4977.6  407.98  4991.6  406.50
  4994.7  403.98  5006.8  399.53  5007.9  399.03  5013.5  399.53  5031.4  403.06
  5040.7  407.63  5050.9  408.99  5135.9  408.07  5223.8  409.13  5351.9  417.72
  5488.4  413.40  5572.3  416.41  5624.9  419.24  5730.0  428.58  5813.9  432.93
#Mann=7,-1,0
  4552.8     0.1       0  4656.3    0.12       0  4767.2    0.05       0
  4994.7    0.12       0  5006.8    0.07       0  5013.5    0.12       0
  5135.9    0.05       0
Bank Sta=5006.8,5013.5
Exp/Cntr=0.3,0.1