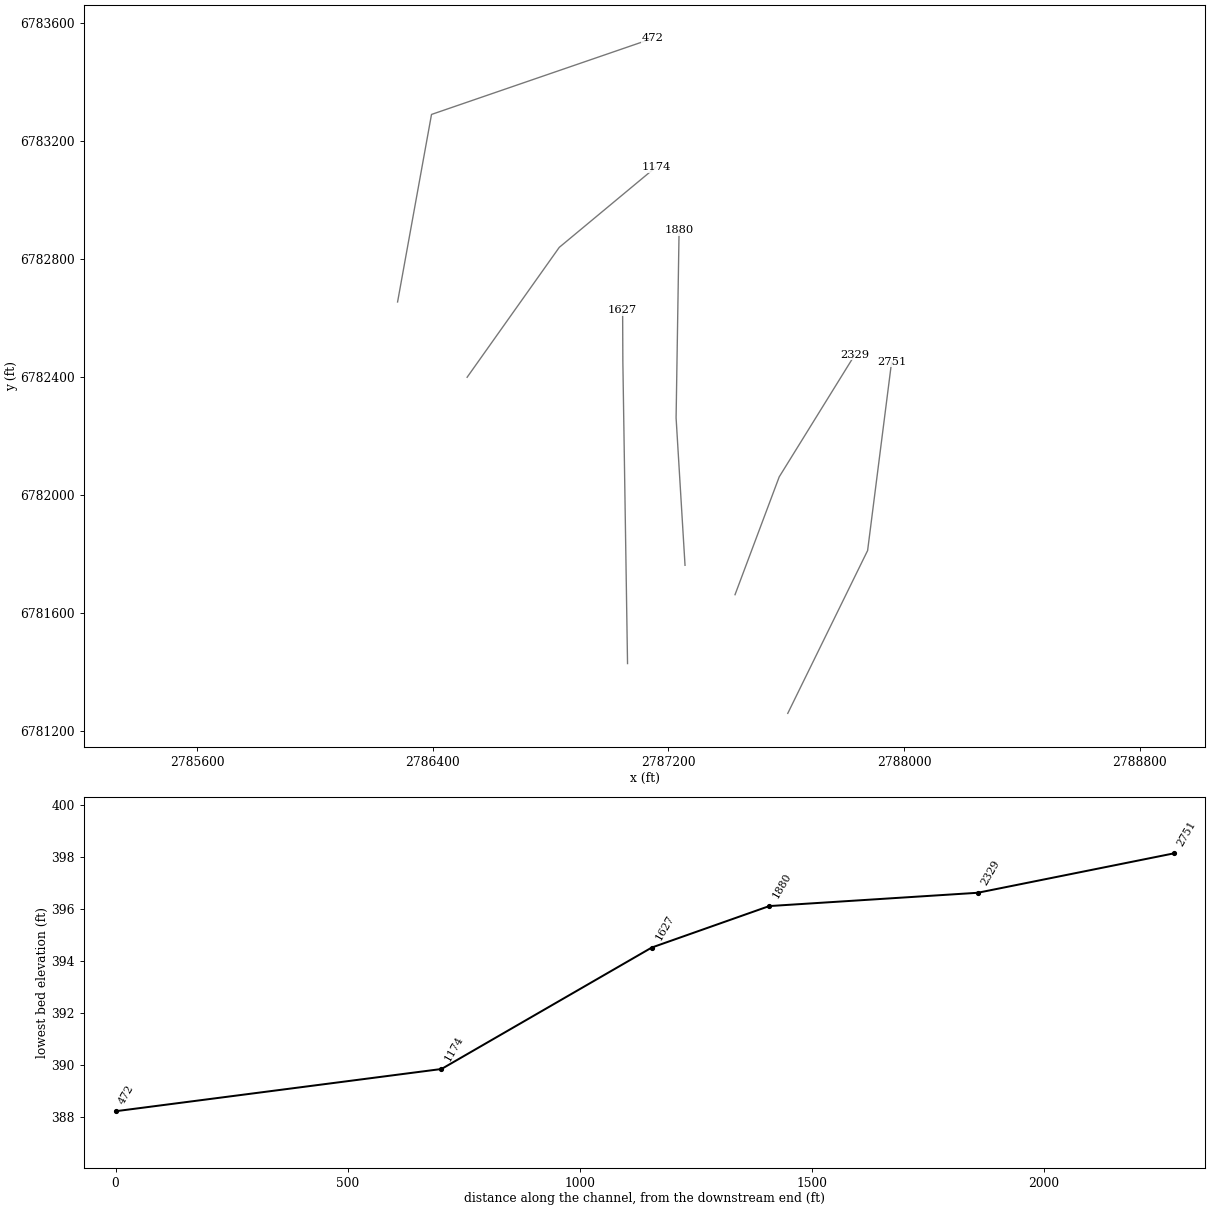
HEC-RAS study Caney Creek T 13.prj: Caney Creek T 13 Base Level Engineering

--- Caney Creek T 13.g01 (geometry) --- (continued)

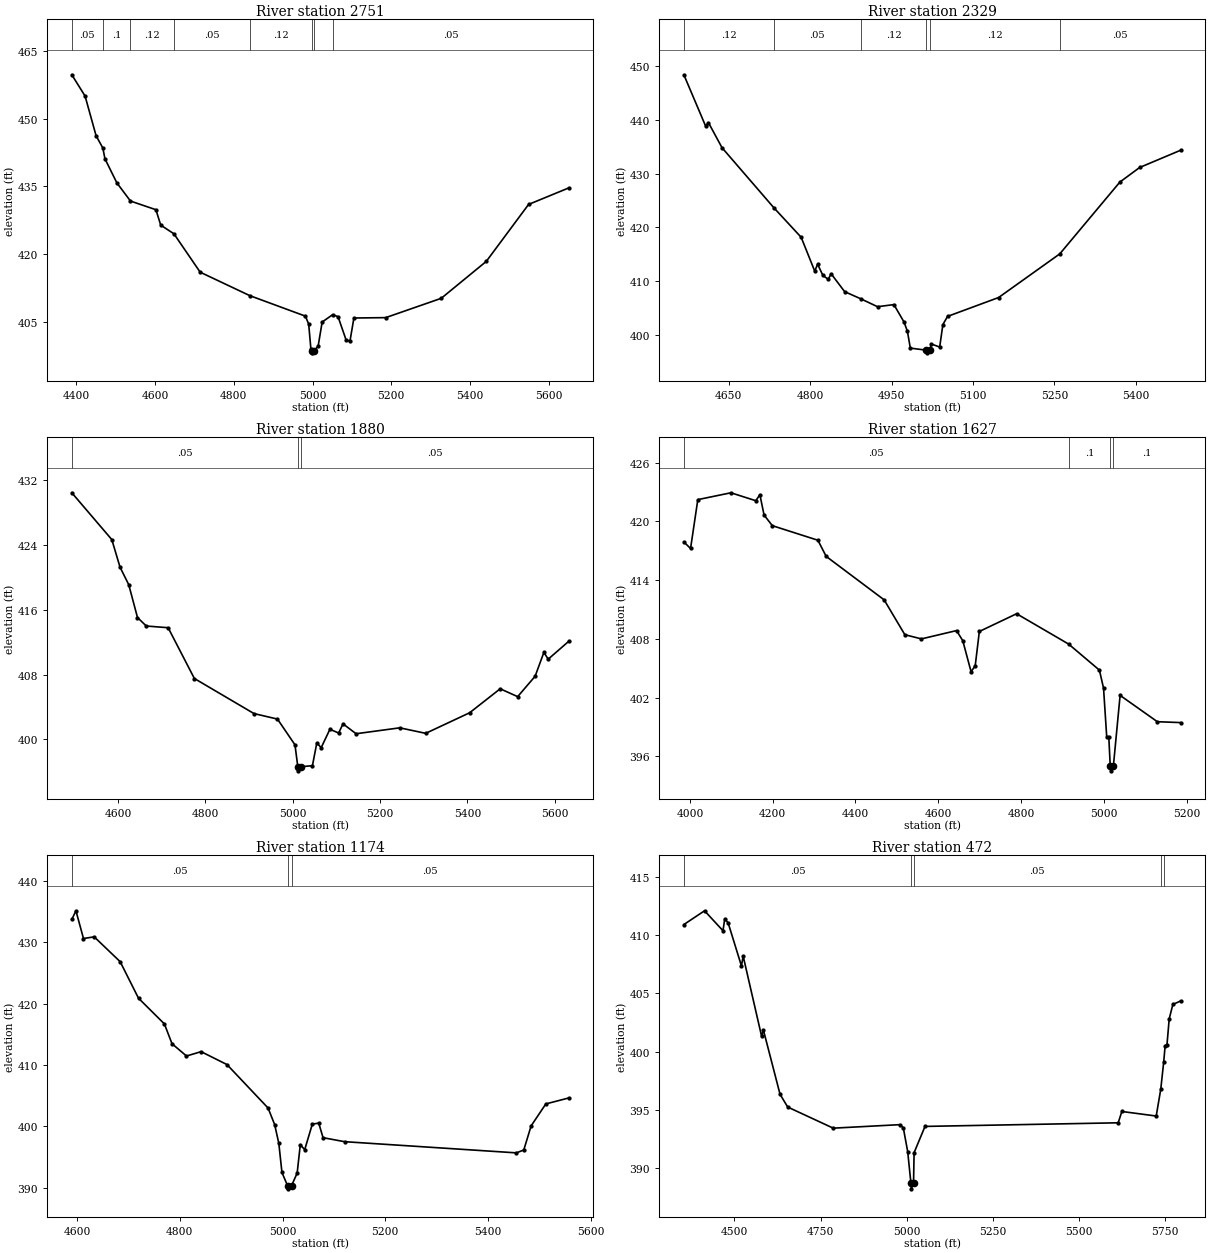
Type RM Length L Ch R = 1,2751,422,422,422
BEGIN DESCRIPTION:
Caney Creek T 13 4.0
END DESCRIPTION:
XS GIS Cut Line= 3
      2787604.96      6781258.28      2787876.00      6781811.00
      2787957.52      6782451.73
#Sta/Elev= 30
  4388.7  459.74  4422.4  455.02  4450.4  446.22  4467.4  443.53  4472.9  441.12
  4503.1  435.79  4537.7  431.76  4602.3  429.84  4614.5  426.43  4648.1  424.50
  4714.7  416.00  4840.8  410.80  4982.0  406.26  4990.3  404.48  4995.8  399.05
  4998.1  398.63  4999.2  398.13  5004.9  398.63  5014.4  399.66  5024.5  404.96
  5051.1  406.58  5064.8  406.15  5084.9  401.08  5095.0  400.66  5105.1  405.85
  5185.8  405.93  5326.9  410.21  5441.4  418.40  5548.7  431.01  5650.2  434.65
#Mann=8,-1,0
  4388.7    0.05       0  4467.4     0.1       0  4537.7    0.12       0
  4648.1    0.05       0  4840.8    0.12       0  4998.1    0.07       0
  5004.9    0.12       0  5051.1    0.05       0
Bank Sta=4998.1,5004.9
Exp/Cntr=0.3,0.1

Type RM Length L Ch R = 1,2329,449,449,449
BEGIN DESCRIPTION:
Caney Creek T 13 3.0
END DESCRIPTION:
XS GIS Cut Line= 3
      2787426.01      6781661.03      2787576.00      6782061.00
      2787833.15      6782476.14
#Sta/Elev= 30
  4567.2  448.45  4607.2  438.91  4612.6  439.52  4637.5  434.86  4733.1  423.66
  4783.4  418.16  4808.4  411.85  4813.7  413.14  4823.5  411.04  4833.3  410.33
  4838.6  411.36  4863.5  408.03  4893.3  406.69  4924.1  405.22  4954.3  405.61
  4973.0  402.36  4979.2  400.64  4984.6  397.50  5014.0  397.12  5015.1  396.62
  5020.8  397.12  5023.3  398.27  5038.7  397.70  5044.6  401.89  5053.2  403.41
  5147.3  406.93  5260.1  415.07  5370.8  428.45  5407.3  431.17  5482.7  434.38
#Mann=6,-1,0
  4567.2    0.12       0  4733.1    0.05       0  4893.3    0.12       0
  5014.0    0.07       0  5020.8    0.12       0  5260.1    0.05       0
Bank Sta=5014,5020.8
Exp/Cntr=0.3,0.1

Type RM Length L Ch R = 1,1880,253,253,253
BEGIN DESCRIPTION:
Caney Creek T 13 2.0
END DESCRIPTION:
XS GIS Cut Line= 3
      2787256.32      6781760.84      2787226.00      6782261.00
      2787236.14      6782897.45
#Sta/Elev= 30
  4494.2  430.44  4585.8  424.66  4604.6  421.26  4624.6  419.09  4644.6  415.04
  4664.7  413.99  4714.8  413.78  4774.9  407.51  4911.4  403.18  4965.2  402.50
  5005.3  399.32  5011.8  396.61  5012.9  396.11  5018.7  396.61  5045.3  396.75
  5055.3  399.56  5065.3  398.97  5085.3  401.24  5105.3  400.78  5115.3  401.91
  5145.3  400.69  5245.3  401.42  5304.7  400.74  5405.3  403.28  5475.3  406.24
  5515.3  405.27  5555.3  407.79  5575.3  410.73  5585.3  409.90  5631.8  412.08
#Mann=3,-1,0
  4494.2    0.05       0  5011.8    0.05       0  5018.7    0.05       0
Bank Sta=5011.8,5018.7
Exp/Cntr=0.3,0.1

Type RM Length L Ch R = 1,1627,453,453,453
BEGIN DESCRIPTION:
Mapping XS e4cd985c
END DESCRIPTION:
XS GIS Cut Line= 3
      2787061.21      6781427.29      2787045.33      6782451.27
      2787044.54      6782627.06
#Sta/Elev= 30
  3985.4  417.90  4001.6  417.24  4019.1  422.23  4099.1  422.93  4159.1  422.12
  4169.1  422.73  4179.1  420.66  4199.1  419.57  4309.2  418.08  4329.2  416.43
  4469.2  411.99  4519.2  408.43  4559.2  408.00  4644.1  408.85  4659.2  407.81
  4679.2  404.65  4689.2  405.25  4699.2  408.76  4789.2  410.57  4914.9  407.47
  4989.2  404.81  4999.2  402.97  5006.9  397.97  5011.9  397.97  5015.4  395.02
  5016.6  394.52  5023.0  395.02  5039.2  402.23  5129.2  399.54  5185.3  399.45
#Mann=4,-1,0
  3985.4    0.05       0  4914.9     0.1       0  5015.4    0.07       0
  5023.0     0.1       0
Bank Sta=5015.4,5023
Exp/Cntr=0.3,0.1

Type RM Length L Ch R = 1,1174,702,702,702
BEGIN DESCRIPTION:
Mapping XS 12bf0401
END DESCRIPTION:
XS GIS Cut Line= 3
      2786516.78      6782398.96      2786829.49      6782839.83
      2787157.43      6783112.19
#Sta/Elev= 30
  4589.9  433.67  4597.9  435.08  4612.6  430.57  4633.5  430.84  4684.0  426.80
  4719.7  420.86  4770.1  416.68  4784.9  413.46  4813.1  411.46  4841.5  412.17
  4891.9  410.07  4971.9  403.00  4984.7  400.31  4992.8  397.26  4998.9  392.52
  5009.9  390.36  5011.1  389.86  5017.5  390.36  5028.5  392.42  5034.6  397.03
  5043.2  396.23  5058.0  400.38  5070.5  400.55  5078.9  398.18  5120.7  397.53
  5455.2  395.71  5469.6  396.18  5483.9  400.10  5512.5  403.67  5556.7  404.63
#Mann=3,-1,0
  4589.9    0.05       0  5009.9    0.04       0  5017.5    0.05       0
Bank Sta=5009.9,5017.5
Exp/Cntr=0.3,0.1

Type RM Length L Ch R = 1,472,0,0,0
BEGIN DESCRIPTION:
Caney Creek T 13 1.0
END DESCRIPTION:
XS GIS Cut Line= 3
      2786280.74      6782654.51      2786395.93      6783290.97
      2787147.17      6783549.25
#Sta/Elev= 30
  4353.2  410.89  4413.2  412.07  4466.7  410.36  4471.8  411.38  4481.7  411.03
  4520.2  407.35  4525.3  408.18  4578.8  401.31  4583.9  401.86  4632.3  396.34
  4654.5  395.25  4786.6  393.44  4979.7  393.74  4989.9  393.47  5002.7  391.42
  5011.9  388.74  5013.1  388.24  5019.6  388.74  5021.2  391.34  5052.9  393.59
  5613.4  393.90  5624.0  394.87  5723.7  394.48  5736.9  396.78  5745.4  399.10
  5749.6  400.50  5754.9  400.57  5761.4  402.81  5772.0  404.04  5794.4  404.34
#Mann=5,-1,0
  4353.2    0.05       0  5011.9    0.04       0  5019.6    0.05       0
  5736.9    0.12       0  5745.4    0.05       0
Bank Sta=5011.9,5019.6
Exp/Cntr=0.3,0.1

Chan Stop Cuts=-1