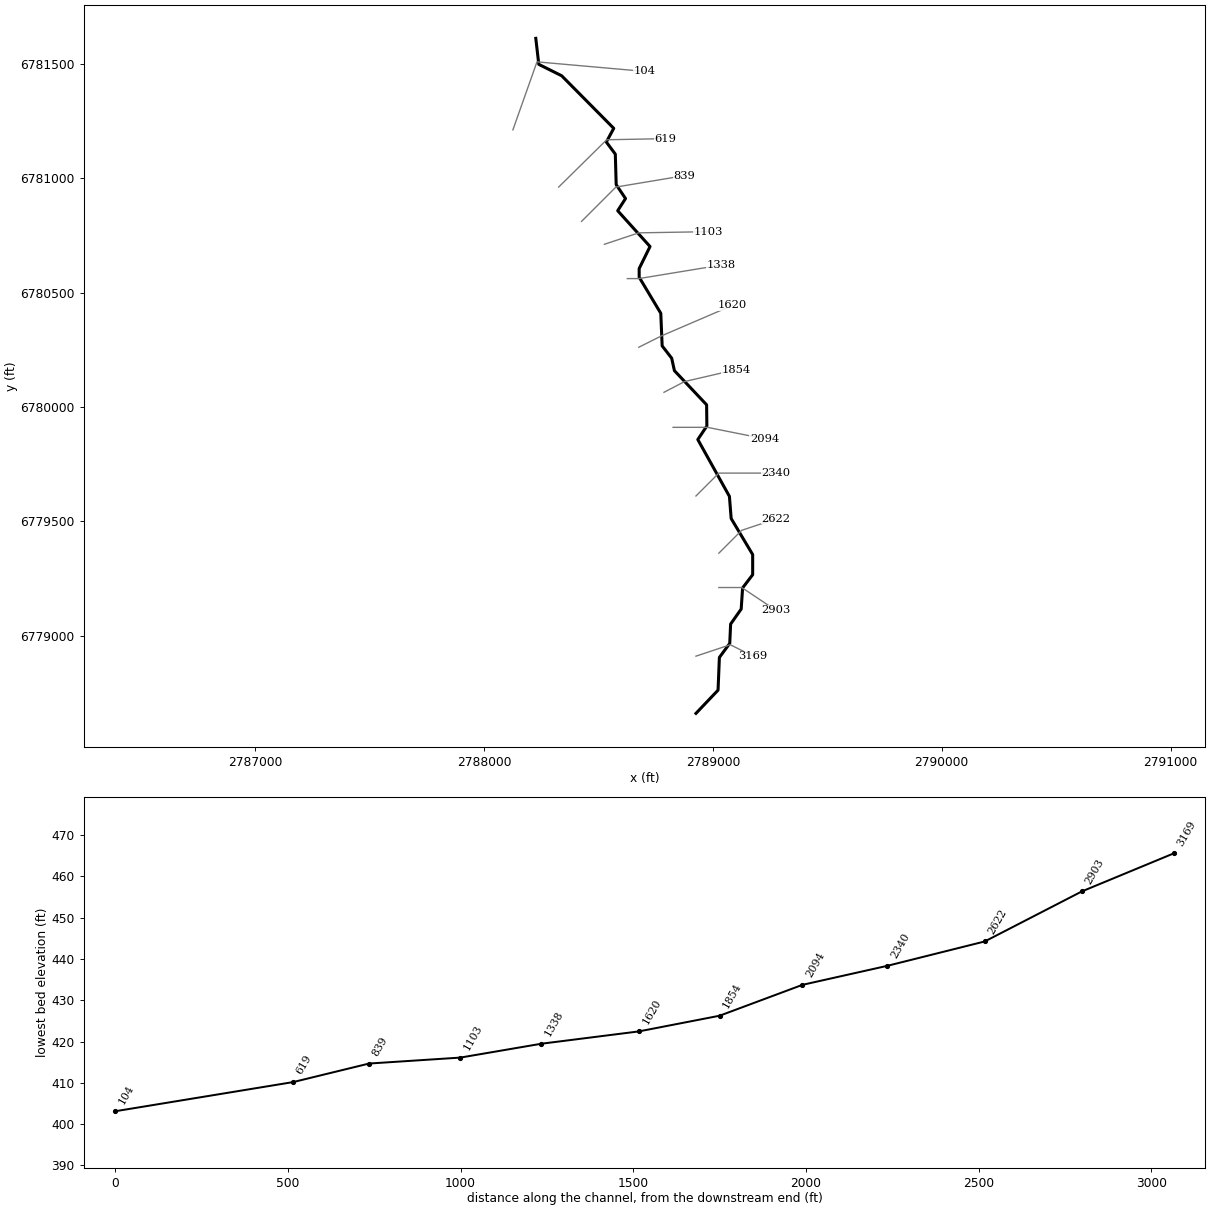
--- Caney Creek T 13 A.prj (project) ---

Proj Title=Caney Creek T 13 A Base Level Engineering
Current Plan=p01
Default Exp/Contr=0.3,0.1
English Units
Geom File=g01
Flow File=f01
Plan File=p01
BEGIN DESCRIPTION:
Caney Creek T 13 A
END DESCRIPTION:

--- Caney Creek T 13 A.p01 (plan) ---

Plan Title=Multiple Run
Short Identifier=Multiple
Geom File=g01
Flow File=f01
Subcritical Flow
K Sum by GR= 0
Std Step Tol= 0.01
Critical Tol= 0.01
Num of Std Step Trials= 20
Max Error Tol= 0.3
Flow Tol Ratio= 0.001
Split Flow NTrial= 30
Split Flow Tol= 0.02
Split Flow Ratio= 0.02
Log Output Level= 0
Friction Slope Method= 1
Unsteady Friction Slope Method= 2
Unsteady Bridges Friction Slope Method= 1
Parabolic Critical Depth
Global Vel Dist=  1 , 1 , 1
Global Log Level= 0
CheckData=True
Encroach Param= -1, 0, 0, 0
BEGIN DESCRIPTION:
Multiple Run
END DESCRIPTION:

--- Caney Creek T 13 A.f01 (steady flow) ---

Flow Title=Multiple
Number of Profiles=7
Profile Names=10-year,25-year,50-year,1pct_min,100-year,1pct_plu,500-year
River Rch & RM= Caney Creek T 13,Reach-1,3169
     244     316     372     220     438     875     606
Boundary for River Rch & Prof#=Caney Creek T 13,Reach-1,1
Up Type=0
Dn Type=3
Dn Slope=0.005
Boundary for River Rch & Prof#=Caney Creek T 13,Reach-1,2
Up Type=0
Dn Type=3
Dn Slope=0.005
Boundary for River Rch & Prof#=Caney Creek T 13,Reach-1,3
Up Type=0
Dn Type=3
Dn Slope=0.005
Boundary for River Rch & Prof#=Caney Creek T 13,Reach-1,4
Up Type=0
Dn Type=3
Dn Slope=0.005
Boundary for River Rch & Prof#=Caney Creek T 13,Reach-1,5
Up Type=0
Dn Type=3
Dn Slope=0.005
Boundary for River Rch & Prof#=Caney Creek T 13,Reach-1,6
Up Type=0
Dn Type=3
Dn Slope=0.005
Boundary for River Rch & Prof#=Caney Creek T 13,Reach-1,7
Up Type=0
Dn Type=3
Dn Slope=0.005

--- Caney Creek T 13 A.g01 (geometry) ---

Geom Title=Existing Conditions

River Reach=Caney Creek T 13,Reach-1
Reach XY= 30
      2788926.00      6778661.00      2789022.51      6778762.45
      2789028.39      6778905.47      2789073.64      6778966.98
      2789077.49      6779051.29      2789123.65      6779116.97
      2789129.86      6779209.40      2789173.83      6779266.97
      2789173.86      6779355.03      2789079.83      6779512.58
      2789072.17      6779609.42      2788934.05      6779857.68
      2788973.64      6779916.90      2788972.54      6780009.50
      2788831.83      6780158.70      2788819.86      6780213.17
      2788778.25      6780266.93      2788772.24      6780409.44
      2788677.80      6780567.11      2788677.84      6780604.89
      2788725.24      6780701.22      2788583.99      6780857.66
      2788618.19      6780910.90      2788577.39      6780971.44
      2788573.54      6781105.14      2788534.29      6781157.79
      2788566.70      6781217.67      2788339.20      6781447.36
      2788239.19      6781497.28      2788226.00      6781611.00

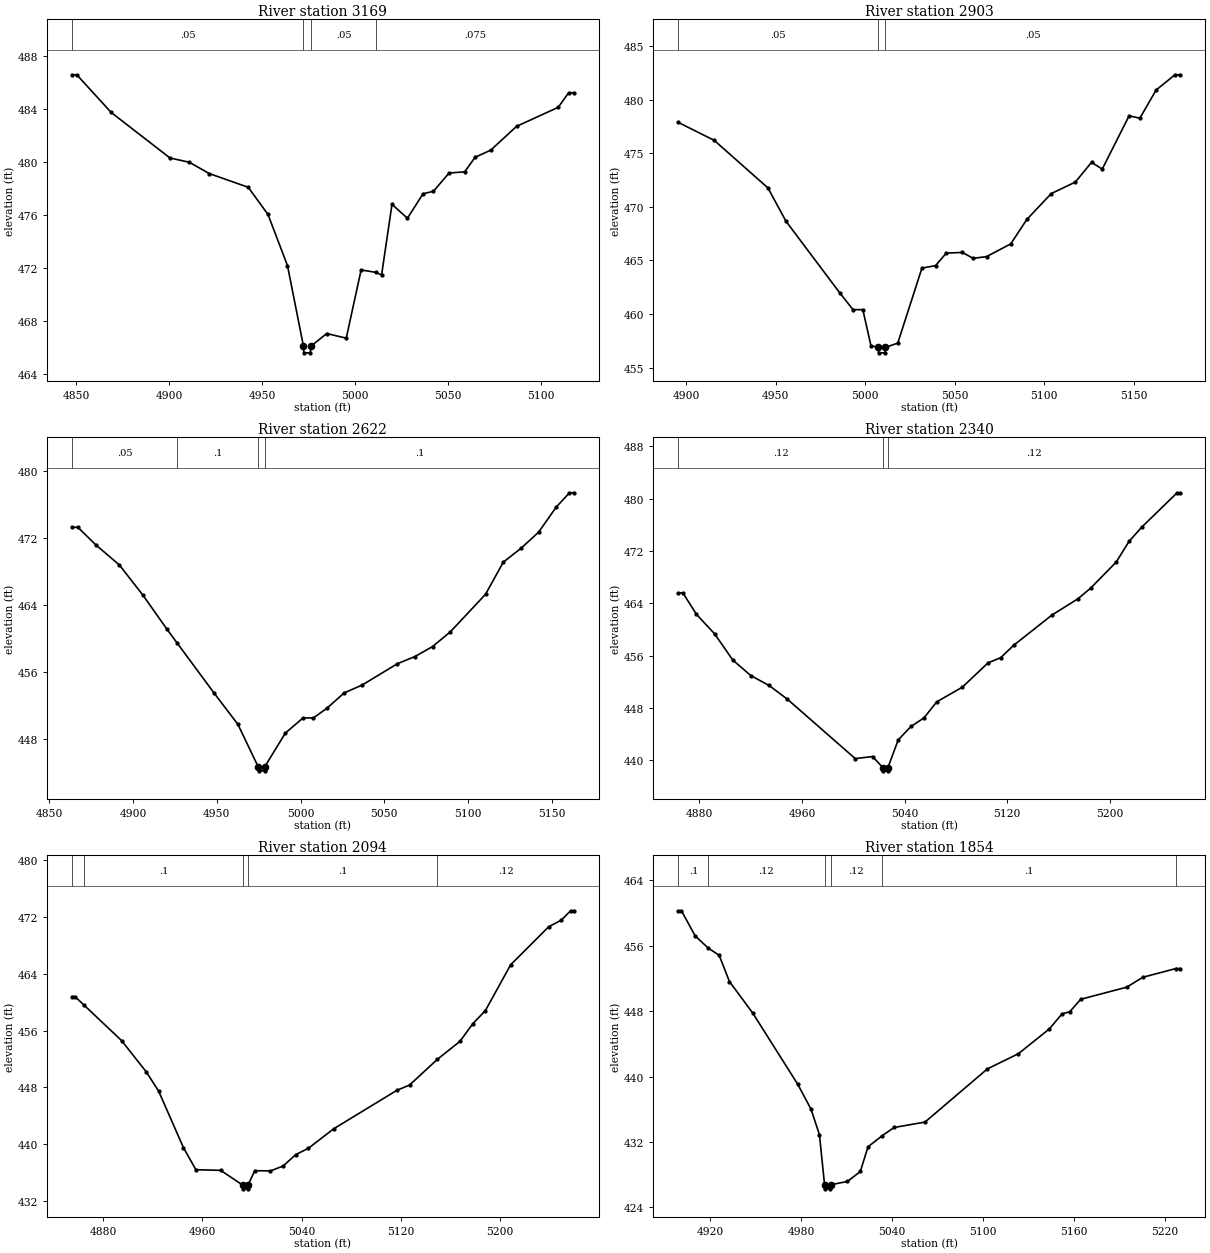
Type RM Length L Ch R = 1,3169,266,266,266
BEGIN DESCRIPTION:
Caney Creek T 13 A 12.0
END DESCRIPTION:
XS GIS Cut Line= 3
      2788926.02      6778911.01      2789076.00      6778961.00
      2789176.01      6778911.00
#Sta/Elev= 30
  4847.8  486.61  4850.4  486.61  4868.9  483.76  4900.5  480.32  4911.0  479.99
  4921.6  479.14  4942.6  478.10  4953.2  476.05  4963.7  472.18  4972.3  466.08
  4972.5  465.58  4976.0  465.58  4976.3  466.08  4984.8  467.04  4995.3  466.69
  5003.3  471.85  5011.5  471.66  5014.3  471.46  5019.9  476.81  5028.2  475.76
  5036.6  477.61  5042.2  477.80  5050.6  479.18  5059.0  479.27  5064.6  480.37
  5073.0  480.91  5086.9  482.71  5109.3  484.15  5114.9  485.25  5117.7  485.25
#Mann=4,-1,0
  4847.8    0.05       0  4972.3    0.03       0  4976.3    0.05       0
  5011.5   0.075       0
Bank Sta=4972.3,4976.3
Exp/Cntr=0.3,0.1

Type RM Length L Ch R = 1,2903,281,281,281
BEGIN DESCRIPTION:
Caney Creek T 13 A 11.0
END DESCRIPTION:
XS GIS Cut Line= 3
      2789026.01      6779211.00      2789126.00      6779211.00
      2789276.02      6779110.98
#Sta/Elev= 30
  4895.7  477.87  4915.7  476.20  4945.7  471.76  4955.7  468.67  4985.7  461.99
  4993.2  460.40  4998.7  460.40  5003.2  457.05  5007.2  456.87  5007.5  456.37
  5011.0  456.37  5011.2  456.87  5018.2  457.28  5031.7  464.28  5039.3  464.51
  5045.3  465.68  5054.3  465.74  5060.3  465.19  5067.8  465.35  5081.3  466.54
  5090.3  468.82  5103.9  471.23  5117.4  472.31  5126.4  474.15  5132.4  473.52
  5147.4  478.49  5153.4  478.27  5162.5  480.90  5173.0  482.32  5176.0  482.32
#Mann=3,-1,0
  4895.7    0.05       0  5007.2    0.03       0  5011.2    0.05       0
Bank Sta=5007.2,5011.2
Exp/Cntr=0.3,0.1

Type RM Length L Ch R = 1,2622,282,282,282
BEGIN DESCRIPTION:
Caney Creek T 13 A 10.0
END DESCRIPTION:
XS GIS Cut Line= 3
      2789025.99      6779360.99      2789126.00      6779461.00
      2789275.96      6779510.99
#Sta/Elev= 30
  4863.6  473.30  4867.1  473.30  4877.8  471.21  4891.9  468.80  4906.0  465.19
  4920.2  461.17  4926.5  459.46  4948.5  453.51  4962.6  449.81  4974.7  444.76
  4975.0  444.26  4978.5  444.26  4978.7  444.76  4990.9  448.75  5001.5  450.57
  5007.7  450.57  5015.6  451.70  5026.1  453.56  5036.7  454.48  5057.7  457.02
  5068.3  457.89  5078.8  459.08  5089.4  460.83  5110.4  465.31  5121.0  469.14
  5131.5  470.78  5142.1  472.72  5152.6  475.71  5160.5  477.41  5163.1  477.41
#Mann=4,-1,0
  4863.6    0.05       0  4926.5     0.1       0  4974.7    0.07       0
  4978.7     0.1       0
Bank Sta=4974.7,4978.7
Exp/Cntr=0.3,0.1

Type RM Length L Ch R = 1,2340,246,246,246
BEGIN DESCRIPTION:
Caney Creek T 13 A 9.0
END DESCRIPTION:
XS GIS Cut Line= 3
      2788926.01      6779611.01      2789026.00      6779711.00
      2789276.00      6779711.00
#Sta/Elev= 30
  4863.6  465.58  4867.1  465.58  4877.7  462.30  4891.9  459.30  4906.0  455.31
  4920.1  452.93  4934.3  451.42  4948.4  449.35  5001.5  440.23  5015.0  440.55
  5023.0  438.86  5023.3  438.36  5026.8  438.36  5027.0  438.86  5035.0  443.09
  5045.0  445.16  5055.0  446.44  5065.0  448.91  5085.0  451.16  5105.0  454.87
  5115.0  455.68  5125.0  457.56  5155.0  462.21  5175.0  464.66  5185.0  466.30
  5205.0  470.30  5215.0  473.46  5225.0  475.66  5252.5  480.90  5255.0  480.90
#Mann=3,-1,0
  4863.6    0.12       0  5023.0    0.07       0  5027.0    0.12       0
Bank Sta=5023,5027
Exp/Cntr=0.3,0.1

Type RM Length L Ch R = 1,2094,240,240,240
BEGIN DESCRIPTION:
Caney Creek T 13 A 8.0
END DESCRIPTION:
XS GIS Cut Line= 3
      2788825.99      6779911.00      2788976.00      6779911.00
      2789226.04      6779860.99
#Sta/Elev= 30
  4854.7  460.77  4857.2  460.77  4864.5  459.57  4894.7  454.60  4914.7  450.19
  4924.7  447.47  4944.7  439.53  4954.7  436.44  4974.7  436.35  4992.7  434.25
  4993.0  433.75  4996.5  433.75  4996.7  434.25  5002.2  436.30  5014.9  436.27
  5025.1  436.96  5035.3  438.56  5045.5  439.45  5065.9  442.19  5116.9  447.60
  5127.1  448.34  5149.6  451.96  5167.9  454.50  5178.1  456.96  5188.3  458.80
  5208.7  465.25  5239.3  470.58  5249.5  471.52  5257.1  472.84  5259.7  472.84
#Mann=5,-1,0
  4854.7    0.12       0  4864.5     0.1       0  4992.7    0.07       0
  4996.7     0.1       0  5149.6    0.12       0
Bank Sta=4992.7,4996.7
Exp/Cntr=0.3,0.1

Type RM Length L Ch R = 1,1854,234,234,234
BEGIN DESCRIPTION:
Caney Creek T 13 A 7.0
END DESCRIPTION:
XS GIS Cut Line= 3
      2788786.17      6780064.09      2788876.00      6780111.00
      2789100.12      6780162.93
#Sta/Elev= 30
  4898.9  460.26  4900.9  460.26  4910.0  457.18  4918.6  455.70  4925.8  454.82
  4932.6  451.61  4947.9  447.78  4977.7  439.05  4986.4  436.03  4992.0  432.90
  4995.4  426.77  4995.7  426.27  4999.2  426.27  4999.4  426.77  5010.5  427.17
  5019.0  428.39  5024.1  431.41  5033.3  432.74  5041.3  433.77  5061.7  434.43
  5102.9  440.93  5123.4  442.79  5143.9  445.83  5152.2  447.66  5157.3  447.91
  5164.5  449.44  5194.9  450.92  5205.5  452.13  5227.4  453.20  5230.3  453.20
#Mann=6,-1,0
  4898.9     0.1       0  4918.6    0.12       0  4995.4    0.07       0
  4999.4    0.12       0  5033.3     0.1       0  5227.4    0.12       0
Bank Sta=4995.4,4999.4
Exp/Cntr=0.3,0.1

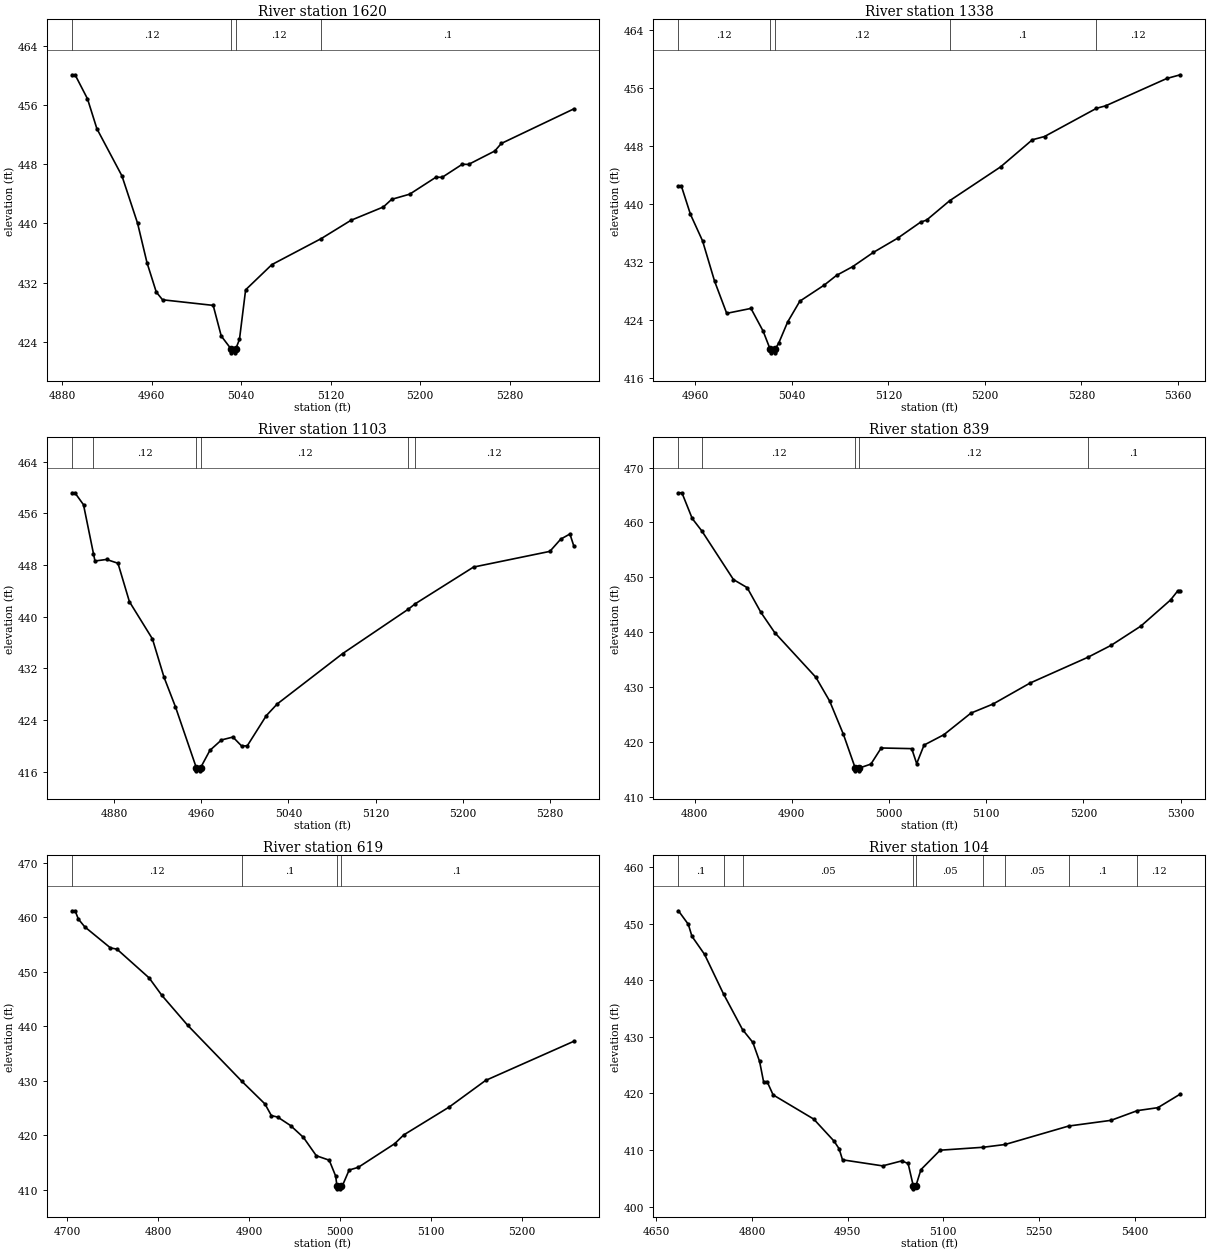
Type RM Length L Ch R = 1,1620,282,282,282
BEGIN DESCRIPTION:
Caney Creek T 13 A 6.0
END DESCRIPTION:
XS GIS Cut Line= 3
      2788676.03      6780261.01      2788776.00      6780311.00
      2789085.67      6780444.01
#Sta/Elev= 30
  4888.6  460.15  4891.4  460.15  4902.5  456.89  4910.9  452.84  4933.3  446.45
  4947.3  440.02  4955.7  434.69  4964.0  430.71  4969.6  429.66  5014.9  428.90
  5022.1  424.75  5031.0  422.97  5031.2  422.47  5034.7  422.47  5035.0  422.97
  5038.4  424.30  5043.9  431.01  5067.4  434.43  5111.6  437.96  5138.1  440.43
  5167.1  442.24  5174.5  443.27  5190.6  443.97  5214.2  446.28  5219.6  446.25
  5237.7  448.03  5243.2  448.00  5266.7  449.82  5272.5  450.84  5337.4  455.53
#Mann=4,-1,0
  4888.6    0.12       0  5031.0    0.07       0  5035.0    0.12       0
  5111.6     0.1       0
Bank Sta=5031,5035
Exp/Cntr=0.3,0.1

Type RM Length L Ch R = 1,1338,235,235,235
BEGIN DESCRIPTION:
Caney Creek T 13 A 5.0
END DESCRIPTION:
XS GIS Cut Line= 3
      2788626.05      6780561.00      2788676.00      6780561.00
      2789037.01      6780620.28
#Sta/Elev= 30
  4946.1  442.48  4948.6  442.48  4956.1  438.59  4966.1  434.94  4976.1  429.36
  4986.1  424.94  5006.2  425.62  5016.3  422.48  5022.1  419.99  5022.4  419.49
  5025.9  419.49  5026.1  419.99  5029.2  420.83  5036.6  423.75  5046.7  426.62
  5067.0  428.85  5077.1  430.18  5090.5  431.39  5107.5  433.34  5127.8  435.32
  5146.7  437.52  5151.7  437.81  5170.8  440.48  5213.0  445.15  5239.3  448.89
  5249.4  449.34  5292.4  453.23  5300.1  453.58  5350.7  457.35  5361.9  457.86
#Mann=5,-1,0
  4946.1    0.12       0  5022.1    0.07       0  5026.1    0.12       0
  5170.8     0.1       0  5292.4    0.12       0
Bank Sta=5022.1,5026.1
Exp/Cntr=0.3,0.1

Type RM Length L Ch R = 1,1103,264,264,264
BEGIN DESCRIPTION:
Caney Creek T 13 A 4.0
END DESCRIPTION:
XS GIS Cut Line= 3
      2788525.97      6780710.99      2788676.00      6780761.00
      2788978.01      6780766.00
#Sta/Elev= 30
  4841.5  459.17  4844.2  459.17  4852.1  457.32  4861.2  449.77  4862.6  448.61
  4873.2  448.85  4883.7  448.26  4894.2  442.31  4915.3  436.55  4925.9  430.63
  4936.4  426.04  4955.5  416.63  4955.7  416.13  4959.2  416.13  4959.5  416.63
  4968.0  419.30  4978.6  420.91  4989.1  421.36  4997.0  419.99  5002.2  419.99
  5019.7  424.67  5029.7  426.48  5089.7  434.28  5150.0  441.16  5156.0  441.96
  5209.7  447.67  5279.7  450.10  5289.7  452.00  5298.1  452.79  5301.7  450.91
#Mann=6,-1,0
  4841.5    0.05       0  4861.2    0.12       0  4955.5    0.07       0
  4959.5    0.12       0  5150.0     0.1       0  5156.0    0.12       0
Bank Sta=4955.5,4959.5
Exp/Cntr=0.3,0.1

Type RM Length L Ch R = 1,839,220,220,220
BEGIN DESCRIPTION:
Caney Creek T 13 A 3.0
END DESCRIPTION:
XS GIS Cut Line= 3
      2788425.98      6780810.98      2788576.00      6780961.00
      2788876.01      6781011.00
#Sta/Elev= 30
  4783.4  465.41  4787.0  465.41  4797.6  460.72  4807.6  458.42  4840.0  449.58
  4854.1  448.11  4868.3  443.58  4882.4  439.92  4924.8  431.75  4939.0  427.41
  4953.1  421.36  4965.3  415.19  4965.5  414.69  4969.0  414.69  4969.3  415.19
  4981.4  415.92  4992.0  418.86  5023.4  418.74  5028.5  416.01  5036.1  419.39
  5056.4  421.27  5084.3  425.22  5107.1  426.88  5145.1  430.70  5204.8  435.42
  5228.7  437.60  5259.1  441.09  5289.6  445.85  5297.2  447.55  5299.7  447.55
#Mann=5,-1,0
  4783.4    0.05       0  4807.6    0.12       0  4965.3    0.07       0
  4969.3    0.12       0  5204.8     0.1       0
Bank Sta=4965.3,4969.3
Exp/Cntr=0.3,0.1

Type RM Length L Ch R = 1,619,515,515,515
BEGIN DESCRIPTION:
Caney Creek T 13 A 2.0
END DESCRIPTION:
XS GIS Cut Line= 3
      2788326.03      6780961.03      2788535.79      6781167.74
      2788792.94      6781172.66
#Sta/Elev= 30
  4705.5  461.17  4709.0  461.17  4712.5  459.66  4719.6  458.22  4747.8  454.37
  4755.0  454.13  4790.3  448.87  4804.4  445.65  4832.7  440.18  4892.4  429.89
  4917.6  425.77  4924.7  423.63  4931.7  423.35  4945.8  421.80  4960.0  419.62
  4974.1  416.27  4988.3  415.45  4995.4  412.53  4996.8  410.70  4997.0  410.20
  5000.5  410.20  5000.8  410.70  5002.6  410.70  5010.2  413.65  5020.2  414.14
  5060.2  418.47  5070.2  420.08  5120.2  425.20  5160.2  430.07  5257.2  437.25
#Mann=4,-1,0
  4705.5    0.12       0  4892.4     0.1       0  4996.8    0.07       0
  5000.8     0.1       0
Bank Sta=4996.8,5000.8
Exp/Cntr=0.3,0.1

Type RM Length L Ch R = 1,104,0,0,0
BEGIN DESCRIPTION:
Caney Creek T 13 A 1.0
END DESCRIPTION:
XS GIS Cut Line= 3
      2788126.00      6781210.99      2788231.23      6781508.22
      2788701.09      6781466.55
#Sta/Elev= 30
  4684.7  452.30  4700.2  449.91  4705.9  447.79  4725.7  444.59  4755.4  437.60
  4785.2  431.30  4801.4  429.03  4812.0  425.66  4818.4  421.98  4823.7  422.11
  4833.2  419.75  4896.9  415.47  4928.7  411.58  4936.7  410.22  4942.0  408.27
  5004.9  407.20  5034.9  408.08  5044.9  407.62  5053.0  403.64  5053.2  403.14
  5057.0  403.64  5065.0  406.54  5095.1  409.97  5162.5  410.49  5197.0  410.98
  5296.5  414.24  5363.0  415.25  5404.4  416.97  5436.5  417.49  5471.7  419.90
#Mann=9,-1,0
  4684.7     0.1       0  4755.4    0.12       0  4785.2    0.05       0
  5053.0    0.05       0  5057.0    0.05       0  5162.5    0.12       0
  5197.0    0.05       0  5296.5     0.1       0  5404.4    0.12       0
Bank Sta=5053,5057
Exp/Cntr=0.3,0.1

Chan Stop Cuts=-1