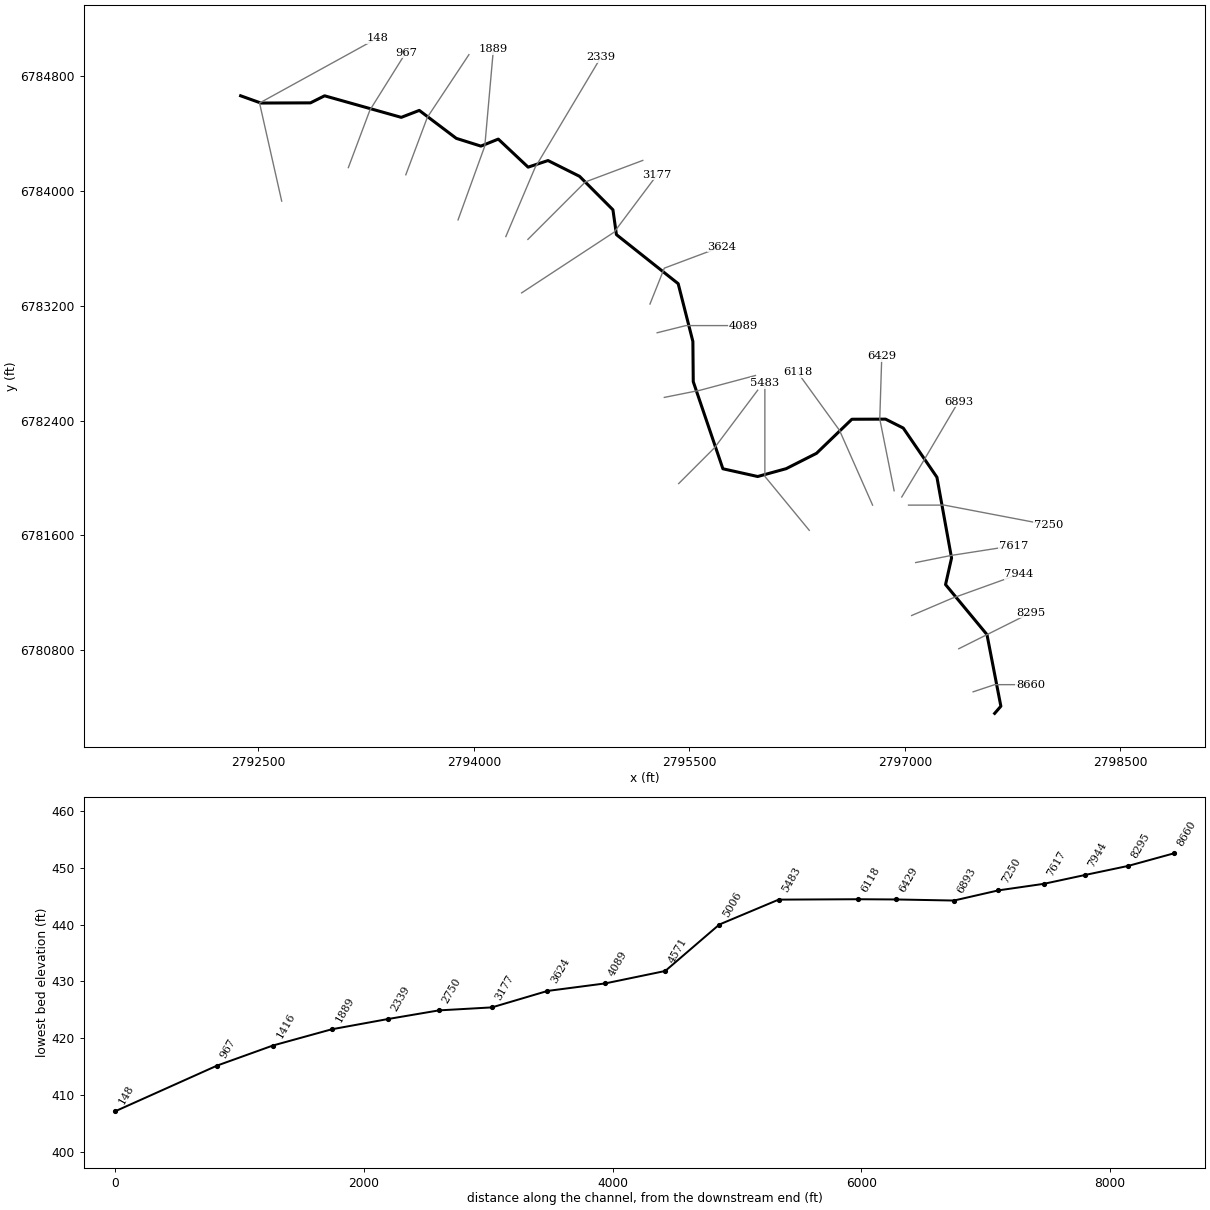
--- Caney Creek T 14.prj (project) ---

Proj Title=Caney Creek T 14 Base Level Engineering
Current Plan=p01
Default Exp/Contr=0.3,0.1
English Units
Geom File=g01
Flow File=f01
Plan File=p01
BEGIN DESCRIPTION:
Caney Creek T 14
END DESCRIPTION:

--- Caney Creek T 14.p01 (plan) ---

Plan Title=Multiple Run
Short Identifier=Multiple
Geom File=g01
Flow File=f01
Subcritical Flow
K Sum by GR= 0
Std Step Tol= 0.01
Critical Tol= 0.01
Num of Std Step Trials= 20
Max Error Tol= 0.3
Flow Tol Ratio= 0.001
Split Flow NTrial= 30
Split Flow Tol= 0.02
Split Flow Ratio= 0.02
Log Output Level= 0
Friction Slope Method= 1
Unsteady Friction Slope Method= 2
Unsteady Bridges Friction Slope Method= 1
Parabolic Critical Depth
Global Vel Dist=  1 , 1 , 1
Global Log Level= 0
CheckData=True
Encroach Param= -1, 0, 0, 0
BEGIN DESCRIPTION:
Multiple Run
END DESCRIPTION:

--- Caney Creek T 14.f01 (steady flow) ---

Flow Title=Multiple
Number of Profiles=7
Profile Names=10-year,25-year,50-year,1pct_min,100-year,1pct_plu,500-year
River Rch & RM= Caney Creek T 14,Reach-1,8660
     771    1070    1323     814    1625    3242    2453
River Rch & RM= Caney Creek T 14,Reach-1,6429
     795    1106    1368     842    1679    3350    2536
River Rch & RM= Caney Creek T 14,Reach-1,5483
     964    1352    1682    1040    2076    4142    3169
River Rch & RM= Caney Creek T 14,Reach-1,3177
    1120    1572    1955    1208    2410    4808    3670
Boundary for River Rch & Prof#=Caney Creek T 14,Reach-1,1
Up Type=0
Dn Type=3
Dn Slope=0.005
Boundary for River Rch & Prof#=Caney Creek T 14,Reach-1,2
Up Type=0
Dn Type=3
Dn Slope=0.005
Boundary for River Rch & Prof#=Caney Creek T 14,Reach-1,3
Up Type=0
Dn Type=3
Dn Slope=0.005
Boundary for River Rch & Prof#=Caney Creek T 14,Reach-1,4
Up Type=0
Dn Type=3
Dn Slope=0.005
Boundary for River Rch & Prof#=Caney Creek T 14,Reach-1,5
Up Type=0
Dn Type=3
Dn Slope=0.005
Boundary for River Rch & Prof#=Caney Creek T 14,Reach-1,6
Up Type=0
Dn Type=3
Dn Slope=0.005
Boundary for River Rch & Prof#=Caney Creek T 14,Reach-1,7
Up Type=0
Dn Type=3
Dn Slope=0.005

--- Caney Creek T 14.g01 (geometry) ---

Geom Title=Existing Conditions

River Reach=Caney Creek T 14,Reach-1
Reach XY= 30
      2797626.00      6780361.00      2797669.09      6780410.86
      2797572.39      6780909.50      2797284.04      6781257.68
      2797325.81      6781442.72      2797223.93      6782005.14
      2796989.57      6782347.53      2796866.35      6782409.64
      2796631.85      6782408.94      2796385.68      6782171.76
      2796174.42      6782064.83      2795976.00      6782010.18
      2795733.68      6782064.10      2795527.38      6782670.66
      2795524.78      6782950.50      2795422.43      6783352.85
      2794992.43      6783694.24      2794968.18      6783867.19
      2794735.68      6784100.24      2794516.16      6784210.09
      2794377.63      6784164.13      2794169.97      6784359.38
      2794048.81      6784310.63      2793877.50      6784364.61
      2793619.89      6784559.20      2793494.43      6784510.83
      2792960.61      6784660.91      2792862.09      6784611.70
      2792516.72      6784610.54      2792376.00      6784661.00

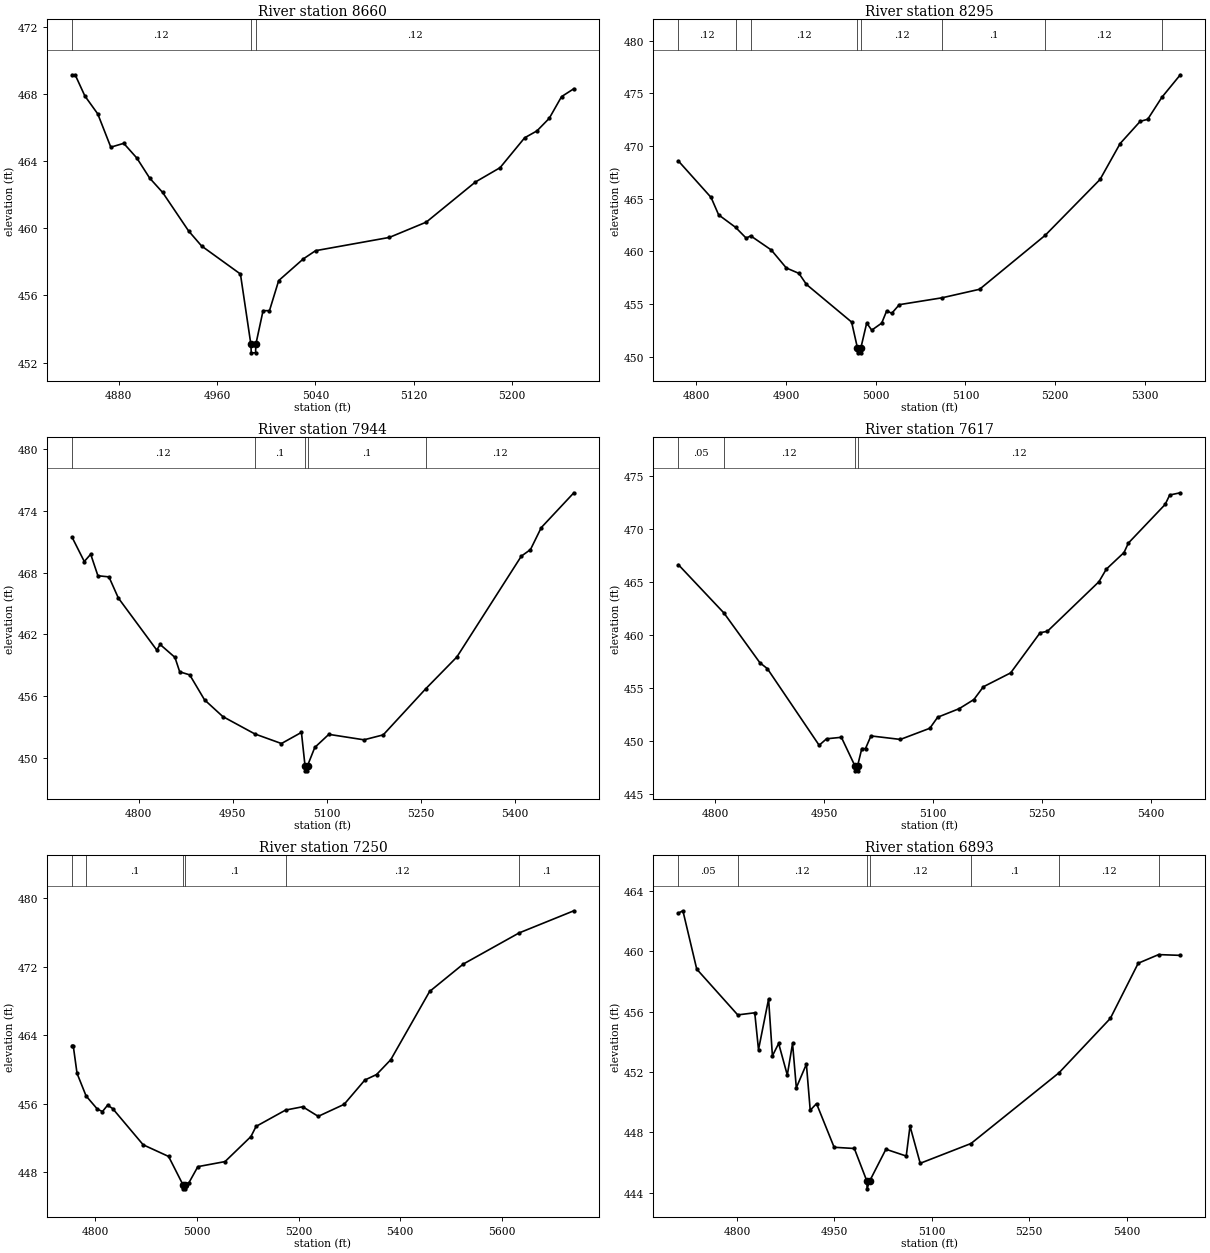
Type RM Length L Ch R = 1,8660,365,365,365
BEGIN DESCRIPTION:
Caney Creek T 14 20.0
END DESCRIPTION:
XS GIS Cut Line= 3
      2797476.04      6780511.01      2797626.00      6780561.00
      2797876.02      6780561.00
#Sta/Elev= 30
  4842.0  469.13  4844.6  469.13  4852.5  467.87  4863.0  466.80  4873.6  464.82
  4884.1  465.05  4894.7  464.18  4905.2  462.98  4915.7  462.13  4936.8  459.84
  4947.4  458.94  4979.0  457.27  4987.5  453.08  4987.8  452.58  4991.3  452.58
  4991.5  453.08  4997.4  455.09  5002.6  455.09  5010.1  456.88  5030.1  458.17
  5040.1  458.66  5100.1  459.45  5130.1  460.36  5170.1  462.75  5190.1  463.60
  5210.1  465.38  5220.1  465.79  5230.1  466.54  5240.1  467.83  5250.1  468.30
#Mann=3,-1,0
  4842.0    0.12       0  4987.5    0.07       0  4991.5    0.12       0
Bank Sta=4987.5,4991.5
Exp/Cntr=0.3,0.1

Type RM Length L Ch R = 1,8295,351,351,351
BEGIN DESCRIPTION:
Caney Creek T 14 19.0
END DESCRIPTION:
XS GIS Cut Line= 3
      2797375.97      6780810.99      2797576.00      6780911.00
      2797875.96      6781060.98
#Sta/Elev= 30
  4780.3  468.58  4816.7  465.12  4825.1  463.47  4843.9  462.29  4855.8  461.26
  4860.8  461.48  4883.7  460.14  4900.5  458.43  4914.5  457.92  4922.9  456.87
  4973.2  453.30  4979.6  450.88  4979.8  450.38  4983.3  450.38  4983.6  450.88
  4990.0  453.21  4995.6  452.53  5006.7  453.20  5012.3  454.37  5017.9  454.13
  5026.3  454.95  5073.8  455.60  5115.7  456.41  5188.8  461.53  5249.9  466.83
  5272.3  470.24  5294.6  472.34  5303.0  472.54  5318.8  474.63  5339.3  476.76
#Mann=8,-1,0
  4780.3    0.12       0  4843.9     0.1       0  4860.8    0.12       0
  4979.6    0.07       0  4983.6    0.12       0  5073.8     0.1       0
  5188.8    0.12       0  5318.8     0.1       0
Bank Sta=4979.6,4983.6
Exp/Cntr=0.3,0.1

Type RM Length L Ch R = 1,7944,327,327,327
BEGIN DESCRIPTION:
Caney Creek T 14 18.0
END DESCRIPTION:
XS GIS Cut Line= 3
      2797047.91      6781042.36      2797326.00      6781161.00
      2797794.88      6781329.86
#Sta/Elev= 30
  4693.4  471.45  4713.1  469.07  4723.3  469.78  4734.8  467.69  4752.4  467.58
  4767.4  465.53  4828.7  460.48  4834.1  461.02  4857.7  459.77  4865.3  458.37
  4881.3  458.07  4904.9  455.65  4934.0  454.03  4985.2  452.34  5027.6  451.41
  5059.5  452.49  5065.2  449.26  5065.4  448.76  5068.9  448.76  5069.2  449.26
  5080.8  451.03  5103.2  452.30  5159.3  451.77  5190.0  452.25  5257.6  456.71
  5307.5  459.81  5410.3  469.59  5424.9  470.23  5442.1  472.36  5494.1  475.74
#Mann=5,-1,0
  4693.4    0.12       0  4985.2     0.1       0  5065.2    0.07       0
  5069.2     0.1       0  5257.6    0.12       0
Bank Sta=5065.2,5069.2
Exp/Cntr=0.3,0.1

Type RM Length L Ch R = 1,7617,367,367,367
BEGIN DESCRIPTION:
Caney Creek T 14 17.0
END DESCRIPTION:
XS GIS Cut Line= 3
      2797076.02      6781411.00      2797326.00      6781461.00
      2797756.68      6781528.05
#Sta/Elev= 30
  4749.3  466.64  4812.0  462.09  4861.5  457.40  4871.7  456.85  4943.0  449.63
  4953.2  450.24  4973.6  450.38  4992.0  447.72  4992.3  447.22  4995.8  447.22
  4996.0  447.72  5001.7  449.32  5006.8  449.32  5014.3  450.51  5054.8  450.18
  5095.3  451.23  5106.1  452.27  5135.8  453.08  5156.0  453.94  5169.0  455.14
  5206.6  456.45  5247.1  460.23  5257.2  460.37  5328.1  465.04  5338.2  466.22
  5362.6  467.79  5368.6  468.68  5419.2  472.32  5425.5  473.21  5440.1  473.42
#Mann=4,-1,0
  4749.3    0.05       0  4812.0    0.12       0  4992.0    0.07       0
  4996.0    0.12       0
Bank Sta=4992,4996
Exp/Cntr=0.3,0.1

Type RM Length L Ch R = 1,7250,357,357,357
BEGIN DESCRIPTION:
Caney Creek T 14 16.0
END DESCRIPTION:
XS GIS Cut Line= 3
      2797026.03      6781811.00      2797276.00      6781811.00
      2797999.55      6781672.81
#Sta/Elev= 30
  4754.6  462.78  4757.1  462.78  4764.6  459.54  4782.4  456.90  4804.6  455.36
  4814.6  455.08  4824.6  455.82  4834.6  455.43  4894.6  451.20  4944.6  449.84
  4972.6  446.56  4972.8  446.06  4976.3  446.06  4976.6  446.56  4984.6  446.78
  5002.1  448.65  5055.5  449.24  5106.4  452.16  5116.6  453.35  5174.5  455.25
  5208.2  455.64  5238.7  454.52  5289.6  455.92  5330.4  458.76  5353.4  459.40
  5381.3  461.13  5457.6  469.09  5523.8  472.29  5633.4  475.92  5741.2  478.51
#Mann=6,-1,0
  4754.6    0.05       0  4782.4     0.1       0  4972.6    0.07       0
  4976.6     0.1       0  5174.5    0.12       0  5633.4     0.1       0
Bank Sta=4972.6,4976.6
Exp/Cntr=0.3,0.1

Type RM Length L Ch R = 1,6893,464,464,464
BEGIN DESCRIPTION:
Caney Creek T 14 15.0
END DESCRIPTION:
XS GIS Cut Line= 3
      2796979.00      6781867.57      2797126.00      6782111.00
      2797374.18      6782531.45
#Sta/Elev= 30
  4709.9  462.52  4716.8  462.67  4738.1  458.81  4801.2  455.78  4827.4  455.92
  4833.2  453.48  4848.7  456.83  4854.6  453.07  4864.2  453.89  4877.5  451.80
  4885.6  453.89  4891.4  450.96  4906.9  452.52  4912.8  449.47  4922.5  449.91
  4949.6  447.02  4980.7  446.94  5000.1  444.77  5000.3  444.27  5004.1  444.77
  5029.3  446.89  5060.6  446.44  5066.4  448.42  5082.1  445.96  5160.3  447.27
  5295.8  451.95  5374.8  455.55  5417.7  459.20  5449.1  459.77  5482.5  459.72
#Mann=7,-1,0
  4709.9    0.05       0  4801.2    0.12       0  5000.1    0.07       0
  5004.1    0.12       0  5160.3     0.1       0  5295.8    0.12       0
  5449.1     0.1       0
Bank Sta=5000.1,5004.1
Exp/Cntr=0.3,0.1

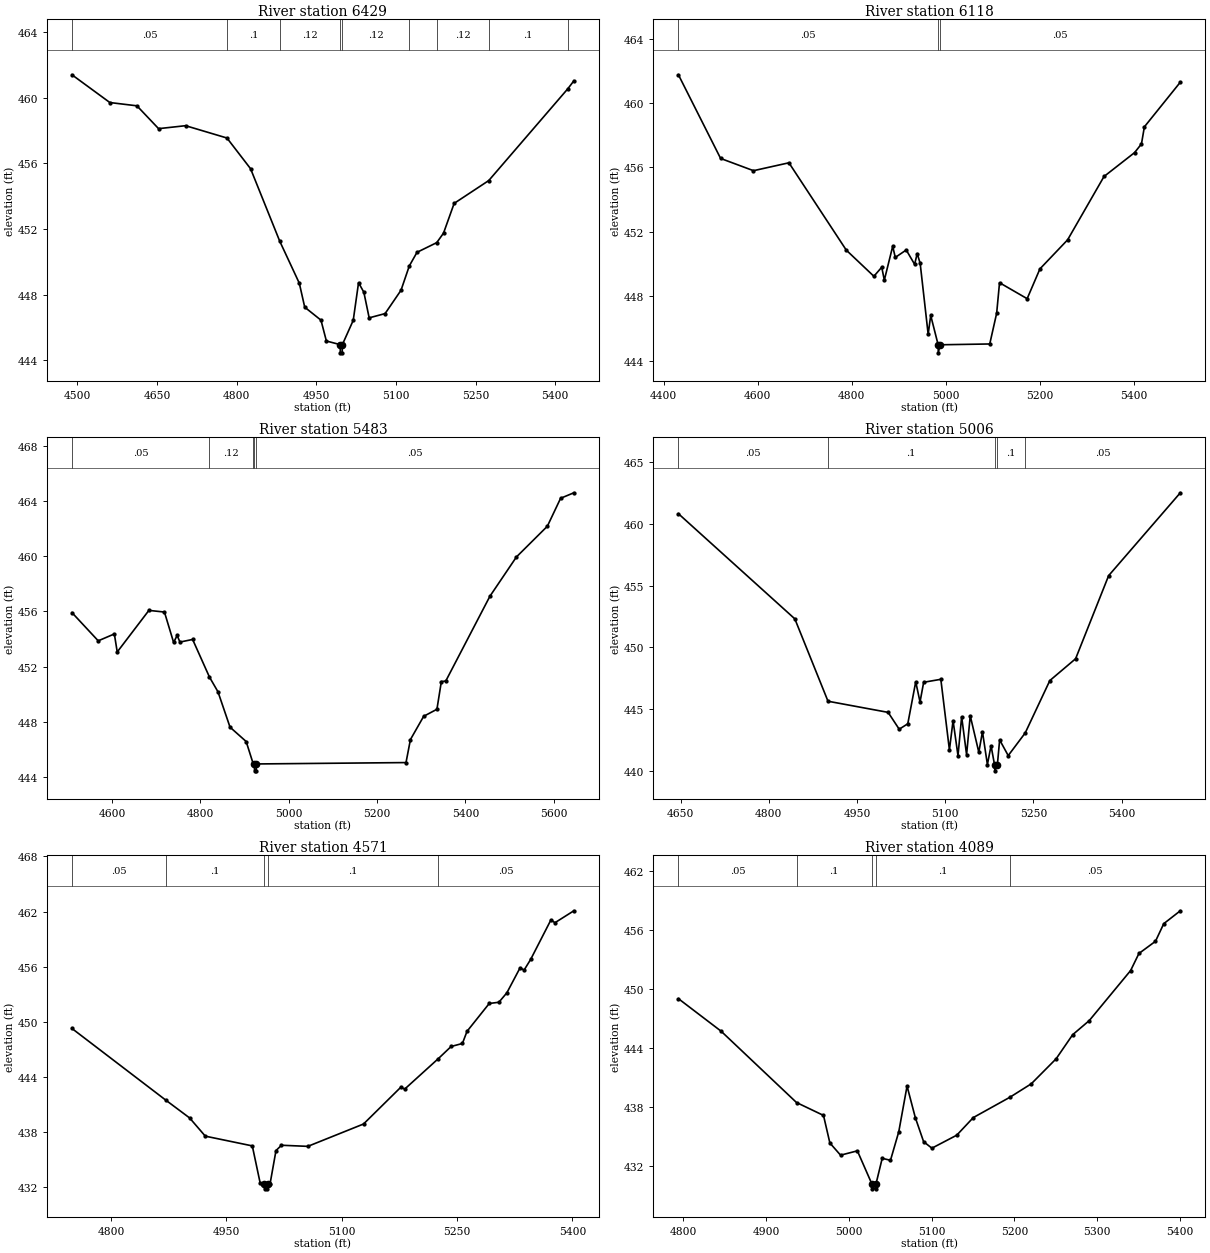
Type RM Length L Ch R = 1,6429,311,311,311
BEGIN DESCRIPTION:
Caney Creek T 14 14.0
END DESCRIPTION:
XS GIS Cut Line= 3
      2796926.00      6781911.01      2796826.00      6782411.00
      2796839.92      6782846.38
#Sta/Elev= 30
  4489.7  461.39  4561.1  459.70  4612.1  459.50  4652.9  458.11  4703.8  458.29
  4781.7  457.54  4826.2  455.67  4881.1  451.26  4918.0  448.70  4928.2  447.24
  4958.8  446.45  4969.0  445.18  4995.0  444.96  4995.3  444.46  4998.8  444.46
  4999.1  444.96  5019.6  446.44  5029.6  448.73  5039.6  448.15  5049.6  446.59
  5079.6  446.85  5109.6  448.27  5125.2  449.75  5139.7  450.58  5176.9  451.17
  5189.7  451.75  5209.7  453.56  5274.9  454.95  5423.6  460.53  5435.2  461.02
#Mann=9,-1,0
  4489.7    0.05       0  4781.7     0.1       0  4881.1    0.12       0
  4995.0    0.07       0  4999.1    0.12       0  5125.2     0.1       0
  5176.9    0.12       0  5274.9     0.1       0  5423.6    0.05       0
Bank Sta=4995,4999.1
Exp/Cntr=0.3,0.1

Type RM Length L Ch R = 1,6118,635,635,635
BEGIN DESCRIPTION:
Caney Creek T 14 13.0
END DESCRIPTION:
XS GIS Cut Line= 3
      2796775.98      6781811.04      2796545.98      6782331.04
      2796254.08      6782734.90
#Sta/Elev= 30
  4431.4  461.75  4521.1  456.56  4591.0  455.80  4666.3  456.29  4788.3  450.87
  4846.9  449.25  4863.6  449.81  4869.1  449.01  4886.9  451.11  4892.4  450.42
  4915.7  450.88  4933.5  449.99  4939.0  450.66  4945.3  450.05  4962.3  445.65
  4967.7  446.82  4983.5  445.00  4983.8  444.50  4987.6  445.00  5093.2  445.05
  5107.9  446.96  5114.0  448.85  5172.7  447.86  5199.9  449.71  5258.7  451.51
  5336.1  455.44  5401.0  456.92  5415.7  457.46  5421.9  458.52  5498.3  461.29
#Mann=3,-1,0
  4431.4    0.05       0  4983.5    0.03       0  4987.6    0.05       0
Bank Sta=4983.5,4987.6
Exp/Cntr=0.3,0.1

Type RM Length L Ch R = 1,5483,477,477,477
BEGIN DESCRIPTION:
Caney Creek T 14 12.0
END DESCRIPTION:
XS GIS Cut Line= 3
      2796335.05      6781635.55      2796026.00      6782011.00
      2796026.00      6782661.01
#Sta/Elev= 30
  4509.2  455.92  4568.7  453.87  4605.2  454.37  4611.7  453.06  4683.4  456.08
  4718.6  455.96  4739.4  453.75  4747.3  454.26  4753.7  453.78  4782.4  453.97
  4820.5  451.24  4839.8  450.17  4867.1  447.60  4903.6  446.56  4919.6  444.94
  4922.0  444.93  4922.6  444.43  4926.3  444.43  4926.9  444.93  5265.5  445.03
  5275.5  446.70  5305.5  448.39  5335.5  448.90  5345.5  450.91  5355.5  450.95
  5455.5  457.11  5515.5  459.96  5585.5  462.19  5615.5  464.22  5645.5  464.62
#Mann=5,-1,0
  4509.2    0.05       0  4820.5    0.12       0  4919.6    0.05       0
  4922.0    0.03       0  4926.9    0.05       0
Bank Sta=4922,4926.9
Exp/Cntr=0.3,0.1

Type RM Length L Ch R = 1,5006,435,435,435
BEGIN DESCRIPTION:
Caney Creek T 14 11.0
END DESCRIPTION:
XS GIS Cut Line= 3
      2795425.97      6781960.97      2795676.00      6782211.00
      2795976.00      6782611.00
#Sta/Elev= 30
  4646.4  460.80  4844.4  452.31  4900.8  445.66  5003.1  444.76  5021.9  443.40
  5036.5  443.84  5050.0  447.23  5057.3  445.60  5063.5  447.19  5092.7  447.43
  5107.3  441.73  5113.5  444.09  5121.9  441.26  5128.1  444.41  5136.5  441.34
  5142.7  444.49  5157.3  441.54  5163.5  443.20  5171.9  440.55  5178.1  442.07
  5184.0  440.54  5184.6  440.04  5188.9  440.54  5192.7  442.54  5207.3  441.27
  5236.2  443.10  5278.1  447.33  5321.9  449.09  5378.1  455.80  5500.0  462.49
#Mann=5,-1,0
  4646.4    0.05       0  4900.8     0.1       0  5184.0    0.07       0
  5188.9     0.1       0  5236.2    0.05       0
Bank Sta=5184,5188.9
Exp/Cntr=0.3,0.1

Type RM Length L Ch R = 1,4571,482,482,482
BEGIN DESCRIPTION:
Caney Creek T 14 10.0
END DESCRIPTION:
XS GIS Cut Line= 3
      2795326.01      6782561.00      2795576.00      6782611.00
      2795960.20      6782713.58
#Sta/Elev= 30
  4749.3  449.29  4871.1  441.51  4902.3  439.56  4922.7  437.58  4983.8  436.52
  4994.0  432.49  4999.2  432.35  4999.8  431.85  5003.5  431.85  5004.2  432.35
  5006.8  432.35  5014.6  436.01  5021.7  436.59  5056.0  436.47  5128.4  438.90
  5176.9  442.90  5182.0  442.70  5225.8  446.02  5242.3  447.33  5257.0  447.66
  5263.0  448.98  5291.9  452.01  5304.4  452.14  5314.8  453.17  5332.0  455.89
  5337.2  455.64  5345.8  456.81  5372.1  461.10  5377.3  460.79  5401.9  462.09
#Mann=5,-1,0
  4749.3    0.05       0  4871.1     0.1       0  4999.2    0.07       0
  5004.2     0.1       0  5225.8    0.05       0
Bank Sta=4999.2,5004.2
Exp/Cntr=0.3,0.1

Type RM Length L Ch R = 1,4089,465,465,465
BEGIN DESCRIPTION:
Caney Creek T 14 9.0
END DESCRIPTION:
XS GIS Cut Line= 3
      2795276.03      6783011.01      2795476.00      6783061.00
      2795875.98      6783061.00
#Sta/Elev= 30
  4794.2  448.98  4845.7  445.68  4936.8  438.43  4969.4  437.12  4977.1  434.32
  4990.0  433.08  5010.3  433.52  5027.8  430.16  5028.4  429.66  5032.2  429.66
  5032.8  430.16  5040.3  432.76  5050.3  432.56  5060.3  435.46  5070.3  440.10
  5080.3  436.89  5090.3  434.45  5100.3  433.79  5130.3  435.11  5150.3  436.90
  5194.6  438.97  5220.3  440.33  5250.3  442.87  5270.3  445.32  5290.3  446.75
  5340.3  451.84  5350.3  453.57  5370.3  454.81  5380.3  456.60  5400.3  457.91
#Mann=5,-1,0
  4794.2    0.05       0  4936.8     0.1       0  5027.8    0.07       0
  5032.8     0.1       0  5194.6    0.05       0
Bank Sta=5027.8,5032.8
Exp/Cntr=0.3,0.1

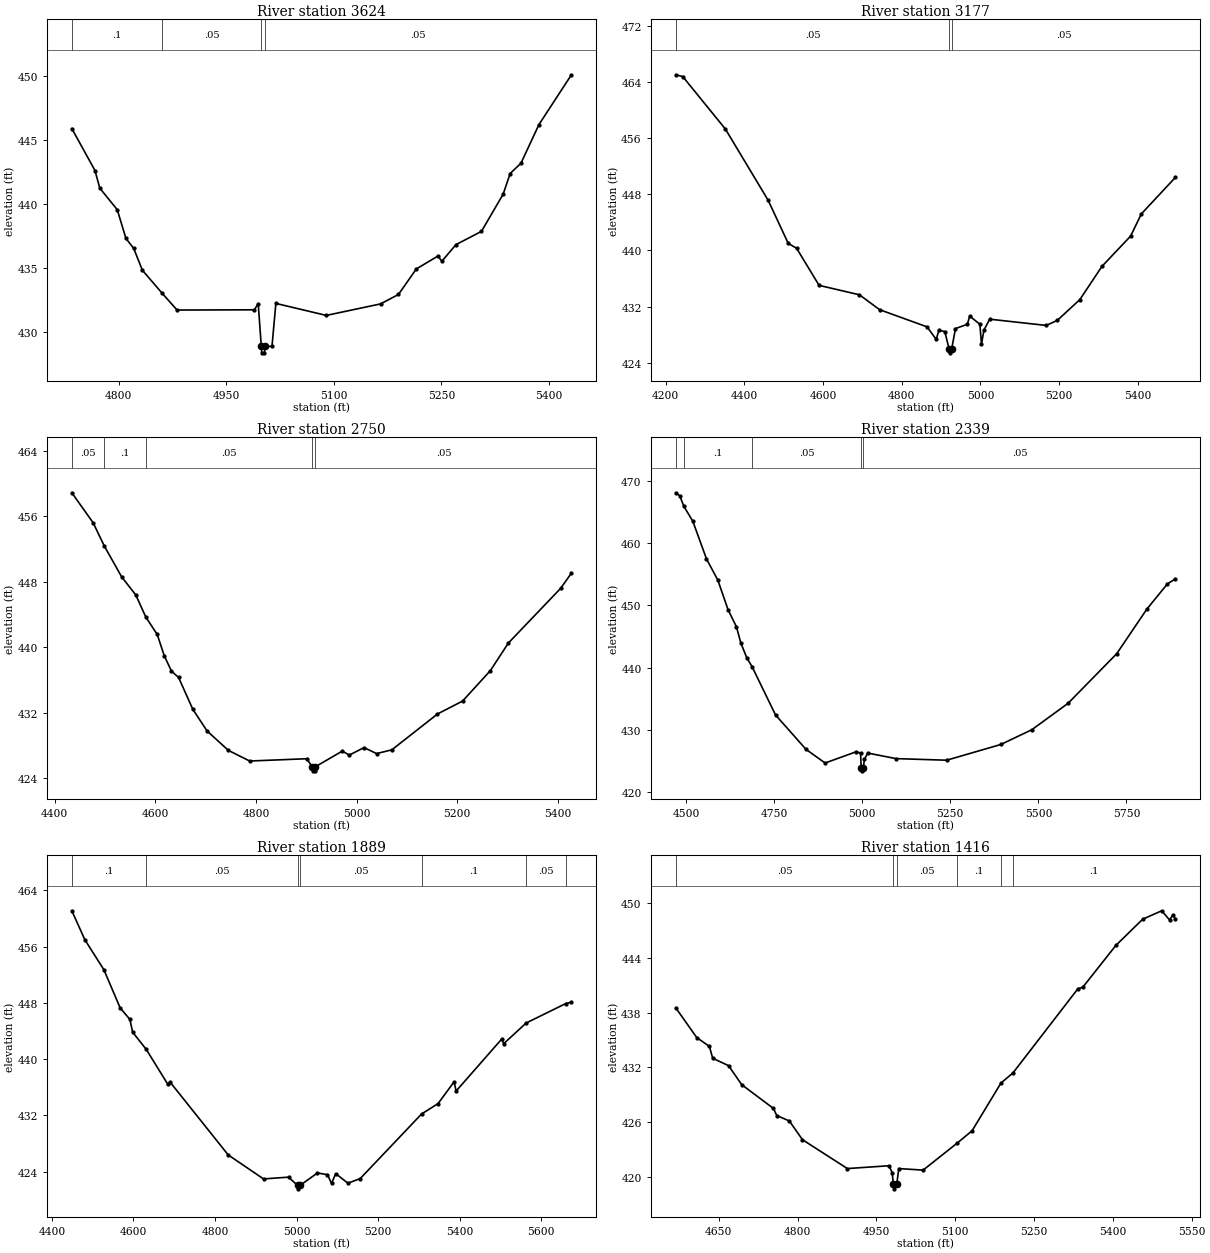
Type RM Length L Ch R = 1,3624,447,447,447
BEGIN DESCRIPTION:
Caney Creek T 14 8.0
END DESCRIPTION:
XS GIS Cut Line= 3
      2795226.00      6783211.01      2795326.00      6783461.00
      2795725.96      6783610.98
#Sta/Elev= 30
  4734.9  445.89  4767.2  442.60  4773.9  441.22  4798.2  439.54  4810.3  437.29
  4821.1  436.51  4833.2  434.80  4860.4  433.02  4881.6  431.68  4989.3  431.70
  4994.7  432.18  4999.0  428.83  4999.6  428.33  5003.4  428.33  5004.0  428.83
  5013.9  428.84  5019.3  432.20  5089.6  431.26  5165.2  432.16  5190.2  432.90
  5215.1  434.90  5245.3  435.91  5250.7  435.50  5270.3  436.80  5305.9  437.84
  5336.1  440.75  5345.9  442.37  5361.0  443.18  5386.0  446.20  5431.3  450.10
#Mann=4,-1,0
  4734.9     0.1       0  4860.4    0.05       0  4999.0    0.04       0
  5004.0    0.05       0
Bank Sta=4999,5004
Exp/Cntr=0.3,0.1

Type RM Length L Ch R = 1,3177,427,427,427
BEGIN DESCRIPTION:
Caney Creek T 14 7.0
END DESCRIPTION:
XS GIS Cut Line= 3
      2794332.51      6783288.72      2794976.00      6783711.00
      2795276.02      6784111.02
#Sta/Elev= 30
  4225.7  465.00  4243.4  464.75  4351.9  457.27  4460.4  447.15  4511.7  440.99
  4532.7  440.32  4590.0  435.03  4692.5  433.69  4743.8  431.57  4864.2  429.13
  4887.7  427.34  4894.4  428.66  4909.5  428.45  4920.5  425.93  4921.5  425.43
  4926.7  425.93  4936.6  428.88  4966.8  429.50  4972.7  430.66  4998.5  429.50
  5002.7  426.67  5008.9  428.67  5023.5  430.22  5167.2  429.33  5195.4  430.05
  5252.7  433.01  5308.9  437.74  5381.8  442.05  5408.9  445.20  5495.4  450.39
#Mann=3,-1,0
  4225.7    0.05       0  4920.5    0.04       0  4926.7    0.05       0
Bank Sta=4920.5,4926.7
Exp/Cntr=0.3,0.1

Type RM Length L Ch R = 1,2750,411,411,411
BEGIN DESCRIPTION:
Caney Creek T 14 6.0
END DESCRIPTION:
XS GIS Cut Line= 3
      2794376.02      6783661.02      2794776.00      6784061.00
      2795176.04      6784211.02
#Sta/Elev= 30
  4434.1  458.89  4476.5  455.22  4498.4  452.41  4533.1  448.61  4561.3  446.39
  4581.2  443.69  4603.8  441.57  4617.9  438.95  4632.1  437.09  4646.2  436.32
  4674.5  432.43  4702.8  429.78  4745.2  427.40  4787.6  426.10  4900.8  426.38
  4911.8  425.40  4912.8  424.90  4917.0  424.90  4918.1  425.40  4971.5  427.31
  4985.6  426.83  5014.9  427.74  5039.8  427.01  5070.1  427.47  5160.8  431.85
  5210.7  433.43  5265.9  437.15  5301.5  440.51  5405.6  447.21  5427.0  449.07
#Mann=5,-1,0
  4434.1    0.05       0  4498.4     0.1       0  4581.2    0.05       0
  4911.8    0.04       0  4918.1    0.05       0
Bank Sta=4911.8,4918.1
Exp/Cntr=0.3,0.1

Type RM Length L Ch R = 1,2339,450,450,450
BEGIN DESCRIPTION:
Caney Creek T 14 5.0
END DESCRIPTION:
XS GIS Cut Line= 3
      2794222.41      6783680.73      2794426.00      6784161.00
      2794885.30      6784930.74
#Sta/Elev= 30
  4470.8  468.12  4482.0  467.64  4493.9  465.93  4519.2  463.54  4558.0  457.48
  4590.2  454.06  4619.3  449.29  4643.0  446.55  4655.7  443.91  4672.1  441.60
  4687.5  440.12  4754.0  432.36  4840.4  426.83  4894.7  424.63  4983.3  426.45
  4995.3  426.21  4997.1  423.87  4998.1  423.37  5003.4  423.87  5006.1  425.22
  5015.7  426.23  5095.6  425.34  5239.6  425.08  5393.3  427.61  5481.5  429.99
  5584.1  434.23  5722.3  442.22  5807.9  449.40  5866.3  453.46  5888.8  454.26
#Mann=5,-1,0
  4470.8    0.05       0  4493.9     0.1       0  4687.5    0.05       0
  4997.1    0.04       0  5003.4    0.05       0
Bank Sta=4997.1,5003.4
Exp/Cntr=0.3,0.1

Type RM Length L Ch R = 1,1889,473,473,473
BEGIN DESCRIPTION:
Caney Creek T 14 4.0
END DESCRIPTION:
XS GIS Cut Line= 3
      2793889.79      6783797.00      2794076.00      6784311.00
      2794136.12      6784986.94
#Sta/Elev= 30
  4448.8  461.09  4480.7  456.98  4527.5  452.70  4567.3  447.29  4591.3  445.64
  4597.9  443.84  4631.3  441.39  4684.5  436.40  4689.8  436.74  4832.3  426.39
  4918.9  422.98  4980.2  423.23  5002.3  422.07  5003.3  421.57  5008.8  422.07
  5051.3  423.83  5075.8  423.58  5085.8  422.33  5095.9  423.73  5126.0  422.37
  5156.1  423.03  5306.6  432.21  5346.9  433.68  5386.3  436.78  5391.3  435.47
  5503.0  442.85  5508.0  442.20  5563.1  445.14  5660.1  447.90  5674.1  448.10
#Mann=7,-1,0
  4448.8     0.1       0  4631.3    0.05       0  5002.3    0.04       0
  5008.8    0.05       0  5306.6     0.1       0  5563.1    0.05       0
  5660.1    0.12       0
Bank Sta=5002.3,5008.8
Exp/Cntr=0.3,0.1

Type RM Length L Ch R = 1,1416,449,449,449
BEGIN DESCRIPTION:
Caney Creek T 14 3.0
END DESCRIPTION:
XS GIS Cut Line= 3
      2793526.01      6784111.03      2793676.00      6784511.00
      2793965.50      6784947.45
#Sta/Elev= 30
  4568.1  438.53  4608.1  435.27  4632.1  434.31  4638.4  433.01  4668.6  432.20
  4693.6  430.12  4754.1  427.51  4760.3  426.74  4784.3  426.14  4809.3  424.09
  4894.7  420.93  4973.9  421.24  4980.1  420.48  4982.2  419.21  4983.3  418.71
  4988.7  419.21  4992.6  420.93  5038.9  420.76  5104.2  423.74  5132.1  425.07
  5187.0  430.29  5210.0  431.41  5333.6  440.63  5342.7  440.78  5405.8  445.37
  5456.9  448.24  5493.0  449.16  5508.1  448.15  5514.1  448.73  5519.0  448.27
#Mann=6,-1,0
  4568.1    0.05       0  4982.2    0.04       0  4988.7    0.05       0
  5104.2     0.1       0  5187.0    0.12       0  5210.0     0.1       0
Bank Sta=4982.2,4988.7
Exp/Cntr=0.3,0.1

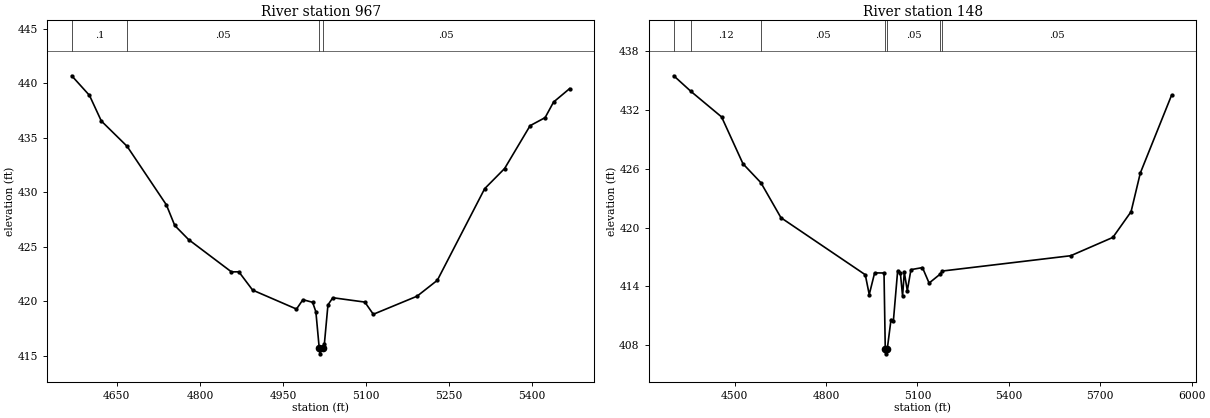
Type RM Length L Ch R = 1,967,819,819,819
BEGIN DESCRIPTION:
Caney Creek T 14 2.0
END DESCRIPTION:
XS GIS Cut Line= 3
      2793126.00      6784161.00      2793276.00      6784561.00
      2793526.00      6784961.00
#Sta/Elev= 30
  4568.6  440.69  4600.6  438.89  4622.0  436.54  4668.5  434.22  4739.5  428.84
  4754.6  426.95  4779.5  425.66  4857.0  422.69  4870.3  422.70  4895.2  421.02
  4974.4  419.28  4986.0  420.14  5003.5  419.90  5009.4  419.03  5015.5  415.67
  5016.5  415.17  5022.1  415.67  5024.7  416.05  5031.2  419.66  5040.0  420.32
  5097.8  419.92  5113.1  418.80  5192.1  420.46  5228.7  421.92  5314.2  430.33
  5350.2  432.18  5396.2  436.11  5423.3  436.85  5438.6  438.28  5467.5  439.51
#Mann=4,-1,0
  4568.6     0.1       0  4668.5    0.05       0  5015.5    0.04       0
  5022.1    0.05       0
Bank Sta=5015.5,5022.1
Exp/Cntr=0.3,0.1

Type RM Length L Ch R = 1,148,0,0,0
BEGIN DESCRIPTION:
Caney Creek T 14 1.0
END DESCRIPTION:
XS GIS Cut Line= 3
      2792661.86      6783927.79      2792507.65      6784610.59
      2793325.99      6785060.99
#Sta/Elev= 30
  4300.0  435.49  4356.7  433.89  4457.1  431.29  4527.3  426.51  4586.1  424.58
  4651.9  421.01  4928.7  415.19  4941.7  413.17  4959.4  415.38  4990.2  415.37
  4994.3  407.62  4995.4  407.12  5000.9  407.62  5013.2  410.62  5020.9  410.46
  5035.0  415.61  5043.8  415.40  5051.1  413.03  5056.8  415.45  5066.6  413.56
  5078.6  415.71  5116.4  415.92  5138.2  414.34  5173.6  415.23  5181.9  415.57
  5603.1  417.13  5741.4  419.00  5801.1  421.62  5831.4  425.56  5934.1  433.51
#Mann=7,-1,0
  4300.0    0.05       0  4356.7    0.12       0  4586.1    0.05       0
  4994.3    0.04       0  5000.9    0.05       0  5173.6    0.12       0
  5181.9    0.05       0
Bank Sta=4994.3,5000.9
Exp/Cntr=0.3,0.1

Chan Stop Cuts=-1