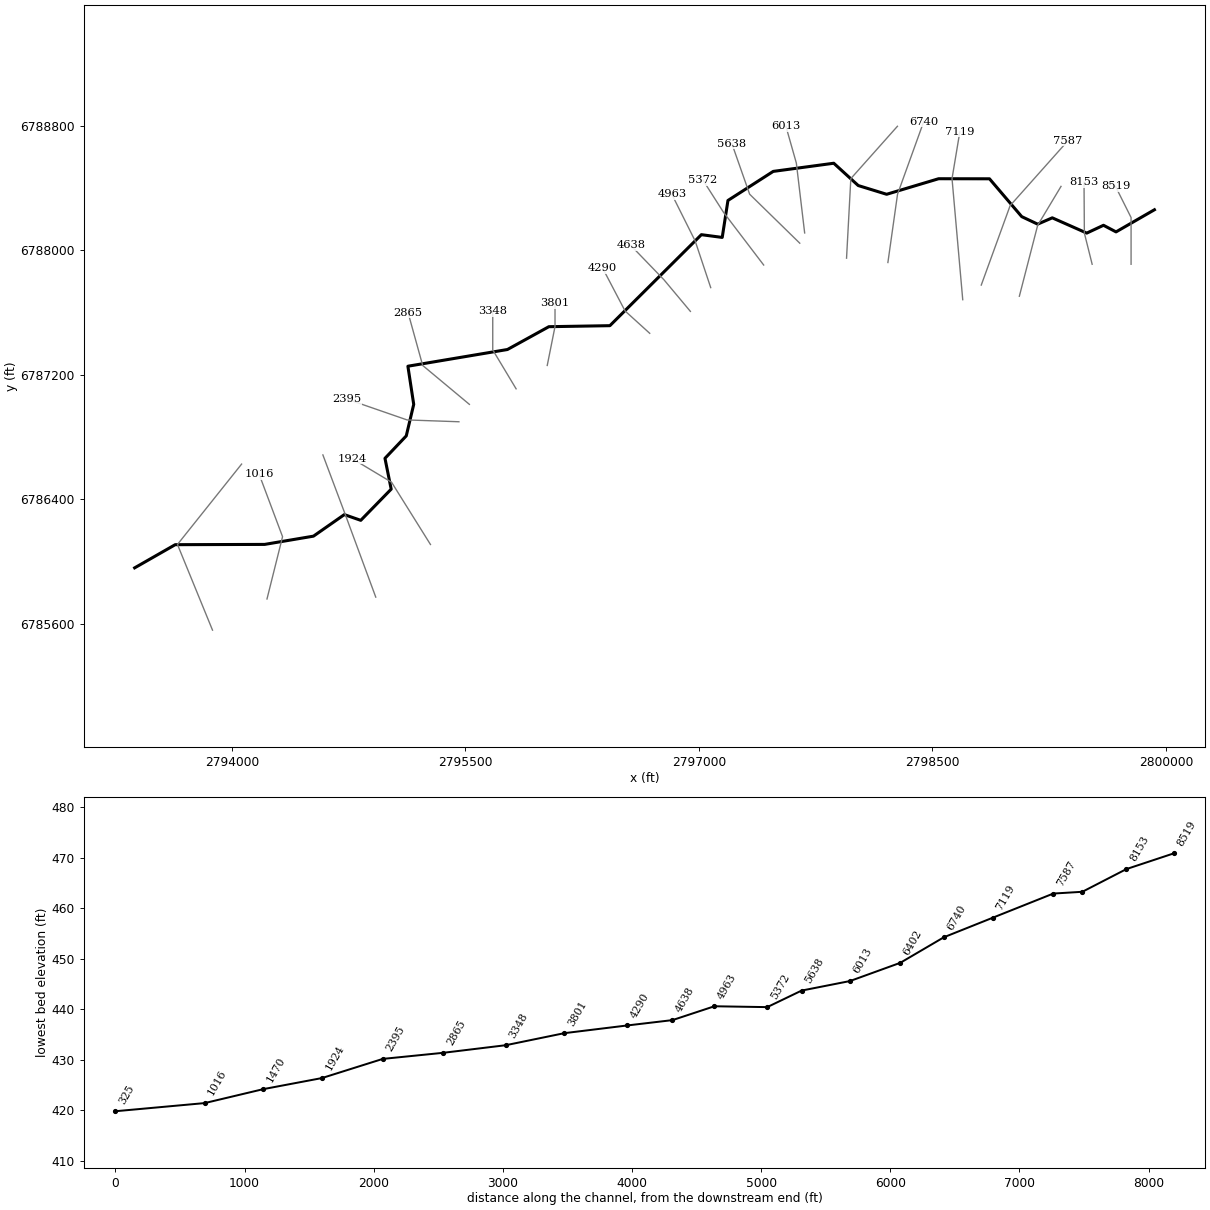
--- Caney Creek T 15.prj (project) ---

Proj Title=Caney Creek T 15 Base Level Engineering
Current Plan=p01
Default Exp/Contr=0.3,0.1
English Units
Geom File=g01
Flow File=f01
Plan File=p01
BEGIN DESCRIPTION:
Caney Creek T 15
END DESCRIPTION:

--- Caney Creek T 15.p01 (plan) ---

Plan Title=Multiple Run
Short Identifier=Multiple
Geom File=g01
Flow File=f01
Subcritical Flow
K Sum by GR= 0
Std Step Tol= 0.01
Critical Tol= 0.01
Num of Std Step Trials= 20
Max Error Tol= 0.3
Flow Tol Ratio= 0.001
Split Flow NTrial= 30
Split Flow Tol= 0.02
Split Flow Ratio= 0.02
Log Output Level= 0
Friction Slope Method= 1
Unsteady Friction Slope Method= 2
Unsteady Bridges Friction Slope Method= 1
Parabolic Critical Depth
Global Vel Dist=  1 , 1 , 1
Global Log Level= 0
CheckData=True
Encroach Param= -1, 0, 0, 0
BEGIN DESCRIPTION:
Multiple Run
END DESCRIPTION:

--- Caney Creek T 15.f01 (steady flow) ---

Flow Title=Multiple
Number of Profiles=7
Profile Names=10-year,25-year,50-year,1pct_min,100-year,1pct_plu,500-year
River Rch & RM= Caney Creek T 15,Reach-1,8519
     672     919    1124     684    1365    2723    2015
River Rch & RM= Caney Creek T 15,Reach-1,3801
     739    1014    1241     756    1508    3008    2229
Boundary for River Rch & Prof#=Caney Creek T 15,Reach-1,1
Up Type=0
Dn Type=3
Dn Slope=0.005
Boundary for River Rch & Prof#=Caney Creek T 15,Reach-1,2
Up Type=0
Dn Type=3
Dn Slope=0.005
Boundary for River Rch & Prof#=Caney Creek T 15,Reach-1,3
Up Type=0
Dn Type=3
Dn Slope=0.005
Boundary for River Rch & Prof#=Caney Creek T 15,Reach-1,4
Up Type=0
Dn Type=3
Dn Slope=0.005
Boundary for River Rch & Prof#=Caney Creek T 15,Reach-1,5
Up Type=0
Dn Type=3
Dn Slope=0.005
Boundary for River Rch & Prof#=Caney Creek T 15,Reach-1,6
Up Type=0
Dn Type=3
Dn Slope=0.005
Boundary for River Rch & Prof#=Caney Creek T 15,Reach-1,7
Up Type=0
Dn Type=3
Dn Slope=0.005

--- Caney Creek T 15.g01 (geometry) ---

Geom Title=Existing Conditions

River Reach=Caney Creek T 15,Reach-1
Reach XY= 30
      2799926.00      6788261.00      2799679.40      6788118.83
      2799598.84      6788161.28      2799491.40      6788111.10
      2799269.87      6788209.14      2799176.00      6788168.56
      2799073.71      6788216.81      2798866.57      6788459.86
      2798539.92      6788460.32      2798205.95      6788360.40
      2798023.57      6788416.52      2797866.41      6788559.80
      2797477.50      6788507.39      2797186.75      6788320.72
      2797149.98      6788083.30      2797016.01      6788100.93
      2796428.45      6787516.46      2796036.44      6787509.94
      2795770.47      6787363.39      2795131.00      6787256.00
      2795168.44      6787011.00      2795120.53      6786808.55
      2794983.80      6786664.42      2795023.67      6786466.50
      2794828.28      6786266.13      2794722.69      6786302.93
      2794524.53      6786164.55      2794210.78      6786111.52
      2793636.50      6786109.80      2793376.00      6785961.00

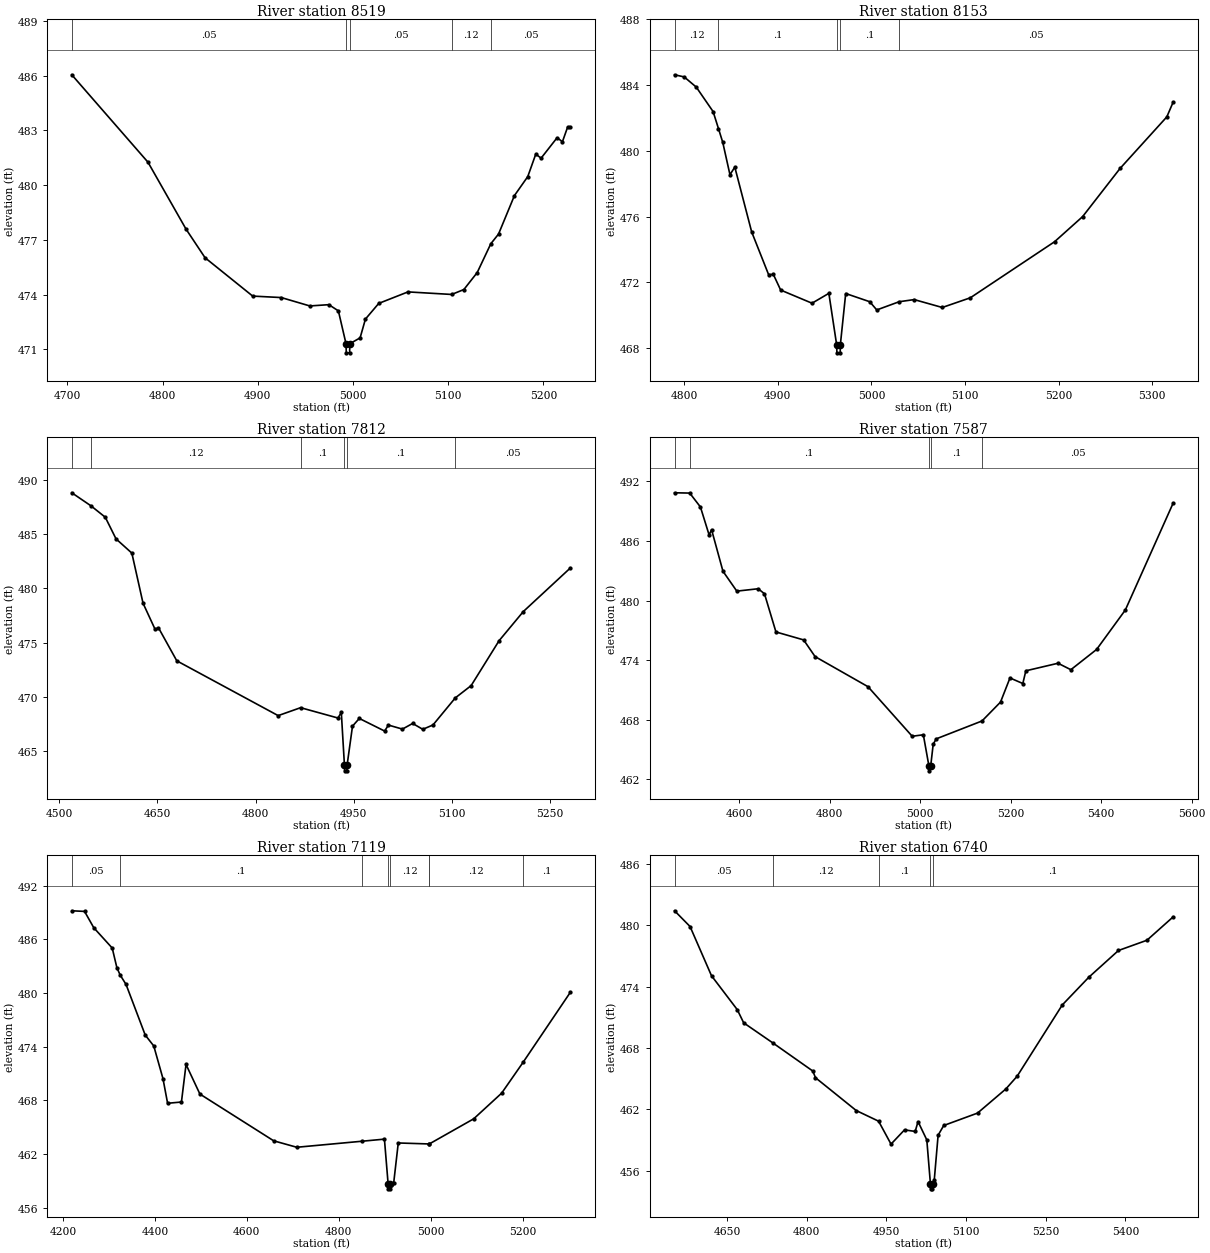
Type RM Length L Ch R = 1,8519,366,366,366
BEGIN DESCRIPTION:
Caney Creek T 15 21.0
END DESCRIPTION:
XS GIS Cut Line= 3
      2799776.00      6787910.97      2799776.00      6788211.00
      2799676.02      6788410.96
#Sta/Elev= 30
  4704.7  486.05  4784.7  481.26  4824.7  477.59  4844.7  476.02  4894.7  473.92
  4924.7  473.84  4954.7  473.38  4974.7  473.45  4984.7  473.11  4992.7  471.31
  4993.0  470.81  4996.5  470.81  4996.7  471.31  5007.5  471.63  5013.1  472.66
  5027.1  473.52  5057.8  474.15  5103.7  474.01  5116.5  474.28  5130.5  475.21
  5144.8  476.79  5152.9  477.32  5169.6  479.43  5183.6  480.47  5192.0  481.70
  5197.6  481.48  5214.4  482.60  5220.0  482.38  5225.5  483.19  5228.3  483.19
#Mann=5,-1,0
  4704.7    0.05       0  4992.7    0.04       0  4996.7    0.05       0
  5103.7    0.12       0  5144.8    0.05       0
Bank Sta=4992.7,4996.7
Exp/Cntr=0.3,0.1

Type RM Length L Ch R = 1,8153,341,341,341
BEGIN DESCRIPTION:
Caney Creek T 15 20.0
END DESCRIPTION:
XS GIS Cut Line= 3
      2799525.99      6787911.03      2799476.00      6788111.00
      2799473.79      6788437.67
#Sta/Elev= 30
  4789.6  484.63  4799.9  484.50  4812.8  483.88  4830.8  482.39  4836.5  481.36
  4841.1  480.52  4848.8  478.55  4854.0  479.01  4872.0  475.07  4890.1  472.47
  4895.2  472.48  4903.0  471.53  4936.5  470.73  4954.5  471.33  4962.8  468.21
  4963.1  467.71  4966.6  467.71  4966.8  468.21  4972.5  471.32  4998.2  470.82
  5005.7  470.32  5029.6  470.82  5045.7  470.95  5075.7  470.47  5105.7  471.06
  5195.7  474.47  5225.7  476.00  5265.7  478.93  5315.7  482.07  5322.4  482.96
#Mann=5,-1,0
  4789.6    0.12       0  4836.5     0.1       0  4962.8    0.07       0
  4966.8     0.1       0  5029.6    0.05       0
Bank Sta=4962.8,4966.8
Exp/Cntr=0.3,0.1

Type RM Length L Ch R = 1,7812,225,225,225
BEGIN DESCRIPTION:
Caney Creek T 15 19.0
END DESCRIPTION:
XS GIS Cut Line= 3
      2799058.42      6787705.59      2799176.00      6788161.00
      2799326.01      6788411.01
#Sta/Elev= 30
  4519.2  488.80  4548.5  487.60  4570.4  486.55  4586.8  484.56  4611.0  483.25
  4628.1  478.64  4646.5  476.24  4651.7  476.38  4679.7  473.34  4834.6  468.30
  4868.9  469.03  4926.0  468.08  4931.1  468.60  4935.9  463.72  4936.2  463.22
  4939.7  463.22  4939.9  463.72  4948.2  467.33  4958.6  468.04  4997.3  466.88
  5003.1  467.43  5024.5  467.06  5040.1  467.58  5055.6  467.04  5071.2  467.44
  5105.3  469.93  5129.5  471.06  5172.2  475.19  5209.2  477.87  5281.1  481.88
#Mann=6,-1,0
  4519.2    0.05       0  4548.5    0.12       0  4868.9     0.1       0
  4935.9    0.07       0  4939.9     0.1       0  5105.3    0.05       0
Bank Sta=4935.9,4939.9
Exp/Cntr=0.3,0.1

Type RM Length L Ch R = 1,7587,468,468,468
BEGIN DESCRIPTION:
Caney Creek T 15 18.0
END DESCRIPTION:
XS GIS Cut Line= 3
      2798813.77      6787777.25      2798999.25      6788287.59
      2799371.15      6788704.93
#Sta/Elev= 30
  4457.0  490.86  4490.5  490.83  4514.2  489.43  4533.4  486.61  4538.8  487.15
  4564.0  482.96  4594.6  480.96  4641.9  481.20  4655.8  480.69  4681.1  476.85
  4742.3  476.05  4767.6  474.37  4884.6  471.34  4982.3  466.35  5006.9  466.50
  5019.2  463.37  5019.4  462.87  5023.2  463.37  5028.7  465.55  5035.4  466.09
  5136.6  467.89  5177.5  469.79  5198.4  472.22  5226.8  471.66  5233.5  472.94
  5304.6  473.70  5333.0  473.05  5389.9  475.09  5453.4  479.06  5559.0  489.81
#Mann=5,-1,0
  4457.0    0.05       0  4490.5     0.1       0  5019.2    0.07       0
  5023.2     0.1       0  5136.6    0.05       0
Bank Sta=5019.2,5023.2
Exp/Cntr=0.3,0.1

Type RM Length L Ch R = 1,7119,379,379,379
BEGIN DESCRIPTION:
Caney Creek T 15 17.0
END DESCRIPTION:
XS GIS Cut Line= 3
      2798694.77      6787683.33      2798626.00      6788461.00
      2798675.99      6788760.95
#Sta/Elev= 30
  4219.2  489.20  4247.0  489.13  4267.1  487.30  4307.2  485.03  4317.3  482.84
  4324.4  482.02  4337.3  480.96  4379.0  475.30  4397.6  474.08  4417.6  470.43
  4427.7  467.67  4457.8  467.81  4467.8  472.01  4498.0  468.70  4658.6  463.47
  4708.8  462.75  4849.8  463.42  4899.5  463.66  4907.6  458.60  4907.8  458.10
  4911.3  458.10  4911.6  458.60  4919.6  458.74  4929.6  463.23  4996.9  463.12
  4997.1  463.12  5093.7  465.93  5154.5  468.80  5201.2  472.25  5304.0  480.08
#Mann=8,-1,0
  4219.2    0.05       0  4324.4     0.1       0  4849.8    0.12       0
  4907.6    0.07       0  4911.6    0.12       0  4996.9     0.1       0
  4997.1    0.12       0  5201.2     0.1       0
Bank Sta=4907.6,4911.6
Exp/Cntr=0.3,0.1

Type RM Length L Ch R = 1,6740,338,338,338
BEGIN DESCRIPTION:
Caney Creek T 15 16.0
END DESCRIPTION:
XS GIS Cut Line= 3
      2798214.07      6787922.12      2798276.00      6788361.00
      2798444.29      6788827.34
#Sta/Elev= 30
  4550.9  481.40  4580.1  479.86  4620.5  475.05  4669.0  471.74  4681.1  470.45
  4736.8  468.46  4811.3  465.74  4816.3  465.09  4893.1  461.88  4935.2  460.84
  4958.6  458.60  4984.0  459.99  5004.1  459.84  5009.5  460.80  5026.0  459.01
  5032.8  454.73  5033.1  454.23  5036.6  454.23  5036.8  454.73  5040.1  455.12
  5047.3  459.47  5057.9  460.42  5121.5  461.63  5174.9  463.99  5196.1  465.23
  5281.2  472.20  5331.0  474.90  5387.0  477.52  5440.6  478.52  5489.9  480.80
#Mann=5,-1,0
  4550.9    0.05       0  4736.8    0.12       0  4935.2     0.1       0
  5032.8    0.07       0  5036.8     0.1       0
Bank Sta=5032.8,5036.8
Exp/Cntr=0.3,0.1

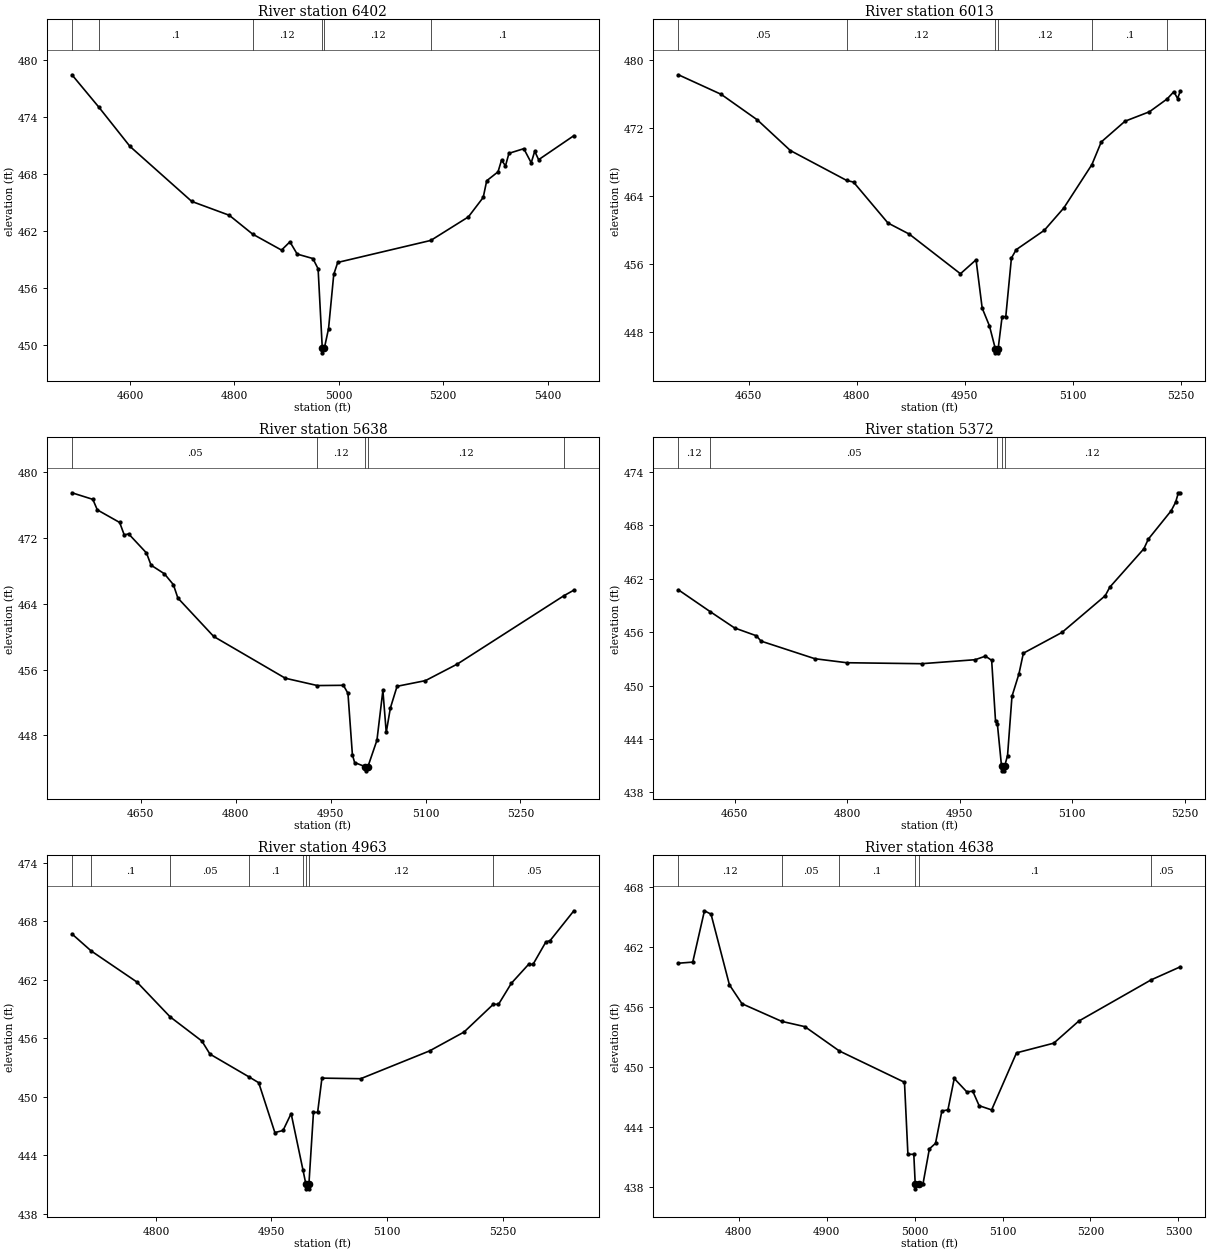
Type RM Length L Ch R = 1,6402,389,389,389
BEGIN DESCRIPTION:
Caney Creek T 15 15.0
END DESCRIPTION:
XS GIS Cut Line= 3
      2797948.47      6787949.98      2797976.00      6788461.00
      2798275.23      6788797.15
#Sta/Elev= 30
  4488.6  478.48  4540.1  475.07  4599.8  470.93  4718.2  465.13  4790.1  463.67
  4834.7  461.69  4890.2  460.00  4906.3  460.87  4920.2  459.58  4950.3  459.11
  4960.3  458.03  4968.3  449.67  4968.6  449.17  4972.3  449.67  4980.3  451.71
  4990.3  457.44  4997.9  458.70  5176.3  461.02  5248.3  463.50  5276.7  465.55
  5283.4  467.31  5305.1  468.25  5311.8  469.48  5319.4  468.88  5326.0  470.20
  5354.5  470.69  5368.7  469.20  5375.4  470.42  5382.9  469.53  5450.4  472.06
#Mann=6,-1,0
  4488.6    0.05       0  4540.1     0.1       0  4834.7    0.12       0
  4968.3    0.07       0  4972.3    0.12       0  5176.3     0.1       0
Bank Sta=4968.3,4972.3
Exp/Cntr=0.3,0.1

Type RM Length L Ch R = 1,6013,375,375,375
BEGIN DESCRIPTION:
Caney Creek T 15 14.0
END DESCRIPTION:
XS GIS Cut Line= 3
      2797679.44      6788112.03      2797626.00      6788561.00
      2797559.13      6788796.66
#Sta/Elev= 30
  4552.2  478.27  4611.6  475.97  4661.9  472.96  4707.7  469.36  4786.0  465.84
  4795.4  465.65  4843.2  460.84  4872.9  459.53  4943.9  454.87  4965.6  456.51
  4974.1  450.83  4984.2  448.74  4992.3  446.07  4992.5  445.57  4996.0  445.57
  4996.3  446.07  5001.8  449.84  5006.9  449.84  5014.7  456.71  5021.3  457.70
  5060.4  459.98  5087.5  462.61  5126.5  467.71  5139.5  470.37  5172.5  472.81
  5206.4  473.92  5231.0  475.43  5240.3  476.28  5245.5  475.48  5249.3  476.35
#Mann=6,-1,0
  4552.2    0.05       0  4786.0    0.12       0  4992.3    0.07       0
  4996.3    0.12       0  5126.5     0.1       0  5231.0    0.05       0
Bank Sta=4992.3,4996.3
Exp/Cntr=0.3,0.1

Type RM Length L Ch R = 1,5638,266,266,266
BEGIN DESCRIPTION:
Caney Creek T 15 13.0
END DESCRIPTION:
XS GIS Cut Line= 3
      2797647.98      6788046.28      2797326.00      6788361.00
      2797212.32      6788684.56
#Sta/Elev= 30
  4541.2  477.49  4574.2  476.69  4581.3  475.41  4616.6  473.88  4623.8  472.37
  4630.8  472.49  4659.0  470.17  4666.2  468.69  4687.3  467.64  4701.5  466.32
  4708.6  464.69  4765.2  460.02  4878.4  454.94  4929.1  454.05  4970.2  454.08
  4977.4  453.10  4984.4  445.65  4987.9  444.69  5004.9  444.18  5005.2  443.68
  5008.9  444.18  5023.2  447.40  5032.6  453.46  5037.9  448.35  5044.4  451.31
  5055.0  453.96  5099.9  454.65  5150.4  456.67  5318.6  464.97  5334.4  465.65
#Mann=5,-1,0
  4541.2    0.05       0  4929.1    0.12       0  5004.9    0.07       0
  5008.9    0.12       0  5318.6    0.05       0
Bank Sta=5004.9,5008.9
Exp/Cntr=0.3,0.1

Type RM Length L Ch R = 1,5372,409,409,409
BEGIN DESCRIPTION:
Caney Creek T 15 12.0
END DESCRIPTION:
XS GIS Cut Line= 3
      2797416.13      6787906.11      2797158.46      6788244.34
      2797026.99      6788450.37
#Sta/Elev= 30
  4574.8  460.75  4617.4  458.29  4649.7  456.47  4678.8  455.59  4685.0  454.99
  4756.9  453.01  4799.4  452.56  4899.2  452.45  4970.7  452.90  4984.4  453.30
  4992.7  452.83  4997.9  445.96  5000.3  445.70  5005.9  440.91  5006.1  440.41
  5009.6  440.41  5009.9  440.91  5013.9  442.13  5019.8  448.78  5029.1  451.31
  5035.0  453.63  5086.6  455.97  5144.2  460.09  5150.3  461.05  5195.8  465.37
  5201.7  466.45  5232.2  469.64  5238.1  470.59  5241.8  471.66  5244.4  471.66
#Mann=5,-1,0
  4574.8    0.12       0  4617.4    0.05       0  5000.3    0.12       0
  5005.9    0.04       0  5009.9    0.12       0
Bank Sta=5005.9,5009.9
Exp/Cntr=0.3,0.1

Type RM Length L Ch R = 1,4963,325,325,325
BEGIN DESCRIPTION:
Caney Creek T 15 11.0
END DESCRIPTION:
XS GIS Cut Line= 3
      2797076.01      6787760.98      2796976.00      6788061.00
      2796825.98      6788361.03
#Sta/Elev= 30
  4690.9  466.69  4715.8  464.95  4775.3  461.76  4818.3  458.20  4859.6  455.72
  4870.1  454.38  4920.7  452.05  4933.4  451.45  4954.4  446.34  4965.0  446.56
  4975.5  448.29  4990.8  442.54  4994.6  441.08  4994.9  440.58  4998.4  440.58
  4998.6  441.08  5004.5  448.41  5009.9  448.41  5015.5  451.92  5065.8  451.86
  5155.3  454.71  5200.0  456.64  5238.1  459.49  5244.7  459.47  5261.5  461.64
  5283.9  463.58  5289.5  463.56  5306.2  465.86  5311.8  466.01  5342.6  469.06
#Mann=8,-1,0
  4690.9    0.12       0  4715.8     0.1       0  4818.3    0.05       0
  4920.7     0.1       0  4990.8    0.12       0  4994.6    0.07       0
  4998.6    0.12       0  5238.1    0.05       0
Bank Sta=4994.6,4998.6
Exp/Cntr=0.3,0.1

Type RM Length L Ch R = 1,4638,348,348,348
BEGIN DESCRIPTION:
Caney Creek T 15 10.0
END DESCRIPTION:
XS GIS Cut Line= 3
      2796945.49      6787608.30      2796776.00      6787811.00
      2796563.06      6788031.56
#Sta/Elev= 30
  4731.4  460.39  4747.7  460.50  4761.0  465.63  4768.5  465.29  4789.4  458.23
  4803.7  456.34  4848.8  454.58  4875.2  454.05  4914.4  451.62  4988.5  448.49
  4992.4  441.29  4999.1  441.29  5000.7  438.34  5000.9  437.84  5004.7  438.34
  5009.6  438.36  5016.8  441.83  5023.8  442.39  5031.0  445.62  5037.9  445.73
  5045.1  448.87  5059.3  447.54  5066.2  447.59  5073.4  446.15  5087.6  445.73
  5115.9  451.43  5158.3  452.40  5186.6  454.60  5268.9  458.72  5302.2  460.03
#Mann=6,-1,0
  4731.4    0.12       0  4848.8    0.05       0  4914.4     0.1       0
  5000.7    0.07       0  5004.7     0.1       0  5268.9    0.05       0
Bank Sta=5000.7,5004.7
Exp/Cntr=0.3,0.1

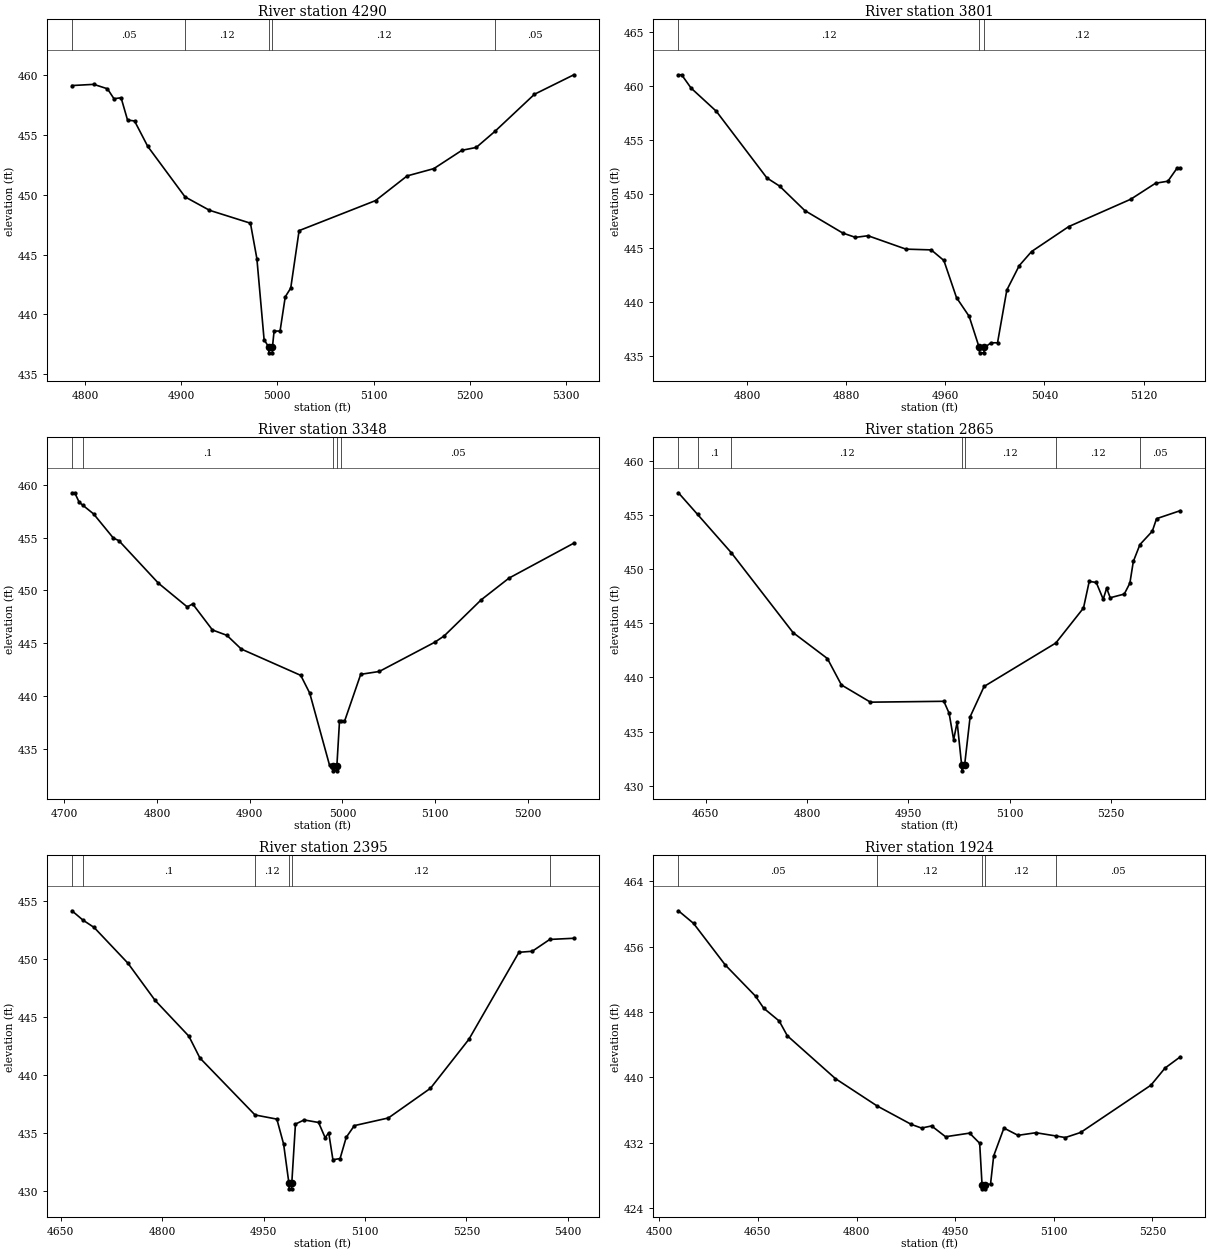
Type RM Length L Ch R = 1,4290,489,489,489
BEGIN DESCRIPTION:
Caney Creek T 15 9.0
END DESCRIPTION:
XS GIS Cut Line= 3
      2796684.18      6787467.43      2796526.00      6787611.00
      2796382.90      6787884.06
#Sta/Elev= 30
  4786.4  459.12  4809.1  459.22  4823.3  458.85  4830.1  458.02  4837.5  458.10
  4844.2  456.24  4851.5  456.16  4865.2  454.04  4904.0  449.82  4929.4  448.70
  4972.0  447.62  4978.7  444.66  4986.2  437.89  4990.9  437.29  4991.2  436.79
  4994.7  436.79  4994.9  437.29  4996.6  438.61  5002.8  438.61  5008.2  441.47
  5013.9  442.20  5022.6  447.00  5102.1  449.51  5134.9  451.57  5162.7  452.18
  5191.9  453.71  5206.8  453.95  5226.2  455.29  5267.3  458.39  5308.3  460.02
#Mann=5,-1,0
  4786.4    0.05       0  4904.0    0.12       0  4990.9    0.07       0
  4994.9    0.12       0  5226.2    0.05       0
Bank Sta=4990.9,4994.9
Exp/Cntr=0.3,0.1

Type RM Length L Ch R = 1,3801,453,453,453
BEGIN DESCRIPTION:
Caney Creek T 15 8.0
END DESCRIPTION:
XS GIS Cut Line= 3
      2796025.99      6787260.97      2796076.00      6787511.00
      2796076.00      6787661.02
#Sta/Elev= 30
  4744.6  461.00  4747.2  461.00  4754.8  459.77  4775.2  457.62  4816.0  451.45
  4826.2  450.70  4846.6  448.43  4877.2  446.35  4887.4  445.95  4897.6  446.10
  4928.2  444.86  4948.6  444.79  4958.8  443.81  4969.0  440.37  4979.2  438.64
  4987.3  435.76  4987.6  435.26  4991.1  435.26  4991.5  435.76  4997.0  436.19
  5002.1  436.19  5009.6  441.07  5019.6  443.33  5029.6  444.64  5059.6  446.95
  5109.6  449.48  5129.6  450.96  5139.6  451.15  5147.1  452.38  5149.6  452.38
#Mann=3,-1,0
  4744.6    0.12       0  4987.3    0.07       0  4991.5    0.12       0
Bank Sta=4987.3,4991.5
Exp/Cntr=0.3,0.1

Type RM Length L Ch R = 1,3348,483,483,483
BEGIN DESCRIPTION:
Caney Creek T 15 7.0
END DESCRIPTION:
XS GIS Cut Line= 3
      2795826.02      6787110.97      2795676.00      6787361.00
      2795676.00      6787611.01
#Sta/Elev= 30
  4708.1  459.27  4711.1  459.27  4715.9  458.37  4719.8  458.09  4731.5  457.26
  4752.8  454.97  4758.7  454.73  4801.4  450.69  4832.5  448.44  4838.4  448.72
  4859.7  446.25  4875.3  445.74  4890.8  444.44  4955.0  441.94  4964.7  440.25
  4986.1  433.40  4989.8  433.38  4990.1  432.88  4993.7  432.88  4994.0  433.38
  4996.8  437.57  4998.5  437.57  5002.2  437.57  5019.7  442.04  5039.7  442.31
  5099.7  445.09  5109.7  445.68  5149.7  449.11  5179.7  451.17  5249.7  454.49
#Mann=5,-1,0
  4708.1    0.05       0  4719.8     0.1       0  4989.8    0.04       0
  4994.0     0.1       0  4998.5    0.05       0
Bank Sta=4989.8,4994
Exp/Cntr=0.3,0.1

Type RM Length L Ch R = 1,2865,470,470,470
BEGIN DESCRIPTION:
Caney Creek T 15 6.0
END DESCRIPTION:
XS GIS Cut Line= 3
      2795525.98      6787011.02      2795226.00      6787261.00
      2795131.89      6787601.03
#Sta/Elev= 30
  4609.4  457.05  4637.8  455.05  4687.8  451.51  4779.2  444.14  4830.0  441.75
  4850.8  439.31  4893.8  437.72  5002.5  437.80  5010.3  436.70  5017.0  434.25
  5022.2  435.87  5028.9  431.88  5029.2  431.38  5033.2  431.88  5041.4  436.37
  5062.1  439.17  5168.3  443.18  5209.3  446.41  5217.8  448.87  5228.2  448.77
  5238.5  447.22  5243.6  448.24  5248.9  447.36  5269.7  447.70  5278.0  448.71
  5283.1  450.71  5292.9  452.27  5311.2  453.50  5317.5  454.66  5352.7  455.40
#Mann=7,-1,0
  4609.4    0.05       0  4637.8     0.1       0  4687.8    0.12       0
  5028.9    0.07       0  5033.2    0.12       0  5168.3    0.12       0
  5292.9    0.05       0
Bank Sta=5028.9,5033.2
Exp/Cntr=0.3,0.1

Type RM Length L Ch R = 1,2395,471,471,471
BEGIN DESCRIPTION:
Caney Creek T 15 5.0
END DESCRIPTION:
XS GIS Cut Line= 3
      2795458.78      6786899.32      2795126.00      6786911.00
      2794739.32      6787044.91
#Sta/Elev= 30
  4666.7  454.14  4682.9  453.34  4699.5  452.70  4749.5  449.62  4789.6  446.42
  4839.6  443.33  4855.9  441.45  4937.4  436.54  4969.7  436.18  4979.7  434.03
  4987.5  430.67  4987.9  430.17  4991.5  430.17  4991.8  430.67  4997.2  435.75
  5010.0  436.11  5031.4  435.89  5041.1  434.58  5046.4  435.00  5052.6  432.68
  5063.2  432.78  5072.3  434.61  5084.3  435.62  5134.6  436.28  5196.9  438.84
  5253.7  443.06  5327.7  450.56  5347.4  450.65  5373.3  451.67  5408.9  451.77
#Mann=6,-1,0
  4666.7    0.05       0  4682.9     0.1       0  4937.4    0.12       0
  4987.5    0.07       0  4991.8    0.12       0  5373.3    0.05       0
Bank Sta=4987.5,4991.8
Exp/Cntr=0.3,0.1

Type RM Length L Ch R = 1,1924,454,454,454
BEGIN DESCRIPTION:
Caney Creek T 15 4.0
END DESCRIPTION:
XS GIS Cut Line= 3
      2795275.98      6786111.03      2795026.00      6786511.00
      2794776.01      6786661.00
#Sta/Elev= 30
  4529.2  460.37  4552.2  458.83  4600.5  453.74  4646.5  449.93  4658.9  448.46
  4682.5  446.89  4694.8  445.09  4768.0  439.85  4831.4  436.51  4883.5  434.25
  4898.9  433.81  4914.2  434.07  4935.4  432.75  4972.0  433.19  4987.3  431.95
  4990.9  426.88  4991.4  426.38  4995.0  426.38  4995.4  426.88  5003.8  426.95
  5008.6  430.41  5024.2  433.81  5045.6  432.92  5072.8  433.24  5103.5  432.84
  5117.5  432.65  5140.8  433.27  5247.7  439.05  5269.1  441.14  5292.4  442.52
#Mann=5,-1,0
  4529.2    0.05       0  4831.4    0.12       0  4990.9    0.07       0
  4995.4    0.12       0  5103.5    0.05       0
Bank Sta=4990.9,4995.4
Exp/Cntr=0.3,0.1

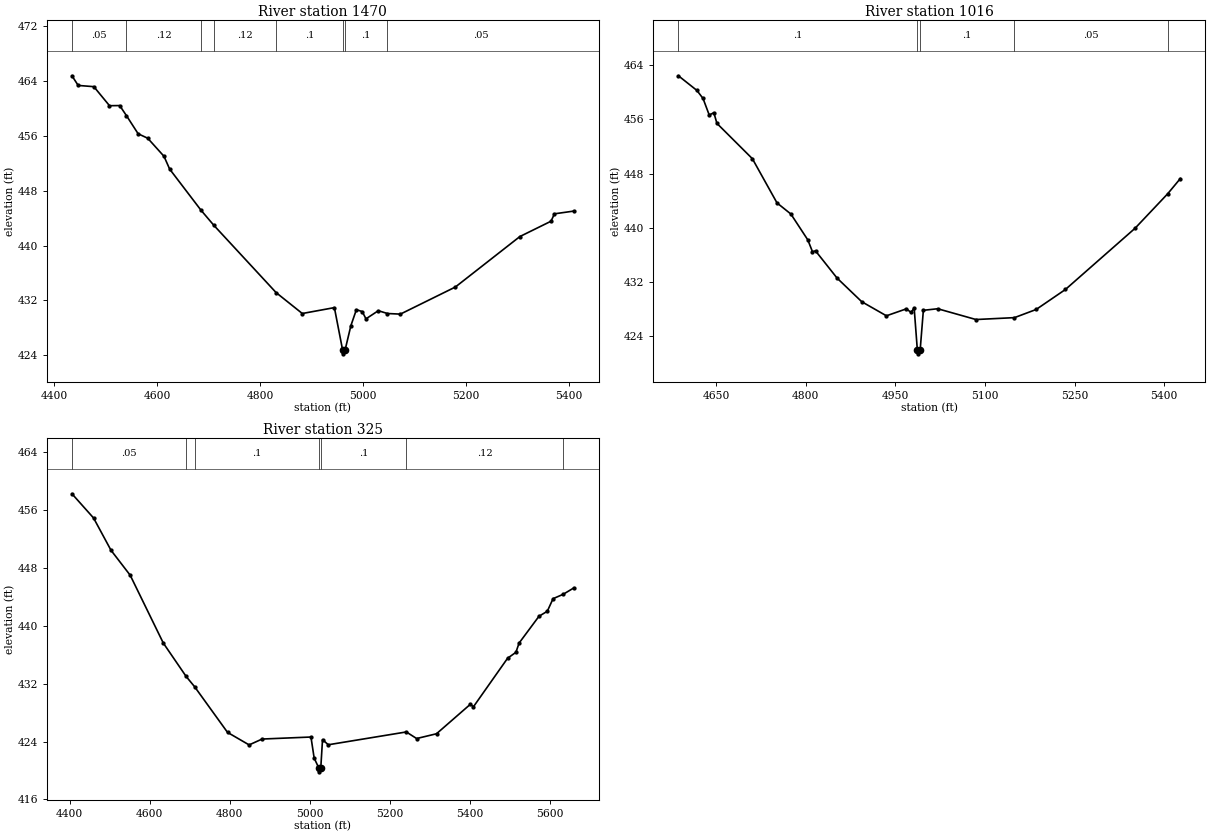
Type RM Length L Ch R = 1,1470,454,454,454
BEGIN DESCRIPTION:
Caney Creek T 15 3.0
END DESCRIPTION:
XS GIS Cut Line= 3
      2794924.56      6785773.00      2794726.00      6786311.00
      2794585.00      6786686.32
#Sta/Elev= 30
  4435.1  464.80  4447.2  463.39  4477.6  463.21  4508.0  460.43  4527.8  460.45
  4540.9  458.98  4563.6  456.33  4582.2  455.68  4613.8  453.04  4624.8  451.17
  4685.6  445.17  4710.6  442.96  4831.5  433.13  4882.3  430.08  4944.6  430.94
  4960.7  424.69  4961.1  424.19  4965.2  424.69  4976.6  428.30  4987.3  430.64
  4998.7  430.36  5005.9  429.30  5029.9  430.49  5047.6  430.08  5072.7  429.99
  5179.5  433.95  5304.7  441.32  5365.2  443.56  5371.8  444.64  5409.5  445.04
#Mann=8,-1,0
  4435.1    0.05       0  4540.9    0.12       0  4685.6     0.1       0
  4710.6    0.12       0  4831.5     0.1       0  4960.7    0.07       0
  4965.2     0.1       0  5047.6    0.05       0
Bank Sta=4960.7,4965.2
Exp/Cntr=0.3,0.1

Type RM Length L Ch R = 1,1016,691,691,691
BEGIN DESCRIPTION:
Caney Creek T 15 2.0
END DESCRIPTION:
XS GIS Cut Line= 3
      2794226.00      6785761.02      2794326.00      6786161.00
      2794176.00      6786561.01
#Sta/Elev= 30
  4587.3  462.44  4618.2  460.28  4628.5  459.09  4638.8  456.66  4646.6  456.99
  4651.7  455.42  4711.0  450.21  4752.2  443.69  4775.4  442.05  4803.7  438.24
  4811.5  436.50  4816.6  436.62  4852.7  432.60  4893.9  429.12  4935.2  427.04
  4968.7  428.07  4976.4  427.53  4981.6  428.21  4987.0  421.93  4987.5  421.43
  4991.6  421.93  4997.0  427.85  5021.0  428.08  5085.0  426.49  5149.4  426.77
  5185.6  427.97  5234.6  430.92  5351.1  439.95  5405.6  445.03  5426.8  447.28
#Mann=5,-1,0
  4587.3     0.1       0  4987.0    0.07       0  4991.6     0.1       0
  5149.4    0.05       0  5405.6    0.12       0
Bank Sta=4987,4991.6
Exp/Cntr=0.3,0.1

Type RM Length L Ch R = 1,325,0,0,0
BEGIN DESCRIPTION:
Caney Creek T 15 1.0
END DESCRIPTION:
XS GIS Cut Line= 3
      2793876.01      6785560.97      2793650.91      6786111.21
      2794062.86      6786627.38
#Sta/Elev= 30
  4405.5  458.23  4459.6  454.88  4503.1  450.43  4551.1  446.98  4633.9  437.61
  4691.1  432.99  4712.0  431.59  4794.5  425.27  4848.5  423.54  4880.9  424.35
  5003.1  424.63  5011.1  421.72  5023.0  420.32  5023.5  419.82  5027.6  420.32
  5032.0  424.27  5046.4  423.56  5241.5  425.33  5267.3  424.42  5317.0  425.08
  5401.8  429.16  5409.2  428.80  5494.7  435.51  5515.5  436.33  5523.5  437.61
  5573.2  441.31  5594.0  442.00  5608.4  443.74  5633.9  444.35  5660.4  445.23
#Mann=7,-1,0
  4405.5    0.05       0  4691.1    0.12       0  4712.0     0.1       0
  5023.0    0.07       0  5027.6     0.1       0  5241.5    0.12       0
  5633.9    0.05       0
Bank Sta=5023,5027.6
Exp/Cntr=0.3,0.1

Chan Stop Cuts=-1