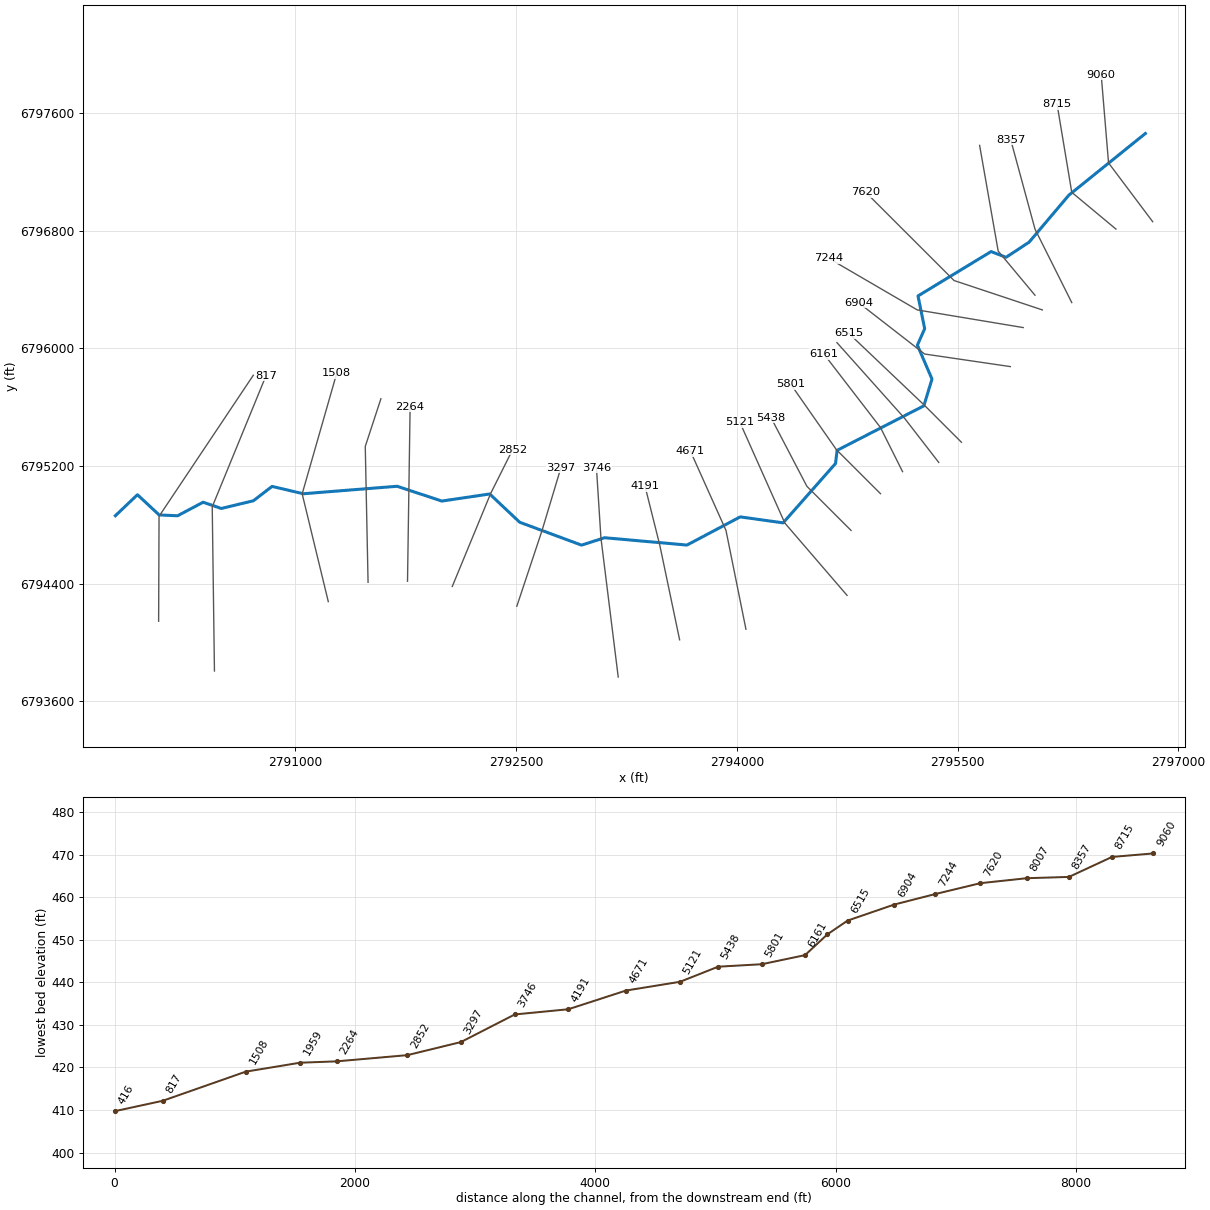
--- Caney Creek T 16.prj (project) ---

Proj Title=Caney Creek T 16 Base Level Engineering
Current Plan=p01
Default Exp/Contr=0.3,0.1
English Units
Geom File=g01
Flow File=f01
Plan File=p01
BEGIN DESCRIPTION:
Caney Creek T 16
END DESCRIPTION:

--- Caney Creek T 16.p01 (plan) ---

Plan Title=Multiple Run
Short Identifier=Multiple
Geom File=g01
Flow File=f01
Subcritical Flow
K Sum by GR= 0
Std Step Tol= 0.01
Critical Tol= 0.01
Num of Std Step Trials= 20
Max Error Tol= 0.3
Flow Tol Ratio= 0.001
Split Flow NTrial= 30
Split Flow Tol= 0.02
Split Flow Ratio= 0.02
Log Output Level= 0
Friction Slope Method= 1
Unsteady Friction Slope Method= 2
Unsteady Bridges Friction Slope Method= 1
Parabolic Critical Depth
Global Vel Dist=  1 , 1 , 1
Global Log Level= 0
CheckData=True
Encroach Param= -1, 0, 0, 0
BEGIN DESCRIPTION:
Multiple Run
END DESCRIPTION:

--- Caney Creek T 16.f01 (steady flow) ---

Flow Title=Multiple
Number of Profiles=7
Profile Names=10-year,25-year,50-year,1pct_min,100-year,1pct_plu,500-year
River Rch & RM= Caney Creek T 16,Reach-1,9060
     600     813     988     597    1191    2377    1737
River Rch & RM= Caney Creek T 16,Reach-1,4671
     936    1298    1602     981    1958    3907    2934
Boundary for River Rch & Prof#=Caney Creek T 16,Reach-1,1
Up Type=0
Dn Type=3
Dn Slope=0.005
Boundary for River Rch & Prof#=Caney Creek T 16,Reach-1,2
Up Type=0
Dn Type=3
Dn Slope=0.005
Boundary for River Rch & Prof#=Caney Creek T 16,Reach-1,3
Up Type=0
Dn Type=3
Dn Slope=0.005
Boundary for River Rch & Prof#=Caney Creek T 16,Reach-1,4
Up Type=0
Dn Type=3
Dn Slope=0.005
Boundary for River Rch & Prof#=Caney Creek T 16,Reach-1,5
Up Type=0
Dn Type=3
Dn Slope=0.005
Boundary for River Rch & Prof#=Caney Creek T 16,Reach-1,6
Up Type=0
Dn Type=3
Dn Slope=0.005
Boundary for River Rch & Prof#=Caney Creek T 16,Reach-1,7
Up Type=0
Dn Type=3
Dn Slope=0.005

--- Caney Creek T 16.g01 (geometry) ---

Geom Title=Existing Conditions

River Reach=Caney Creek T 16,Reach-1
Reach XY= 30
      2796776.00      6797461.00      2796255.91      6797041.21
      2795986.00      6796721.65      2795829.40      6796618.83
      2795727.65      6796657.83      2795231.02      6796355.92
      2795276.37      6796133.80      2795226.93      6796020.85
      2795326.28      6795790.82      2795270.58      6795608.33
      2794681.14      6795305.82      2794670.72      6795216.52
      2794314.45      6794812.55      2794022.59      6794853.19
      2793660.79      6794661.51      2793101.04      6794711.31
      2792944.33      6794661.04      2792523.70      6794816.83
      2792320.15      6795008.94      2791994.43      6794960.82
      2791691.18      6795061.43      2791053.19      6795010.62
      2790841.20      6795060.51      2790714.05      6794962.93
      2790496.04      6794910.42      2790372.68      6794952.95
      2790198.84      6794860.68      2790073.55      6794866.45
      2789926.00      6795003.94      2789776.00      6794861.00

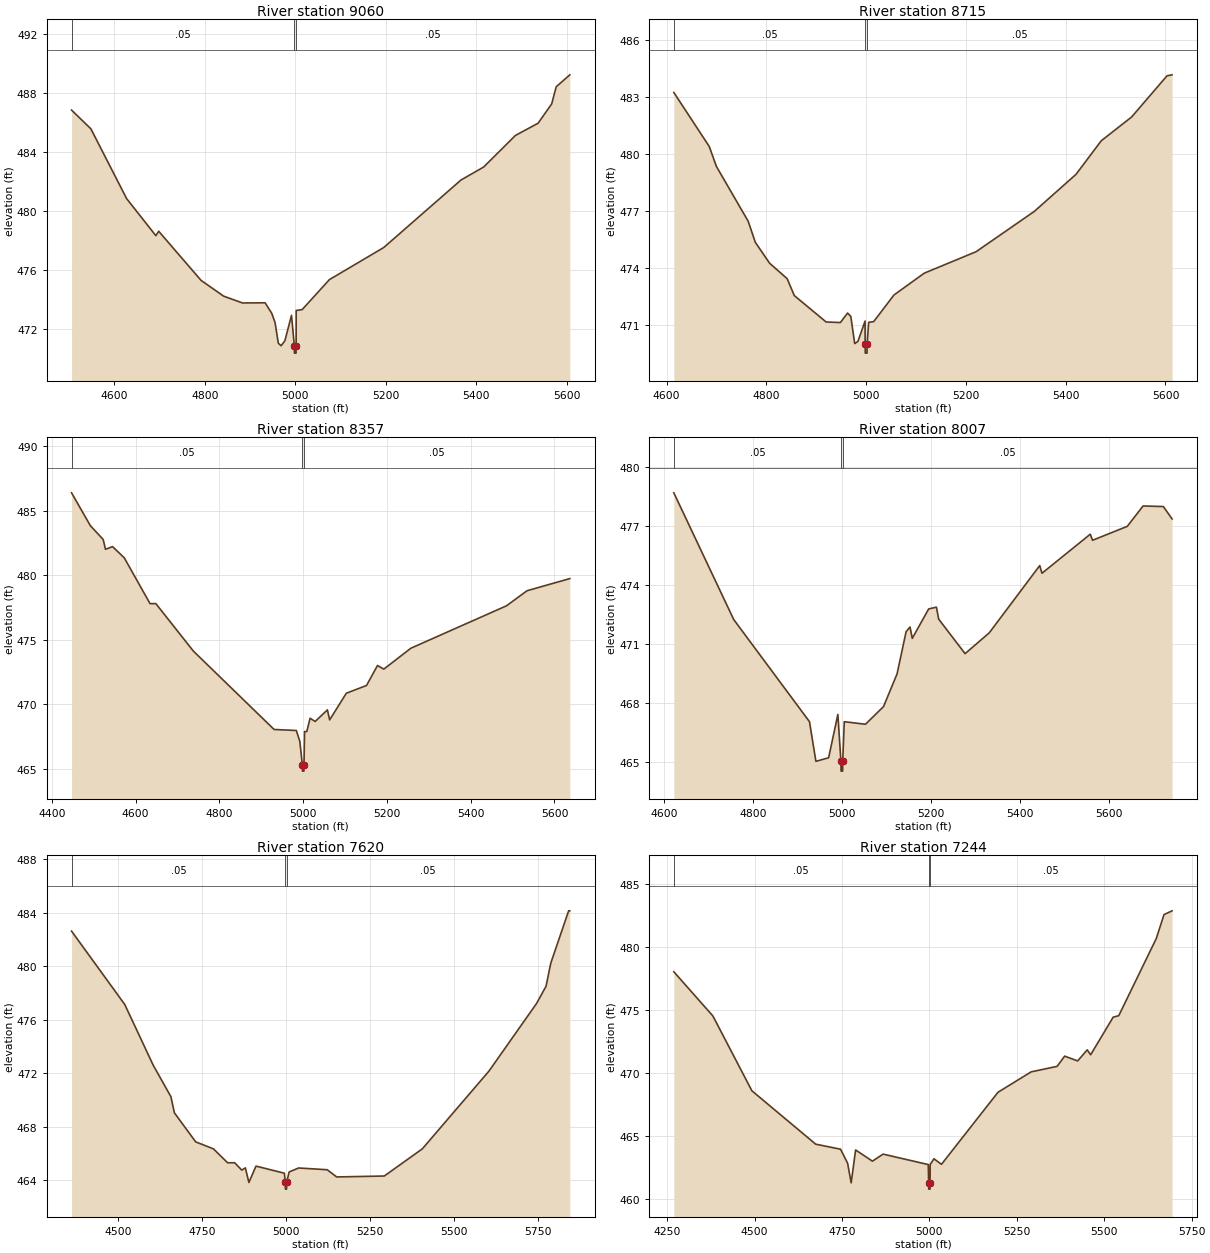
Type RM Length L Ch R = 1,9060,345,345,345
BEGIN DESCRIPTION:
Caney Creek T 16 18.0
END DESCRIPTION:
XS GIS Cut Line= 3
      2796825.98      6796861.03      2796526.00      6797261.00
      2796476.00      6797860.96
#Sta/Elev= 30
  4505.3  486.81  4548.0  485.54  4627.1  480.81  4691.7  478.30  4698.0  478.60
  4791.7  475.27  4841.7  474.20  4883.4  473.74  4933.4  473.75  4948.0  473.04
  4955.3  472.42  4962.6  471.01  4968.8  470.84  4977.1  471.18  4991.7  472.90
  4998.0  470.84  4998.3  470.34  5001.8  470.34  5002.0  470.84  5002.1  473.23
  5015.3  473.29  5075.5  475.32  5195.9  477.50  5366.5  482.07  5416.7  482.95
  5486.9  485.09  5537.1  485.92  5567.2  487.23  5577.2  488.39  5607.3  489.20
#Mann=3,-1,0
  4505.3    0.05       0  4998.0    0.04       0  5002.0    0.05       0
Bank Sta=4998,5002
Exp/Cntr=0.3,0.1

Type RM Length L Ch R = 1,8715,358,358,358
BEGIN DESCRIPTION:
Caney Creek T 16 17.0
END DESCRIPTION:
XS GIS Cut Line= 3
      2796576.04      6796810.97      2796276.00      6797061.00
      2796176.01      6797660.96
#Sta/Elev= 30
  4614.5  483.23  4685.5  480.39  4699.8  479.34  4763.6  476.45  4777.9  475.34
  4806.6  474.24  4841.7  473.43  4856.0  472.54  4919.8  471.15  4948.4  471.12
  4962.8  471.62  4969.3  471.44  4977.1  470.01  4983.6  470.13  4997.9  471.20
  4998.0  470.01  4998.3  469.51  5001.8  469.51  5002.0  470.01  5005.1  471.13
  5015.2  471.17  5055.8  472.57  5116.6  473.72  5220.5  474.85  5337.1  476.97
  5420.7  478.92  5471.4  480.69  5532.2  481.94  5603.2  484.11  5613.3  484.16
#Mann=3,-1,0
  4614.5    0.05       0  4998.0    0.04       0  5002.0    0.05       0
Bank Sta=4998,5002
Exp/Cntr=0.3,0.1

Type RM Length L Ch R = 1,8357,350,350,350
BEGIN DESCRIPTION:
Caney Creek T 16 16.0
END DESCRIPTION:
XS GIS Cut Line= 3
      2796276.00      6796311.01      2796026.00      6796811.00
      2795860.79      6797419.46
#Sta/Elev= 30
  4447.1  486.39  4491.8  483.85  4522.6  482.77  4528.1  482.01  4544.9  482.22
  4572.9  481.35  4634.4  477.80  4648.3  477.80  4737.8  474.12  4930.6  468.04
  4983.7  467.96  4992.1  467.11  4998.0  465.31  4998.3  464.81  5001.8  464.81
  5002.0  465.31  5003.3  467.88  5008.7  467.88  5016.5  468.91  5028.6  468.66
  5057.9  469.56  5063.2  468.78  5103.0  470.85  5151.2  471.45  5177.5  473.00
  5192.6  472.72  5257.1  474.34  5485.5  477.63  5534.6  478.80  5636.6  479.74
#Mann=3,-1,0
  4447.1    0.05       0  4998.0    0.04       0  5002.0    0.05       0
Bank Sta=4998,5002
Exp/Cntr=0.3,0.1

Type RM Length L Ch R = 1,8007,387,387,387
BEGIN DESCRIPTION:
Caney Creek T 16 15.0
END DESCRIPTION:
XS GIS Cut Line= 3
      2796026.00      6796361.00      2795776.00      6796661.00
      2795649.73      6797380.29
#Sta/Elev= 30
  4622.1  478.70  4756.8  472.24  4927.3  467.03  4941.7  465.01  4970.3  465.19
  4991.1  467.40  4998.0  465.01  4998.3  464.51  5001.8  464.51  5002.0  465.01
  5005.5  467.03  5053.2  466.90  5093.8  467.80  5124.3  469.47  5144.6  471.62
  5153.4  471.86  5158.5  471.28  5195.4  472.78  5212.8  472.87  5217.9  472.26
  5277.3  470.50  5331.6  471.56  5445.2  474.99  5450.3  474.60  5558.9  476.59
  5564.0  476.28  5642.1  476.99  5677.7  478.03  5723.3  478.00  5742.9  477.37
#Mann=3,-1,0
  4622.1    0.05       0  4998.0    0.04       0  5002.0    0.05       0
Bank Sta=4998,5002
Exp/Cntr=0.3,0.1

Type RM Length L Ch R = 1,7620,376,376,376
BEGIN DESCRIPTION:
Caney Creek T 16 14.0
END DESCRIPTION:
XS GIS Cut Line= 3
      2796076.02      6796260.99      2795476.00      6796461.00
      2794876.00      6797061.00
#Sta/Elev= 30
  4362.7  482.62  4520.8  477.14  4605.2  472.61  4657.9  470.25  4668.4  469.04
  4731.7  466.87  4784.4  466.35  4826.5  465.31  4847.6  465.31  4868.7  464.76
  4879.2  464.93  4889.8  463.84  4910.9  465.06  4995.2  464.53  4998.0  463.84
  4998.3  463.34  5001.8  463.34  5002.0  463.84  5009.3  464.62  5037.6  464.92
  5122.5  464.79  5150.7  464.25  5292.2  464.32  5405.3  466.35  5603.3  472.16
  5744.7  477.21  5773.0  478.50  5787.1  480.23  5840.2  484.14  5843.7  484.14
#Mann=3,-1,0
  4362.7    0.05       0  4998.0    0.04       0  5002.0    0.05       0
Bank Sta=4998,5002
Exp/Cntr=0.3,0.1

Type RM Length L Ch R = 1,7244,340,340,340
BEGIN DESCRIPTION:
Caney Creek T 16 13.0
END DESCRIPTION:
XS GIS Cut Line= 3
      2795946.16      6796140.91      2795226.00      6796261.00
      2794626.03      6796610.99
#Sta/Elev= 30
  4269.3  478.04  4381.0  474.53  4492.5  468.59  4675.0  464.35  4746.0  463.95
  4766.2  462.84  4776.4  461.28  4789.1  463.89  4837.2  463.00  4867.6  463.56
  4996.9  462.73  4998.0  461.28  4998.3  460.78  5001.8  460.78  5002.0  461.28
  5002.3  462.73  5013.1  463.19  5034.6  462.75  5196.2  468.47  5290.9  470.09
  5365.3  470.53  5386.8  471.34  5424.0  470.96  5451.3  471.84  5461.2  471.45
  5525.7  474.44  5541.5  474.55  5649.0  480.69  5670.9  482.58  5694.0  482.88
#Mann=3,-1,0
  4269.3    0.05       0  4998.0    0.04       0  5002.0    0.05       0
Bank Sta=4998,5002
Exp/Cntr=0.3,0.1

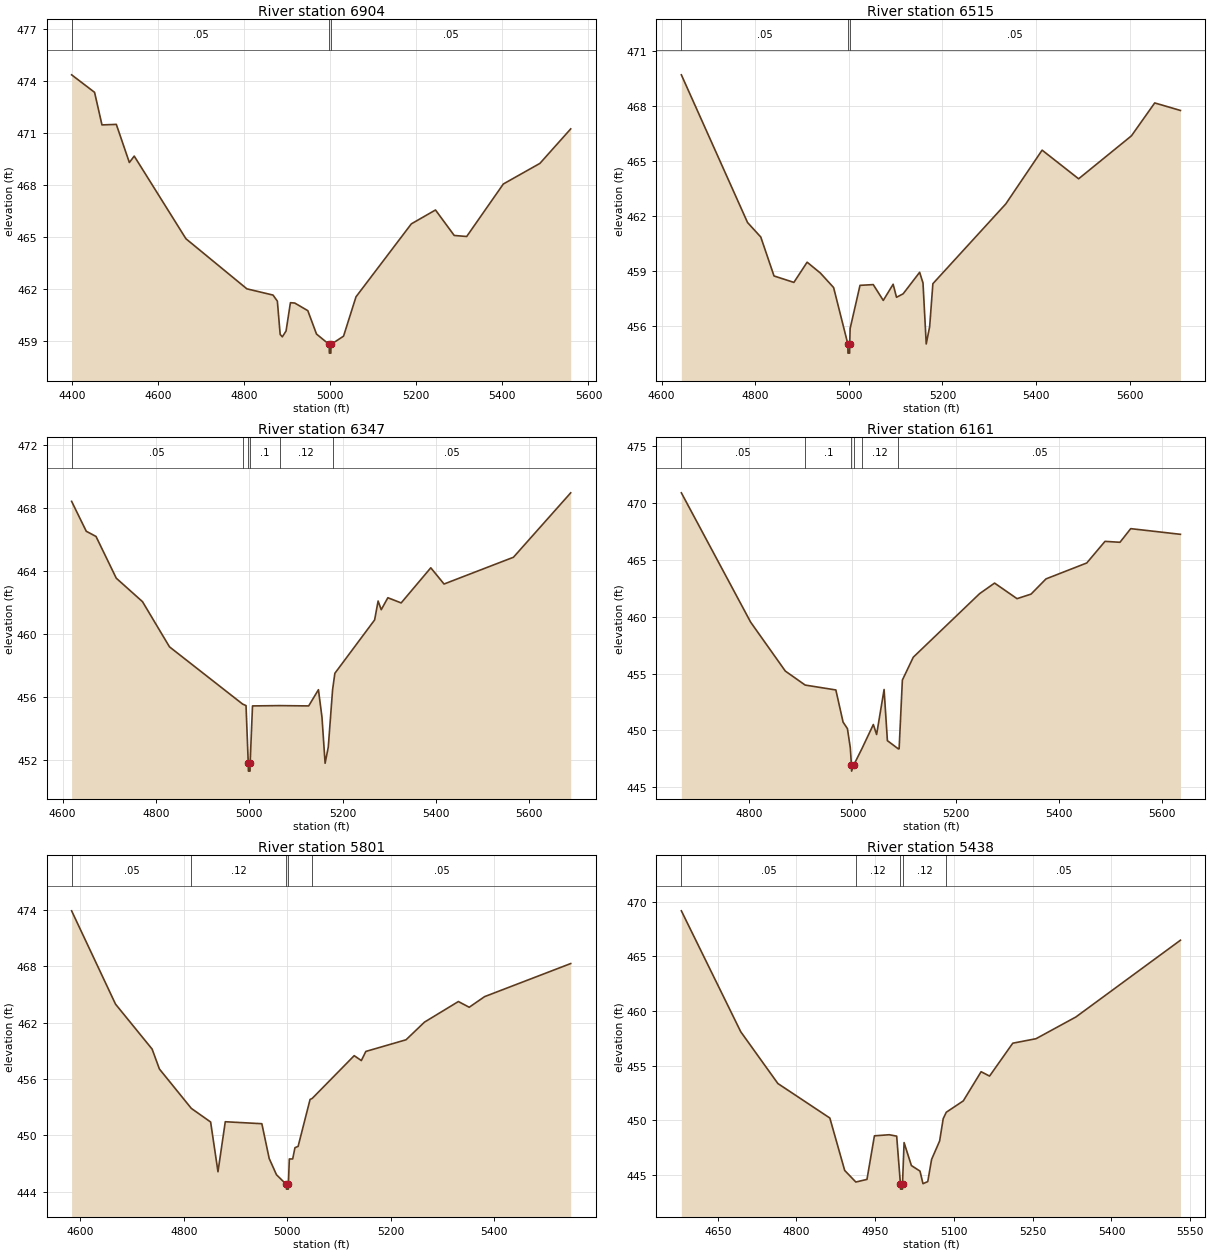
Type RM Length L Ch R = 1,6904,389,389,389
BEGIN DESCRIPTION:
Caney Creek T 16 12.0
END DESCRIPTION:
XS GIS Cut Line= 3
      2795858.70      6795875.44      2795276.00      6795961.00
      2794826.03      6796310.98
#Sta/Elev= 30
  4399.8  474.38  4453.1  473.37  4470.3  471.49  4503.6  471.52  4533.9  469.32
  4545.2  469.69  4665.3  464.92  4806.8  462.03  4867.5  461.67  4877.6  461.32
  4884.1  459.40  4889.1  459.26  4897.8  459.60  4907.9  461.23  4918.0  461.21
  4948.3  460.77  4968.5  459.42  4998.0  458.82  4998.3  458.32  5001.8  458.32
  5002.0  458.82  5031.3  459.30  5060.2  461.57  5188.7  465.78  5244.8  466.58
  5288.3  465.11  5317.2  465.05  5402.3  468.08  5487.3  469.27  5558.8  471.26
#Mann=3,-1,0
  4399.8    0.05       0  4998.0    0.04       0  5002.0    0.05       0
Bank Sta=4998,5002
Exp/Cntr=0.3,0.1

Type RM Length L Ch R = 1,6515,168,168,168
BEGIN DESCRIPTION:
Caney Creek T 16 11.0
END DESCRIPTION:
XS GIS Cut Line= 3
      2795526.00      6795361.00      2795276.00      6795611.00
      2794759.65      6796102.47
#Sta/Elev= 30
  4642.3  469.69  4783.7  461.65  4812.0  460.86  4840.3  458.74  4882.7  458.39
  4911.0  459.49  4939.3  458.90  4967.6  458.11  4998.0  455.04  4998.3  454.54
  5001.8  454.54  5002.0  455.04  5002.9  455.88  5024.0  458.23  5052.3  458.27
  5073.7  457.41  5094.8  458.29  5102.0  457.58  5116.2  457.77  5151.4  458.94
  5158.6  458.36  5165.5  455.04  5172.8  455.98  5179.7  458.32  5335.4  462.66
  5413.1  465.59  5491.1  464.03  5604.0  466.37  5653.7  468.16  5708.7  467.75
#Mann=3,-1,0
  4642.3    0.05       0  4998.0    0.04       0  5002.0    0.05       0
Bank Sta=4998,5002
Exp/Cntr=0.3,0.1

Type RM Length L Ch R = 1,6347,186,186,186
BEGIN DESCRIPTION:
Mapping XS e421f055
END DESCRIPTION:
XS GIS Cut Line= 3
      2795372.03      6795223.46      2795139.24      6795524.56
      2794680.17      6796038.48
#Sta/Elev= 30
  4619.4  468.44  4650.8  466.54  4671.7  466.21  4715.1  463.56  4771.3  462.07
  4829.2  459.20  4985.8  455.57  4993.2  455.47  4998.0  451.81  4998.3  451.31
  5001.8  451.31  5002.0  451.81  5007.1  455.45  5065.0  455.47  5127.5  455.45
  5148.4  456.48  5156.0  454.73  5162.7  451.81  5169.5  452.84  5178.7  456.47
  5183.6  457.52  5268.8  460.91  5276.3  462.11  5283.0  461.56  5297.2  462.32
  5325.7  461.99  5389.2  464.22  5417.6  463.19  5566.4  464.89  5689.1  468.98
#Mann=6,-1,0
  4619.4    0.05       0  4985.8     0.1       0  4998.0    0.07       0
  5002.0     0.1       0  5065.0    0.12       0  5178.7    0.05       0
Bank Sta=4998,5002
Exp/Cntr=0.3,0.1

Type RM Length L Ch R = 1,6161,360,360,360
BEGIN DESCRIPTION:
Caney Creek T 16 10.0
END DESCRIPTION:
XS GIS Cut Line= 3
      2795126.02      6795160.96      2794976.00      6795461.00
      2794591.28      6795960.95
#Sta/Elev= 30
  4668.7  470.90  4802.9  459.52  4870.0  455.22  4908.4  453.99  4967.8  453.56
  4981.8  450.73  4990.2  450.16  4995.8  448.47  4998.0  446.92  4998.3  446.42
  5002.0  446.92  5018.1  448.38  5040.4  450.52  5046.7  449.64  5061.2  453.60
  5067.6  449.10  5089.0  448.37  5090.3  448.39  5096.6  454.43  5117.7  456.44
  5246.1  462.03  5275.1  462.96  5318.6  461.59  5345.7  461.99  5374.7  463.33
  5453.6  464.73  5488.9  466.63  5517.9  466.55  5538.7  467.75  5635.0  467.25
#Mann=6,-1,0
  4668.7    0.05       0  4908.4     0.1       0  4998.0    0.07       0
  5002.0     0.1       0  5018.1    0.12       0  5089.0    0.05       0
Bank Sta=4998,5002
Exp/Cntr=0.3,0.1

Type RM Length L Ch R = 1,5801,363,363,363
BEGIN DESCRIPTION:
Caney Creek T 16 9.0
END DESCRIPTION:
XS GIS Cut Line= 3
      2794976.03      6795010.97      2794676.00      6795311.00
      2794367.02      6795754.35
#Sta/Elev= 30
  4583.0  473.89  4667.9  463.96  4738.6  459.18  4752.7  457.06  4814.4  452.87
  4851.7  451.42  4865.9  446.13  4880.0  451.45  4950.7  451.24  4964.9  447.54
  4979.0  445.81  4998.0  444.78  4998.3  444.28  5001.8  444.28  5002.0  444.78
  5003.8  447.49  5010.3  447.49  5014.7  448.69  5020.8  448.83  5043.9  453.82
  5048.2  453.94  5129.2  458.48  5143.0  457.96  5151.7  458.93  5229.4  460.17
  5265.1  462.05  5330.6  464.24  5351.5  463.63  5381.2  464.76  5547.7  468.28
#Mann=5,-1,0
  4583.0    0.05       0  4814.4    0.12       0  4998.0    0.07       0
  5002.0    0.12       0  5048.2    0.05       0
Bank Sta=4998,5002
Exp/Cntr=0.3,0.1

Type RM Length L Ch R = 1,5438,317,317,317
BEGIN DESCRIPTION:
Caney Creek T 16 8.0
END DESCRIPTION:
XS GIS Cut Line= 3
      2794775.97      6794761.03      2794476.00      6795061.00
      2794232.37      6795527.60
#Sta/Elev= 30
  4580.8  469.18  4693.9  458.11  4764.6  453.37  4863.6  450.21  4891.9  445.41
  4913.1  444.35  4934.3  444.59  4948.5  448.58  4976.7  448.68  4990.9  448.55
  4998.0  444.20  4998.3  443.70  5001.8  443.70  5002.0  444.20  5005.0  447.96
  5018.9  445.86  5035.3  445.35  5041.0  444.20  5050.1  444.39  5057.4  446.42
  5072.7  448.11  5079.5  450.15  5085.4  450.74  5117.8  451.78  5151.7  454.45
  5167.8  454.05  5212.0  457.06  5256.2  457.47  5332.2  459.46  5531.4  466.49
#Mann=5,-1,0
  4580.8    0.05       0  4913.1    0.12       0  4998.0    0.07       0
  5002.0    0.12       0  5085.4    0.05       0
Bank Sta=4998,5002
Exp/Cntr=0.3,0.1

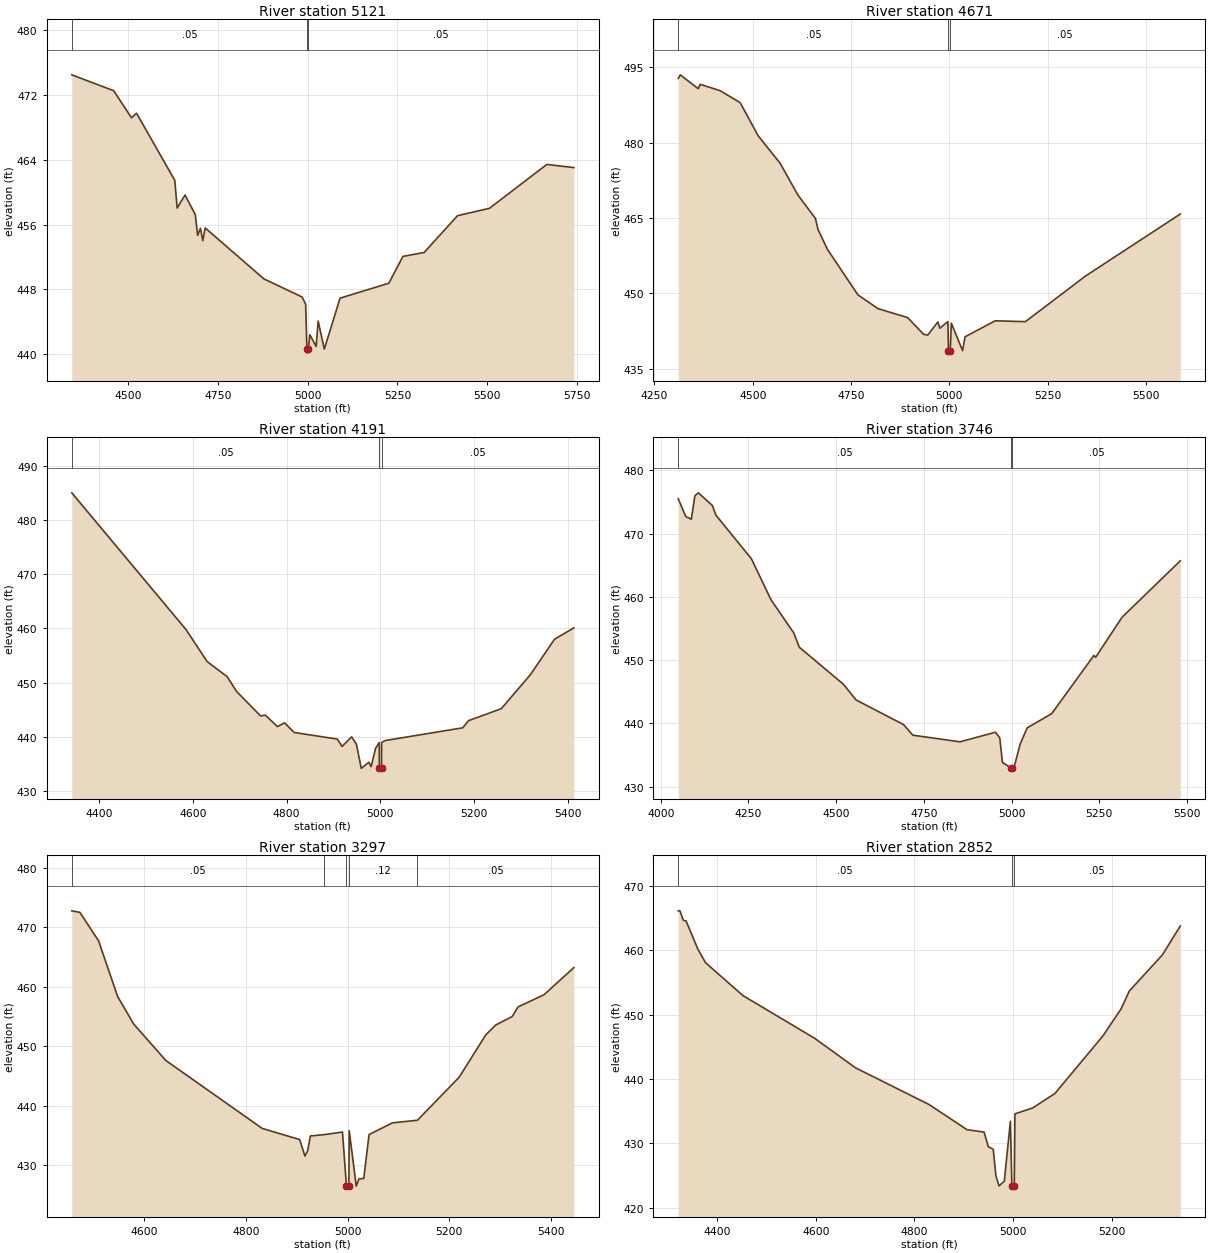
Type RM Length L Ch R = 1,5121,450,450,450
BEGIN DESCRIPTION:
Caney Creek T 16 7.0
END DESCRIPTION:
XS GIS Cut Line= 3
      2794748.75      6794319.34      2794326.00      6794811.00
      2794020.78      6795495.52
#Sta/Elev= 30
  4343.3  474.47  4460.1  472.51  4509.5  469.17  4523.7  469.73  4630.2  461.45
  4636.7  458.04  4658.7  459.65  4687.2  457.23  4693.8  454.67  4701.5  455.55
  4708.1  454.02  4714.8  455.59  4878.1  449.31  4984.6  447.07  4994.5  446.18
  4998.0  440.65  4998.3  440.15  5002.0  440.65  5006.1  442.43  5023.8  440.97
  5029.3  444.10  5046.5  440.65  5090.3  446.93  5226.1  448.77  5265.4  452.08
  5324.4  452.56  5417.3  457.10  5506.3  458.01  5666.0  463.42  5741.2  463.03
#Mann=3,-1,0
  4343.3    0.05       0  4998.0    0.04       0  5002.0    0.05       0
Bank Sta=4998,5002
Exp/Cntr=0.3,0.1

Type RM Length L Ch R = 1,4671,480,480,480
BEGIN DESCRIPTION:
Caney Creek T 16 6.0
END DESCRIPTION:
XS GIS Cut Line= 3
      2794061.60      6794088.88      2793926.00      6794761.00
      2793684.16      6795300.52
#Sta/Elev= 30
  4310.4  492.81  4315.6  493.53  4361.2  490.77  4366.3  491.64  4417.1  490.37
  4467.9  487.99  4513.6  481.40  4569.5  475.91  4615.2  469.53  4659.4  464.91
  4666.0  462.69  4690.0  458.74  4767.5  449.69  4818.3  446.96  4894.0  445.16
  4934.8  441.81  4945.1  441.70  4970.7  444.30  4975.8  443.05  4996.1  444.38
  4997.7  438.59  4998.2  438.09  5002.3  438.59  5004.9  444.06  5033.6  438.59
  5039.9  441.35  5116.6  444.53  5193.3  444.36  5345.9  453.43  5587.3  465.80
#Mann=3,-1,0
  4310.4    0.05       0  4997.7    0.04       0  5002.3    0.05       0
Bank Sta=4997.7,5002.3
Exp/Cntr=0.3,0.1

Type RM Length L Ch R = 1,4191,445,445,445
BEGIN DESCRIPTION:
Caney Creek T 16 5.0
END DESCRIPTION:
XS GIS Cut Line= 3
      2793610.86      6794017.04      2793476.00      6794661.00
      2793376.01      6795060.96
#Sta/Elev= 30
  4342.1  484.99  4585.8  459.77  4630.6  453.89  4673.1  451.12  4693.5  448.37
  4744.6  443.86  4754.8  444.01  4780.4  441.90  4795.7  442.60  4816.1  440.81
  4908.1  439.60  4918.3  438.24  4938.7  440.01  4948.9  438.64  4959.2  434.19
  4975.1  435.32  4980.2  434.53  4989.8  437.91  4997.5  438.96  4997.7  434.19
  4998.2  433.69  5002.4  434.19  5002.6  438.96  5010.3  439.33  5175.3  441.67
  5188.1  443.00  5257.7  445.20  5319.6  451.46  5371.1  458.00  5412.3  460.10
#Mann=3,-1,0
  4342.1    0.05       0  4997.7    0.04       0  5002.4    0.05       0
Bank Sta=4997.7,5002.4
Exp/Cntr=0.3,0.1

Type RM Length L Ch R = 1,3746,449,449,449
BEGIN DESCRIPTION:
Caney Creek T 16 4.0
END DESCRIPTION:
XS GIS Cut Line= 3
      2793193.55      6793763.99      2793076.00      6794711.00
      2793045.61      6795186.66
#Sta/Elev= 30
  4049.8  475.52  4071.2  472.71  4087.1  472.28  4097.2  475.97  4107.2  476.45
  4147.1  474.44  4157.6  472.89  4258.4  466.02  4313.9  459.58  4379.3  454.29
  4394.8  452.05  4520.4  446.21  4556.6  443.72  4691.7  439.83  4718.4  438.15
  4852.9  437.10  4953.7  438.62  4966.1  437.74  4973.8  433.85  4997.7  432.97
  4998.2  432.47  5002.4  432.97  5006.6  432.99  5024.1  436.72  5044.2  439.30
  5114.3  441.56  5234.4  450.75  5239.4  450.46  5314.7  456.79  5480.7  465.71
#Mann=3,-1,0
  4049.8    0.05       0  4997.7    0.04       0  5002.4    0.05       0
Bank Sta=4997.7,5002.4
Exp/Cntr=0.3,0.1

Type RM Length L Ch R = 1,3297,445,445,445
BEGIN DESCRIPTION:
Caney Creek T 16 3.0
END DESCRIPTION:
XS GIS Cut Line= 3
      2792504.53      6794245.31      2792676.00      6794761.00
      2792803.94      6795187.05
#Sta/Elev= 30
  4456.9  472.77  4472.8  472.52  4509.7  467.72  4547.2  458.36  4578.8  453.73
  4642.0  447.61  4831.7  436.18  4905.5  434.30  4915.9  431.53  4921.2  432.42
  4926.6  434.91  4954.2  435.14  4989.8  435.57  4997.6  426.47  4998.2  425.97
  5002.4  426.47  5003.0  435.81  5016.9  426.47  5022.1  427.68  5031.7  427.77
  5042.1  435.14  5088.2  437.12  5137.3  437.55  5219.6  444.80  5271.8  451.91
  5291.7  453.58  5324.0  455.01  5335.2  456.60  5386.7  458.67  5445.2  463.22
#Mann=5,-1,0
  4456.9    0.05       0  4954.2    0.12       0  4997.6    0.07       0
  5002.4    0.12       0  5137.3    0.05       0
Bank Sta=4997.6,5002.4
Exp/Cntr=0.3,0.1

Type RM Length L Ch R = 1,2852,588,588,588
BEGIN DESCRIPTION:
Caney Creek T 16 2.0
END DESCRIPTION:
XS GIS Cut Line= 3
      2792065.62      6794379.66      2792326.00      6795011.00
      2792475.98      6795310.97
#Sta/Elev= 30
  4320.9  466.14  4324.3  466.14  4331.4  464.66  4336.8  464.57  4360.7  460.19
  4376.4  458.07  4452.2  452.97  4597.7  446.33  4680.4  441.75  4829.3  436.06
  4906.5  432.14  4941.3  431.76  4949.7  429.50  4959.8  429.08  4965.2  424.99
  4971.4  423.40  4982.2  424.13  4994.6  433.45  4997.6  423.40  4998.2  422.90
  5001.9  422.90  5002.5  423.40  5003.8  434.59  5040.2  435.53  5084.9  437.76
  5182.7  446.75  5219.0  450.90  5235.8  453.68  5302.9  459.30  5339.2  463.79
#Mann=3,-1,0
  4320.9    0.05       0  4997.6    0.04       0  5002.5    0.05       0
Bank Sta=4997.6,5002.5
Exp/Cntr=0.3,0.1

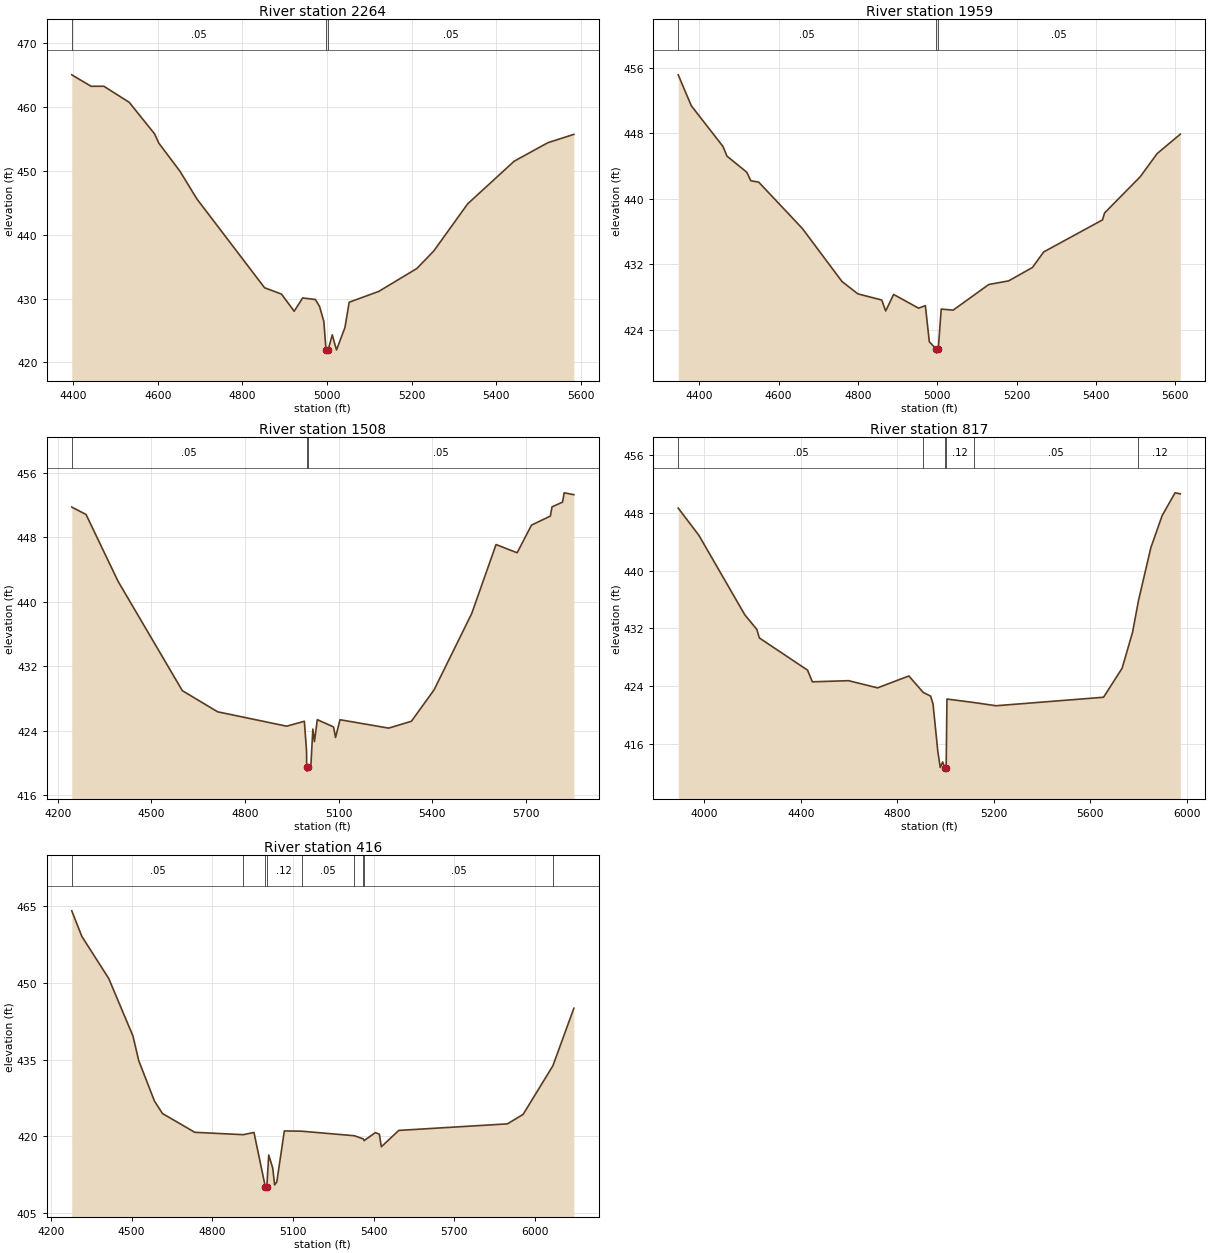
Type RM Length L Ch R = 1,2264,305,305,305
BEGIN DESCRIPTION:
Mapping XS dca348f6
END DESCRIPTION:
XS GIS Cut Line= 2
      2791761.50      6794415.25      2791779.21      6795602.02
#Sta/Elev= 30
  4396.4  465.08  4442.2  463.28  4472.2  463.29  4532.2  460.77  4592.2  455.82
  4602.2  454.37  4652.2  449.96  4692.2  445.62  4852.2  431.69  4892.2  430.70
  4922.2  428.01  4942.2  430.09  4972.2  429.85  4982.2  428.75  4992.2  426.43
  4997.5  421.94  4998.2  421.44  5001.9  421.44  5002.5  421.94  5012.2  424.31
  5022.2  421.94  5042.2  425.45  5052.2  429.42  5122.2  431.12  5212.2  434.71
  5252.2  437.46  5332.3  444.85  5442.3  451.54  5522.3  454.45  5583.3  455.74
#Mann=3,-1,0
  4396.4    0.05       0  4997.5    0.04       0  5002.5    0.05       0
Bank Sta=4997.5,5002.5
Exp/Cntr=0.3,0.1

Type RM Length L Ch R = 1,1959,451,451,451
BEGIN DESCRIPTION:
Mapping XS 8197d4b0
END DESCRIPTION:
XS GIS Cut Line= 3
      2791493.43      6794408.15      2791474.40      6795332.45
      2791580.73      6795656.67
#Sta/Elev= 30
  4347.0  455.17  4379.9  451.39  4459.9  446.40  4469.9  445.22  4519.9  443.25
  4529.9  442.21  4549.9  442.04  4659.9  436.37  4759.9  429.88  4799.9  428.37
  4860.0  427.62  4870.0  426.28  4890.0  428.30  4952.9  426.62  4970.0  426.93
  4980.0  422.51  4997.5  421.62  4998.1  421.12  5002.5  421.62  5010.0  426.51
  5040.0  426.38  5130.0  429.52  5180.0  429.96  5240.0  431.60  5268.3  433.50
  5416.5  437.42  5421.8  438.27  5512.0  442.72  5554.4  445.54  5612.7  447.91
#Mann=3,-1,0
  4347.0    0.05       0  4997.5    0.04       0  5002.5    0.05       0
Bank Sta=4997.5,5002.5
Exp/Cntr=0.3,0.1

Type RM Length L Ch R = 1,1508,691,691,691
BEGIN DESCRIPTION:
Mapping XS d36ccdc1
END DESCRIPTION:
XS GIS Cut Line= 3
      2791223.10      6794276.57      2791045.62      6795009.84
      2791280.78      6795831.50
#Sta/Elev= 30
  4244.6  451.74  4290.3  450.83  4393.2  442.53  4599.0  428.99  4712.2  426.37
  4933.5  424.59  4990.0  425.20  4997.1  421.47  4997.5  419.52  4998.1  419.02
  5002.5  419.52  5010.7  419.52  5017.2  424.23  5022.4  422.68  5031.5  425.40
  5083.5  424.50  5090.0  423.19  5104.3  425.39  5260.3  424.35  5333.1  425.20
  5405.9  429.10  5526.5  438.56  5604.4  447.10  5672.0  446.08  5718.0  449.51
  5778.5  450.63  5783.7  451.77  5817.5  452.36  5822.7  453.51  5853.7  453.28
#Mann=3,-1,0
  4244.6    0.05       0  4997.5    0.04       0  5002.5    0.05       0
Bank Sta=4997.5,5002.5
Exp/Cntr=0.3,0.1

Type RM Length L Ch R = 1,817,401,401,401
BEGIN DESCRIPTION:
Mapping XS 95c1f127
END DESCRIPTION:
XS GIS Cut Line= 3
      2790449.37      6793804.94      2790434.33      6794921.62
      2790800.15      6795814.18
#Sta/Elev= 30
  3892.1  448.66  3978.2  444.86  4168.2  433.85  4218.2  431.82  4228.2  430.65
  4428.2  426.18  4448.2  424.56  4598.2  424.72  4718.2  423.72  4848.2  425.37
  4907.7  423.09  4938.3  422.58  4948.3  421.51  4968.3  414.89  4978.3  412.67
  4988.3  413.44  4997.2  412.67  4998.1  412.17  5002.9  412.67  5006.1  422.17
  5117.5  421.69  5209.6  421.24  5655.3  422.42  5732.3  426.45  5775.5  431.43
  5800.0  435.81  5851.2  443.15  5898.2  447.62  5951.6  450.78  5973.5  450.64
#Mann=6,-1,0
  3892.1    0.05       0  4907.7    0.12       0  4997.2    0.07       0
  5002.9    0.12       0  5117.5    0.05       0  5800.0    0.12       0
Bank Sta=4997.2,5002.9
Exp/Cntr=0.3,0.1

Type RM Length L Ch R = 1,416,0,0,0
BEGIN DESCRIPTION:
Caney Creek T 16 1.0
END DESCRIPTION:
XS GIS Cut Line= 3
      2790070.03      6794143.42      2790072.86      6794857.09
      2790713.30      6795816.37
#Sta/Elev= 30
  4277.5  464.04  4315.1  459.04  4415.1  450.82  4505.1  439.60  4526.4  434.82
  4585.1  426.89  4615.1  424.46  4735.1  420.80  4915.3  420.34  4955.1  420.77
  4997.1  410.21  4998.1  409.71  5002.9  410.21  5009.9  416.37  5024.9  413.82
  5031.9  410.53  5039.9  411.10  5068.0  421.07  5132.2  421.02  5328.7  420.13
  5361.7  419.51  5364.6  419.18  5406.4  420.74  5421.4  420.44  5428.7  417.98
  5493.5  421.17  5897.7  422.45  5956.1  424.31  6066.7  433.79  6144.6  445.02
#Mann=9,-1,0
  4277.5    0.05       0  4915.3    0.12       0  4997.1    0.07       0
  5002.9    0.12       0  5132.2    0.05       0  5328.7    0.12       0
  5361.7     0.1       0  5364.6    0.05       0  6066.7    0.12       0
Bank Sta=4997.1,5002.9
Exp/Cntr=0.3,0.1

Chan Stop Cuts=-1