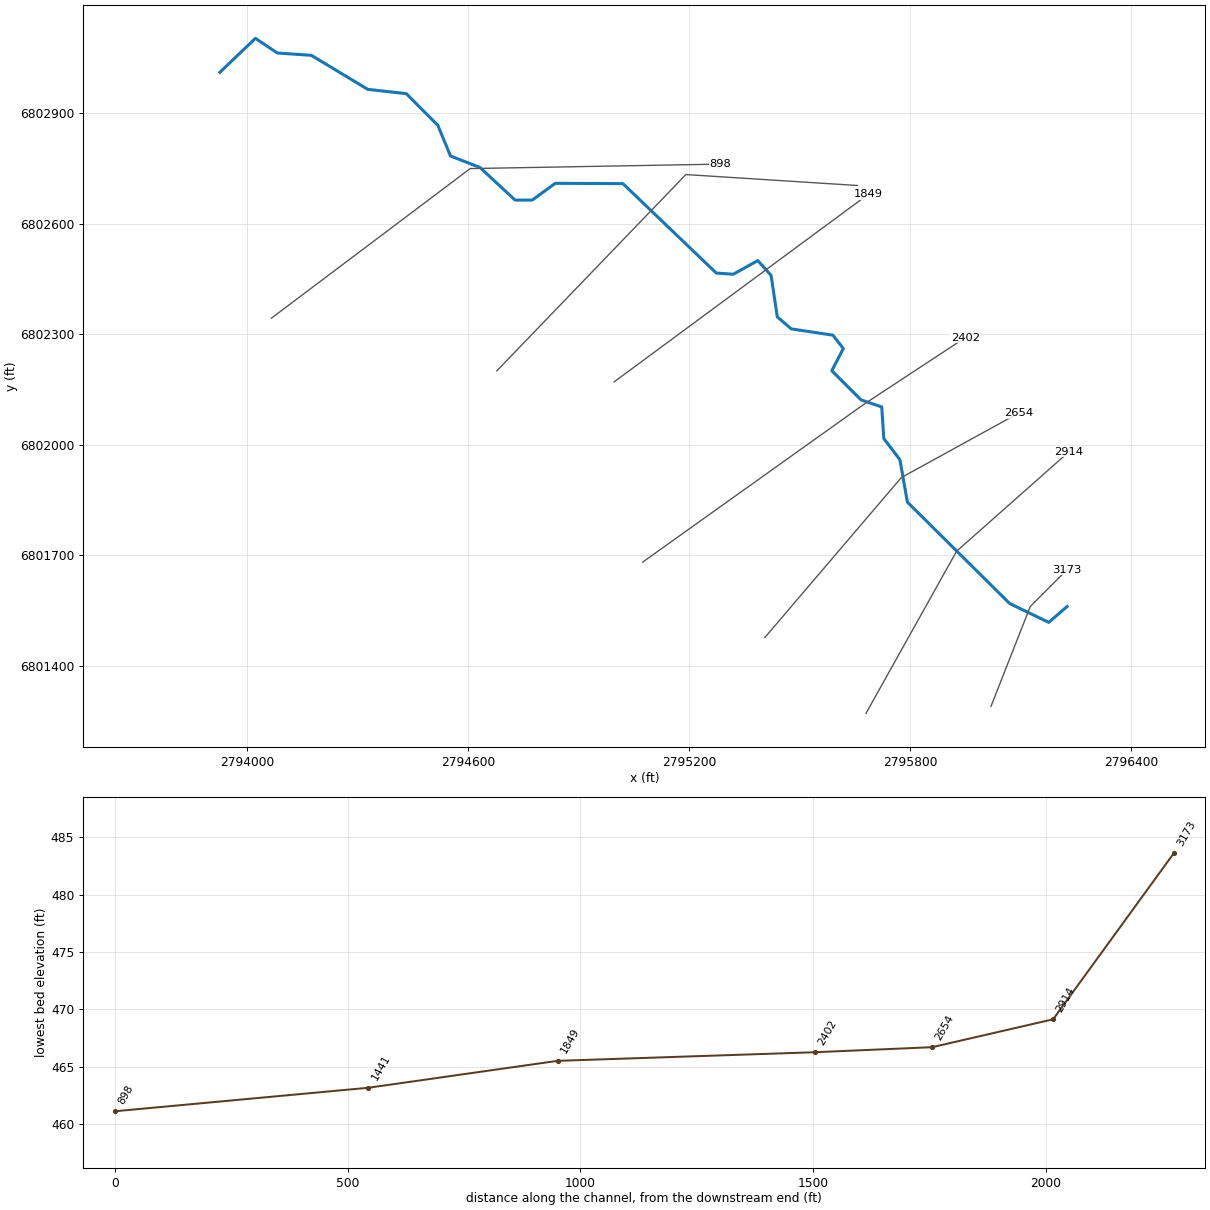
--- Caney Creek T 17.prj (project) ---

Proj Title=Caney Creek T 17 Base Level Engineering
Current Plan=p01
Default Exp/Contr=0.3,0.1
English Units
Geom File=g01
Flow File=f01
Plan File=p01
BEGIN DESCRIPTION:
Caney Creek T 17
END DESCRIPTION:

--- Caney Creek T 17.p01 (plan) ---

Plan Title=Multiple Run
Short Identifier=Multiple
Geom File=g01
Flow File=f01
Subcritical Flow
K Sum by GR= 0
Std Step Tol= 0.01
Critical Tol= 0.01
Num of Std Step Trials= 20
Max Error Tol= 0.3
Flow Tol Ratio= 0.001
Split Flow NTrial= 30
Split Flow Tol= 0.02
Split Flow Ratio= 0.02
Log Output Level= 0
Friction Slope Method= 1
Unsteady Friction Slope Method= 2
Unsteady Bridges Friction Slope Method= 1
Parabolic Critical Depth
Global Vel Dist=  1 , 1 , 1
Global Log Level= 0
CheckData=True
Encroach Param= -1, 0, 0, 0
BEGIN DESCRIPTION:
Multiple Run
END DESCRIPTION:

--- Caney Creek T 17.f01 (steady flow) ---

Flow Title=Multiple
Number of Profiles=7
Profile Names=10-year,25-year,50-year,1pct_min,100-year,1pct_plu,500-year
River Rch & RM= Caney Creek T 17,Reach-1,3173
     153     188     214     122     243     485     312
Boundary for River Rch & Prof#=Caney Creek T 17,Reach-1,1
Up Type=0
Dn Type=3
Dn Slope=0.005
Boundary for River Rch & Prof#=Caney Creek T 17,Reach-1,2
Up Type=0
Dn Type=3
Dn Slope=0.005
Boundary for River Rch & Prof#=Caney Creek T 17,Reach-1,3
Up Type=0
Dn Type=3
Dn Slope=0.005
Boundary for River Rch & Prof#=Caney Creek T 17,Reach-1,4
Up Type=0
Dn Type=3
Dn Slope=0.005
Boundary for River Rch & Prof#=Caney Creek T 17,Reach-1,5
Up Type=0
Dn Type=3
Dn Slope=0.005
Boundary for River Rch & Prof#=Caney Creek T 17,Reach-1,6
Up Type=0
Dn Type=3
Dn Slope=0.005
Boundary for River Rch & Prof#=Caney Creek T 17,Reach-1,7
Up Type=0
Dn Type=3
Dn Slope=0.005

--- Caney Creek T 17.g01 (geometry) ---

Geom Title=Existing Conditions

River Reach=Caney Creek T 17,Reach-1
Reach XY= 30
      2796226.00      6801561.00      2796176.12      6801517.87
      2796069.95      6801569.12      2795792.46      6801844.25
      2795772.14      6801959.41      2795728.39      6802017.06
      2795722.83      6802102.66      2795666.58      6802121.90
      2795587.24      6802200.99      2795618.54      6802261.24
      2795590.09      6802297.59      2795477.26      6802314.51
      2795439.23      6802347.28      2795422.39      6802459.98
      2795386.43      6802500.04      2795319.96      6802462.99
      2795273.71      6802466.12      2795020.15      6802708.94
      2794836.50      6802709.76      2794774.25      6802664.34
      2794727.64      6802664.14      2794632.02      6802752.81
      2794552.16      6802783.86      2794517.84      6802867.05
      2794432.19      6802953.15      2794327.59      6802964.83
      2794174.41      6803057.18      2794081.89      6803063.56
      2794022.58      6803103.33      2793926.00      6803011.00

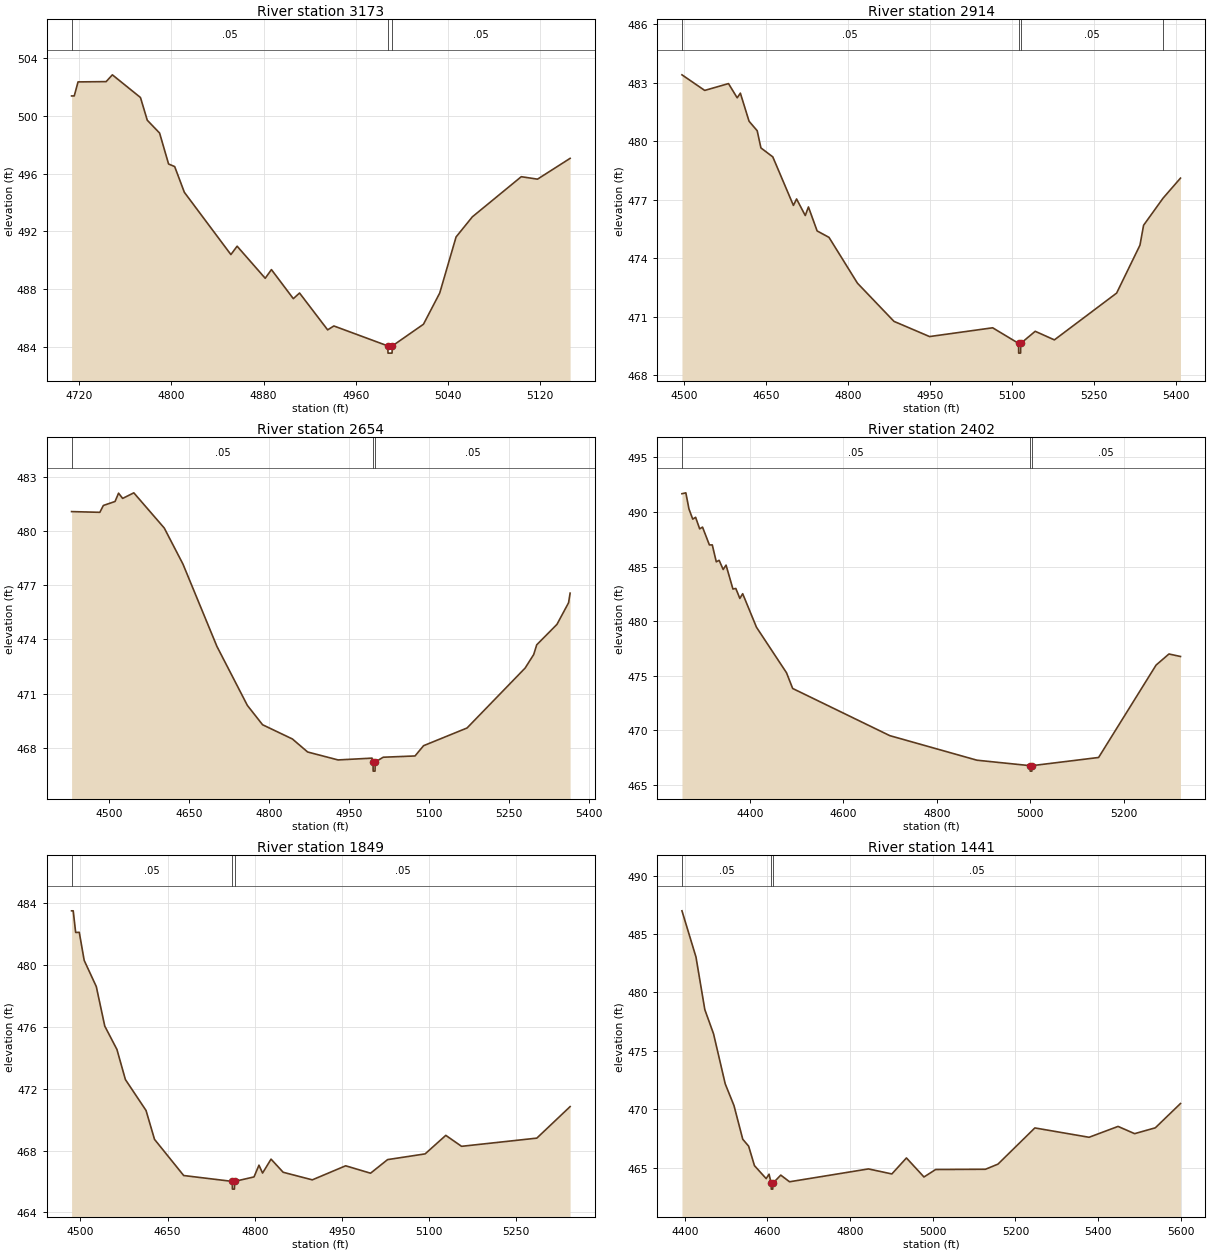
Type RM Length L Ch R = 1,3173,259,259,259
BEGIN DESCRIPTION:
Caney Creek T 17 5.0
END DESCRIPTION:
XS GIS Cut Line= 3
      2796019.32      6801289.87      2796126.00      6801561.00
      2796226.01      6801661.01
#Sta/Elev= 30
  4713.3  501.38  4715.6  501.38  4718.9  502.35  4743.3  502.37  4748.7  502.84
  4773.1  501.27  4779.0  499.70  4789.7  498.81  4797.5  496.67  4802.8  496.49
  4811.2  494.71  4851.6  490.40  4857.0  490.98  4881.4  488.76  4886.8  489.36
  4905.8  487.35  4911.2  487.74  4935.6  485.19  4941.0  485.46  4987.8  484.08
  4988.0  483.58  4991.5  483.58  4991.8  484.08  5018.8  485.58  5032.9  487.74
  5047.1  491.62  5061.2  493.01  5103.7  495.79  5117.8  495.62  5146.1  497.06
#Mann=3,-1,0
  4713.3    0.05       0  4987.8    0.04       0  4991.8    0.05       0
Bank Sta=4987.8,4991.8
Exp/Cntr=0.3,0.1

Type RM Length L Ch R = 1,2914,260,260,260
BEGIN DESCRIPTION:
Caney Creek T 17 4.0
END DESCRIPTION:
XS GIS Cut Line= 3
      2795680.01      6801270.85      2795926.00      6801711.00
      2796231.12      6801981.08
#Sta/Elev= 30
  4495.8  483.41  4537.4  482.61  4580.9  482.96  4596.8  482.23  4602.6  482.47
  4618.5  481.03  4633.4  480.54  4640.2  479.66  4661.9  479.20  4699.6  476.71
  4705.4  477.04  4721.3  476.19  4727.1  476.63  4743.0  475.40  4764.7  475.07
  4816.7  472.72  4883.5  470.76  4948.6  469.98  5064.0  470.43  5111.4  469.63
  5111.6  469.13  5115.1  469.13  5115.4  469.63  5141.8  470.25  5176.9  469.81
  5290.7  472.21  5333.4  474.67  5340.0  475.69  5375.6  477.08  5407.5  478.11
#Mann=4,-1,0
  4495.8    0.05       0  5111.4    0.04       0  5115.4    0.05       0
  5375.6    0.12       0
Bank Sta=5111.4,5115.4
Exp/Cntr=0.3,0.1

Type RM Length L Ch R = 1,2654,252,252,252
BEGIN DESCRIPTION:
Caney Creek T 17 3.0
END DESCRIPTION:
XS GIS Cut Line= 3
      2795405.59      6801476.90      2795776.00      6801911.00
      2796095.35      6802086.38
#Sta/Elev= 30
  4429.4  481.08  4482.4  481.04  4489.0  481.42  4510.9  481.64  4517.5  482.10
  4525.2  481.81  4546.1  482.12  4603.2  480.17  4638.3  478.17  4702.0  473.61
  4759.1  470.34  4787.6  469.27  4843.6  468.48  4872.1  467.76  4929.2  467.32
  4992.9  467.42  4994.8  467.20  4995.0  466.70  4998.5  466.70  4998.8  467.20
  5013.8  467.47  5073.5  467.54  5089.6  468.11  5171.1  469.09  5280.0  472.41
  5296.1  473.16  5301.8  473.70  5339.7  474.83  5361.5  476.03  5364.4  476.56
#Mann=3,-1,0
  4429.4    0.05       0  4994.8    0.04       0  4998.8    0.05       0
Bank Sta=4994.8,4998.8
Exp/Cntr=0.3,0.1

Type RM Length L Ch R = 1,2402,553,553,553
BEGIN DESCRIPTION:
Caney Creek T 17 2.0
END DESCRIPTION:
XS GIS Cut Line= 3
      2795073.79      6801681.45      2795676.00      6802111.00
      2795949.67      6802290.88
#Sta/Elev= 30
  4254.4  491.67  4262.7  491.75  4269.4  490.27  4277.5  489.34  4283.6  489.51
  4292.3  488.45  4298.4  488.61  4313.1  486.98  4319.3  486.98  4327.9  485.43
  4334.0  485.57  4342.6  484.73  4348.8  485.13  4363.5  482.94  4369.7  482.99
  4378.3  482.08  4384.4  482.51  4413.9  479.44  4478.2  475.27  4491.4  473.83
  4699.3  469.51  4885.9  467.26  4999.7  466.76  4999.9  466.26  5003.4  466.26
  5003.7  466.76  5146.3  467.51  5269.3  475.97  5296.9  476.99  5321.6  476.76
#Mann=3,-1,0
  4254.4    0.05       0  4999.7    0.04       0  5003.7    0.05       0
Bank Sta=4999.7,5003.7
Exp/Cntr=0.3,0.1

Type RM Length L Ch R = 1,1849,408,408,408
BEGIN DESCRIPTION:
Mapping XS 09e0a254
END DESCRIPTION:
XS GIS Cut Line= 2
      2794996.57      6802170.91      2795686.71      6802680.36
#Sta/Elev= 30
  4484.8  483.52  4487.6  483.52  4491.8  482.12  4498.0  482.13  4506.5  480.31
  4527.3  478.62  4541.9  476.06  4562.8  474.55  4577.4  472.60  4612.9  470.60
  4627.5  468.73  4677.7  466.39  4761.3  466.01  4761.5  465.51  4765.0  465.51
  4765.3  466.01  4798.7  466.30  4807.2  467.06  4813.4  466.55  4828.0  467.45
  4848.9  466.60  4899.0  466.11  4956.4  467.02  4999.2  466.54  5028.5  467.42
  5093.1  467.79  5128.7  468.99  5155.8  468.28  5285.3  468.81  5342.6  470.85
#Mann=3,-1,0
  4484.8    0.05       0  4761.3    0.04       0  4765.3    0.05       0
Bank Sta=4761.3,4765.3
Exp/Cntr=0.3,0.1

Type RM Length L Ch R = 1,1441,543,543,543
BEGIN DESCRIPTION:
Mapping XS 1423b8bc
END DESCRIPTION:
XS GIS Cut Line= 3
      2794678.08      6802200.90      2795191.13      6802733.55
      2795656.74      6802703.84
#Sta/Elev= 30
  4393.1  486.99  4427.0  483.04  4448.4  478.53  4469.5  476.46  4497.8  472.17
  4518.9  470.32  4540.2  467.43  4554.4  466.84  4568.5  465.17  4596.8  464.06
  4603.8  464.44  4609.0  463.66  4609.2  463.16  4612.7  463.16  4613.0  463.66
  4632.1  464.36  4653.4  463.79  4844.3  464.89  4900.9  464.46  4936.2  465.83
  4978.6  464.20  5006.9  464.84  5127.3  464.86  5157.6  465.30  5246.9  468.40
  5378.0  467.60  5448.2  468.53  5488.2  467.91  5538.3  468.41  5599.2  470.49
#Mann=3,-1,0
  4393.1    0.05       0  4609.0    0.04       0  4613.0    0.05       0
Bank Sta=4609,4613
Exp/Cntr=0.3,0.1

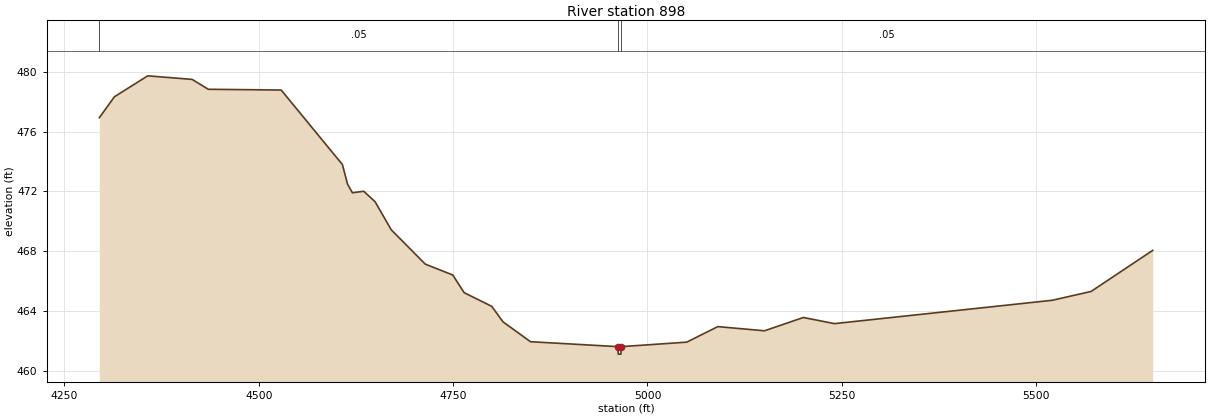
Type RM Length L Ch R = 1,898,0,0,0
BEGIN DESCRIPTION:
Caney Creek T 17 1.0
END DESCRIPTION:
XS GIS Cut Line= 3
      2794066.21      6802343.78      2794605.66      6802749.77
      2795285.29      6802761.92
#Sta/Elev= 30
  4295.0  476.93  4314.4  478.33  4357.3  479.73  4414.4  479.49  4435.2  478.83
  4528.9  478.78  4607.6  473.80  4614.3  472.48  4620.5  471.91  4635.1  472.01
  4649.7  471.31  4670.5  469.43  4714.2  467.14  4749.6  466.41  4764.2  465.23
  4799.6  464.32  4814.2  463.28  4849.6  461.95  4962.1  461.62  4962.4  461.12
  4965.9  461.12  4966.1  461.62  5050.5  461.92  5090.5  462.96  5150.5  462.68
  5200.5  463.57  5240.5  463.16  5520.6  464.72  5570.6  465.31  5649.9  468.06
#Mann=3,-1,0
  4295.0    0.05       0  4962.1    0.04       0  4966.1    0.05       0
Bank Sta=4962.1,4966.1
Exp/Cntr=0.3,0.1

Chan Stop Cuts=-1