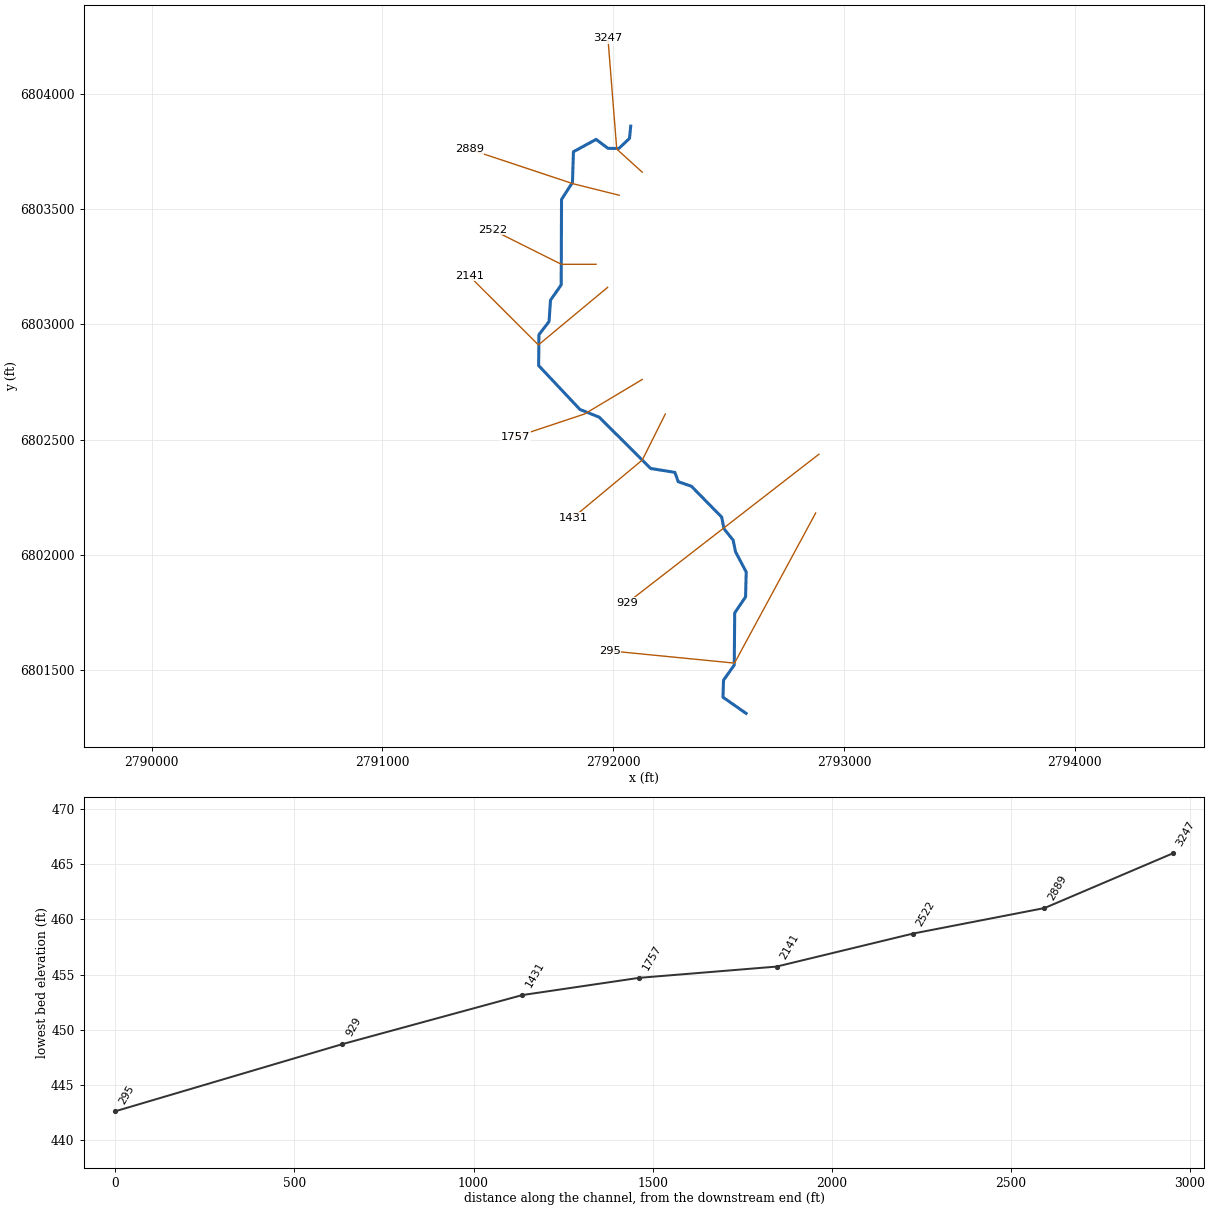
--- Caney Creek T 18.prj (project) ---

Proj Title=Caney Creek T 18 Base Level Engineering
Current Plan=p01
Default Exp/Contr=0.3,0.1
English Units
Geom File=g01
Flow File=f01
Plan File=p01
BEGIN DESCRIPTION:
Caney Creek T 18
END DESCRIPTION:

--- Caney Creek T 18.p01 (plan) ---

Plan Title=Multiple Run
Short Identifier=Multiple
Geom File=g01
Flow File=f01
Subcritical Flow
K Sum by GR= 0
Std Step Tol= 0.01
Critical Tol= 0.01
Num of Std Step Trials= 20
Max Error Tol= 0.3
Flow Tol Ratio= 0.001
Split Flow NTrial= 30
Split Flow Tol= 0.02
Split Flow Ratio= 0.02
Log Output Level= 0
Friction Slope Method= 1
Unsteady Friction Slope Method= 2
Unsteady Bridges Friction Slope Method= 1
Parabolic Critical Depth
Global Vel Dist=  1 , 1 , 1
Global Log Level= 0
CheckData=True
Encroach Param= -1, 0, 0, 0
BEGIN DESCRIPTION:
Multiple Run
END DESCRIPTION:

--- Caney Creek T 18.f01 (steady flow) ---

Flow Title=Multiple
Number of Profiles=7
Profile Names=10-year,25-year,50-year,1pct_min,100-year,1pct_plu,500-year
River Rch & RM= Caney Creek T 18,Reach-1,3247
     640     867    1053     636    1269    2532    1847
River Rch & RM= Caney Creek T 18,Reach-1,929
     655     888    1080     652    1302    2597    1896
Boundary for River Rch & Prof#=Caney Creek T 18,Reach-1,1
Up Type=0
Dn Type=3
Dn Slope=0.005
Boundary for River Rch & Prof#=Caney Creek T 18,Reach-1,2
Up Type=0
Dn Type=3
Dn Slope=0.005
Boundary for River Rch & Prof#=Caney Creek T 18,Reach-1,3
Up Type=0
Dn Type=3
Dn Slope=0.005
Boundary for River Rch & Prof#=Caney Creek T 18,Reach-1,4
Up Type=0
Dn Type=3
Dn Slope=0.005
Boundary for River Rch & Prof#=Caney Creek T 18,Reach-1,5
Up Type=0
Dn Type=3
Dn Slope=0.005
Boundary for River Rch & Prof#=Caney Creek T 18,Reach-1,6
Up Type=0
Dn Type=3
Dn Slope=0.005
Boundary for River Rch & Prof#=Caney Creek T 18,Reach-1,7
Up Type=0
Dn Type=3
Dn Slope=0.005

--- Caney Creek T 18.g01 (geometry) ---

Geom Title=Existing Conditions

River Reach=Caney Creek T 18,Reach-1
Reach XY= 30
      2792076.00      6803861.00      2792070.85      6803808.00
      2792024.54      6803763.96      2791977.66      6803764.56
      2791925.97      6803803.45      2791827.86      6803749.89
      2791823.61      6803616.54      2791776.21      6803542.73
      2791774.78      6803171.50      2791728.47      6803105.43
      2791722.14      6803012.60      2791678.37      6802955.47
      2791677.04      6802821.44      2791855.91      6802630.79
      2791939.21      6802597.37      2792162.73      6802374.41
      2792267.52      6802357.50      2792281.80      6802317.05
      2792339.00      6802297.31      2792470.17      6802163.30
      2792480.19      6802112.74      2792519.92      6802063.20
      2792530.19      6802012.74      2792576.49      6801924.80
      2792573.75      6801816.94      2792526.68      6801747.08
      2792524.62      6801520.66      2792478.13      6801454.94
      2792475.83      6801381.20      2792576.00      6801311.00

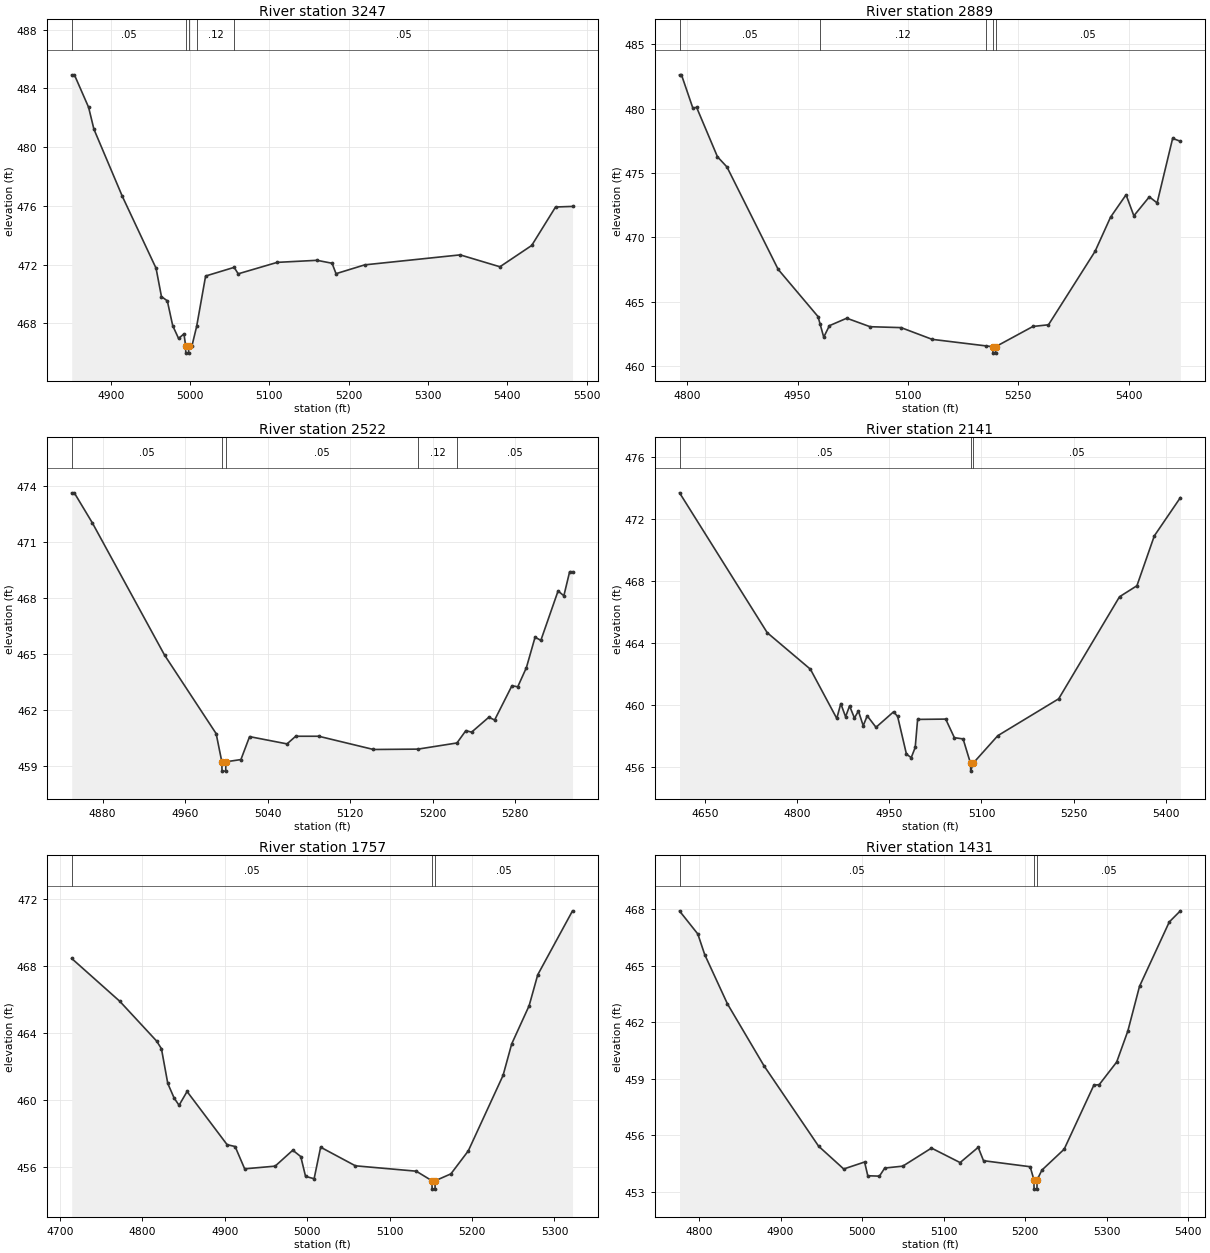
Type RM Length L Ch R = 1,3247,358,358,358
BEGIN DESCRIPTION:
Caney Creek T 18 7.0
END DESCRIPTION:
XS GIS Cut Line= 3
      2792126.00      6803661.00      2792015.47      6803761.51
      2791977.33      6804242.30
#Sta/Elev= 30
  4850.6  484.92  4854.0  484.92  4871.9  482.71  4878.6  481.22  4914.5  476.64
  4957.0  471.75  4963.8  469.82  4971.2  469.53  4978.0  467.84  4985.4  466.97
  4992.2  467.28  4994.3  466.47  4994.5  465.97  4998.0  465.97  4998.3  466.47
  5002.3  466.47  5008.2  467.79  5019.5  471.22  5055.5  471.81  5060.6  471.37
  5109.8  472.15  5160.0  472.29  5179.0  472.09  5184.0  471.38  5220.2  471.98
  5340.6  472.66  5390.7  471.85  5430.8  473.30  5460.9  475.92  5482.3  475.96
#Mann=5,-1,0
  4850.6    0.05       0  4994.3    0.04       0  4998.3    0.05       0
  5008.2    0.12       0  5055.5    0.05       0
Bank Sta=4994.3,4998.3
Exp/Cntr=0.3,0.1

Type RM Length L Ch R = 1,2889,367,367,367
BEGIN DESCRIPTION:
Caney Creek T 18 6.0
END DESCRIPTION:
XS GIS Cut Line= 3
      2792026.01      6803561.00      2791826.00      6803611.00
      2791376.00      6803761.00
#Sta/Elev= 30
  4789.7  482.62  4792.3  482.62  4807.7  480.05  4812.9  480.09  4841.2  476.26
  4854.1  475.47  4923.7  467.52  4977.8  463.86  4980.5  463.31  4985.6  462.26
  4993.3  463.15  5016.9  463.73  5048.6  463.07  5090.7  463.00  5132.9  462.09
  5206.2  461.58  5215.2  461.52  5215.5  461.02  5219.0  461.02  5219.2  461.52
  5269.9  463.09  5291.0  463.22  5354.3  468.92  5375.3  471.57  5396.4  473.31
  5407.0  471.68  5428.0  473.15  5438.6  472.68  5459.7  477.69  5470.2  477.46
#Mann=5,-1,0
  4789.7    0.05       0  4980.5    0.12       0  5206.2    0.05       0
  5215.2    0.07       0  5219.2    0.05       0
Bank Sta=5215.2,5219.2
Exp/Cntr=0.3,0.1

Type RM Length L Ch R = 1,2522,381,381,381
BEGIN DESCRIPTION:
Caney Creek T 18 5.0
END DESCRIPTION:
XS GIS Cut Line= 3
      2791925.99      6803261.00      2791776.00      6803261.00
      2791476.00      6803411.00
#Sta/Elev= 30
  4850.1  473.63  4852.6  473.63  4870.1  472.02  4940.1  464.93  4990.1  460.72
  4995.6  459.21  4995.8  458.71  4999.3  458.71  4999.6  459.21  5014.1  459.33
  5022.5  460.56  5058.8  460.17  5067.2  460.58  5089.5  460.58  5142.6  459.87
  5185.7  459.89  5223.5  460.22  5232.1  460.88  5237.7  460.80  5254.4  461.60
  5260.0  461.45  5276.8  463.29  5282.4  463.23  5290.8  464.26  5299.2  465.89
  5304.8  465.72  5321.5  468.37  5327.1  468.11  5332.7  469.40  5335.5  469.40
#Mann=5,-1,0
  4850.1    0.05       0  4995.6    0.04       0  4999.6    0.05       0
  5185.7    0.12       0  5223.5    0.05       0
Bank Sta=4995.6,4999.6
Exp/Cntr=0.3,0.1

Type RM Length L Ch R = 1,2141,384,384,384
BEGIN DESCRIPTION:
Caney Creek T 18 4.0
END DESCRIPTION:
XS GIS Cut Line= 3
      2791976.03      6803161.02      2791676.00      6802911.00
      2791376.01      6803210.99
#Sta/Elev= 30
  4608.8  473.69  4751.4  464.66  4821.7  462.30  4864.6  459.12  4871.1  460.08
  4878.9  459.23  4885.4  459.93  4893.3  459.15  4899.8  459.60  4907.6  458.65
  4914.1  459.29  4928.4  458.55  4957.0  459.55  4963.6  459.25  4977.9  456.82
  4985.7  456.59  4992.2  457.25  4996.1  459.06  5041.8  459.08  5055.9  457.88
  5070.1  457.80  5082.2  456.22  5082.5  455.72  5086.2  456.22  5126.6  458.01
  5225.6  460.39  5324.6  466.98  5352.9  467.69  5381.2  470.91  5423.6  473.38
#Mann=3,-1,0
  4608.8    0.05       0  5082.2    0.04       0  5086.2    0.05       0
Bank Sta=5082.2,5086.2
Exp/Cntr=0.3,0.1

Type RM Length L Ch R = 1,1757,326,326,326
BEGIN DESCRIPTION:
Caney Creek T 18 3.0
END DESCRIPTION:
XS GIS Cut Line= 3
      2792126.03      6802761.02      2791876.00      6802611.00
      2791576.01      6802511.00
#Sta/Elev= 30
  4714.1  468.45  4772.4  465.90  4817.1  463.53  4823.0  463.07  4830.7  461.00
  4838.5  460.12  4844.4  459.70  4854.1  460.52  4902.7  457.35  4912.4  457.24
  4924.0  455.91  4961.0  456.07  4982.4  457.02  4992.1  456.64  4997.9  455.46
  5008.3  455.32  5016.2  457.20  5058.4  456.09  5132.2  455.77  5151.3  455.20
  5151.5  454.70  5155.0  454.70  5155.3  455.20  5174.3  455.61  5195.4  456.98
  5237.6  461.48  5248.1  463.36  5269.2  465.63  5279.7  467.48  5321.9  471.29
#Mann=3,-1,0
  4714.1    0.05       0  5151.3    0.04       0  5155.3    0.05       0
Bank Sta=5151.3,5155.3
Exp/Cntr=0.3,0.1

Type RM Length L Ch R = 1,1431,502,502,502
BEGIN DESCRIPTION:
Caney Creek T 18 2.0
END DESCRIPTION:
XS GIS Cut Line= 3
      2792226.01      6802611.02      2792126.00      6802411.00
      2791826.03      6802161.02
#Sta/Elev= 30
  4776.1  467.91  4798.5  466.69  4806.9  465.60  4834.8  462.98  4879.5  459.70
  4946.6  455.42  4977.4  454.21  5003.0  454.58  5006.9  453.85  5021.2  453.83
  5027.7  454.26  5049.8  454.36  5085.0  455.32  5120.1  454.55  5142.3  455.36
  5148.8  454.65  5206.0  454.33  5210.6  453.64  5210.8  453.14  5214.3  453.14
  5214.6  453.64  5220.4  454.15  5247.7  455.26  5284.1  458.66  5290.7  458.69
  5312.1  459.89  5325.8  461.54  5340.1  463.91  5376.6  467.33  5390.2  467.92
#Mann=3,-1,0
  4776.1    0.05       0  5210.6    0.04       0  5214.6    0.05       0
Bank Sta=5210.6,5214.6
Exp/Cntr=0.3,0.1

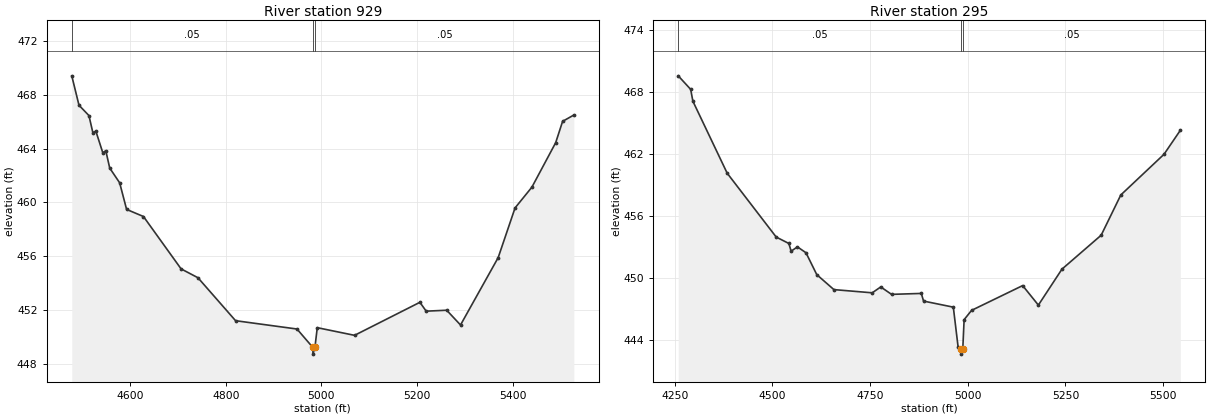
Type RM Length L Ch R = 1,929,634,634,634
BEGIN DESCRIPTION:
Mapping XS ddf19e4e
END DESCRIPTION:
XS GIS Cut Line= 2
      2792891.53      6802436.39      2792062.11      6801791.86
#Sta/Elev= 30
  4477.7  469.43  4492.8  467.24  4513.6  466.47  4521.8  465.20  4528.1  465.31
  4542.6  463.70  4548.9  463.85  4557.1  462.56  4577.9  461.46  4592.4  459.48
  4627.7  458.95  4706.4  455.05  4741.7  454.39  4820.4  451.19  4948.9  450.57
  4982.0  449.20  4982.4  448.70  4986.4  449.20  4991.3  450.67  5069.3  450.10
  5206.0  452.56  5219.2  451.90  5262.1  451.97  5291.0  450.87  5369.8  455.89
  5405.1  459.59  5440.4  461.14  5490.1  464.45  5504.6  466.04  5528.1  466.51
#Mann=3,-1,0
  4477.7    0.05       0  4982.0    0.04       0  4986.4    0.05       0
Bank Sta=4982,4986.4
Exp/Cntr=0.3,0.1

Type RM Length L Ch R = 1,295,0,0,0
BEGIN DESCRIPTION:
Caney Creek T 18 1.0
END DESCRIPTION:
XS GIS Cut Line= 3
      2792877.59      6802181.20      2792525.79      6801529.27
      2791984.52      6801582.71
#Sta/Elev= 30
  4259.2  469.58  4291.0  468.27  4296.7  467.12  4384.4  460.15  4509.9  453.96
  4542.3  453.34  4548.0  452.59  4564.2  453.01  4586.1  452.44  4613.7  450.32
  4657.5  448.87  4755.6  448.56  4777.4  449.13  4805.0  448.41  4881.2  448.50
  4886.9  447.76  4963.1  447.17  4975.3  443.32  4982.8  443.12  4983.2  442.62
  4987.3  443.12  4990.7  445.96  5009.8  446.86  5140.5  449.26  5180.7  447.37
  5241.0  450.85  5341.4  454.14  5391.7  458.04  5502.2  461.98  5543.9  464.30
#Mann=3,-1,0
  4259.2    0.05       0  4982.8    0.04       0  4987.3    0.05       0
Bank Sta=4982.8,4987.3
Exp/Cntr=0.3,0.1

Chan Stop Cuts=-1