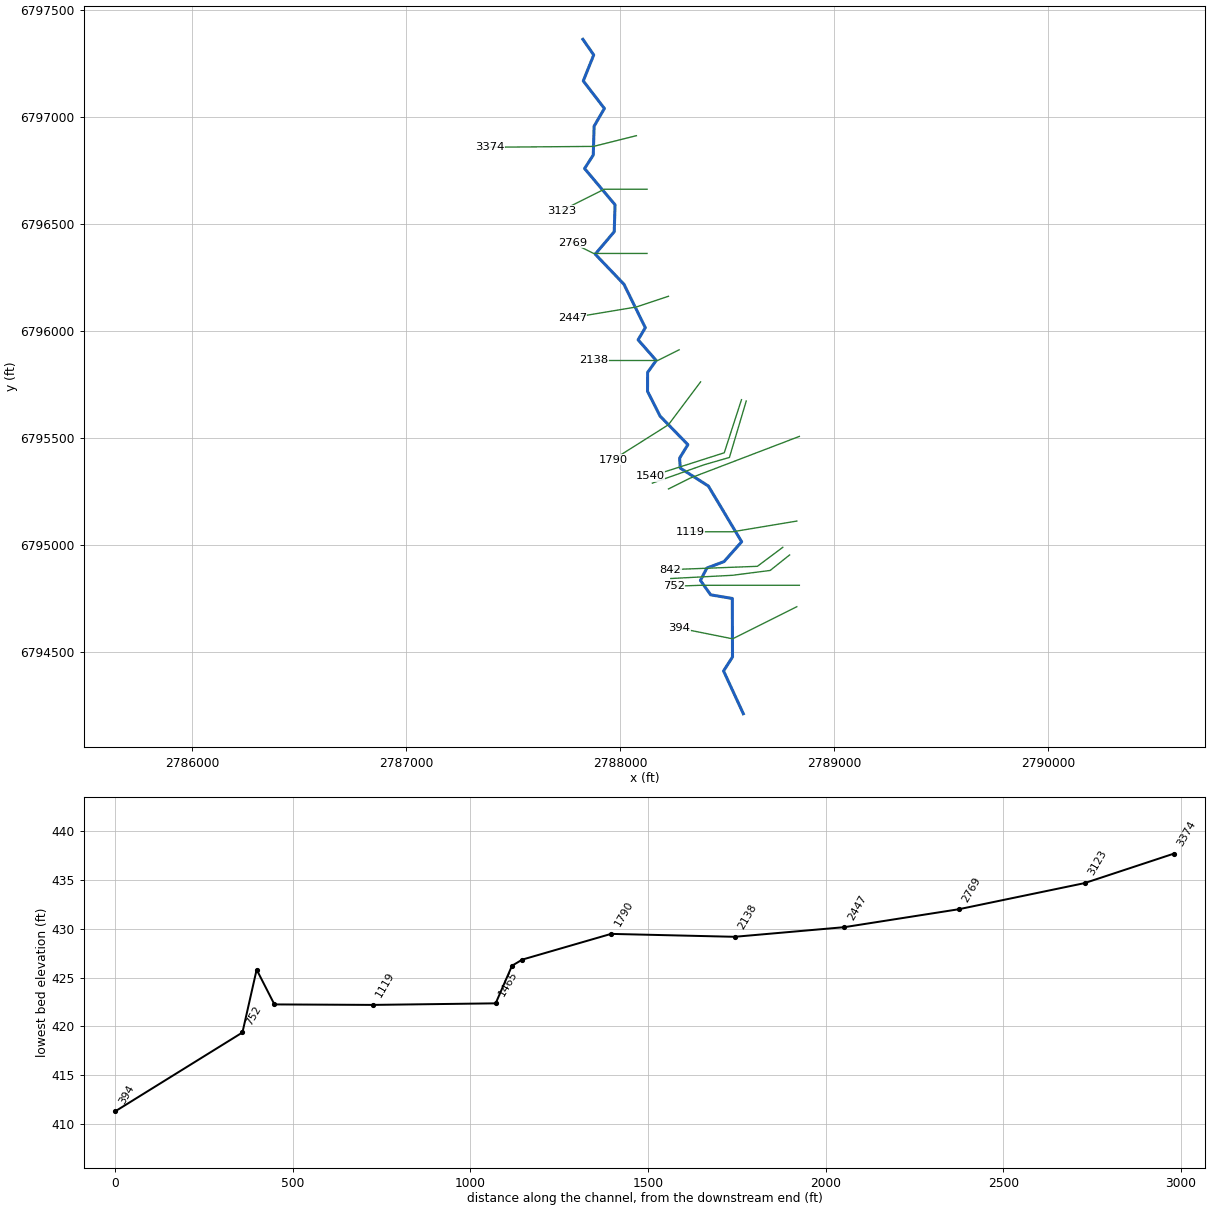
--- Caney Creek T 19.prj (project) ---

Proj Title=Caney Creek T 19 Base Level Engineering
Current Plan=p01
Default Exp/Contr=0.3,0.1
English Units
Geom File=g01
Flow File=f01
Plan File=p01
BEGIN DESCRIPTION:
Caney Creek T 19
END DESCRIPTION:

--- Caney Creek T 19.p01 (plan) ---

Plan Title=Multiple Run
Short Identifier=Multiple
Geom File=g01
Flow File=f01
Subcritical Flow
K Sum by GR= 0
Std Step Tol= 0.01
Critical Tol= 0.01
Num of Std Step Trials= 20
Max Error Tol= 0.3
Flow Tol Ratio= 0.001
Split Flow NTrial= 30
Split Flow Tol= 0.02
Split Flow Ratio= 0.02
Log Output Level= 0
Friction Slope Method= 1
Unsteady Friction Slope Method= 2
Unsteady Bridges Friction Slope Method= 1
Parabolic Critical Depth
Global Vel Dist=  1 , 1 , 1
Global Log Level= 0
CheckData=True
Encroach Param= -1, 0, 0, 0
BEGIN DESCRIPTION:
Multiple Run
END DESCRIPTION:

--- Caney Creek T 19.f01 (steady flow) ---

Flow Title=Multiple
Number of Profiles=7
Profile Names=10-year,25-year,50-year,1pct_min,100-year,1pct_plu,500-year
River Rch & RM= Caney Creek T 19,Reach-1,3374
     370     483     573     338     674    1345     936
Boundary for River Rch & Prof#=Caney Creek T 19,Reach-1,1
Up Type=0
Dn Type=3
Dn Slope=0.005
Boundary for River Rch & Prof#=Caney Creek T 19,Reach-1,2
Up Type=0
Dn Type=3
Dn Slope=0.005
Boundary for River Rch & Prof#=Caney Creek T 19,Reach-1,3
Up Type=0
Dn Type=3
Dn Slope=0.005
Boundary for River Rch & Prof#=Caney Creek T 19,Reach-1,4
Up Type=0
Dn Type=3
Dn Slope=0.005
Boundary for River Rch & Prof#=Caney Creek T 19,Reach-1,5
Up Type=0
Dn Type=3
Dn Slope=0.005
Boundary for River Rch & Prof#=Caney Creek T 19,Reach-1,6
Up Type=0
Dn Type=3
Dn Slope=0.005
Boundary for River Rch & Prof#=Caney Creek T 19,Reach-1,7
Up Type=0
Dn Type=3
Dn Slope=0.005

--- Caney Creek T 19.g01 (geometry) ---

Geom Title=Existing Conditions

River Reach=Caney Creek T 19,Reach-1
Reach XY= 30
      2787826.00      6797361.00      2787876.60      6797288.14
      2787827.74      6797166.63      2787926.48      6797038.24
      2787878.41      6796955.48      2787874.43      6796820.59
      2787833.79      6796757.58      2787976.22      6796588.34
      2787972.45      6796462.47      2787883.60      6796357.66
      2788017.86      6796217.06      2788117.75      6796014.23
      2788084.02      6795957.66      2788168.66      6795861.10
      2788128.49      6795805.52      2788128.15      6795716.97
      2788186.76      6795601.32      2788316.85      6795467.73
      2788278.10      6795405.32      2788281.01      6795358.46
      2788412.51      6795274.56      2788568.17      6795014.22
      2788485.71      6794921.79      2788405.31      6794891.36
      2788375.36      6794833.77      2788423.31      6794766.45
      2788524.50      6794749.47      2788525.34      6794476.16
      2788483.53      6794410.99      2788576.00      6794211.00

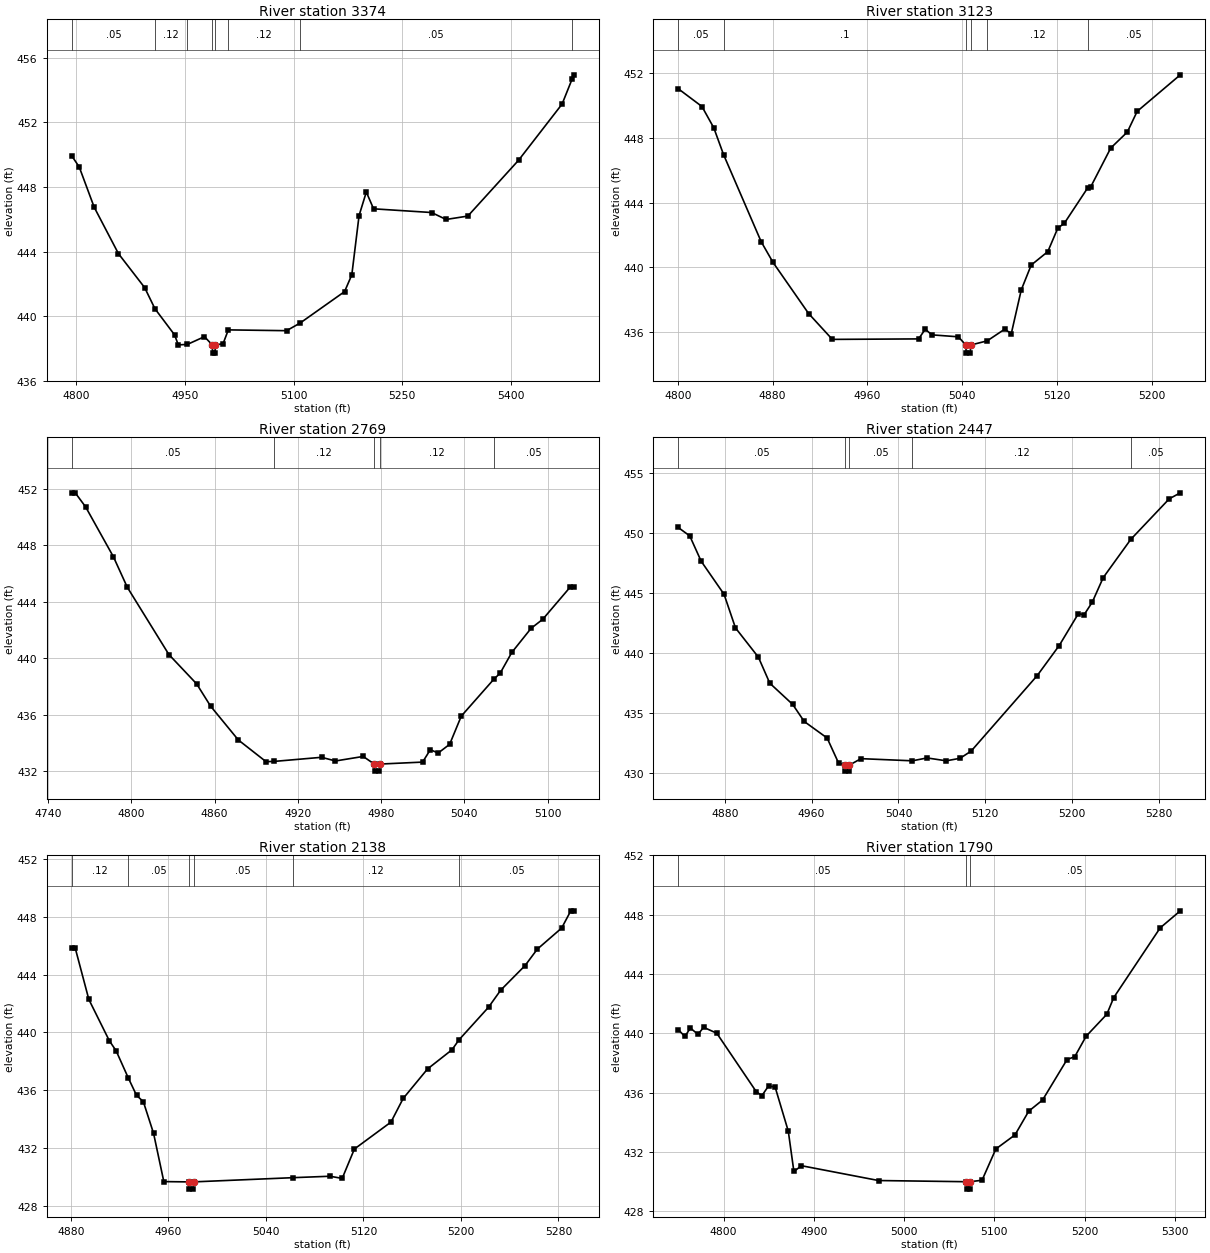
Type RM Length L Ch R = 1,3374,251,251,251
BEGIN DESCRIPTION:
Caney Creek T 19 10.0
END DESCRIPTION:
XS GIS Cut Line= 3
      2788076.02      6796911.01      2787876.00      6796861.00
      2787389.80      6796857.07
#Sta/Elev= 30
  4794.1  449.93  4804.4  449.24  4825.0  446.75  4858.5  443.87  4894.6  441.77
  4908.8  440.46  4935.9  438.84  4941.0  438.22  4953.5  438.25  4977.1  438.73
  4988.0  438.21  4988.2  437.71  4991.7  437.71  4992.0  438.21  5002.8  438.30
  5010.0  439.15  5090.3  439.10  5108.9  439.57  5170.3  441.52  5180.3  442.56
  5190.3  446.23  5200.3  447.69  5210.3  446.65  5290.3  446.42  5310.3  445.99
  5340.3  446.20  5410.3  449.66  5470.3  453.14  5484.2  454.70  5486.5  454.95
#Mann=8,-1,0
  4794.1    0.05       0  4908.8    0.12       0  4953.5     0.1       0
  4988.0    0.07       0  4992.0     0.1       0  5010.0    0.12       0
  5108.9    0.05       0  5484.2    0.12       0
Bank Sta=4988,4992
Exp/Cntr=0.3,0.1

Type RM Length L Ch R = 1,3123,354,354,354
BEGIN DESCRIPTION:
Caney Creek T 19 9.0
END DESCRIPTION:
XS GIS Cut Line= 3
      2788125.98      6796661.00      2787926.00      6796661.00
      2787725.99      6796560.99
#Sta/Elev= 30
  4800.4  451.05  4820.4  449.95  4830.4  448.63  4838.6  446.98  4870.4  441.58
  4880.4  440.30  4910.4  437.14  4930.4  435.54  5003.2  435.57  5008.8  436.17
  5014.4  435.82  5036.7  435.70  5043.1  435.19  5043.3  434.69  5046.8  434.69
  5047.1  435.19  5061.1  435.45  5075.8  436.17  5081.4  435.90  5089.8  438.60
  5098.2  440.14  5112.2  440.97  5120.6  442.42  5126.2  442.73  5146.0  444.93
  5148.5  444.99  5165.3  447.38  5179.3  448.37  5187.6  449.65  5224.0  451.91
#Mann=6,-1,0
  4800.4    0.05       0  4838.6     0.1       0  5043.1    0.07       0
  5047.1     0.1       0  5061.1    0.12       0  5146.0    0.05       0
Bank Sta=5043.1,5047.1
Exp/Cntr=0.3,0.1

Type RM Length L Ch R = 1,2769,322,322,322
BEGIN DESCRIPTION:
Caney Creek T 19 8.0
END DESCRIPTION:
XS GIS Cut Line= 3
      2788125.98      6796361.00      2787876.00      6796361.00
      2787775.99      6796411.01
#Sta/Elev= 30
  4757.1  451.73  4759.6  451.73  4767.1  450.73  4787.1  447.20  4797.1  445.04
  4827.1  440.27  4847.1  438.19  4857.1  436.62  4877.1  434.22  4897.1  432.68
  4903.1  432.70  4937.1  432.99  4947.1  432.73  4967.1  433.05  4975.1  432.51
  4975.3  432.01  4978.8  432.01  4979.1  432.51  5009.9  432.65  5015.5  433.53
  5021.1  433.29  5029.4  433.91  5037.8  435.91  5061.4  438.54  5065.8  438.95
  5074.2  440.42  5088.1  442.13  5096.5  442.77  5116.1  445.03  5118.9  445.03
#Mann=5,-1,0
  4757.1    0.05       0  4903.1    0.12       0  4975.1    0.07       0
  4979.1    0.12       0  5061.4    0.05       0
Bank Sta=4975.1,4979.1
Exp/Cntr=0.3,0.1

Type RM Length L Ch R = 1,2447,309,309,309
BEGIN DESCRIPTION:
Caney Creek T 19 7.0
END DESCRIPTION:
XS GIS Cut Line= 3
      2788226.02      6796161.01      2788076.00      6796111.00
      2787775.97      6796061.00
#Sta/Elev= 30
  4837.2  450.48  4847.8  449.78  4858.3  447.67  4879.4  444.91  4889.9  442.11
  4911.0  439.67  4921.5  437.50  4942.6  435.73  4953.2  434.31  4974.3  432.93
  4984.8  430.85  4990.7  430.67  4990.9  430.17  4994.4  430.17  4994.7  430.67
  5005.5  431.21  5052.8  431.03  5066.3  431.27  5084.0  431.03  5096.7  431.24
  5106.9  431.84  5167.7  438.13  5188.0  440.64  5205.7  443.31  5210.8  443.19
  5218.4  444.25  5228.5  446.30  5253.9  449.49  5289.3  452.87  5299.5  453.37
#Mann=5,-1,0
  4837.2    0.05       0  4990.7    0.04       0  4994.7    0.05       0
  5052.8    0.12       0  5253.9    0.05       0
Bank Sta=4990.7,4994.7
Exp/Cntr=0.3,0.1

Type RM Length L Ch R = 1,2138,348,348,348
BEGIN DESCRIPTION:
Caney Creek T 19 6.0
END DESCRIPTION:
XS GIS Cut Line= 3
      2788276.03      6795911.02      2788176.00      6795861.00
      2787876.04      6795861.00
#Sta/Elev= 30
  4880.8  445.84  4883.6  445.84  4894.8  442.28  4911.6  439.43  4917.2  438.73
  4927.1  436.87  4933.9  435.66  4939.5  435.22  4947.9  433.03  4956.3  429.70
  4976.7  429.68  4976.9  429.18  4980.4  429.18  4980.7  429.68  5061.9  429.97
  5092.6  430.07  5102.6  429.92  5112.6  431.95  5142.6  433.81  5152.6  435.44
  5172.6  437.48  5192.6  438.80  5198.5  439.50  5222.6  441.74  5232.6  442.92
  5252.6  444.62  5262.6  445.75  5282.6  447.21  5290.1  448.40  5292.6  448.40
#Mann=6,-1,0
  4880.8    0.12       0  4927.1    0.05       0  4976.7    0.03       0
  4980.7    0.05       0  5061.9    0.12       0  5198.5    0.05       0
Bank Sta=4976.7,4980.7
Exp/Cntr=0.3,0.1

Type RM Length L Ch R = 1,1790,250,250,250
BEGIN DESCRIPTION:
Caney Creek T 19 5.0
END DESCRIPTION:
XS GIS Cut Line= 3
      2788376.00      6795761.00      2788226.00      6795561.00
      2787967.15      6795397.62
#Sta/Elev= 30
  4749.8  440.25  4757.1  439.78  4763.3  440.35  4771.7  439.92  4777.9  440.40
  4792.5  440.00  4836.3  436.05  4842.5  435.79  4849.8  436.44  4857.1  436.37
  4871.7  433.39  4877.9  430.67  4886.3  431.06  4971.7  430.06  5069.0  429.98
  5069.3  429.48  5072.8  429.48  5073.0  429.98  5086.3  430.08  5101.6  432.19
  5122.8  433.14  5138.0  434.74  5153.3  435.49  5180.4  438.22  5189.0  438.42
  5201.6  439.80  5224.5  441.28  5232.2  442.41  5283.6  447.11  5305.9  448.26
#Mann=3,-1,0
  4749.8    0.05       0  5069.0    0.03       0  5073.0    0.05       0
Bank Sta=5069,5073
Exp/Cntr=0.3,0.1

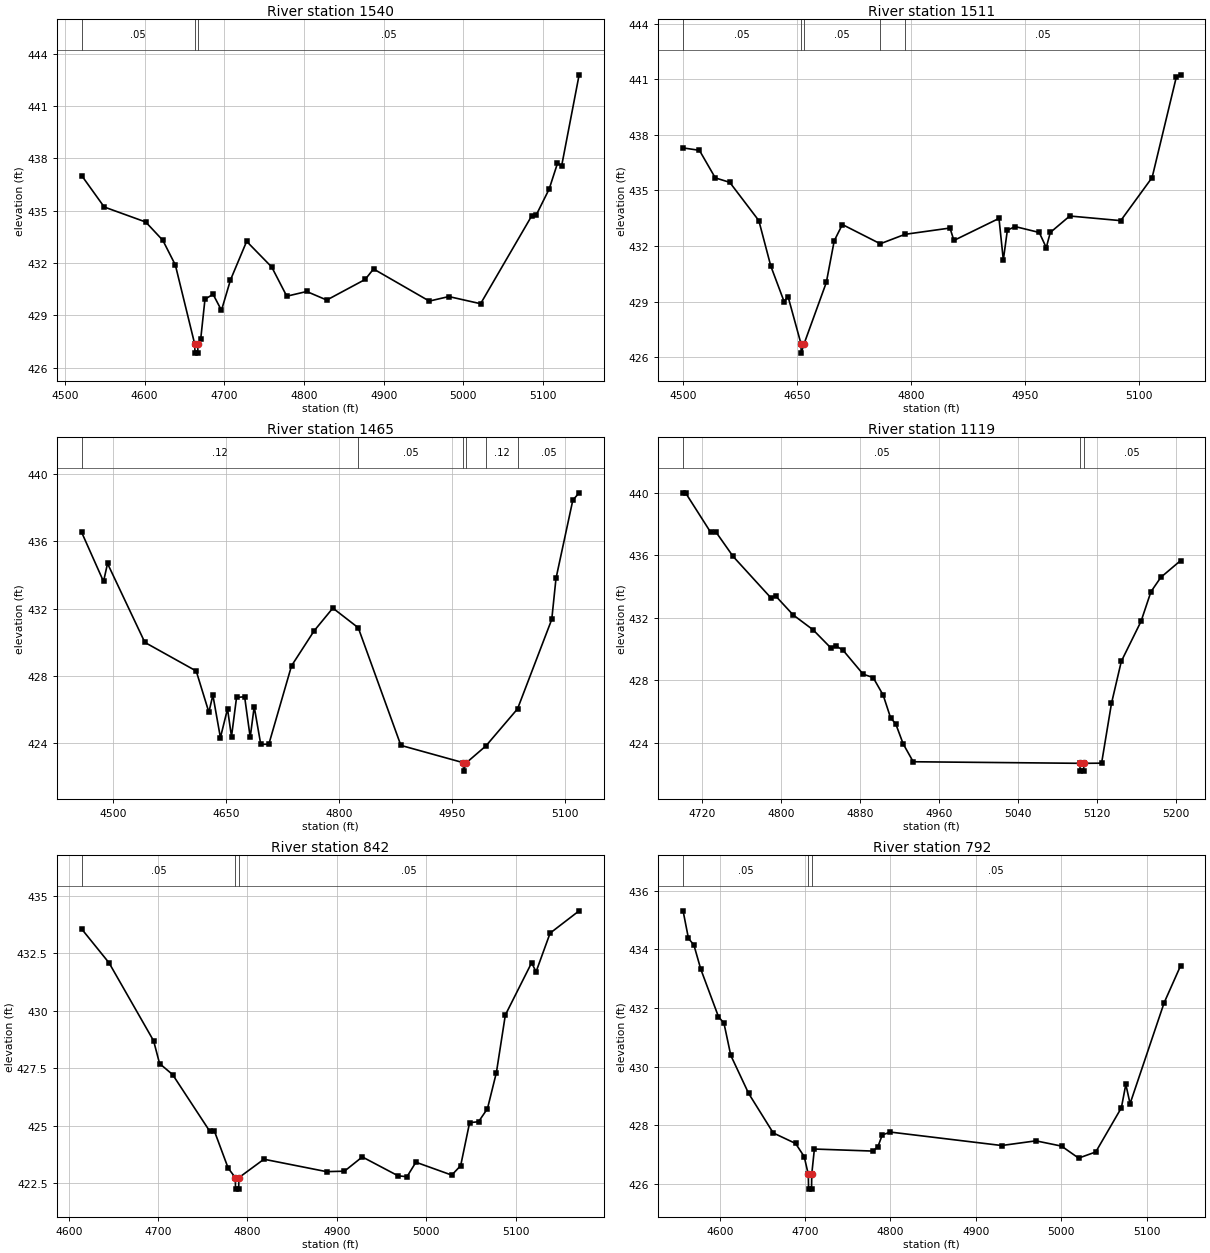
Type RM Length L Ch R = 1,1540,29,29,29
BEGIN DESCRIPTION:
Mapping XS 248b3611
END DESCRIPTION:
XS GIS Cut Line= 3
      2788567.29      6795677.93      2788486.77      6795430.02
      2788140.18      6795319.31
#Sta/Elev= 30
  4520.9  437.01  4549.2  435.21  4601.3  434.35  4622.8  433.30  4638.5  431.89
  4662.9  427.34  4663.1  426.84  4666.6  426.84  4666.9  427.34  4670.4  427.67
  4675.7  429.93  4685.9  430.21  4696.4  429.29  4707.7  431.03  4728.0  433.24
  4759.5  431.77  4778.4  430.10  4803.4  430.37  4828.6  429.88  4876.8  431.06
  4887.3  431.66  4957.3  429.82  4981.8  430.08  5021.7  429.67  5086.1  434.72
  5091.3  434.73  5107.8  436.24  5118.2  437.71  5123.5  437.58  5145.4  442.78
#Mann=3,-1,0
  4520.9    0.05       0  4662.9    0.03       0  4666.9    0.05       0
Bank Sta=4662.9,4666.9
Exp/Cntr=0.3,0.1

Type RM Length L Ch R = 1,1511,46,46,46
BEGIN DESCRIPTION:
Mapping XS 9198d6ad
END DESCRIPTION:
XS GIS Cut Line= 4
      2788589.53      6795671.59      2788510.86      6795408.11
      2788392.55      6795373.95      2788150.79      6795288.28
#Sta/Elev= 30
  4499.5  437.30  4521.0  437.17  4541.9  435.68  4560.9  435.44  4599.2  433.37
  4614.9  430.92  4632.4  429.00  4637.6  429.27  4654.7  426.71  4654.9  426.21
  4658.7  426.71  4688.0  430.03  4698.4  432.28  4709.1  433.16  4759.0  432.12
  4791.5  432.63  4850.7  432.97  4855.9  432.30  4915.2  433.49  4920.9  431.24
  4926.2  432.85  4936.4  433.05  4968.2  432.73  4977.4  431.91  4982.7  432.73
  5008.3  433.62  5075.4  433.37  5116.7  435.70  5148.6  441.14  5154.1  441.25
#Mann=5,-1,0
  4499.5    0.05       0  4654.7    0.03       0  4658.7    0.05       0
  4759.0    0.12       0  4791.5    0.05       0
Bank Sta=4654.7,4658.7
Exp/Cntr=0.3,0.1

Type RM Length L Ch R = 1,1465,346,346,346
BEGIN DESCRIPTION:
Caney Creek T 19 4.0
END DESCRIPTION:
XS GIS Cut Line= 3
      2788837.89      6795506.42      2788326.00      6795311.00
      2788226.02      6795261.01
#Sta/Elev= 30
  4458.8  436.54  4487.8  433.62  4493.1  434.69  4542.6  430.00  4610.7  428.30
  4627.5  425.85  4632.8  426.87  4642.8  424.34  4652.2  426.05  4657.5  424.40
  4664.2  426.73  4674.9  426.77  4682.3  424.36  4687.6  426.18  4696.3  423.94
  4707.0  423.95  4737.1  428.61  4767.1  430.69  4791.9  432.04  4825.6  430.87
  4882.1  423.88  4965.0  422.85  4965.2  422.35  4969.0  422.85  4994.9  423.85
  5036.8  426.05  5082.2  431.37  5087.8  433.80  5110.1  438.45  5118.5  438.89
#Mann=6,-1,0
  4458.8    0.12       0  4825.6    0.05       0  4965.0    0.07       0
  4969.0    0.05       0  4994.9    0.12       0  5036.8    0.05       0
Bank Sta=4965,4969
Exp/Cntr=0.3,0.1

Type RM Length L Ch R = 1,1119,277,277,277
BEGIN DESCRIPTION:
Caney Creek T 19 3.0
END DESCRIPTION:
XS GIS Cut Line= 3
      2788826.01      6795111.00      2788526.00      6795061.00
      2788326.05      6795061.00
#Sta/Elev= 30
  4700.8  440.00  4703.3  440.00  4728.7  437.48  4733.8  437.52  4751.5  435.93
  4789.5  433.30  4794.6  433.40  4812.3  432.19  4832.6  431.23  4850.3  430.09
  4855.4  430.22  4863.0  429.92  4883.3  428.39  4893.4  428.18  4903.6  427.05
  4911.2  425.58  4916.2  425.23  4923.8  423.94  4934.0  422.79  5102.9  422.69
  5103.2  422.19  5106.7  422.19  5106.9  422.69  5124.9  422.70  5134.9  426.52
  5144.9  429.22  5164.9  431.78  5174.9  433.67  5184.9  434.59  5204.9  435.66
#Mann=3,-1,0
  4700.8    0.05       0  5102.9    0.03       0  5106.9    0.05       0
Bank Sta=5102.9,5106.9
Exp/Cntr=0.3,0.1

Type RM Length L Ch R = 1,842,50,50,50
BEGIN DESCRIPTION:
Mapping XS 7d8ef276
END DESCRIPTION:
XS GIS Cut Line= 3
      2788760.56      6794988.39      2788641.41      6794899.65
      2788233.48      6794884.14
#Sta/Elev= 30
  4614.4  433.55  4645.0  432.08  4694.9  428.69  4701.6  427.70  4716.2  427.22
  4757.7  424.76  4763.0  424.76  4778.4  423.15  4786.4  422.74  4786.6  422.24
  4790.1  422.24  4790.4  422.74  4818.4  423.54  4888.5  423.00  4908.5  423.02
  4928.5  423.64  4968.5  422.82  4978.5  422.78  4988.5  423.41  5028.6  422.85
  5038.6  423.26  5048.6  425.13  5058.6  425.17  5068.6  425.74  5078.6  427.31
  5088.6  429.81  5118.0  432.08  5123.0  431.69  5138.7  433.37  5171.2  434.34
#Mann=3,-1,0
  4614.4    0.05       0  4786.4    0.04       0  4790.4    0.05       0
Bank Sta=4786.4,4790.4
Exp/Cntr=0.3,0.1

Type RM Length L Ch R = 1,792,40,40,40
BEGIN DESCRIPTION:
Mapping XS bbf29b87
END DESCRIPTION:
XS GIS Cut Line= 4
      2788792.32      6794952.80      2788701.48      6794880.38
      2788525.50      6794857.75      2788236.80      6794842.66
#Sta/Elev= 30
  4557.1  435.32  4563.4  434.38  4569.8  434.15  4577.8  433.33  4598.6  431.70
  4605.0  431.48  4613.0  430.38  4633.9  429.08  4662.7  427.73  4688.9  427.37
  4699.0  426.92  4703.8  426.31  4704.1  425.81  4707.6  425.81  4707.8  426.31
  4710.9  427.18  4779.6  427.11  4785.3  427.26  4790.4  427.66  4799.8  427.76
  4930.3  427.30  4970.4  427.46  5000.4  427.28  5020.4  426.87  5040.5  427.08
  5070.5  428.59  5075.7  429.39  5080.7  428.73  5120.6  432.18  5139.8  433.44
#Mann=3,-1,0
  4557.1    0.05       0  4703.8    0.04       0  4707.8    0.05       0
Bank Sta=4703.8,4707.8
Exp/Cntr=0.3,0.1

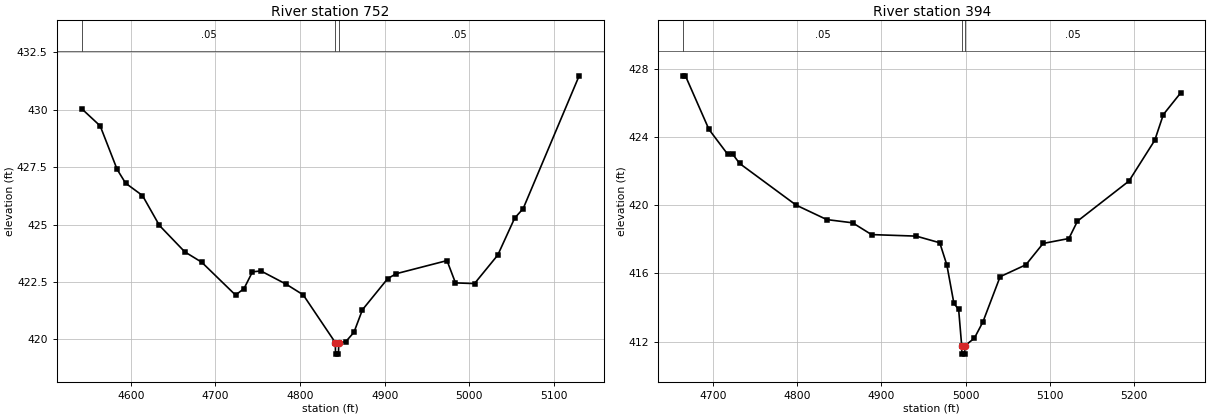
Type RM Length L Ch R = 1,752,358,358,358
BEGIN DESCRIPTION:
Caney Creek T 19 2.0
END DESCRIPTION:
XS GIS Cut Line= 3
      2788837.89      6794811.09      2788376.00      6794811.00
      2788249.87      6794806.64
#Sta/Elev= 30
  4541.8  430.04  4563.7  429.29  4583.7  427.40  4593.7  426.80  4613.7  426.26
  4633.7  424.96  4663.7  423.81  4683.7  423.36  4723.7  421.93  4733.7  422.21
  4743.7  422.94  4753.7  422.98  4783.7  422.40  4803.7  421.94  4841.7  419.86
  4841.9  419.36  4845.4  419.36  4845.7  419.86  4853.7  419.89  4863.7  420.31
  4873.7  421.29  4903.7  422.65  4913.7  422.86  4973.7  423.43  4983.7  422.46
  5006.2  422.43  5033.7  423.67  5053.7  425.28  5063.7  425.69  5129.9  431.47
#Mann=3,-1,0
  4541.8    0.05       0  4841.7    0.04       0  4845.7    0.05       0
Bank Sta=4841.7,4845.7
Exp/Cntr=0.3,0.1

Type RM Length L Ch R = 1,394,0,0,0
BEGIN DESCRIPTION:
Caney Creek T 19 1.0
END DESCRIPTION:
XS GIS Cut Line= 3
      2788825.98      6794710.99      2788526.00      6794561.00
      2788276.03      6794610.99
#Sta/Elev= 30
  4664.7  427.59  4667.5  427.59  4695.4  424.45  4717.8  422.98  4723.4  423.01
  4731.8  422.45  4798.8  420.01  4835.2  419.16  4865.9  418.97  4888.3  418.28
  4941.4  418.19  4969.3  417.80  4977.7  416.50  4986.1  414.24  4991.7  413.89
  4995.3  411.77  4995.5  411.27  4999.0  411.27  4999.3  411.77  5010.3  412.20
  5020.5  413.16  5040.9  415.81  5071.5  416.51  5091.9  417.76  5122.5  418.05
  5132.7  419.07  5193.8  421.42  5224.4  423.81  5234.6  425.32  5255.0  426.58
#Mann=3,-1,0
  4664.7    0.05       0  4995.3    0.04       0  4999.3    0.05       0
Bank Sta=4995.3,4999.3
Exp/Cntr=0.3,0.1

Chan Stop Cuts=-1