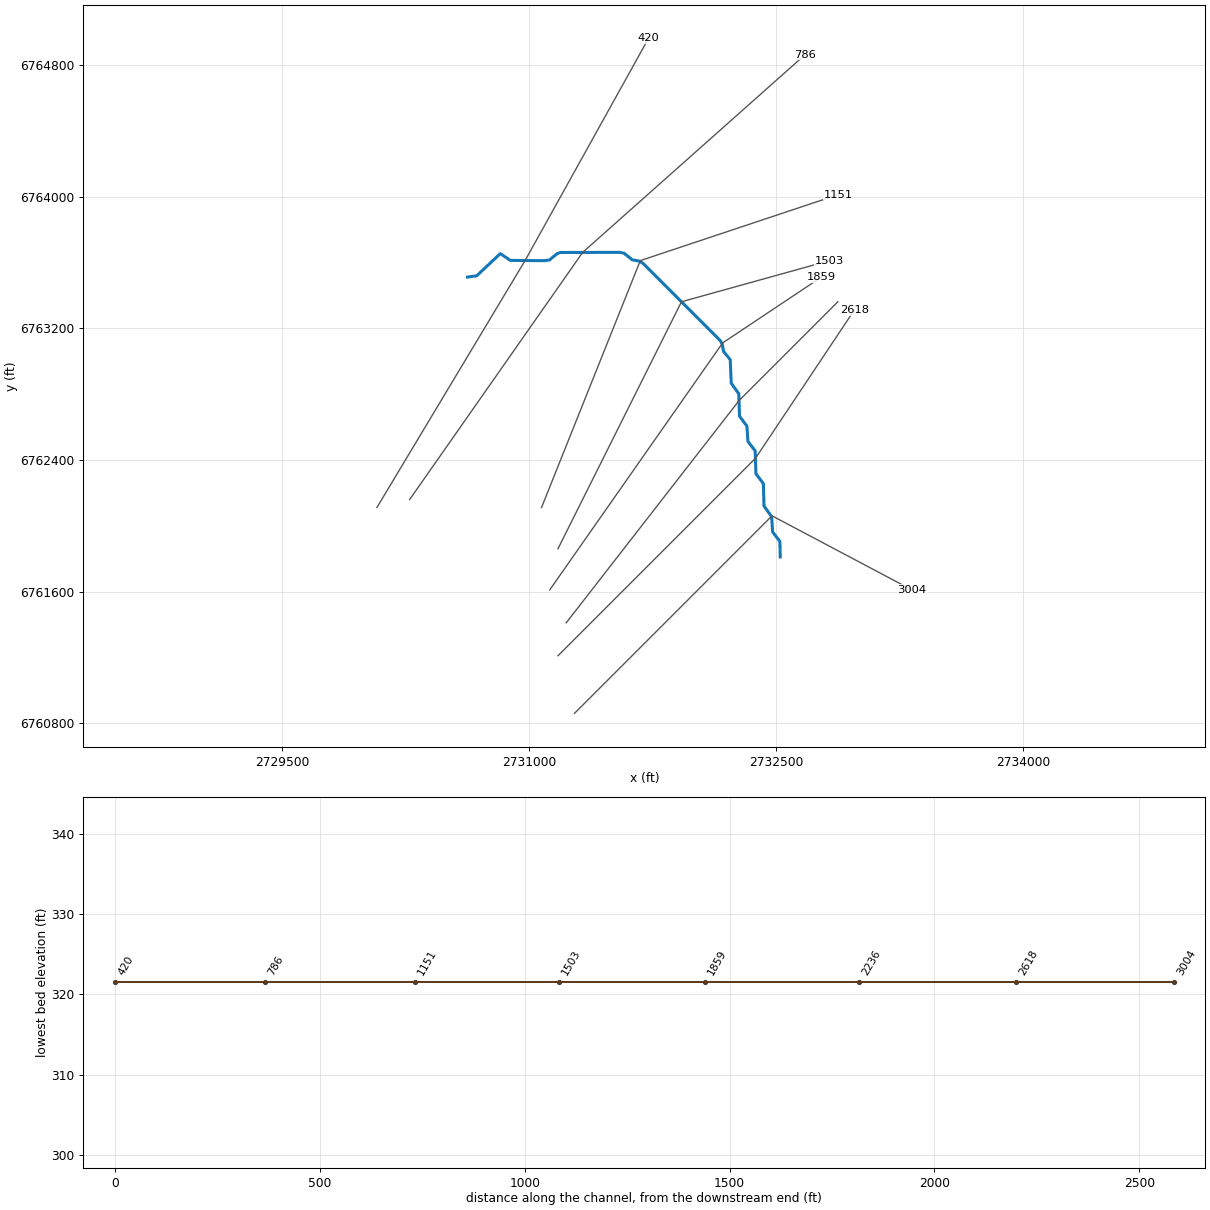
--- Caney Creek T 2.prj (project) ---

Proj Title=Caney Creek T 2 Base Level Engineering
Current Plan=p01
Default Exp/Contr=0.3,0.1
English Units
Geom File=g01
Flow File=f01
Plan File=p01
BEGIN DESCRIPTION:
Caney Creek T 2
END DESCRIPTION:

--- Caney Creek T 2.p01 (plan) ---

Plan Title=Multiple Run
Short Identifier=Multiple
Geom File=g01
Flow File=f01
Subcritical Flow
K Sum by GR= 0
Std Step Tol= 0.01
Critical Tol= 0.01
Num of Std Step Trials= 20
Max Error Tol= 0.3
Flow Tol Ratio= 0.001
Split Flow NTrial= 30
Split Flow Tol= 0.02
Split Flow Ratio= 0.02
Log Output Level= 0
Friction Slope Method= 1
Unsteady Friction Slope Method= 2
Unsteady Bridges Friction Slope Method= 1
Parabolic Critical Depth
Global Vel Dist=  1 , 1 , 1
Global Log Level= 0
CheckData=True
Encroach Param= -1, 0, 0, 0
BEGIN DESCRIPTION:
Multiple Run
END DESCRIPTION:

--- Caney Creek T 2.f01 (steady flow) ---

Flow Title=Multiple
Number of Profiles=7
Profile Names=10-year,25-year,50-year,1pct_min,100-year,1pct_plu,500-year
River Rch & RM= Caney Creek T 2,Reach-1,3004
     476     619     731     428     854    1705    1165
Boundary for River Rch & Prof#=Caney Creek T 2,Reach-1,1
Up Type=0
Dn Type=3
Dn Slope=0.005
Boundary for River Rch & Prof#=Caney Creek T 2,Reach-1,2
Up Type=0
Dn Type=3
Dn Slope=0.005
Boundary for River Rch & Prof#=Caney Creek T 2,Reach-1,3
Up Type=0
Dn Type=3
Dn Slope=0.005
Boundary for River Rch & Prof#=Caney Creek T 2,Reach-1,4
Up Type=0
Dn Type=3
Dn Slope=0.005
Boundary for River Rch & Prof#=Caney Creek T 2,Reach-1,5
Up Type=0
Dn Type=3
Dn Slope=0.005
Boundary for River Rch & Prof#=Caney Creek T 2,Reach-1,6
Up Type=0
Dn Type=3
Dn Slope=0.005
Boundary for River Rch & Prof#=Caney Creek T 2,Reach-1,7
Up Type=0
Dn Type=3
Dn Slope=0.005

--- Caney Creek T 2.g01 (geometry) ---

Geom Title=Existing Conditions

River Reach=Caney Creek T 2,Reach-1
Reach XY= 30
      2732526.00      6761811.00      2732523.78      6761905.53
      2732479.83      6761962.58      2732473.53      6762055.43
      2732427.39      6762120.67      2732423.61      6762255.47
      2732378.27      6762316.94      2732373.61      6762455.47
      2732329.86      6762512.60      2732323.53      6762605.43
      2732278.39      6762666.53      2732274.61      6762801.33
      2732228.39      6762866.53      2732222.24      6763009.44
      2732182.14      6763058.83      2732173.39      6763105.38
      2732159.36      6763127.68      2731692.68      6763594.36
      2731670.38      6763608.39      2731627.75      6763615.22
      2731578.35      6763655.29      2731553.32      6763661.11
      2731191.22      6763660.48      2731169.94      6763652.86
      2731124.43      6763614.78      2731089.82      6763610.56
      2730886.43      6763612.39      2730825.90      6763653.68
      2730682.21      6763518.76      2730626.00      6763511.00

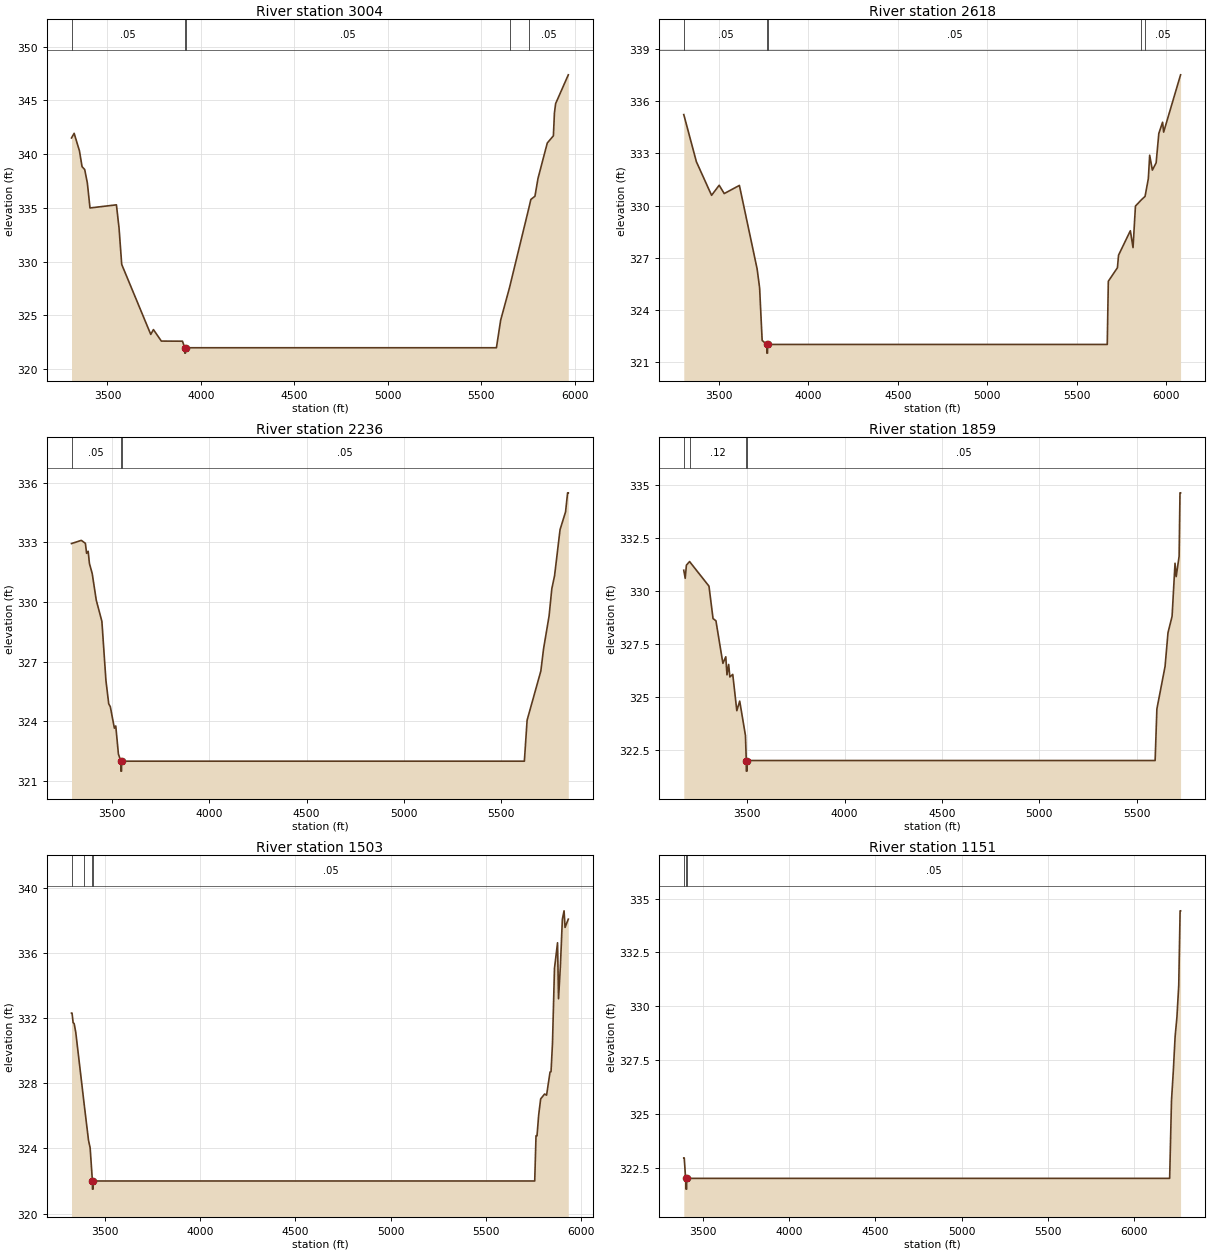
Type RM Length L Ch R = 1,3004,386,386,386
BEGIN DESCRIPTION:
Caney Creek T 2 8.0
END DESCRIPTION:
XS GIS Cut Line= 3
      2731276.02      6760861.02      2732476.00      6762061.00
      2733326.00      6761611.00
#Sta/Elev= 30
  3307.6  341.51  3321.7  341.94  3350.0  340.32  3364.1  338.84  3378.3  338.57
  3392.4  337.32  3406.6  335.00  3548.0  335.29  3562.1  333.12  3576.3  329.75
  3731.8  323.24  3746.0  323.69  3788.4  322.62  3901.5  322.61  3913.7  322.00
  3913.9  321.50  3917.4  321.50  3917.7  322.00  5581.7  322.00  5604.3  324.56
  5651.7  327.59  5755.4  335.00  5765.9  335.79  5787.9  336.09  5804.2  337.75
  5853.9  341.04  5886.6  341.71  5892.2  343.84  5898.5  344.70  5966.4  347.38
#Mann=5,-1,0
  3307.6    0.05       0  3913.7    0.03       0  3917.7    0.05       0
  5651.7    0.12       0  5755.4    0.05       0
Bank Sta=3913.7,3917.7
Exp/Cntr=0.3,0.1

Type RM Length L Ch R = 1,2618,382,382,382
BEGIN DESCRIPTION:
Caney Creek T 2 7.0
END DESCRIPTION:
XS GIS Cut Line= 3
      2731176.02      6761211.02      2732376.00      6762411.00
      2732976.01      6763311.01
#Sta/Elev= 30
  3302.4  335.24  3373.1  332.52  3457.9  330.59  3500.4  331.17  3528.6  330.69
  3613.5  331.16  3712.5  326.36  3726.6  325.26  3740.8  322.23  3767.1  322.00
  3767.3  321.50  3770.8  321.50  3771.1  322.00  5671.0  322.00  5677.0  325.64
  5728.0  326.42  5734.1  327.14  5800.2  328.55  5815.2  327.58  5828.7  329.97
  5860.8  330.32  5882.5  330.53  5900.8  331.55  5908.3  332.90  5923.3  332.04
  5944.4  332.46  5959.4  334.15  5980.4  334.80  5986.4  334.23  6081.1  337.53
#Mann=5,-1,0
  3302.4    0.05       0  3767.1    0.03       0  3771.1    0.05       0
  5860.8    0.12       0  5882.5    0.05       0
Bank Sta=3767.1,3771.1
Exp/Cntr=0.3,0.1

Type RM Length L Ch R = 1,2236,377,377,377
BEGIN DESCRIPTION:
Caney Creek T 2 6.0
END DESCRIPTION:
XS GIS Cut Line= 3
      2731226.02      6761411.03      2732276.00      6762761.00
      2732876.03      6763361.03
#Sta/Elev= 30
  3289.3  332.94  3339.9  333.10  3360.8  332.95  3367.1  332.45  3375.2  332.55
  3381.6  331.94  3396.0  331.43  3416.9  330.09  3445.8  329.03  3466.6  326.06
  3481.1  324.88  3489.2  324.74  3510.1  323.66  3517.3  323.77  3530.9  322.36
  3543.4  322.00  3543.6  321.50  3547.1  321.50  3547.4  322.00  5621.8  322.00
  5635.9  324.06  5706.6  326.53  5720.8  327.66  5749.1  329.30  5763.2  330.67
  5777.3  331.32  5805.6  333.64  5833.9  334.53  5844.5  335.49  5848.1  335.49
#Mann=3,-1,0
  3289.3    0.05       0  3543.4    0.03       0  3547.4    0.05       0
Bank Sta=3543.4,3547.4
Exp/Cntr=0.3,0.1

Type RM Length L Ch R = 1,1859,356,356,356
BEGIN DESCRIPTION:
Caney Creek T 2 5.0
END DESCRIPTION:
XS GIS Cut Line= 3
      2731125.99      6761610.99      2732176.00      6763111.00
      2732775.99      6763511.00
#Sta/Elev= 30
  3174.3  330.97  3181.7  330.59  3187.8  331.21  3204.1  331.38  3303.8  330.22
  3324.7  328.69  3339.5  328.59  3375.3  326.58  3390.1  326.89  3396.2  326.04
  3404.9  326.53  3411.0  325.94  3425.9  326.06  3446.8  324.35  3461.6  324.80
  3491.2  323.18  3495.4  322.00  3495.6  321.50  3499.1  321.50  3499.4  322.00
  5595.7  322.00  5604.7  324.43  5646.8  326.44  5661.8  328.03  5682.8  328.80
  5697.9  331.30  5703.9  330.67  5718.9  331.63  5723.4  334.62  5726.4  334.62
#Mann=4,-1,0
  3174.3    0.05       0  3204.1    0.12       0  3495.4    0.03       0
  3499.4    0.05       0
Bank Sta=3495.4,3499.4
Exp/Cntr=0.3,0.1

Type RM Length L Ch R = 1,1503,352,352,352
BEGIN DESCRIPTION:
Caney Creek T 2 4.0
END DESCRIPTION:
XS GIS Cut Line= 3
      2731175.98      6761860.96      2731926.00      6763361.00
      2732826.02      6763611.01
#Sta/Elev= 30
  3322.9  332.31  3325.7  332.31  3331.3  331.73  3336.9  331.66  3345.3  331.13
  3390.7  326.59  3412.4  324.49  3420.8  324.04  3432.8  322.00  3433.0  321.50
  3436.5  321.50  3436.8  322.00  5757.6  322.00  5764.4  324.78  5769.6  324.77
  5778.4  326.05  5788.8  327.04  5809.5  327.34  5819.9  327.27  5838.1  328.69
  5843.3  328.71  5851.0  330.46  5861.4  335.05  5877.5  336.63  5882.7  333.19
  5892.6  335.23  5902.9  338.08  5911.8  338.59  5917.0  337.57  5934.1  338.08
#Mann=4,-1,0
  3322.9    0.12       0  3390.7    0.05       0  3432.8    0.03       0
  3436.8    0.05       0
Bank Sta=3432.8,3436.8
Exp/Cntr=0.3,0.1

Type RM Length L Ch R = 1,1151,365,365,365
BEGIN DESCRIPTION:
Caney Creek T 2 3.0
END DESCRIPTION:
XS GIS Cut Line= 3
      2731075.99      6762110.98      2731676.00      6763611.00
      2732876.02      6764011.01
#Sta/Elev= 18
  3388.7  322.95  3391.4  322.95  3398.1  322.14  3401.5  322.00  3401.8  321.50
  3405.3  321.50  3405.5  322.00  4994.8  322.00  5001.6  322.00  5004.3  322.00
  6205.9  322.00  6216.5  325.61  6227.0  326.97  6237.6  328.59  6248.1  329.50
  6258.6  330.97  6266.5  334.43  6269.2  334.43
#Mann=3,-1,0
  3388.7    0.05       0  3401.5    0.03       0  3405.5    0.05       0
Bank Sta=3401.5,3405.5
Exp/Cntr=0.3,0.1

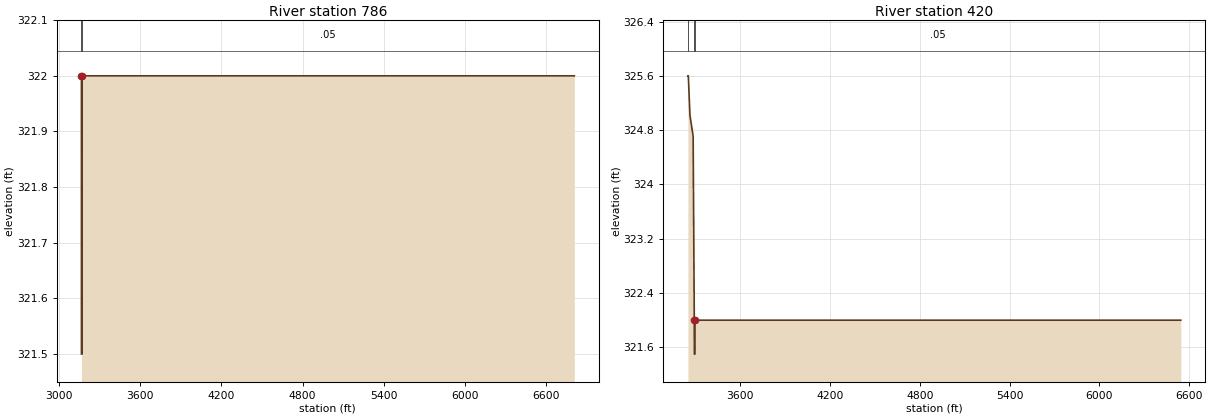
Type RM Length L Ch R = 1,786,366,366,366
BEGIN DESCRIPTION:
Caney Creek T 2 2.0
END DESCRIPTION:
XS GIS Cut Line= 3
      2730274.86      6762159.38      2731326.00      6763661.00
      2732676.00      6764861.00
#Sta/Elev= 7
  3167.0  322.00  3167.2  321.50  3170.7  321.50  3171.0  322.00  5000.0  322.00
  5003.3  322.00  6806.2  322.00
#Mann=2,-1,0
  3167.0    0.03       0  3171.0    0.05       0
Bank Sta=3167,3171
Exp/Cntr=0.3,0.1

Type RM Length L Ch R = 1,420,0,0,0
BEGIN DESCRIPTION:
Caney Creek T 2 1.0
END DESCRIPTION:
XS GIS Cut Line= 3
      2730075.99      6762110.98      2730976.00      6763611.00
      2731726.02      6764961.04
#Sta/Elev= 11
  3250.8  325.60  3253.7  325.60  3264.4  325.02  3285.8  324.71  3293.5  322.00
  3293.8  321.50  3297.3  321.50  3297.5  322.00  4997.2  322.00  5000.1  322.00
  6544.5  322.00
#Mann=3,-1,0
  3250.8    0.05       0  3293.5    0.03       0  3297.5    0.05       0
Bank Sta=3293.5,3297.5
Exp/Cntr=0.3,0.1

Chan Stop Cuts=-1