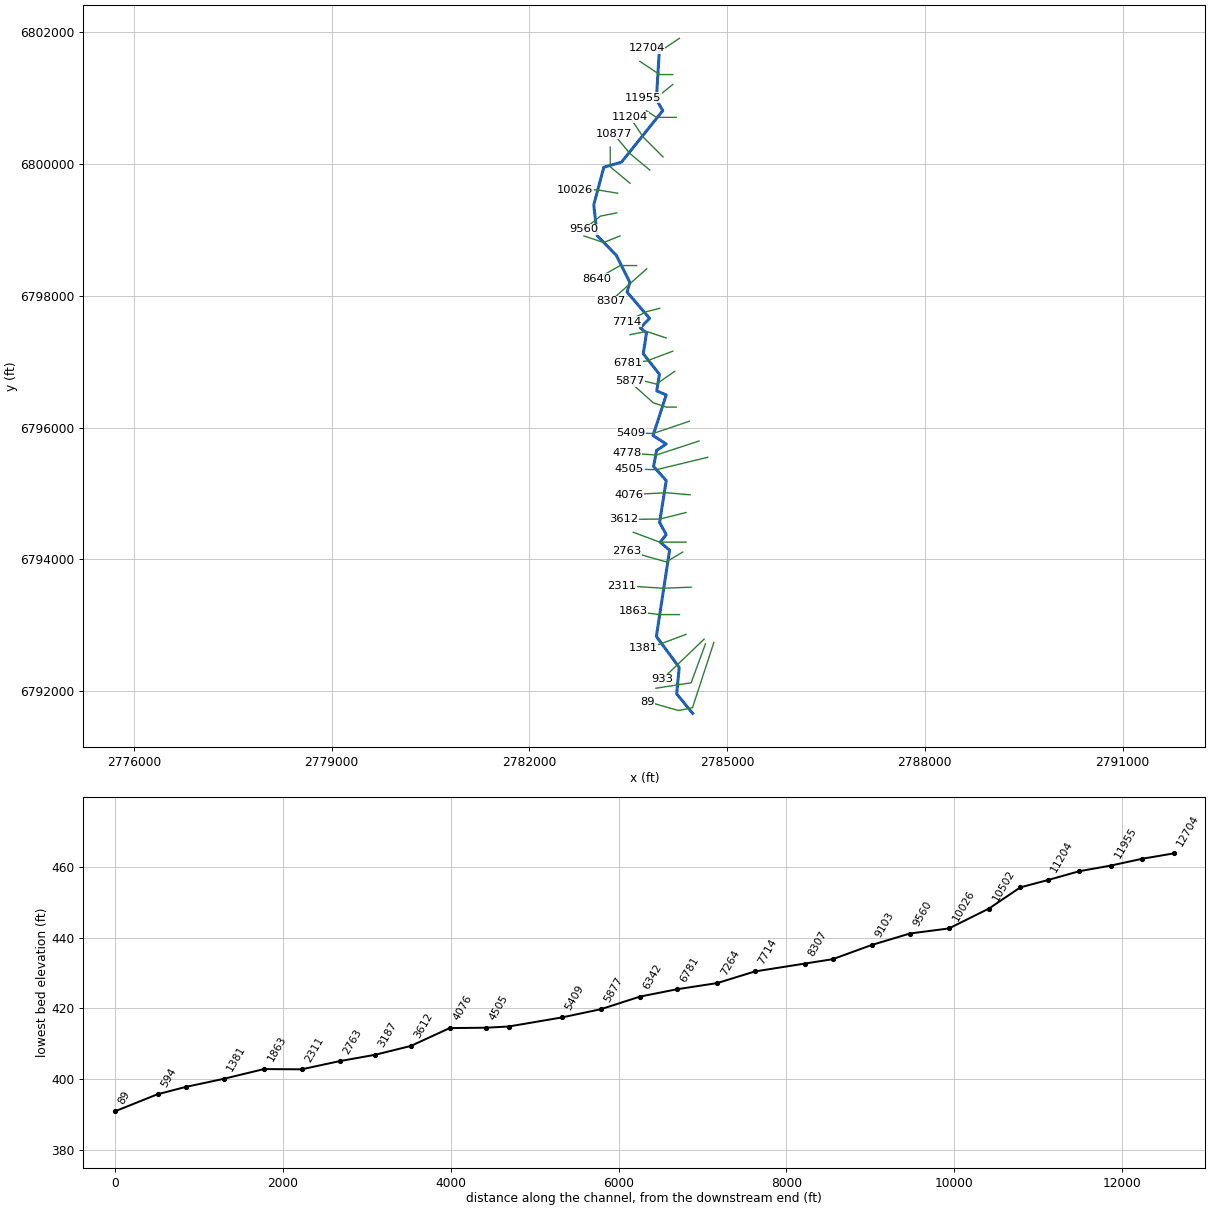
--- Caney Creek T 20.prj (project) ---

Proj Title=Caney Creek T 20 Base Level Engineering
Current Plan=p01
Default Exp/Contr=0.3,0.1
English Units
Geom File=g01
Flow File=f01
Plan File=p01
Y Axis Title=Elevation
X Axis Title(PF)=Main Channel Distance
X Axis Title(XS)=Station
BEGIN DESCRIPTION:
Caney Creek T 20
END DESCRIPTION:
DSS Export Rating Curves= 0
DSS Export Rating Curve Sorted= 0
DSS Export Volume Flow Curves= 0
DXF OffsetX= 0
DXF OffsetY= 0
DXF ScaleX= 1
DXF ScaleY= 10

--- Caney Creek T 20.p01 (plan) ---

Plan Title=Multiple Run
Short Identifier=Multiple
Geom File=g01
Flow File=f01
Subcritical Flow
K Sum by GR= 0
Std Step Tol= 0.01
Critical Tol= 0.01
Num of Std Step Trials= 20
Max Error Tol= 0.3
Flow Tol Ratio= 0.001
Split Flow NTrial= 30
Split Flow Tol= 0.02
Split Flow Ratio= 0.02
Log Output Level= 0
Friction Slope Method= 1
Unsteady Friction Slope Method= 2
Unsteady Bridges Friction Slope Method= 1
Parabolic Critical Depth
Global Vel Dist=  1 , 1 , 1
Global Log Level= 0
CheckData=True
Encroach Param= -1, 0, 0, 0
BEGIN DESCRIPTION:
Multiple Run
END DESCRIPTION:

--- Caney Creek T 20.f01 (steady flow) ---

Flow Title=Multiple
Number of Profiles=7
Profile Names=10-year,25-year,50-year,1pct_min,100-year,1pct_plu,500-year
River Rch & RM= Caney Creek T 20,Reach-1,12704
     445     590     708     423     843    1682    1197
River Rch & RM= Caney Creek T 20,Reach-1,10026
     891    1226    1506     917    1831    3652    2713
Boundary for River Rch & Prof#=Caney Creek T 20,Reach-1,1
Up Type=0
Dn Type=3
Dn Slope=0.005
Boundary for River Rch & Prof#=Caney Creek T 20,Reach-1,2
Up Type=0
Dn Type=3
Dn Slope=0.005
Boundary for River Rch & Prof#=Caney Creek T 20,Reach-1,3
Up Type=0
Dn Type=3
Dn Slope=0.005
Boundary for River Rch & Prof#=Caney Creek T 20,Reach-1,4
Up Type=0
Dn Type=3
Dn Slope=0.005
Boundary for River Rch & Prof#=Caney Creek T 20,Reach-1,5
Up Type=0
Dn Type=3
Dn Slope=0.005
Boundary for River Rch & Prof#=Caney Creek T 20,Reach-1,6
Up Type=0
Dn Type=3
Dn Slope=0.005
Boundary for River Rch & Prof#=Caney Creek T 20,Reach-1,7
Up Type=0
Dn Type=3
Dn Slope=0.005

--- Caney Creek T 20.g01 (geometry) ---

Geom Title=Existing Conditions
Program Version=4.10

River Reach=Caney Creek T 20,Reach-1
Reach XY= 30
        2783976.        6801811.      2783925.81      6800983.65
       2784022.9      6800812.65      2783396.16      6800030.63
      2783128.58      6799953.44       2782975.7      6799381.39
      2783029.52      6798912.46      2783317.84      6798617.05
      2783524.38      6798204.96      2783481.02      6798058.47
       2783822.7      6797659.24      2783683.44      6797514.41
      2783776.35      6797438.25       2783727.2       6797121.5
      2783972.54       6796809.5      2783931.28      6796558.29
      2784075.44      6796495.42       2783875.3      6795880.76
      2784075.47      6795750.32      2783929.18      6795653.28
      2783883.75      6795411.09      2784075.34      6795195.17
      2783975.12        6794561.      2784075.95      6794375.06
        2783983.      6794260.78      2784126.44      6794138.29
      2783926.04      6792829.32      2784272.63      6792359.26
      2784234.04      6791957.68        2784476.        6791661.

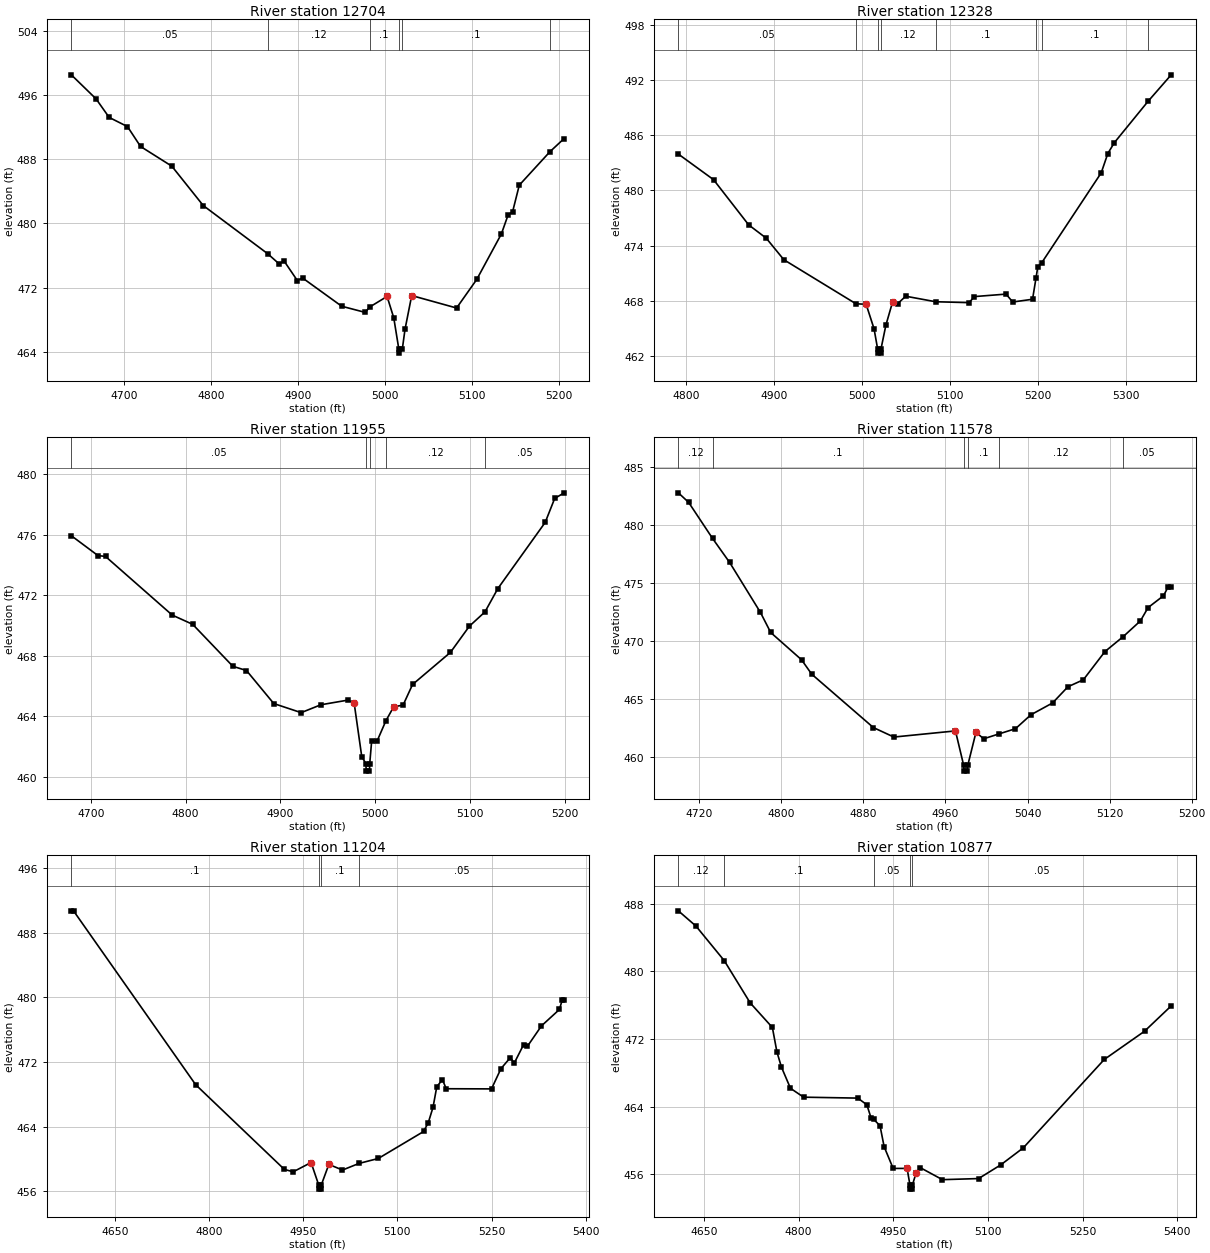
Type RM Length L Ch R = 1 ,12704   ,376,376,376
BEGIN DESCRIPTION:
Caney Creek T 20 28.0
END DESCRIPTION:
XS GIS Cut Line= 3
      2784275.97      6801910.98        2783976.        6801711.
      2783775.98      6801761.01
#Sta/Elev= 30
  4639.6  498.49  4668.1  495.49  4683.1  493.19  4704.2  492.04  4719.2  489.57
  4755.2  487.11  4791.3  482.21  4865.4  476.21  4878.4  474.96  4884.4  475.28
  4899.5  472.87  4905.5  473.19  4950.5  469.67  4977.6   468.9  4982.5  469.56
  5002.7  470.89  5010.4  468.21  5016.2  464.33  5016.4  463.83  5020.2  464.33
  5023.3  466.79    5031     471  5082.6  469.45  5105.8  473.01  5134.1  478.67
  5141.9  481.06    5147  481.43  5154.7  484.75  5189.9  488.91  5206.3  490.56
#Mann= 6 ,-1 , 0
  4639.6     .05       0  4865.4     .12       0  4982.5      .1       0
  5016.2     .07       0  5020.2      .1       0  5189.9     .12       0
Bank Sta=5002.7,5031
XS Rating Curve= 0 ,0
Exp/Cntr=0.3,0.1

Type RM Length L Ch R = 1 ,12328   ,373,373,373
BEGIN DESCRIPTION:
Caney Creek T 20 27.0
END DESCRIPTION:
XS GIS Cut Line= 3
      2784176.05        6801361.        2783976.        6801361.
        2783676.        6801561.
#Sta/Elev= 30
  4791.1  483.96  4831.1  481.18  4871.1  476.26  4891.1  474.81  4911.1  472.47
  4993.1  467.68  5004.7  467.62  5013.7  464.96  5017.7  462.81  5017.9  462.31
  5021.4  462.31  5021.7  462.81  5027.2  465.36  5034.7  467.85  5040.7   467.7
  5049.7   468.5  5083.7   467.9  5121.8   467.8  5127.9  468.46  5163.9  468.73
  5171.4  467.87    5194  468.17  5197.9  470.47    5200  471.71  5204.5  472.15
  5272.1  481.92  5279.6  484.02  5287.1  485.21  5325.4   489.7  5351.7  492.58
#Mann= 8 ,-1 , 0
  4791.1     .05       0  4993.1     .12       0  5017.7     .07       0
  5021.7     .12       0  5083.7      .1       0  5197.9     .12       0
  5204.5      .1       0  5325.4     .05       0
Bank Sta=5004.7,5034.7
XS Rating Curve= 0 ,0
Exp/Cntr=0.3,0.1

Type RM Length L Ch R = 1 ,11955   ,377,377,377
BEGIN DESCRIPTION:
Caney Creek T 20 26.0
END DESCRIPTION:
XS GIS Cut Line= 3
      2784176.04      6801211.03        2783926.        6801011.
        2783726.        6801011.
#Sta/Elev= 30
  4679.4  475.93  4707.5  474.62  4715.5  474.56  4785.9  470.69  4807.5  470.08
  4849.9  467.31  4864.3  467.03  4893.1  464.85    4922  464.25  4942.8  464.77
  4971.6  465.08    4978  464.86    4986  461.33  4990.4  460.89  4990.6  460.39
  4994.1  460.39  4994.4  460.89  4996.4  462.37  5002.1  462.37  5011.5  463.72
  5019.6  464.63  5029.6  464.75  5039.6  466.11  5079.6  468.23  5099.6  469.96
    5116   470.9  5129.6  472.44  5179.6  476.81  5189.6  478.39  5199.6  478.76
#Mann= 5 ,-1 , 0
  4679.4     .05       0  4990.4     .04       0  4994.4     .05       0
  5011.5     .12       0    5116     .05       0
Bank Sta=4978,5019.6
XS Rating Curve= 0 ,0
Exp/Cntr=0.3,0.1

Type RM Length L Ch R = 1 ,11578   ,374,374,374
BEGIN DESCRIPTION:
Caney Creek T 20 25.0
END DESCRIPTION:
XS GIS Cut Line= 3
      2784225.97        6800711.        2783926.        6800711.
      2783776.04      6800810.97
#Sta/Elev= 30
  4699.8   482.8  4709.8  481.98  4733.1  478.87  4749.8  476.79  4779.8  472.48
  4789.8  470.75  4819.8   468.4  4829.8  467.15  4889.8  462.55  4909.8  461.73
  4969.8  462.26  4977.8  459.29    4978  458.79  4981.5  458.79  4981.8  459.29
  4989.8  462.14  4997.3  461.58  5012.5  462.01  5028.3  462.45  5043.3  463.65
  5064.4  464.67  5079.4  466.07  5094.4  466.67  5115.4   469.1  5133.3   470.4
    5150  471.75  5157.5   472.9  5172.5  473.92    5177  474.68    5180  474.68
#Mann= 6 ,-1 , 0
  4699.8     .12       0  4733.1      .1       0  4977.8     .07       0
  4981.8      .1       0  5012.5     .12       0  5133.3     .05       0
Bank Sta=4969.8,4989.8
XS Rating Curve= 0 ,0
Exp/Cntr=0.3,0.1

Type RM Length L Ch R = 1 ,11204   ,327,327,327
BEGIN DESCRIPTION:
Caney Creek T 20 24.0
END DESCRIPTION:
XS GIS Cut Line= 3
      2784025.98      6800111.02        2783726.        6800411.
        2783526.        6800711.
#Sta/Elev= 30
  4580.8  490.72  4584.3  490.72  4778.8  469.21  4920.2  458.72  4934.3  458.44
  4962.6  459.58  4974.8  456.79    4975  456.29  4978.5  456.29  4978.8  456.79
  4990.9  459.35  5012.6  458.65  5038.9  459.47  5069.6  460.08  5141.8  463.42
  5149.3  464.53  5156.8  466.42  5162.8  468.97  5171.8  469.83  5177.8  468.71
  5249.9  468.69  5264.9  471.19    5280  472.57    5286  471.86    5301  474.16
    5307  473.95  5329.5  476.49  5358.1  478.52  5362.6  479.72  5365.6  479.72
#Mann= 4 ,-1 , 0
  4580.8      .1       0  4974.8     .07       0  4978.8      .1       0
  5038.9     .05       0
Bank Sta=4962.6,4990.9
XS Rating Curve= 0 ,0
Exp/Cntr=0.3,0.1

Type RM Length L Ch R = 1 ,10877   ,375,375,375
BEGIN DESCRIPTION:
Caney Creek T 20 23.0
END DESCRIPTION:
XS GIS Cut Line= 3
        2783826.        6799911.        2783526.        6800161.
      2783276.01      6800460.98
#Sta/Elev= 30
  4609.5  487.16  4637.5  485.35  4682.3  481.26  4723.4  476.26  4758.5  473.36
  4765.7  470.47  4772.9  468.66  4787.2  466.16    4808  465.11  4893.9     465
  4908.2  464.21  4914.7   462.7    4919  462.49  4929.1  461.73  4935.6  459.25
  4949.9  456.68    4972  456.68  4976.5  454.73  4976.8  454.23  4980.3  454.23
  4980.5  454.73  4986.3  456.16  4992.9  456.77    5028  455.35  5085.3  455.48
  5120.4   457.1  5156.2  459.12  5284.4  469.57  5348.2  472.91  5390.5  475.91
#Mann= 5 ,-1 , 0
  4609.5     .12       0  4682.3      .1       0    4919     .05       0
  4976.5     .04       0  4980.5     .05       0
Bank Sta=4972,4986.3
XS Rating Curve= 0 ,0
Exp/Cntr=0.3,0.1

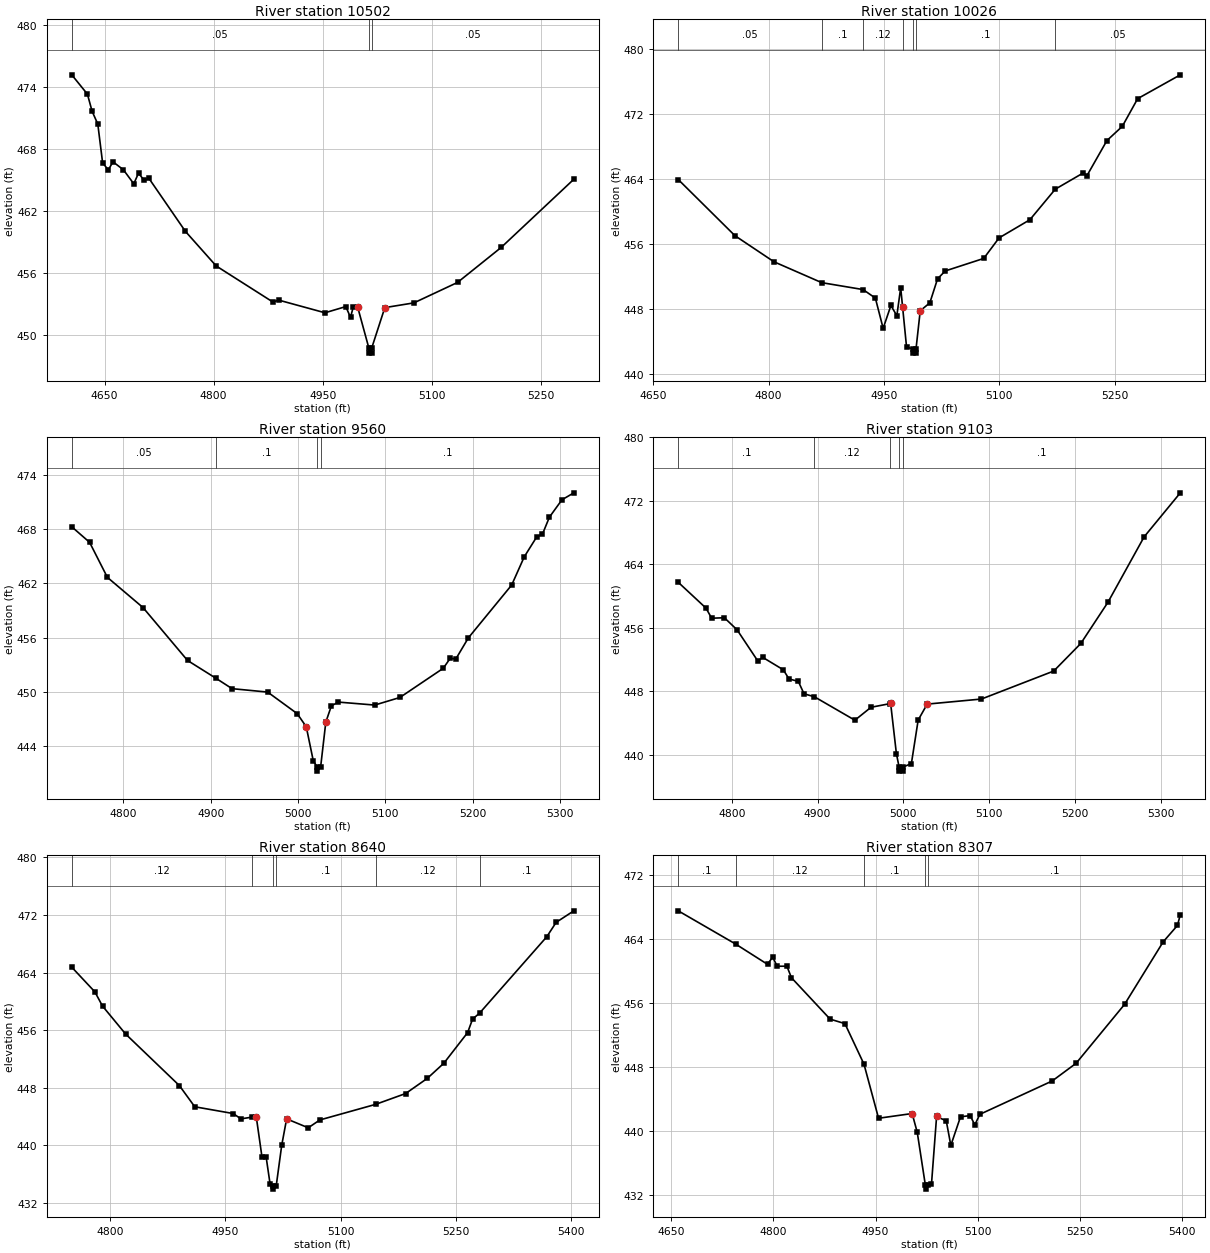
Type RM Length L Ch R = 1 ,10502   ,476,476,476
BEGIN DESCRIPTION:
Caney Creek T 20 22.0
END DESCRIPTION:
XS GIS Cut Line= 3
      2783526.04      6799710.97        2783226.        6799961.
        2783226.      6800261.04
#Sta/Elev= 30
  4604.8   475.2  4626.3  473.33  4632.8  471.66  4640.6  470.43  4647.2  466.68
    4655  465.98  4661.5  466.77  4675.8     466  4690.1  464.64  4696.6  465.67
  4704.4  464.97  4710.9  465.17  4761.1  460.03  4803.4  456.68  4881.5  453.18
  4889.3  453.37  4953.1  452.14  4981.7  452.74  4988.2   451.7  4992.1  452.73
  4997.9  452.73  5013.4  448.73  5013.6  448.23  5017.1  448.23  5017.4  448.73
  5035.4  452.64  5075.4   453.1  5135.4  455.08  5195.4  458.47  5295.4  465.08
#Mann= 3 ,-1 , 0
  4604.8     .05       0  5013.4     .04       0  5017.4     .05       0
Bank Sta=4997.9,5035.4
XS Rating Curve= 0 ,0
Exp/Cntr=0.3,0.1

Type RM Length L Ch R = 1 ,10026   ,466,466,466
BEGIN DESCRIPTION:
Caney Creek T 20 21.0
END DESCRIPTION:
XS GIS Cut Line= 3
      2783338.67      6799558.78        2783026.        6799611.
      2782690.59      6799603.14
#Sta/Elev= 30
  4682.6  463.98  4756.3  457.07    4807  453.86  4869.1  451.29  4922.8  450.44
  4938.8  449.39  4948.9  445.67    4959  448.48  4966.7  447.22  4971.7  450.66
  4974.2  448.27  4979.3  443.39  4987.3  443.12  4987.7  442.62  4991.3  442.62
  4991.6  443.12  4997.1  447.83  5009.6  448.81  5019.6  451.76  5029.6  452.73
  5079.6  454.27  5099.6   456.8  5139.6  459.03  5172.6  462.79  5208.8  464.78
  5213.8  464.46  5239.7  468.77  5259.7  470.52  5279.7  473.93  5335.1  476.86
#Mann= 7 ,-1 , 0
  4682.6     .05       0  4869.1      .1       0  4922.8     .12       0
  4974.2      .1       0  4987.3     .07       0  4991.6      .1       0
  5172.6     .05       0
Bank Sta=4974.2,4997.1
XS Rating Curve= 0 ,0
Exp/Cntr=0.3,0.1

Type RM Length L Ch R = 1 ,9560    ,457,457,457
BEGIN DESCRIPTION:
Caney Creek T 20 20.0
END DESCRIPTION:
XS GIS Cut Line= 3
      2783326.02        6799261.        2783076.        6799211.
      2782826.02      6799011.02
#Sta/Elev= 30
  4740.8  468.29  4761.2  466.57  4781.6  462.68  4822.4  459.33  4873.4  453.46
    4906  451.48  4924.4  450.33  4965.2  449.95    4999  447.56  5009.4   446.1
  5017.4  442.34  5021.6  441.68    5022  441.18  5025.9  441.68  5031.8  446.62
  5038.2  448.43  5046.2  448.84  5087.8  448.51  5116.6  449.35  5166.3  452.59
  5174.3   453.7  5180.7  453.62  5195.1  455.97  5244.7  461.83  5259.1  464.96
  5273.5  467.19  5279.9  467.46  5287.9  469.36  5302.3  471.29  5315.9  472.06
#Mann= 4 ,-1 , 0
  4740.8     .05       0    4906      .1       0  5021.6     .07       0
  5025.9      .1       0
Bank Sta=5009.4,5031.8
XS Rating Curve= 0 ,0
Exp/Cntr=0.3,0.1

Type RM Length L Ch R = 1 ,9103    ,463,463,463
BEGIN DESCRIPTION:
Caney Creek T 20 19.0
END DESCRIPTION:
XS GIS Cut Line= 3
      2783375.99        6798911.        2783126.        6798811.
      2782825.98      6798911.01
#Sta/Elev= 30
  4737.5  461.73  4769.8  458.48  4776.5   457.2  4791.3  457.26  4806.1  455.74
  4830.4  451.79  4835.8  452.28    4860   450.7  4866.7  449.54  4877.5  449.24
  4884.2  447.67  4896.2   447.3  4943.5  444.34  4962.3  445.97  4984.9  446.44
  4985.2  446.45  4991.9  440.13  4995.1  438.42  4995.5  437.92  4999.1  437.92
  4999.5  438.42  5009.4  438.88  5017.3  444.36  5027.8  446.37  5091.1  447.01
  5175.4  450.54    5207  454.02  5238.6  459.21  5280.8  467.46    5323  473.01
#Mann= 5 ,-1 , 0
  4737.5      .1       0  4896.2     .12       0  4984.9      .1       0
  4995.1     .07       0  4999.5      .1       0
Bank Sta=4985.2,5027.8
XS Rating Curve= 0 ,0
Exp/Cntr=0.3,0.1

Type RM Length L Ch R = 1 ,8640    ,333,333,333
BEGIN DESCRIPTION:
Caney Creek T 20 18.0
END DESCRIPTION:
XS GIS Cut Line= 3
      2783626.03        6798461.        2783376.        6798461.
      2783026.04      6798261.02
#Sta/Elev= 30
  4750.3  464.75  4780.3  461.33  4790.3  459.35  4820.3  455.47  4890.3   448.3
  4910.3  445.36  4960.3  444.42  4970.3  443.68  4984.1  443.91  4990.3  443.96
  4997.8  438.33  5003.2  438.33  5008.2  434.68  5011.7  434.42  5012.2  433.92
  5016.3  434.42  5023.4  440.01  5029.8  443.68  5057.9  442.44    5073  443.53
  5145.4  445.69  5184.6   447.2  5212.7   449.3  5234.3  451.41  5265.2  455.66
  5271.7  457.55  5280.7  458.36  5368.2  468.98  5380.4  470.98  5403.4  472.58
#Mann= 6 ,-1 , 0
  4750.3     .12       0  4984.1      .1       0  5011.7     .07       0
  5016.3      .1       0  5145.4     .12       0  5280.7      .1       0
Bank Sta=4990.3,5029.8
XS Rating Curve= 0 ,0
Exp/Cntr=0.3,0.1

Type RM Length L Ch R = 1 ,8307    ,593,593,593
BEGIN DESCRIPTION:
Caney Creek T 20 17.0
END DESCRIPTION:
XS GIS Cut Line= 3
       2783779.9      6798412.27      2783526.49      6798186.03
       2783230.6      6797920.75
#Sta/Elev= 30
  4660.3  467.47  4744.5  463.32  4791.4  460.78  4798.9  461.69  4805.6  460.54
  4819.8  460.55  4826.5  459.11  4883.3  453.93    4905  453.37    4933   448.3
  4954.4  441.54  5003.7  442.13  5011.2  439.78  5023.1  433.18  5023.6  432.68
  5027.7  433.18  5032.1  433.31  5039.6  441.76  5053.8  441.21  5060.5  438.15
  5074.7  441.72  5088.9  441.87  5095.7  440.71  5103.1  442.03  5209.3   446.2
  5244.4  448.41  5315.5  455.77  5372.3   463.6  5393.2  465.64  5397.4     467
#Mann= 5 ,-1 , 0
  4660.3      .1       0  4744.5     .12       0    4933      .1       0
  5023.1     .07       0  5027.7      .1       0
Bank Sta=5003.7,5039.6
XS Rating Curve= 0 ,0
Exp/Cntr=0.3,0.1

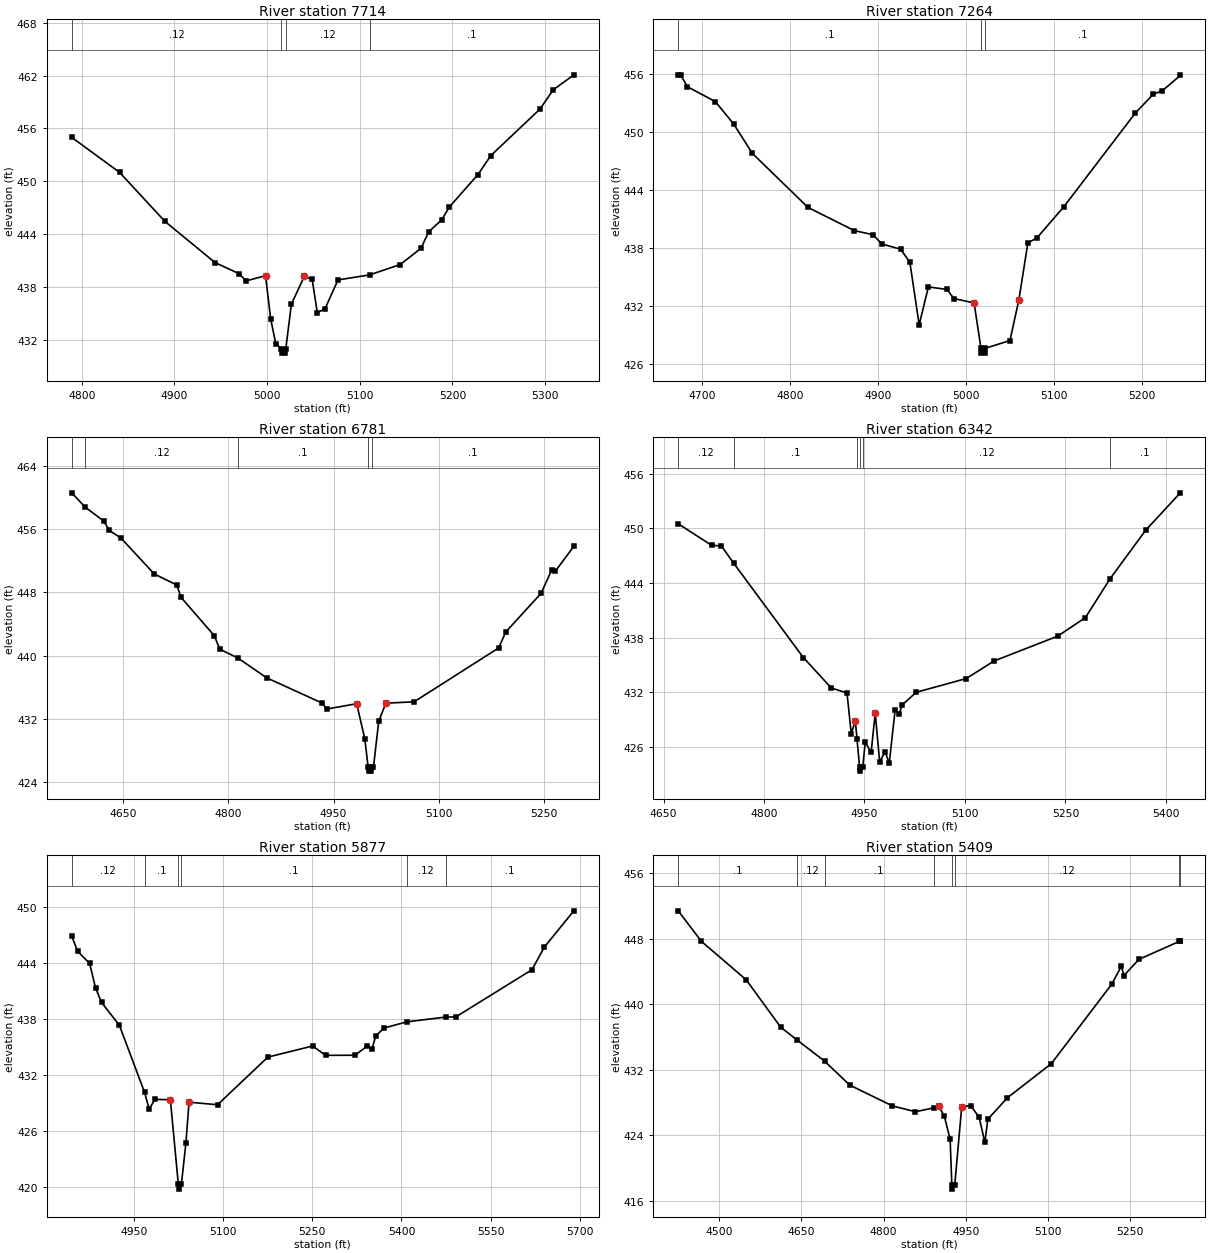
Type RM Length L Ch R = 1 ,7714    ,450,450,450
BEGIN DESCRIPTION:
Caney Creek T 20 16.0
END DESCRIPTION:
XS GIS Cut Line= 3
      2783976.02        6797811.        2783776.        6797761.
      2783475.98      6797610.99
#Sta/Elev= 30
  4789.3  454.98  4840.9     451  4889.8  445.43  4943.9  440.75  4969.7  439.49
  4977.4  438.67  4998.3  439.26  5003.9  434.32  5009.4  431.53  5015.5  430.96
    5016  430.46  5019.7  430.46  5020.2  430.96  5026.2  436.03  5040.2  439.19
  5048.6  438.85  5054.2  435.04  5062.6  435.53  5076.5  438.78  5110.5  439.35
  5143.6  440.53    5166  442.37  5174.4  444.26  5188.3   445.6  5196.7  447.08
  5227.5  450.76  5241.4  452.92  5294.5  458.21  5308.5  460.37  5330.9  462.09
#Mann= 4 ,-1 , 0
  4789.3     .12       0  5015.5     .07       0  5020.2     .12       0
  5110.5      .1       0
Bank Sta=4998.3,5040.2
XS Rating Curve= 0 ,0
Exp/Cntr=0.3,0.1

Type RM Length L Ch R = 1 ,7264    ,483,483,483
BEGIN DESCRIPTION:
Caney Creek T 20 15.0
END DESCRIPTION:
XS GIS Cut Line= 3
        2784076.        6797361.        2783776.        6797461.
      2783525.98        6797411.
#Sta/Elev= 30
  4672.4  455.88    4675  455.88  4682.9  454.65  4714.6  453.12  4735.6  450.79
  4756.7  447.78    4820   442.2  4872.7  439.81  4893.8  439.39  4904.3  438.42
  4925.4  437.89  4935.9  436.55  4946.5  430.09    4957     434  4978.1  433.74
    4986   432.8    5009  432.35  5016.8  427.67  5017.4  427.17  5021.1  427.17
  5021.7  427.67  5049.8  428.47    5060   432.7  5070.2  438.55  5080.4  439.05
    5111  442.26  5192.6  451.96    5213  453.89  5223.2  454.24  5243.6  455.82
#Mann= 3 ,-1 , 0
  4672.4      .1       0  5016.8     .07       0  5021.7      .1       0
Bank Sta=5009,5060
XS Rating Curve= 0 ,0
Exp/Cntr=0.3,0.1

Type RM Length L Ch R = 1 ,6781    ,439,439,439
BEGIN DESCRIPTION:
Caney Creek T 20 14.0
END DESCRIPTION:
XS GIS Cut Line= 3
      2784175.98      6797160.99        2783776.        6797011.
      2783489.45      6796982.97
#Sta/Elev= 30
  4577.1  460.59  4595.7  458.82  4622.5  457.03  4630.5  455.85  4647.4  454.85
  4694.6  450.33  4726.6  448.94  4732.8  447.37    4780  442.54    4788  440.83
  4813.8   439.7  4854.8   437.2    4934     434  4940.2  433.26  4982.9  433.93
  4994.5  429.48  4999.2  425.91  4999.8  425.41  5003.5  425.41  5004.1  425.91
  5006.8  425.91  5014.3   431.7  5024.4     434  5064.6  434.17  5185.1  440.98
  5195.2     443  5245.4  447.87  5260.8  450.86  5265.8  450.68  5292.2  453.83
#Mann= 5 ,-1 , 0
  4577.1     .05       0  4595.7     .12       0  4813.8      .1       0
  4999.2     .07       0  5004.1      .1       0
Bank Sta=4982.9,5024.4
XS Rating Curve= 0 ,0
Exp/Cntr=0.3,0.1

Type RM Length L Ch R = 1 ,6342    ,465,465,465
BEGIN DESCRIPTION:
Caney Creek T 20 13.0
END DESCRIPTION:
XS GIS Cut Line= 3
       2784202.9      6796853.57        2783926.        6796661.
      2783525.99        6796761.
#Sta/Elev= 30
    4672  450.51  4721.7  448.15  4736.5  448.07  4754.8  446.18  4858.7  435.82
  4900.6  432.47    4924  431.92  4930.3  427.45  4936.4  428.86  4938.9  426.87
  4942.7  423.84  4943.3  423.34  4947.6  423.84  4951.2  426.53    4960  425.39
  4966.1  429.73  4972.7  424.36  4980.9  425.48    4987   424.2  4995.8  430.05
  5001.9  429.64  5006.2   430.6  5027.3     432    5102  433.51  5143.3  435.43
  5238.6  438.17  5279.9   440.2  5316.8  444.48  5370.1  449.82  5421.6  453.91
#Mann= 6 ,-1 , 0
    4672     .12       0  4754.8      .1       0  4938.9     .12       0
  4942.7     .07       0  4947.6     .12       0  5316.8      .1       0
Bank Sta=4936.4,4966.1
XS Rating Curve= 0 ,0
Exp/Cntr=0.3,0.1

Type RM Length L Ch R = 1 ,5877    ,468,468,468
BEGIN DESCRIPTION:
Caney Creek T 20 12.0
END DESCRIPTION:
XS GIS Cut Line= 4
      2784225.98        6796311.        2784076.        6796311.
      2783878.04      6796378.03      2783516.86      6796701.45
#Sta/Elev= 30
  4845.9  446.87  4855.9  445.24  4875.9  443.96  4885.9  441.33  4895.9  439.78
  4925.9  437.33  4968.3  430.14  4975.9  428.36  4985.9   429.4  5011.6  429.35
    5025  420.28  5025.7  419.78  5030.1  420.28  5037.7   424.7    5043  429.09
  5090.9  428.82  5175.4  433.92  5250.7  435.11  5272.4  434.11  5321.7  434.12
  5342.7  435.11  5350.2  434.74  5356.9  436.22  5371.1  437.04    5409   437.7
  5474.6  438.21  5491.4  438.23  5619.3  443.28  5640.2  445.71  5689.7  449.59
#Mann= 6 ,-1 , 0
  4845.9     .12       0  4968.3      .1       0    5025     .07       0
  5030.1      .1       0    5409     .12       0  5474.6      .1       0
Bank Sta=5011.6,5043
XS Rating Curve= 0 ,0
Exp/Cntr=0.3,0.1

Type RM Length L Ch R = 1 ,5409    ,631,631,631
BEGIN DESCRIPTION:
Caney Creek T 20 11.0
END DESCRIPTION:
XS GIS Cut Line= 3
      2784425.94       6796096.4        2783876.        6795911.
      2783540.73      6795918.29
#Sta/Elev= 30
  4425.4  451.39  4467.6  447.67  4549.3  442.98  4612.2   437.2  4641.2  435.68
  4692.2  433.06  4738.2  430.13  4815.8   427.6    4858  426.88    4891  427.35
  4900.8  427.54  4910.8  426.31  4921.3  423.53  4924.4  417.94  4925.2  417.44
  4929.7  417.94  4942.4  427.46  4958.5  427.64  4974.1  426.23  4984.6  423.14
    4990  425.96  5025.8  428.59  5105.8  432.74  5215.8  442.42  5233.4  444.61
  5238.4   443.5  5265.8  445.48  5339.4  447.66  5340.9  447.76  5341.1  447.77
#Mann= 8 ,-1 , 0
  4425.4      .1       0  4641.2     .12       0  4692.2      .1       0
    4891     .12       0  4924.4     .07       0  4929.7     .12       0
  5339.4     .05       0  5340.9     .12       0
Bank Sta=4900.8,4942.4
XS Rating Curve= 0 ,0
Exp/Cntr=0.3,0.1

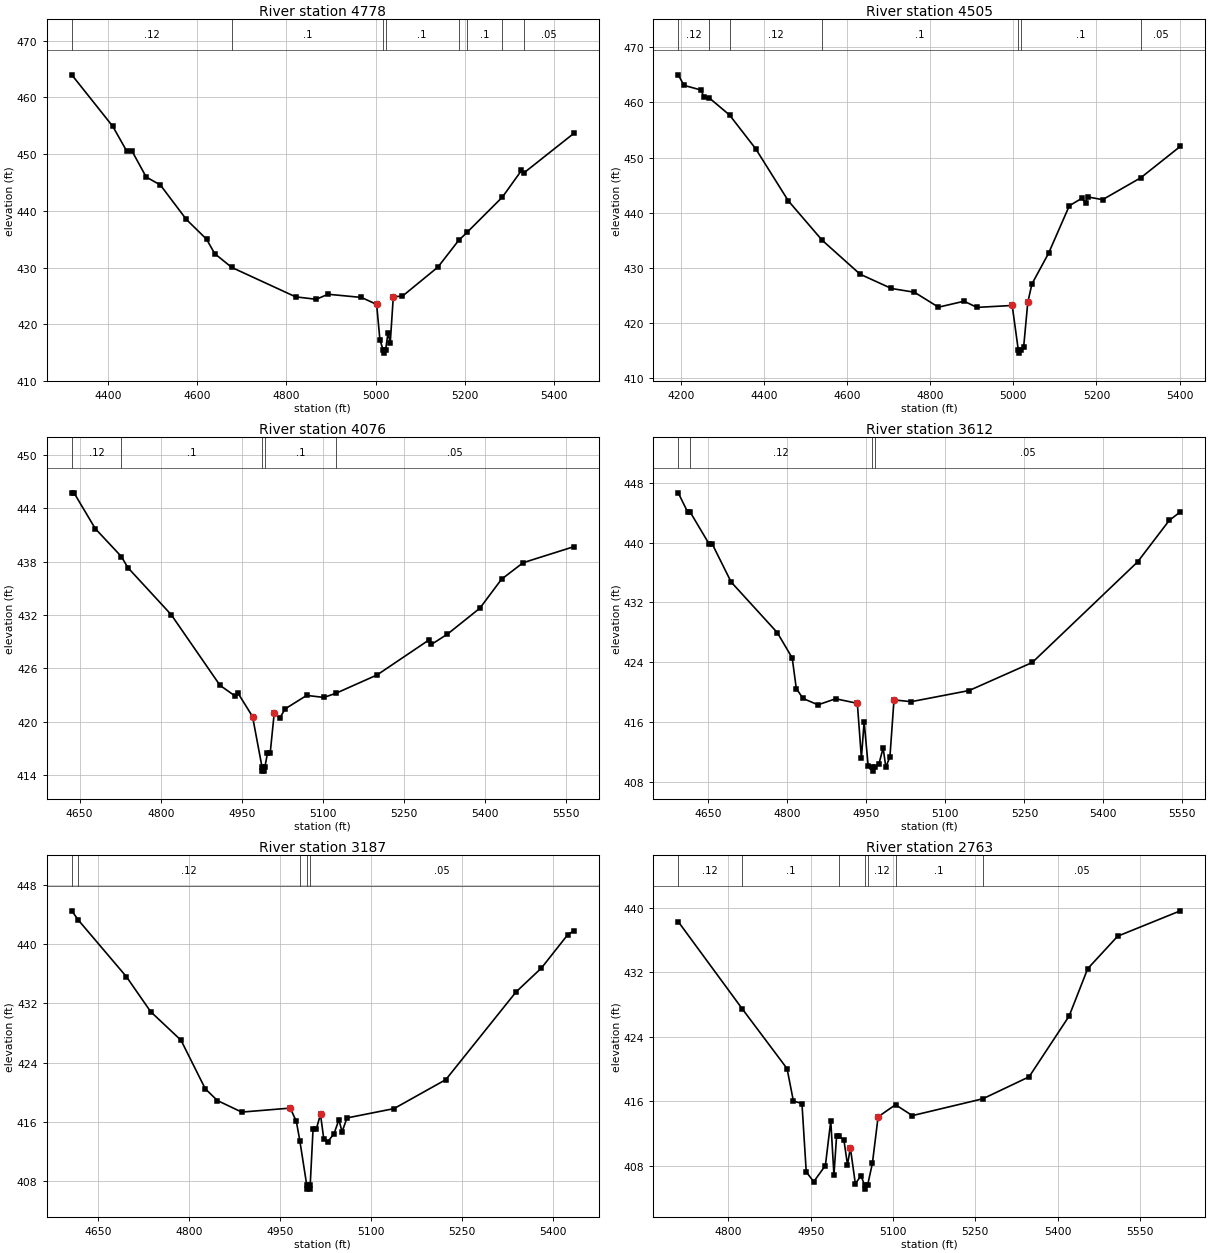
Type RM Length L Ch R = 1 ,4778    ,273,273,273
BEGIN DESCRIPTION:
Caney Creek T 20 10.0
END DESCRIPTION:
XS GIS Cut Line= 3
      2784573.26      6795797.03      2783925.72      6795583.92
      2783481.83      6795613.75
#Sta/Elev= 30
  4318.3     464  4410.2  454.92  4441.7  450.53  4453.5  450.54  4485.3  445.97
  4517.1  444.56  4575.4  438.48  4620.7     435    4639  432.45  4677.1  430.02
  4820.7  424.82  4866.8  424.39  4893.3  425.28  4968.1  424.72  5002.4  423.49
  5009.7  417.27  5017.1  415.39  5017.9  414.89  5022.5  415.39  5027.9   418.5
  5032.9  416.66  5039.8  424.88  5059.9  424.92    5140  430.08  5186.5  434.79
  5205.3   436.2  5284.5  442.42  5327.4  447.12  5332.8  446.69  5444.9  453.67
#Mann= 8 ,-1 , 0
  4318.3     .12       0  4677.1      .1       0  5017.1     .07       0
  5022.5      .1       0  5186.5     .12       0  5205.3      .1       0
  5284.5     .12       0  5332.8     .05       0
Bank Sta=5002.4,5039.8
XS Rating Curve= 0 ,0
Exp/Cntr=0.3,0.1

Type RM Length L Ch R = 1 ,4505    ,429,429,429
BEGIN DESCRIPTION:
Caney Creek T 20 9.0
END DESCRIPTION:
XS GIS Cut Line= 3
      2784704.54      6795549.22        2783926.        6795361.
      2783519.12      6795372.13
#Sta/Elev= 30
  4193.7     465  4207.5  463.09  4249.4  462.23  4254.5  461.03  4268.5   460.8
  4317.2  457.71  4380.1  451.59  4458.6  442.15  4539.9  435.02  4631.2  428.86
  4706.6  426.27  4761.9  425.59  4819.8  422.88  4881.5  423.96  4912.4  422.84
  4997.2  423.19    5012  415.05  5012.8  414.55  5017.4  415.05  5024.7  415.59
  5034.7  423.75  5044.7  427.09  5084.7  432.65  5134.7  441.27  5164.7  442.61
  5173.6  441.83  5178.6  442.87  5214.7  442.37  5306.4  446.33  5401.7  452.03
#Mann= 7 ,-1 , 0
  4193.7     .12       0  4268.5      .1       0  4317.2     .12       0
  4539.9      .1       0    5012     .07       0  5017.4      .1       0
  5306.4     .05       0
Bank Sta=4997.2,5034.7
XS Rating Curve= 0 ,0
Exp/Cntr=0.3,0.1

Type RM Length L Ch R = 1 ,4076    ,464,464,464
BEGIN DESCRIPTION:
Caney Creek T 20 8.0
END DESCRIPTION:
XS GIS Cut Line= 3
       2784439.3       6794979.7        2784076.        6795011.
      2783512.37      6794982.39
#Sta/Elev= 30
  4635.4  445.76  4639.5  445.76  4678.9  441.73  4727.2  438.59  4739.1  437.35
  4819.4  432.05  4909.7   424.1  4938.3  422.87  4943.3  423.19  4969.9  420.59
  4987.3  414.95  4988.1  414.45    4992  414.45  4992.8  414.95  4997.5  416.45
  5002.5  416.45  5010.1  421.04  5020.1  420.39  5030.1  421.45  5070.1  422.97
  5101.9  422.74  5124.6  423.22  5200.3  425.27  5295.7  429.18  5300.7   428.7
  5330.5  429.86  5390.5  432.78  5430.6  436.04  5470.6   437.9  5564.4   439.7
#Mann= 5 ,-1 , 0
  4635.4     .12       0  4727.2      .1       0  4987.3     .07       0
  4992.8      .1       0  5124.6     .05       0
Bank Sta=4969.9,5010.1
XS Rating Curve= 0 ,0
Exp/Cntr=0.3,0.1

Type RM Length L Ch R = 1 ,3612    ,425,425,425
BEGIN DESCRIPTION:
Caney Creek T 20 7.0
END DESCRIPTION:
XS GIS Cut Line= 3
      2784375.96      6794710.99        2783976.        6794611.
      2783434.89      6794606.68
#Sta/Elev= 30
  4592.7  446.66  4610.7  444.07  4614.8  444.15  4651.9  439.74  4657.1  439.83
  4693.2  434.71  4780.8  427.94  4809.1  424.55  4816.9  420.45  4829.7  419.12
  4858.1  418.27  4891.6  419.08  4932.8  418.47  4940.5  411.16  4945.7     416
  4953.4  410.07  4960.9  409.89  4961.8  409.39  4966.5  409.89    4974   410.4
  4981.8   412.5  4986.9  409.92  4994.7  411.32  5002.4  418.93    5035  418.69
    5145  420.18    5265  423.94    5465  437.41    5525  442.96  5546.1  444.11
#Mann= 4 ,-1 , 0
  4592.7      .1       0  4614.8     .12       0  4960.9     .05       0
  4966.5     .05       0
Bank Sta=4932.8,5002.4
XS Rating Curve= 0 ,0
Exp/Cntr=0.3,0.1

Type RM Length L Ch R = 1 ,3187    ,424,424,424
BEGIN DESCRIPTION:
Caney Creek T 20 6.0
END DESCRIPTION:
XS GIS Cut Line= 3
      2784376.03        6794261.        2783976.        6794261.
      2783576.03      6794410.99
#Sta/Elev= 30
    4607  444.51    4618  443.24    4697  435.61    4737  430.88    4787  427.02
    4827  420.45    4847  418.87    4887  417.31    4967  417.85    4977  416.05
  4982.7  413.47  4994.2   407.4  4995.1   406.9    4999   406.9  4999.8   407.4
  5004.5  414.97  5009.7  414.97  5016.8  417.01  5022.2  413.67  5028.4  413.26
  5039.1   414.4  5047.1  416.27  5052.4  414.65  5060.4  416.52  5137.9  417.78
  5223.3   421.7    5339  433.55  5380.8  436.78  5424.4  441.31  5434.2  441.81
#Mann= 5 ,-1 , 0
    4607      .1       0    4618     .12       0  4982.7     .05       0
  4994.2     .05       0  4999.8     .05       0
Bank Sta=4967,5016.8
XS Rating Curve= 0 ,0
Exp/Cntr=0.3,0.1

Type RM Length L Ch R = 1 ,2763    ,452,452,452
BEGIN DESCRIPTION:
Caney Creek T 20 5.0
END DESCRIPTION:
XS GIS Cut Line= 3
      2784326.01      6794111.01        2784076.        6793961.
      2783476.22      6794131.46
#Sta/Elev= 30
  4708.7  438.25  4825.3  427.45    4907  420.04  4918.6  416.02  4934.2  415.71
    4942  407.24  4955.6  406.02  4976.9  408.02  4986.7  413.56  4992.5  406.85
  4997.3  411.66  5001.1  411.66  5010.7  411.18  5017.2  408.11  5022.4  410.22
  5031.5  405.77  5041.8  406.76  5048.3   405.6  5049.1   405.1  5053.9   405.6
  5062.6  408.31    5073  414.06  5104.7  415.56  5135.4  414.21    5264   416.3
  5348.2  419.02  5421.1  426.54    5455  432.42  5509.7  436.45  5623.8  439.59
#Mann= 7 ,-1 , 0
  4708.7     .12       0  4825.3      .1       0  5001.1     .12       0
  5048.3     .07       0  5053.9     .12       0  5104.7      .1       0
    5264     .05       0
Bank Sta=5022.4,5073
XS Rating Curve= 0 ,0
Exp/Cntr=0.3,0.1

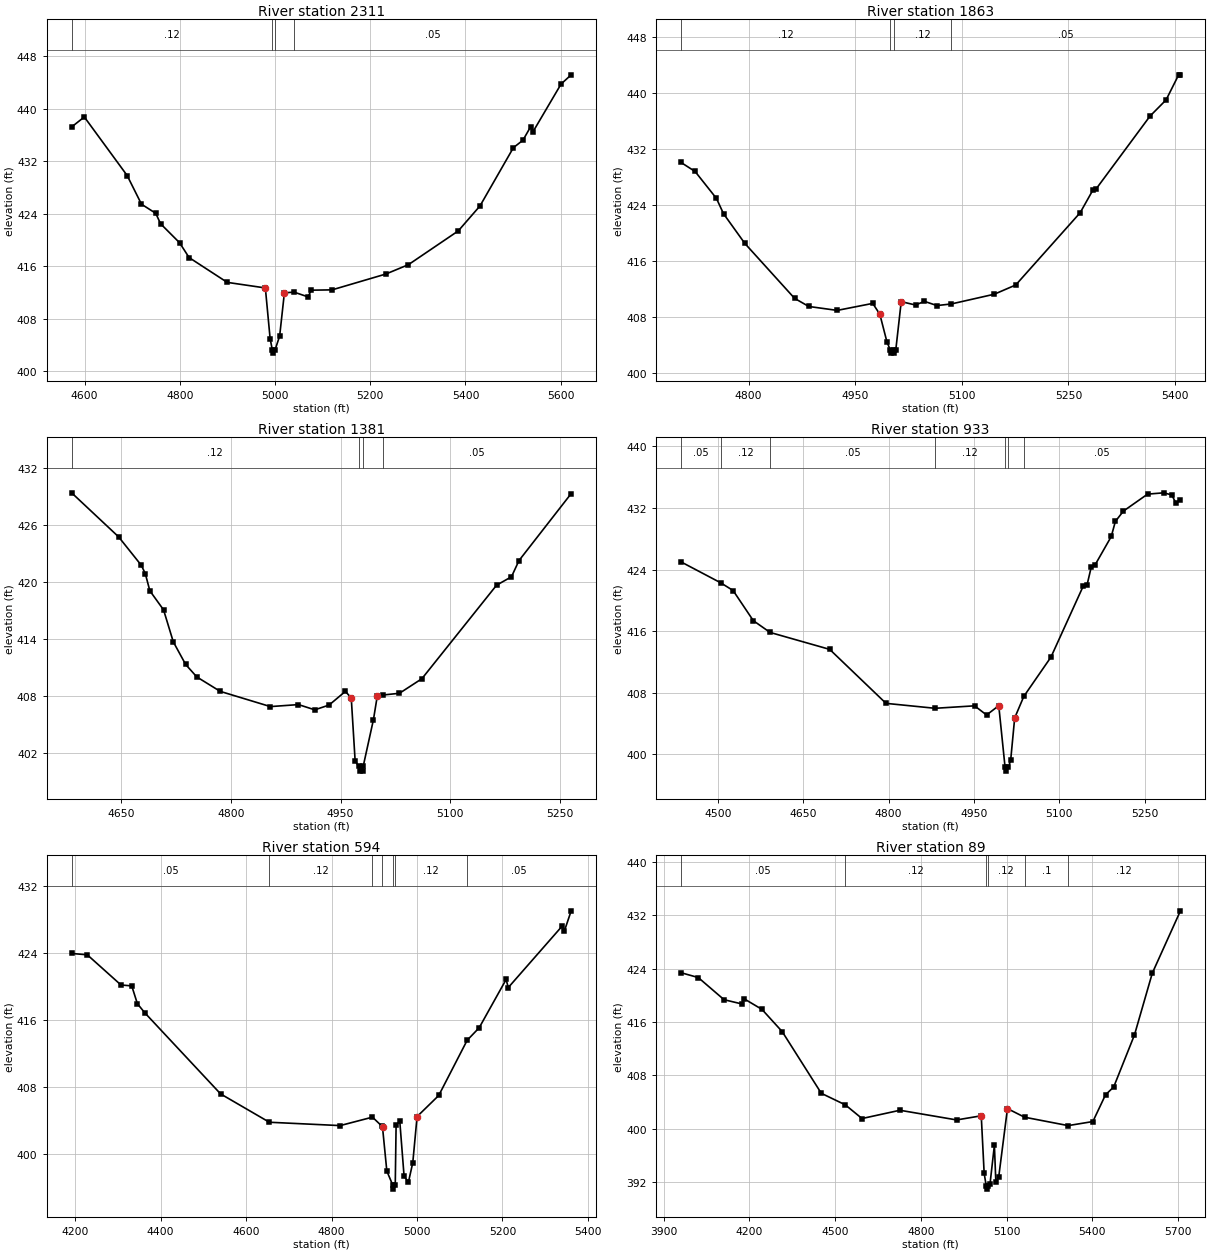
Type RM Length L Ch R = 1 ,2311    ,448,448,448
BEGIN DESCRIPTION:
Caney Creek T 20 4.0
END DESCRIPTION:
XS GIS Cut Line= 3
      2784452.56      6793577.22        2784026.        6793561.
      2783404.88      6793601.46
#Sta/Elev= 30
  4572.8  437.25  4599.4  438.77  4689.4  429.85  4719.5  425.48  4749.5  424.09
  4759.5  422.51  4799.5  419.61  4819.5  417.35  4899.6  413.57  4979.7  412.72
  4989.7  405.01  4994.3  403.29  4995.2  402.79  5000.1  403.29  5009.7  405.38
  5019.7  411.98  5040.1  412.08  5069.8  411.35  5075.7  412.38  5119.9  412.43
  5232.8  414.84  5280.3  416.27  5384.9  421.41  5430.6  425.22  5500.7  434.09
  5520.8  435.23    5537  437.29    5542  436.53  5600.9  443.79  5622.1  445.19
#Mann= 4 ,-1 , 0
  4572.8     .12       0  4994.3     .07       0  5000.1     .12       0
  5040.1     .05       0
Bank Sta=4979.7,5019.7
XS Rating Curve= 0 ,0
Exp/Cntr=0.3,0.1

Type RM Length L Ch R = 1 ,1863    ,482,482,482
BEGIN DESCRIPTION:
Caney Creek T 20 3.0
END DESCRIPTION:
XS GIS Cut Line= 3
      2784275.97        6793161.        2783976.        6793161.
      2783575.99        6793211.
#Sta/Elev= 30
  4704.6  430.09  4724.6  428.79  4754.6  424.95  4764.6  422.76  4794.6  418.52
  4864.6  410.68  4884.6  409.52  4924.6  408.96  4974.6  409.96  4984.6  408.41
  4994.6  404.46  4999.1  403.36  5000.1  402.86  5004.1  402.86    5005  403.36
  5007.1  403.36  5014.7  410.21  5034.8  409.73  5047.4  410.25    5065  409.65
  5085.2  409.88  5145.7  411.27  5175.9  412.59  5266.6  422.91  5284.2  426.09
  5289.3  426.34  5364.9   436.7  5387.5  439.01  5405.2  442.59  5407.7  442.59
#Mann= 4 ,-1 , 0
  4704.6     .12       0  4999.1     .07       0    5005     .12       0
  5085.2     .05       0
Bank Sta=4984.6,5014.7
XS Rating Curve= 0 ,0
Exp/Cntr=0.3,0.1

Type RM Length L Ch R = 1 ,1381    ,448,448,448
BEGIN DESCRIPTION:
Caney Creek T 20 2.0
END DESCRIPTION:
XS GIS Cut Line= 3
      2784375.99        6792861.        2783976.        6792711.
      2783726.04      6792661.01
#Sta/Elev= 30
  4582.8  429.37  4646.9  424.74    4678  421.74  4683.4  420.86  4689.6  419.06
  4708.3  417.06  4721.6  413.69  4738.5  411.31  4753.7     410  4785.7  408.48
  4854.2  406.88  4892.5  407.09  4914.8  406.54  4934.3  407.04  4956.6  408.48
  4964.6  407.79  4969.9  401.16    4975  400.59    4976  400.09    4980  400.09
  4980.9  400.59  4994.9  405.51  5000.2  408.02    5008   408.1  5030.4  408.28
    5061  409.81    5163  419.65  5183.4  420.54  5193.6  422.24  5264.9  429.29
#Mann= 4 ,-1 , 0
  4582.8     .12       0    4975     .07       0  4980.9     .12       0
    5008     .05       0
Bank Sta=4964.6,5000.2
XS Rating Curve= 0 ,0
Exp/Cntr=0.3,0.1

Type RM Length L Ch R = 1 ,933     ,339,339,339
BEGIN DESCRIPTION:
Mapping XS 78700458
END DESCRIPTION:
XS GIS Cut Line= 2
      2784649.34      6792787.51      2784015.81      6792179.34
#Sta/Elev= 30
  4434.9  425.01  4504.8  422.29  4526.7  421.28  4562.2  417.37  4591.7  415.84
  4696.5  413.64  4795.5  406.63  4881.7  405.99  4951.2  406.31  4972.3  405.12
  4993.7  406.33  5004.8  398.33  5005.8  397.83  5010.8  398.33  5014.7  399.29
  5021.7  404.74  5037.8  407.54  5085.5  412.64  5142.1  421.84    5149  422.04
  5156.3  424.33  5163.2  424.63  5191.5   428.3  5198.7  430.26  5212.9   431.6
  5255.3   433.8  5283.6  433.97  5297.8   433.7  5304.7   432.7  5313.1  433.01
#Mann= 7 ,-1 , 0
  4434.9     .05       0  4504.8     .12       0  4591.7     .05       0
  4881.7     .12       0  5004.8     .07       0  5010.8     .12       0
  5037.8     .05       0
Bank Sta=4993.7,5021.7
XS Rating Curve= 0 ,0
Exp/Cntr=0.3,0.1

Type RM Length L Ch R = 1 ,594     ,505,505,505
BEGIN DESCRIPTION:
Mapping XS 41163961
END DESCRIPTION:
XS GIS Cut Line= 3
      2784670.45      6792715.34      2784453.55      6792125.41
      2783919.74      6792042.87
#Sta/Elev= 30
    4192  423.93  4228.6  423.77  4307.4  420.16  4332.6  420.05  4345.8  417.92
    4363  416.84  4540.5  407.13  4654.6  403.74  4820.2  403.34  4895.8  404.35
  4918.5  403.24  4919.3  403.16  4929.4   397.9  4943.1  396.24  4944.1  395.74
  4949.1  396.24  4951.1  403.38  4959.7  403.86  4969.8  397.26    4980  396.59
  4990.1   398.9  5000.2  404.42  5050.8  406.94  5117.4  413.55  5145.4  415.04
  5208.5  420.82  5213.5  419.85  5339.7  427.21  5344.8  426.62  5360.7  429.03
#Mann= 7 ,-1 , 0
    4192     .05       0  4654.6     .12       0  4895.8     .05       0
  4918.5     .12       0  4943.1     .07       0  4949.1     .12       0
  5117.4     .05       0
Bank Sta=4919.3,5000.2
XS Rating Curve= 0 ,0
Exp/Cntr=0.3,0.1

Type RM Length L Ch R = 1 ,89      ,0,0,0
BEGIN DESCRIPTION:
Caney Creek T 20 1.0
END DESCRIPTION:
XS GIS Cut Line= 4
      2784798.52      6792738.08      2784473.54      6791746.31
      2784261.42      6791704.93      2783791.21      6791838.15
#Sta/Elev= 30
  3960.2  423.38    4021  422.65  4111.3  419.33  4174.9  418.68  4180.2   419.5
  4243.9  417.88  4314.9  414.54  4451.7   405.3  4535.7  403.57  4594.2  401.52
  4726.8  402.76  4925.3  401.31  5011.5  401.93  5021.7   393.3  5028.9  391.44
  5029.9  390.94  5034.9  391.44  5042.1  391.69  5057.5  397.51  5062.6  391.98
  5072.7  392.78  5103.2  403.01    5163  401.72  5315.7  400.46  5402.2  401.07
  5446.5  405.08  5475.1  406.25  5547.8  414.05  5610.2  423.31  5708.7  432.65
#Mann= 6 ,-1 , 0
  3960.2     .05       0  4535.7     .12       0  5028.9     .07       0
  5034.9     .12       0    5163      .1       0  5315.7     .12       0
Bank Sta=5011.5,5103.2
XS Rating Curve= 0 ,0
Exp/Cntr=0.3,0.1

Chan Stop Cuts=-1
Use User Specified Reach Order=0
Composite Channel Slope=5