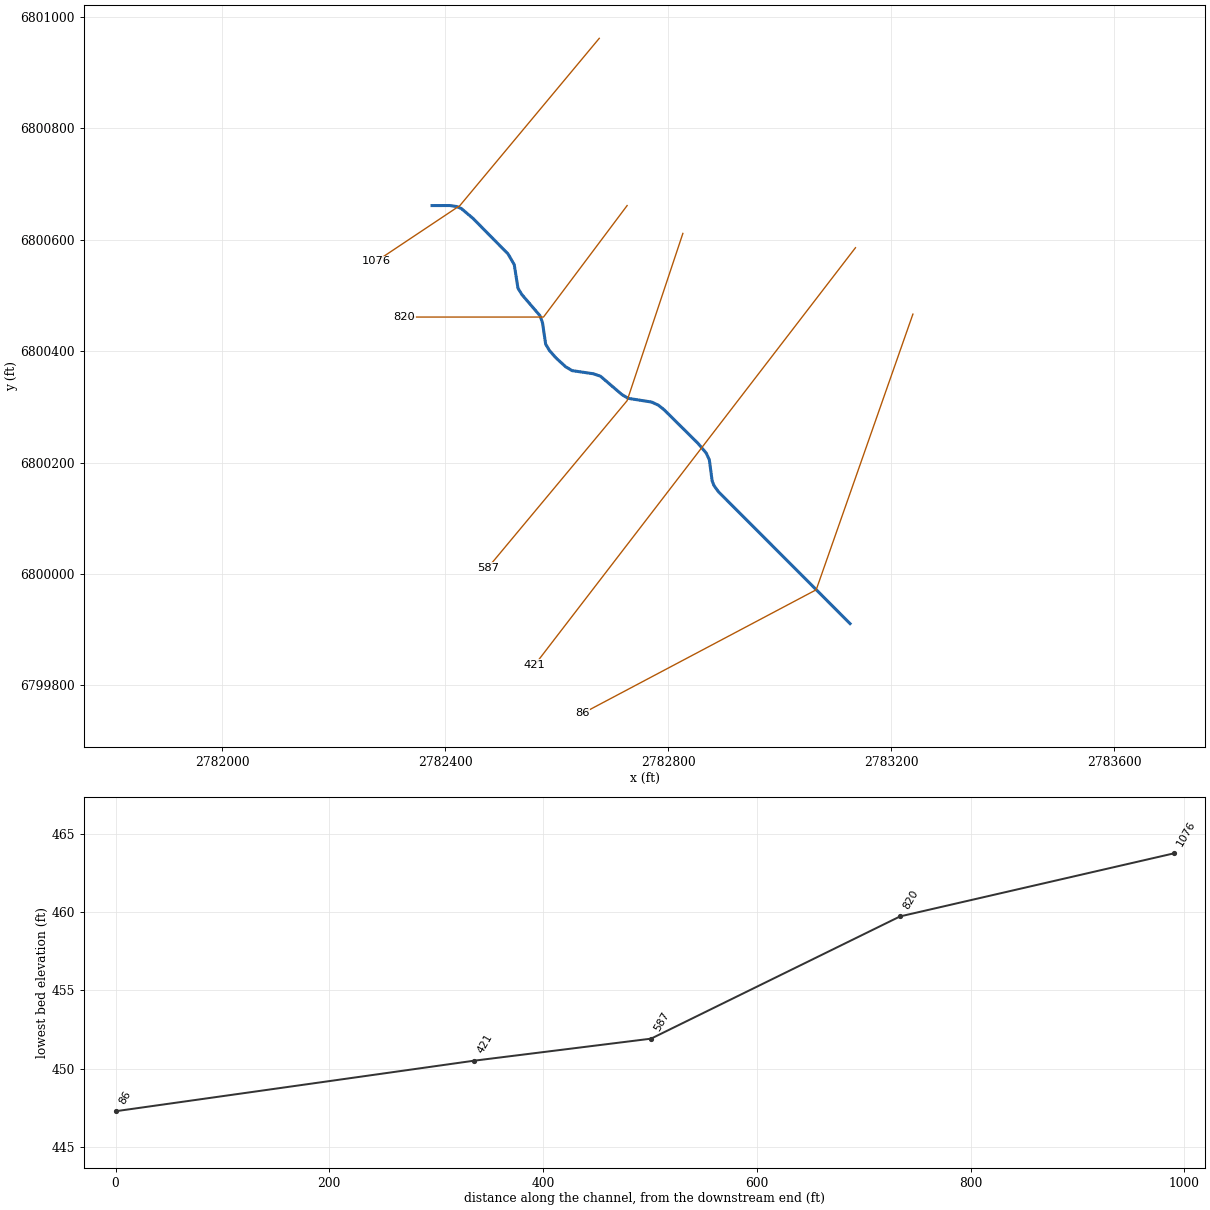
--- Caney Creek T 21.prj (project) ---

Proj Title=Caney Creek T 21 Base Level Engineering
Current Plan=p01
Default Exp/Contr=0.3,0.1
English Units
Geom File=g01
Flow File=f01
Plan File=p01
BEGIN DESCRIPTION:
Caney Creek T 21
END DESCRIPTION:

--- Caney Creek T 21.p01 (plan) ---

Plan Title=Multiple Run
Short Identifier=Multiple
Geom File=g01
Flow File=f01
Subcritical Flow
K Sum by GR= 0
Std Step Tol= 0.01
Critical Tol= 0.01
Num of Std Step Trials= 20
Max Error Tol= 0.3
Flow Tol Ratio= 0.001
Split Flow NTrial= 30
Split Flow Tol= 0.02
Split Flow Ratio= 0.02
Log Output Level= 0
Friction Slope Method= 1
Unsteady Friction Slope Method= 2
Unsteady Bridges Friction Slope Method= 1
Parabolic Critical Depth
Global Vel Dist=  1 , 1 , 1
Global Log Level= 0
CheckData=True
Encroach Param= -1, 0, 0, 0
BEGIN DESCRIPTION:
Multiple Run
END DESCRIPTION:

--- Caney Creek T 21.f01 (steady flow) ---

Flow Title=Multiple
Number of Profiles=7
Profile Names=10-year,25-year,50-year,1pct_min,100-year,1pct_plu,500-year
River Rch & RM= Caney Creek T 21,Reach-1,1076
     348     458     545     324     647    1292     912
Boundary for River Rch & Prof#=Caney Creek T 21,Reach-1,1
Up Type=0
Dn Type=3
Dn Slope=0.005
Boundary for River Rch & Prof#=Caney Creek T 21,Reach-1,2
Up Type=0
Dn Type=3
Dn Slope=0.005
Boundary for River Rch & Prof#=Caney Creek T 21,Reach-1,3
Up Type=0
Dn Type=3
Dn Slope=0.005
Boundary for River Rch & Prof#=Caney Creek T 21,Reach-1,4
Up Type=0
Dn Type=3
Dn Slope=0.005
Boundary for River Rch & Prof#=Caney Creek T 21,Reach-1,5
Up Type=0
Dn Type=3
Dn Slope=0.005
Boundary for River Rch & Prof#=Caney Creek T 21,Reach-1,6
Up Type=0
Dn Type=3
Dn Slope=0.005
Boundary for River Rch & Prof#=Caney Creek T 21,Reach-1,7
Up Type=0
Dn Type=3
Dn Slope=0.005

--- Caney Creek T 21.g01 (geometry) ---

Geom Title=Existing Conditions

River Reach=Caney Creek T 21,Reach-1
Reach XY= 30
      2782376.00      6800661.00      2782407.89      6800661.08
      2782419.87      6800659.33      2782428.54      6800655.70
      2782449.52      6800637.98      2782512.40      6800574.24
      2782523.51      6800554.97      2782530.19      6800512.73
      2782537.10      6800501.45      2782569.89      6800463.16
      2782574.28      6800450.25      2782579.86      6800412.42
      2782586.63      6800401.00      2782598.85      6800387.16
      2782616.00      6800371.63      2782627.42      6800364.86
      2782665.25      6800359.28      2782678.16      6800354.89
      2782716.45      6800322.10      2782727.74      6800315.19
      2782769.97      6800308.50      2782782.07      6800302.87
      2782792.71      6800294.37      2782853.01      6800234.51
      2782867.85      6800217.07      2782873.47      6800204.96
      2782878.54      6800167.05      2782881.86      6800158.71
      2782889.63      6800147.79      2783126.00      6799911.00

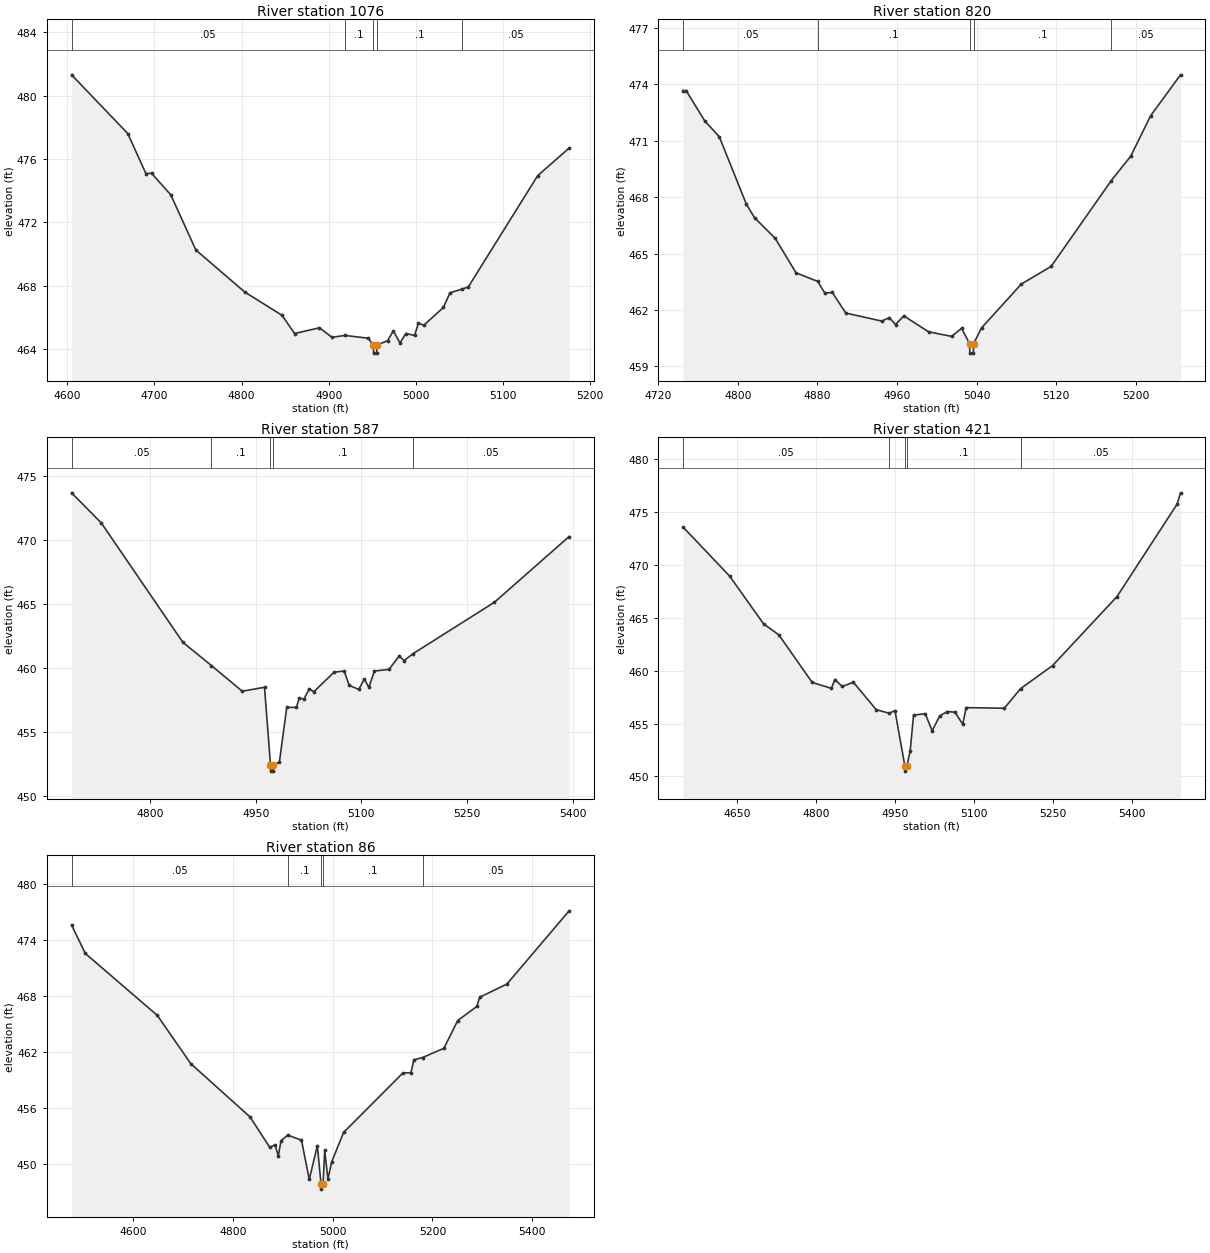
Type RM Length L Ch R = 1,1076,256,256,256
BEGIN DESCRIPTION:
Caney Creek T 21 4.0
END DESCRIPTION:
XS GIS Cut Line= 3
      2782676.02      6800961.02      2782426.00      6800661.00
      2782276.01      6800561.01
#Sta/Elev= 30
  4605.0  481.32  4669.5  477.61  4690.3  475.08  4696.8  475.10  4718.9  473.73
  4747.6  470.25  4803.5  467.60  4846.5  466.12  4860.8  464.97  4889.4  465.33
  4903.8  464.73  4918.7  464.85  4945.4  464.67  4951.2  464.23  4951.5  463.73
  4955.0  463.73  4955.2  464.23  4967.6  464.52  4974.1  465.13  4981.9  464.37
  4988.4  464.97  4998.5  464.85  5003.0  465.63  5009.1  465.49  5031.6  466.62
  5039.1  467.54  5053.2  467.78  5060.1  467.91  5139.8  474.95  5175.8  476.69
#Mann=5,-1,0
  4605.0    0.05       0  4918.7     0.1       0  4951.2    0.07       0
  4955.2     0.1       0  5053.2    0.05       0
Bank Sta=4951.2,4955.2
Exp/Cntr=0.3,0.1

Type RM Length L Ch R = 1,820,233,233,233
BEGIN DESCRIPTION:
Caney Creek T 21 3.0
END DESCRIPTION:
XS GIS Cut Line= 3
      2782726.02      6800661.03      2782576.00      6800461.00
      2782326.04      6800461.00
#Sta/Elev= 30
  4744.9  473.66  4748.1  473.66  4766.8  472.05  4781.4  471.21  4808.5  467.64
  4816.8  466.91  4837.6  465.81  4858.5  463.98  4880.3  463.52  4887.6  462.89
  4894.9  462.94  4908.5  461.84  4944.9  461.41  4952.2  461.60  4958.5  461.23
  4966.8  461.69  4991.8  460.84  5014.9  460.60  5024.9  461.03  5032.9  460.21
  5033.2  459.71  5036.7  459.71  5036.9  460.21  5044.9  461.05  5084.9  463.38
  5114.9  464.32  5175.3  468.88  5194.9  470.18  5214.9  472.33  5244.9  474.50
#Mann=5,-1,0
  4744.9    0.05       0  4880.3     0.1       0  5032.9    0.07       0
  5036.9     0.1       0  5175.3    0.05       0
Bank Sta=5032.9,5036.9
Exp/Cntr=0.3,0.1

Type RM Length L Ch R = 1,587,166,166,166
BEGIN DESCRIPTION:
Caney Creek T 21 2.0
END DESCRIPTION:
XS GIS Cut Line= 3
      2782826.01      6800611.04      2782726.00      6800311.00
      2782475.99      6800010.98
#Sta/Elev= 30
  4688.3  473.68  4730.5  471.33  4846.5  461.98  4887.0  460.17  4930.8  458.16
  4962.4  458.47  4970.9  452.41  4971.2  451.91  4974.7  451.91  4974.9  452.41
  4983.5  452.60  4994.0  456.90  5007.8  456.89  5011.7  457.64  5018.2  457.53
  5026.0  458.34  5032.6  458.13  5061.2  459.65  5075.5  459.74  5082.7  458.62
  5096.3  458.30  5104.1  459.11  5110.7  458.46  5118.5  459.74  5139.3  459.87
  5153.6  460.91  5160.8  460.56  5173.5  461.10  5289.0  465.12  5395.1  470.26
#Mann=5,-1,0
  4688.3    0.05       0  4887.0     0.1       0  4970.9    0.07       0
  4974.9     0.1       0  5173.5    0.05       0
Bank Sta=4970.9,4974.9
Exp/Cntr=0.3,0.1

Type RM Length L Ch R = 1,421,335,335,335
BEGIN DESCRIPTION:
Mapping XS 761857a1
END DESCRIPTION:
XS GIS Cut Line= 2
      2783135.66      6800585.41      2782560.28      6799836.91
#Sta/Elev= 30
  4547.8  473.60  4636.4  468.95  4700.8  464.43  4729.8  463.39  4793.0  458.89
  4829.5  458.33  4835.8  459.16  4850.3  458.51  4871.1  458.91  4914.6  456.31
  4939.2  455.98  4950.0  456.23  4968.8  451.00  4969.0  450.50  4972.8  451.00
  4979.0  452.44  4985.3  455.79  5007.4  455.94  5020.6  454.32  5035.1  455.73
  5049.6  456.14  5064.1  456.07  5078.7  454.93  5085.0  456.51  5157.5  456.45
  5188.3  458.30  5249.0  460.48  5371.4  467.02  5485.6  475.78  5491.9  476.83
#Mann=5,-1,0
  4547.8    0.05       0  4939.2     0.1       0  4968.8    0.07       0
  4972.8     0.1       0  5188.3    0.05       0
Bank Sta=4968.8,4972.8
Exp/Cntr=0.3,0.1

Type RM Length L Ch R = 1,86,0,0,0
BEGIN DESCRIPTION:
Caney Creek T 21 1.0
END DESCRIPTION:
XS GIS Cut Line= 3
      2783238.72      6800466.30      2783065.25      6799971.74
      2782646.20      6799749.99
#Sta/Elev= 30
  4475.9  475.64  4503.6  472.58  4648.0  465.93  4715.3  460.74  4834.0  455.03
  4873.6  451.76  4884.2  452.04  4890.7  450.84  4896.0  452.46  4909.5  453.08
  4937.2  452.53  4952.8  448.33  4969.0  451.94  4976.5  447.78  4976.7  447.28
  4980.5  447.78  4983.8  451.44  4990.2  448.34  4997.7  450.21  5021.8  453.37
  5140.6  459.75  5156.9  459.78  5162.6  461.17  5180.1  461.41  5222.9  462.40
  5250.6  465.38  5288.9  466.89  5294.6  467.88  5349.3  469.30  5474.1  477.16
#Mann=5,-1,0
  4475.9    0.05       0  4909.5     0.1       0  4976.5    0.07       0
  4980.5     0.1       0  5180.1    0.05       0
Bank Sta=4976.5,4980.5
Exp/Cntr=0.3,0.1

Chan Stop Cuts=-1