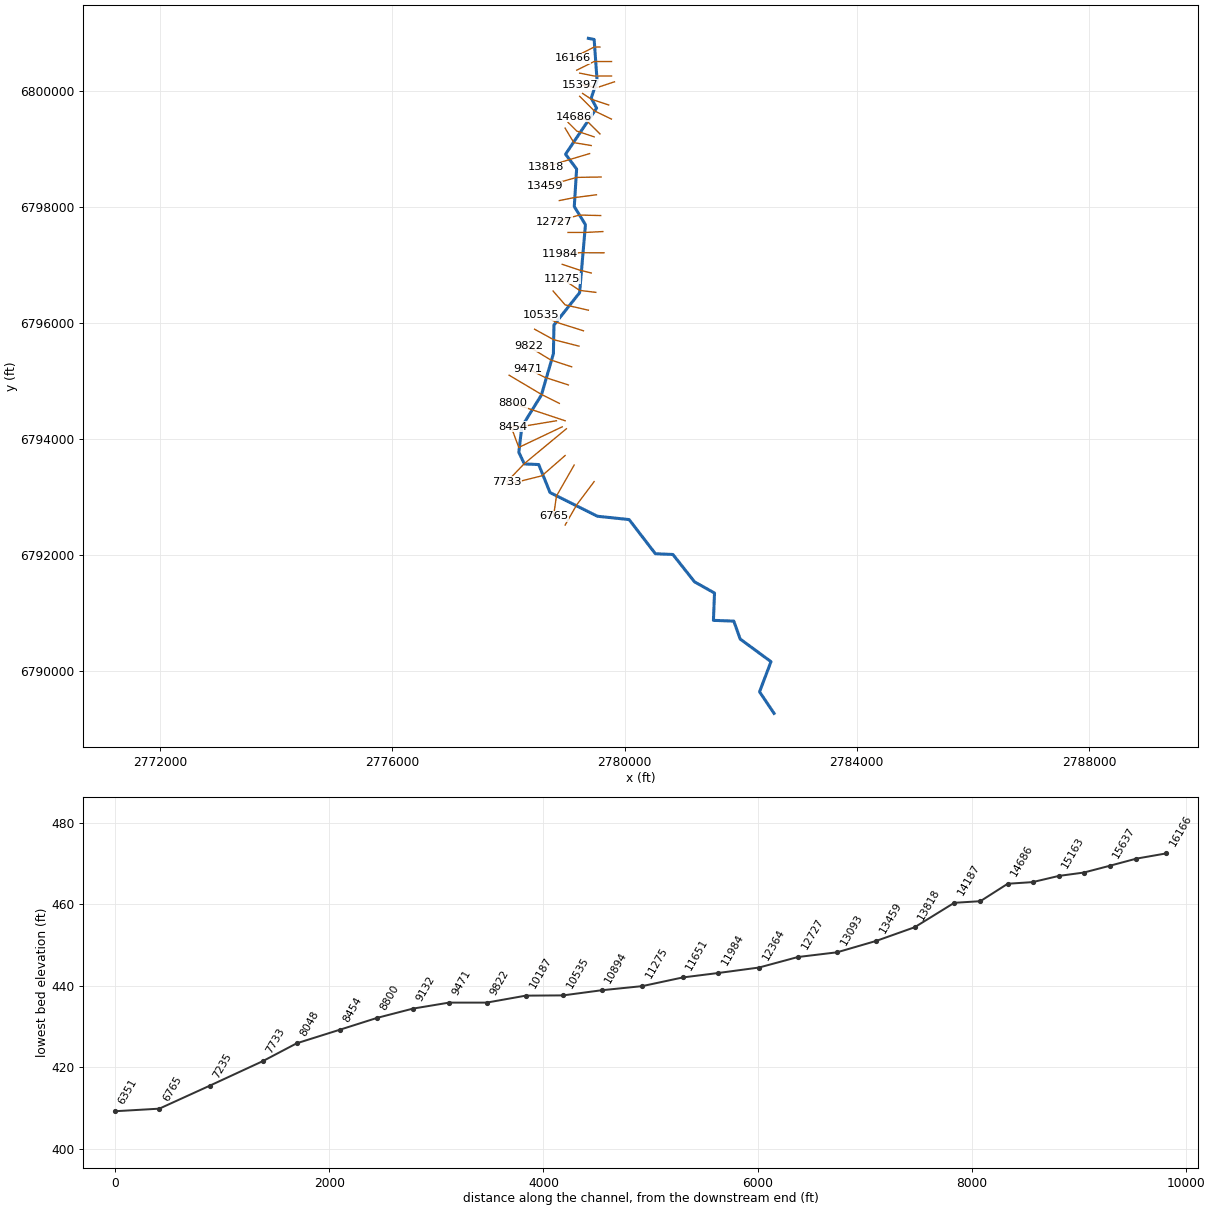
--- Caney Creek T 22.prj (project) ---

Proj Title=Caney Creek T 22 Base Level Engineering
Current Plan=p01
Default Exp/Contr=0.3,0.1
English Units
Geom File=g01
Flow File=f01
Plan File=p01
Y Axis Title=Elevation
X Axis Title(PF)=Main Channel Distance
X Axis Title(XS)=Station
BEGIN DESCRIPTION:
Caney Creek T 22
END DESCRIPTION:
DSS Export Rating Curves= 0
DSS Export Rating Curve Sorted= 0
DSS Export Volume Flow Curves= 0
DXF OffsetX= 0
DXF OffsetY= 0
DXF ScaleX= 1
DXF ScaleY= 10

--- Caney Creek T 22.p01 (plan) ---

Plan Title=Multiple Run
Short Identifier=Multiple
Geom File=g01
Flow File=f01
Subcritical Flow
K Sum by GR= 0
Std Step Tol= 0.01
Critical Tol= 0.01
Num of Std Step Trials= 20
Max Error Tol= 0.3
Flow Tol Ratio= 0.001
Split Flow NTrial= 30
Split Flow Tol= 0.02
Split Flow Ratio= 0.02
Log Output Level= 0
Friction Slope Method= 1
Unsteady Friction Slope Method= 2
Unsteady Bridges Friction Slope Method= 1
Parabolic Critical Depth
Global Vel Dist=  1 , 1 , 1
Global Log Level= 0
CheckData=True
Encroach Param= -1, 0, 0, 0
BEGIN DESCRIPTION:
Multiple Run
END DESCRIPTION:

--- Caney Creek T 22.f01 (steady flow) ---

Flow Title=Multiple
Number of Profiles=7
Profile Names=10-year,25-year,50-year,1pct_min,100-year,1pct_plu,500-year
River Rch & RM= Caney Creek T 22,Reach-1,16166
     335     438     519     307     612    1221     851
River Rch & RM= Caney Creek T 22,Reach-1,13818
     557     749     906     545    1087    2169    1568
River Rch & RM= Caney Creek T 22,Reach-1,7733
    1129    1581    1965    1211    2417    4822    3668
River Rch & RM= Caney Creek T 22,Reach-1,4508
    1401    1981    2477    1536    3064    6113    4701
Boundary for River Rch & Prof#=Caney Creek T 22,Reach-1,1
Up Type=0
Dn Type=3
Dn Slope=0.005
Boundary for River Rch & Prof#=Caney Creek T 22,Reach-1,2
Up Type=0
Dn Type=3
Dn Slope=0.005
Boundary for River Rch & Prof#=Caney Creek T 22,Reach-1,3
Up Type=0
Dn Type=3
Dn Slope=0.005
Boundary for River Rch & Prof#=Caney Creek T 22,Reach-1,4
Up Type=0
Dn Type=3
Dn Slope=0.005
Boundary for River Rch & Prof#=Caney Creek T 22,Reach-1,5
Up Type=0
Dn Type=3
Dn Slope=0.005
Boundary for River Rch & Prof#=Caney Creek T 22,Reach-1,6
Up Type=0
Dn Type=3
Dn Slope=0.005
Boundary for River Rch & Prof#=Caney Creek T 22,Reach-1,7
Up Type=0
Dn Type=3
Dn Slope=0.005

--- Caney Creek T 22.g01 (geometry) ---

Geom Title=Existing Conditions
Program Version=4.10

River Reach=Caney Creek T 22,Reach-1
Reach XY= 30
        2779376.        6800911.      2779476.08      6800891.08
      2779526.28      6800183.76       2779425.7      6799881.18
      2779518.33      6799707.34      2778983.28      6798911.09
      2779173.83      6798655.56      2779133.83       6798007.6
      2779325.99      6797695.64      2779225.25      6796520.77
      2778783.79      6795964.42      2778773.62      6795466.53
       2778566.7      6794754.33      2778229.83      6794209.42
      2778178.14      6793766.51      2778273.48      6793565.85
      2778520.42      6793555.43        2778716.      6793071.63
      2779531.45      6792663.17      2780078.73      6792605.65
      2780531.08      6792016.03      2780832.52      6792003.32
      2781205.91      6791530.79      2781549.86      6791337.94
      2781531.18      6790866.38      2781882.19      6790853.25
      2781992.27      6790543.86      2782522.92      6790153.38
      2782325.78      6789633.65        2782576.        6789261.

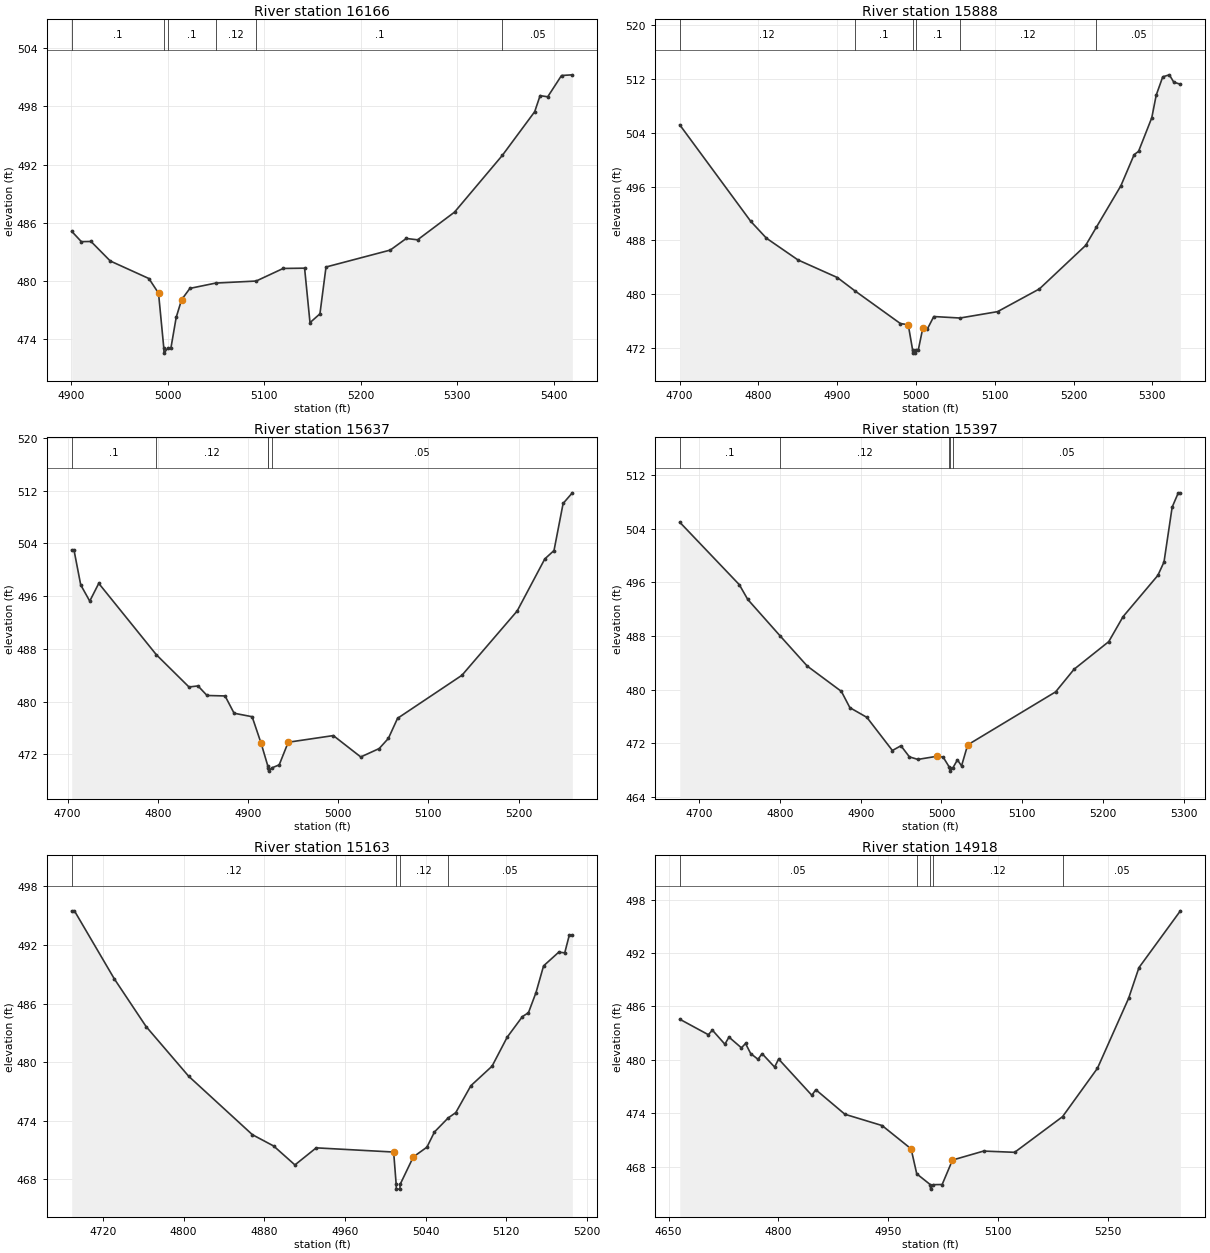
Type RM Length L Ch R = 1 ,16166   ,278,278,278
BEGIN DESCRIPTION:
Caney Creek T 22 41.0
END DESCRIPTION:
XS GIS Cut Line= 3
      2779575.98        6800761.        2779476.        6800761.
      2779103.27      6800569.77
#Sta/Elev= 30
  4900.4   485.1  4910.4  484.03  4920.4  484.05  4940.4  482.03  4980.4  480.22
  4990.4  478.71  4995.9  473.01  4996.1  472.51  4999.9  473.01  5003.2  473.01
  5008.7   476.2  5014.3  478.03  5022.9   479.2  5049.7  479.75  5091.6  479.96
  5119.6  481.26  5141.8  481.29  5147.4  475.66  5157.7  476.57    5164  481.41
  5230.6  483.16  5247.2  484.36  5258.9  484.22  5297.2  487.08  5346.8  492.95
  5380.3  497.46  5385.9  499.12  5393.8     499  5408.1   501.2  5419.3  501.27
#Mann= 6 ,-1 , 0
  4900.4      .1       0  4995.9     .07       0  4999.9      .1       0
  5049.7     .12       0  5091.6      .1       0  5346.8     .05       0
Bank Sta=4990.4,5014.3
XS Rating Curve= 0 ,0
Exp/Cntr=0.3,0.1

Type RM Length L Ch R = 1 ,15888   ,251,251,251
BEGIN DESCRIPTION:
Caney Creek T 22 40.0
END DESCRIPTION:
XS GIS Cut Line= 3
        2779776.        6800511.        2779476.        6800511.
      2779176.01        6800361.
#Sta/Elev= 30
  4700.1  505.17  4790.1  490.84  4810.1  488.32  4850.1  485.09  4900.1  482.47
  4922.2  480.51  4980.1  475.63  4990.1  475.45  4995.6  471.73  4995.8  471.23
  4999.3  471.23  4999.6  471.73  5002.9  471.73  5008.5  474.91  5014.1  474.76
  5022.5  476.67  5055.8  476.45  5103.5   477.4  5156.6  480.78  5215.3  487.25
  5228.9  489.96    5260  496.12  5276.8  500.74  5282.4  501.23  5299.2  506.23
  5304.8  509.58  5313.1  512.31  5321.5  512.61  5327.1  511.52  5335.5  511.21
#Mann= 6 ,-1 , 0
  4700.1     .12       0  4922.2      .1       0  4995.6     .07       0
  4999.6      .1       0  5055.8     .12       0  5228.9     .05       0
Bank Sta=4990.1,5008.5
XS Rating Curve= 0 ,0
Exp/Cntr=0.3,0.1

Type RM Length L Ch R = 1 ,15637   ,240,240,240
BEGIN DESCRIPTION:
Caney Creek T 22 39.0
END DESCRIPTION:
XS GIS Cut Line= 3
        2779776.        6800261.        2779476.        6800261.
      2779226.05      6800310.99
#Sta/Elev= 30
  4704.6  503.02  4707.1  503.02  4714.6   497.7  4724.6  495.24  4734.6  497.93
  4798.5   487.1  4834.6  482.22  4844.6  482.38  4854.6  480.93  4874.6  480.86
  4884.6  478.24  4904.6  477.71  4914.6  473.66  4922.1  470.19  4922.6  469.96
  4922.8  469.46  4926.6  469.96  4934.6  470.41  4944.6  473.84  4994.6  474.85
    5025  471.61  5045.4  472.88  5055.6  474.42  5065.8  477.47  5137.2     484
  5198.4  493.75    5229  501.64  5239.2  502.91  5249.3  510.05  5259.5  511.66
#Mann= 5 ,-1 , 0
  4704.6      .1       0  4798.5     .12       0  4922.1     .05       0
  4922.6     .05       0  4926.6     .05       0
Bank Sta=4914.6,4944.6
XS Rating Curve= 0 ,0
Exp/Cntr=0.3,0.1

Type RM Length L Ch R = 1 ,15397   ,234,234,234
BEGIN DESCRIPTION:
Caney Creek T 22 38.0
END DESCRIPTION:
XS GIS Cut Line= 3
      2779825.99        6800161.        2779526.        6800061.
      2779225.95      6800111.01
#Sta/Elev= 30
  4675.7  504.99  4749.5  495.66    4760  493.45  4800.3  487.98  4833.8  483.49
    4876  479.72  4886.5  477.29  4907.6  475.84  4939.2  470.89  4949.8   471.6
  4960.3  469.94  4970.8  469.56  4994.5  470.03  5002.1  469.91  5009.5  468.45
  5010.2  468.31  5010.4  467.81  5014.2  468.31  5019.8  469.49  5024.9  468.59
  5032.5  471.73  5141.5  479.65  5164.3  483.02  5207.3  487.15  5225.1  490.89
  5268.2  497.05  5275.8  499.05  5285.9  507.24  5293.5  509.38  5296.1  509.38
#Mann= 5 ,-1 , 0
  4675.7      .1       0  4800.3     .12       0  5009.5     .05       0
  5010.2     .07       0  5014.2     .05       0
Bank Sta=4994.5,5032.5
XS Rating Curve= 0 ,0
Exp/Cntr=0.3,0.1

Type RM Length L Ch R = 1 ,15163   ,245,245,245
BEGIN DESCRIPTION:
Caney Creek T 22 37.0
END DESCRIPTION:
XS GIS Cut Line= 3
      2779726.03      6799760.99        2779426.        6799861.
      2779276.03      6799960.98
#Sta/Elev= 30
  4689.1   495.5  4691.8   495.5  4731.3  488.54  4762.9  483.64  4805.1  478.55
  4868.3  472.56  4889.4   471.4  4910.5  469.46  4931.6  471.21  5008.4  470.78
  5010.9  467.48  5011.1  466.98  5014.6  466.98  5014.9  467.48  5027.9  470.28
  5041.4  471.28  5048.9  472.84  5062.4  474.27    5070  474.82    5085  477.58
    5106  479.58    5121  482.55  5136.1  484.66  5142.1  485.06  5149.6  487.13
  5157.1  489.86  5172.1  491.26  5178.1   491.2  5182.6  493.01  5185.6  493.01
#Mann= 4 ,-1 , 0
  4689.1     .12       0  5010.9     .07       0  5014.9     .12       0
  5062.4     .05       0
Bank Sta=5008.4,5027.9
XS Rating Curve= 0 ,0
Exp/Cntr=0.3,0.1

Type RM Length L Ch R = 1 ,14918   ,232,232,232
BEGIN DESCRIPTION:
Caney Creek T 22 36.0
END DESCRIPTION:
XS GIS Cut Line= 3
      2779773.28      6799517.68        2779476.        6799661.
      2779225.98      6799911.02
#Sta/Elev= 30
  4665.3  484.57  4704.3  482.83  4709.9  483.34  4726.9  481.76  4732.5  482.56
  4749.5  481.35  4755.1  481.84  4762.2   480.7  4772.2  480.06  4777.7   480.7
  4794.8  479.19  4800.3  480.09  4845.6  476.02  4851.1  476.64  4890.8  473.88
  4941.6  472.61  4981.2  469.99  4988.9  467.18  5007.5  465.96  5007.7  465.46
  5011.5  465.96  5023.6  465.98  5037.7  468.73  5080.2  469.74  5122.6   469.6
    5188  473.61  5235.7  479.06  5278.2  486.92  5292.3  490.37  5348.9  496.76
#Mann= 5 ,-1 , 0
  4665.3     .05       0  4988.9     .12       0  5007.5     .07       0
  5011.5     .12       0    5188     .05       0
Bank Sta=4981.2,5037.7
XS Rating Curve= 0 ,0
Exp/Cntr=0.3,0.1

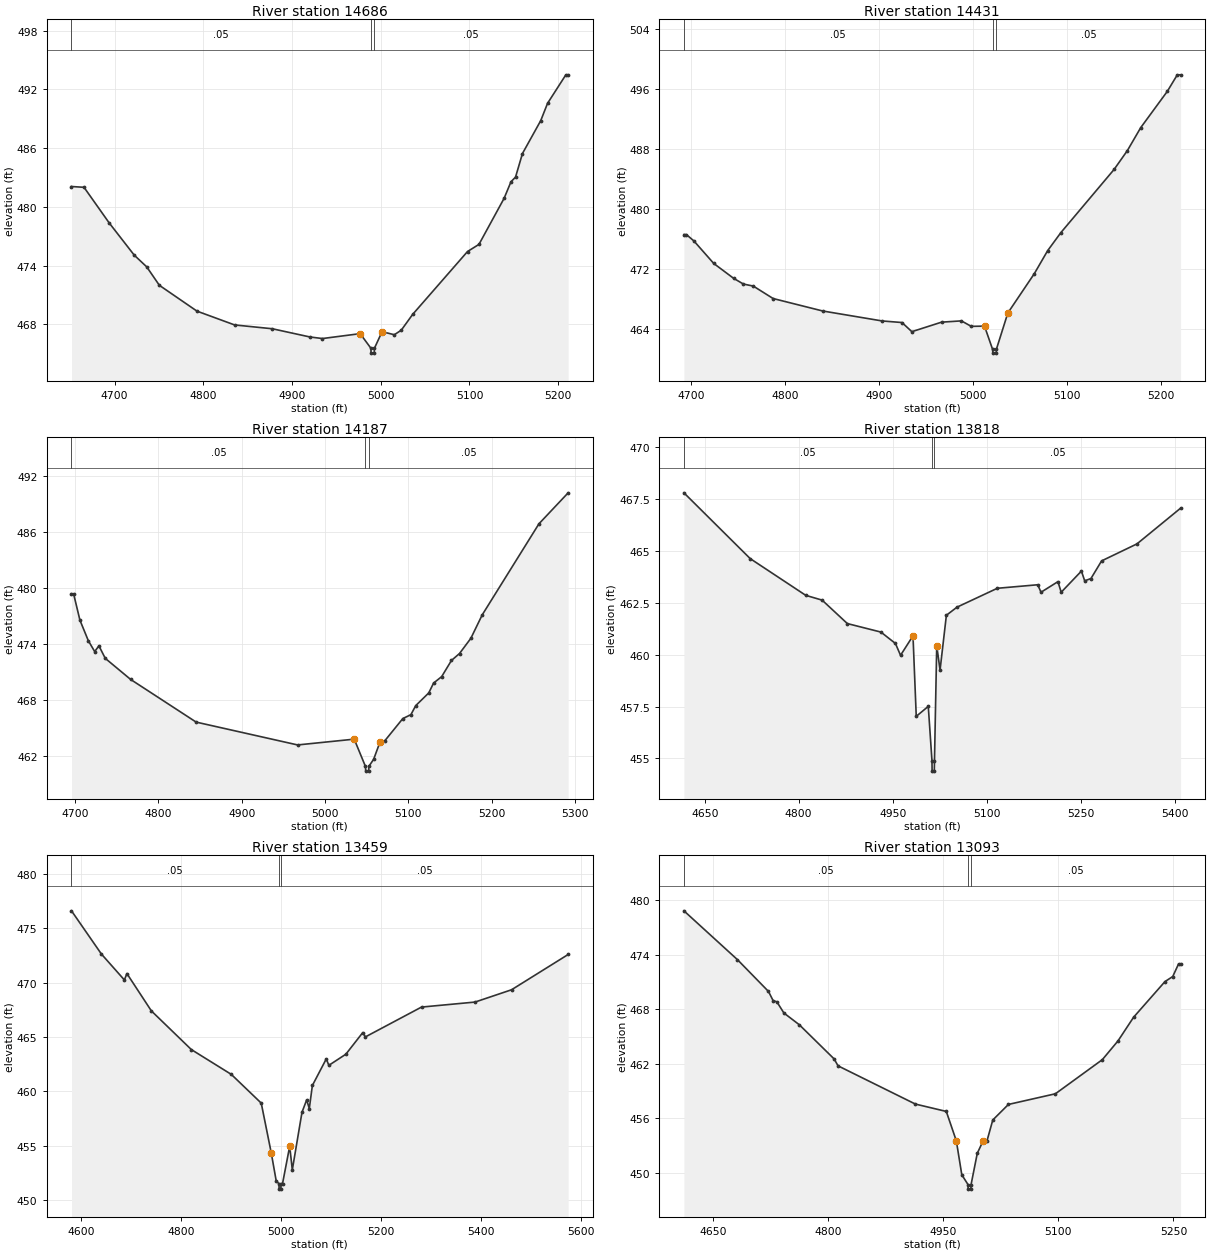
Type RM Length L Ch R = 1 ,14686   ,255,255,255
BEGIN DESCRIPTION:
Caney Creek T 22 35.0
END DESCRIPTION:
XS GIS Cut Line= 3
      2779575.99      6799261.01        2779326.        6799511.
      2779125.99        6799561.
#Sta/Elev= 30
  4651.5  482.08  4665.6     482  4693.9  478.37  4722.2  475.07  4736.3  473.87
  4750.5  471.99  4792.9  469.35  4835.3  467.94  4877.8  467.55  4920.2  466.71
  4934.3  466.55  4976.8  467.05  4988.9  465.56  4989.1  465.06  4992.6  465.06
  4992.9  465.56  5001.5  467.25  5015.3  466.94  5023.1   467.4    5036  469.02
  5097.8  475.44  5110.7  476.17    5139  480.87  5146.8  482.57  5151.9  483.04
  5159.7  485.45  5180.3  488.81    5188  490.58  5208.6  493.49  5211.2  493.49
#Mann= 3 ,-1 , 0
  4651.5     .05       0  4988.9     .04       0  4992.9     .05       0
Bank Sta=4976.8,5001.5
XS Rating Curve= 0 ,0
Exp/Cntr=0.3,0.1

Type RM Length L Ch R = 1 ,14431   ,244,244,244
BEGIN DESCRIPTION:
Caney Creek T 22 34.0
END DESCRIPTION:
XS GIS Cut Line= 3
      2779476.05      6799210.98        2779176.        6799311.
      2779026.01      6799460.99
#Sta/Elev= 30
  4692.2  476.58  4694.9  476.58  4702.8  475.74  4723.9  472.74    4745  470.76
  4755.5  469.99    4766  469.72  4787.1  468.06  4839.8   466.4  4903.1  465.07
  4924.2  464.86  4934.7  463.64  4966.3  464.91  4987.4  465.08  4997.9  464.35
    5012  464.38  5020.6  461.28  5020.9  460.78  5024.4  460.78  5024.6  461.28
  5036.8  466.13    5065  471.38  5079.2  474.45  5093.3  476.86  5149.9  485.28
    5164  487.79  5178.2  490.85  5206.5  495.69  5217.1  497.89  5220.6  497.89
#Mann= 3 ,-1 , 0
  4692.2     .05       0  5020.6     .04       0  5024.6     .05       0
Bank Sta=5012,5036.8
XS Rating Curve= 0 ,0
Exp/Cntr=0.3,0.1

Type RM Length L Ch R = 1 ,14187   ,369,369,369
BEGIN DESCRIPTION:
Caney Creek T 22 33.0
END DESCRIPTION:
XS GIS Cut Line= 3
      2779425.97      6799061.01        2779126.        6799111.
      2778975.98      6799361.04
#Sta/Elev= 30
  4695.9  479.41  4698.4  479.41    4706  476.58  4716.1  474.37  4723.7  473.21
  4728.8  473.82  4736.4  472.48  4766.8  470.22  4845.4  465.64  4967.1  463.19
    5035  463.81  5048.5  460.88  5048.8  460.38  5052.3  460.38  5052.5  460.88
  5058.3  461.65  5066.1  463.54  5071.9  463.66  5093.3  466.02    5103  466.44
  5108.8  467.41  5124.4  468.77  5130.2  469.83  5139.9  470.52  5151.6  472.25
  5161.3     473  5174.9  474.63  5188.5  477.14  5256.6  486.92  5291.6  490.24
#Mann= 3 ,-1 , 0
  4695.9     .05       0  5048.5     .04       0  5052.5     .05       0
Bank Sta=5035,5066.1
XS Rating Curve= 0 ,0
Exp/Cntr=0.3,0.1

Type RM Length L Ch R = 1 ,13818   ,359,359,359
BEGIN DESCRIPTION:
Caney Creek T 22 32.0
END DESCRIPTION:
XS GIS Cut Line= 3
      2779397.42      6798921.46        2779026.        6798811.
      2778639.65      6798688.18
#Sta/Elev= 30
  4616.8   467.8  4722.6  464.63  4811.3  462.86  4837.4  462.63  4877.7   461.5
  4931.3  461.09  4954.5  460.54  4962.6  459.97  4982.5  460.91  4987.7  457.03
  5006.9  457.51  5012.8  454.89    5013  454.39  5016.5  454.39  5016.8  454.89
  5020.4  460.43  5025.7  459.26  5035.8   461.9  5052.7  462.29  5117.1   463.2
  5181.6  463.37  5186.9  463.01  5213.9  463.52  5219.1  463.01  5251.4  464.03
  5256.6  463.56  5266.6  463.67  5283.6  464.52  5340.1  465.34  5409.7  467.06
#Mann= 3 ,-1 , 0
  4616.8     .05       0  5012.8     .04       0  5016.8     .05       0
Bank Sta=4982.5,5020.4
XS Rating Curve= 0 ,0
Exp/Cntr=0.3,0.1

Type RM Length L Ch R = 1 ,13459   ,366,366,366
BEGIN DESCRIPTION:
Caney Creek T 22 31.0
END DESCRIPTION:
XS GIS Cut Line= 3
      2779595.87      6798517.71        2779176.        6798511.
      2778623.14      6798354.87
#Sta/Elev= 30
  4580.1  476.59    4640  472.62    4686  470.24    4691  470.83    4740   467.4
    4820  463.85    4900  461.57    4960  458.93    4980  454.37    4990  451.78
  4995.5  451.53  4995.8  451.03  4999.3  451.03  4999.5  451.53  5002.6  451.53
    5017  454.97  5022.2   452.8  5041.6  458.09    5051  459.23  5056.2  458.43
  5062.4  460.55  5090.2  462.99  5095.4   462.4  5129.4  463.42  5163.3  465.41
  5168.5  465.01  5280.9  467.75    5388  468.21  5461.2  469.34  5574.5  472.58
#Mann= 3 ,-1 , 0
  4580.1     .05       0  4995.5     .04       0  4999.5     .05       0
Bank Sta=4980,5017
XS Rating Curve= 0 ,0
Exp/Cntr=0.3,0.1

Type RM Length L Ch R = 1 ,13093   ,366,366,366
BEGIN DESCRIPTION:
Caney Creek T 22 30.0
END DESCRIPTION:
XS GIS Cut Line= 3
      2779515.26      6798210.89        2779126.        6798161.
        2778876.        6798111.
#Sta/Elev= 30
  4611.9  478.82  4681.7  473.45  4722.1  469.96  4728.1  468.96  4733.1  468.81
  4742.2  467.59  4762.4  466.29  4807.7  462.54  4812.8  461.78  4913.6  457.58
  4953.9  456.77    4967  453.53  4974.1  449.81  4982.2  448.73  4982.4  448.23
  4985.9  448.23  4986.2  448.73  4994.3  452.17  5001.8  453.52  5006.9  453.52
  5014.5  455.83  5034.9  457.54  5096.1  458.71  5157.3  462.46  5177.7  464.52
  5198.1  467.13  5238.9  471.04  5249.1   471.6  5256.7  472.99  5259.3  472.99
#Mann= 3 ,-1 , 0
  4611.9     .05       0  4982.2     .04       0  4986.2     .05       0
Bank Sta=4967,5001.8
XS Rating Curve= 0 ,0
Exp/Cntr=0.3,0.1

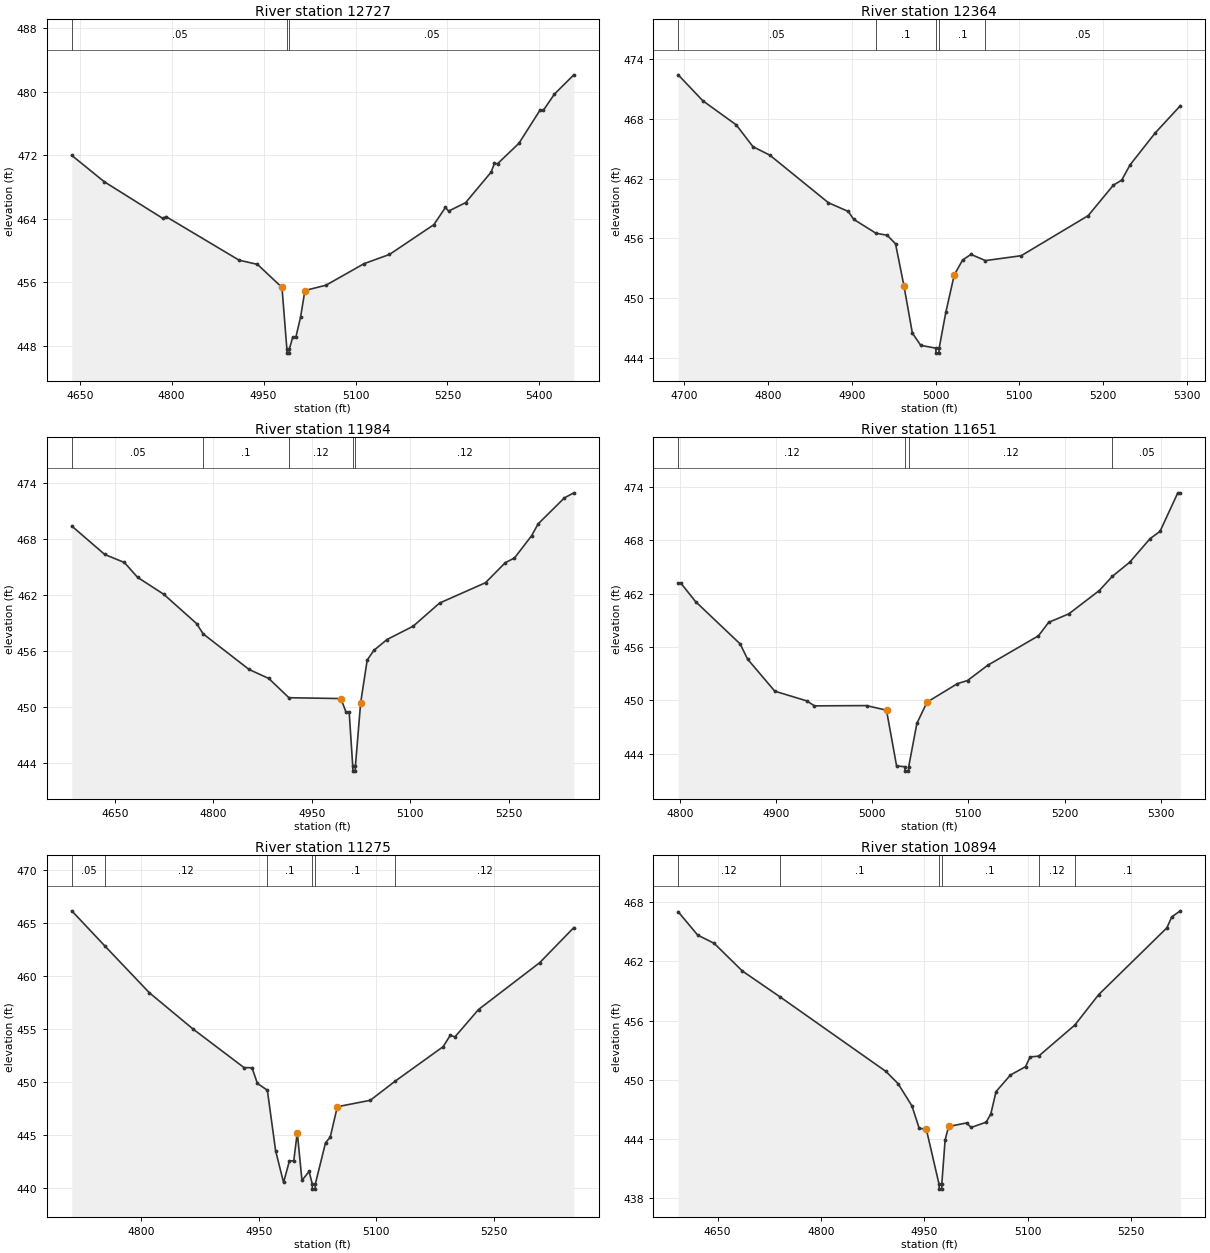
Type RM Length L Ch R = 1 ,12727   ,363,363,363
BEGIN DESCRIPTION:
Caney Creek T 22 29.0
END DESCRIPTION:
XS GIS Cut Line= 3
      2779588.91       6797852.5        2779226.        6797861.
       2778785.5      6797742.38
#Sta/Elev= 30
    4637  471.96  4689.9  468.65  4785.7  464.02  4790.7  464.26    4910  458.77
    4940  458.24    4980  455.34    4988  447.57  4988.3  447.07  4991.8  447.07
    4992  447.57  4997.5  449.07  5002.6  449.07  5010.4  451.63  5017.4  454.95
  5051.8  455.62  5113.9  458.33  5155.4  459.49  5227.8  463.24  5246.7  465.41
  5251.9  464.95  5279.6  466.01  5321.1  469.84  5326.6  470.95  5331.7  470.91
  5366.5  473.47  5401.3  477.69  5406.4  477.63  5424.6  479.68  5456.2   482.1
#Mann= 3 ,-1 , 0
    4637     .05       0    4988     .04       0    4992     .05       0
Bank Sta=4980,5017.4
XS Rating Curve= 0 ,0
Exp/Cntr=0.3,0.1

Type RM Length L Ch R = 1 ,12364   ,380,380,380
BEGIN DESCRIPTION:
Caney Creek T 22 28.0
END DESCRIPTION:
XS GIS Cut Line= 3
       2779625.2      6797576.31        2779326.        6797561.
      2779025.99        6797561.
#Sta/Elev= 30
  4692.6   472.4  4721.8  469.81  4761.9  467.38  4781.9  465.19  4801.9  464.35
    4872  459.57  4895.7   458.7  4902.1  457.91  4928.6  456.52  4942.1  456.31
  4952.1  455.46  4962.2  451.22  4972.2   446.5  4982.2  445.27  5000.2  444.99
  5000.4  444.49  5003.9  444.49  5004.2  444.99  5012.2   448.6  5022.2  452.32
  5032.2  453.83  5042.2  454.39  5059.5  453.77  5102.2  454.26  5182.2  458.28
  5212.2  461.33  5222.2  461.84  5232.2  463.37  5262.2  466.57  5292.2   469.3
#Mann= 5 ,-1 , 0
  4692.6     .05       0  4928.6      .1       0  5000.2     .07       0
  5004.2      .1       0  5059.5     .05       0
Bank Sta=4962.2,5022.2
XS Rating Curve= 0 ,0
Exp/Cntr=0.3,0.1

Type RM Length L Ch R = 1 ,11984   ,333,333,333
BEGIN DESCRIPTION:
Caney Creek T 22 27.0
END DESCRIPTION:
XS GIS Cut Line= 3
      2779646.15      6797209.68        2779226.        6797211.
      2778881.66      6797190.59
#Sta/Elev= 30
  4584.1  469.36  4634.3  466.32  4664.3  465.46  4684.3  463.88  4724.3  462.06
  4774.3  458.93  4784.3  457.83  4854.3  454.02  4884.3  453.06    4915     451
  4994.3  450.91  5001.8  449.49  5006.8  449.49  5012.3  443.65  5012.5  443.15
    5016  443.15  5016.3  443.65  5024.3  450.45  5034.3  455.03  5044.3  456.05
  5064.4  457.22  5104.4  458.65  5144.5  461.12  5214.6   463.3  5244.7  465.44
  5258.7  465.94  5284.7  468.31  5294.8  469.59  5334.8  472.37  5349.2  472.91
#Mann= 5 ,-1 , 0
  4584.1     .05       0  4784.3      .1       0    4915     .12       0
  5012.3     .07       0  5016.3     .12       0
Bank Sta=4994.3,5024.3
XS Rating Curve= 0 ,0
Exp/Cntr=0.3,0.1

Type RM Length L Ch R = 1 ,11651   ,376,376,376
BEGIN DESCRIPTION:
Caney Creek T 22 26.0
END DESCRIPTION:
XS GIS Cut Line= 3
      2779426.01        6796861.        2779226.        6796911.
      2778925.99        6797011.
#Sta/Elev= 30
  4798.1  463.21  4800.7  463.21  4816.1  461.12  4862.5  456.36  4870.3  454.64
  4898.6  451.04  4932.1  449.94  4939.8  449.39    4994  449.42  5014.8   448.9
  5025.3  442.63  5033.9  442.55  5034.1  442.05  5037.6  442.05  5037.9  442.55
  5046.4  447.42    5057  449.81  5088.6  451.89  5099.1  452.24  5120.2  453.96
  5172.9  457.27  5183.5  458.78  5204.5  459.74  5236.2  462.36  5249.8  463.96
  5267.8  465.54  5288.9  468.18  5299.4  469.02  5317.9  473.35  5320.5  473.35
#Mann= 4 ,-1 , 0
  4798.1     .12       0  5033.9     .07       0  5037.9     .12       0
  5249.8     .05       0
Bank Sta=5014.8,5057
XS Rating Curve= 0 ,0
Exp/Cntr=0.3,0.1

Type RM Length L Ch R = 1 ,11275   ,381,381,381
BEGIN DESCRIPTION:
Caney Creek T 22 25.0
END DESCRIPTION:
XS GIS Cut Line= 3
      2779504.39      6796527.25        2779226.        6796561.
      2778925.99      6796761.01
#Sta/Elev= 30
  4711.2  466.18  4753.9  462.83  4810.3  458.45  4866.4  455.01  4931.2  451.39
  4941.3  451.38  4948.2   449.9  4960.9  449.26  4971.5  443.53  4981.6  440.56
  4989.1   442.6  4994.6   442.6  4999.1  445.26  5005.1  440.75  5014.2   441.6
  5018.2  440.43  5018.4  439.93  5021.9  439.93  5022.2  440.43  5035.2  444.31
  5041.2  444.83  5050.2   447.7  5092.3  448.31  5124.2  450.12  5185.4  453.37
  5194.4  454.44  5200.4  454.29  5230.5  456.87  5308.6  461.29  5352.2   464.6
#Mann= 6 ,-1 , 0
  4711.2     .05       0  4753.9     .12       0  4960.9      .1       0
  5018.2     .07       0  5022.2      .1       0  5124.2     .12       0
Bank Sta=4999.1,5050.2
XS Rating Curve= 0 ,0
Exp/Cntr=0.3,0.1

Type RM Length L Ch R = 1 ,10894   ,359,359,359
BEGIN DESCRIPTION:
Caney Creek T 22 24.0
END DESCRIPTION:
XS GIS Cut Line= 3
      2779376.66      6796219.27        2778976.        6796311.
      2778768.16      6796550.46
#Sta/Elev= 30
  4592.9  467.02  4621.1  464.66  4644.9  463.83  4685.9  461.02  4740.9  458.38
  4894.1  450.84  4911.6  449.61  4931.8  447.35  4942.4  445.06  4952.6  445.01
  4971.1  439.41  4971.4  438.91  4974.9  438.91  4975.1  439.41  4979.9  443.88
    4985  445.26    5011  445.62  5017.7  445.16  5039.5   445.7  5046.2  446.53
  5053.8   448.8  5074.7  450.48  5096.5  451.32  5103.2  452.31  5115.5  452.39
    5168  455.54  5202.5  458.62  5301.6   465.4  5308.5   466.5    5321  467.12
#Mann= 6 ,-1 , 0
  4592.9     .12       0  4740.9      .1       0  4971.1     .07       0
  4975.1      .1       0  5115.5     .12       0    5168      .1       0
Bank Sta=4952.6,4985
XS Rating Curve= 0 ,0
Exp/Cntr=0.3,0.1

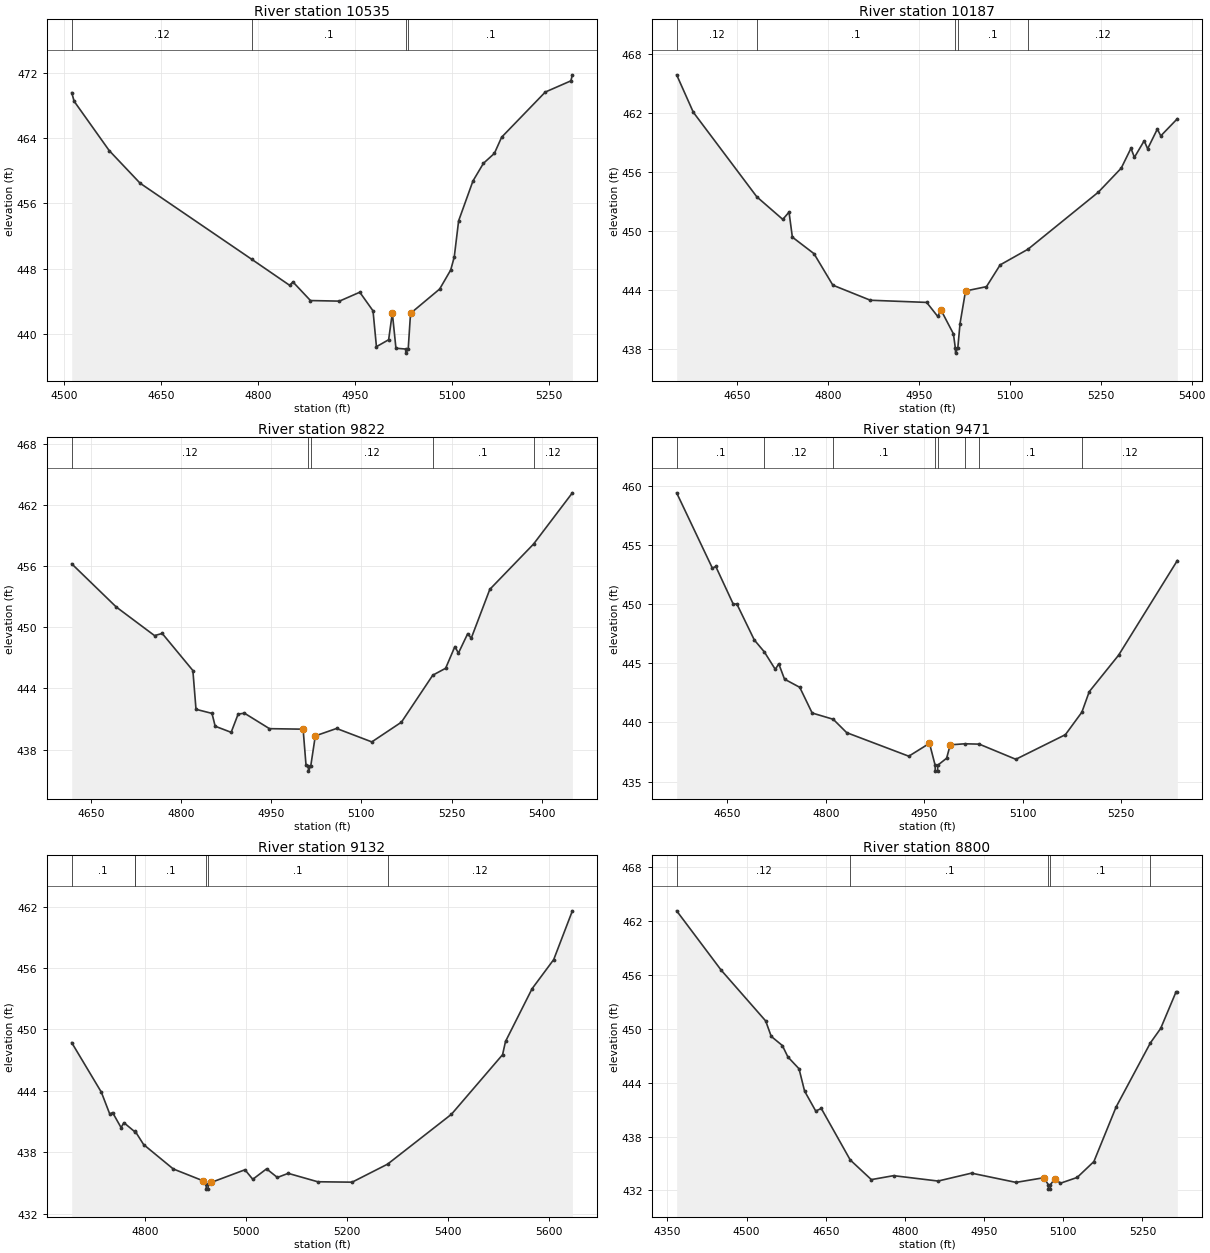
Type RM Length L Ch R = 1 ,10535   ,348,348,348
BEGIN DESCRIPTION:
Caney Creek T 22 23.0
END DESCRIPTION:
XS GIS Cut Line= 3
      2779291.42      6795863.83        2778826.        6796011.
       2778567.4      6796136.33
#Sta/Elev= 30
  4511.5  469.56  4515.3   468.5  4569.6  462.46  4617.5  458.46  4790.4  449.14
    4849  445.96  4854.2  446.37  4881.3  444.09  4926.2  444.02  4957.7  445.11
  4978.2  442.83  4983.5  438.44  5002.4  439.29  5008.1  442.57  5013.7  438.25
  5028.7  438.15    5029  437.65  5032.7  438.15  5036.3  442.52  5081.4   445.5
  5098.5  447.83    5104  449.41  5110.8  453.86    5133  458.74  5149.2   460.9
  5166.2  462.12  5177.4   464.1    5245  469.63  5284.6     471    5287  471.74
#Mann= 4 ,-1 , 0
  4511.5     .12       0  4790.4      .1       0  5028.7     .07       0
  5032.7      .1       0
Bank Sta=5008.1,5036.3
XS Rating Curve= 0 ,0
Exp/Cntr=0.3,0.1

Type RM Length L Ch R = 1 ,10187   ,365,365,365
BEGIN DESCRIPTION:
Caney Creek T 22 22.0
END DESCRIPTION:
XS GIS Cut Line= 3
      2779215.66      6795598.69        2778776.        6795711.
      2778450.09      6795890.81
#Sta/Elev= 30
  4550.4  465.85  4577.9  462.05  4682.7  453.46  4725.5  451.17  4735.8  451.91
  4741.3  449.37    4777  447.69  4808.1  444.49    4870  442.96  4962.9  442.74
  4981.2  441.31  4986.3  441.99    5007  439.55  5010.2  438.09  5010.5  437.59
  5014.2  438.09  5017.9  440.59    5027   443.9  5061.5  444.34  5084.1  446.55
    5130  448.14    5246  453.93  5283.8  456.37  5299.9  458.39  5305.6  457.47
  5321.7  459.15  5327.4  458.34  5343.4  460.34  5349.1  459.65  5376.4  461.39
#Mann= 5 ,-1 , 0
  4550.4     .12       0  4682.7      .1       0  5010.2     .07       0
  5014.2      .1       0    5130     .12       0
Bank Sta=4986.3,5027
XS Rating Curve= 0 ,0
Exp/Cntr=0.3,0.1

Type RM Length L Ch R = 1 ,9822    ,351,351,351
BEGIN DESCRIPTION:
Caney Creek T 22 21.0
END DESCRIPTION:
XS GIS Cut Line= 3
      2779089.19      6795242.24        2778726.        6795361.
      2778341.26      6795596.11
#Sta/Elev= 30
    4618  456.24  4692.1     452  4755.8  449.19  4768.6   449.4  4819.6  445.76
  4824.8  441.95  4851.4  441.55  4856.7  440.29  4883.3  439.69  4894.9  441.48
  4905.4  441.57    4947  440.05    5003     440  5007.8  436.49  5011.7  436.38
  5011.9  435.88  5015.7  436.38  5023.3  439.34  5058.7  440.07  5117.3  438.75
  5166.6  440.69  5218.7   445.3  5240.1  445.98  5255.5  448.11  5261.4  447.47
  5276.9  449.39  5282.7  448.93  5313.6  453.73  5386.4  458.18    5451  463.21
#Mann= 5 ,-1 , 0
    4618     .12       0  5011.7     .07       0  5015.7     .12       0
  5218.7      .1       0  5386.4     .12       0
Bank Sta=5003,5023.3
XS Rating Curve= 0 ,0
Exp/Cntr=0.3,0.1

Type RM Length L Ch R = 1 ,9471    ,339,339,339
BEGIN DESCRIPTION:
Caney Creek T 22 20.0
END DESCRIPTION:
XS GIS Cut Line= 3
      2779032.31      6794929.08        2778626.        6795061.
        2778326.        6795211.
#Sta/Elev= 30
  4572.8  459.39  4627.2  453.03  4632.4  453.17  4659.1  449.98  4664.4  450.01
  4691.1  446.96  4706.4  445.95  4723.1  444.47  4728.3  444.95  4737.1  443.65
  4760.3  442.96  4779.2  440.79  4811.3  440.26  4831.8  439.13  4926.4  437.14
  4957.9  438.23  4966.5  436.38  4966.7  435.88  4970.2  435.88  4970.5  436.38
    4984  436.97  4989.5   438.1  5011.7  438.19  5033.7  438.16  5089.4  436.88
  5164.9  438.96    5190  440.86  5201.2  442.59    5246  445.68  5335.4  453.67
#Mann= 8 ,-1 , 0
  4572.8      .1       0  4706.4     .12       0  4811.3      .1       0
  4966.5     .07       0  4970.5      .1       0  5011.7     .12       0
  5033.7      .1       0    5190     .12       0
Bank Sta=4957.9,4989.5
XS Rating Curve= 0 ,0
Exp/Cntr=0.3,0.1

Type RM Length L Ch R = 1 ,9132    ,332,332,332
BEGIN DESCRIPTION:
Caney Creek T 22 19.0
END DESCRIPTION:
XS GIS Cut Line= 3
      2778875.98      6794611.01        2778576.        6794761.
      2778011.79      6795096.47
#Sta/Elev= 30
  4654.1  448.71  4712.8  443.87  4729.5  441.73  4735.1  441.88  4751.9  440.41
  4757.5  440.89  4778.9  440.01  4779.9  440.05  4796.6  438.75  4855.3  436.37
    4914  435.22  4920.4   434.9  4920.7   434.4  4924.2   434.4  4924.4   434.9
  4930.8  435.06  4997.3  436.29  5012.8  435.36  5040.1  436.38  5061.5  435.54
    5083  435.94  5141.4  435.12  5209.6  435.08  5279.8  436.84  5406.3  441.71
  5507.6  447.53  5513.4  448.82    5566  453.97  5608.9  456.82  5645.9  461.58
#Mann= 6 ,-1 , 0
  4654.1      .1       0  4778.9     .12       0  4779.9      .1       0
  4920.4     .07       0  4924.4      .1       0  5279.8     .12       0
Bank Sta=4914,4930.8
XS Rating Curve= 0 ,0
Exp/Cntr=0.3,0.1

Type RM Length L Ch R = 1 ,8800    ,346,346,346
BEGIN DESCRIPTION:
Caney Creek T 22 18.0
END DESCRIPTION:
XS GIS Cut Line= 3
        2778976.        6794311.        2778376.        6794511.
      2778075.98      6794611.01
#Sta/Elev= 30
  4367.5  463.13  4451.8  456.53  4536.2  450.87  4546.7  449.15  4567.8  448.13
  4578.3  446.86  4599.4  445.54  4609.9  443.06    4631  440.84  4641.6  441.12
  4696.4  435.39  4736.4   433.2  4778.6  433.64  4862.9  433.04  4926.2  433.92
  5010.5  432.89  5063.2  433.41  5071.7  432.64    5072  432.14  5075.5  432.14
  5075.7  432.64  5084.3   433.3  5094.8   432.8  5126.4  433.44  5158.1  435.21
  5200.2  441.29  5265.2  448.43  5284.6  450.03  5313.5  454.07  5316.2  454.07
#Mann= 5 ,-1 , 0
  4367.5     .12       0  4696.4      .1       0  5071.7     .07       0
  5075.7      .1       0  5265.2     .12       0
Bank Sta=5063.2,5084.3
XS Rating Curve= 0 ,0
Exp/Cntr=0.3,0.1

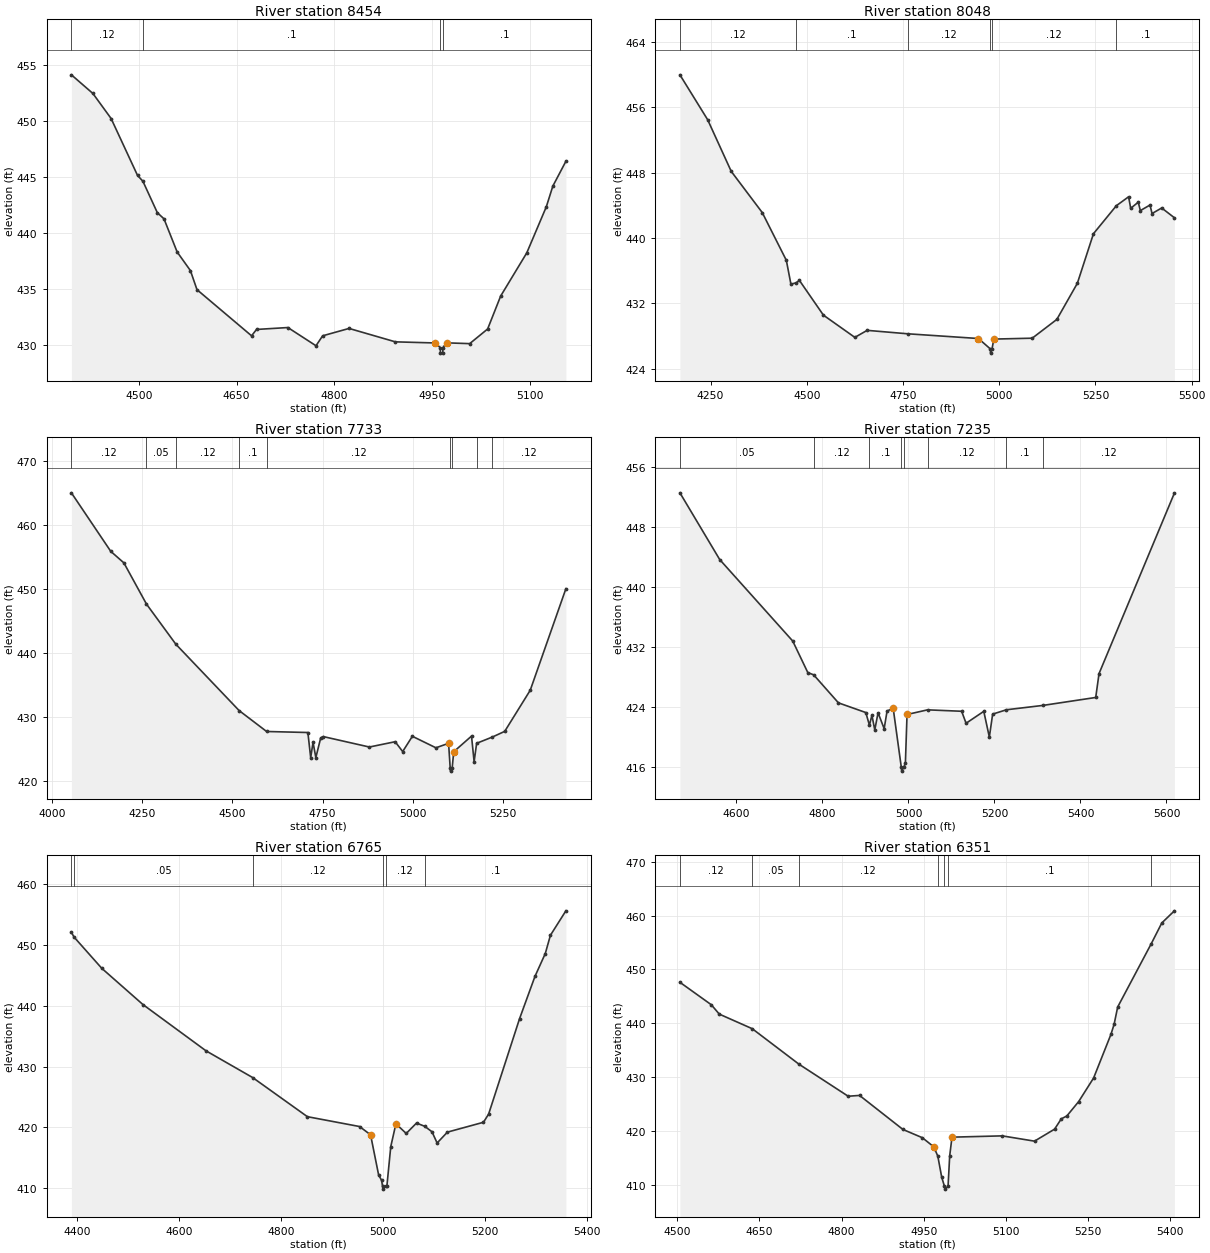
Type RM Length L Ch R = 1 ,8454    ,406,406,406
BEGIN DESCRIPTION:
Caney Creek T 22 17.0
END DESCRIPTION:
XS GIS Cut Line= 3
      2778826.02        6794311.        2778226.        6794211.
        2778076.        6794211.
#Sta/Elev= 30
  4396.8  454.16  4429.8  452.49  4457.7  450.25  4498.2  445.16  4506.5  444.63
  4528.6  441.82  4538.8  441.27    4559   438.3  4579.3  436.64  4589.4  434.93
  4673.1   430.8  4680.7  431.37  4728.8  431.54  4771.9  429.91  4782.1   430.8
  4822.6  431.46  4893.6  430.26  4954.4  430.16  4962.5  429.75  4962.8  429.25
  4966.3  429.25  4966.5  429.75  4972.2  430.17  5007.6   430.1  5035.1  431.41
  5055.1  434.36  5095.1  438.22  5125.1  442.35  5135.1   444.2  5155.1  446.42
#Mann= 4 ,-1 , 0
  4396.8     .12       0  4506.5      .1       0  4962.5     .07       0
  4966.5      .1       0
Bank Sta=4954.4,4972.2
XS Rating Curve= 0 ,0
Exp/Cntr=0.3,0.1

Type RM Length L Ch R = 1 ,8048    ,315,315,315
BEGIN DESCRIPTION:
Caney Creek T 22 16.0
END DESCRIPTION:
XS GIS Cut Line= 3
      2778926.48      6794206.76      2778177.27      6793850.52
      2778019.86      6794277.64
#Sta/Elev= 30
  4170.4  459.98  4242.5  454.48  4303.8  448.15  4384.3  443.11  4446.9  437.26
  4458.8  434.34  4472.2   434.5    4481  434.79  4543.3  430.54  4624.9  427.82
  4656.9  428.68  4761.8  428.26  4946.1  427.68  4977.3  426.39  4977.5  425.89
  4981.3  426.39    4986  427.61  5085.8  427.72  5149.7  430.02    5203  434.44
  5244.9  440.52  5304.4  443.95  5336.2  445.04  5341.6  443.63  5361.3  444.38
  5366.7  443.35  5391.8  444.03  5397.1  442.99  5422.2  443.67  5455.2  442.47
#Mann= 6 ,-1 , 0
  4170.4     .12       0  4472.2      .1       0  4761.8     .12       0
  4977.3     .07       0  4981.3     .12       0  5304.4      .1       0
Bank Sta=4946.1,4986
XS Rating Curve= 0 ,0
Exp/Cntr=0.3,0.1

Type RM Length L Ch R = 1 ,7733    ,498,498,498
BEGIN DESCRIPTION:
Caney Creek T 22 15.0
END DESCRIPTION:
XS GIS Cut Line= 3
      2778998.18      6794173.12      2778269.69      6793568.21
        2777976.        6793261.
#Sta/Elev= 30
  4053.1  465.06  4162.3  455.91  4198.8   454.1  4261.4  447.66  4342.9  441.38
  4518.5     431  4594.7  427.73  4709.2  427.57    4717  423.64  4723.5  426.04
  4731.3  423.65  4744.8  426.73  4752.2  426.93  4879.8   425.3  4951.4  426.13
  4972.2  424.59  4999.1  426.98  5064.4  425.18  5099.6  425.88    5104  422.03
  5104.9  421.53  5109.6  422.03  5113.8  424.56  5163.2  427.01  5170.4  423.01
  5177.4  425.88  5221.3  426.87  5255.3  427.75  5326.1  434.18    5425  450.06
#Mann= 9 ,-1 , 0
  4053.1     .12       0  4261.4     .05       0  4342.9     .12       0
  4518.5      .1       0  4594.7     .12       0    5104     .07       0
  5109.6     .12       0  5177.4      .1       0  5221.3     .12       0
Bank Sta=5099.6,5113.8
XS Rating Curve= 0 ,0
Exp/Cntr=0.3,0.1

Type RM Length L Ch R = 1 ,7235    ,470,470,470
BEGIN DESCRIPTION:
Caney Creek T 22 14.0
END DESCRIPTION:
XS GIS Cut Line= 3
      2778975.98      6793710.99        2778576.        6793361.
      2777975.95      6793210.99
#Sta/Elev= 30
  4468.5  452.57    4561  443.68  4730.9  432.81    4766   428.6  4779.5  428.31
  4837.2  424.57  4900.8  423.28  4909.2   421.6    4915  422.91  4921.7  420.97
  4929.3  423.25  4943.5  421.13  4950.2  423.46  4964.4  423.89  4983.4  415.97
  4984.3  415.47    4989  415.97  4992.9  416.57  4996.7  423.02  5044.4  423.64
  5123.7  423.45    5134  421.85  5175.2  423.44  5188.1  420.01  5195.8  423.07
  5227.9  423.65  5312.7  424.23  5435.5  425.29  5443.2  428.47  5618.5  452.54
#Mann= 8 ,-1 , 0
  4468.5     .05       0  4779.5     .12       0  4909.2      .1       0
  4983.4     .07       0    4989      .1       0  5044.4     .12       0
  5227.9      .1       0  5312.7     .12       0
Bank Sta=4964.4,4996.7
XS Rating Curve= 0 ,0
Exp/Cntr=0.3,0.1

Type RM Length L Ch R = 1 ,6765    ,414,414,414
BEGIN DESCRIPTION:
Caney Creek T 22 13.0
END DESCRIPTION:
XS GIS Cut Line= 3
      2779131.56      6793546.07        2778826.        6793011.
        2778776.      6792661.03
#Sta/Elev= 30
  4388.4   452.1  4393.6  451.31    4448  446.17  4528.7  440.21  4652.5  432.59
    4744  428.19  4851.2  421.76  4953.5  420.14  4975.1  418.78  4990.9  412.17
  4996.7  411.29  4998.5  410.34  4999.5  409.84  5004.9  410.34  5007.1  410.34
  5014.7  416.84  5024.8  420.59    5045     419  5065.2  420.71  5081.2  420.18
  5095.5  419.28  5105.6  417.43  5125.8  419.22  5196.5  420.84  5206.6  422.19
  5267.2  437.87  5297.5  444.85  5317.7   448.6  5327.8  451.61  5358.1  455.63
#Mann= 6 ,-1 , 0
  4388.4     .12       0  4393.6     .05       0    4744     .12       0
  4998.5     .07       0  5004.9     .12       0  5081.2      .1       0
Bank Sta=4975.1,5024.8
XS Rating Curve= 0 ,0
Exp/Cntr=0.3,0.1

Type RM Length L Ch R = 1 ,6351    ,465,465,465
BEGIN DESCRIPTION:
Caney Creek T 22 12.0
END DESCRIPTION:
XS GIS Cut Line= 3
      2779476.01      6793261.01        2779176.        6792861.
      2778976.01      6792511.02
#Sta/Elev= 30
  4504.7  447.62    4562  443.45  4576.6  441.71  4636.8     439    4722  432.42
    4812  426.46  4832.8  426.61    4912  420.29  4947.4  418.76  4968.3  417.07
  4975.7  415.34  4982.8  411.43  4987.9  409.71    4989  409.21  4994.4  409.71
  4997.4  415.39  5001.6  418.86  5093.3   419.1  5152.3  418.12    5189  420.35
  5201.2  422.26  5211.3  422.79  5232.9  425.46  5260.3  429.86  5291.9  437.95
  5297.7  439.83  5304.2  443.03  5365.6   454.8  5384.8  458.64  5407.8  460.89
#Mann= 7 ,-1 , 0
  4504.7     .12       0  4636.8     .05       0    4722     .12       0
  4975.7      .1       0  4987.9     .07       0  4994.4      .1       0
  5365.6     .12       0
Bank Sta=4968.3,5001.6
XS Rating Curve= 0 ,0
Exp/Cntr=0.3,0.1