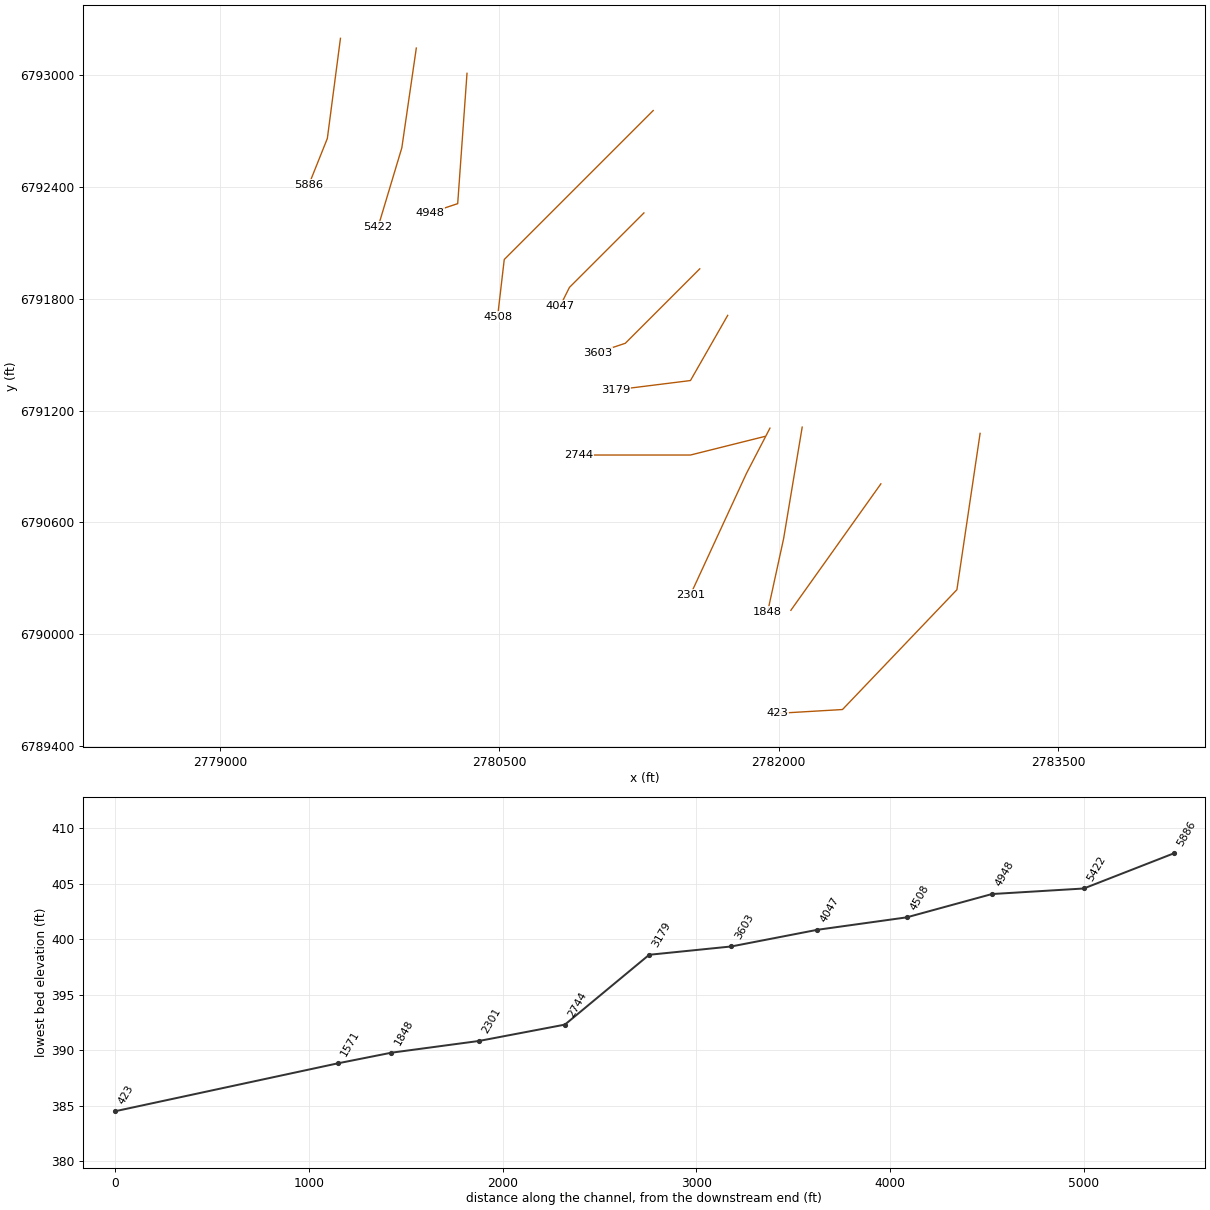
HEC-RAS study Caney Creek T 22.prj: Caney Creek T 22 Base Level Engineering

--- Caney Creek T 22.g01 (geometry) --- (continued)

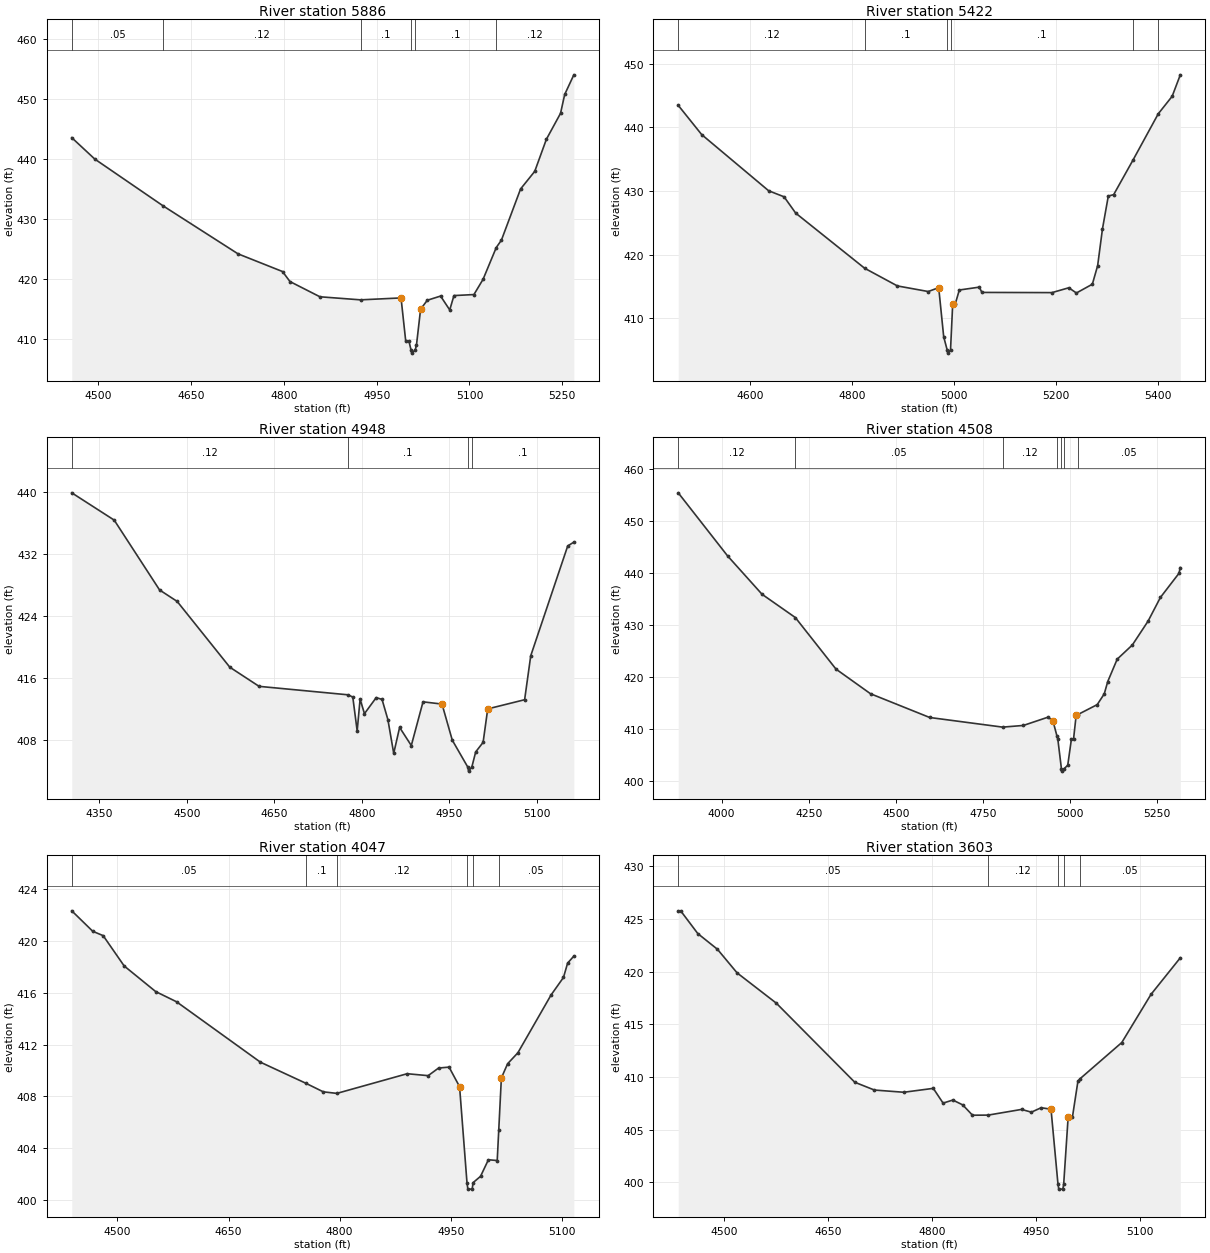
Type RM Length L Ch R = 1 ,5886    ,464,464,464
BEGIN DESCRIPTION:
Caney Creek T 22 11.0
END DESCRIPTION:
XS GIS Cut Line= 3
      2779646.37      6793198.69        2779576.        6792661.
      2779476.01      6792411.03
#Sta/Elev= 30
  4457.2  443.55  4494.4  439.99  4604.8  432.21  4725.9  424.23  4797.8  421.29
  4809.9  419.62  4858.3  417.09  4923.9  416.58  4989.4   416.9    4997  409.69
  5002.2  409.69  5005.6  408.22  5006.6  407.72  5012.2  408.22  5014.3  409.02
    5021  415.02  5031.8  416.51  5053.3  417.21  5068.1   414.9  5074.9  417.29
  5107.2  417.46    5122     420  5143.3  425.28  5151.6   426.5  5182.6  435.02
  5205.5  437.95  5224.3  443.28  5247.2   447.6  5253.9  450.73  5268.7     454
#Mann= 6 ,-1 , 0
  4457.2     .05       0  4604.8     .12       0  4923.9      .1       0
  5005.6     .07       0  5012.2      .1       0  5143.3     .12       0
Bank Sta=4989.4,5021
XS Rating Curve= 0 ,0
Exp/Cntr=0.3,0.1

Type RM Length L Ch R = 1 ,5422    ,474,474,474
BEGIN DESCRIPTION:
Caney Creek T 22 10.0
END DESCRIPTION:
XS GIS Cut Line= 3
      2780053.76      6793146.53        2779976.        6792611.
      2779848.34      6792185.69
#Sta/Elev= 30
  4458.4  443.46  4504.4  438.87  4635.8  430.05  4666.1   429.1  4688.9  426.54
  4824.1  417.89  4888.4  415.11    4949  414.23  4969.5  414.84  4979.3  407.13
  4986.1  405.06  4987.2  404.56  4992.7  405.06    4997  412.35  5002.2  412.35
    5010  414.47  5049.1  414.92  5054.3  414.09  5191.8  414.06  5224.8  414.82
  5239.7     414    5271  415.38  5281.4   418.3  5290.9  424.09  5302.3  429.22
  5312.8  429.44  5350.7  434.86  5400.3  442.13  5427.6  444.88  5443.6  448.25
#Mann= 6 ,-1 , 0
  4458.4     .12       0  4824.1      .1       0  4986.1     .07       0
  4992.7      .1       0  5350.7     .12       0  5400.3      .1       0
Bank Sta=4969.5,4997
XS Rating Curve= 0 ,0
Exp/Cntr=0.3,0.1

Type RM Length L Ch R = 1 ,4948    ,440,440,440
BEGIN DESCRIPTION:
Caney Creek T 22 9.0
END DESCRIPTION:
XS GIS Cut Line= 3
        2780326.      6793011.03        2780276.        6792311.
      2780126.03      6792261.01
#Sta/Elev= 30
  4303.1  439.84  4375.8  436.33  4453.5  427.35  4483.6  425.88  4573.8  417.42
  4623.9  414.96  4776.5  413.87  4784.4  413.58  4791.9  409.23  4796.9  413.31
  4804.4  411.45  4824.5  413.51  4834.5  413.28  4844.5  410.69  4854.5  406.35
  4864.6  409.68  4884.6  407.35  4904.7  412.97  4937.2  412.68  4954.8  408.04
  4981.5  404.56  4982.6  404.06  4988.2  404.56  4994.9  406.53  5007.6  407.76
  5015.5  412.06  5078.7  413.24  5089.2   418.9  5152.5  433.01    5163   433.5
#Mann= 4 ,-1 , 0
  4303.1     .12       0  4776.5      .1       0  4981.5     .07       0
  4988.2      .1       0
Bank Sta=4937.2,5015.5
XS Rating Curve= 0 ,0
Exp/Cntr=0.3,0.1

Type RM Length L Ch R = 1 ,4508    ,461,461,461
BEGIN DESCRIPTION:
Caney Creek T 22 8.0
END DESCRIPTION:
XS GIS Cut Line= 3
      2781325.99      6792810.99        2780526.        6792011.
      2780490.27      6791704.33
#Sta/Elev= 30
  3875.8   455.4  4017.2   443.3  4116.2  435.92  4211.7  431.45  4328.3  421.55
  4427.3  416.82    4597  412.26  4806.2  410.41  4865.7  410.73  4936.4  412.32
  4950.6  411.61    4962  408.72  4964.7  408.04  4974.8  402.46    4976  401.96
    4983  402.46    4993  403.08  5003.6  408.14  5009.7  408.14  5017.2  412.69
    5022  412.82  5077.6  414.73  5097.8   416.8  5107.8  419.17  5134.9  423.46
  5178.3  426.18  5223.4  430.76  5258.8  435.31  5311.9  439.93  5315.9  441.05
#Mann= 7 ,-1 , 0
  3875.8     .12       0  4211.7     .05       0  4806.2     .12       0
    4962      .1       0  4974.8     .07       0    4983      .1       0
    5022     .05       0
Bank Sta=4950.6,5017.2
XS Rating Curve= 0 ,0
Exp/Cntr=0.3,0.1

Type RM Length L Ch R = 1 ,4047    ,444,444,444
BEGIN DESCRIPTION:
Caney Creek T 22 7.0
END DESCRIPTION:
XS GIS Cut Line= 3
      2781276.02      6792261.02        2780876.        6791861.
      2780826.01      6791761.01
#Sta/Elev= 30
  4438.5  422.35  4466.8  420.77  4480.9  420.43  4509.2  418.09  4551.7  416.11
  4579.9  415.32  4693.1  410.65  4754.1  409.03  4777.9  408.36  4796.2  408.24
  4891.1  409.76  4919.4  409.61  4933.5   410.2  4947.6  410.27  4961.8  408.76
  4971.8  401.34    4973  400.84  4978.8  400.84    4980  401.34  4990.1  401.83
  5000.7  403.11  5012.6  403.05  5014.7  405.44  5018.2  409.43  5026.6  410.53
  5040.5  411.38  5085.3  415.85    5102   417.2  5107.6  418.31    5116  418.85
#Mann= 6 ,-1 , 0
  4438.5     .05       0  4754.1      .1       0  4796.2     .12       0
  4971.8     .07       0    4980     .12       0  5014.7     .05       0
Bank Sta=4961.8,5018.2
XS Rating Curve= 0 ,0
Exp/Cntr=0.3,0.1

Type RM Length L Ch R = 1 ,3603    ,424,424,424
BEGIN DESCRIPTION:
Caney Creek T 22 6.0
END DESCRIPTION:
XS GIS Cut Line= 3
      2781575.97      6791960.97        2781176.        6791561.
      2781025.96      6791510.99
#Sta/Elev= 30
  4434.1  425.77  4437.6  425.77  4462.3  423.61  4490.6  422.12  4518.9  419.88
  4575.5     417  4688.6  409.49  4716.9  408.75  4759.3  408.54  4801.8  408.91
  4815.9  407.51    4830   407.8  4844.2  407.34  4858.3  406.36  4880.9  406.37
    4929  406.91  4943.2  406.65  4957.3  407.07  4971.5  406.93  4981.5  399.84
  4982.7  399.34  4988.6  399.34  4989.8  399.84  4996.2  406.19  5002.4  406.19
  5010.3  409.59  5013.3  409.82  5073.5  413.26  5115.7  417.84  5157.9  421.31
#Mann= 5 ,-1 , 0
  4434.1     .05       0  4880.9     .12       0  4981.5     .07       0
  4989.8     .12       0  5013.3     .05       0
Bank Sta=4971.5,4996.2
XS Rating Curve= 0 ,0
Exp/Cntr=0.3,0.1

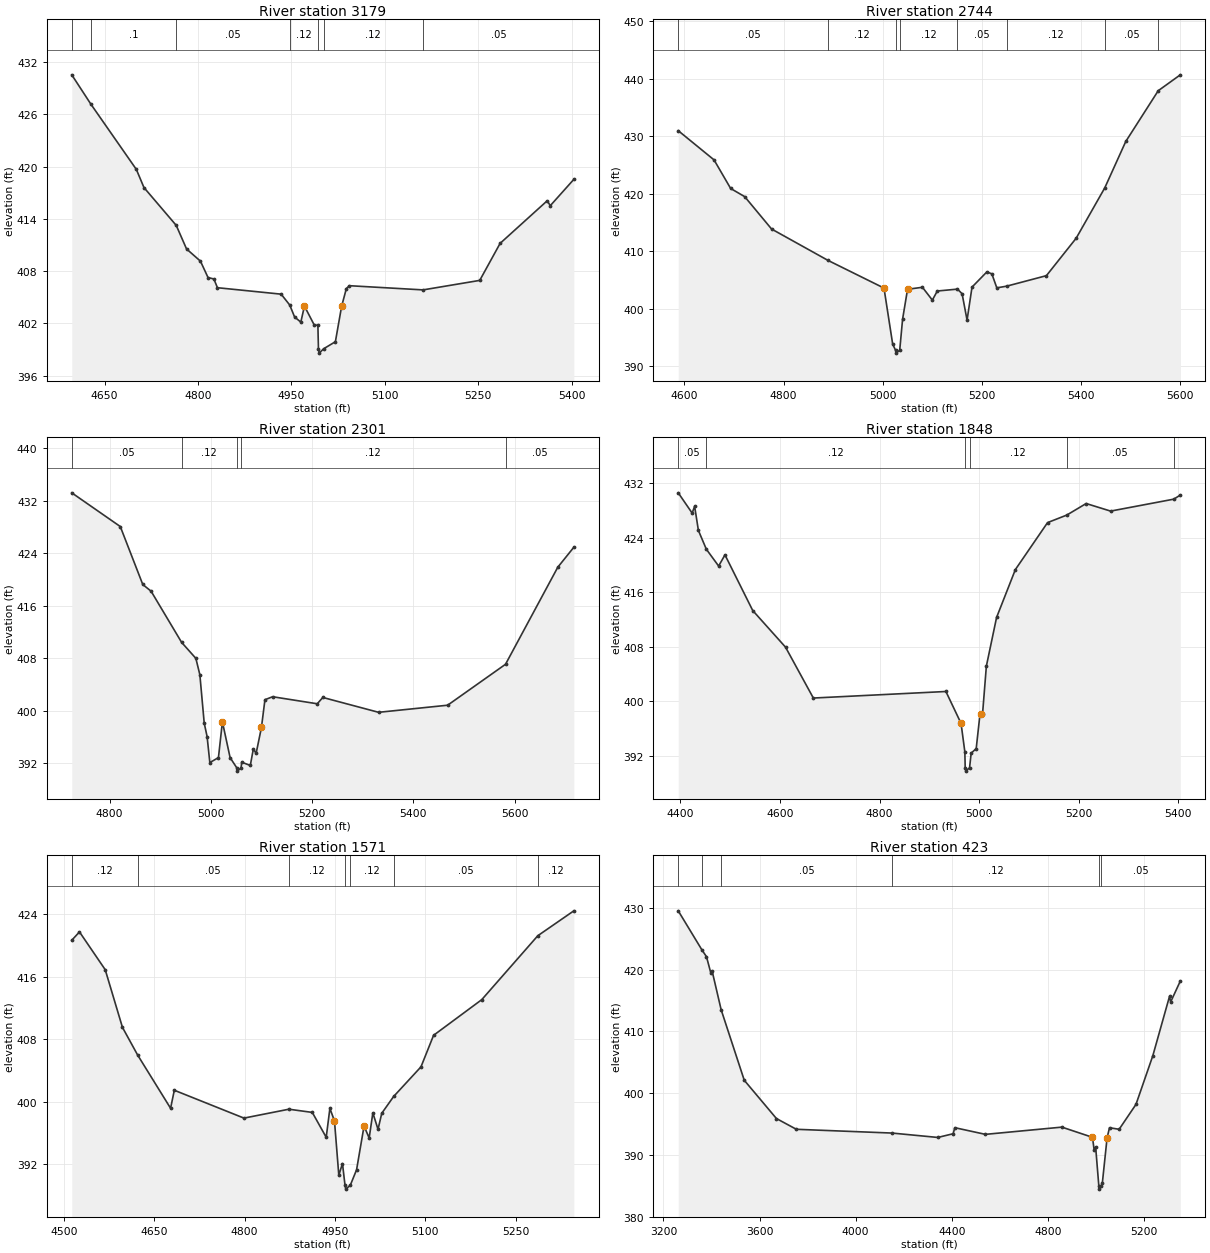
Type RM Length L Ch R = 1 ,3179    ,435,435,435
BEGIN DESCRIPTION:
Caney Creek T 22 5.0
END DESCRIPTION:
XS GIS Cut Line= 3
        2781726.      6791710.99        2781526.        6791361.
      2781126.02        6791311.
#Sta/Elev= 30
  4597.4  430.54  4628.2  427.16  4701.1  419.68  4713.3   417.6  4765.2  413.25
  4781.7  410.55    4804  409.15  4816.2  407.27  4825.6   407.1  4831.3   406.1
  4933.6  405.36  4947.4  404.11  4955.2  402.74  4965.2  402.15    4971  403.99
  4986.8  401.81  4992.6  401.79  4993.5  399.09  4994.7  398.59  5001.8  399.09
  5020.7   399.9  5030.7  403.96  5038.3     406  5043.3  406.33  5161.5  405.85
  5252.5  406.94  5285.2  411.19  5360.8  416.08  5365.8  415.52  5403.6  418.54
#Mann= 7 ,-1 , 0
  4597.4     .05       0  4628.2      .1       0  4765.2     .05       0
  4947.4     .12       0  4993.5     .07       0  5001.8     .12       0
  5161.5     .05       0
Bank Sta=4971,5030.7
XS Rating Curve= 0 ,0
Exp/Cntr=0.3,0.1

Type RM Length L Ch R = 1 ,2744    ,443,443,443
BEGIN DESCRIPTION:
Caney Creek T 22 4.0
END DESCRIPTION:
XS GIS Cut Line= 3
      2781926.04      6791061.01        2781526.        6790961.
      2780925.95        6790961.
#Sta/Elev= 30
  4587.5  430.98  4659.7   425.9  4693.2  420.93  4721.5  419.51  4775.7  413.88
  4889.6  408.42  5002.4  403.61  5019.9  393.87  5025.7   392.8  5026.9   392.3
  5034.1   392.8  5039.9  398.21  5049.9   403.4  5079.9  403.75  5099.9  401.52
  5109.9   403.1  5150.6  403.43  5159.9  402.62  5169.9  398.04  5179.9  403.78
  5209.9  406.43  5219.9  406.08  5229.9  403.65  5249.6  403.94  5329.9  405.77
  5389.9  412.28  5447.5  421.02  5489.9   429.1  5555.4  437.93  5599.9  440.69
#Mann= 8 ,-1 , 0
  4587.5     .05       0  4889.6     .12       0  5025.7     .07       0
  5034.1     .12       0  5150.6     .05       0  5249.6     .12       0
  5447.5     .05       0  5555.4      .1       0
Bank Sta=5002.4,5049.9
XS Rating Curve= 0 ,0
Exp/Cntr=0.3,0.1

Type RM Length L Ch R = 1 ,2301    ,453,453,453
BEGIN DESCRIPTION:
Caney Creek T 22 3.0
END DESCRIPTION:
XS GIS Cut Line= 3
      2781952.89      6791105.43        2781826.        6790861.
        2781526.      6790210.99
#Sta/Elev= 30
  4725.5  433.18  4821.3  428.05  4865.7  419.23  4882.1  418.21  4942.4  410.42
  4970.5  407.99  4978.4   405.5    4987  398.14  4992.7  396.09  4998.1  392.13
  5015.1  392.89  5022.9  398.33  5038.1  392.89  5051.3  391.33  5052.5  390.83
  5059.8  391.33    5061  392.19    5078  391.69    5084  394.22  5089.5  393.53
    5100  397.48  5106.9   401.7  5122.1  402.15  5210.2  401.08  5221.2  402.04
  5331.3  399.78  5467.6  400.86  5581.9  407.09  5685.1  421.86  5716.8   424.9
#Mann= 5 ,-1 , 0
  4725.5     .05       0  4942.4     .12       0  5051.3     .07       0
  5059.8     .12       0  5581.9     .05       0
Bank Sta=5022.9,5100
XS Rating Curve= 0 ,0
Exp/Cntr=0.3,0.1

Type RM Length L Ch R = 1 ,1848    ,277,277,277
BEGIN DESCRIPTION:
Caney Creek T 22 2.0
END DESCRIPTION:
XS GIS Cut Line= 3
        2782126.      6791110.98        2782026.        6790511.
      2781940.91      6790120.63
#Sta/Elev= 30
    4396  430.59  4423.9  427.62  4428.9  428.61  4436.5  425.07  4452.4  422.32
  4477.1  419.85  4489.8  421.49  4545.5  413.33  4611.4  407.95  4667.2  400.49
  4933.3  401.45  4963.7  396.77  4971.3   392.6    4972  390.27  4973.3  389.77
  4980.8  390.27    4984  392.41  4994.1  393.07  5001.7  398.12  5004.3  398.12
  5006.8  398.12  5014.5  405.17    5035  412.31  5072.7  419.33  5137.3  426.22
    5176  427.33  5214.8  429.02  5263.9  427.91  5390.6  429.66  5403.8  430.26
#Mann= 6 ,-1 , 0
    4396     .05       0  4452.4     .12       0    4972     .07       0
  4980.8     .12       0    5176     .05       0  5390.6     .12       0
Bank Sta=4963.7,5004.3
XS Rating Curve= 0 ,0
Exp/Cntr=0.3,0.1

Type RM Length L Ch R = 1 ,1571    ,1148,1148,1148
BEGIN DESCRIPTION:
Mapping XS 1f4f0473
END DESCRIPTION:
XS GIS Cut Line= 2
      2782548.57      6790806.21      2782065.32      6790127.35
#Sta/Elev= 30
  4513.1   420.7  4525.9  421.77  4568.6  416.93  4597.2  409.54  4622.5  405.98
  4677.1  399.17  4683.3  401.48  4798.9  397.91  4873.5  399.05  4912.3  398.64
  4935.4  395.45  4941.5  399.15  4949.1  397.56  4956.3   390.6  4962.4  392.08
  4966.6  389.31  4967.9  388.81  4975.4  389.31  4985.8  391.29  4998.2  396.89
  5006.7  395.36  5012.8  398.58  5021.4  396.47  5027.6  398.53  5047.3  400.68
  5092.7  404.48  5113.6  408.52  5193.6  413.09  5286.6  421.28  5346.4  424.47
#Mann= 7 ,-1 , 0
  4513.1     .12       0  4622.5     .05       0  4873.5     .12       0
  4966.6     .07       0  4975.4     .12       0  5047.3     .05       0
  5286.6     .12       0
Bank Sta=4949.1,4998.2
XS Rating Curve= 0 ,0
Exp/Cntr=0.3,0.1

Type RM Length L Ch R = 1 ,423     ,0,0,0
BEGIN DESCRIPTION:
Caney Creek T 22 1.0
END DESCRIPTION:
XS GIS Cut Line= 4
      2783081.43      6791077.32      2782956.82      6790237.67
      2782342.43      6789594.24      2781991.83      6789573.61
#Sta/Elev= 30
  3261.5  429.52  3360.7  423.16  3379.1   422.1  3397.5  419.41  3402.5  419.79
  3440.1  413.52  3536.3  402.11  3670.2  395.92  3753.1  394.18  4151.3  393.57
  4341.8  392.86  4405.7  393.46  4412.6  394.44    4540  393.36  4858.3  394.53
  4985.7  392.88  4992.6  390.81  4998.8  391.32  5012.1     385  5013.3   384.5
  5020.9     385  5026.5  385.42  5046.5  392.82  5056.5  394.43  5096.6  394.18
  5166.7  398.21  5236.8  406.08  5306.2  415.67  5311.2  414.79  5351.2  418.16
#Mann= 6 ,-1 , 0
  3261.5      .1       0  3360.7     .12       0  3440.1     .05       0
  4151.3     .12       0  5012.1     .07       0  5020.9     .05       0
Bank Sta=4985.7,5046.5
XS Rating Curve= 0 ,0
Exp/Cntr=0.3,0.1

Chan Stop Cuts=-1
Use User Specified Reach Order=0
Composite Channel Slope=5