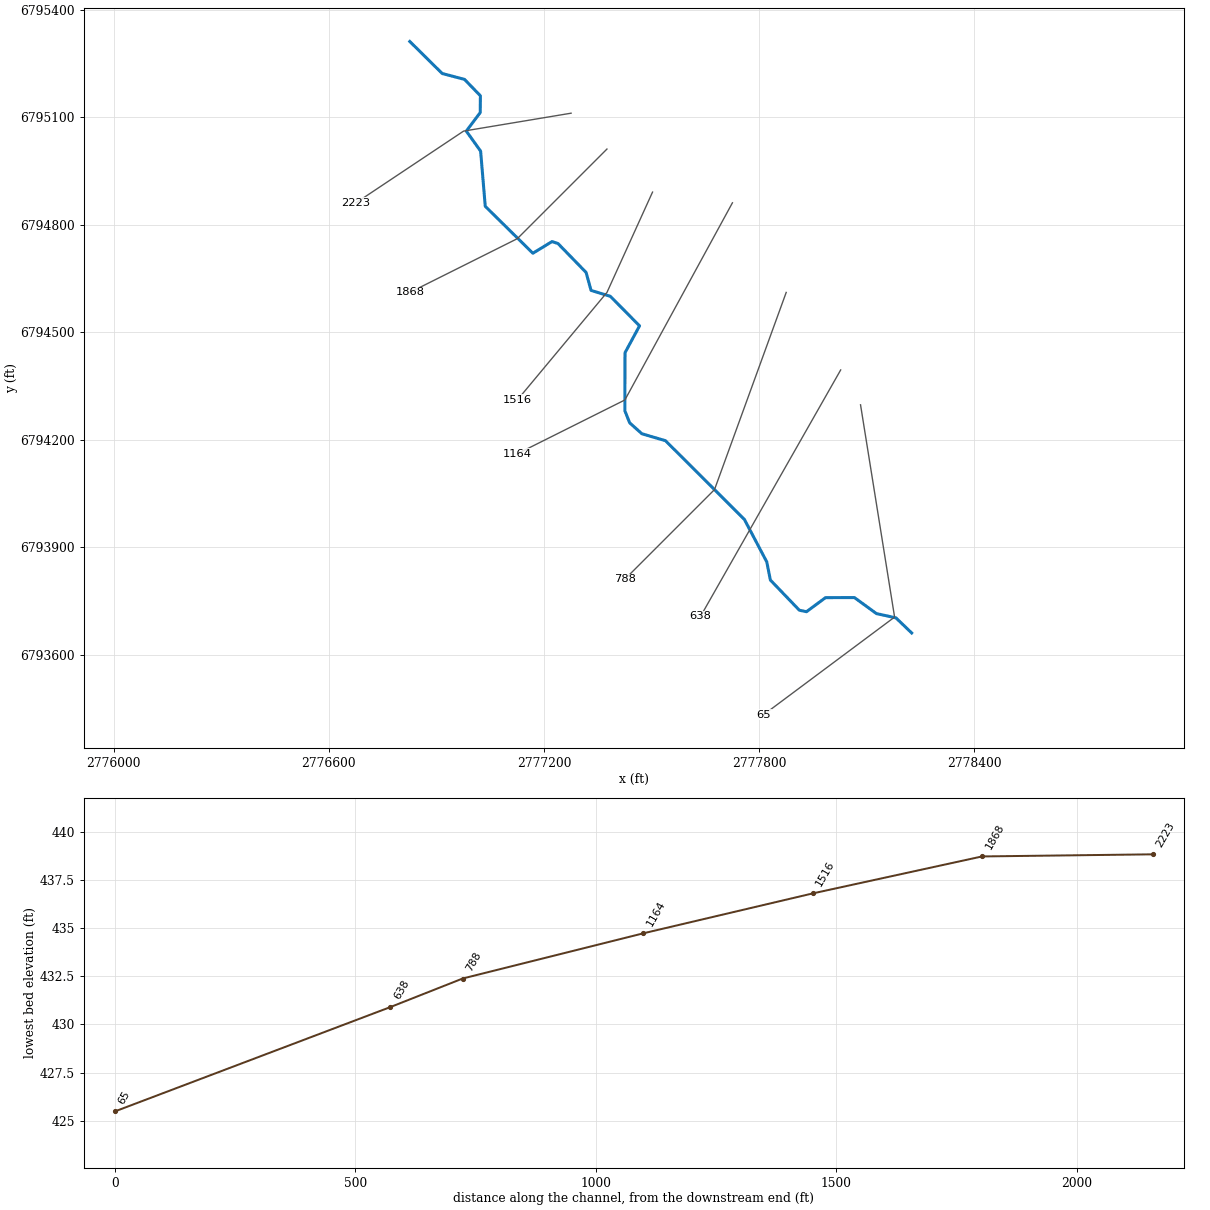
--- Caney Creek T 23.prj (project) ---

Proj Title=Caney Creek T 23 Base Level Engineering
Current Plan=p01
Default Exp/Contr=0.3,0.1
English Units
Geom File=g01
Flow File=f01
Plan File=p01
BEGIN DESCRIPTION:
Caney Creek T 23
END DESCRIPTION:

--- Caney Creek T 23.p01 (plan) ---

Plan Title=Multiple Run
Short Identifier=Multiple
Geom File=g01
Flow File=f01
Subcritical Flow
K Sum by GR= 0
Std Step Tol= 0.01
Critical Tol= 0.01
Num of Std Step Trials= 20
Max Error Tol= 0.3
Flow Tol Ratio= 0.001
Split Flow NTrial= 30
Split Flow Tol= 0.02
Split Flow Ratio= 0.02
Log Output Level= 0
Friction Slope Method= 1
Unsteady Friction Slope Method= 2
Unsteady Bridges Friction Slope Method= 1
Parabolic Critical Depth
Global Vel Dist=  1 , 1 , 1
Global Log Level= 0
CheckData=True
Encroach Param= -1, 0, 0, 0
BEGIN DESCRIPTION:
Multiple Run
END DESCRIPTION:

--- Caney Creek T 23.f01 (steady flow) ---

Flow Title=Multiple
Number of Profiles=7
Profile Names=10-year,25-year,50-year,1pct_min,100-year,1pct_plu,500-year
River Rch & RM= Caney Creek T 23,Reach-1,2223
     630     864    1059     647    1290    2575    1918
Boundary for River Rch & Prof#=Caney Creek T 23,Reach-1,1
Up Type=0
Dn Type=3
Dn Slope=0.005
Boundary for River Rch & Prof#=Caney Creek T 23,Reach-1,2
Up Type=0
Dn Type=3
Dn Slope=0.005
Boundary for River Rch & Prof#=Caney Creek T 23,Reach-1,3
Up Type=0
Dn Type=3
Dn Slope=0.005
Boundary for River Rch & Prof#=Caney Creek T 23,Reach-1,4
Up Type=0
Dn Type=3
Dn Slope=0.005
Boundary for River Rch & Prof#=Caney Creek T 23,Reach-1,5
Up Type=0
Dn Type=3
Dn Slope=0.005
Boundary for River Rch & Prof#=Caney Creek T 23,Reach-1,6
Up Type=0
Dn Type=3
Dn Slope=0.005
Boundary for River Rch & Prof#=Caney Creek T 23,Reach-1,7
Up Type=0
Dn Type=3
Dn Slope=0.005

--- Caney Creek T 23.g01 (geometry) ---

Geom Title=Existing Conditions

River Reach=Caney Creek T 23,Reach-1
Reach XY= 30
      2776826.00      6795311.00      2776916.32      6795221.72
      2776978.62      6795205.26      2777022.93      6795159.57
      2777022.44      6795112.68      2776983.59      6795061.01
      2777023.53      6795005.14      2777036.48      6794851.20
      2777169.33      6794720.30      2777222.68      6794752.84
      2777239.36      6794747.36      2777317.72      6794666.79
      2777331.62      6794616.62      2777385.46      6794600.11
      2777466.88      6794517.76      2777426.34      6794442.78
      2777425.91      6794280.88      2777439.22      6794247.33
      2777473.42      6794216.74      2777539.20      6794197.36
      2777759.36      6793977.68      2777821.81      6793859.26
      2777831.83      6793808.67      2777912.59      6793724.52
      2777932.52      6793720.29      2777985.63      6793759.55
      2778066.30      6793759.75      2778127.69      6793715.08
      2778182.15      6793703.09      2778226.00      6793661.00

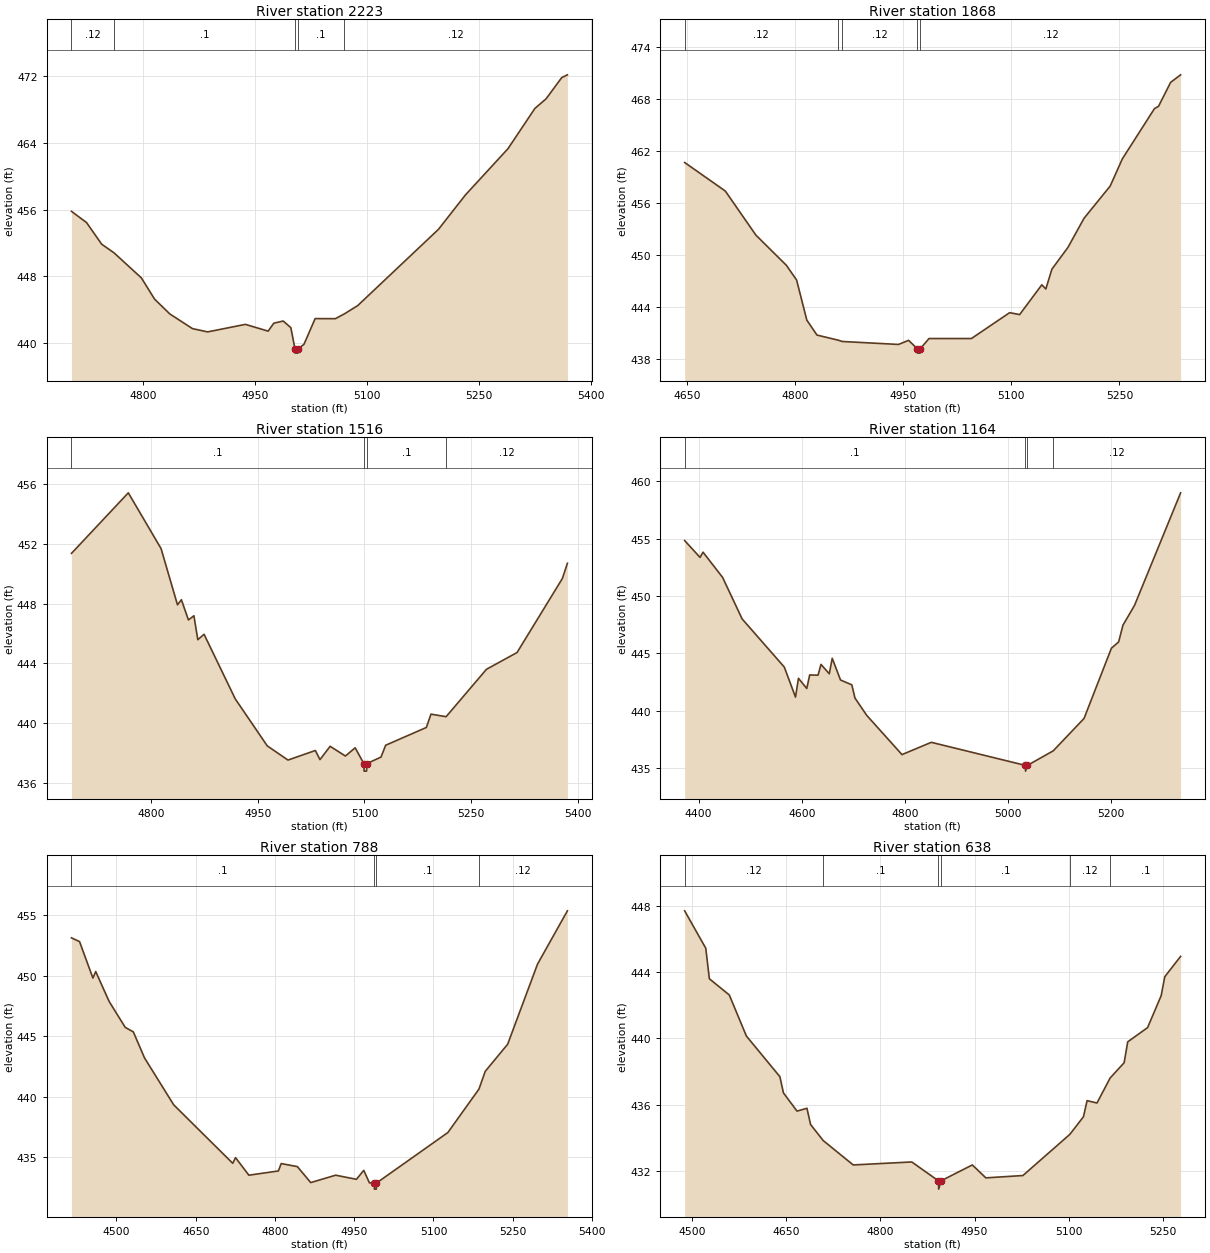
Type RM Length L Ch R = 1,2223,355,355,355
BEGIN DESCRIPTION:
Caney Creek T 23 6.0
END DESCRIPTION:
XS GIS Cut Line= 3
      2777275.97      6795110.99      2776976.00      6795061.00
      2776675.97      6794860.98
#Sta/Elev= 30
  4703.8  455.79  4724.0  454.45  4744.3  451.86  4760.8  450.83  4797.5  447.83
  4815.3  445.28  4835.6  443.52  4866.0  441.76  4886.3  441.37  4936.9  442.27
  4967.4  441.46  4975.0  442.41  4987.6  442.67  4997.8  441.88  5003.4  439.33
  5003.6  438.83  5007.1  438.83  5007.4  439.33  5015.4  439.88  5030.4  442.96
  5057.5  442.95  5069.7  443.53  5087.5  444.52  5195.7  453.64  5231.8  457.75
  5288.8  463.28  5324.9  468.10  5339.9  469.25  5360.9  471.79  5368.5  472.12
#Mann=5,-1,0
  4703.8    0.12       0  4760.8     0.1       0  5003.4    0.07       0
  5007.4     0.1       0  5069.7    0.12       0
Bank Sta=5003.4,5007.4
Exp/Cntr=0.3,0.1

Type RM Length L Ch R = 1,1868,352,352,352
BEGIN DESCRIPTION:
Caney Creek T 23 5.0
END DESCRIPTION:
XS GIS Cut Line= 3
      2777375.98      6795010.98      2777126.00      6794761.00
      2776826.04      6794611.02
#Sta/Elev= 30
  4646.1  460.68  4702.6  457.39  4745.1  452.31  4787.5  448.83  4801.6  447.14
  4815.8  442.52  4829.9  440.80  4859.0  440.22  4865.1  440.06  4943.1  439.72
  4957.2  440.19  4969.3  439.22  4969.6  438.72  4973.1  438.72  4973.3  439.22
  4985.5  440.40  5044.4  440.40  5097.5  443.38  5111.4  443.16  5142.2  446.59
  5147.8  446.11  5156.2  448.39  5178.5  450.90  5200.9  454.26  5237.2  457.97
  5254.0  461.09  5298.7  466.89  5304.3  467.15  5321.1  469.91  5335.0  470.78
#Mann=5,-1,0
  4646.1    0.12       0  4859.0     0.1       0  4865.1    0.12       0
  4969.3    0.07       0  4973.3    0.12       0
Bank Sta=4969.3,4973.3
Exp/Cntr=0.3,0.1

Type RM Length L Ch R = 1,1516,352,352,352
BEGIN DESCRIPTION:
Caney Creek T 23 4.0
END DESCRIPTION:
XS GIS Cut Line= 3
      2777503.13      6794890.89      2777376.00      6794611.00
      2777126.02      6794311.02
#Sta/Elev= 30
  4687.7  451.36  4767.7  455.41  4813.8  451.68  4836.9  447.92  4842.4  448.26
  4852.3  446.91  4860.0  447.19  4865.5  445.59  4874.3  445.95  4918.2  441.63
  4963.2  438.49  4992.4  437.54  5030.9  438.18  5037.4  437.57  5051.7  438.46
  5073.2  437.81  5086.9  438.36  5099.2  437.30  5099.5  436.80  5103.0  436.80
  5103.2  437.30  5123.3  437.74  5129.8  438.53  5187.1  439.72  5193.6  440.61
  5214.9  440.44  5271.7  443.61  5314.7  444.73  5378.5  449.68  5385.6  450.70
#Mann=4,-1,0
  4687.7     0.1       0  5099.2    0.07       0  5103.2     0.1       0
  5214.9    0.12       0
Bank Sta=5099.2,5103.2
Exp/Cntr=0.3,0.1

Type RM Length L Ch R = 1,1164,376,376,376
BEGIN DESCRIPTION:
Caney Creek T 23 3.0
END DESCRIPTION:
XS GIS Cut Line= 3
      2777726.00      6794860.99      2777426.00      6794311.00
      2777126.00      6794161.00
#Sta/Elev= 30
  4373.0  454.82  4402.9  453.35  4408.6  453.81  4446.6  451.61  4484.5  447.99
  4566.2  443.80  4588.0  441.18  4593.7  442.82  4609.8  441.93  4615.5  443.11
  4631.7  443.09  4637.4  444.03  4653.5  443.21  4659.2  444.56  4675.3  442.67
  4697.2  442.25  4703.3  441.10  4726.1  439.59  4794.5  436.17  4851.4  437.24
  5033.8  435.23  5034.1  434.73  5037.8  435.23  5087.9  436.50  5147.6  439.32
  5200.7  445.44  5214.7  445.99  5223.1  447.45  5245.5  449.17  5334.9  458.98
#Mann=4,-1,0
  4373.0     0.1       0  5033.8    0.07       0  5037.8     0.1       0
  5087.9    0.12       0
Bank Sta=5033.8,5037.8
Exp/Cntr=0.3,0.1

Type RM Length L Ch R = 1,788,150,150,150
BEGIN DESCRIPTION:
Caney Creek T 23 2.0
END DESCRIPTION:
XS GIS Cut Line= 3
      2777876.00      6794611.00      2777676.00      6794061.00
      2777425.99      6793810.99
#Sta/Elev= 30
  4414.8  453.12  4430.1  452.81  4455.4  449.80  4460.7  450.34  4486.0  447.88
  4516.6  445.73  4531.9  445.36  4553.1  443.21  4608.3  439.34  4720.1  434.51
  4725.4  434.98  4750.6  433.53  4806.5  433.88  4811.8  434.49  4842.4  434.24
  4867.7  432.92  4914.9  433.53  4954.2  433.19  4968.1  433.93  4978.8  432.90
  4988.1  432.88  4988.3  432.38  4991.8  432.38  4992.1  432.88  5127.3  437.05
  5186.2  440.64  5198.0  442.10  5240.5  444.34  5297.0  450.95  5353.6  455.35
#Mann=4,-1,0
  4414.8     0.1       0  4988.1    0.07       0  4992.1     0.1       0
  5186.2    0.12       0
Bank Sta=4988.1,4992.1
Exp/Cntr=0.3,0.1

Type RM Length L Ch R = 1,638,573,573,573
BEGIN DESCRIPTION:
Mapping XS 052564f6
END DESCRIPTION:
XS GIS Cut Line= 2
      2778027.96      6794394.72      2777636.83      6793706.95
#Sta/Elev= 30
  4487.6  447.70  4521.3  445.44  4527.0  443.60  4558.8  442.62  4586.1  440.14
  4639.5  437.69  4645.2  436.71  4666.8  435.61  4682.7  435.78  4688.5  434.80
  4708.7  433.83  4756.5  432.36  4849.9  432.54  4892.5  431.40  4892.8  430.90
  4896.5  431.40  4946.5  432.36  4968.1  431.58  5027.2  431.72  5102.2  434.21
  5123.8  435.27  5129.6  436.24  5145.4  436.10  5166.4  437.61  5188.7  438.53
  5194.4  439.79  5226.1  440.65  5247.8  442.58  5253.5  443.72  5278.8  444.95
#Mann=6,-1,0
  4487.6    0.12       0  4708.7     0.1       0  4892.5    0.07       0
  4896.5     0.1       0  5102.2    0.12       0  5166.4     0.1       0
Bank Sta=4892.5,4896.5
Exp/Cntr=0.3,0.1

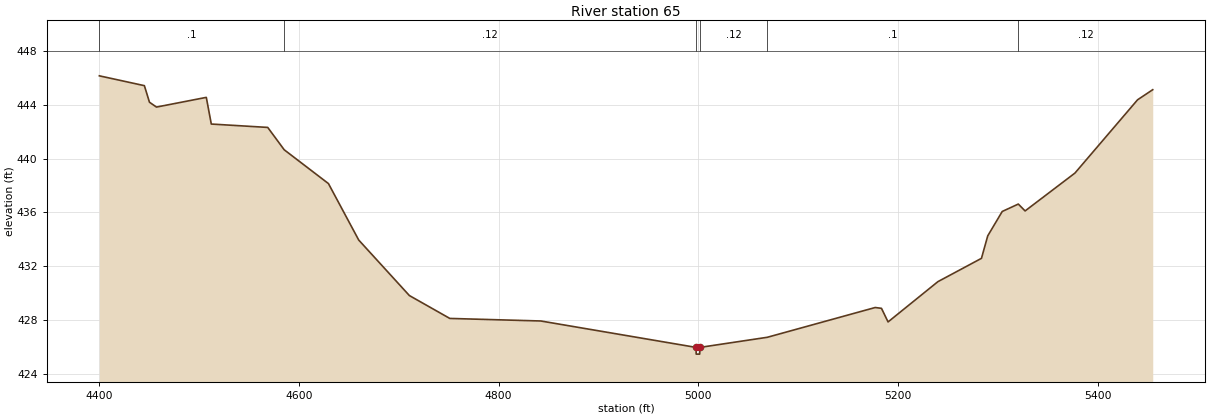
Type RM Length L Ch R = 1,65,0,0,0
BEGIN DESCRIPTION:
Caney Creek T 23 1.0
END DESCRIPTION:
XS GIS Cut Line= 3
      2778083.36      6794297.46      2778178.37      6793705.33
      2777813.57      6793433.40
#Sta/Elev= 30
  4400.3  446.14  4445.4  445.41  4450.5  444.18  4457.5  443.82  4507.4  444.54
  4512.4  442.56  4568.9  442.31  4585.4  440.65  4629.7  438.14  4660.0  433.95
  4710.7  429.83  4751.2  428.13  4842.3  427.94  4997.7  425.98  4997.9  425.48
  5001.4  425.48  5001.7  425.98  5069.1  426.73  5177.1  428.94  5183.4  428.88
  5190.0  427.87  5239.9  430.86  5283.5  432.59  5289.8  434.26  5304.3  436.07
  5320.4  436.62  5327.2  436.11  5377.1  438.92  5439.8  444.36  5455.0  445.11
#Mann=6,-1,0
  4400.3     0.1       0  4585.4    0.12       0  4997.7    0.07       0
  5001.7    0.12       0  5069.1     0.1       0  5320.4    0.12       0
Bank Sta=4997.7,5001.7
Exp/Cntr=0.3,0.1

Chan Stop Cuts=-1