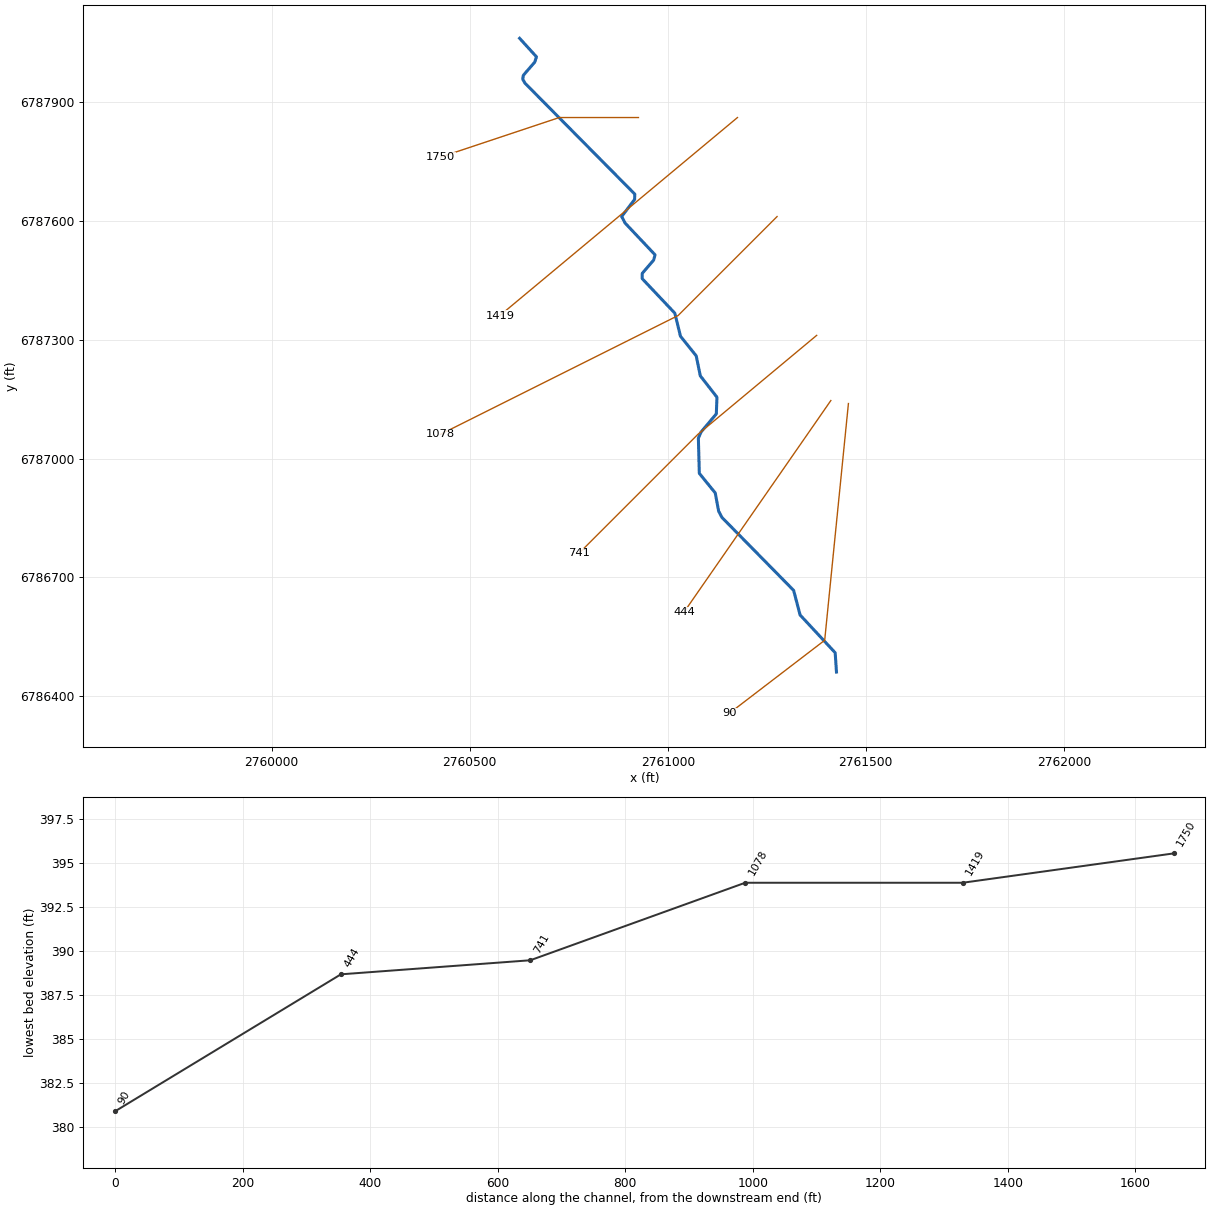
--- Caney Creek T 24.prj (project) ---

Proj Title=Caney Creek T 24 Base Level Engineering
Current Plan=p01
Default Exp/Contr=0.3,0.1
English Units
Geom File=g01
Flow File=f01
Plan File=p01
BEGIN DESCRIPTION:
Caney Creek T 24
END DESCRIPTION:

--- Caney Creek T 24.p01 (plan) ---

Plan Title=Multiple Run
Short Identifier=Multiple
Geom File=g01
Flow File=f01
Subcritical Flow
K Sum by GR= 0
Std Step Tol= 0.01
Critical Tol= 0.01
Num of Std Step Trials= 20
Max Error Tol= 0.3
Flow Tol Ratio= 0.001
Split Flow NTrial= 30
Split Flow Tol= 0.02
Split Flow Ratio= 0.02
Log Output Level= 0
Friction Slope Method= 1
Unsteady Friction Slope Method= 2
Unsteady Bridges Friction Slope Method= 1
Parabolic Critical Depth
Global Vel Dist=  1 , 1 , 1
Global Log Level= 0
CheckData=True
Encroach Param= -1, 0, 0, 0
BEGIN DESCRIPTION:
Multiple Run
END DESCRIPTION:

--- Caney Creek T 24.f01 (steady flow) ---

Flow Title=Multiple
Number of Profiles=7
Profile Names=10-year,25-year,50-year,1pct_min,100-year,1pct_plu,500-year
River Rch & RM= Caney Creek T 24,Reach-1,1750
     402     531     634     377     753    1503    1063
Boundary for River Rch & Prof#=Caney Creek T 24,Reach-1,1
Up Type=0
Dn Type=3
Dn Slope=0.005
Boundary for River Rch & Prof#=Caney Creek T 24,Reach-1,2
Up Type=0
Dn Type=3
Dn Slope=0.005
Boundary for River Rch & Prof#=Caney Creek T 24,Reach-1,3
Up Type=0
Dn Type=3
Dn Slope=0.005
Boundary for River Rch & Prof#=Caney Creek T 24,Reach-1,4
Up Type=0
Dn Type=3
Dn Slope=0.005
Boundary for River Rch & Prof#=Caney Creek T 24,Reach-1,5
Up Type=0
Dn Type=3
Dn Slope=0.005
Boundary for River Rch & Prof#=Caney Creek T 24,Reach-1,6
Up Type=0
Dn Type=3
Dn Slope=0.005
Boundary for River Rch & Prof#=Caney Creek T 24,Reach-1,7
Up Type=0
Dn Type=3
Dn Slope=0.005

--- Caney Creek T 24.g01 (geometry) ---

Geom Title=Existing Conditions

River Reach=Caney Creek T 24,Reach-1
Reach XY= 30
      2760626.00      6788061.00      2760668.48      6788014.33
      2760664.15      6788001.00      2760635.36      6787967.67
      2760633.86      6787957.67      2760639.59      6787947.67
      2760916.70      6787667.67      2760916.38      6787654.33
      2760883.59      6787611.00      2760892.46      6787594.33
      2760967.97      6787514.33      2760964.28      6787501.00
      2760935.62      6787467.67      2760935.32      6787454.34
      2761017.82      6787367.06      2761032.10      6787308.81
      2761071.85      6787259.28      2761082.16      6787208.80
      2761124.20      6787154.89      2761122.63      6787112.74
      2761084.14      6787067.05      2761077.29      6787051.30
      2761079.67      6786962.58      2761119.85      6786913.17
      2761128.49      6786867.03      2761136.76      6786851.32
      2761317.84      6786667.05      2761334.16      6786604.95
      2761422.71      6786509.64      2761426.00      6786461.00

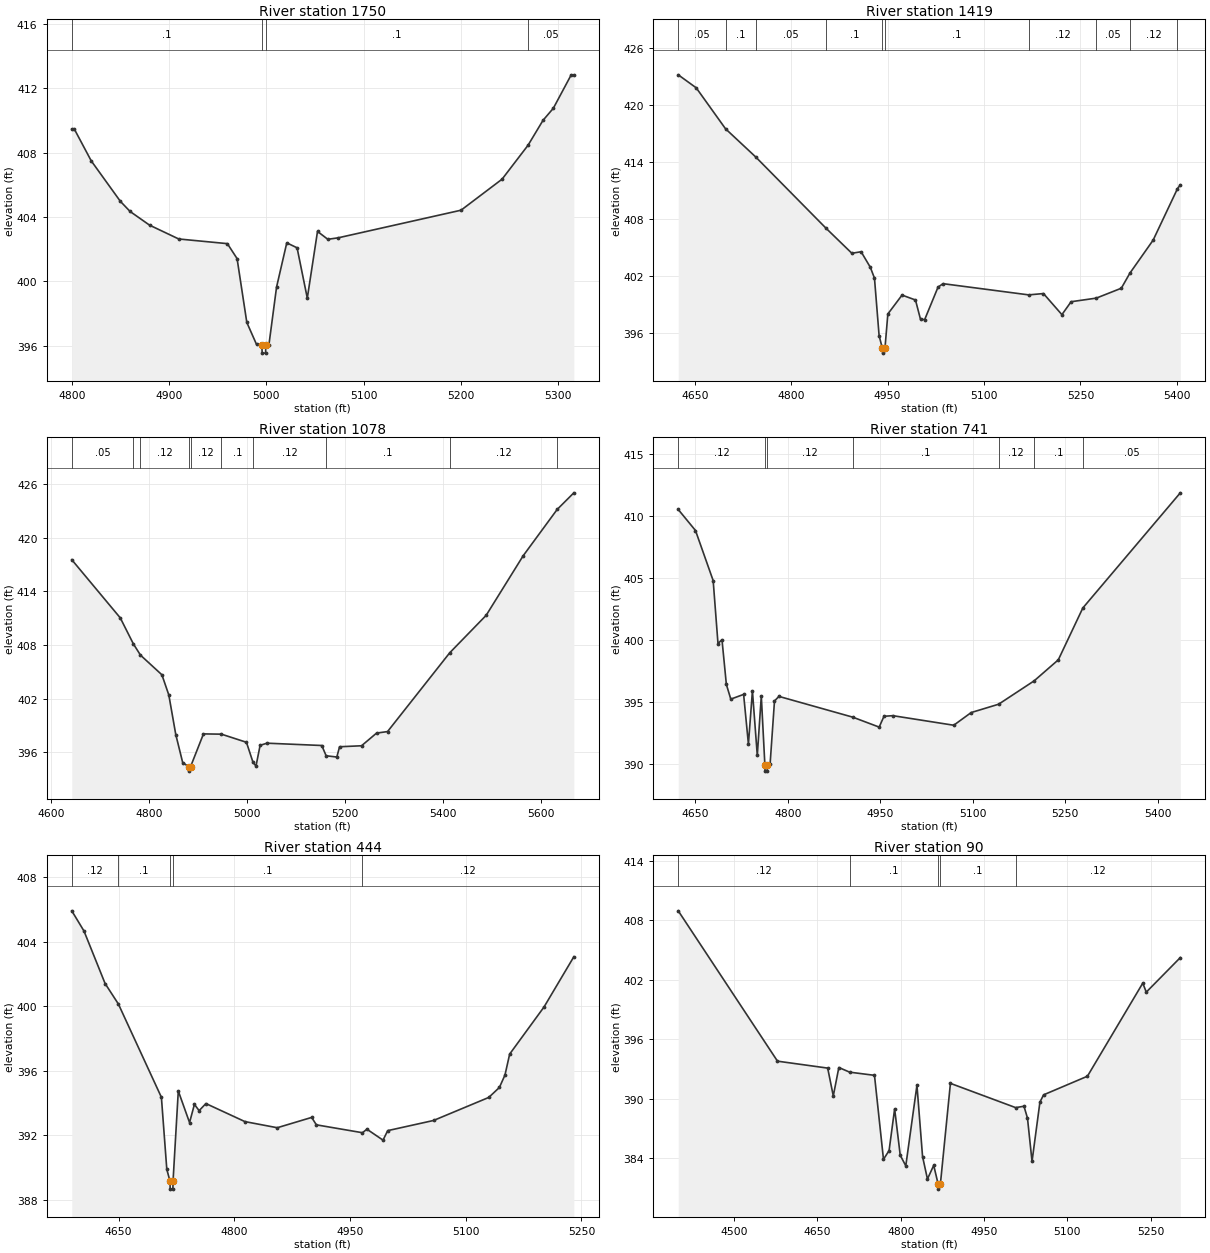
Type RM Length L Ch R = 1,1750,331,331,331
BEGIN DESCRIPTION:
Caney Creek T 24 5.0
END DESCRIPTION:
XS GIS Cut Line= 3
      2760926.03      6787861.00      2760726.00      6787861.00
      2760425.96      6787760.99
#Sta/Elev= 30
  4799.9  409.49  4802.4  409.49  4819.9  407.50  4849.9  404.98  4859.9  404.35
  4879.9  403.50  4909.9  402.64  4959.9  402.35  4969.9  401.42  4979.9  397.45
  4989.9  396.08  4995.4  396.04  4995.7  395.54  4999.2  395.54  4999.4  396.04
  5002.6  396.04  5010.5  399.65  5021.0  402.40  5031.6  402.09  5042.1  398.96
  5052.6  403.11  5063.2  402.62  5073.7  402.71  5200.2  404.43  5242.4  406.36
  5269.1  408.47  5284.5  410.02  5295.1  410.77  5313.5  412.85  5316.2  412.85
#Mann=4,-1,0
  4799.9     0.1       0  4995.4    0.07       0  4999.4     0.1       0
  5269.1    0.05       0
Bank Sta=4995.4,4999.4
Exp/Cntr=0.3,0.1

Type RM Length L Ch R = 1,1419,341,341,341
BEGIN DESCRIPTION:
Caney Creek T 24 4.0
END DESCRIPTION:
XS GIS Cut Line= 3
      2761176.03      6787861.03      2760876.00      6787611.00
      2760575.98      6787360.98
#Sta/Elev= 30
  4624.3  423.16  4652.3  421.79  4697.9  417.48  4744.6  414.53  4854.6  406.99
  4894.4  404.38  4908.8  404.54  4923.1  402.91  4929.6  401.76  4936.8  395.71
  4941.9  394.37  4942.2  393.87  4945.9  394.37  4950.4  397.99  4972.5  399.98
  4993.4  399.46  5001.2  397.43  5007.7  397.40  5028.5  400.82  5036.3  401.18
  5169.5  400.00  5192.5  400.14  5221.2  397.92  5235.5  399.28  5274.7  399.66
  5313.6  400.70  5327.0  402.29  5363.1  405.76  5401.0  411.18  5405.4  411.58
#Mann=10,-1,0
  4624.3    0.05       0  4697.9     0.1       0  4744.6    0.05       0
  4854.6     0.1       0  4941.9    0.07       0  4945.9     0.1       0
  5169.5    0.12       0  5274.7    0.05       0  5327.0    0.12       0
  5401.0    0.05       0
Bank Sta=4941.9,4945.9
Exp/Cntr=0.3,0.1

Type RM Length L Ch R = 1,1078,337,337,337
BEGIN DESCRIPTION:
Caney Creek T 24 3.0
END DESCRIPTION:
XS GIS Cut Line= 3
      2761276.01      6787611.01      2761026.00      6787361.00
      2760425.99      6787061.00
#Sta/Elev= 30
  4642.1  417.55  4741.1  411.03  4767.7  408.13  4782.3  406.86  4826.0  404.66
  4840.1  402.40  4854.3  397.97  4868.4  394.83  4880.5  394.37  4880.8  393.87
  4884.5  394.37  4910.8  398.04  4947.5  398.01  4998.5  397.10  5012.0  394.84
  5018.0  394.44  5026.4  396.76  5040.4  397.00  5152.2  396.74  5161.1  395.59
  5182.9  395.45  5188.5  396.60  5233.3  396.71  5264.0  398.13  5286.4  398.30
  5413.2  407.12  5487.6  411.32  5563.1  417.99  5632.5  423.18  5666.5  425.04
#Mann=10,-1,0
  4642.1    0.05       0  4767.7     0.1       0  4782.3    0.12       0
  4880.5    0.07       0  4884.5    0.12       0  4947.5     0.1       0
  5012.0    0.12       0  5161.1     0.1       0  5413.2    0.12       0
  5632.5    0.05       0
Bank Sta=4880.5,4884.5
Exp/Cntr=0.3,0.1

Type RM Length L Ch R = 1,741,297,297,297
BEGIN DESCRIPTION:
Caney Creek T 24 2.0
END DESCRIPTION:
XS GIS Cut Line= 3
      2761376.03      6787311.02      2761076.00      6787061.00
      2760776.01      6786761.01
#Sta/Elev= 30
  4622.0  410.50  4650.0  408.81  4678.7  404.78  4686.5  399.72  4693.0  400.03
  4700.1  396.43  4707.3  395.25  4728.1  395.63  4735.9  391.63  4742.4  395.91
  4750.3  390.72  4756.8  395.50  4762.6  389.96  4762.8  389.46  4766.3  389.46
  4766.6  389.96  4771.1  390.04  4778.2  395.10  4785.4  395.47  4905.2  393.80
  4948.1  393.00  4955.9  393.87  4970.2  393.92  5069.1  393.15  5097.4  394.17
  5141.9  394.84  5199.6  396.72  5238.8  398.41  5278.6  402.58  5436.8  411.84
#Mann=7,-1,0
  4622.0    0.12       0  4762.6    0.07       0  4766.6    0.12       0
  4905.2     0.1       0  5141.9    0.12       0  5199.6     0.1       0
  5278.6    0.05       0
Bank Sta=4762.6,4766.6
Exp/Cntr=0.3,0.1

Type RM Length L Ch R = 1,444,354,354,354
BEGIN DESCRIPTION:
Mapping XS 78156a97
END DESCRIPTION:
XS GIS Cut Line= 2
      2761411.81      6787146.46      2761040.69      6786611.73
#Sta/Elev= 30
  4589.3  405.93  4605.1  404.68  4632.5  401.42  4649.7  400.15  4705.5  394.36
  4712.5  389.89  4716.6  389.16  4716.9  388.66  4720.4  388.66  4720.6  389.16
  4727.4  394.75  4742.0  392.79  4748.3  393.92  4754.4  393.53  4763.2  393.97
  4813.8  392.85  4855.7  392.47  4900.3  393.11  4906.4  392.65  4966.2  392.16
  4971.9  392.38  4992.8  391.70  4998.9  392.29  5058.3  392.92  5129.9  394.35
  5143.7  394.97  5150.9  395.74  5157.0  397.04  5201.5  399.96  5240.2  403.08
#Mann=5,-1,0
  4589.3    0.12       0  4649.7     0.1       0  4716.6    0.07       0
  4720.6     0.1       0  4966.2    0.12       0
Bank Sta=4716.6,4720.6
Exp/Cntr=0.3,0.1

Type RM Length L Ch R = 1,90,0,0,0
BEGIN DESCRIPTION:
Caney Creek T 24 1.0
END DESCRIPTION:
XS GIS Cut Line= 3
      2761456.14      6787138.90      2761396.23      6786541.09
      2761155.17      6786356.53
#Sta/Elev= 30
  4399.2  408.97  4578.0  393.79  4668.4  393.09  4678.5  390.28  4688.5  393.15
  4708.0  392.68  4752.7  392.36  4768.9  383.88  4779.0  384.76  4789.0  388.97
  4799.1  384.29  4809.1  383.22  4829.2  391.36  4839.3  384.16  4848.1  381.89
  4859.4  383.27  4867.4  381.37  4867.7  380.87  4871.4  381.37  4889.5  391.55
  5007.0  389.10  5022.0  389.24  5028.3  388.04  5036.5  383.67  5050.7  389.65
  5057.3  390.39  5136.3  392.27  5236.0  401.67  5242.3  400.76  5303.6  404.25
#Mann=5,-1,0
  4399.2    0.12       0  4708.0     0.1       0  4867.4    0.07       0
  4871.4     0.1       0  5007.0    0.12       0
Bank Sta=4867.4,4871.4
Exp/Cntr=0.3,0.1

Chan Stop Cuts=-1