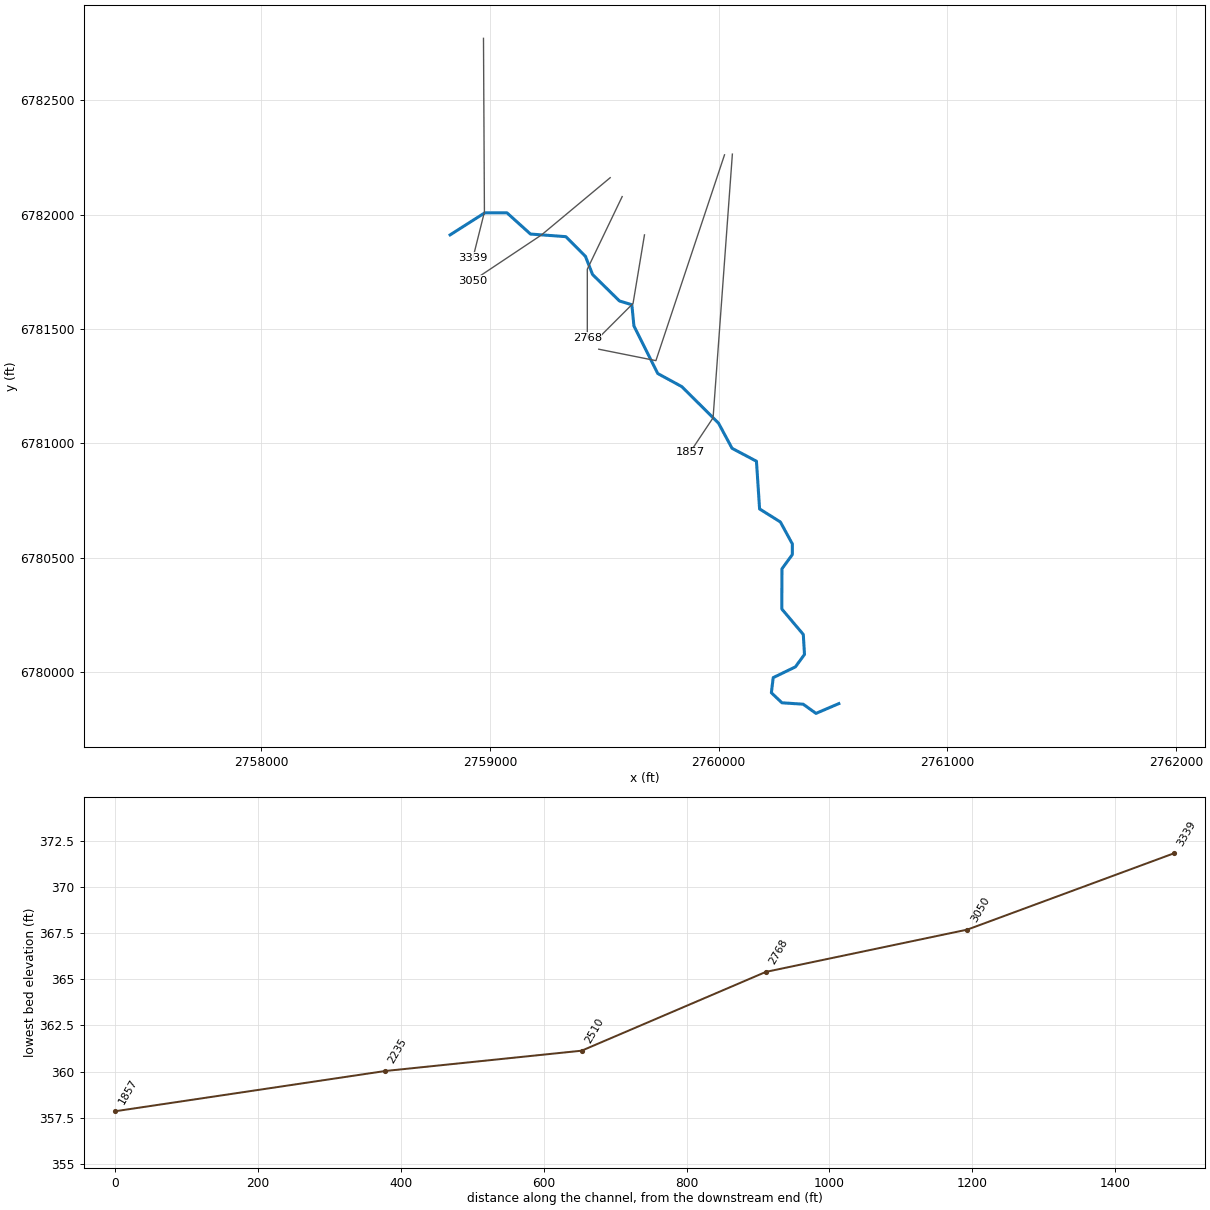
--- Caney Creek T 25.prj (project) ---

Proj Title=Caney Creek T 25 Base Level Engineering
Current Plan=p01
Default Exp/Contr=0.3,0.1
English Units
Geom File=g01
Flow File=f01
Plan File=p01
BEGIN DESCRIPTION:
Caney Creek T 25
END DESCRIPTION:

--- Caney Creek T 25.p01 (plan) ---

Plan Title=Multiple Run
Short Identifier=Multiple
Geom File=g01
Flow File=f01
Subcritical Flow
K Sum by GR= 0
Std Step Tol= 0.01
Critical Tol= 0.01
Num of Std Step Trials= 20
Max Error Tol= 0.3
Flow Tol Ratio= 0.001
Split Flow NTrial= 30
Split Flow Tol= 0.02
Split Flow Ratio= 0.02
Log Output Level= 0
Friction Slope Method= 1
Unsteady Friction Slope Method= 2
Unsteady Bridges Friction Slope Method= 1
Parabolic Critical Depth
Global Vel Dist=  1 , 1 , 1
Global Log Level= 0
CheckData=True
Encroach Param= -1, 0, 0, 0
BEGIN DESCRIPTION:
Multiple Run
END DESCRIPTION:

--- Caney Creek T 25.f01 (steady flow) ---

Flow Title=Multiple
Number of Profiles=7
Profile Names=10-year,25-year,50-year,1pct_min,100-year,1pct_plu,500-year
River Rch & RM= Caney Creek T 25,Reach-1,3339
     416     549     656     390     778    1551    1095
Boundary for River Rch & Prof#=Caney Creek T 25,Reach-1,1
Up Type=0
Dn Type=3
Dn Slope=0.005
Boundary for River Rch & Prof#=Caney Creek T 25,Reach-1,2
Up Type=0
Dn Type=3
Dn Slope=0.005
Boundary for River Rch & Prof#=Caney Creek T 25,Reach-1,3
Up Type=0
Dn Type=3
Dn Slope=0.005
Boundary for River Rch & Prof#=Caney Creek T 25,Reach-1,4
Up Type=0
Dn Type=3
Dn Slope=0.005
Boundary for River Rch & Prof#=Caney Creek T 25,Reach-1,5
Up Type=0
Dn Type=3
Dn Slope=0.005
Boundary for River Rch & Prof#=Caney Creek T 25,Reach-1,6
Up Type=0
Dn Type=3
Dn Slope=0.005
Boundary for River Rch & Prof#=Caney Creek T 25,Reach-1,7
Up Type=0
Dn Type=3
Dn Slope=0.005

--- Caney Creek T 25.g01 (geometry) ---

Geom Title=Existing Conditions

River Reach=Caney Creek T 25,Reach-1
Reach XY= 30
      2758826.00      6781911.00      2758977.58      6782007.34
      2759074.50      6782007.53      2759177.47      6781914.56
      2759332.21      6781903.19      2759417.85      6781817.07
      2759449.01      6781737.53      2759566.62      6781621.90
      2759620.74      6781605.53      2759629.86      6781512.66
      2759734.02      6781304.66      2759839.20      6781247.36
      2759999.70      6781087.82      2760058.96      6780977.50
      2760165.65      6780921.12      2760179.48      6780712.26
      2760270.38      6780655.38      2760322.67      6780559.31
      2760322.63      6780512.74      2760277.24      6780450.50
      2760276.54      6780274.86      2760370.59      6780163.42
      2760375.82      6780076.09      2760336.04      6780021.63
      2760238.96      6779974.55      2760230.94      6779908.45
      2760277.22      6779864.52      2760370.10      6779858.46
      2760426.04      6779818.31      2760526.00      6779861.00

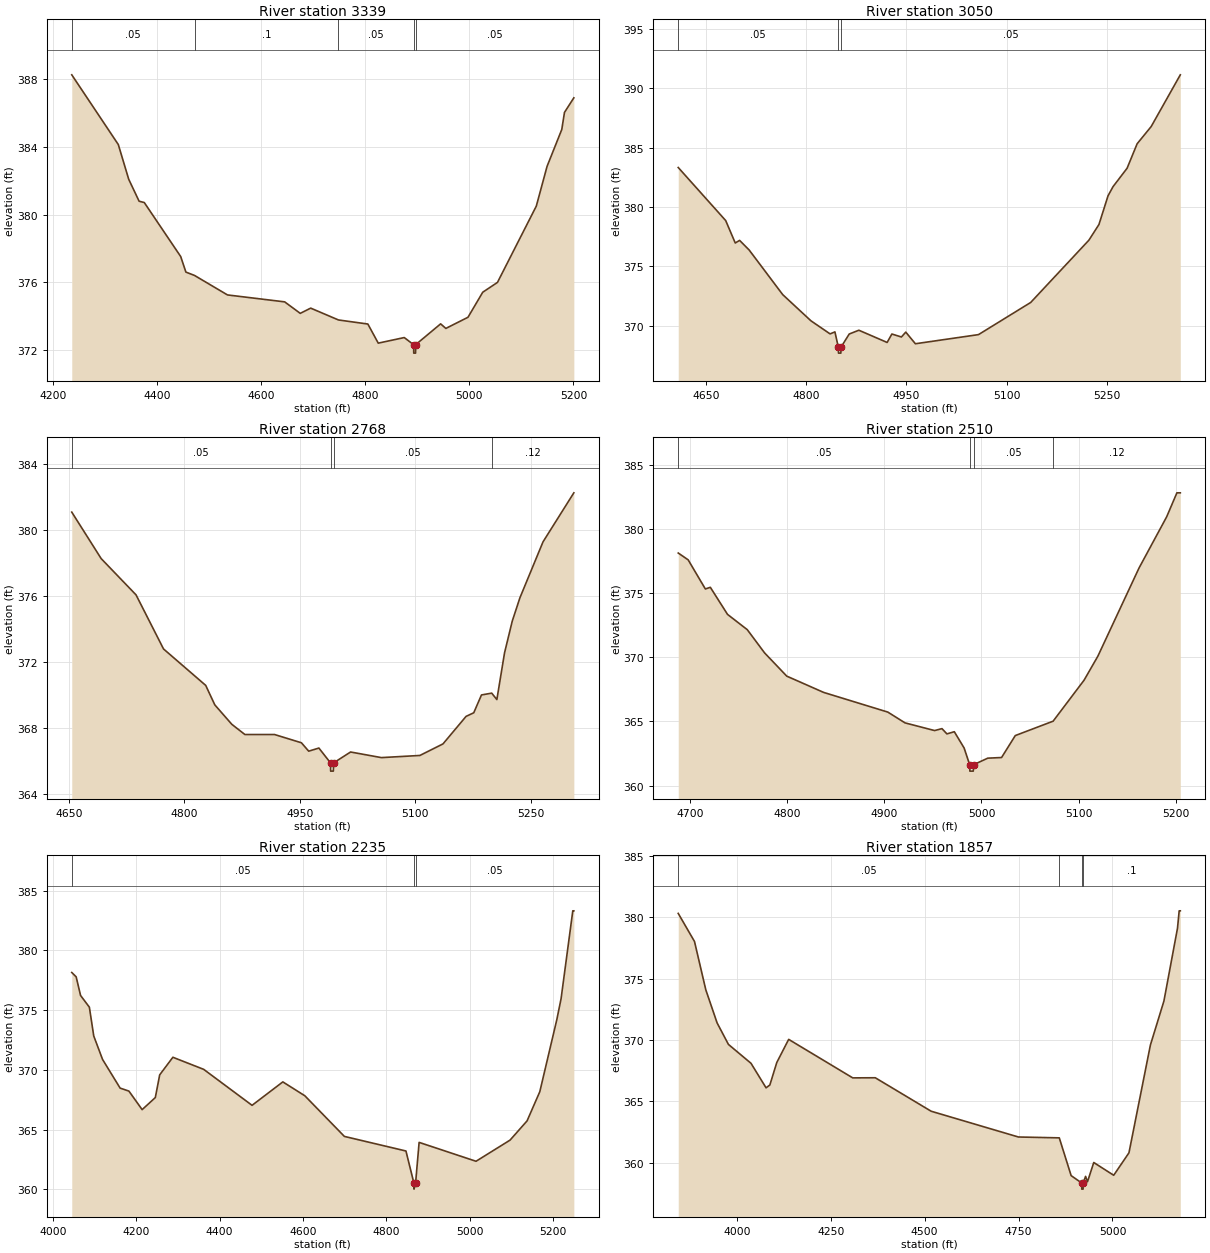
Type RM Length L Ch R = 1,3339,289,289,289
BEGIN DESCRIPTION:
Caney Creek T 25 6.0
END DESCRIPTION:
XS GIS Cut Line= 3
      2758971.93      6782770.53      2758976.00      6782011.00
      2758926.00      6781811.00
#Sta/Elev= 30
  4235.2  388.27  4324.7  384.15  4344.7  382.10  4364.7  380.80  4374.7  380.72
  4444.7  377.53  4454.7  376.61  4471.4  376.41  4534.7  375.26  4644.7  374.85
  4674.7  374.17  4694.7  374.48  4748.2  373.78  4804.7  373.54  4824.7  372.41
  4874.7  372.74  4892.7  372.32  4893.0  371.82  4896.5  371.82  4896.7  372.32
  4944.7  373.55  4954.7  373.28  4997.3  373.94  5025.7  375.42  5054.0  376.00
  5128.7  380.51  5149.4  382.86  5177.7  385.04  5182.9  386.05  5200.9  386.91
#Mann=5,-1,0
  4235.2    0.05       0  4471.4     0.1       0  4748.2    0.05       0
  4892.7    0.04       0  4896.7    0.05       0
Bank Sta=4892.7,4896.7
Exp/Cntr=0.3,0.1

Type RM Length L Ch R = 1,3050,282,282,282
BEGIN DESCRIPTION:
Caney Creek T 25 5.0
END DESCRIPTION:
XS GIS Cut Line= 3
      2759526.04      6782161.03      2759226.00      6781911.00
      2758926.01      6781711.01
#Sta/Elev= 30
  4608.8  383.33  4679.8  378.86  4694.1  376.97  4700.6  377.19  4714.9  376.38
  4765.1  372.62  4807.4  370.41  4836.0  369.31  4843.2  369.48  4848.3  368.19
  4848.6  367.69  4852.1  367.69  4852.3  368.19  4864.6  369.30  4879.0  369.62
  4921.3  368.59  4928.4  369.30  4942.7  369.05  4949.2  369.46  4963.6  368.48
  5058.0  369.25  5136.1  371.96  5223.2  377.21  5238.2  378.53  5251.8  380.95
  5259.3  381.72  5280.3  383.27  5295.3  385.33  5316.3  386.78  5359.9  391.14
#Mann=3,-1,0
  4608.8    0.05       0  4848.3    0.04       0  4852.3    0.05       0
Bank Sta=4848.3,4852.3
Exp/Cntr=0.3,0.1

Type RM Length L Ch R = 1,2768,258,258,258
BEGIN DESCRIPTION:
Caney Creek T 25 4.0
END DESCRIPTION:
XS GIS Cut Line= 3
      2759578.49      6782078.44      2759426.00      6781761.00
      2759426.00      6781460.97
#Sta/Elev= 30
  4654.0  381.11  4692.2  378.29  4737.5  376.09  4773.2  372.81  4828.0  370.60
  4839.8  369.42  4861.9  368.24  4878.9  367.62  4917.4  367.62  4952.3  367.12
  4961.8  366.61  4975.0  366.80  4990.1  365.90  4990.3  365.40  4993.8  365.40
  4994.1  365.90  5016.2  366.56  5056.2  366.22  5106.2  366.35  5136.2  367.05
  5166.2  368.72  5176.2  368.94  5186.2  370.02  5199.5  370.13  5206.2  369.74
  5216.2  372.58  5226.2  374.50  5236.2  375.92  5266.2  379.31  5306.2  382.28
#Mann=4,-1,0
  4654.0    0.05       0  4990.1    0.04       0  4994.1    0.05       0
  5199.5    0.12       0
Bank Sta=4990.1,4994.1
Exp/Cntr=0.3,0.1

Type RM Length L Ch R = 1,2510,275,275,275
BEGIN DESCRIPTION:
Caney Creek T 25 3.0
END DESCRIPTION:
XS GIS Cut Line= 3
      2759676.01      6781911.05      2759626.00      6781611.00
      2759476.01      6781461.01
#Sta/Elev= 30
  4688.2  378.12  4698.4  377.59  4716.1  375.32  4721.2  375.45  4738.9  373.34
  4759.2  372.15  4777.0  370.34  4799.8  368.53  4837.8  367.26  4903.7  365.73
  4921.4  364.89  4951.8  364.29  4959.4  364.44  4964.5  364.03  4972.1  364.20
  4982.2  362.93  4987.9  361.63  4988.1  361.13  4991.6  361.13  4991.9  361.63
  5006.5  362.14  5020.7  362.19  5034.8  363.90  5073.7  365.02  5105.5  368.21
  5119.7  370.08  5162.1  376.96  5190.4  380.93  5201.0  382.81  5204.5  382.81
#Mann=4,-1,0
  4688.2    0.05       0  4987.9    0.04       0  4991.9    0.05       0
  5073.7    0.12       0
Bank Sta=4987.9,4991.9
Exp/Cntr=0.3,0.1

Type RM Length L Ch R = 1,2235,378,378,378
BEGIN DESCRIPTION:
Caney Creek T 25 2.0
END DESCRIPTION:
XS GIS Cut Line= 3
      2760026.00      6782261.00      2759726.00      6781361.00
      2759476.03      6781410.99
#Sta/Elev= 30
  4045.6  378.15  4056.1  377.79  4066.7  376.23  4087.8  375.25  4098.3  372.84
  4119.4  370.88  4161.5  368.48  4182.6  368.23  4214.3  366.68  4245.9  367.69
  4256.4  369.59  4288.0  371.06  4361.8  370.05  4477.8  367.04  4551.6  369.00
  4604.3  367.84  4699.1  364.44  4846.7  363.22  4865.8  360.53  4866.0  360.03
  4869.8  360.53  4878.3  363.94  5014.7  362.36  5096.3  364.13  5137.1  365.74
  5167.6  368.18  5208.4  374.21  5218.6  375.96  5246.7  383.31  5249.2  383.31
#Mann=3,-1,0
  4045.6    0.05       0  4865.8    0.04       0  4869.8    0.05       0
Bank Sta=4865.8,4869.8
Exp/Cntr=0.3,0.1

Type RM Length L Ch R = 1,1857,0,0,0
BEGIN DESCRIPTION:
Caney Creek T 25 1.0
END DESCRIPTION:
XS GIS Cut Line= 3
      2760060.39      6782264.22      2759976.00      6781111.00
      2759875.99      6780960.98
#Sta/Elev= 30
  3844.0  380.33  3887.3  378.04  3917.4  374.10  3947.5  371.40  3977.6  369.65
  4037.7  368.11  4077.8  366.11  4087.9  366.34  4106.3  368.17  4138.0  370.06
  4308.5  366.92  4368.6  366.93  4517.4  364.20  4749.6  362.10  4858.4  362.03
  4890.0  358.95  4918.1  358.35  4918.3  357.85  4921.8  357.85  4922.1  358.35
  4928.4  358.89  4933.5  358.45  4950.2  360.02  5003.3  358.98  5043.9  360.81
  5101.0  369.60  5137.0  373.19  5173.1  379.12  5177.6  380.54  5180.6  380.54
#Mann=4,-1,0
  3844.0    0.05       0  4858.4     0.1       0  4918.1    0.07       0
  4922.1     0.1       0
Bank Sta=4918.1,4922.1
Exp/Cntr=0.3,0.1

Chan Stop Cuts=-1