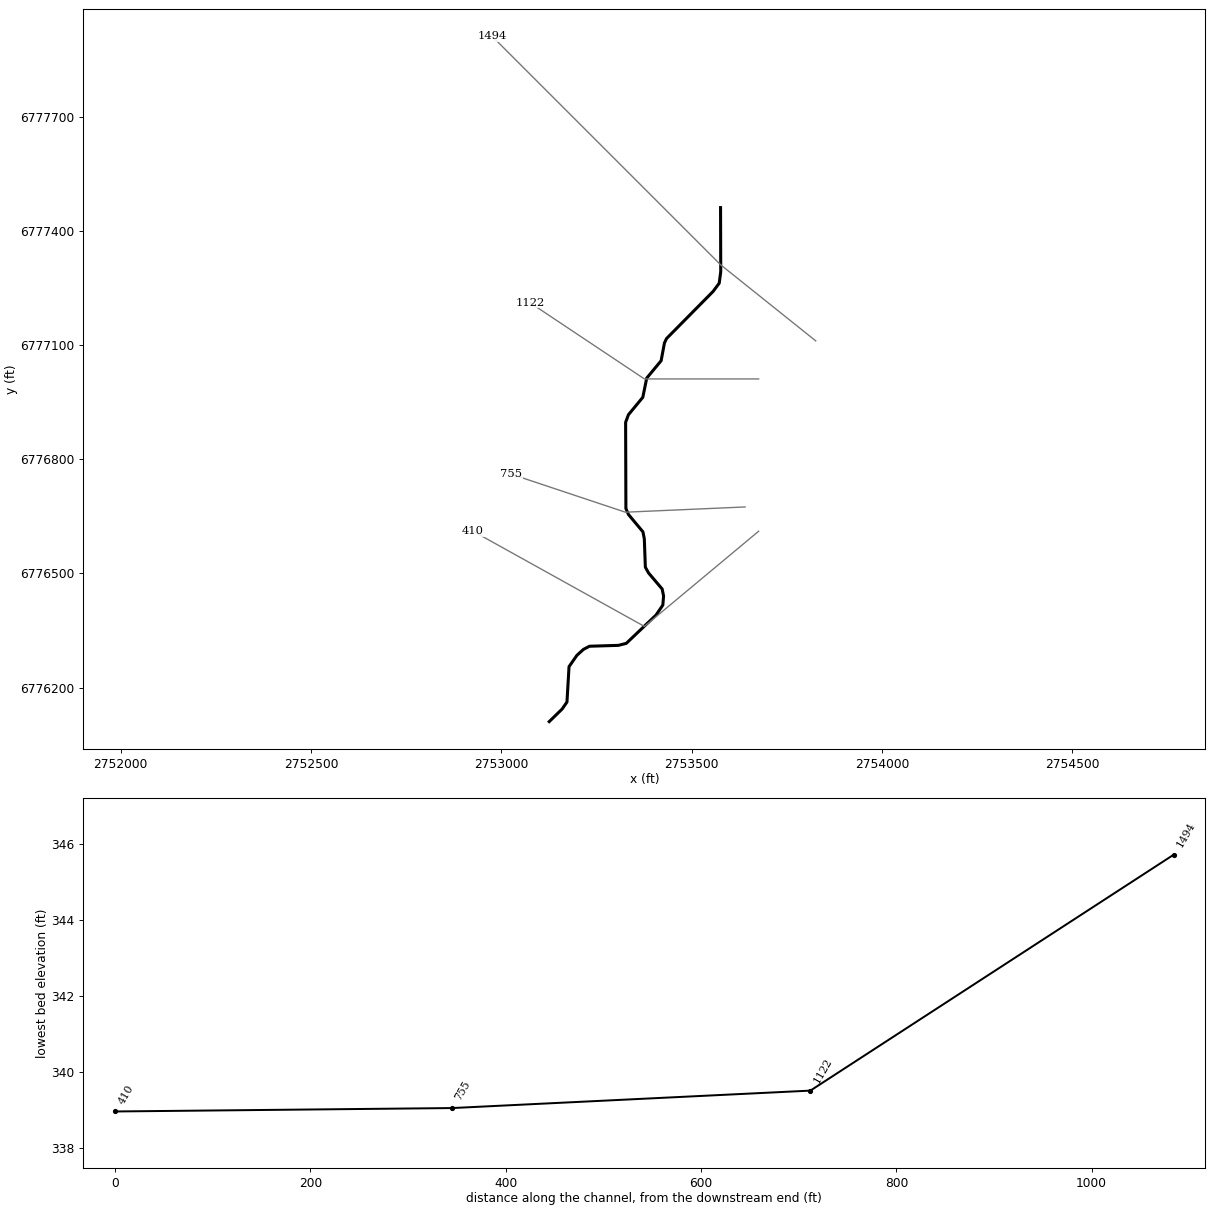
--- Caney Creek T 26.prj (project) ---

Proj Title=Caney Creek T 26 Base Level Engineering
Current Plan=p01
Default Exp/Contr=0.3,0.1
English Units
Geom File=g01
Flow File=f01
Plan File=p01
BEGIN DESCRIPTION:
Caney Creek T 26
END DESCRIPTION:

--- Caney Creek T 26.p01 (plan) ---

Plan Title=Multiple Run
Short Identifier=Multiple
Geom File=g01
Flow File=f01
Subcritical Flow
K Sum by GR= 0
Std Step Tol= 0.01
Critical Tol= 0.01
Num of Std Step Trials= 20
Max Error Tol= 0.3
Flow Tol Ratio= 0.001
Split Flow NTrial= 30
Split Flow Tol= 0.02
Split Flow Ratio= 0.02
Log Output Level= 0
Friction Slope Method= 1
Unsteady Friction Slope Method= 2
Unsteady Bridges Friction Slope Method= 1
Parabolic Critical Depth
Global Vel Dist=  1 , 1 , 1
Global Log Level= 0
CheckData=True
Encroach Param= -1, 0, 0, 0
BEGIN DESCRIPTION:
Multiple Run
END DESCRIPTION:

--- Caney Creek T 26.f01 (steady flow) ---

Flow Title=Multiple
Number of Profiles=7
Profile Names=10-year,25-year,50-year,1pct_min,100-year,1pct_plu,500-year
River Rch & RM= Caney Creek T 26,Reach-1,1494
     360     470     558     329     657    1311     913
Boundary for River Rch & Prof#=Caney Creek T 26,Reach-1,1
Up Type=0
Dn Type=3
Dn Slope=0.005
Boundary for River Rch & Prof#=Caney Creek T 26,Reach-1,2
Up Type=0
Dn Type=3
Dn Slope=0.005
Boundary for River Rch & Prof#=Caney Creek T 26,Reach-1,3
Up Type=0
Dn Type=3
Dn Slope=0.005
Boundary for River Rch & Prof#=Caney Creek T 26,Reach-1,4
Up Type=0
Dn Type=3
Dn Slope=0.005
Boundary for River Rch & Prof#=Caney Creek T 26,Reach-1,5
Up Type=0
Dn Type=3
Dn Slope=0.005
Boundary for River Rch & Prof#=Caney Creek T 26,Reach-1,6
Up Type=0
Dn Type=3
Dn Slope=0.005
Boundary for River Rch & Prof#=Caney Creek T 26,Reach-1,7
Up Type=0
Dn Type=3
Dn Slope=0.005

--- Caney Creek T 26.g01 (geometry) ---

Geom Title=Existing Conditions

River Reach=Caney Creek T 26,Reach-1
Reach XY= 30
      2753576.00      6777461.00      2753576.48      6777292.62
      2753572.47      6777262.46      2753556.40      6777240.84
      2753434.14      6777117.06      2753428.61      6777105.37
      2753419.90      6777058.81      2753382.08      6777013.20
      2753371.81      6776962.74      2753334.09      6776917.08
      2753326.67      6776897.09      2753327.38      6776670.66
      2753334.14      6776654.94      2753372.14      6776609.40
      2753375.76      6776590.90      2753378.50      6776516.56
      2753386.95      6776501.35      2753422.66      6776459.25
      2753426.36      6776440.79      2753424.39      6776417.02
      2753406.59      6776390.87      2753328.44      6776316.52
      2753307.71      6776311.25      2753231.69      6776308.93
      2753215.84      6776300.64      2753198.67      6776285.01
      2753178.03      6776255.33      2753172.61      6776162.41
      2753159.87      6776143.96      2753126.00      6776111.00

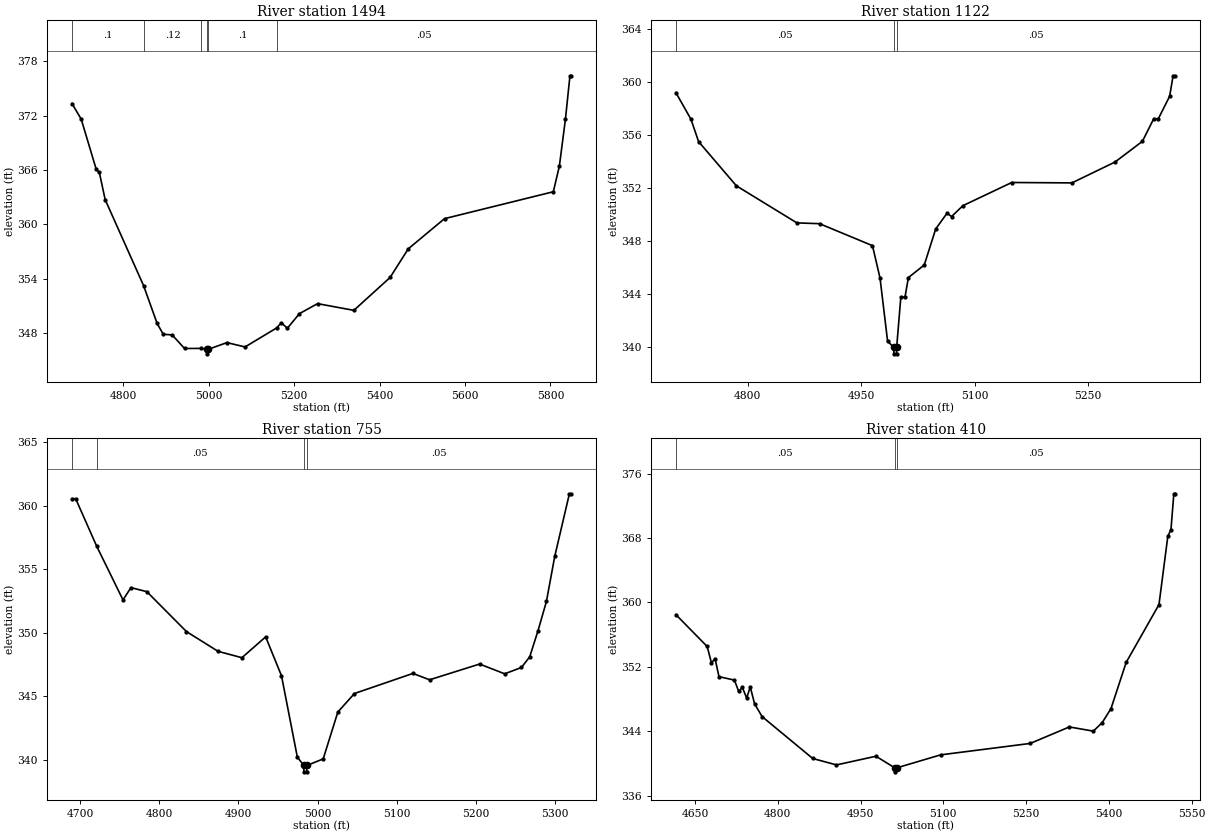
Type RM Length L Ch R = 1,1494,372,372,372
BEGIN DESCRIPTION:
Caney Creek T 26 4.0
END DESCRIPTION:
XS GIS Cut Line= 3
      2753826.02      6777110.98      2753576.00      6777311.00
      2752976.01      6777910.99
#Sta/Elev= 30
  4680.4  373.35  4702.0  371.63  4737.3  366.07  4744.5  365.74  4758.1  362.74
  4848.0  353.25  4879.7  349.07  4894.1  347.88  4914.9  347.81  4943.8  346.31
  4983.4  346.32  4995.4  346.22  4995.6  345.72  4999.4  346.22  5043.0  346.96
  5085.4  346.48  5159.4  348.58  5170.3  349.15  5184.4  348.54  5212.7  350.16
  5255.1  351.26  5340.0  350.52  5424.8  354.15  5467.3  357.31  5552.1  360.64
  5806.7  363.61  5820.8  366.43  5835.0  371.60  5845.6  376.41  5849.1  376.41
#Mann=6,-1,0
  4680.4     0.1       0  4848.0    0.12       0  4983.4     0.1       0
  4995.4    0.07       0  4999.4     0.1       0  5159.4    0.05       0
Bank Sta=4995.4,4999.4
Exp/Cntr=0.3,0.1

Type RM Length L Ch R = 1,1122,367,367,367
BEGIN DESCRIPTION:
Caney Creek T 26 3.0
END DESCRIPTION:
XS GIS Cut Line= 3
      2753676.00      6777011.00      2753376.00      6777011.00
      2753075.96      6777211.02
#Sta/Elev= 30
  4705.0  359.23  4725.0  357.21  4735.0  355.53  4785.0  352.19  4865.0  349.39
  4895.0  349.33  4965.0  347.67  4975.0  345.22  4985.0  340.45  4993.0  340.00
  4993.3  339.50  4996.8  339.50  4997.0  340.00  5002.5  343.78  5008.0  343.78
  5012.5  345.26  5033.5  346.21  5048.6  348.93  5063.6  350.12  5069.6  349.87
  5084.6  350.69  5149.2  352.44  5228.8  352.41  5285.9  353.99  5322.0  355.55
  5337.0  357.26  5343.0  357.25  5358.0  358.95  5362.6  360.50  5365.6  360.50
#Mann=3,-1,0
  4705.0    0.05       0  4993.0    0.04       0  4997.0    0.05       0
Bank Sta=4993,4997
Exp/Cntr=0.3,0.1

Type RM Length L Ch R = 1,755,345,345,345
BEGIN DESCRIPTION:
Caney Creek T 26 2.0
END DESCRIPTION:
XS GIS Cut Line= 3
      2753640.47      6776674.77      2753326.00      6776661.00
      2753026.00      6776761.00
#Sta/Elev= 30
  4689.7  360.55  4694.4  360.55  4721.1  356.79  4754.2  352.58  4764.2  353.55
  4784.3  353.23  4834.3  350.09  4874.3  348.53  4904.4  348.03  4934.4  349.67
  4954.4  346.61  4974.4  340.21  4982.5  339.54  4982.7  339.04  4986.2  339.04
  4986.5  339.54  5007.1  340.06  5025.6  343.75  5046.6  345.21  5120.4  346.79
  5141.5  346.29  5204.7  347.53  5236.4  346.76  5257.5  347.26  5268.0  348.10
  5278.5  350.16  5289.1  352.46  5299.6  356.01  5318.1  360.94  5320.7  360.94
#Mann=4,-1,0
  4689.7    0.12       0  4721.1    0.05       0  4982.5    0.04       0
  4986.5    0.05       0
Bank Sta=4982.5,4986.5
Exp/Cntr=0.3,0.1

Type RM Length L Ch R = 1,410,0,0,0
BEGIN DESCRIPTION:
Caney Creek T 26 1.0
END DESCRIPTION:
XS GIS Cut Line= 3
      2753676.03      6776611.03      2753376.00      6776361.00
      2752926.03      6776610.98
#Sta/Elev= 30
  4615.2  358.49  4671.9  354.53  4679.7  352.48  4686.2  353.03  4693.3  350.78
  4721.3  350.35  4729.1  348.94  4735.6  349.45  4743.5  348.12  4750.0  349.51
  4757.8  347.41  4771.4  345.82  4863.2  340.61  4906.2  339.81  4977.8  340.89
  5011.8  339.45  5012.0  338.95  5015.8  339.45  5095.0  341.06  5257.4  342.48
  5328.3  344.53  5371.8  344.01  5387.8  345.06  5403.8  346.81  5431.3  352.55
  5490.8  359.74  5506.8  368.22  5512.5  369.05  5517.7  373.51  5520.5  373.51
#Mann=3,-1,0
  4615.2    0.05       0  5011.8    0.03       0  5015.8    0.05       0
Bank Sta=5011.8,5015.8
Exp/Cntr=0.3,0.1

Chan Stop Cuts=-1