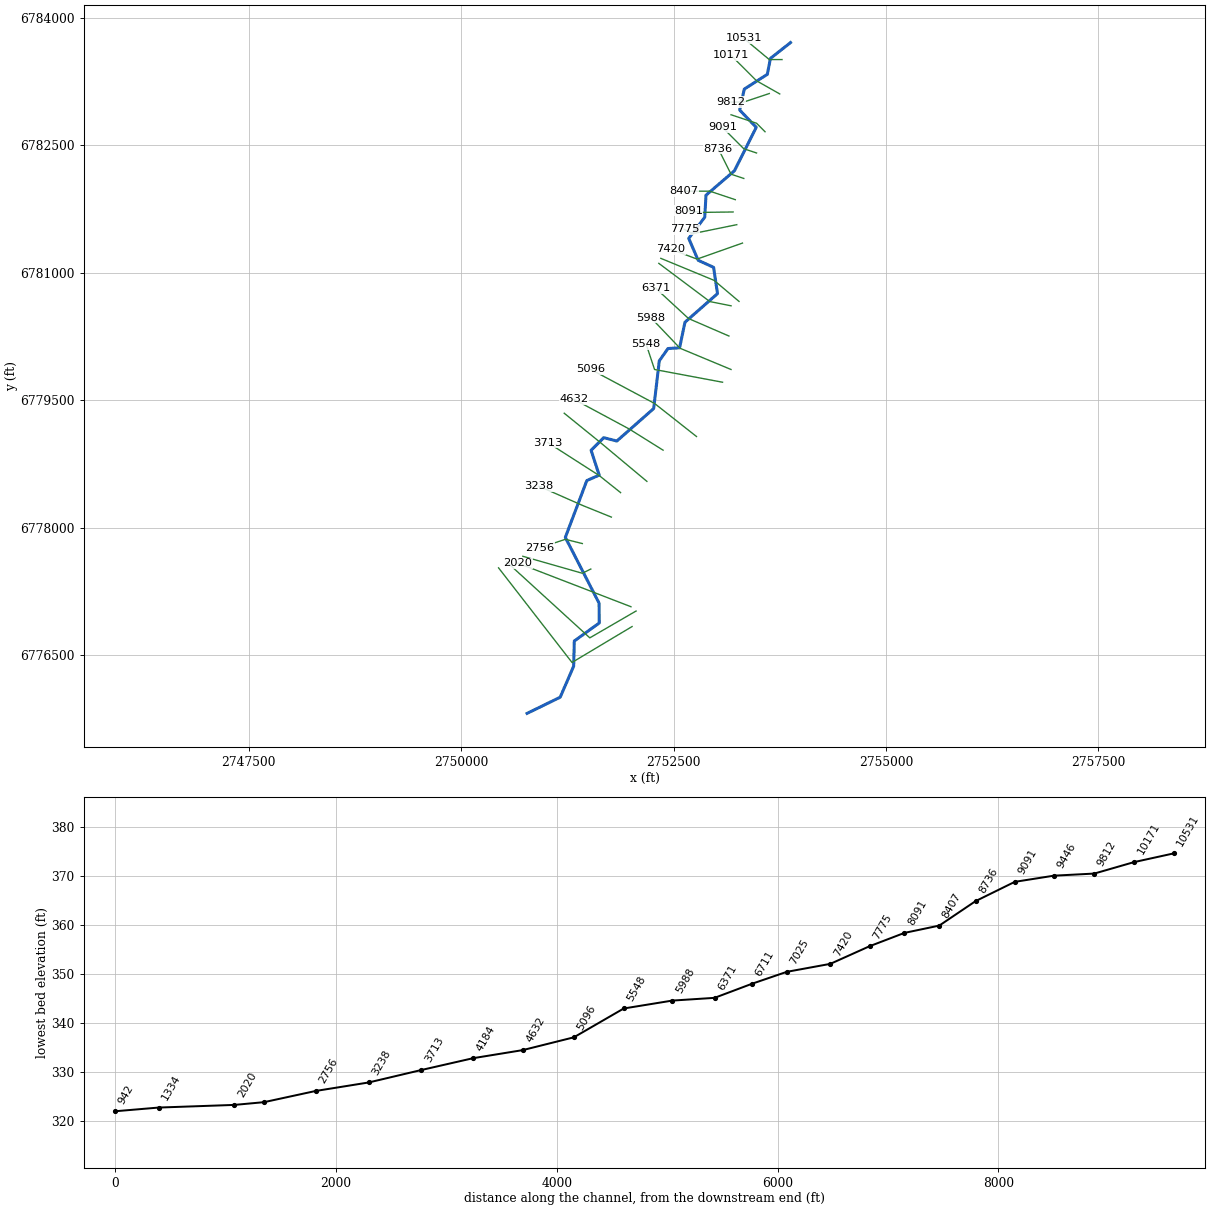
--- Caney Creek T 27.prj (project) ---

Proj Title=Caney Creek T 27 Base Level Engineering
Current Plan=p01
Default Exp/Contr=0.3,0.1
English Units
Geom File=g01
Flow File=f01
Plan File=p01
BEGIN DESCRIPTION:
Caney Creek T 27
END DESCRIPTION:

--- Caney Creek T 27.p01 (plan) ---

Plan Title=Multiple Run
Short Identifier=Multiple
Geom File=g01
Flow File=f01
Subcritical Flow
K Sum by GR= 0
Std Step Tol= 0.01
Critical Tol= 0.01
Num of Std Step Trials= 20
Max Error Tol= 0.3
Flow Tol Ratio= 0.001
Split Flow NTrial= 30
Split Flow Tol= 0.02
Split Flow Ratio= 0.02
Log Output Level= 0
Friction Slope Method= 1
Unsteady Friction Slope Method= 2
Unsteady Bridges Friction Slope Method= 1
Parabolic Critical Depth
Global Vel Dist=  1 , 1 , 1
Global Log Level= 0
CheckData=True
Encroach Param= -1, 0, 0, 0
BEGIN DESCRIPTION:
Multiple Run
END DESCRIPTION:

--- Caney Creek T 27.f01 (steady flow) ---

Flow Title=Multiple
Number of Profiles=7
Profile Names=10-year,25-year,50-year,1pct_min,100-year,1pct_plu,500-year
River Rch & RM= Caney Creek T 27,Reach-1,10531
     544     731     883     531    1059    2112    1525
River Rch & RM= Caney Creek T 27,Reach-1,5548
     842    1158    1421     866    1728    3447    2561
Boundary for River Rch & Prof#=Caney Creek T 27,Reach-1,1
Up Type=0
Dn Type=3
Dn Slope=0.005
Boundary for River Rch & Prof#=Caney Creek T 27,Reach-1,2
Up Type=0
Dn Type=3
Dn Slope=0.005
Boundary for River Rch & Prof#=Caney Creek T 27,Reach-1,3
Up Type=0
Dn Type=3
Dn Slope=0.005
Boundary for River Rch & Prof#=Caney Creek T 27,Reach-1,4
Up Type=0
Dn Type=3
Dn Slope=0.005
Boundary for River Rch & Prof#=Caney Creek T 27,Reach-1,5
Up Type=0
Dn Type=3
Dn Slope=0.005
Boundary for River Rch & Prof#=Caney Creek T 27,Reach-1,6
Up Type=0
Dn Type=3
Dn Slope=0.005
Boundary for River Rch & Prof#=Caney Creek T 27,Reach-1,7
Up Type=0
Dn Type=3
Dn Slope=0.005

--- Caney Creek T 27.g01 (geometry) ---

Geom Title=Existing Conditions

River Reach=Caney Creek T 27,Reach-1
Reach XY= 30
      2753876.00      6783711.00      2753639.63      6783524.36
      2753603.15      6783337.16      2753331.80      6783163.30
      2753277.69      6782916.46      2753472.89      6782712.65
      2753215.61      6782200.90      2752881.12      6781913.29
      2752866.70      6781654.33      2752677.88      6781405.28
      2752789.23      6781147.28      2752970.65      6781063.73
      2753016.71      6780754.33      2752633.69      6780417.48
      2752570.58      6780116.18      2752434.02      6780107.75
      2752331.82      6779963.28      2752265.61      6779400.90
      2751832.06      6779018.48      2751677.63      6779057.87
      2751529.13      6778909.37      2751624.47      6778616.83
      2751478.95      6778553.02      2751225.89      6777883.68
      2751622.86      6777109.36      2751625.62      6776875.63
      2751331.46      6776663.45      2751323.94      6776366.86
      2751165.53      6776001.18      2750776.00      6775811.00

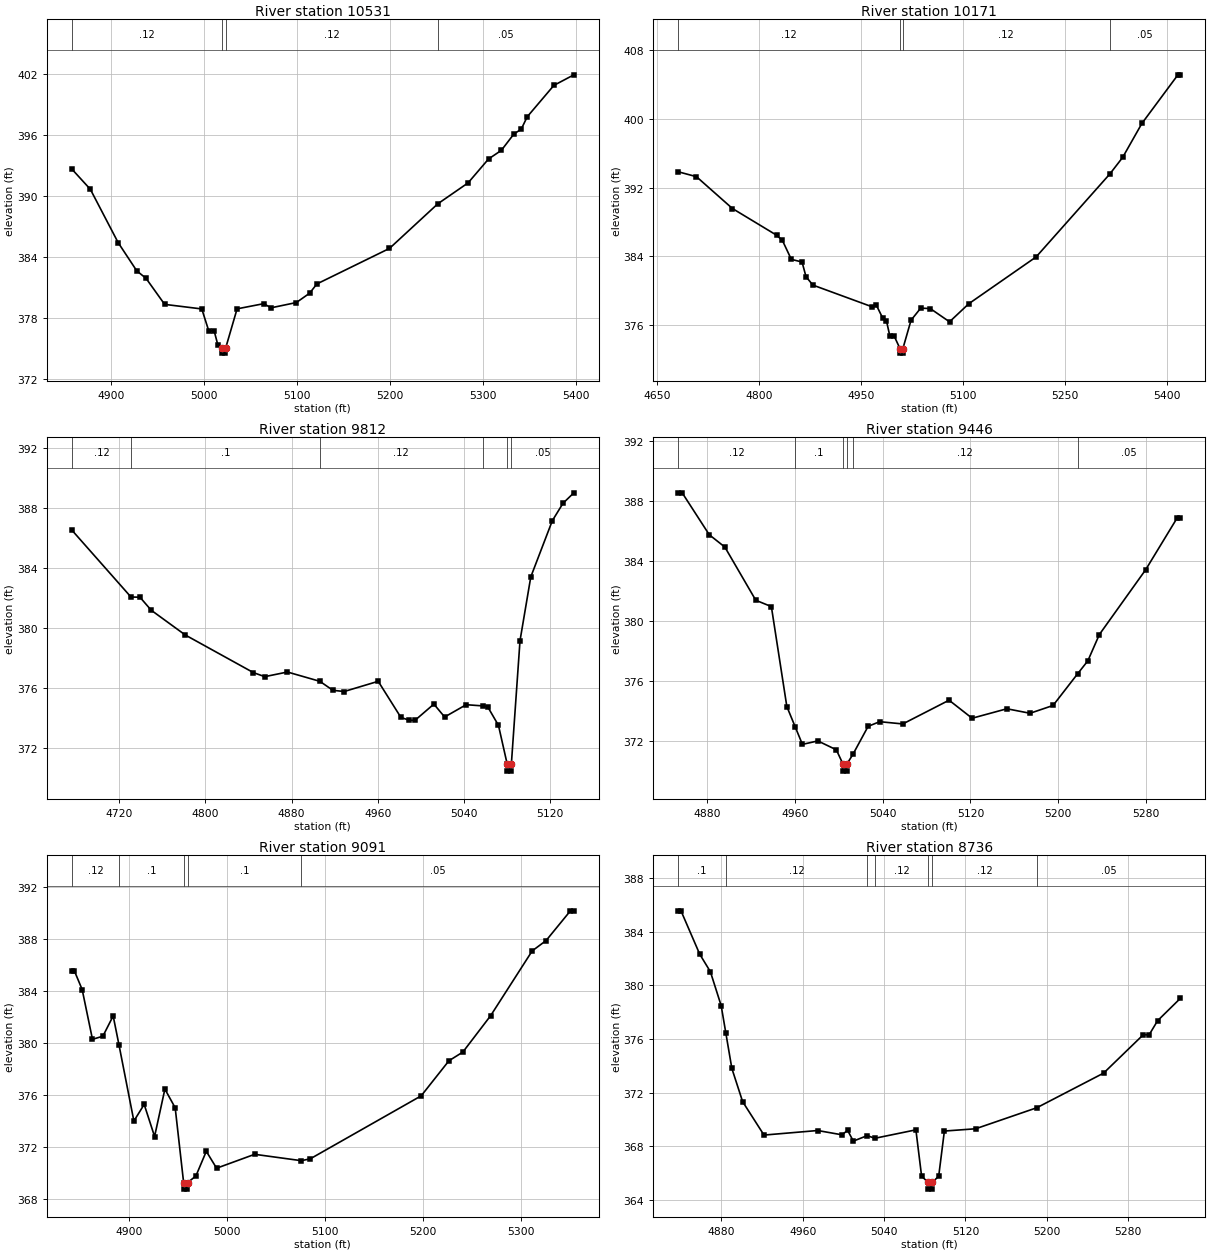
Type RM Length L Ch R = 1,10531,360,360,360
BEGIN DESCRIPTION:
Caney Creek T 27 23.0
END DESCRIPTION:
XS GIS Cut Line= 3
      2753776.05      6783511.00      2753626.00      6783511.00
      2753325.97      6783761.02
#Sta/Elev= 30
  4857.5  392.67  4877.5  390.67  4907.5  385.41  4927.5  382.64  4937.5  381.90
  4957.5  379.34  4997.5  378.89  5005.0  376.73  5010.8  376.73  5014.7  375.38
  5019.2  375.04  5019.5  374.54  5023.0  374.54  5023.2  375.04  5035.5  378.90
  5064.2  379.41  5072.0  379.00  5099.3  379.52  5113.6  380.44  5121.4  381.35
  5199.6  384.85  5251.6  389.24  5284.2  391.30  5306.3  393.66  5320.0  394.50
  5333.6  396.12  5341.4  396.58  5347.9  397.81  5376.6  400.90  5398.1  401.94
#Mann=4,-1,0
  4857.5    0.12       0  5019.2    0.07       0  5023.2    0.12       0
  5251.6    0.05       0
Bank Sta=5019.2,5023.2
Exp/Cntr=0.3,0.1

Type RM Length L Ch R = 1,10171,359,359,359
BEGIN DESCRIPTION:
Caney Creek T 27 22.0
END DESCRIPTION:
XS GIS Cut Line= 3
      2753749.33      6783106.12      2753476.00      6783261.00
      2753176.02      6783560.98
#Sta/Elev= 30
  4680.8  393.84  4707.6  393.27  4760.5  389.57  4825.4  386.47  4834.0  385.86
  4847.1  383.66  4862.9  383.35  4868.7  381.65  4878.8  380.67  4965.4  378.16
  4972.0  378.36  4981.3  376.87  4987.0  376.52  4992.1  374.72  4998.5  374.72
  5007.1  373.26  5007.4  372.76  5010.9  372.76  5011.1  373.26  5023.2  376.59
  5037.4  377.99  5051.5  377.94  5079.8  376.40  5108.1  378.50  5207.1  383.94
  5315.6  393.59  5334.4  395.51  5362.7  399.46  5415.7  405.11  5419.2  405.11
#Mann=4,-1,0
  4680.8    0.12       0  5007.1    0.07       0  5011.1    0.12       0
  5315.6    0.05       0
Bank Sta=5007.1,5011.1
Exp/Cntr=0.3,0.1

Type RM Length L Ch R = 1,9812,366,366,366
BEGIN DESCRIPTION:
Caney Creek T 27 21.0
END DESCRIPTION:
XS GIS Cut Line= 3
      2753626.03      6783111.01      2753326.00      6783011.00
      2753175.96      6783011.00
#Sta/Elev= 30
  4675.9  386.51  4730.9  382.04  4739.2  382.03  4749.7  381.16  4781.3  379.51
  4844.6  377.00  4855.1  376.73  4876.2  377.04  4906.3  376.42  4918.4  375.82
  4928.9  375.74  4960.5  376.42  4981.6  374.01  4989.5  373.82  4994.7  373.82
  5012.2  374.90  5022.2  374.04  5042.2  374.86  5057.6  374.78  5062.2  374.72
  5072.2  373.48  5080.2  370.93  5080.4  370.43  5083.9  370.43  5084.2  370.93
  5092.2  379.13  5102.2  383.38  5122.2  387.13  5132.2  388.30  5142.2  388.99
#Mann=6,-1,0
  4675.9    0.12       0  4730.9     0.1       0  4906.3    0.12       0
  5057.6    0.05       0  5080.2    0.07       0  5084.2    0.05       0
Bank Sta=5080.2,5084.2
Exp/Cntr=0.3,0.1

Type RM Length L Ch R = 1,9446,355,355,355
BEGIN DESCRIPTION:
Caney Creek T 27 20.0
END DESCRIPTION:
XS GIS Cut Line= 3
      2753576.03      6782660.97      2753476.00      6782761.00
      2753175.99      6782861.00
#Sta/Elev= 30
  4853.6  388.52  4857.2  388.52  4881.9  385.73  4896.1  384.91  4924.3  381.37
  4938.5  380.95  4952.6  374.30  4960.2  372.95  4966.8  371.78  4980.9  372.01
  4997.7  371.42  5003.6  370.50  5003.8  370.00  5007.3  370.00  5007.6  370.50
  5012.8  371.11  5026.7  372.98  5037.2  373.29  5058.3  373.14  5100.5  374.72
  5121.5  373.52  5153.2  374.15  5174.3  373.85  5195.3  374.37  5217.6  376.47
  5227.0  377.34  5237.5  379.09  5279.7  383.40  5308.6  386.87  5311.3  386.87
#Mann=6,-1,0
  4853.6    0.12       0  4960.2     0.1       0  5003.6    0.07       0
  5007.6     0.1       0  5012.8    0.12       0  5217.6    0.05       0
Bank Sta=5003.6,5007.6
Exp/Cntr=0.3,0.1

Type RM Length L Ch R = 1,9091,355,355,355
BEGIN DESCRIPTION:
Caney Creek T 27 19.0
END DESCRIPTION:
XS GIS Cut Line= 3
      2753476.04      6782410.99      2753326.00      6782461.00
      2753076.00      6782711.00
#Sta/Elev= 30
  4841.9  385.53  4844.6  385.53  4852.5  384.10  4863.0  380.27  4873.6  380.51
  4884.1  382.07  4890.1  379.81  4905.2  373.98  4915.7  375.26  4926.3  372.79
  4936.8  376.44  4947.3  375.00  4955.9  369.24  4956.1  368.74  4959.6  368.74
  4959.9  369.24  4968.4  369.75  4979.0  371.65  4989.5  370.35  5028.3  371.42
  5075.8  370.93  5084.9  371.07  5198.0  375.92  5226.3  378.62  5240.5  379.29
  5268.8  382.09  5311.2  387.08  5325.3  387.87  5350.1  390.16  5353.6  390.16
#Mann=5,-1,0
  4841.9    0.12       0  4890.1     0.1       0  4955.9    0.07       0
  4959.9     0.1       0  5075.8    0.05       0
Bank Sta=4955.9,4959.9
Exp/Cntr=0.3,0.1

Type RM Length L Ch R = 1,8736,329,329,329
BEGIN DESCRIPTION:
Caney Creek T 27 18.0
END DESCRIPTION:
XS GIS Cut Line= 3
      2753326.02      6782110.99      2753176.00      6782161.00
      2753026.02      6782460.96
#Sta/Elev= 30
  4837.7  385.56  4840.4  385.56  4858.8  382.33  4869.3  381.02  4879.9  378.49
  4884.5  376.44  4890.4  373.81  4901.0  371.33  4922.0  368.84  4974.8  369.18
  4998.6  368.86  5004.2  369.19  5009.8  368.39  5023.5  368.80  5030.9  368.60
  5071.3  369.23  5076.9  365.78  5083.3  365.31  5083.5  364.81  5087.0  364.81
  5087.3  365.31  5093.7  365.77  5099.3  369.14  5130.0  369.31  5190.2  370.88
  5255.8  373.46  5294.9  376.33  5300.5  376.31  5308.9  377.37  5331.2  379.03
#Mann=7,-1,0
  4837.7     0.1       0  4884.5    0.12       0  5023.5     0.1       0
  5030.9    0.12       0  5083.3    0.07       0  5087.3    0.12       0
  5190.2    0.05       0
Bank Sta=5083.3,5087.3
Exp/Cntr=0.3,0.1

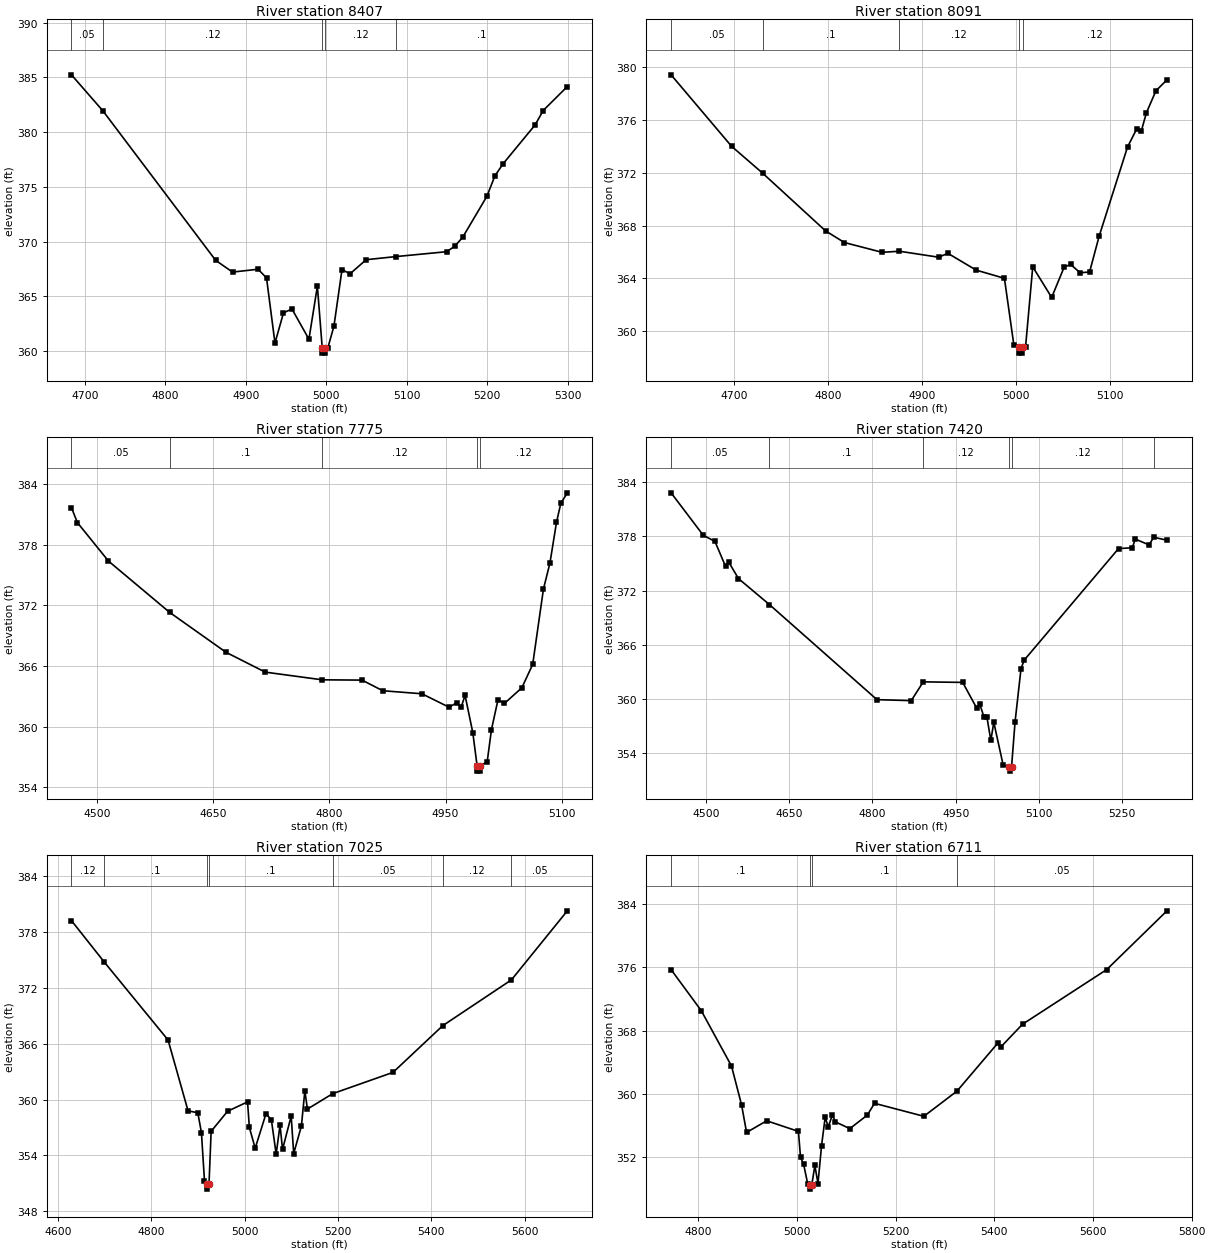
Type RM Length L Ch R = 1,8407,316,316,316
BEGIN DESCRIPTION:
Caney Creek T 27 17.0
END DESCRIPTION:
XS GIS Cut Line= 3
      2753225.96      6781861.01      2752926.00      6781961.00
      2752625.99      6781961.00
#Sta/Elev= 30
  4683.4  385.23  4722.7  381.92  4862.6  368.29  4883.6  367.22  4915.3  367.48
  4925.8  366.69  4936.3  360.74  4946.9  363.50  4957.4  363.85  4978.5  361.09
  4989.0  365.93  4995.0  360.32  4995.2  359.82  4998.7  359.82  4999.0  360.32
  5002.1  360.32  5009.6  362.29  5019.6  367.45  5029.6  367.06  5049.6  368.35
  5087.3  368.64  5149.6  369.08  5159.6  369.57  5169.6  370.40  5199.6  374.13
  5209.6  376.00  5219.6  377.09  5259.6  380.66  5269.6  381.97  5299.6  384.16
#Mann=5,-1,0
  4683.4    0.05       0  4722.7    0.12       0  4995.0    0.07       0
  4999.0    0.12       0  5087.3     0.1       0
Bank Sta=4995,4999
Exp/Cntr=0.3,0.1

Type RM Length L Ch R = 1,8091,316,316,316
BEGIN DESCRIPTION:
Caney Creek T 27 16.0
END DESCRIPTION:
XS GIS Cut Line= 3
      2753200.17      6781716.03      2752826.00      6781711.00
      2752674.40      6781729.31
#Sta/Elev= 30
  4633.4  379.42  4697.6  374.01  4730.8  371.96  4797.6  367.59  4817.6  366.71
  4857.6  365.97  4876.1  366.05  4917.6  365.60  4927.6  365.89  4957.6  364.62
  4987.6  364.00  4997.6  358.96  5003.1  358.83  5003.3  358.33  5006.8  358.33
  5007.1  358.83  5010.1  358.83  5017.7  364.87  5037.8  362.55  5051.1  364.85
  5058.0  365.05  5068.0  364.42  5078.1  364.48  5088.2  367.18  5118.4  373.95
  5128.1  375.31  5133.1  375.17  5138.5  376.55  5148.6  378.21  5160.3  379.04
#Mann=5,-1,0
  4633.4    0.05       0  4730.8     0.1       0  4876.1    0.12       0
  5003.1    0.07       0  5007.1    0.12       0
Bank Sta=5003.1,5007.1
Exp/Cntr=0.3,0.1

Type RM Length L Ch R = 1,7775,355,355,355
BEGIN DESCRIPTION:
Caney Creek T 27 15.0
END DESCRIPTION:
XS GIS Cut Line= 3
      2753243.54      6781566.42      2752726.00      6781461.00
      2752625.98      6781511.01
#Sta/Elev= 30
  4467.2  381.66  4474.9  380.18  4515.0  376.38  4593.9  371.31  4666.7  367.36
  4717.3  365.40  4790.8  364.64  4842.3  364.61  4869.0  363.56  4919.5  363.26
  4954.6  361.93  4964.8  362.39  4970.1  361.91  4975.2  363.11  4985.2  359.42
  4990.8  356.11  4991.1  355.61  4994.6  355.61  4994.8  356.11  5003.8  356.55
  5009.3  359.72  5017.7  362.66  5026.1  362.31  5048.5  363.85  5062.5  366.16
  5076.4  373.62  5084.8  376.20  5093.2  380.20  5098.8  382.09  5107.2  383.13
#Mann=5,-1,0
  4467.2    0.05       0  4593.9     0.1       0  4790.8    0.12       0
  4990.8    0.07       0  4994.8    0.12       0
Bank Sta=4990.8,4994.8
Exp/Cntr=0.3,0.1

Type RM Length L Ch R = 1,7420,395,395,395
BEGIN DESCRIPTION:
Caney Creek T 27 14.0
END DESCRIPTION:
XS GIS Cut Line= 3
      2753310.56      6781349.83      2752776.00      6781161.00
      2752469.94      6781277.16
#Sta/Elev= 30
  4436.8  382.82  4494.7  378.13  4515.9  377.44  4535.1  374.67  4540.4  375.19
  4558.3  373.33  4614.2  370.45  4808.1  359.93  4869.9  359.82  4891.6  361.90
  4962.7  361.84  4988.3  358.96  4993.6  359.43  5001.1  358.00  5006.4  358.00
  5013.5  355.41  5018.8  357.43  5035.8  352.66  5046.9  352.52  5047.2  352.02
  5050.9  352.52  5057.2  357.49  5067.9  363.36  5073.7  364.31  5243.8  376.65
  5268.6  376.74  5274.0  377.70  5298.8  377.06  5307.2  377.90  5331.1  377.58
#Mann=6,-1,0
  4436.8    0.05       0  4614.2     0.1       0  4891.6    0.12       0
  5046.9    0.07       0  5050.9    0.12       0  5307.2    0.05       0
Bank Sta=5046.9,5050.9
Exp/Cntr=0.3,0.1

Type RM Length L Ch R = 1,7025,314,314,314
BEGIN DESCRIPTION:
Caney Creek T 27 13.0
END DESCRIPTION:
XS GIS Cut Line= 3
      2753269.78      6780663.01      2752976.00      6780911.00
      2752349.40      6781170.08
#Sta/Elev= 30
  4629.2  379.20  4699.1  374.78  4836.2  366.39  4879.1  358.78  4899.9  358.59
  4907.7  356.45  4914.2  351.30  4919.9  350.89  4920.2  350.39  4923.9  350.89
  4928.5  356.59  4963.6  358.74  5006.5  359.75  5010.4  357.01  5022.9  354.78
  5046.1  358.49  5057.6  357.82  5067.8  354.15  5076.1  357.25  5081.5  354.66
  5100.0  358.22  5105.4  354.21  5121.9  357.16  5129.3  360.94  5134.8  358.98
  5188.8  360.63  5318.3  362.92  5424.8  367.93  5571.9  372.84  5691.7  380.25
#Mann=7,-1,0
  4629.2    0.12       0  4699.1     0.1       0  4919.9    0.07       0
  4923.9     0.1       0  5188.8    0.05       0  5424.8    0.12       0
  5571.9    0.05       0
Bank Sta=4919.9,4923.9
Exp/Cntr=0.3,0.1

Type RM Length L Ch R = 1,6711,340,340,340
BEGIN DESCRIPTION:
Caney Creek T 27 12.0
END DESCRIPTION:
XS GIS Cut Line= 3
      2753176.01      6780611.00      2752926.00      6780661.00
      2752325.97      6781111.02
#Sta/Elev= 30
  4744.9  375.73  4806.1  370.53  4867.3  363.54  4887.7  358.64  4897.9  355.14
  4938.7  356.61  5003.0  355.27  5007.2  352.00  5013.4  351.14  5021.7  348.67
  5026.0  348.47  5026.2  347.97  5030.0  348.47  5036.3  350.96  5042.6  348.68
  5049.9  353.48  5057.2  357.06  5063.4  355.84  5071.7  357.33  5078.0  356.47
  5107.2  355.62  5142.6  357.33  5157.2  358.82  5257.2  357.18  5324.3  360.36
  5407.2  366.44  5413.4  365.96  5457.2  368.82  5628.0  375.74  5749.9  383.16
#Mann=4,-1,0
  4744.9     0.1       0  5026.0    0.07       0  5030.0     0.1       0
  5324.3    0.05       0
Bank Sta=5026,5030
Exp/Cntr=0.3,0.1

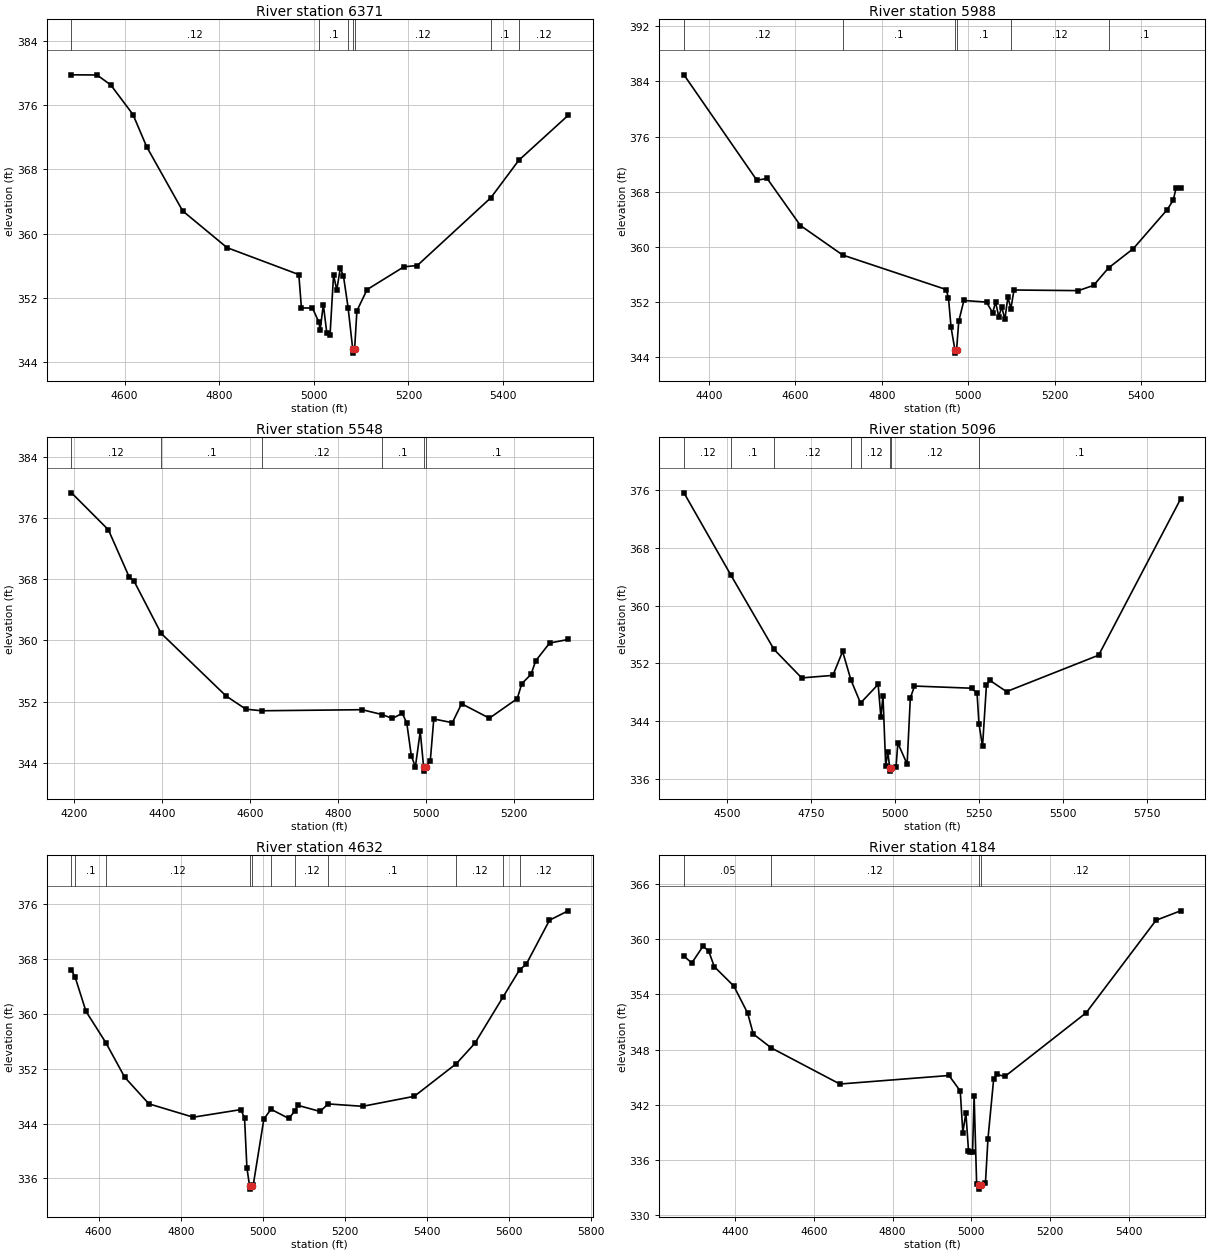
Type RM Length L Ch R = 1,6371,383,383,383
BEGIN DESCRIPTION:
Caney Creek T 27 11.0
END DESCRIPTION:
XS GIS Cut Line= 3
      2753151.53      6780254.94      2752676.00      6780461.00
      2752285.70      6780821.10
#Sta/Elev= 30
  4488.0  379.81  4542.0  379.79  4570.9  378.55  4617.9  374.86  4646.8  370.84
  4722.9  362.83  4816.6  358.25  4968.3  354.89  4973.8  350.73  4997.2  350.71
  5010.7  348.94  5013.3  347.94  5020.1  351.15  5027.5  347.56  5034.3  347.41
  5041.7  354.85  5048.5  352.95  5055.9  355.71  5062.7  354.68  5072.4  350.78
  5082.2  345.59  5082.5  345.09  5086.2  345.59  5091.0  350.37  5112.6  353.02
  5190.3  355.86  5218.6  356.02  5374.1  364.48  5433.1  369.15  5537.3  374.75
#Mann=7,-1,0
  4488.0    0.12       0  5010.7     0.1       0  5072.4    0.12       0
  5082.2    0.07       0  5086.2    0.12       0  5374.1     0.1       0
  5433.1    0.12       0
Bank Sta=5082.2,5086.2
Exp/Cntr=0.3,0.1

Type RM Length L Ch R = 1,5988,440,440,440
BEGIN DESCRIPTION:
Caney Creek T 27 10.0
END DESCRIPTION:
XS GIS Cut Line= 3
      2753176.04      6779860.98      2752576.00      6780111.00
      2752232.30      6780471.73
#Sta/Elev= 30
  4342.4  384.96  4510.9  369.65  4534.7  369.90  4611.7  363.07  4709.4  358.78
  4948.6  353.77  4954.0  352.56  4959.9  348.33  4968.8  345.03  4969.0  344.53
  4972.8  345.03  4977.8  349.17  4989.7  352.18  5042.0  351.94  5056.1  350.39
  5063.0  351.91  5070.3  349.84  5077.2  351.24  5084.4  349.44  5091.4  352.68
  5098.3  350.99  5105.5  353.70  5254.3  353.61  5289.5  354.37  5324.1  356.91
  5381.4  359.71  5459.4  365.35  5473.5  366.71  5480.4  368.54  5490.7  368.56
#Mann=6,-1,0
  4342.4    0.12       0  4709.4     0.1       0  4968.8    0.07       0
  4972.8     0.1       0  5098.3    0.12       0  5324.1     0.1       0
Bank Sta=4968.8,4972.8
Exp/Cntr=0.3,0.1

Type RM Length L Ch R = 1,5548,452,452,452
BEGIN DESCRIPTION:
Caney Creek T 27 9.0
END DESCRIPTION:
XS GIS Cut Line= 3
      2753075.96      6779711.01      2752276.00      6779861.00
      2752176.01      6780160.97
#Sta/Elev= 30
  4194.0  379.30  4277.9  374.47  4325.4  368.28  4336.4  367.75  4397.8  360.94
  4545.8  352.74  4590.8  351.02  4626.4  350.81  4855.3  350.95  4901.2  350.31
  4924.0  349.81  4946.9  350.47  4957.0  349.19  4967.2  344.96  4976.5  343.47
  4987.6  348.11  4995.3  343.42  4995.9  342.92  5000.2  343.42  5010.5  344.30
  5018.4  349.74  5060.6  349.25  5081.7  351.73  5144.9  349.84  5208.2  352.39
  5218.7  354.35  5239.8  355.58  5250.3  357.34  5282.0  359.66  5324.1  360.13
#Mann=6,-1,0
  4194.0    0.12       0  4397.8     0.1       0  4626.4    0.12       0
  4901.2     0.1       0  4995.3    0.07       0  5000.2     0.1       0
Bank Sta=4995.3,5000.2
Exp/Cntr=0.3,0.1

Type RM Length L Ch R = 1,5096,464,464,464
BEGIN DESCRIPTION:
Caney Creek T 27 8.0
END DESCRIPTION:
XS GIS Cut Line= 3
      2752769.51      6779071.51      2752276.00      6779461.00
      2751525.99      6779861.00
#Sta/Elev= 30
  4371.4  375.64  4511.6  364.19  4639.4  353.93  4721.9  349.97  4814.9  350.32
  4843.8  353.64  4868.8  349.65  4897.1  346.48  4949.6  349.07  4957.6  344.59
  4964.0  347.45  4972.1  337.75  4978.4  339.69  4984.1  337.54  4984.7  337.04
  4989.0  337.54  5002.9  337.65  5008.2  340.93  5035.9  338.02  5045.4  347.17
  5057.8  348.84  5227.8  348.54  5244.1  347.84  5249.8  343.60  5260.4  340.47
  5272.1  349.02  5282.4  349.62  5331.9  348.07  5606.1  353.12  5850.1  374.78
#Mann=8,-1,0
  4371.4    0.12       0  4511.6     0.1       0  4639.4    0.12       0
  4868.8     0.1       0  4897.1    0.12       0  4984.1    0.07       0
  4989.0    0.12       0  5249.8     0.1       0
Bank Sta=4984.1,4989
Exp/Cntr=0.3,0.1

Type RM Length L Ch R = 1,4632,448,448,448
BEGIN DESCRIPTION:
Caney Creek T 27 7.0
END DESCRIPTION:
XS GIS Cut Line= 3
      2752375.97      6778911.02      2751976.00      6779161.00
      2751326.01      6779510.99
#Sta/Elev= 30
  4533.9  366.39  4542.9  365.35  4569.2  360.38  4617.5  355.82  4663.6  350.76
  4722.5  346.88  4830.5  344.93  4946.6  346.04  4955.5  344.78  4961.3  337.50
  4967.7  334.93  4968.3  334.43  4972.7  334.93  4976.7  335.04  5002.6  344.67
  5019.9  346.09  5063.2  344.75  5078.4  345.85  5085.1  346.67  5139.4  345.77
  5159.2  346.87  5243.3  346.52  5369.0  347.98  5471.7  352.76  5516.7  355.73
  5585.6  362.52  5625.8  366.48  5641.6  367.24  5698.4  373.69  5743.8  375.06
#Mann=11,-1,0
  4533.9    0.12       0  4542.9     0.1       0  4617.5    0.12       0
  4967.7    0.07       0  4972.7    0.12       0  5019.9     0.1       0
  5078.4    0.12       0  5159.2     0.1       0  5471.7    0.12       0
  5585.6     0.1       0  5625.8    0.12       0
Bank Sta=4967.7,4972.7
Exp/Cntr=0.3,0.1

Type RM Length L Ch R = 1,4184,471,471,471
BEGIN DESCRIPTION:
Caney Creek T 27 6.0
END DESCRIPTION:
XS GIS Cut Line= 3
      2752186.10      6778543.11      2751626.00      6779011.00
      2751213.00      6779345.68
#Sta/Elev= 30
  4269.9  358.17  4289.8  357.43  4318.4  359.26  4332.7  358.73  4347.0  357.02
  4396.5  354.92  4431.6  351.97  4446.0  349.69  4491.9  348.17  4665.9  344.24
  4943.1  345.17  4971.7  343.48  4978.2  338.95  4986.0  341.09  4992.6  336.99
  4996.5  336.83  5002.9  336.83  5006.9  342.93  5013.3  333.36  5018.7  333.29
  5019.4  332.79  5023.8  333.29  5035.7  333.49  5042.1  338.30  5056.5  344.76
  5064.1  345.28  5085.2  345.07  5291.4  352.00  5468.9  362.08  5531.3  363.11
#Mann=4,-1,0
  4269.9    0.05       0  4491.9    0.12       0  5018.7    0.07       0
  5023.8    0.12       0
Bank Sta=5018.7,5023.8
Exp/Cntr=0.3,0.1

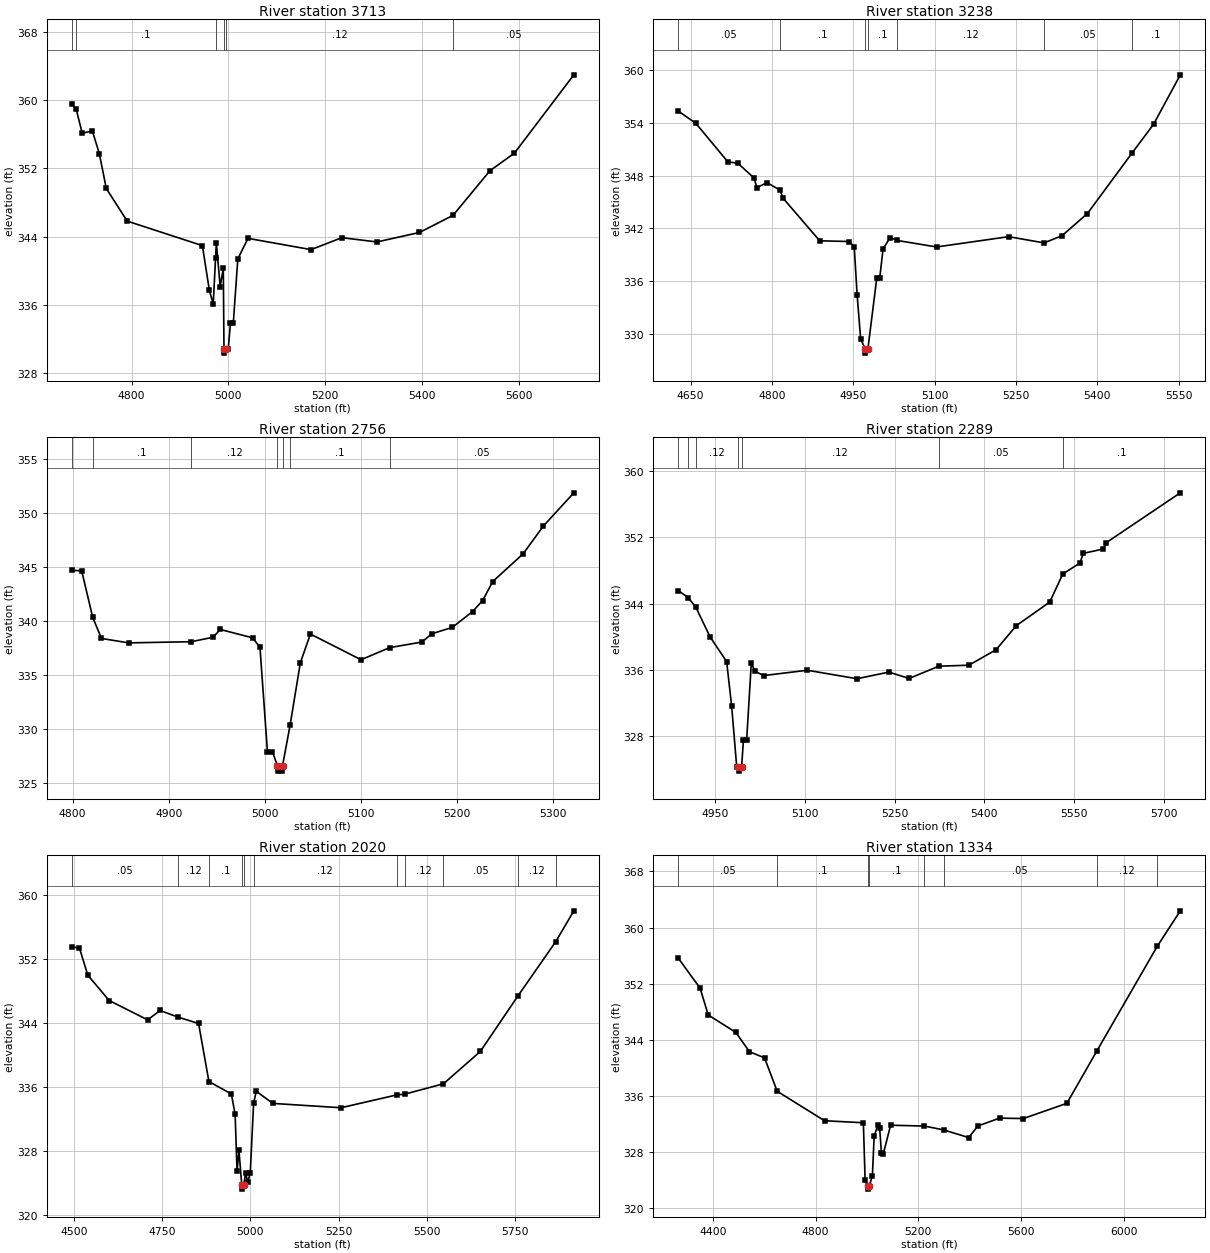
Type RM Length L Ch R = 1,3713,475,475,475
BEGIN DESCRIPTION:
Caney Creek T 27 5.0
END DESCRIPTION:
XS GIS Cut Line= 3
      2751876.02      6778410.98      2751626.00      6778611.00
      2751022.64      6778998.21
#Sta/Elev= 30
  4676.4  359.53  4685.2  359.01  4698.0  356.11  4718.8  356.40  4733.3  353.74
  4747.7  349.65  4790.9  345.83  4946.2  342.96  4960.6  337.73  4968.6  336.12
  4973.4  341.48  4975.0  343.26  4983.0  338.17  4989.4  340.33  4990.8  330.87
  4991.5  330.37  4996.0  330.87  4999.6  330.87  5004.2  333.90  5010.1  333.93
  5019.4  341.41  5040.5  343.81  5170.7  342.49  5234.2  343.89  5306.8  343.39
  5394.6  344.50  5464.1  346.51  5540.0  351.72  5590.7  353.79  5713.5  362.96
#Mann=6,-1,0
  4676.4    0.05       0  4685.2     0.1       0  4973.4    0.12       0
  4990.8    0.07       0  4996.0    0.12       0  5464.1    0.05       0
Bank Sta=4990.8,4996
Exp/Cntr=0.3,0.1

Type RM Length L Ch R = 1,3238,482,482,482
BEGIN DESCRIPTION:
Caney Creek T 27 4.0
END DESCRIPTION:
XS GIS Cut Line= 3
      2751767.92      6778122.56      2751426.00      6778261.00
      2750916.33      6778486.22
#Sta/Elev= 30
  4627.2  355.32  4659.6  353.93  4718.6  349.56  4737.2  349.39  4766.9  347.73
  4772.3  346.63  4791.0  347.19  4815.0  346.34  4820.5  345.43  4888.2  340.59
  4942.1  340.51  4951.8  339.94  4957.2  334.42  4963.7  329.45  4971.9  328.34
  4972.6  327.84  4977.1  328.34  4993.4  336.36  4998.8  336.36  5005.0  339.66
  5017.9  340.95  5031.1  340.63  5103.7  339.89  5236.6  341.06  5302.2  340.35
  5335.3  341.18  5381.9  343.68  5464.5  350.57  5503.9  353.81  5553.3  359.43
#Mann=7,-1,0
  4627.2    0.05       0  4815.0     0.1       0  4971.9    0.07       0
  4977.1     0.1       0  5031.1    0.12       0  5302.2    0.05       0
  5464.5     0.1       0
Bank Sta=4971.9,4977.1
Exp/Cntr=0.3,0.1

Type RM Length L Ch R = 1,2756,467,467,467
BEGIN DESCRIPTION:
Caney Creek T 27 3.0
END DESCRIPTION:
XS GIS Cut Line= 3
      2751425.98      6777811.00      2751226.00      6777861.00
      2750925.97      6777760.99
#Sta/Elev= 30
  4799.2  344.68  4809.5  344.65  4821.0  340.33  4830.1  338.38  4858.5  337.97
  4923.6  338.08  4946.1  338.49  4953.8  339.21  4987.3  338.44  4995.0  337.57
  5002.8  327.89  5008.0  327.89  5013.2  326.60  5014.0  326.10  5017.8  326.10
  5018.5  326.60  5026.4  330.37  5037.0  336.12  5047.5  338.79  5100.2  336.41
  5129.9  337.53  5163.5  338.05  5174.0  338.82  5195.1  339.40  5216.2  340.87
  5226.7  341.89  5237.2  343.65  5268.9  346.22  5289.9  348.79  5321.6  351.86
#Mann=7,-1,0
  4799.2    0.12       0  4821.0     0.1       0  4923.6    0.12       0
  5013.2    0.07       0  5018.5    0.12       0  5026.4     0.1       0
  5129.9    0.05       0
Bank Sta=5013.2,5018.5
Exp/Cntr=0.3,0.1

Type RM Length L Ch R = 1,2289,269,269,269
BEGIN DESCRIPTION:
Caney Creek T 27 2.0
END DESCRIPTION:
XS GIS Cut Line= 3
      2751525.97      6777510.99      2751426.00      6777461.00
      2750725.98      6777661.00
#Sta/Elev= 30
  4888.1  345.59  4904.6  344.75  4917.5  343.59  4941.2  340.02  4969.1  337.02
  4977.5  331.62  4985.9  324.33  4988.8  324.32  4989.6  323.82  4994.1  324.32
  4997.1  327.52  5002.5  327.52  5010.3  336.83  5016.8  335.84  5031.1  335.34
  5103.9  335.98  5187.1  334.96  5240.4  335.76  5274.2  334.99  5324.0  336.47
  5374.3  336.59  5419.8  338.46  5453.6  341.36  5509.5  344.20  5531.3  347.59
  5560.2  348.91  5565.4  350.07  5599.2  350.60  5604.4  351.38  5727.9  357.37
#Mann=7,-1,0
  4888.1    0.05       0  4904.6     0.1       0  4917.5    0.12       0
  4988.8    0.07       0  4994.1    0.12       0  5324.0    0.05       0
  5531.3     0.1       0
Bank Sta=4988.8,4994.1
Exp/Cntr=0.3,0.1

Type RM Length L Ch R = 1,2020,686,686,686
BEGIN DESCRIPTION:
Mapping XS e1caf3f1
END DESCRIPTION:
XS GIS Cut Line= 2
      2751998.34      6777067.10      2750669.74      6777580.11
#Sta/Elev= 30
  4493.2  353.45  4514.8  353.36  4538.6  349.95  4599.4  346.78  4708.5  344.37
  4743.8  345.54  4794.8  344.71  4852.9  343.92  4882.2  336.68  4945.9  335.13
  4956.6  332.58  4962.0  325.49  4967.4  328.11  4975.4  323.76  4976.2  323.26
  4980.8  323.76  4986.7  325.30  4992.0  324.09  4999.5  325.24  5009.0  333.99
  5016.6  335.46  5063.8  333.95  5256.8  333.41  5415.1  335.01  5437.2  335.10
  5547.6  336.40  5652.1  340.43  5758.4  347.33  5865.5  354.09  5917.4  357.97
#Mann=11,-1,0
  4493.2    0.05       0  4794.8    0.12       0  4882.2     0.1       0
  4975.4    0.07       0  4980.8     0.1       0  5009.0    0.12       0
  5415.1    0.05       0  5437.2    0.12       0  5547.6    0.05       0
  5758.4    0.12       0  5865.5     0.1       0
Bank Sta=4975.4,4980.8
Exp/Cntr=0.3,0.1

Type RM Length L Ch R = 1,1334,392,392,392
BEGIN DESCRIPTION:
Mapping XS ea3233b5
END DESCRIPTION:
XS GIS Cut Line= 3
      2752058.50      6777016.60      2751514.09      6776700.39
      2750535.73      6777594.70
#Sta/Elev= 30
  4264.9  355.65  4350.1  351.36  4381.6  347.55  4489.2  345.06  4542.2  342.31
  4601.0  341.43  4650.2  336.67  4834.5  332.47  4985.8  332.18  4992.6  324.00
  5004.1  323.22  5004.9  322.72  5009.5  323.22  5021.0  324.66  5027.8  330.26
  5041.9  331.83  5049.4  331.37  5056.1  327.83  5063.5  327.76  5091.9  331.83
  5223.8  331.71  5298.5  331.16  5395.9  330.07  5431.7  331.72  5516.2  332.84
  5608.7  332.78  5778.3  334.95  5895.4  342.44  6130.8  357.37  6220.0  362.39
#Mann=8,-1,0
  4264.9    0.05       0  4650.2     0.1       0  5004.1    0.07       0
  5009.5     0.1       0  5223.8    0.12       0  5298.5    0.05       0
  5895.4    0.12       0  6130.8     0.1       0
Bank Sta=5004.1,5009.5
Exp/Cntr=0.3,0.1

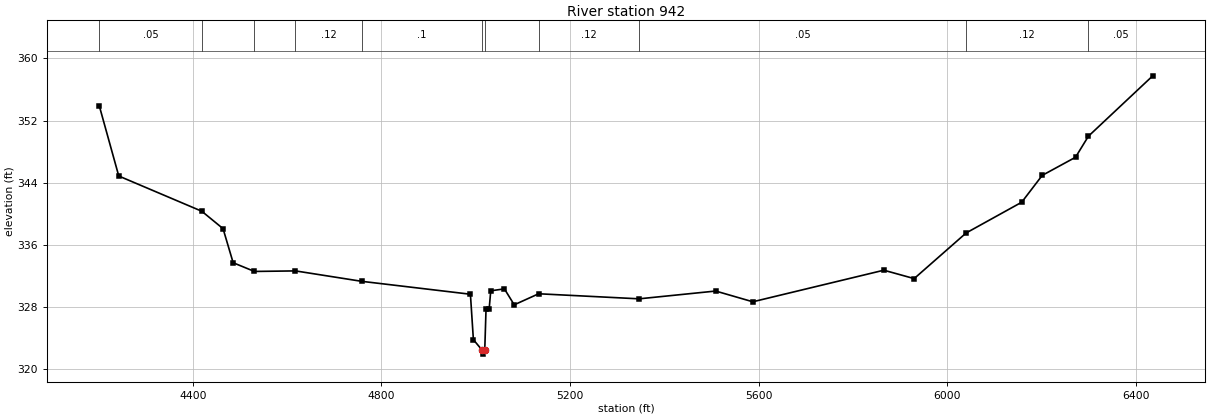
Type RM Length L Ch R = 1,942,0,0,0
BEGIN DESCRIPTION:
Caney Creek T 27 1.0
END DESCRIPTION:
XS GIS Cut Line= 3
      2752011.36      6776833.61      2751304.33      6776410.52
      2750440.13      6777524.81
#Sta/Elev= 30
  4201.7  353.87  4242.9  344.87  4419.0  340.34  4464.1  338.10  4485.5  333.72
  4530.6  332.60  4617.7  332.67  4758.1  331.33  4988.7  329.67  4995.0  323.83
  5013.7  322.47  5014.5  321.97  5019.1  322.47  5021.8  327.73  5028.4  327.73
  5031.8  330.11  5060.8  330.36  5081.6  328.31  5133.4  329.73  5346.4  329.08
  5508.9  330.08  5587.6  328.70  5865.5  332.76  5929.8  331.68  6040.1  337.55
  6157.9  341.50  6201.4  344.95  6272.0  347.28  6299.4  349.99  6435.8  357.75
#Mann=11,-1,0
  4201.7    0.05       0  4419.0    0.12       0  4530.6     0.1       0
  4617.7    0.12       0  4758.1     0.1       0  5013.7    0.07       0
  5019.1     0.1       0  5133.4    0.12       0  5346.4    0.05       0
  6040.1    0.12       0  6299.4    0.05       0
Bank Sta=5013.7,5019.1
Exp/Cntr=0.3,0.1

Chan Stop Cuts=-1