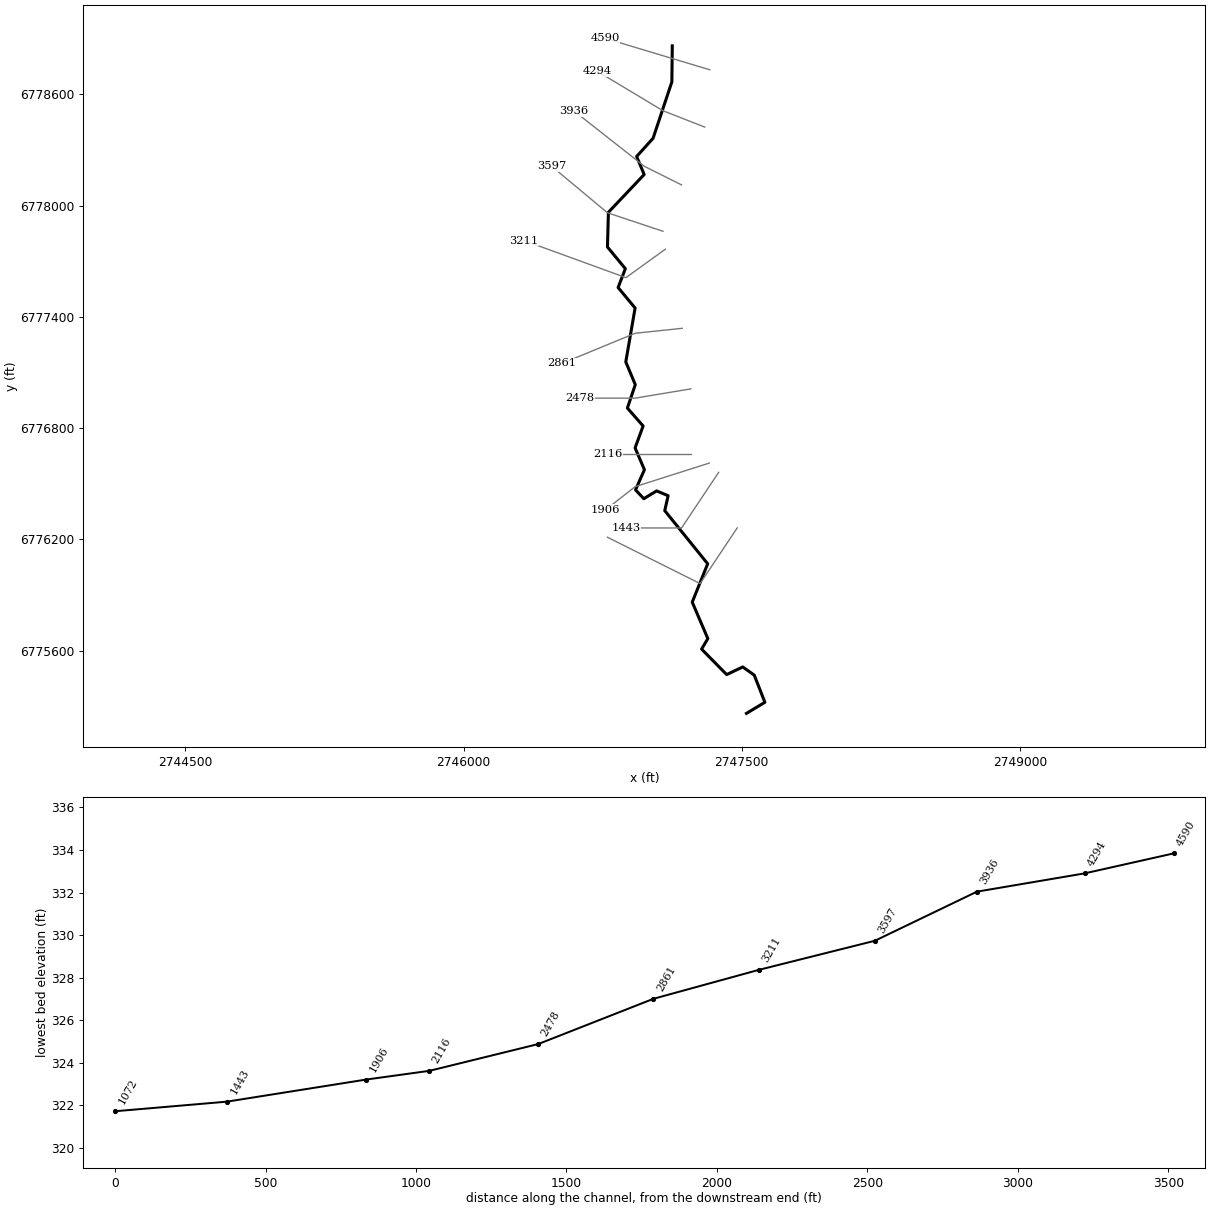
--- Caney Creek T 28.prj (project) ---

Proj Title=Caney Creek T 28 Base Level Engineering
Current Plan=p01
Default Exp/Contr=0.3,0.1
English Units
Geom File=g01
Flow File=f01
Plan File=p01
BEGIN DESCRIPTION:
Caney Creek T 28
END DESCRIPTION:

--- Caney Creek T 28.p01 (plan) ---

Plan Title=Multiple Run
Short Identifier=Multiple
Geom File=g01
Flow File=f01
Subcritical Flow
K Sum by GR= 0
Std Step Tol= 0.01
Critical Tol= 0.01
Num of Std Step Trials= 20
Max Error Tol= 0.3
Flow Tol Ratio= 0.001
Split Flow NTrial= 30
Split Flow Tol= 0.02
Split Flow Ratio= 0.02
Log Output Level= 0
Friction Slope Method= 1
Unsteady Friction Slope Method= 2
Unsteady Bridges Friction Slope Method= 1
Parabolic Critical Depth
Global Vel Dist=  1 , 1 , 1
Global Log Level= 0
CheckData=True
Encroach Param= -1, 0, 0, 0
BEGIN DESCRIPTION:
Multiple Run
END DESCRIPTION:

--- Caney Creek T 28.f01 (steady flow) ---

Flow Title=Multiple
Number of Profiles=7
Profile Names=10-year,25-year,50-year,1pct_min,100-year,1pct_plu,500-year
River Rch & RM= Caney Creek T 28,Reach-1,4590
     466     622     748     448     894    1784    1278
Boundary for River Rch & Prof#=Caney Creek T 28,Reach-1,1
Up Type=0
Dn Type=3
Dn Slope=0.005
Boundary for River Rch & Prof#=Caney Creek T 28,Reach-1,2
Up Type=0
Dn Type=3
Dn Slope=0.005
Boundary for River Rch & Prof#=Caney Creek T 28,Reach-1,3
Up Type=0
Dn Type=3
Dn Slope=0.005
Boundary for River Rch & Prof#=Caney Creek T 28,Reach-1,4
Up Type=0
Dn Type=3
Dn Slope=0.005
Boundary for River Rch & Prof#=Caney Creek T 28,Reach-1,5
Up Type=0
Dn Type=3
Dn Slope=0.005
Boundary for River Rch & Prof#=Caney Creek T 28,Reach-1,6
Up Type=0
Dn Type=3
Dn Slope=0.005
Boundary for River Rch & Prof#=Caney Creek T 28,Reach-1,7
Up Type=0
Dn Type=3
Dn Slope=0.005

--- Caney Creek T 28.g01 (geometry) ---

Geom Title=Existing Conditions

River Reach=Caney Creek T 28,Reach-1
Reach XY= 30
      2747126.00      6778861.00      2747123.63      6778666.53
      2747022.36      6778362.50      2746933.84      6778264.40
      2746974.34      6778167.05      2746781.46      6777963.45
      2746776.39      6777776.16      2746872.83      6777659.35
      2746833.84      6777557.60      2746925.45      6777447.14
      2746875.19      6777156.43      2746926.49      6777033.75
      2746883.83      6776907.58      2746968.66      6776811.10
      2746925.38      6776692.76      2746975.74      6776575.09
      2746927.73      6776466.22      2746972.27      6776418.72
      2747041.47      6776460.83      2747103.64      6776434.95
      2747085.32      6776354.35      2747316.87      6776067.74
      2747233.56      6775861.00      2747317.71      6775664.22
      2747283.99      6775607.66      2747419.27      6775470.15
      2747505.94      6775511.36      2747567.98      6775467.43
      2747625.39      6775320.66      2747526.00      6775261.00

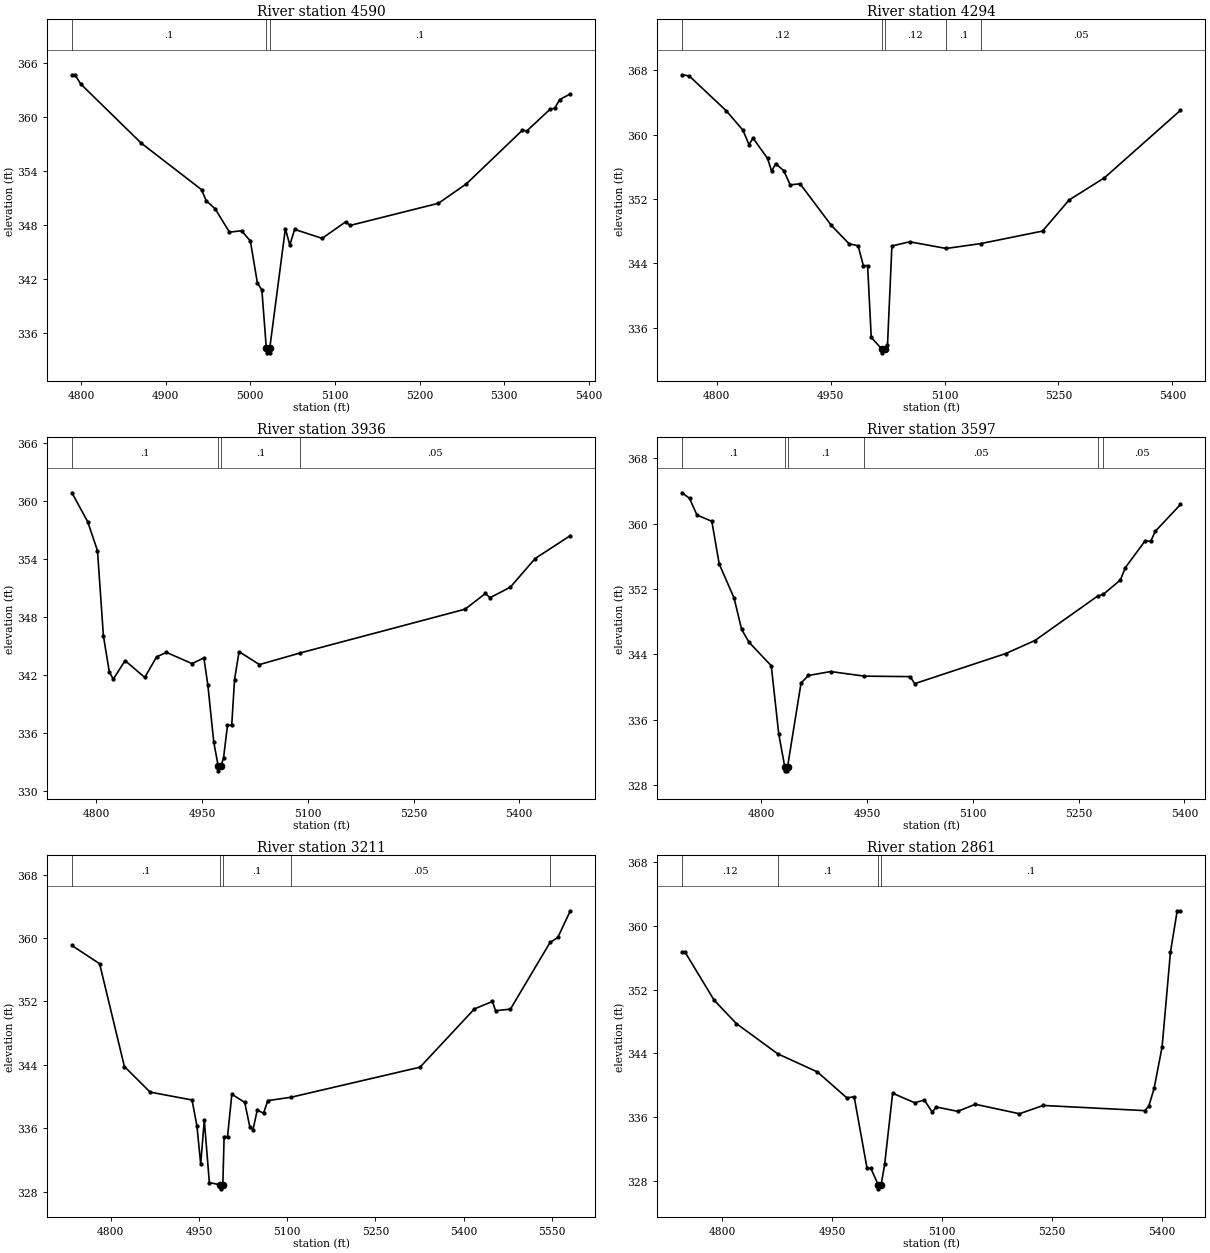
Type RM Length L Ch R = 1,4590,296,296,296
BEGIN DESCRIPTION:
2503
END DESCRIPTION:
XS GIS Cut Line= 2
      2747327.92      6778732.02      2746764.05      6778901.55
#Sta/Elev= 30
  4789.2  364.74  4792.8  364.74  4799.7  363.71  4871.0  357.15  4942.3  351.98
  4947.8  350.75  4958.3  349.86  4975.3  347.25  4989.6  347.41  5000.0  346.27
  5008.3  341.62  5013.6  340.83  5018.9  334.34  5019.2  333.84  5022.7  333.84
  5022.9  334.34  5041.4  347.65  5046.6  345.81  5052.3  347.56  5084.8  346.56
  5112.6  348.40  5117.9  348.00  5222.2  350.46  5255.2  352.62  5321.3  358.57
  5326.5  358.49  5354.3  360.93  5359.5  361.01  5365.5  361.99  5378.0  362.61
#Mann=3,-1,0
  4789.2     0.1       0  5018.9    0.07       0  5022.9     0.1       0
Bank Sta=5018.9,5022.9
Exp/Cntr=0.3,0.1

Type RM Length L Ch R = 1,4294,358,358,358
BEGIN DESCRIPTION:
1550
END DESCRIPTION:
XS GIS Cut Line= 3
      2747300.72      6778422.97      2747076.00      6778511.00
      2746720.25      6778724.61
#Sta/Elev= 30
  4754.4  367.43  4763.8  367.29  4812.7  362.95  4834.6  360.54  4842.5  358.76
  4847.9  359.56  4866.9  357.05  4872.3  355.46  4877.7  356.39  4888.3  355.52
  4896.8  353.76  4909.8  353.89  4951.0  348.72  4974.3  346.44  4986.2  346.20
  4993.1  343.73  4998.7  343.73  5003.5  334.83  5017.1  333.40  5017.3  332.90
  5021.1  333.40  5024.9  333.85  5030.7  346.17  5054.1  346.69  5102.2  345.86
  5147.9  346.47  5229.0  348.02  5264.0  351.88  5310.6  354.64  5410.7  363.02
#Mann=5,-1,0
  4754.4    0.12       0  5017.1    0.07       0  5021.1    0.12       0
  5102.2     0.1       0  5147.9    0.05       0
Bank Sta=5017.1,5021.1
Exp/Cntr=0.3,0.1

Type RM Length L Ch R = 1,3936,339,339,339
BEGIN DESCRIPTION:
1549
END DESCRIPTION:
XS GIS Cut Line= 3
      2747176.01      6778111.00      2746976.00      6778211.00
      2746595.80      6778509.99
#Sta/Elev= 30
  4765.2  360.80  4787.6  357.81  4801.5  354.81  4809.9  346.00  4818.3  342.27
  4823.9  341.52  4840.7  343.44  4868.6  341.70  4885.4  343.83  4899.4  344.29
  4935.7  343.13  4952.5  343.72  4958.1  340.93  4966.5  335.02  4972.8  332.54
  4973.1  332.04  4976.8  332.54  4980.4  333.38  4986.0  336.76  4992.0  336.76
  4996.0  341.48  5002.4  344.37  5031.3  343.03  5089.0  344.23  5323.2  348.76
  5352.1  350.39  5358.5  349.94  5387.4  351.04  5422.6  354.00  5472.5  356.37
#Mann=4,-1,0
  4765.2     0.1       0  4972.8    0.07       0  4976.8     0.1       0
  5089.0    0.05       0
Bank Sta=4972.8,4976.8
Exp/Cntr=0.3,0.1

Type RM Length L Ch R = 1,3597,386,386,386
BEGIN DESCRIPTION:
1548
END DESCRIPTION:
XS GIS Cut Line= 3
      2747076.02      6777860.99      2746776.00      6777961.00
      2746475.97      6778211.02
#Sta/Elev= 30
  4687.6  363.76  4698.2  363.08  4708.7  361.04  4729.8  360.27  4740.3  355.04
  4761.4  350.87  4772.0  347.05  4782.5  345.47  4814.1  342.59  4824.7  334.24
  4833.2  330.23  4833.4  329.73  4836.9  329.73  4837.2  330.23  4856.3  340.47
  4866.8  341.40  4898.4  341.88  4946.1  341.32  5011.0  341.26  5017.5  340.40
  5146.4  344.08  5188.0  345.68  5276.9  351.12  5284.8  351.32  5309.1  353.08
  5316.3  354.61  5344.3  357.89  5352.1  357.81  5358.6  359.04  5394.4  362.33
#Mann=6,-1,0
  4687.6     0.1       0  4833.2    0.04       0  4837.2     0.1       0
  4946.1    0.05       0  5276.9    0.12       0  5284.8    0.05       0
Bank Sta=4833.2,4837.2
Exp/Cntr=0.3,0.1

Type RM Length L Ch R = 1,3211,350,350,350
BEGIN DESCRIPTION:
1547
END DESCRIPTION:
XS GIS Cut Line= 3
      2747088.39      6777764.11      2746876.00      6777611.00
      2746325.96      6777811.01
#Sta/Elev= 30
  4734.2  359.06  4781.3  356.76  4823.4  343.79  4867.2  340.56  4938.4  339.57
  4946.7  336.28  4953.1  331.49  4959.2  337.04  4967.8  329.15  4986.7  328.86
  4986.9  328.36  4990.7  328.86  4992.9  334.95  4998.7  334.95  5006.0  340.29
  5027.9  339.27  5036.6  336.18  5041.9  335.80  5049.2  338.29  5059.9  337.91
  5067.2  339.49  5107.0  339.92  5325.9  343.71  5418.3  351.06  5448.9  352.00
  5454.2  350.83  5479.5  351.03  5546.8  359.44  5560.0  360.07  5581.3  363.44
#Mann=5,-1,0
  4734.2     0.1       0  4986.7    0.07       0  4990.7     0.1       0
  5107.0    0.05       0  5546.8    0.12       0
Bank Sta=4986.7,4990.7
Exp/Cntr=0.3,0.1

Type RM Length L Ch R = 1,2861,383,383,383
BEGIN DESCRIPTION:
1546
END DESCRIPTION:
XS GIS Cut Line= 3
      2747179.59      6777337.67      2746926.00      6777311.00
      2746532.76      6777148.99
#Sta/Elev= 30
  4745.4  356.66  4749.7  356.66  4789.2  350.66  4819.4  347.74  4875.9  343.94
  4930.0  341.67  4970.2  338.42  4980.3  338.54  4997.9  329.57  5003.1  329.57
  5013.1  327.50  5013.3  327.00  5017.1  327.50  5022.0  330.13  5032.8  338.99
  5062.9  337.80  5076.1  338.14  5086.9  336.61  5092.3  337.27  5121.6  336.72
  5145.6  337.61  5205.9  336.42  5238.3  337.46  5377.3  336.81  5382.7  337.45
  5389.7  339.60  5400.6  344.81  5412.0  356.70  5421.2  361.88  5425.7  361.88
#Mann=4,-1,0
  4745.4    0.12       0  4875.9     0.1       0  5013.1    0.07       0
  5017.1     0.1       0
Bank Sta=5013.1,5017.1
Exp/Cntr=0.3,0.1

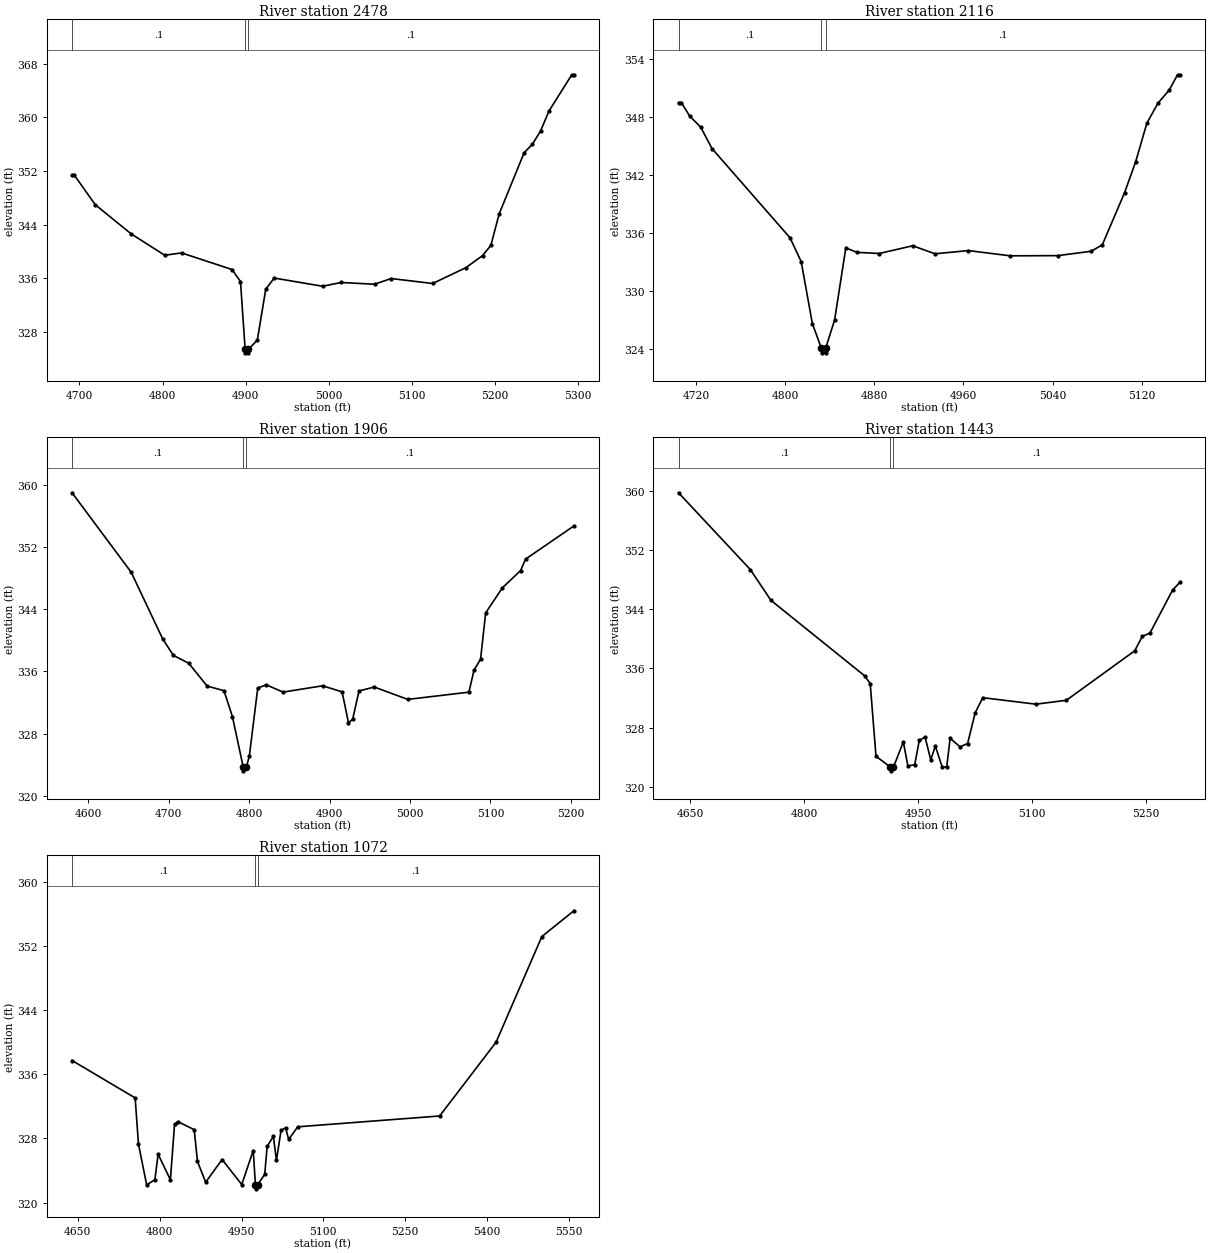
Type RM Length L Ch R = 1,2478,362,362,362
BEGIN DESCRIPTION:
1545
END DESCRIPTION:
XS GIS Cut Line= 3
      2747226.04      6777011.01      2746926.00      6776961.00
      2746625.98      6776961.00
#Sta/Elev= 30
  4691.1  351.38  4693.7  351.38  4719.0  346.96  4762.1  342.62  4802.7  339.42
  4822.9  339.77  4883.8  337.29  4893.9  335.50  4899.5  325.37  4899.8  324.87
  4903.3  324.87  4903.5  325.37  4914.2  326.79  4924.3  334.36  4934.5  336.02
  4992.7  334.80  5015.3  335.36  5055.3  335.10  5075.3  335.95  5125.3  335.21
  5165.3  337.57  5185.3  339.36  5195.3  340.88  5205.3  345.56  5235.3  354.68
  5245.3  355.96  5255.3  357.97  5265.3  360.92  5292.8  366.33  5295.3  366.33
#Mann=3,-1,0
  4691.1     0.1       0  4899.5    0.07       0  4903.5     0.1       0
Bank Sta=4899.5,4903.5
Exp/Cntr=0.3,0.1

Type RM Length L Ch R = 1,2116,210,210,210
BEGIN DESCRIPTION:
1544
END DESCRIPTION:
XS GIS Cut Line= 3
      2747226.04      6776661.00      2746926.00      6776661.00
      2746776.04      6776661.00
#Sta/Elev= 30
  4704.5  349.46  4707.0  349.46  4714.5  348.07  4724.5  346.90  4734.5  344.71
  4804.5  335.49  4814.5  333.03  4824.5  326.64  4832.5  324.11  4832.8  323.61
  4836.3  323.61  4836.5  324.11  4844.5  327.02  4854.5  334.45  4864.5  333.99
  4884.5  333.87  4914.5  334.67  4934.5  333.84  4964.5  334.17  5002.0  333.63
  5044.5  333.65  5074.5  334.10  5084.5  334.76  5104.5  340.15  5114.5  343.37
  5124.5  347.33  5134.5  349.41  5144.5  350.74  5152.0  352.33  5154.5  352.33
#Mann=3,-1,0
  4704.5     0.1       0  4832.5    0.07       0  4836.5     0.1       0
Bank Sta=4832.5,4836.5
Exp/Cntr=0.3,0.1

Type RM Length L Ch R = 1,1906,463,463,463
BEGIN DESCRIPTION:
1543
END DESCRIPTION:
XS GIS Cut Line= 3
      2747326.04      6776611.01      2746925.53      6776483.56
      2746765.17      6776357.94
#Sta/Elev= 30
  4579.7  358.97  4653.2  348.75  4692.5  340.15  4705.7  338.05  4724.8  337.04
  4747.6  334.11  4768.6  333.51  4779.1  330.18  4792.5  323.70  4792.7  323.20
  4796.5  323.70  4800.1  325.07  4810.6  333.85  4821.1  334.27  4842.1  333.33
  4891.2  334.14  4915.5  333.36  4923.4  329.39  4928.6  329.81  4936.5  333.48
  4955.6  333.98  4997.1  332.39  5073.2  333.32  5079.5  336.14  5087.7  337.57
  5094.0  343.51  5114.8  346.74  5137.4  348.96  5143.7  350.44  5203.7  354.70
#Mann=3,-1,0
  4579.7     0.1       0  4792.5    0.07       0  4796.5     0.1       0
Bank Sta=4792.5,4796.5
Exp/Cntr=0.3,0.1

Type RM Length L Ch R = 1,1443,371,371,371
BEGIN DESCRIPTION:
1542
END DESCRIPTION:
XS GIS Cut Line= 3
      2747375.98      6776560.96      2747176.00      6776261.00
      2746876.01      6776261.00
#Sta/Elev= 30
  4634.7  359.75  4729.3  349.36  4756.3  345.21  4879.5  335.02  4887.0  333.96
  4894.6  324.14  4913.6  322.66  4913.8  322.16  4917.6  322.66  4930.6  326.07
  4936.6  322.82  4945.6  323.00  4951.6  326.27  4959.2  326.74  4966.7  323.65
  4972.7  325.51  4981.7  322.69  4987.7  322.68  4992.2  326.56  5005.2  325.41
  5015.2  325.85  5025.2  330.02  5035.2  332.05  5105.2  331.17  5145.2  331.70
  5235.2  338.39  5245.2  340.34  5255.2  340.78  5285.2  346.63  5295.2  347.70
#Mann=3,-1,0
  4634.7     0.1       0  4913.6    0.07       0  4917.6     0.1       0
Bank Sta=4913.6,4917.6
Exp/Cntr=0.3,0.1

Type RM Length L Ch R = 1,1072,0,0,0
BEGIN DESCRIPTION:
1541
END DESCRIPTION:
XS GIS Cut Line= 3
      2747475.98      6776260.97      2747276.00      6775961.00
      2746776.04      6776210.98
#Sta/Elev= 30
  4639.5  337.72  4755.1  333.05  4761.2  327.27  4776.2  322.21  4791.2  322.84
  4797.2  326.03  4819.7  322.83  4827.3  329.77  4833.3  330.10  4863.3  329.09
  4869.3  325.13  4884.3  322.53  4914.4  325.37  4950.4  322.25  4971.5  326.49
  4975.5  322.21  4975.7  321.71  4979.5  322.21  4992.5  323.52  4997.0  327.01
  5008.4  328.26  5014.0  325.25  5022.4  328.99  5030.8  329.33  5036.4  327.88
  5053.1  329.45  5313.1  330.80  5416.5  340.01  5500.3  353.18  5559.0  356.40
#Mann=3,-1,0
  4639.5     0.1       0  4975.5    0.07       0  4979.5     0.1       0
Bank Sta=4975.5,4979.5
Exp/Cntr=0.3,0.1

Chan Stop Cuts=-1