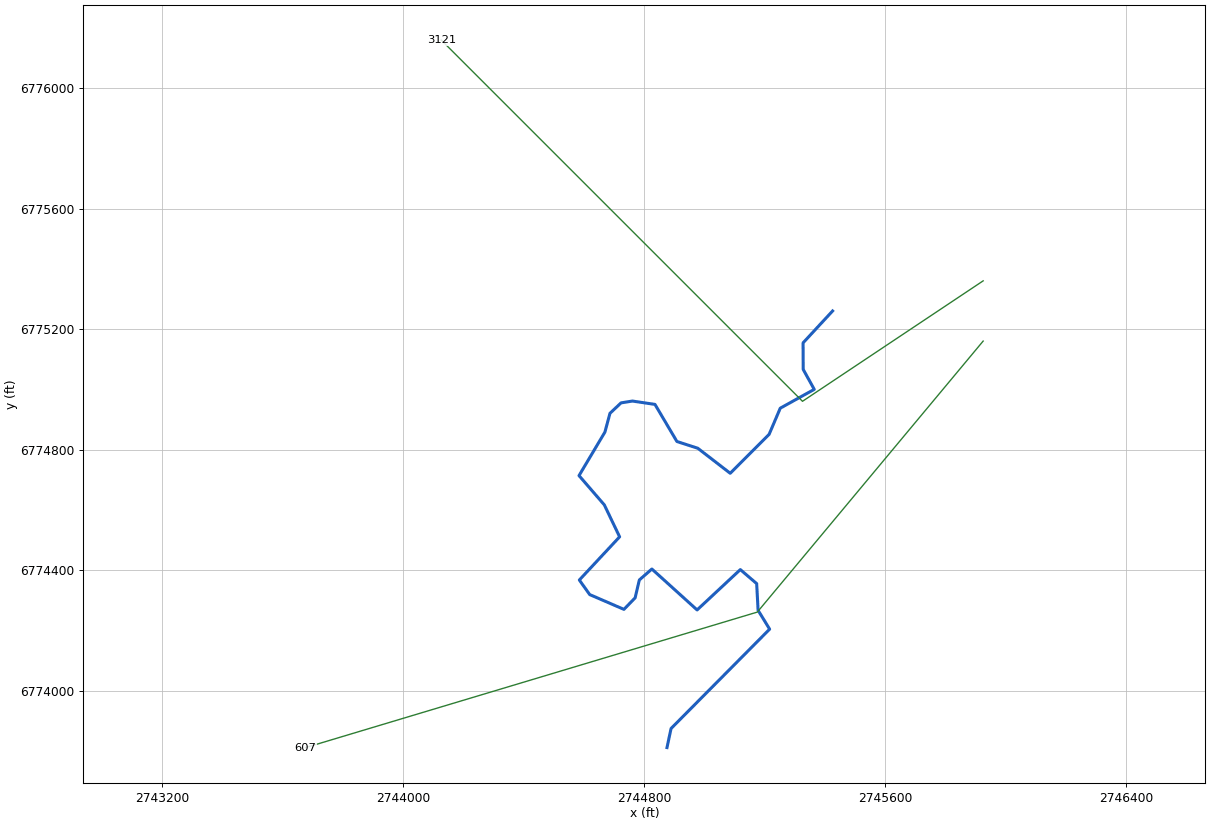
--- Caney Creek T 29.prj (project) ---

Proj Title=Caney Creek T 29 Base Level Engineering
Current Plan=p01
Default Exp/Contr=0.3,0.1
English Units
Geom File=g01
Flow File=f01
Plan File=p01
BEGIN DESCRIPTION:
Caney Creek T 29
END DESCRIPTION:

--- Caney Creek T 29.p01 (plan) ---

Plan Title=Multiple Run
Short Identifier=Multiple
Geom File=g01
Flow File=f01
Subcritical Flow
K Sum by GR= 0
Std Step Tol= 0.01
Critical Tol= 0.01
Num of Std Step Trials= 20
Max Error Tol= 0.3
Flow Tol Ratio= 0.001
Split Flow NTrial= 30
Split Flow Tol= 0.02
Split Flow Ratio= 0.02
Log Output Level= 0
Friction Slope Method= 1
Unsteady Friction Slope Method= 2
Unsteady Bridges Friction Slope Method= 1
Parabolic Critical Depth
Global Vel Dist=  1 , 1 , 1
Global Log Level= 0
CheckData=True
Encroach Param= -1, 0, 0, 0
BEGIN DESCRIPTION:
Multiple Run
END DESCRIPTION:

--- Caney Creek T 29.f01 (steady flow) ---

Flow Title=Multiple
Number of Profiles=7
Profile Names=10-year,25-year,50-year,1pct_min,100-year,1pct_plu,500-year
River Rch & RM= Caney Creek T 29,Reach-1,3121
     203     256     297     172     342     683     455
Boundary for River Rch & Prof#=Caney Creek T 29,Reach-1,1
Up Type=0
Dn Type=3
Dn Slope=0.005
Boundary for River Rch & Prof#=Caney Creek T 29,Reach-1,2
Up Type=0
Dn Type=3
Dn Slope=0.005
Boundary for River Rch & Prof#=Caney Creek T 29,Reach-1,3
Up Type=0
Dn Type=3
Dn Slope=0.005
Boundary for River Rch & Prof#=Caney Creek T 29,Reach-1,4
Up Type=0
Dn Type=3
Dn Slope=0.005
Boundary for River Rch & Prof#=Caney Creek T 29,Reach-1,5
Up Type=0
Dn Type=3
Dn Slope=0.005
Boundary for River Rch & Prof#=Caney Creek T 29,Reach-1,6
Up Type=0
Dn Type=3
Dn Slope=0.005
Boundary for River Rch & Prof#=Caney Creek T 29,Reach-1,7
Up Type=0
Dn Type=3
Dn Slope=0.005

--- Caney Creek T 29.g01 (geometry) ---

Geom Title=Existing Conditions

River Reach=Caney Creek T 29,Reach-1
Reach XY= 30
      2745426.00      6775261.00      2745327.93      6775155.12
      2745328.37      6775066.88      2745365.03      6775000.62
      2745252.18      6774938.14      2745215.21      6774851.34
      2745086.00      6774721.96      2744978.27      6774805.10
      2744908.95      6774827.50      2744836.10      6774950.70
      2744760.88      6774961.82      2744723.33      6774955.71
      2744686.61      6774921.07      2744669.88      6774858.84
      2744583.84      6774714.23      2744667.84      6774617.05
      2744718.71      6774510.91      2744584.89      6774367.51
      2744619.29      6774319.12      2744733.01      6774269.99
      2744770.15      6774308.20      2744784.16      6774367.67
      2744825.79      6774404.01      2744976.00      6774268.07
      2745119.51      6774402.12      2745173.85      6774355.52
      2745178.56      6774266.90      2745216.87      6774204.26
      2744889.47      6773874.27      2744876.00      6773811.00

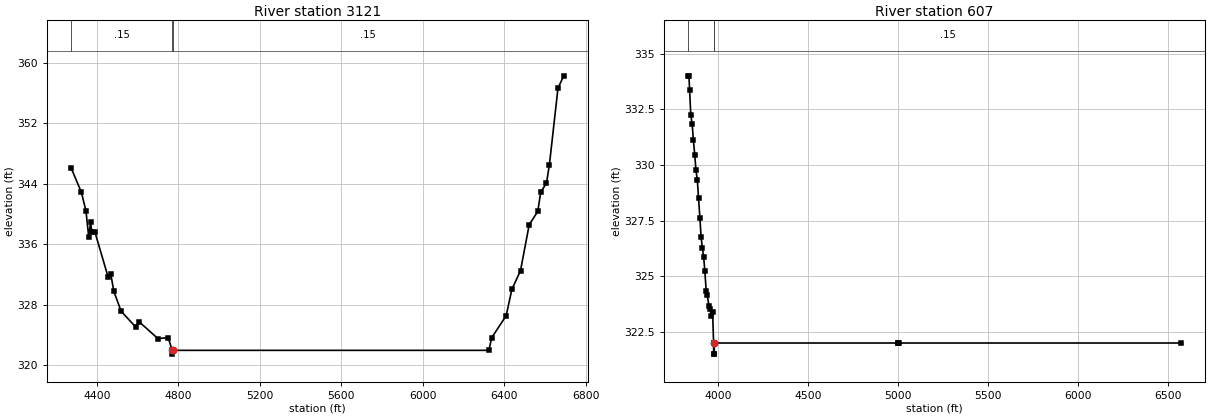
Type RM Length L Ch R = 1,3121,2514,2514,2514
BEGIN DESCRIPTION:
Caney Creek T 29 2.0
END DESCRIPTION:
XS GIS Cut Line= 3
      2745926.01      6775361.01      2745326.00      6774961.00
      2744125.99      6776161.01
#Sta/Elev= 30
  4274.2  346.05  4323.8  342.88  4346.3  340.41  4359.8  336.99  4368.9  338.93
  4374.9  337.63  4389.9  337.67  4454.5  331.73  4468.0  332.11  4483.0  329.80
  4519.1  327.16  4591.2  325.06  4606.2  325.80  4699.4  323.56  4750.4  323.67
  4769.5  322.00  4769.7  321.50  4773.5  322.00  6324.7  322.00  6338.8  323.68
  6409.5  326.57  6437.8  330.05  6480.2  332.54  6522.7  338.59  6565.1  340.37
  6579.2  342.88  6607.5  344.10  6621.7  346.46  6664.1  356.64  6692.4  358.27
#Mann=3,-1,0
  4274.2    0.15       0  4769.5    0.05       0  4773.5    0.15       0
Bank Sta=4769.5,4773.5
Exp/Cntr=0.3,0.1

Type RM Length L Ch R = 1,607,0,0,0
BEGIN DESCRIPTION:
Caney Creek T 29 1.0
END DESCRIPTION:
XS GIS Cut Line= 3
      2745925.97      6775160.97      2745176.00      6774261.00
      2743676.04      6773811.01
#Sta/Elev= 29
  3833.6  334.01  3836.8  334.01  3840.7  333.38  3847.2  332.24  3855.0  331.84
  3861.5  331.13  3869.4  330.44  3875.9  329.77  3883.7  329.32  3890.2  328.51
  3898.0  327.61  3904.5  326.76  3911.7  326.26  3918.8  325.87  3925.3  325.23
  3933.1  324.32  3939.6  324.15  3947.5  323.68  3954.0  323.52  3961.8  323.22
  3968.3  323.41  3974.1  322.00  3974.3  321.50  3977.8  321.50  3978.1  322.00
  4997.9  322.00  5001.8  322.00  5005.1  322.00  6571.1  322.00
#Mann=3,-1,0
  3833.6    0.15       0  3974.1    0.05       0  3978.1    0.15       0
Bank Sta=3974.1,3978.1
Exp/Cntr=0.3,0.1

Chan Stop Cuts=-1