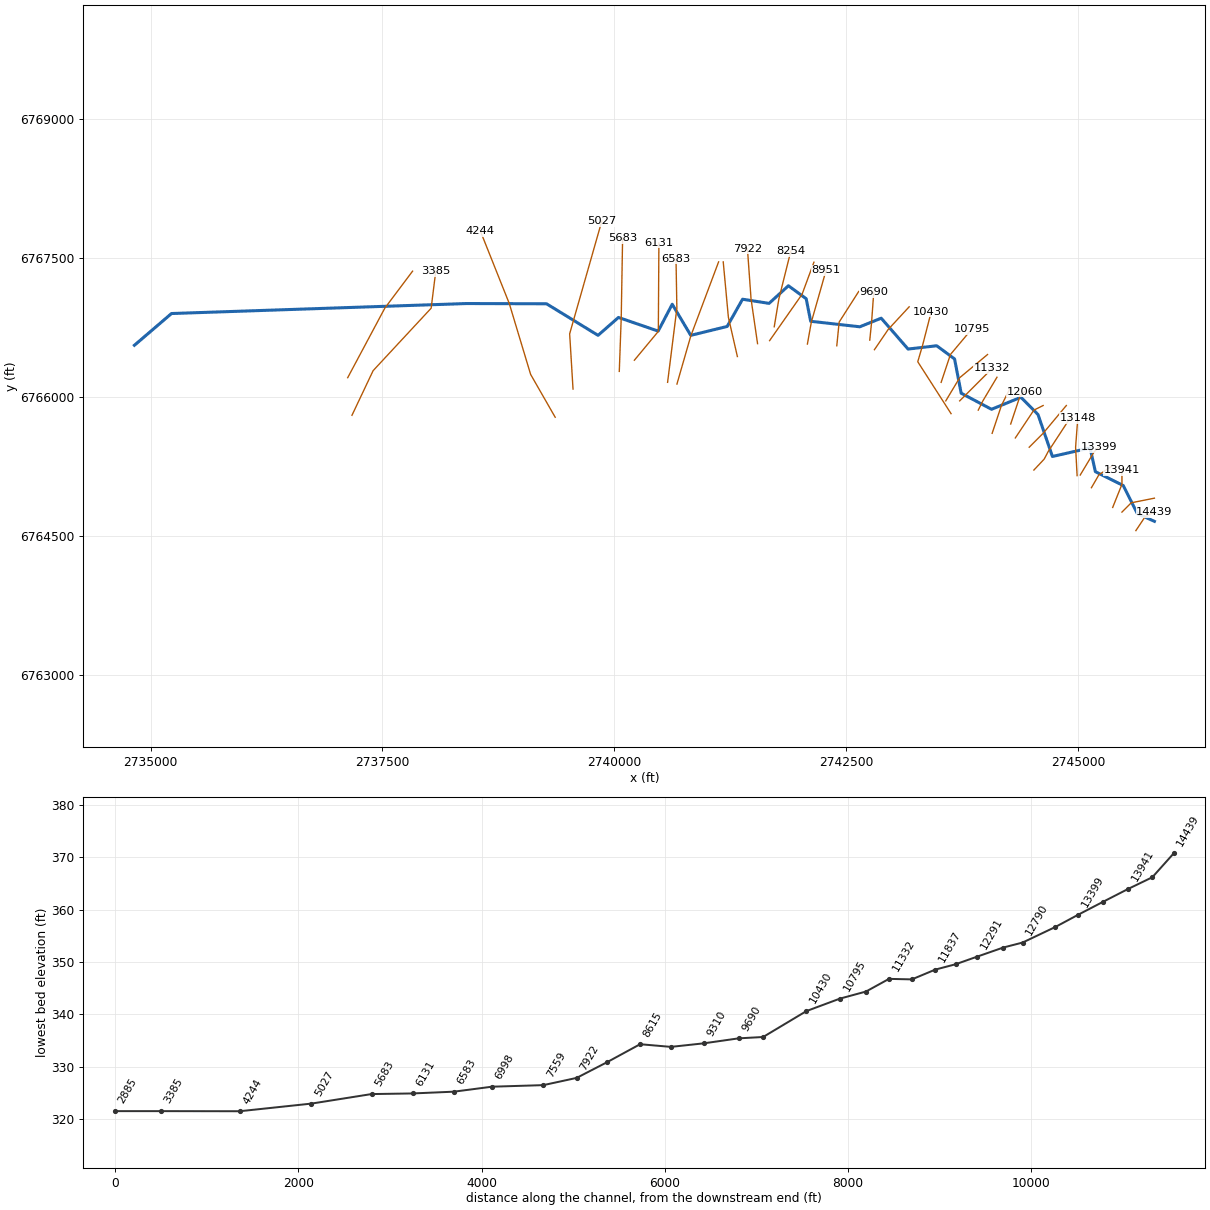
--- Caney Creek T 3.prj (project) ---

Proj Title=Caney Creek T 3 Base Level Engineering
Current Plan=p01
Default Exp/Contr=0.3,0.1
English Units
Geom File=g01
Flow File=f01
Plan File=p01
BEGIN DESCRIPTION:
Caney Creek T 3
END DESCRIPTION:

--- Caney Creek T 3.p01 (plan) ---

Plan Title=Multiple Run
Short Identifier=Multiple
Geom File=g01
Flow File=f01
Subcritical Flow
K Sum by GR= 0
Std Step Tol= 0.01
Critical Tol= 0.01
Num of Std Step Trials= 20
Max Error Tol= 0.3
Flow Tol Ratio= 0.001
Split Flow NTrial= 30
Split Flow Tol= 0.02
Split Flow Ratio= 0.02
Log Output Level= 0
Friction Slope Method= 1
Unsteady Friction Slope Method= 2
Unsteady Bridges Friction Slope Method= 1
Parabolic Critical Depth
Global Vel Dist=  1 , 1 , 1
Global Log Level= 0
CheckData=True
Encroach Param= -1, 0, 0, 0
BEGIN DESCRIPTION:
Multiple Run
END DESCRIPTION:

--- Caney Creek T 3.f01 (steady flow) ---

Flow Title=Multiple
Number of Profiles=7
Profile Names=10-year,25-year,50-year,1pct_min,100-year,1pct_plu,500-year
River Rch & RM= Caney Creek T 3,Reach-1,14439
     190     240     279     161     322     643     430
River Rch & RM= Caney Creek T 3,Reach-1,12790
     339     443     527     312     622    1242     869
River Rch & RM= Caney Creek T 3,Reach-1,9958
     568     768     932     563    1123    2240    1632
River Rch & RM= Caney Creek T 3,Reach-1,6998
     878    1200    1464     885    1765    3523    2568
Boundary for River Rch & Prof#=Caney Creek T 3,Reach-1,1
Up Type=0
Dn Type=3
Dn Slope=0.005
Boundary for River Rch & Prof#=Caney Creek T 3,Reach-1,2
Up Type=0
Dn Type=3
Dn Slope=0.005
Boundary for River Rch & Prof#=Caney Creek T 3,Reach-1,3
Up Type=0
Dn Type=3
Dn Slope=0.005
Boundary for River Rch & Prof#=Caney Creek T 3,Reach-1,4
Up Type=0
Dn Type=3
Dn Slope=0.005
Boundary for River Rch & Prof#=Caney Creek T 3,Reach-1,5
Up Type=0
Dn Type=3
Dn Slope=0.005
Boundary for River Rch & Prof#=Caney Creek T 3,Reach-1,6
Up Type=0
Dn Type=3
Dn Slope=0.005
Boundary for River Rch & Prof#=Caney Creek T 3,Reach-1,7
Up Type=0
Dn Type=3
Dn Slope=0.005

--- Caney Creek T 3.g01 (geometry) ---

Geom Title=Existing Conditions

River Reach=Caney Creek T 3,Reach-1
Reach XY= 30
      2745826.00      6764661.00      2745642.49      6764743.95
      2745490.00      6765047.38      2745189.22      6765197.33
      2745132.38      6765453.02      2744726.00      6765361.00
      2744570.64      6765813.70      2744386.38      6766000.03
      2744069.27      6765870.11      2743742.15      6766043.75
      2743670.64      6766413.70      2743478.28      6766555.87
      2743169.26      6766520.13      2742879.67      6766853.33
      2742648.75      6766760.50      2742118.94      6766820.01
      2742070.55      6767063.47      2741879.05      6767203.24
      2741670.07      6767013.23      2741384.32      6767058.03
      2741218.28      6766764.19      2740825.98      6766668.08
      2740625.97      6767003.92      2740474.38      6766714.12
      2740046.13      6766861.41      2739826.00      6766668.08
      2739270.56      6767008.81      2738407.66      6767011.39
      2735225.90      6766903.68      2734826.00      6766561.00

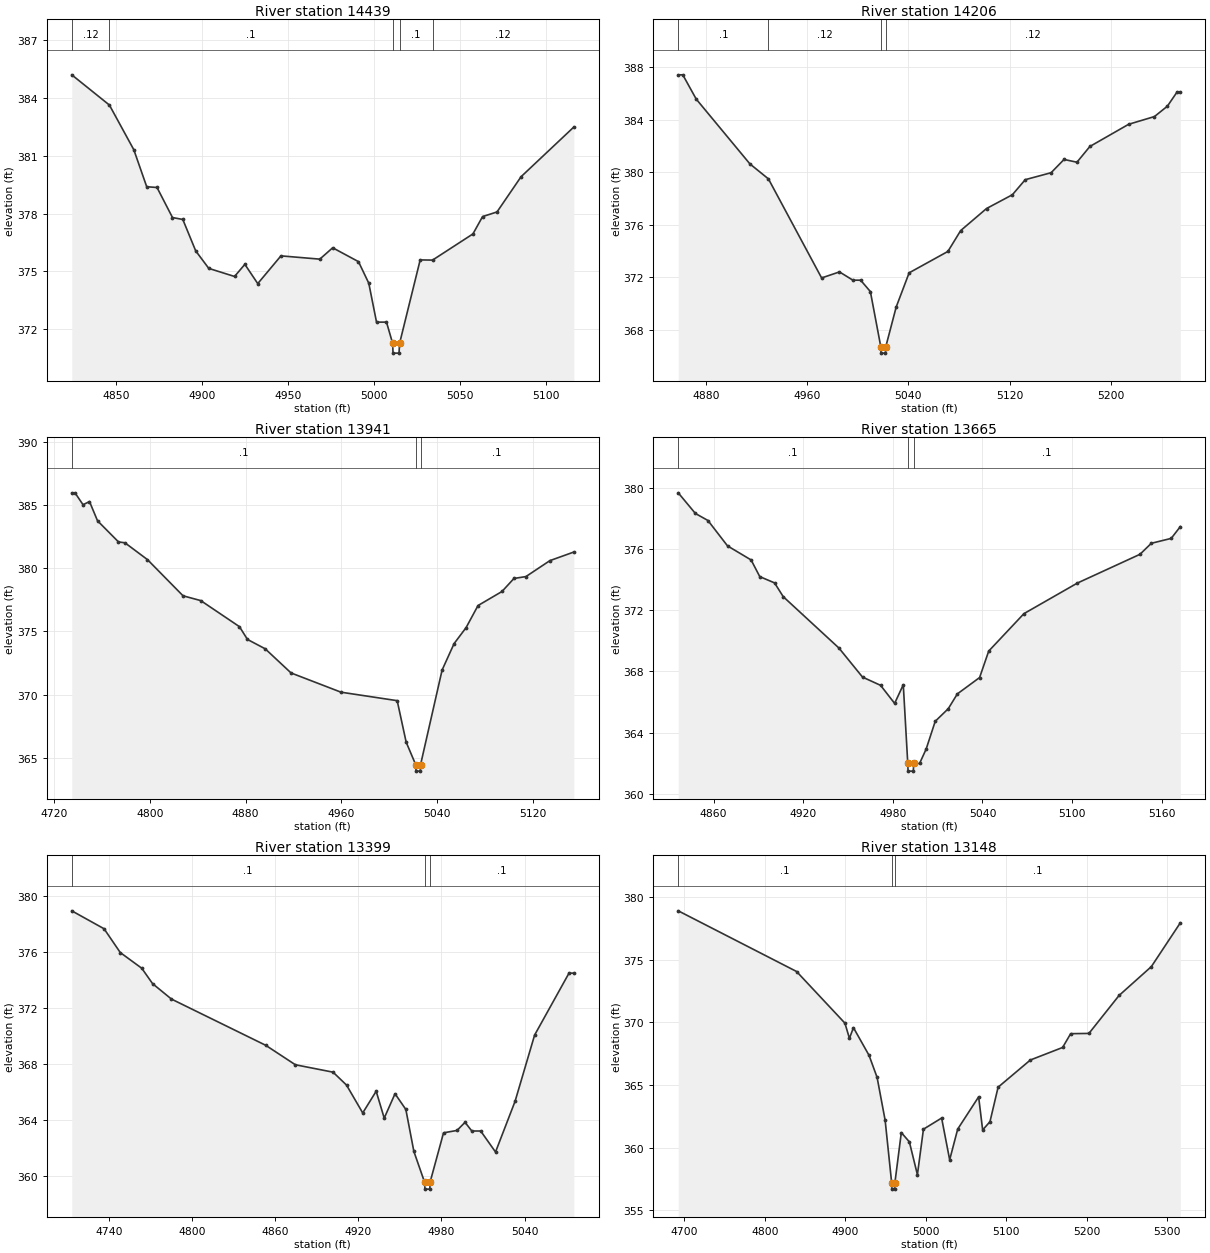
Type RM Length L Ch R = 1,14439,233,233,233
BEGIN DESCRIPTION:
Caney Creek T 3 31.0
END DESCRIPTION:
XS GIS Cut Line= 3
      2745625.98      6764560.97      2745726.00      6764711.00
      2745825.99      6764760.99
#Sta/Elev= 30
  4824.3  385.21  4846.2  383.64  4860.4  381.32  4867.9  379.40  4873.9  379.36
  4882.9  377.80  4888.9  377.70  4896.4  376.07  4904.0  375.16  4919.0  374.74
  4925.0  375.37  4932.5  374.37  4946.0  375.81  4968.6  375.64  4976.1  376.23
  4991.1  375.51  4997.1  374.39  5001.6  372.37  5007.4  372.37  5011.0  371.26
  5011.2  370.76  5014.7  370.76  5015.0  371.26  5027.0  375.60  5034.2  375.59
  5057.7  376.95  5063.3  377.85  5071.7  378.09  5085.7  379.92  5116.4  382.50
#Mann=5,-1,0
  4824.3    0.12       0  4846.2     0.1       0  5011.0    0.07       0
  5015.0     0.1       0  5034.2    0.12       0
Bank Sta=5011,5015
Exp/Cntr=0.3,0.1

Type RM Length L Ch R = 1,14206,265,265,265
BEGIN DESCRIPTION:
Caney Creek T 3 30.0
END DESCRIPTION:
XS GIS Cut Line= 3
      2745475.97      6764760.97      2745576.00      6764861.00
      2745825.98      6764911.00
#Sta/Elev= 30
  4858.3  387.41  4861.9  387.41  4872.5  385.56  4914.9  380.62  4929.5  379.48
  4971.5  371.93  4985.6  372.39  4996.2  371.76  5002.3  371.76  5010.0  370.89
  5018.2  366.70  5018.4  366.20  5021.9  366.20  5022.2  366.70  5030.4  369.72
  5040.6  372.32  5071.2  373.95  5081.3  375.54  5101.7  377.22  5122.1  378.27
  5132.3  379.42  5152.7  379.95  5162.9  380.96  5173.1  380.75  5183.3  381.95
  5213.9  383.64  5234.3  384.23  5244.5  385.02  5252.2  386.11  5254.7  386.11
#Mann=4,-1,0
  4858.3     0.1       0  4929.5    0.12       0  5018.2    0.07       0
  5022.2    0.12       0
Bank Sta=5018.2,5022.2
Exp/Cntr=0.3,0.1

Type RM Length L Ch R = 1,13941,276,276,276
BEGIN DESCRIPTION:
Caney Creek T 3 29.0
END DESCRIPTION:
XS GIS Cut Line= 3
      2745376.01      6764811.03      2745476.00      6765061.00
      2745476.00      6765210.98
#Sta/Elev= 30
  4734.9  385.96  4737.6  385.96  4744.3  385.02  4749.7  385.27  4756.4  383.75
  4773.9  382.08  4779.3  382.01  4798.1  380.68  4827.8  377.82  4842.6  377.44
  4874.9  375.38  4881.6  374.37  4896.4  373.63  4918.0  371.72  4959.7  370.20
  5006.6  369.53  5014.1  366.25  5022.1  364.46  5022.4  363.96  5025.9  363.96
  5026.1  364.46  5044.1  371.95  5054.1  374.04  5064.1  375.30  5074.1  377.05
  5094.1  378.16  5104.1  379.19  5114.1  379.34  5134.1  380.60  5154.1  381.28
#Mann=3,-1,0
  4734.9     0.1       0  5022.1    0.07       0  5026.1     0.1       0
Bank Sta=5022.1,5026.1
Exp/Cntr=0.3,0.1

Type RM Length L Ch R = 1,13665,266,266,266
BEGIN DESCRIPTION:
Caney Creek T 3 28.0
END DESCRIPTION:
XS GIS Cut Line= 3
      2745146.62      6765023.74      2745226.00      6765161.00
      2745371.92      6765262.31
#Sta/Elev= 30
  4836.3  379.68  4847.8  378.33  4856.2  377.87  4869.3  376.21  4885.1  375.29
  4890.9  374.20  4900.8  373.79  4906.6  372.89  4943.9  369.53  4959.7  367.63
  4971.8  367.09  4981.2  365.91  4987.0  367.13  4990.0  361.98  4990.2  361.48
  4993.7  361.48  4994.0  361.98  4997.9  361.98  5002.3  362.92  5008.4  364.74
  5017.1  365.56  5023.2  366.53  5038.1  367.60  5044.2  369.33  5067.8  371.78
  5103.6  373.78  5145.5  375.66  5153.1  376.38  5166.4  376.70  5172.5  377.47
#Mann=3,-1,0
  4836.3     0.1       0  4990.0    0.07       0  4994.0     0.1       0
Bank Sta=4990,4994
Exp/Cntr=0.3,0.1

Type RM Length L Ch R = 1,13399,251,251,251
BEGIN DESCRIPTION:
Caney Creek T 3 27.0
END DESCRIPTION:
XS GIS Cut Line= 3
      2745026.02      6765161.03      2745176.00      6765411.00
      2745225.98      6765460.98
#Sta/Elev= 30
  4713.3  378.93  4736.6  377.65  4748.3  375.95  4763.8  374.83  4771.6  373.73
  4785.2  372.63  4853.2  369.33  4874.6  367.94  4901.8  367.41  4911.5  366.49
  4923.2  364.50  4932.9  366.05  4938.7  364.13  4946.5  365.87  4954.3  364.75
  4960.1  361.75  4967.8  359.56  4968.1  359.06  4971.6  359.06  4971.8  359.56
  4981.5  363.08  4991.2  363.25  4997.0  363.83  5001.9  363.21  5008.3  363.21
  5019.0  361.71  5033.1  365.33  5047.2  370.06  5072.0  374.48  5075.5  374.48
#Mann=3,-1,0
  4713.3     0.1       0  4967.8    0.07       0  4971.8     0.1       0
Bank Sta=4967.8,4971.8
Exp/Cntr=0.3,0.1

Type RM Length L Ch R = 1,13148,358,358,358
BEGIN DESCRIPTION:
Caney Creek T 3 26.0
END DESCRIPTION:
XS GIS Cut Line= 3
      2744992.37      6765154.12      2744976.00      6765461.00
      2744999.67      6765776.90
#Sta/Elev= 30
  4692.5  378.90  4839.6  374.06  4899.7  369.94  4905.3  368.73  4910.3  369.58
  4929.7  367.37  4939.7  365.61  4949.7  362.19  4957.8  357.20  4958.0  356.70
  4961.5  356.70  4961.8  357.20  4969.8  361.21  4979.8  360.47  4989.8  357.85
  4997.3  361.48  5019.9  362.37  5029.9  359.04  5039.9  361.49  5065.9  364.06
  5070.9  361.42  5080.0  362.08  5090.1  364.83  5130.2  367.00  5170.3  368.00
  5180.3  369.10  5203.0  369.12  5240.5  372.15  5280.6  374.45  5316.6  377.94
#Mann=3,-1,0
  4692.5     0.1       0  4957.8    0.07       0  4961.8     0.1       0
Bank Sta=4957.8,4961.8
Exp/Cntr=0.3,0.1

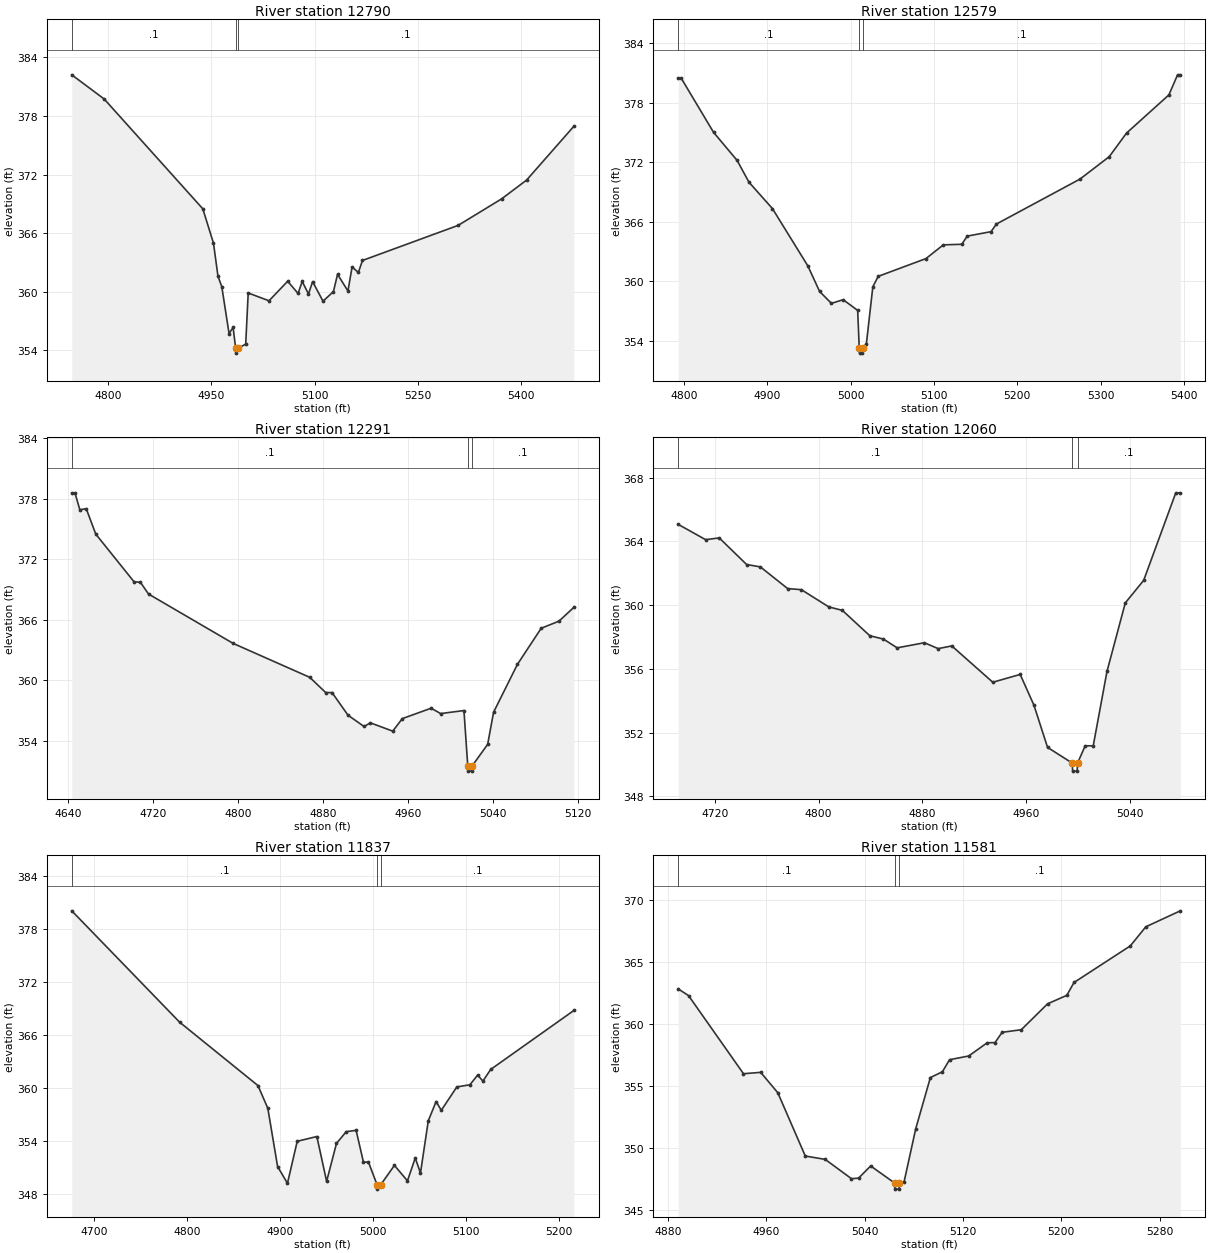
Type RM Length L Ch R = 1,12790,211,211,211
BEGIN DESCRIPTION:
Caney Creek T 3 25.0
END DESCRIPTION:
XS GIS Cut Line= 4
      2744526.15      6765214.39      2744637.36      6765332.58
      2744679.39      6765412.40      2744940.03      6765811.06
#Sta/Elev= 30
  4747.5  382.22  4794.6  379.74  4937.7  368.50  4953.2  364.98  4959.7  361.61
  4965.3  360.51  4975.8  355.73  4981.7  356.35  4985.4  354.22  4985.6  353.72
  4989.4  354.22  5000.0  354.65  5003.6  359.88  5033.8  359.08  5060.9  361.08
  5076.0  359.83  5082.0  361.06  5091.1  359.78  5097.1  361.04  5112.2  359.04
  5127.3  360.02  5133.3  361.79  5148.4  360.08  5154.4  362.55  5163.5  361.98
  5169.5  363.21  5308.3  366.80  5371.5  369.52  5407.7  371.44  5476.3  376.95
#Mann=3,-1,0
  4747.5     0.1       0  4985.4    0.07       0  4989.4     0.1       0
Bank Sta=4985.4,4989.4
Exp/Cntr=0.3,0.1

Type RM Length L Ch R = 1,12579,288,288,288
BEGIN DESCRIPTION:
Caney Creek T 3 24.0
END DESCRIPTION:
XS GIS Cut Line= 3
      2744475.99      6765460.99      2744626.00      6765611.00
      2744876.03      6765911.03
#Sta/Elev= 30
  4792.9  380.46  4796.4  380.46  4835.3  375.00  4863.6  372.17  4877.8  369.98
  4906.0  367.32  4948.5  361.55  4962.6  358.98  4976.8  357.78  4990.9  358.15
  5008.3  357.07  5010.2  353.27  5010.5  352.77  5014.0  352.77  5014.2  353.27
  5018.7  353.67  5026.5  359.45  5033.0  360.50  5090.3  362.29  5111.1  363.67
  5133.3  363.73  5139.8  364.55  5168.4  365.00  5174.9  365.77  5275.1  370.29
  5310.3  372.55  5331.1  374.93  5381.9  378.77  5392.3  380.79  5395.6  380.79
#Mann=3,-1,0
  4792.9     0.1       0  5010.2    0.07       0  5014.2     0.1       0
Bank Sta=5010.2,5014.2
Exp/Cntr=0.3,0.1

Type RM Length L Ch R = 1,12291,231,231,231
BEGIN DESCRIPTION:
Caney Creek T 3 23.0
END DESCRIPTION:
XS GIS Cut Line= 3
      2744325.98      6765560.96      2744526.00      6765861.00
      2744626.00      6765911.00
#Sta/Elev= 30
  4643.7  378.57  4646.7  378.57  4651.3  376.89  4657.3  377.00  4666.3  374.48
  4702.3  369.76  4708.3  369.71  4715.9  368.55  4795.5  363.66  4867.6  360.30
  4882.6  358.79  4888.6  358.79  4903.6  356.55  4918.7  355.43  4924.7  355.79
  4945.7  354.97  4954.7  356.21  4981.8  357.24  4990.8  356.71  5012.7  357.01
  5016.3  351.51  5016.5  351.01  5020.0  351.01  5020.3  351.51  5035.0  353.66
  5040.6  356.85  5063.0  361.58  5085.4  365.16  5102.1  365.86  5116.1  367.23
#Mann=3,-1,0
  4643.7     0.1       0  5016.3    0.07       0  5020.3     0.1       0
Bank Sta=5016.3,5020.3
Exp/Cntr=0.3,0.1

Type RM Length L Ch R = 1,12060,223,223,223
BEGIN DESCRIPTION:
Caney Creek T 3 22.0
END DESCRIPTION:
XS GIS Cut Line= 3
      2744276.00      6765710.99      2744376.00      6766011.00
      2744425.97      6766060.97
#Sta/Elev= 30
  4691.9  365.07  4713.0  364.11  4723.5  364.22  4744.6  362.55  4755.2  362.40
  4776.2  361.04  4786.8  360.97  4807.9  359.89  4818.4  359.67  4839.5  358.08
  4850.0  357.87  4860.6  357.32  4881.6  357.64  4892.2  357.27  4902.7  357.44
  4934.3  355.16  4955.4  355.65  4966.0  353.72  4976.5  351.07  4995.6  350.08
  4995.8  349.58  4999.3  349.58  4999.6  350.08  5005.5  351.17  5011.7  351.17
  5022.3  355.84  5036.4  360.14  5050.6  361.56  5075.3  367.05  5078.8  367.05
#Mann=3,-1,0
  4691.9     0.1       0  4995.6    0.07       0  4999.6     0.1       0
Bank Sta=4995.6,4999.6
Exp/Cntr=0.3,0.1

Type RM Length L Ch R = 1,11837,256,256,256
BEGIN DESCRIPTION:
Caney Creek T 3 21.0
END DESCRIPTION:
XS GIS Cut Line= 3
      2744076.01      6765611.03      2744176.00      6765911.00
      2744276.00      6766111.00
#Sta/Elev= 30
  4676.1  380.08  4792.0  367.47  4876.3  360.28  4886.9  357.70  4897.4  351.10
  4908.0  349.21  4918.5  353.97  4939.6  354.51  4950.1  349.43  4960.7  353.73
  4971.2  355.06  4981.8  355.21  4989.7  351.61  4995.1  351.61  5004.3  349.05
  5004.5  348.55  5008.3  349.05  5023.0  351.24  5037.0  349.49  5045.4  352.08
  5051.0  350.37  5059.4  356.29  5067.8  358.47  5073.4  357.48  5090.1  360.13
  5104.1  360.37  5112.5  361.47  5118.1  360.79  5126.5  362.11  5215.9  368.79
#Mann=3,-1,0
  4676.1     0.1       0  5004.3    0.07       0  5008.3     0.1       0
Bank Sta=5004.3,5008.3
Exp/Cntr=0.3,0.1

Type RM Length L Ch R = 1,11581,249,249,249
BEGIN DESCRIPTION:
Caney Creek T 3 20.0
END DESCRIPTION:
XS GIS Cut Line= 3
      2743926.00      6765861.01      2743976.00      6765961.00
      2744127.89      6766216.00
#Sta/Elev= 30
  4888.2  362.83  4896.6  362.29  4941.3  355.99  4955.3  356.10  4969.2  354.46
  4991.6  349.35  5007.8  349.08  5029.2  347.52  5035.0  347.57  5044.8  348.55
  5064.2  347.18  5064.5  346.68  5068.0  346.68  5068.2  347.18  5072.0  347.27
  5081.5  351.56  5093.4  355.68  5103.2  356.15  5109.0  357.12  5124.6  357.42
  5139.7  358.49  5146.0  358.50  5151.8  359.33  5167.4  359.54  5188.8  361.63
  5204.4  362.31  5210.3  363.35  5256.1  366.30  5268.7  367.84  5296.8  369.13
#Mann=3,-1,0
  4888.2     0.1       0  5064.2    0.07       0  5068.2     0.1       0
Bank Sta=5064.2,5068.2
Exp/Cntr=0.3,0.1

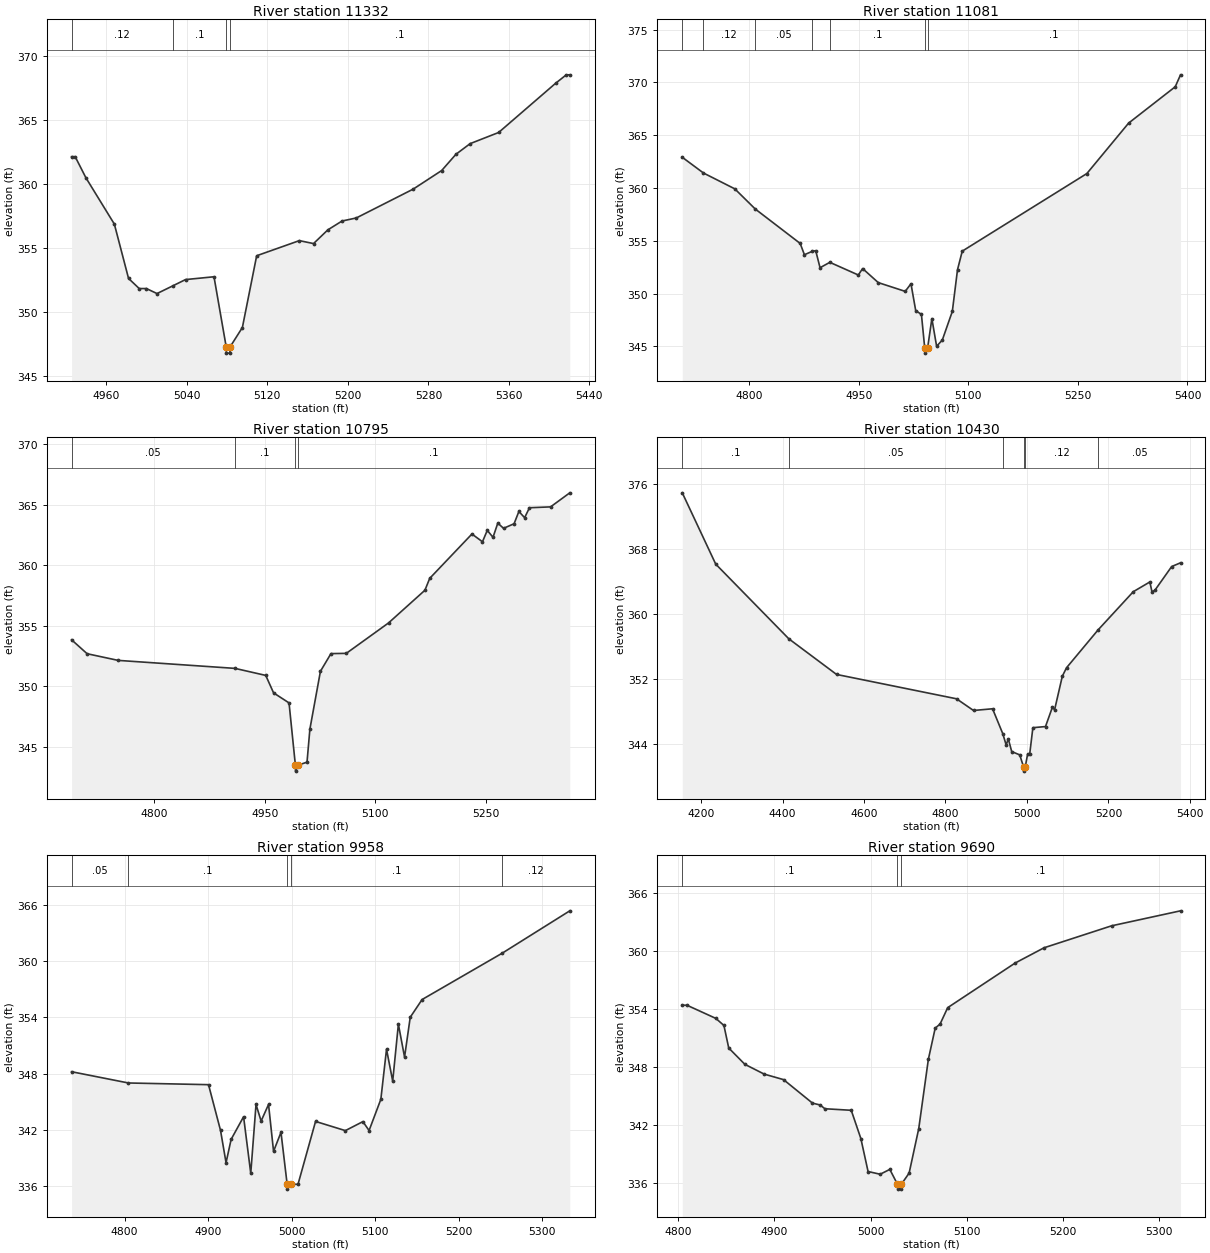
Type RM Length L Ch R = 1,11332,251,251,251
BEGIN DESCRIPTION:
Caney Creek T 3 19.0
END DESCRIPTION:
XS GIS Cut Line= 3
      2743725.98      6765960.98      2743776.00      6766011.00
      2744075.99      6766310.99
#Sta/Elev= 30
  4925.5  362.11  4929.1  362.11  4939.7  360.47  4968.0  356.85  4982.1  352.61
  4992.7  351.82  4999.8  351.82  5010.4  351.43  5025.8  352.02  5038.7  352.52
  5067.0  352.74  5079.1  347.28  5079.3  346.78  5082.8  346.78  5083.1  347.28
  5095.2  348.78  5109.4  354.38  5151.8  355.56  5165.9  355.33  5180.1  356.40
  5194.2  357.09  5208.4  357.33  5264.9  359.58  5293.2  361.03  5307.4  362.30
  5321.5  363.13  5349.8  364.00  5406.4  367.84  5417.0  368.50  5420.5  368.50
#Mann=4,-1,0
  4925.5    0.12       0  5025.8     0.1       0  5079.1    0.07       0
  5083.1     0.1       0
Bank Sta=5079.1,5083.1
Exp/Cntr=0.3,0.1

Type RM Length L Ch R = 1,11081,286,286,286
BEGIN DESCRIPTION:
Caney Creek T 3 18.0
END DESCRIPTION:
XS GIS Cut Line= 3
      2743575.98      6765960.97      2743726.00      6766211.00
      2744026.01      6766461.01
#Sta/Elev= 30
  4708.4  362.91  4737.4  361.42  4780.3  359.92  4808.3  358.01  4869.8  354.75
  4875.6  353.68  4886.6  354.01  4891.1  354.06  4897.0  352.45  4910.4  352.96
  4949.4  351.76  4955.3  352.37  4976.7  351.04  5013.6  350.21  5021.5  350.93
  5028.0  348.38  5035.8  348.03  5040.3  344.86  5040.5  344.36  5044.3  344.86
  5050.1  347.63  5056.6  345.01  5064.4  345.60  5078.1  348.31  5085.2  352.26
  5091.7  354.02  5262.3  361.37  5319.5  366.15  5383.3  369.59  5390.5  370.72
#Mann=7,-1,0
  4708.4     0.1       0  4737.4    0.12       0  4808.3    0.05       0
  4886.6    0.12       0  4910.4     0.1       0  5040.3    0.07       0
  5044.3     0.1       0
Bank Sta=5040.3,5044.3
Exp/Cntr=0.3,0.1

Type RM Length L Ch R = 1,10795,365,365,365
BEGIN DESCRIPTION:
Caney Creek T 3 17.0
END DESCRIPTION:
XS GIS Cut Line= 3
      2743526.00      6766161.00      2743626.00      6766461.00
      2743857.04      6766736.91
#Sta/Elev= 30
  4687.9  353.84  4709.0  352.69  4751.1  352.14  4909.7  351.48  4951.4  350.90
  4962.0  349.46  4983.0  348.63  4991.6  343.50  4991.8  343.00  4995.6  343.50
  5007.4  343.74  5011.3  346.47  5025.6  351.24  5039.9  352.70  5060.7  352.72
  5118.0  355.23  5167.4  357.93  5173.9  358.91  5231.2  362.57  5245.5  361.93
  5252.0  362.87  5259.8  362.30  5266.3  363.47  5274.1  363.04  5288.4  363.42
  5294.9  364.43  5302.7  363.92  5309.3  364.74  5337.9  364.81  5364.0  365.97
#Mann=4,-1,0
  4687.9    0.05       0  4909.7     0.1       0  4991.6    0.07       0
  4995.6     0.1       0
Bank Sta=4991.6,4995.6
Exp/Cntr=0.3,0.1

Type RM Length L Ch R = 1,10430,472,472,472
BEGIN DESCRIPTION:
Caney Creek T 3 16.0
END DESCRIPTION:
XS GIS Cut Line= 4
      2743632.92      6765823.19      2743273.80      6766383.29
      2743326.00      6766561.00      2743418.96      6766922.06
#Sta/Elev= 30
  4153.7  374.90  4235.8  366.12  4415.3  356.92  4532.5  352.53  4827.1  349.53
  4868.8  348.09  4915.6  348.30  4940.7  345.23  4949.0  343.84  4954.2  344.60
  4962.6  343.03  4982.4  342.62  4991.8  341.12  4992.1  340.62  4995.8  341.12
  5001.7  342.72  5006.8  342.72  5014.6  345.97  5045.6  346.11  5062.7  348.52
  5067.9  348.17  5086.9  352.31  5097.2  353.35  5174.8  358.02  5261.1  362.72
  5301.8  363.92  5307.0  362.72  5314.1  362.89  5355.4  365.82  5377.1  366.28
#Mann=6,-1,0
  4153.7     0.1       0  4415.3    0.05       0  4940.7    0.12       0
  4991.8    0.07       0  4995.8    0.12       0  5174.8    0.05       0
Bank Sta=4991.8,4995.8
Exp/Cntr=0.3,0.1

Type RM Length L Ch R = 1,9958,268,268,268
BEGIN DESCRIPTION:
Caney Creek T 3 15.0
END DESCRIPTION:
XS GIS Cut Line= 3
      2742806.61      6766513.51      2742954.78      6766731.41
      2743181.07      6766975.98
#Sta/Elev= 30
  4736.5  348.19  4804.6  346.99  4900.5  346.81  4914.9  341.93  4921.5  338.49
  4927.6  340.98  4942.5  343.39  4951.1  337.36  4957.4  344.70  4963.5  342.93
  4972.4  344.70  4978.4  339.70  4987.3  341.73  4994.7  336.17  4995.0  335.67
  4998.7  336.17  5007.7  336.19  5028.7  342.89  5064.4  341.91  5085.4  342.87
  5092.8  341.92  5106.9  345.25  5113.7  350.59  5121.1  347.19  5127.9  353.26
  5135.3  349.75  5142.1  354.00  5156.3  355.89  5252.2  360.83  5333.2  365.35
#Mann=5,-1,0
  4736.5    0.05       0  4804.6     0.1       0  4994.7    0.07       0
  4998.7     0.1       0  5252.2    0.12       0
Bank Sta=4994.7,4998.7
Exp/Cntr=0.3,0.1

Type RM Length L Ch R = 1,9690,380,380,380
BEGIN DESCRIPTION:
Caney Creek T 3 14.0
END DESCRIPTION:
XS GIS Cut Line= 3
      2742756.31      6766616.24      2742776.00      6766811.00
      2742799.22      6767132.51
#Sta/Elev= 30
  4804.2  354.42  4809.1  354.42  4839.1  353.06  4847.5  352.33  4852.5  350.00
  4869.3  348.31  4889.4  347.30  4909.5  346.73  4939.6  344.30  4947.5  344.11
  4952.5  343.72  4979.9  343.56  4989.9  340.64  4997.4  337.23  5010.0  336.95
  5020.0  337.45  5028.0  335.91  5028.3  335.41  5031.8  335.41  5032.0  335.91
  5040.1  337.07  5050.1  341.67  5060.1  348.83  5067.2  352.05  5072.3  352.48
  5080.2  354.17  5150.3  358.78  5180.4  360.36  5250.6  362.63  5322.3  364.18
#Mann=3,-1,0
  4804.2     0.1       0  5028.0    0.07       0  5032.0     0.1       0
Bank Sta=5028,5032
Exp/Cntr=0.3,0.1

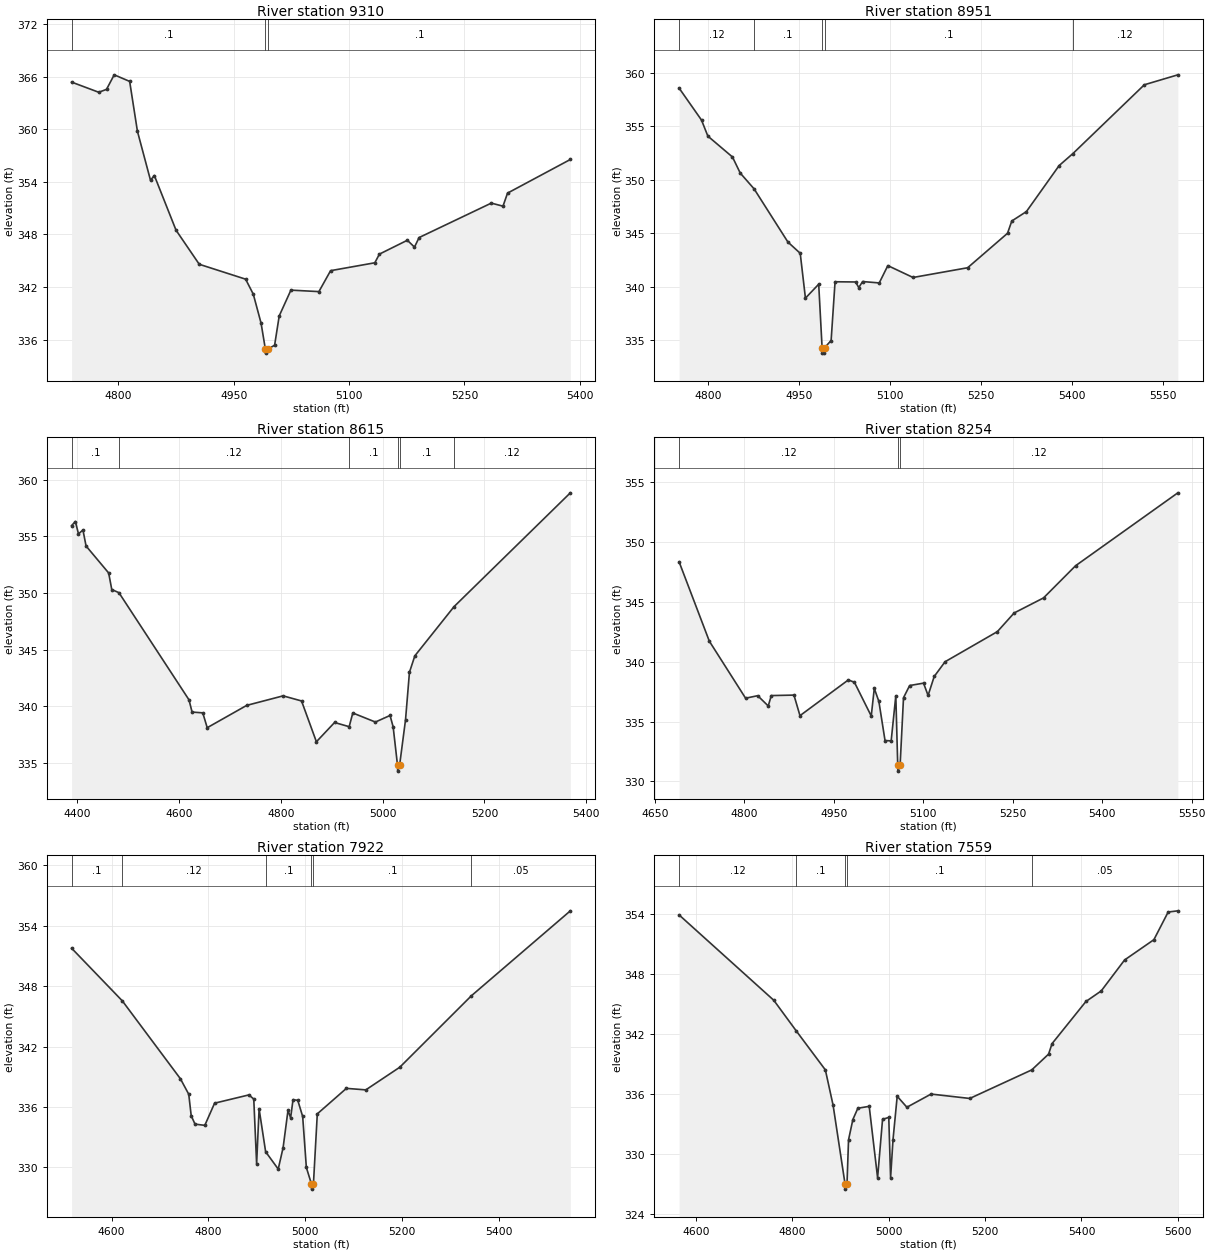
Type RM Length L Ch R = 1,9310,359,359,359
BEGIN DESCRIPTION:
Caney Creek T 3 13.0
END DESCRIPTION:
XS GIS Cut Line= 3
      2742400.68      6766555.83      2742426.00      6766811.00
      2742637.02      6767141.56
#Sta/Elev= 30
  4739.1  365.39  4774.4  364.23  4784.5  364.56  4794.5  366.22  4814.6  365.47
  4824.7  359.78  4841.7  354.19  4846.7  354.73  4874.9  348.49  4905.1  344.60
  4965.4  342.90  4975.4  341.18  4985.5  337.88  4991.0  334.96  4991.3  334.46
  4995.0  334.96  5003.1  335.36  5009.1  338.71  5024.3  341.65  5060.7  341.48
  5075.9  343.87  5133.4  344.77  5139.4  345.76  5175.7  347.34  5185.0  346.56
  5191.0  347.65  5284.9  351.58  5300.1  351.23  5306.0  352.72  5387.7  356.56
#Mann=3,-1,0
  4739.1     0.1       0  4991.0    0.07       0  4995.0     0.1       0
Bank Sta=4991,4995
Exp/Cntr=0.3,0.1

Type RM Length L Ch R = 1,8951,336,336,336
BEGIN DESCRIPTION:
Caney Creek T 3 12.0
END DESCRIPTION:
XS GIS Cut Line= 3
      2742083.67      6766574.24      2742126.00      6766811.00
      2742285.54      6767371.32
#Sta/Elev= 30
  4751.5  358.55  4788.5  355.56  4799.0  354.06  4839.6  352.11  4852.4  350.61
  4875.3  349.13  4931.1  344.16  4951.4  343.11  4960.0  338.92  4981.9  340.22
  4987.5  334.28  4987.7  333.78  4991.2  333.78  4991.5  334.28  5002.4  334.96
  5008.9  340.45  5042.8  340.43  5048.0  339.91  5054.4  340.47  5081.8  340.34
  5096.0  341.96  5137.6  340.85  5227.7  341.76  5293.5  344.98  5300.6  346.13
  5324.7  347.01  5378.7  351.31  5401.4  352.43  5519.3  358.86  5574.6  359.79
#Mann=5,-1,0
  4751.5    0.12       0  4875.3     0.1       0  4987.5    0.07       0
  4991.5     0.1       0  5401.4    0.12       0
Bank Sta=4987.5,4991.5
Exp/Cntr=0.3,0.1

Type RM Length L Ch R = 1,8615,361,361,361
BEGIN DESCRIPTION:
Caney Creek T 3 11.0
END DESCRIPTION:
XS GIS Cut Line= 3
      2741675.98      6766610.98      2742026.00      6767111.00
      2742154.03      6767457.55
#Sta/Elev= 30
  4389.1  355.95  4396.5  356.31  4402.6  355.22  4411.4  355.56  4417.5  354.15
  4461.9  351.77  4468.0  350.31  4482.1  350.03  4619.7  340.58  4625.8  339.50
  4646.8  339.43  4655.5  338.12  4733.1  340.09  4804.6  340.93  4840.8  340.48
  4870.0  336.88  4905.7  338.58  4934.4  338.21  4941.5  339.42  4985.9  338.62
  5014.7  339.20  5020.8  338.19  5029.4  334.79  5029.7  334.29  5033.4  334.79
  5045.1  338.82  5052.8  343.01  5063.4  344.46  5140.4  348.80  5368.9  358.84
#Mann=6,-1,0
  4389.1     0.1       0  4482.1    0.12       0  4934.4     0.1       0
  5029.4    0.07       0  5033.4     0.1       0  5140.4    0.12       0
Bank Sta=5029.4,5033.4
Exp/Cntr=0.3,0.1

Type RM Length L Ch R = 1,8254,332,332,332
BEGIN DESCRIPTION:
Caney Creek T 3 10.0
END DESCRIPTION:
XS GIS Cut Line= 3
      2741726.00      6766761.03      2741776.00      6767061.00
      2741904.80      6767577.37
#Sta/Elev= 30
  4690.6  348.36  4741.3  341.72  4802.1  336.95  4822.4  337.16  4840.1  336.30
  4845.2  337.17  4883.2  337.21  4893.3  335.49  4974.4  338.48  4984.6  338.28
  5012.8  335.46  5017.9  337.77  5025.6  336.68  5035.9  333.41  5046.2  333.38
  5054.0  337.16  5057.2  331.35  5057.4  330.85  5061.2  331.35  5066.9  336.99
  5077.2  338.01  5100.5  338.21  5108.1  337.18  5118.4  338.77  5136.6  340.00
  5224.3  342.52  5252.4  344.08  5301.7  345.34  5355.4  348.03  5526.9  354.13
#Mann=3,-1,0
  4690.6    0.12       0  5057.2    0.07       0  5061.2    0.12       0
Bank Sta=5057.2,5061.2
Exp/Cntr=0.3,0.1

Type RM Length L Ch R = 1,7922,363,363,363
BEGIN DESCRIPTION:
Caney Creek T 3 9.0
END DESCRIPTION:
XS GIS Cut Line= 3
      2741546.11      6766578.74      2741476.00      6767061.00
      2741437.09      6767602.27
#Sta/Elev= 30
  4517.6  351.76  4622.4  346.53  4742.2  338.81  4759.5  337.27  4764.6  335.13
  4772.5  334.30  4792.7  334.18  4812.9  336.38  4883.7  337.20  4893.8  336.79
  4899.7  330.36  4904.8  335.82  4918.3  331.56  4944.3  329.84  4954.4  331.97
  4964.5  335.67  4969.9  334.93  4974.9  336.73  4984.7  336.66  4994.8  335.06
  5002.4  330.00  5013.0  328.35  5013.2  327.85  5017.0  328.35  5025.0  335.32
  5085.1  337.85  5125.2  337.70  5195.4  339.95  5343.0  347.03  5547.6  355.47
#Mann=6,-1,0
  4517.6     0.1       0  4622.4    0.12       0  4918.3     0.1       0
  5013.0    0.07       0  5017.0     0.1       0  5343.0    0.05       0
Bank Sta=5013,5017
Exp/Cntr=0.3,0.1

Type RM Length L Ch R = 1,7559,561,561,561
BEGIN DESCRIPTION:
Caney Creek T 3 8.0
END DESCRIPTION:
XS GIS Cut Line= 3
      2741328.56      6766439.36      2741231.48      6766863.59
      2741176.00      6767461.02
#Sta/Elev= 30
  4564.8  353.93  4761.4  345.38  4807.9  342.32  4868.4  338.41  4884.5  334.86
  4909.3  326.97  4909.6  326.47  4913.3  326.97  4916.5  331.41  4925.5  333.44
  4935.8  334.57  4959.4  334.76  4976.8  327.61  4987.1  333.46  5000.0  333.65
  5003.8  327.61  5008.8  331.42  5017.5  335.77  5037.6  334.67  5087.8  335.99
  5168.1  335.55  5296.8  338.41  5331.7  339.99  5338.9  341.04  5409.2  345.26
  5441.0  346.32  5489.5  349.42  5550.3  351.45  5579.9  354.22  5600.0  354.34
#Mann=5,-1,0
  4564.8    0.12       0  4807.9     0.1       0  4909.3    0.07       0
  4913.3     0.1       0  5296.8    0.05       0
Bank Sta=4909.3,4913.3
Exp/Cntr=0.3,0.1

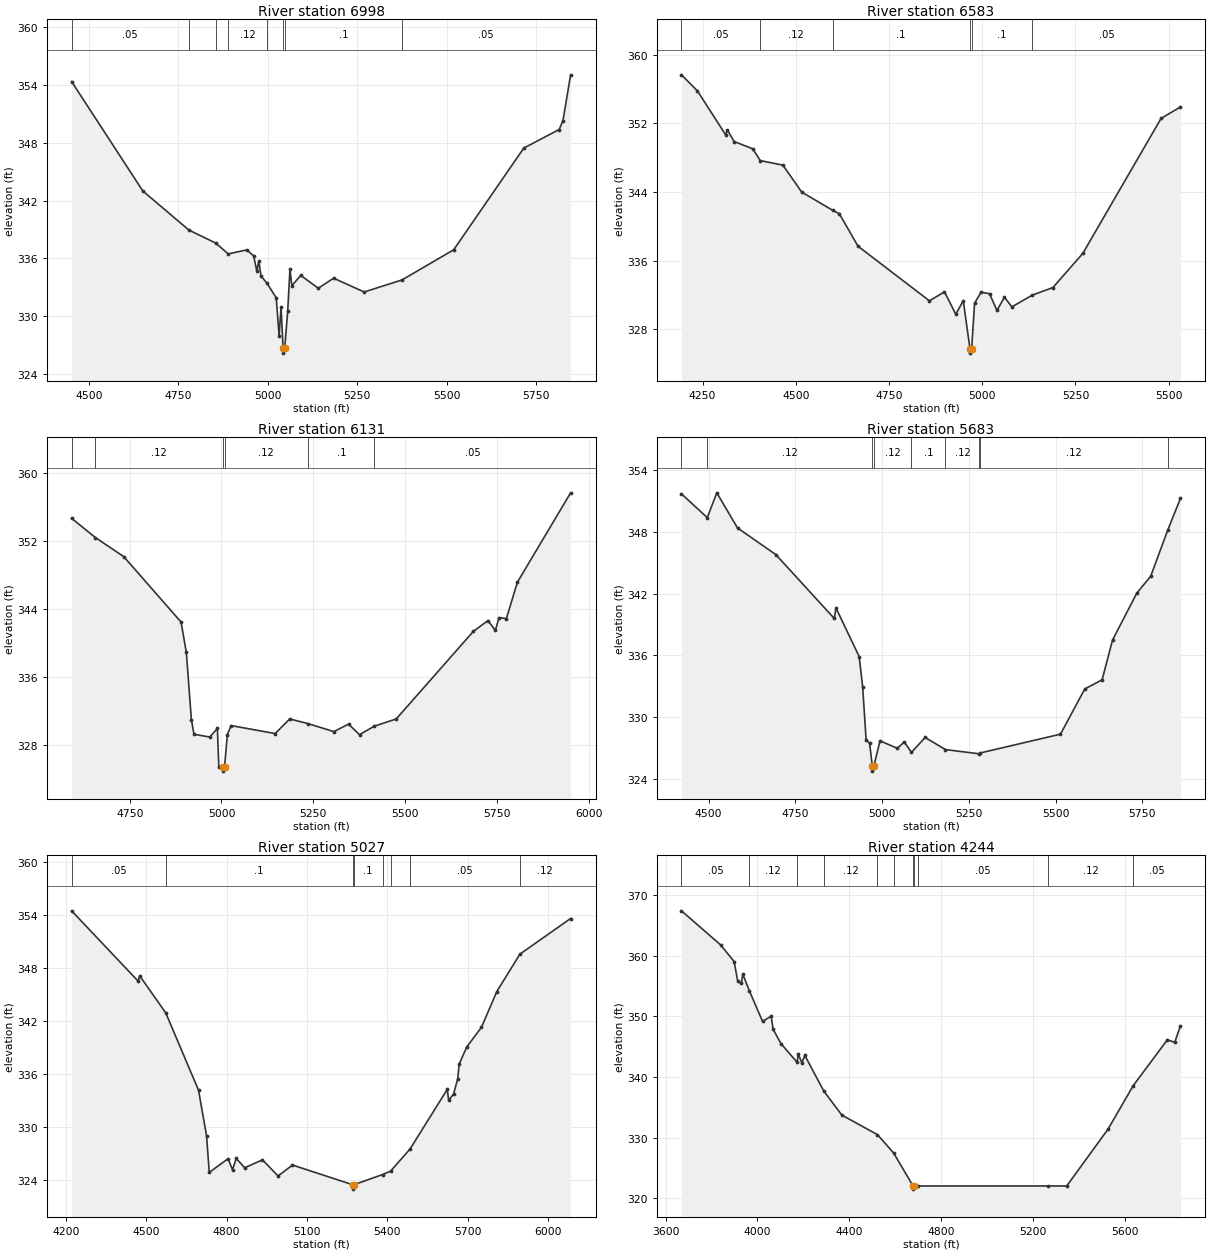
Type RM Length L Ch R = 1,6998,415,415,415
BEGIN DESCRIPTION:
Caney Creek T 3 7.0
END DESCRIPTION:
XS GIS Cut Line= 3
      2740676.69      6766142.40      2740826.00      6766661.00
      2741126.01      6767461.03
#Sta/Elev= 30
  4452.3  354.37  4651.2  343.01  4779.9  338.95  4854.9  337.60  4890.0  336.47
  4941.4  336.89  4960.7  336.28  4969.9  334.67  4975.1  335.75  4981.6  334.16
  4997.0  333.49  5024.0  331.91  5032.0  327.96  5037.4  330.94  5043.2  326.67
  5043.6  326.17  5047.6  326.67  5056.0  330.51  5062.3  334.89  5067.6  333.17
  5092.5  334.24  5141.5  332.91  5184.2  333.95  5269.6  332.52  5375.3  333.77
  5519.7  336.90  5715.5  347.46  5814.3  349.39  5825.0  350.30  5846.4  355.07
#Mann=8,-1,0
  4452.3    0.05       0  4779.9    0.12       0  4854.9     0.1       0
  4890.0    0.12       0  4997.0     0.1       0  5043.2    0.07       0
  5047.6     0.1       0  5375.3    0.05       0
Bank Sta=5043.2,5047.6
Exp/Cntr=0.3,0.1

Type RM Length L Ch R = 1,6583,452,452,452
BEGIN DESCRIPTION:
Caney Creek T 3 6.0
END DESCRIPTION:
XS GIS Cut Line= 3
      2740576.00      6766161.01      2740676.00      6766961.00
      2740666.68      6767493.00
#Sta/Elev= 30
  4193.5  357.64  4236.3  355.77  4311.9  350.66  4316.9  351.21  4334.6  349.87
  4385.0  349.02  4404.7  347.65  4465.6  347.12  4516.0  343.98  4598.6  341.87
  4616.8  341.46  4667.1  337.67  4858.6  331.31  4898.9  332.36  4929.2  329.75
  4949.3  331.33  4967.3  325.72  4967.7  325.22  4971.7  325.72  4979.6  331.04
  4997.2  332.32  5019.7  332.14  5039.7  330.19  5059.7  331.73  5079.7  330.61
  5134.5  331.98  5189.7  332.86  5269.8  336.83  5479.8  352.56  5531.8  353.90
#Mann=6,-1,0
  4193.5    0.05       0  4404.7    0.12       0  4598.6     0.1       0
  4967.3    0.07       0  4971.7     0.1       0  5134.5    0.05       0
Bank Sta=4967.3,4971.7
Exp/Cntr=0.3,0.1

Type RM Length L Ch R = 1,6131,448,448,448
BEGIN DESCRIPTION:
Caney Creek T 3 5.0
END DESCRIPTION:
XS GIS Cut Line= 3
      2740217.79      6766399.95      2740476.00      6766711.00
      2740482.20      6767666.02
#Sta/Elev= 30
  4591.8  354.62  4656.5  352.36  4733.7  350.12  4889.9  342.42  4904.3  338.85
  4918.1  330.93  4925.1  329.22  4968.1  328.89  4988.9  329.91  4992.8  325.39
  5003.8  325.38  5004.3  324.88  5008.3  325.38  5016.1  329.17  5026.1  330.24
  5146.1  329.30  5186.1  331.02  5236.3  330.46  5306.1  329.53  5346.1  330.41
  5376.1  329.17  5416.5  330.17  5476.1  331.02  5686.1  341.32  5726.1  342.59
  5746.1  341.43  5756.1  342.94  5776.1  342.82  5806.1  347.10  5951.1  357.62
#Mann=6,-1,0
  4591.8     0.1       0  4656.5    0.12       0  5003.8    0.07       0
  5008.3    0.12       0  5236.3     0.1       0  5416.5    0.05       0
Bank Sta=5003.8,5008.3
Exp/Cntr=0.3,0.1

Type RM Length L Ch R = 1,5683,656,656,656
BEGIN DESCRIPTION:
Caney Creek T 3 4.0
END DESCRIPTION:
XS GIS Cut Line= 3
      2740055.01      6766279.16      2740076.00      6766861.00
      2740090.78      6767716.75
#Sta/Elev= 30
  4421.9  351.69  4496.3  349.38  4523.8  351.79  4583.4  348.38  4693.9  345.79
  4862.2  339.59  4867.2  340.61  4934.1  335.88  4944.1  332.95  4954.1  327.79
  4964.1  327.46  4971.9  325.26  4972.3  324.76  4976.4  325.26  4994.1  327.70
  5044.1  326.98  5064.1  327.59  5084.8  326.58  5124.1  328.03  5182.8  326.85
  5280.8  326.44  5283.7  326.53  5514.2  328.35  5584.2  332.74  5634.2  333.63
  5664.2  337.49  5734.2  342.05  5774.2  343.68  5823.2  348.16  5860.0  351.25
#Mann=9,-1,0
  4421.9    0.05       0  4496.3    0.12       0  4971.9    0.07       0
  4976.4    0.12       0  5084.8     0.1       0  5182.8    0.12       0
  5280.8     0.1       0  5283.7    0.12       0  5823.2    0.05       0
Bank Sta=4971.9,4976.4
Exp/Cntr=0.3,0.1

Type RM Length L Ch R = 1,5027,783,783,783
BEGIN DESCRIPTION:
Mapping XS 849808ed
END DESCRIPTION:
XS GIS Cut Line= 3
      2739556.09      6766088.20      2739519.84      6766684.86
      2739866.45      6767901.08
#Sta/Elev= 30
  4221.6  354.49  4470.2  346.51  4475.2  347.15  4573.1  342.91  4695.3  334.15
  4725.3  328.98  4735.3  324.83  4805.5  326.39  4822.1  325.14  4836.1  326.42
  4867.3  325.36  4934.0  326.26  4992.1  324.43  5045.9  325.67  5270.6  323.44
  5271.1  322.94  5275.1  323.44  5382.0  324.59  5412.1  324.98  5484.5  327.48
  5623.7  334.25  5628.9  333.00  5647.2  333.73  5662.8  335.47  5668.0  337.11
  5696.6  339.07  5751.2  341.28  5808.5  345.34  5894.7  349.58  6084.0  353.62
#Mann=8,-1,0
  4221.6    0.05       0  4573.1     0.1       0  5270.6    0.07       0
  5275.1     0.1       0  5382.0    0.05       0  5412.1    0.12       0
  5484.5    0.05       0  5894.7    0.12       0
Bank Sta=5270.6,5275.1
Exp/Cntr=0.3,0.1

Type RM Length L Ch R = 1,4244,859,859,859
BEGIN DESCRIPTION:
Caney Creek T 3 3.0
END DESCRIPTION:
XS GIS Cut Line= 4
      2739363.63      6765784.43      2739098.90      6766246.63
      2738868.82      6767011.00      2738556.70      6767794.20
#Sta/Elev= 30
  3669.1  367.41  3839.6  361.79  3898.6  359.04  3914.4  355.76  3930.2  355.43
  3936.0  356.99  3965.3  354.18  4022.4  349.16  4059.7  350.02  4068.5  347.86
  4103.1  345.47  4173.1  342.41  4177.7  343.83  4193.5  342.30  4206.6  343.55
  4288.9  337.68  4368.1  333.69  4523.1  330.47  4593.6  327.44  4678.4  321.98
  4679.0  321.48  4683.2  321.98  4699.4  322.00  5264.2  322.00  5347.6  322.00
  5527.5  331.38  5637.2  338.55  5785.8  346.12  5818.1  345.71  5843.1  348.44
#Mann=11,-1,0
  3669.1    0.05       0  3965.3    0.12       0  4173.1    0.05       0
  4288.9    0.12       0  4523.1     0.1       0  4593.6    0.12       0
  4678.4    0.03       0  4683.2    0.12       0  4699.4    0.05       0
  5264.2    0.12       0  5637.2    0.05       0
Bank Sta=4678.4,4683.2
Exp/Cntr=0.3,0.1

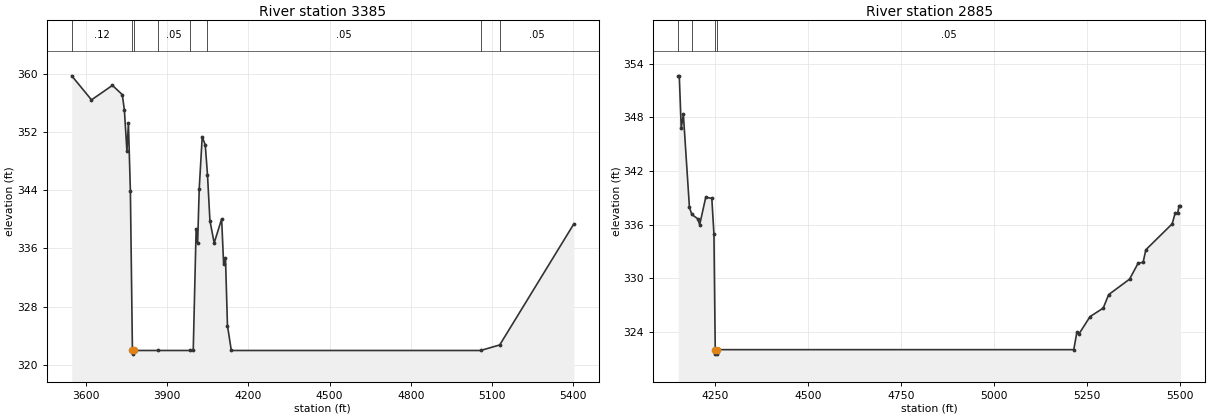
Type RM Length L Ch R = 1,3385,500,500,500
BEGIN DESCRIPTION:
Caney Creek T 3 2.0
END DESCRIPTION:
XS GIS Cut Line= 4
      2737172.10      6765805.19      2737400.30      6766287.16
      2738026.00      6766961.00      2738076.00      6767360.98
#Sta/Elev= 30
  3547.2  359.69  3620.1  356.39  3697.5  358.38  3733.9  357.11  3741.7  355.00
  3751.1  349.32  3756.6  353.20  3763.9  343.84  3771.4  322.00  3772.0  321.50
  3776.3  322.00  3864.7  322.00  3983.5  322.00  3996.2  322.00  4006.9  338.67
  4012.4  336.69  4018.3  344.17  4029.4  351.34  4040.7  350.19  4048.9  346.10
  4057.9  339.82  4073.6  336.75  4101.2  340.05  4108.5  333.87  4115.4  334.69
  4122.7  325.42  4136.9  322.00  5058.4  322.00  5129.1  322.76  5403.1  339.37
#Mann=8,-1,0
  3547.2    0.12       0  3771.4    0.03       0  3776.3    0.12       0
  3864.7    0.05       0  3983.5    0.12       0  4048.9    0.05       0
  5058.4    0.12       0  5129.1    0.05       0
Bank Sta=3771.4,3776.3
Exp/Cntr=0.3,0.1

Type RM Length L Ch R = 1,2885,0,0,0
BEGIN DESCRIPTION:
Caney Creek T 3 1.0
END DESCRIPTION:
XS GIS Cut Line= 3
      2737126.00      6766211.01      2737526.00      6766961.00
      2737826.00      6767361.01
#Sta/Elev= 30
  4150.0  352.65  4152.8  352.65  4158.1  346.79  4163.8  348.34  4180.1  337.93
  4186.6  337.13  4202.1  336.66  4207.7  335.99  4224.0  339.06  4240.3  338.93
  4246.0  334.93  4249.5  322.00  4250.1  321.50  4253.8  321.50  4254.5  322.00
  5213.5  322.00  5221.9  323.95  5228.1  323.80  5257.3  325.70  5292.7  326.65
  5307.3  328.16  5363.5  329.89  5386.5  331.67  5400.0  331.78  5407.3  333.18
  5478.1  336.08  5486.5  337.33  5492.7  337.28  5496.9  338.10  5500.0  338.10
#Mann=4,-1,0
  4150.0    0.12       0  4186.6    0.05       0  4249.5    0.03       0
  4254.5    0.05       0
Bank Sta=4249.5,4254.5
Exp/Cntr=0.3,0.1

Chan Stop Cuts=-1