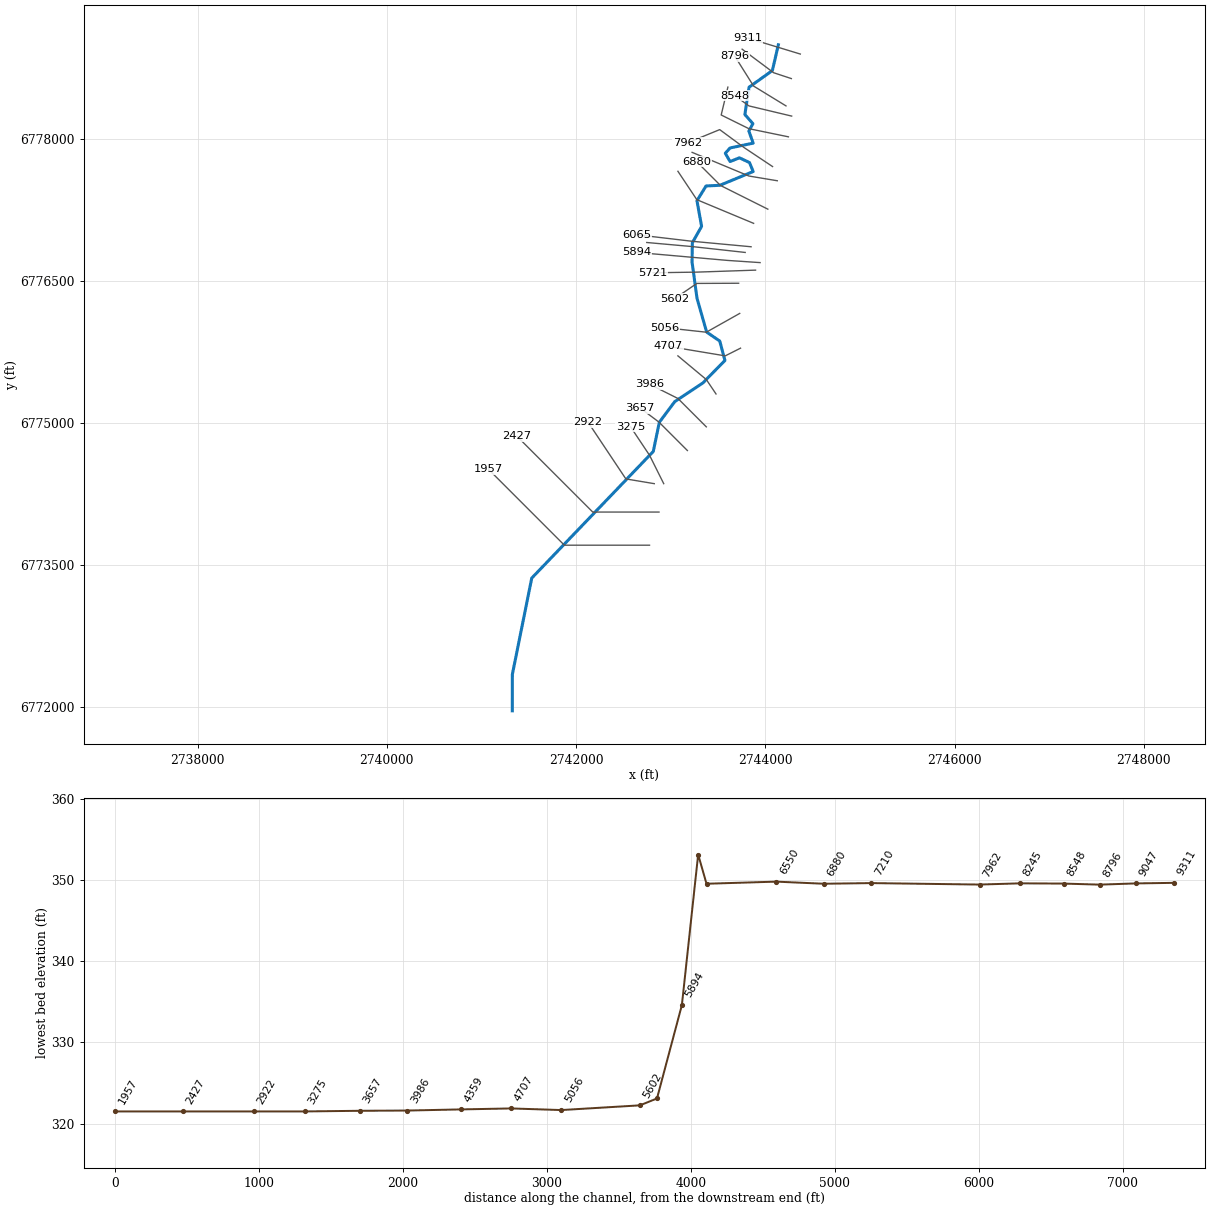
--- Caney Creek T 30.prj (project) ---

Proj Title=Caney Creek T 30 Base Level Engineering
Current Plan=p01
Default Exp/Contr=0.3,0.1
English Units
Geom File=g01
Flow File=f01
Plan File=p01
BEGIN DESCRIPTION:
Caney Creek T 30
END DESCRIPTION:

--- Caney Creek T 30.p01 (plan) ---

Plan Title=Multiple Run
Short Identifier=Multiple
Geom File=g01
Flow File=f01
Subcritical Flow
K Sum by GR= 0
Std Step Tol= 0.01
Critical Tol= 0.01
Num of Std Step Trials= 20
Max Error Tol= 0.3
Flow Tol Ratio= 0.001
Split Flow NTrial= 30
Split Flow Tol= 0.02
Split Flow Ratio= 0.02
Log Output Level= 0
Friction Slope Method= 1
Unsteady Friction Slope Method= 2
Unsteady Bridges Friction Slope Method= 1
Parabolic Critical Depth
Global Vel Dist=  1 , 1 , 1
Global Log Level= 0
CheckData=True
Encroach Param= -1, 0, 0, 0
BEGIN DESCRIPTION:
Multiple Run
END DESCRIPTION:

--- Caney Creek T 30.f01 (steady flow) ---

Flow Title=Multiple
Number of Profiles=7
Profile Names=10-year,25-year,50-year,1pct_min,100-year,1pct_plu,500-year
River Rch & RM= Caney Creek T 30,Reach-1,9311
     518     693     835     500     998    1990    1427
River Rch & RM= Caney Creek T 30,Reach-1,2427
     736     994    1203     722    1440    2873    2062
Boundary for River Rch & Prof#=Caney Creek T 30,Reach-1,1
Up Type=0
Dn Type=3
Dn Slope=0.005
Boundary for River Rch & Prof#=Caney Creek T 30,Reach-1,2
Up Type=0
Dn Type=3
Dn Slope=0.005
Boundary for River Rch & Prof#=Caney Creek T 30,Reach-1,3
Up Type=0
Dn Type=3
Dn Slope=0.005
Boundary for River Rch & Prof#=Caney Creek T 30,Reach-1,4
Up Type=0
Dn Type=3
Dn Slope=0.005
Boundary for River Rch & Prof#=Caney Creek T 30,Reach-1,5
Up Type=0
Dn Type=3
Dn Slope=0.005
Boundary for River Rch & Prof#=Caney Creek T 30,Reach-1,6
Up Type=0
Dn Type=3
Dn Slope=0.005
Boundary for River Rch & Prof#=Caney Creek T 30,Reach-1,7
Up Type=0
Dn Type=3
Dn Slope=0.005

--- Caney Creek T 30.g01 (geometry) ---

Geom Title=Existing Conditions

River Reach=Caney Creek T 30,Reach-1
Reach XY= 30
      2744137.01      6778997.11      2744074.03      6778725.09
      2743827.62      6778549.18      2743783.34      6778260.90
      2743868.15      6778164.41      2743825.70      6778086.03
      2743871.03      6777958.42      2743627.19      6777907.55
      2743576.61      6777851.33      2743627.37      6777764.07
      2743726.00      6777803.44      2743832.43      6777753.00
      2743871.06      6777658.45      2743520.07      6777513.25
      2743373.30      6777505.64      2743277.20      6777350.50
      2743326.19      6777079.43      2743228.35      6776905.48
      2743225.55      6776700.81      2743277.38      6776320.66
      2743379.52      6775962.28      2743518.25      6775867.45
      2743572.88      6775662.62      2743339.24      6775424.61
      2743042.65      6775227.67      2742879.61      6775009.50
      2742815.52      6774701.20      2741531.52      6773363.43
      2741326.68      6772347.08      2741326.00      6771961.00

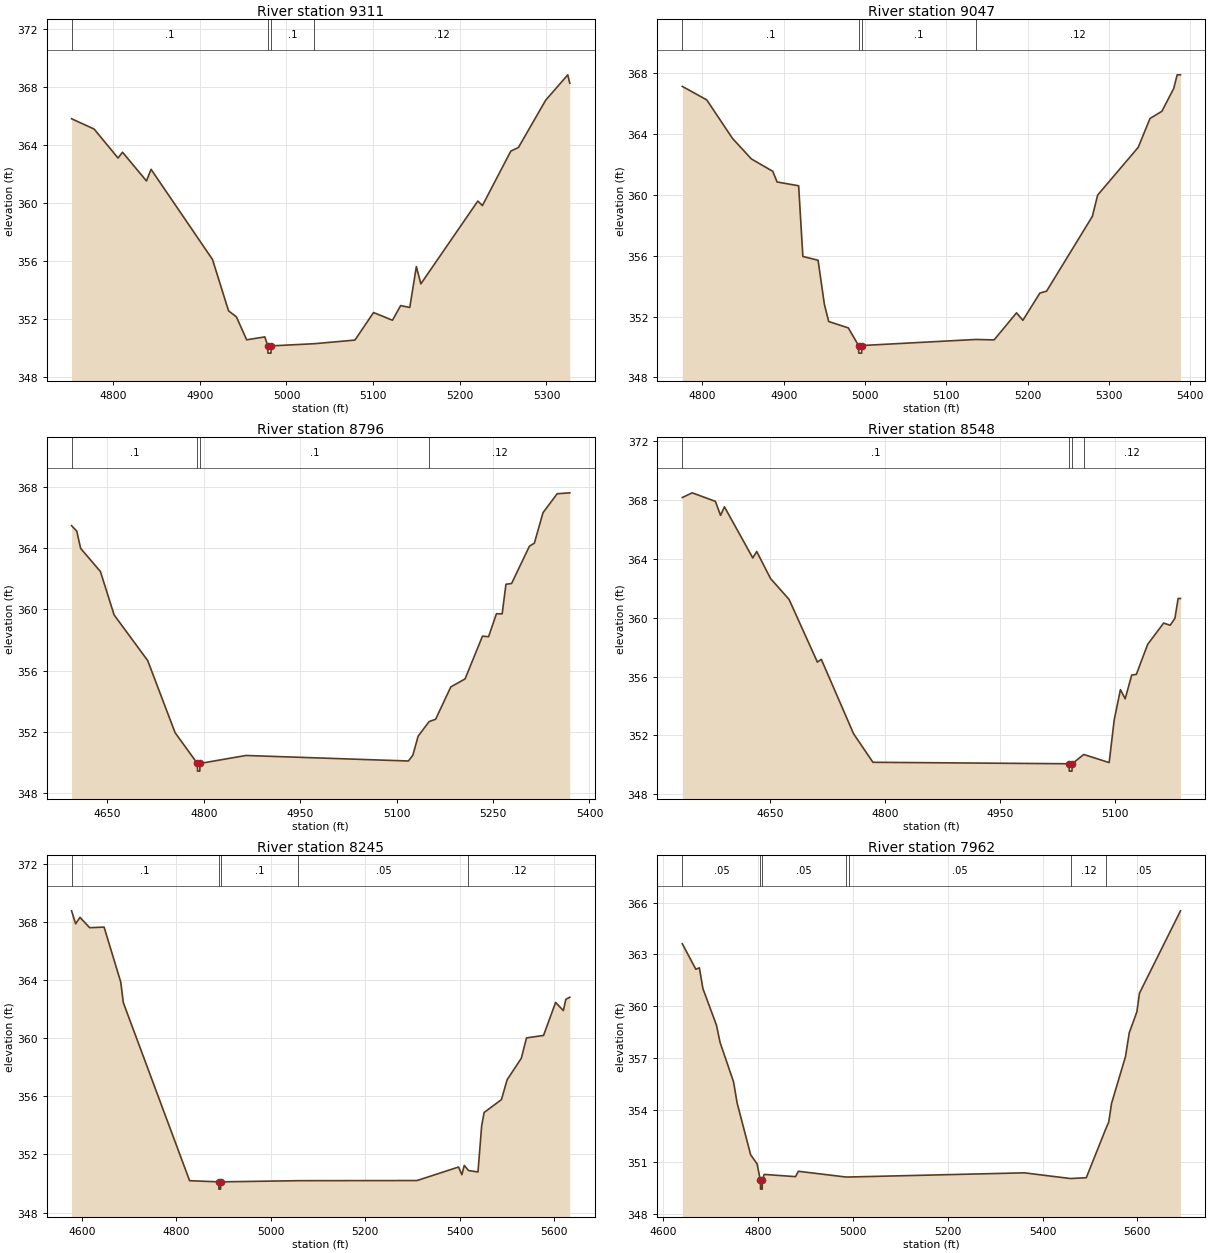
Type RM Length L Ch R = 1,9311,264,264,264
BEGIN DESCRIPTION:
2492
END DESCRIPTION:
XS GIS Cut Line= 2
      2744369.30      6778899.50      2743819.39      6779066.83
#Sta/Elev= 30
  4752.1  365.84  4778.1  365.13  4805.7  363.13  4810.9  363.53  4838.5  361.55
  4843.8  362.35  4914.7  356.13  4933.2  352.59  4942.3  352.17  4954.1  350.59
  4975.1  350.79  4978.4  350.17  4978.7  349.67  4982.2  349.67  4982.4  350.17
  5032.3  350.32  5079.0  350.57  5100.5  352.47  5122.3  351.94  5131.8  352.95
  5142.3  352.82  5149.9  355.64  5155.1  354.45  5220.8  360.16  5226.1  359.85
  5258.9  363.61  5267.7  363.86  5299.1  367.12  5324.6  368.87  5326.9  368.29
#Mann=4,-1,0
  4752.1     0.1       0  4978.4    0.07       0  4982.4     0.1       0
  5032.3    0.12       0
Bank Sta=4978.4,4982.4
Exp/Cntr=0.3,0.1

Type RM Length L Ch R = 1,9047,251,251,251
BEGIN DESCRIPTION:
2491
END DESCRIPTION:
XS GIS Cut Line= 3
      2744274.56      6778640.35      2744087.82      6778702.07
      2743754.36      6778951.00
#Sta/Elev= 30
  4775.3  367.15  4805.4  366.26  4837.0  363.73  4860.2  362.38  4886.6  361.56
  4891.9  360.86  4918.4  360.61  4923.6  355.96  4942.3  355.71  4950.1  352.80
  4955.4  351.68  4979.5  351.26  4992.1  350.10  4992.4  349.60  4995.9  349.60
  4996.1  350.10  5136.7  350.50  5158.8  350.47  5186.4  352.25  5194.2  351.76
  5215.1  353.55  5223.4  353.68  5279.7  358.60  5286.2  360.00  5336.1  363.14
  5350.6  365.04  5365.2  365.51  5379.8  367.02  5384.0  367.91  5388.1  367.91
#Mann=4,-1,0
  4775.3     0.1       0  4992.1    0.07       0  4996.1     0.1       0
  5136.7    0.12       0
Bank Sta=4992.1,4996.1
Exp/Cntr=0.3,0.1

Type RM Length L Ch R = 1,8796,248,248,248
BEGIN DESCRIPTION:
1152
END DESCRIPTION:
XS GIS Cut Line= 3
      2744218.02      6778351.79      2743876.00      6778561.00
      2743676.55      6778877.58
#Sta/Elev= 30
  4594.3  365.45  4602.4  365.09  4608.4  363.97  4639.2  362.46  4660.5  359.63
  4712.7  356.66  4755.3  351.96  4790.0  349.95  4790.3  349.45  4793.8  349.45
  4794.0  349.95  4865.5  350.47  5118.3  350.11  5125.2  350.48  5133.5  351.73
  5150.6  352.68  5160.7  352.83  5184.3  354.94  5206.5  355.46  5233.6  358.25
  5243.0  358.21  5255.3  359.71  5264.2  359.70  5270.1  361.63  5278.9  361.68
  5306.6  364.11  5314.3  364.31  5327.8  366.30  5349.8  367.53  5369.4  367.59
#Mann=4,-1,0
  4594.3     0.1       0  4790.0    0.07       0  4794.0     0.1       0
  5150.6    0.12       0
Bank Sta=4790,4794
Exp/Cntr=0.3,0.1

Type RM Length L Ch R = 1,8548,303,303,303
BEGIN DESCRIPTION:
1151
END DESCRIPTION:
XS GIS Cut Line= 3
      2744278.06      6778244.10      2743826.40      6778351.70
      2743676.02      6778460.99
#Sta/Elev= 30
  4535.7  368.15  4548.6  368.47  4578.9  367.89  4585.6  366.94  4590.7  367.52
  4627.7  364.05  4632.8  364.49  4650.9  362.65  4675.0  361.24  4712.0  356.98
  4717.1  357.17  4759.2  352.12  4784.5  350.18  5040.5  350.08  5040.8  349.58
  5044.3  349.58  5044.5  350.08  5059.6  350.71  5092.8  350.16  5099.4  353.07
  5107.5  355.11  5113.7  354.49  5122.2  356.10  5128.3  356.15  5143.0  358.18
  5163.9  359.63  5172.4  359.48  5178.6  359.95  5182.8  361.30  5185.9  361.30
#Mann=4,-1,0
  4535.7     0.1       0  5040.5    0.07       0  5044.5     0.1       0
  5059.6    0.12       0
Bank Sta=5040.5,5044.5
Exp/Cntr=0.3,0.1

Type RM Length L Ch R = 1,8245,283,283,283
BEGIN DESCRIPTION:
1150
END DESCRIPTION:
XS GIS Cut Line= 4
      2744243.47      6778025.08      2743826.00      6778111.00
      2743533.25      6778255.71      2743603.94      6778550.16
#Sta/Elev= 30
  4577.9  368.75  4586.5  367.86  4595.7  368.30  4616.2  367.59  4646.8  367.63
  4682.1  363.85  4687.6  362.43  4828.0  350.19  4889.8  350.11  4890.1  349.61
  4893.6  349.61  4893.8  350.11  5058.3  350.19  5309.8  350.20  5397.8  351.13
  5404.8  350.60  5410.0  351.24  5418.9  350.89  5439.0  350.79  5446.8  353.96
  5452.0  354.88  5488.8  355.77  5500.7  357.13  5530.8  358.61  5541.8  360.01
  5577.9  360.18  5603.5  362.45  5619.9  361.89  5625.1  362.66  5633.5  362.81
#Mann=5,-1,0
  4577.9     0.1       0  4889.8    0.07       0  4893.8     0.1       0
  5058.3    0.05       0  5418.9    0.12       0
Bank Sta=4889.8,4893.8
Exp/Cntr=0.3,0.1

Type RM Length L Ch R = 1,7962,752,752,752
BEGIN DESCRIPTION:
1149
END DESCRIPTION:
XS GIS Cut Line= 4
      2744075.98      6777711.02      2743776.00      6777911.00
      2743517.50      6778101.26      2743175.98      6777960.99
#Sta/Elev= 30
  4640.2  363.62  4668.7  362.15  4676.2  362.23  4683.7  361.03  4712.3  358.92
  4719.8  357.93  4748.3  355.65  4755.9  354.42  4784.4  351.44  4797.9  350.92
  4804.9  349.96  4805.2  349.46  4808.7  349.46  4808.9  349.96  4812.9  350.31
  4879.0  350.18  4885.0  350.49  4984.7  350.16  4992.5  350.16  5361.5  350.40
  5459.1  350.07  5492.2  350.12  5534.7  353.03  5539.5  353.32  5545.5  354.41
  5574.9  357.11  5582.8  358.48  5598.9  359.69  5604.4  360.77  5690.9  365.52
#Mann=7,-1,0
  4640.2    0.05       0  4804.9    0.03       0  4808.9    0.05       0
  4984.7     0.1       0  4992.5    0.05       0  5459.1    0.12       0
  5534.7    0.05       0
Bank Sta=4804.9,4808.9
Exp/Cntr=0.3,0.1

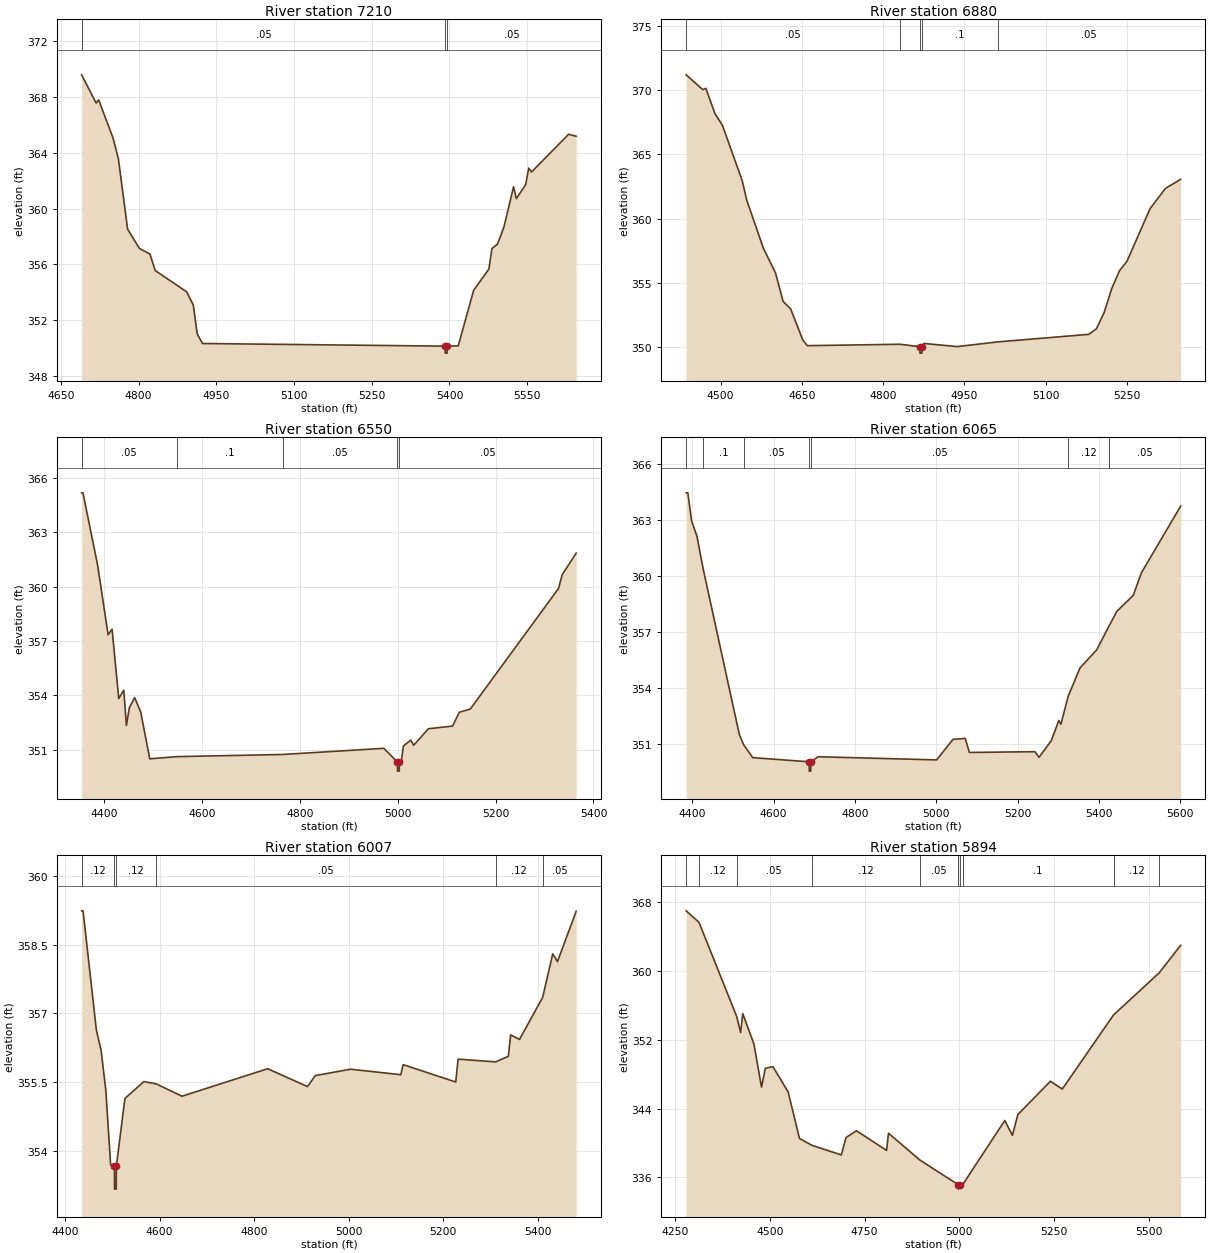
Type RM Length L Ch R = 1,7210,330,330,330
BEGIN DESCRIPTION:
1148
END DESCRIPTION:
XS GIS Cut Line= 3
      2744125.98      6777561.00      2743826.00      6777611.00
      2743226.02      6777860.99
#Sta/Elev= 30
  4690.3  369.58  4718.2  367.56  4723.2  367.78  4751.1  365.03  4761.2  363.56
  4779.0  358.52  4801.8  357.14  4822.1  356.74  4832.2  355.56  4893.0  354.03
  4905.7  353.09  4913.3  351.02  4923.5  350.33  5391.6  350.14  5391.9  349.64
  5395.4  349.64  5395.6  350.14  5416.9  350.16  5446.7  354.15  5476.0  355.66
  5481.9  357.13  5492.8  357.46  5505.2  358.70  5523.6  361.56  5529.0  360.71
  5546.9  361.71  5552.9  362.90  5558.3  362.62  5629.8  365.32  5644.4  365.18
#Mann=3,-1,0
  4690.3    0.05       0  5391.6    0.04       0  5395.6    0.05       0
Bank Sta=5391.6,5395.6
Exp/Cntr=0.3,0.1

Type RM Length L Ch R = 1,6880,330,330,330
BEGIN DESCRIPTION:
1147
END DESCRIPTION:
XS GIS Cut Line= 3
      2744025.97      6777261.01      2743526.00      6777511.00
      2743276.03      6777760.97
#Sta/Elev= 30
  4436.5  371.19  4467.2  370.04  4472.8  370.14  4489.6  368.18  4503.5  367.26
  4539.9  362.97  4548.3  361.45  4579.0  357.71  4601.4  355.79  4615.4  353.58
  4629.3  353.00  4651.7  350.58  4660.1  350.14  4831.1  350.25  4867.7  350.06
  4868.0  349.56  4871.5  349.56  4871.7  350.06  4875.3  350.31  4936.8  350.07
  5011.0  350.43  5179.3  351.02  5193.5  351.45  5207.6  352.70  5221.8  354.58
  5235.9  355.95  5250.0  356.71  5292.5  360.79  5320.8  362.36  5349.0  363.07
#Mann=5,-1,0
  4436.5    0.05       0  4831.1     0.1       0  4867.7    0.07       0
  4871.7     0.1       0  5011.0    0.05       0
Bank Sta=4867.7,4871.7
Exp/Cntr=0.3,0.1

Type RM Length L Ch R = 1,6550,485,485,485
BEGIN DESCRIPTION:
1146
END DESCRIPTION:
XS GIS Cut Line= 3
      2743875.96      6777111.02      2743276.00      6777361.00
      2743076.01      6777660.99
#Sta/Elev= 30
  4354.1  365.19  4356.8  365.19  4386.6  361.22  4408.2  357.35  4416.3  357.66
  4429.9  353.83  4440.2  354.29  4445.6  352.34  4451.6  353.32  4462.4  353.88
  4474.8  353.09  4493.3  350.50  4548.7  350.62  4765.0  350.74  4971.6  351.08
  4999.3  350.32  4999.6  349.82  5003.1  349.82  5003.3  350.32  5007.1  350.32
  5011.6  351.21  5026.6  351.53  5032.6  351.25  5062.6  352.16  5112.2  352.31
  5125.7  353.07  5148.3  353.25  5328.6  359.91  5336.1  360.67  5364.6  361.86
#Mann=5,-1,0
  4354.1    0.05       0  4548.7     0.1       0  4765.0    0.05       0
  4999.3    0.03       0  5003.3    0.05       0
Bank Sta=4999.3,5003.3
Exp/Cntr=0.3,0.1

Type RM Length L Ch R = 1,6065,58,58,58
BEGIN DESCRIPTION:
2427
END DESCRIPTION:
XS GIS Cut Line= 3
      2743849.14      6776863.72      2743226.61      6776921.59
      2742640.07      6776990.60
#Sta/Elev= 30
  4385.0  364.45  4389.1  364.45  4398.2  362.96  4411.5  362.13  4426.7  360.39
  4515.7  351.52  4526.3  350.97  4548.8  350.28  4687.4  350.06  4687.7  349.56
  4691.2  349.56  4691.4  350.06  4709.5  350.33  5000.8  350.16  5041.0  351.26
  5071.2  351.31  5081.3  350.56  5242.4  350.60  5252.5  350.30  5282.7  351.19
  5301.2  352.27  5306.3  352.07  5324.2  353.56  5353.2  355.08  5394.4  356.05
  5424.1  357.30  5443.8  358.11  5484.1  358.96  5504.2  360.17  5600.8  363.74
#Mann=7,-1,0
  4385.0    0.05       0  4426.7     0.1       0  4526.3    0.05       0
  4687.4    0.03       0  4691.4    0.05       0  5324.2    0.12       0
  5424.1    0.05       0
Bank Sta=4687.4,4691.4
Exp/Cntr=0.3,0.1

Type RM Length L Ch R = 1,6007,113,113,113
BEGIN DESCRIPTION:
1145
END DESCRIPTION:
XS GIS Cut Line= 3
      2743786.94      6776803.63      2743225.56      6776865.73
      2742746.68      6776908.70
#Sta/Elev= 30
  4435.2  359.24  4438.2  359.24  4466.3  356.64  4476.4  356.19  4486.4  355.31
  4496.5  353.69  4504.6  353.66  4504.8  353.16  4508.3  353.16  4508.6  353.66
  4526.7  355.14  4566.9  355.51  4592.7  355.46  4647.4  355.19  4828.5  355.79
  4912.8  355.40  4929.1  355.64  5003.8  355.78  5110.0  355.66  5115.0  355.88
  5226.1  355.50  5231.2  356.00  5310.5  355.94  5337.3  356.06  5342.3  356.53
  5361.0  356.43  5410.0  357.35  5431.3  358.30  5441.3  358.13  5480.8  359.23
#Mann=6,-1,0
  4435.2    0.12       0  4504.6    0.03       0  4508.6    0.12       0
  4592.7    0.05       0  5310.5    0.12       0  5410.0    0.05       0
Bank Sta=4504.6,4508.6
Exp/Cntr=0.3,0.1

Type RM Length L Ch R = 1,5894,173,173,173
BEGIN DESCRIPTION:
2426
END DESCRIPTION:
XS GIS Cut Line= 3
      2743944.44      6776696.27      2743602.37      6776719.28
      2742643.53      6776803.78
#Sta/Elev= 30
  4279.2  367.02  4313.1  365.68  4412.5  354.73  4423.0  352.86  4428.6  355.05
  4458.0  351.53  4478.1  346.50  4488.1  348.68  4508.2  348.88  4548.3  345.95
  4578.3  340.52  4611.2  339.72  4688.7  338.60  4701.2  340.63  4728.8  341.41
  4808.3  339.13  4813.3  341.13  4895.7  338.02  4997.9  335.12  4998.1  334.62
  5001.9  335.12  5009.4  335.16  5120.3  342.61  5140.4  340.88  5154.8  343.30
  5240.8  347.18  5272.0  346.27  5407.6  354.91  5527.9  359.80  5584.6  363.01
#Mann=10,-1,0
  4279.2    0.05       0  4313.1    0.12       0  4412.5    0.05       0
  4611.2    0.12       0  4895.7    0.05       0  4997.9    0.03       0
  5001.9    0.05       0  5009.4     0.1       0  5407.6    0.12       0
  5527.9    0.05       0
Bank Sta=4997.9,5001.9
Exp/Cntr=0.3,0.1

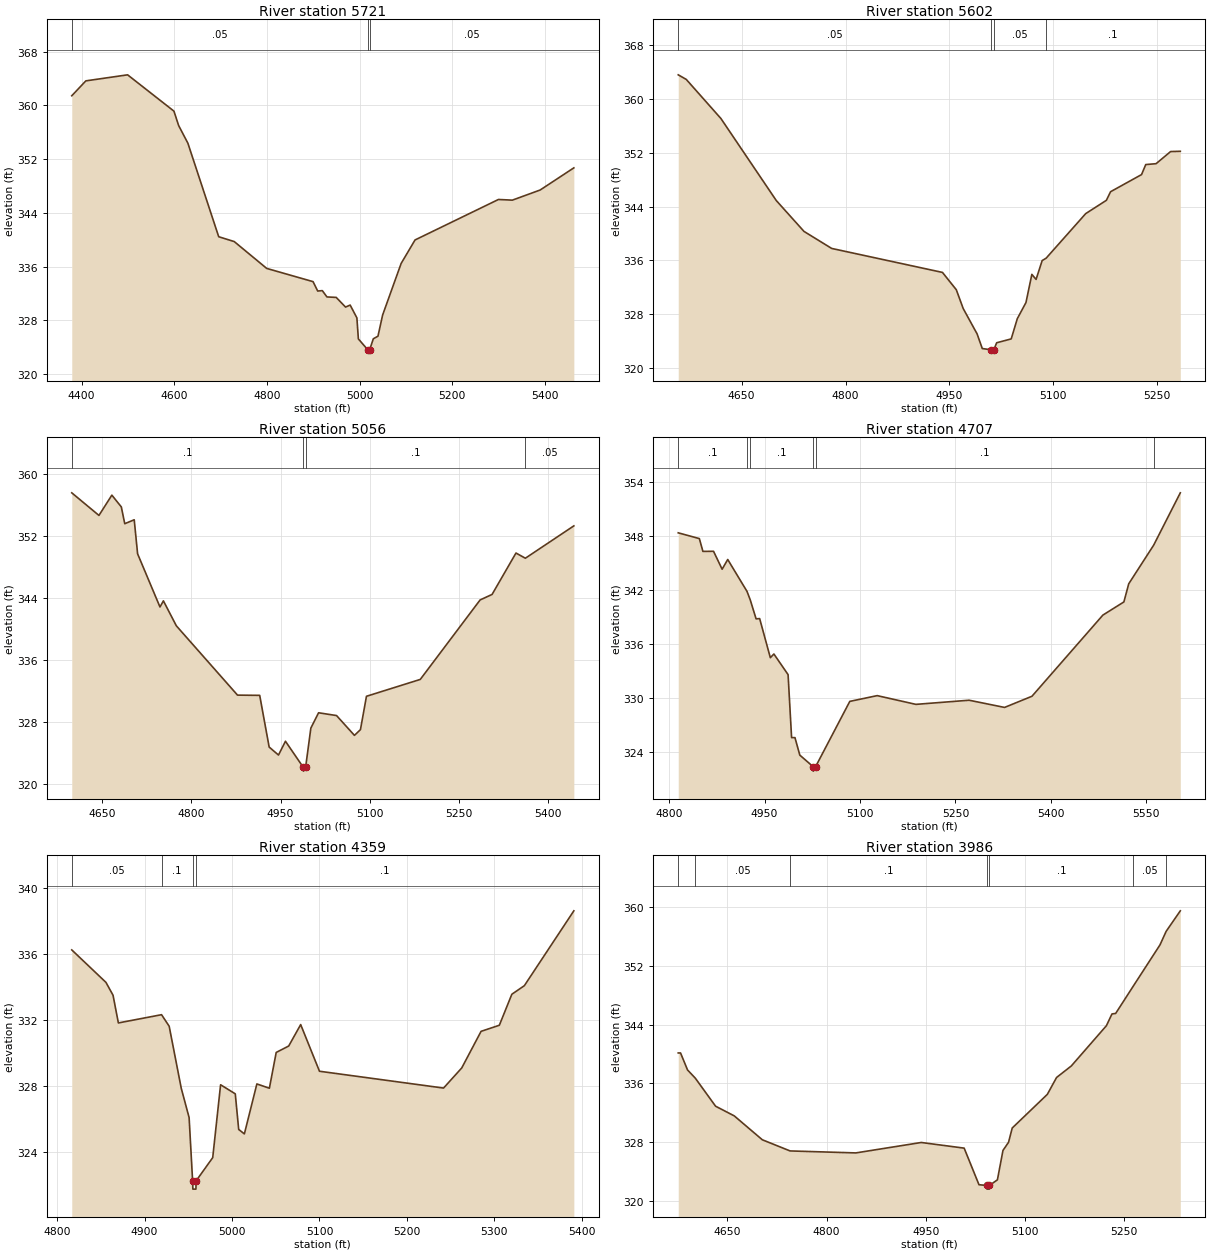
Type RM Length L Ch R = 1,5721,119,119,119
BEGIN DESCRIPTION:
1144
END DESCRIPTION:
XS GIS Cut Line= 3
      2743896.42      6776616.76      2743275.48      6776595.78
      2742813.33      6776588.75
#Sta/Elev= 30
  4378.7  361.44  4409.1  363.66  4499.2  364.56  4599.2  359.15  4609.3  357.01
  4629.3  354.37  4695.8  340.44  4729.3  339.72  4799.4  335.72  4899.4  333.75
  4909.4  332.35  4919.4  332.41  4929.4  331.47  4949.4  331.40  4969.5  329.96
  4979.5  330.26  4994.0  328.35  4997.2  325.22  5017.5  323.60  5017.7  323.10
  5021.5  323.60  5029.5  325.24  5039.5  325.62  5049.5  328.77  5089.5  336.46
  5119.5  339.96  5299.5  345.99  5329.5  345.89  5389.5  347.40  5462.2  350.70
#Mann=3,-1,0
  4378.7    0.05       0  5017.5    0.05       0  5021.5    0.05       0
Bank Sta=5017.5,5021.5
Exp/Cntr=0.3,0.1

Type RM Length L Ch R = 1,5602,546,546,546
BEGIN DESCRIPTION:
1143
END DESCRIPTION:
XS GIS Cut Line= 3
      2743717.62      6776478.27      2743276.03      6776476.39
      2743042.11      6776316.23
#Sta/Elev= 30
  4558.4  363.56  4570.0  362.88  4620.0  357.08  4700.0  344.90  4740.0  340.32
  4780.0  337.79  4940.0  334.23  4960.0  331.66  4970.0  328.86  4990.0  325.11
  4997.5  322.93  5010.2  322.75  5010.4  322.25  5014.2  322.75  5018.3  323.79
  5039.3  324.36  5048.1  327.37  5060.6  329.76  5069.1  333.94  5075.2  333.19
  5084.0  335.99  5089.7  336.34  5146.9  342.96  5176.7  344.93  5182.8  346.21
  5227.5  348.75  5233.6  350.24  5248.5  350.37  5269.5  352.17  5283.5  352.21
#Mann=4,-1,0
  4558.4    0.05       0  5010.2    0.05       0  5014.2    0.05       0
  5089.7     0.1       0
Bank Sta=5010.2,5014.2
Exp/Cntr=0.3,0.1

Type RM Length L Ch R = 1,5056,349,349,349
BEGIN DESCRIPTION:
1142
END DESCRIPTION:
XS GIS Cut Line= 3
      2743728.94      6776159.48      2743376.00      6775961.00
      2742939.32      6776008.77
#Sta/Elev= 30
  4598.9  357.63  4644.6  354.71  4666.3  357.33  4682.2  355.81  4688.0  353.64
  4703.9  354.15  4709.6  349.75  4747.2  342.88  4753.0  343.67  4774.7  340.45
  4877.6  331.49  4914.9  331.46  4930.8  324.78  4946.5  323.75  4958.2  325.53
  4988.1  322.17  4988.4  321.67  4992.1  322.17  5000.9  327.23  5013.9  329.21
  5044.1  328.85  5074.2  326.29  5084.3  327.03  5094.4  331.34  5184.9  333.52
  5285.5  343.79  5305.6  344.50  5345.8  349.85  5361.6  349.18  5443.1  353.36
#Mann=4,-1,0
  4598.9     0.1       0  4988.1    0.07       0  4992.1     0.1       0
  5361.6    0.05       0
Bank Sta=4988.1,4992.1
Exp/Cntr=0.3,0.1

Type RM Length L Ch R = 1,4707,348,348,348
BEGIN DESCRIPTION:
1141
END DESCRIPTION:
XS GIS Cut Line= 3
      2743737.62      6775792.50      2743576.00      6775711.00
      2742975.98      6775811.00
#Sta/Elev= 30
  4814.3  348.32  4847.5  347.68  4853.1  346.26  4869.8  346.27  4883.3  344.28
  4892.1  345.36  4922.5  341.81  4927.6  340.86  4936.7  338.77  4942.3  338.80
  4959.1  334.46  4964.7  334.87  4987.0  332.58  4992.5  325.59  4997.8  325.59
  5005.4  323.65  5026.3  322.37  5026.5  321.87  5030.3  322.37  5084.0  329.61
  5127.1  330.25  5187.9  329.28  5271.6  329.74  5327.3  328.94  5370.4  330.18
  5481.9  339.19  5514.9  340.65  5522.5  342.66  5561.7  346.95  5603.6  352.76
#Mann=6,-1,0
  4814.3     0.1       0  4922.5    0.05       0  4927.6     0.1       0
  5026.3    0.07       0  5030.3     0.1       0  5561.7    0.05       0
Bank Sta=5026.3,5030.3
Exp/Cntr=0.3,0.1

Type RM Length L Ch R = 1,4359,373,373,373
BEGIN DESCRIPTION:
1140
END DESCRIPTION:
XS GIS Cut Line= 3
      2743478.54      6775308.57      2743376.00      6775461.00
      2743076.02      6775710.98
#Sta/Elev= 30
  4816.7  336.26  4855.8  334.29  4863.9  333.51  4870.0  331.83  4919.4  332.33
  4928.1  331.63  4941.9  327.87  4950.9  326.09  4954.9  322.25  4955.2  321.75
  4958.7  321.75  4958.9  322.25  4977.9  323.66  4986.9  328.08  5003.7  327.53
  5007.6  325.37  5014.1  325.10  5028.4  328.13  5042.7  327.87  5050.5  330.04
  5064.8  330.43  5078.5  331.73  5100.0  328.90  5241.9  327.88  5262.7  329.10
  5284.8  331.32  5305.7  331.69  5320.0  333.57  5334.3  334.09  5390.9  338.63
#Mann=4,-1,0
  4816.7    0.05       0  4919.4     0.1       0  4954.9    0.07       0
  4958.9     0.1       0
Bank Sta=4954.9,4958.9
Exp/Cntr=0.3,0.1

Type RM Length L Ch R = 1,3986,329,329,329
BEGIN DESCRIPTION:
1139
END DESCRIPTION:
XS GIS Cut Line= 3
      2743375.97      6774961.03      2743076.00      6775261.00
      2742776.03      6775410.98
#Sta/Elev= 30
  4575.5  340.15  4579.0  340.15  4589.6  337.83  4601.3  336.72  4632.0  332.90
  4660.3  331.58  4702.7  328.33  4744.7  326.81  4844.2  326.54  4943.2  327.96
  5008.1  327.19  5030.5  322.21  5042.4  322.11  5042.7  321.61  5046.2  321.61
  5046.4  322.11  5058.4  322.88  5066.8  326.88  5075.2  327.98  5080.8  329.93
  5133.9  334.51  5147.9  336.81  5170.2  338.38  5223.3  343.86  5231.7  345.46
  5237.3  345.53  5263.6  349.20  5304.4  354.87  5313.7  356.71  5335.1  359.50
#Mann=7,-1,0
  4575.5    0.12       0  4601.3    0.05       0  4744.7     0.1       0
  5042.4    0.07       0  5046.4     0.1       0  5263.6    0.05       0
  5313.7     0.1       0
Bank Sta=5042.4,5046.4
Exp/Cntr=0.3,0.1

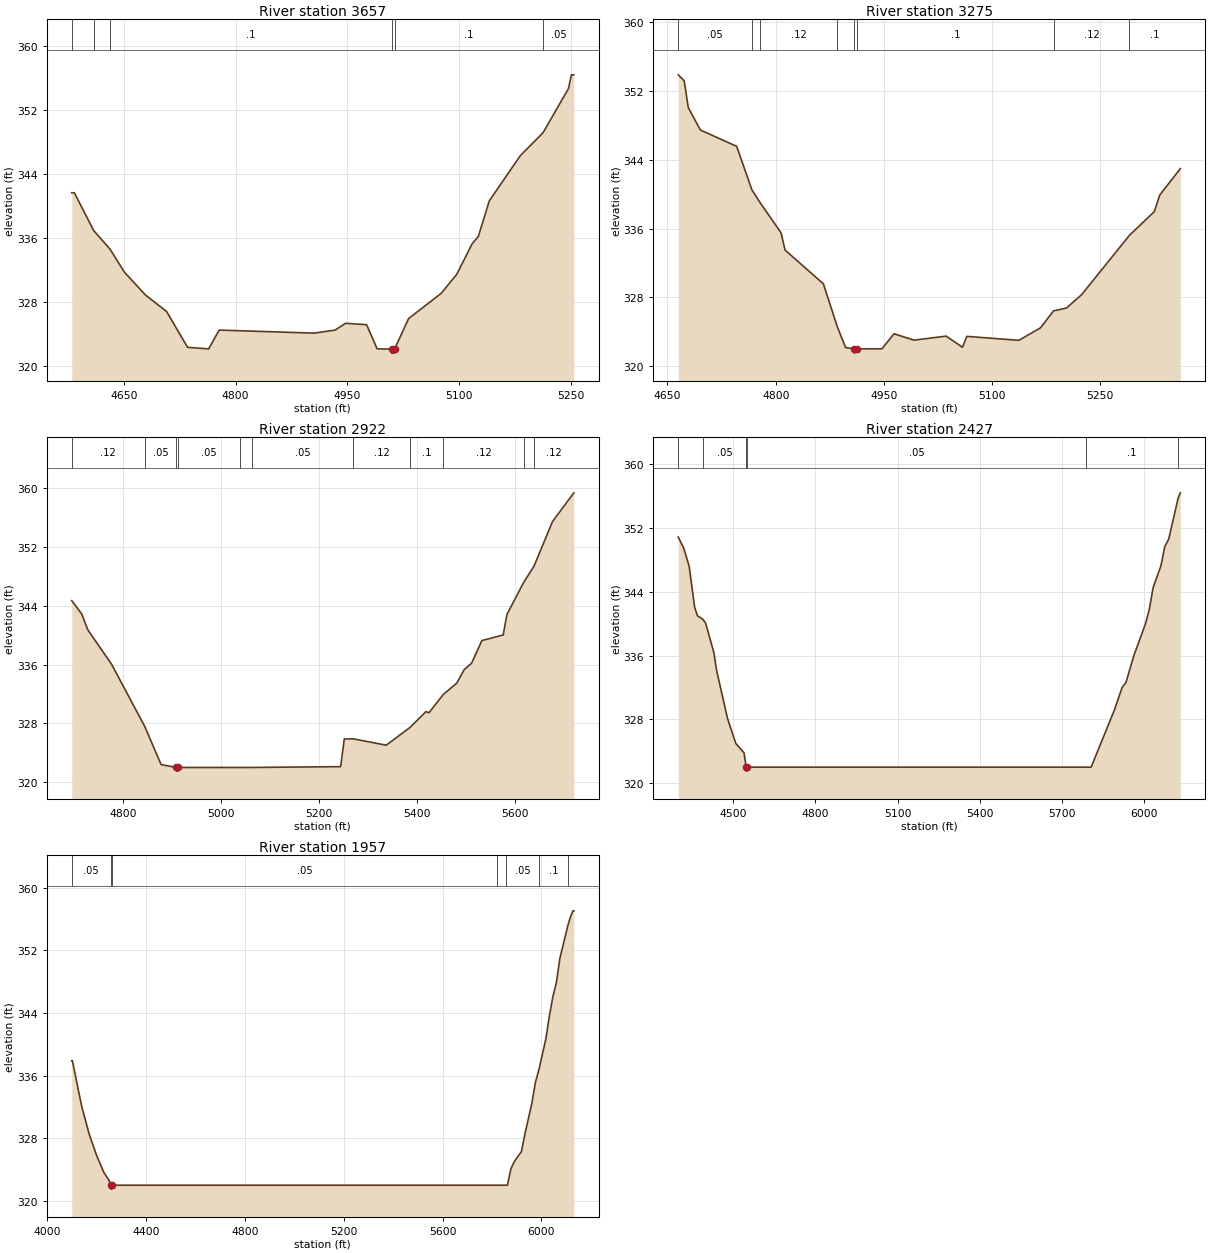
Type RM Length L Ch R = 1,3657,382,382,382
BEGIN DESCRIPTION:
1138
END DESCRIPTION:
XS GIS Cut Line= 3
      2743175.99      6774711.01      2742876.00      6775011.00
      2742675.96      6775161.03
#Sta/Elev= 30
  4580.1  341.62  4583.6  341.62  4609.6  336.89  4631.4  334.59  4650.8  331.70
  4679.1  328.84  4707.4  326.79  4735.6  322.31  4763.9  322.11  4778.1  324.46
  4905.4  324.08  4933.6  324.45  4947.8  325.31  4976.1  325.13  4990.2  322.12
  5009.6  322.08  5009.9  321.58  5013.4  321.58  5013.6  322.08  5032.5  325.90
  5076.2  329.05  5097.1  331.42  5117.9  335.26  5126.2  336.18  5140.8  340.60
  5182.5  346.26  5213.1  349.13  5247.1  354.63  5251.2  356.36  5254.4  356.36
#Mann=6,-1,0
  4580.1    0.05       0  4609.6    0.12       0  4631.4     0.1       0
  5009.6    0.07       0  5013.6     0.1       0  5213.1    0.05       0
Bank Sta=5009.6,5013.6
Exp/Cntr=0.3,0.1

Type RM Length L Ch R = 1,3275,353,353,353
BEGIN DESCRIPTION:
1137
END DESCRIPTION:
XS GIS Cut Line= 3
      2742925.98      6774361.03      2742776.00      6774661.00
      2742576.01      6774960.98
#Sta/Elev= 30
  4664.9  353.88  4673.2  353.18  4678.8  350.08  4695.6  347.46  4745.9  345.56
  4767.1  340.48  4778.4  339.01  4807.4  335.50  4813.0  333.49  4866.1  329.56
  4885.3  324.59  4896.9  322.15  4908.8  322.00  4909.1  321.50  4912.8  322.00
  4947.2  322.00  4963.9  323.75  4991.9  323.01  5036.3  323.48  5058.9  322.18
  5064.9  323.45  5137.0  322.99  5167.0  324.44  5185.1  326.42  5203.1  326.75
  5224.1  328.31  5290.3  335.21  5324.8  337.97  5332.3  339.89  5360.8  342.97
#Mann=8,-1,0
  4664.9    0.05       0  4767.1     0.1       0  4778.4    0.12       0
  4885.3     0.1       0  4908.8    0.07       0  4912.8     0.1       0
  5185.1    0.12       0  5290.3     0.1       0
Bank Sta=4908.8,4912.8
Exp/Cntr=0.3,0.1

Type RM Length L Ch R = 1,2922,495,495,495
BEGIN DESCRIPTION:
1136
END DESCRIPTION:
XS GIS Cut Line= 3
      2742825.97      6774361.00      2742526.00      6774411.00
      2742126.01      6775010.98
#Sta/Elev= 30
  4695.9  344.69  4716.1  342.90  4728.8  340.71  4777.0  336.06  4844.7  327.61
  4878.4  322.39  4909.3  322.00  4909.6  321.50  4913.1  321.50  4913.3  322.00
  5039.0  322.00  5064.5  322.00  5244.9  322.11  5252.4  325.88  5270.8  325.89
  5338.0  325.03  5386.7  327.45  5419.2  329.60  5425.2  329.44  5454.8  331.95
  5482.3  333.49  5497.3  335.32  5512.3  336.18  5533.3  339.26  5576.9  340.03
  5584.4  342.80  5618.4  347.14  5639.8  349.39  5677.6  355.46  5721.1  359.36
#Mann=11,-1,0
  4695.9    0.12       0  4844.7    0.05       0  4909.3    0.03       0
  4913.3    0.05       0  5039.0    0.12       0  5064.5    0.05       0
  5270.8    0.12       0  5386.7     0.1       0  5454.8    0.12       0
  5618.4     0.1       0  5639.8    0.12       0
Bank Sta=4909.3,4913.3
Exp/Cntr=0.3,0.1

Type RM Length L Ch R = 1,2427,470,470,470
BEGIN DESCRIPTION:
1135
END DESCRIPTION:
XS GIS Cut Line= 3
      2742875.99      6774061.00      2742176.00      6774061.00
      2741375.98      6774861.02
#Sta/Elev= 30
  4300.0  350.87  4320.0  349.49  4340.0  347.18  4360.0  342.04  4370.0  341.00
  4390.2  340.54  4400.0  340.06  4430.0  336.36  4440.0  334.13  4480.0  328.08
  4510.0  324.97  4540.0  323.79  4547.9  322.00  4548.2  321.50  4551.7  321.50
  4552.0  322.00  5788.1  322.00  5806.1  322.00  5890.9  329.16  5919.2  332.00
  5933.4  332.65  5961.7  335.96  6004.1  339.96  6018.2  341.78  6032.4  344.55
  6060.7  347.26  6074.8  349.68  6088.9  350.59  6123.6  355.78  6131.4  356.42
#Mann=6,-1,0
  4300.0    0.12       0  4390.2    0.05       0  4547.9    0.03       0
  4552.0    0.05       0  5788.1     0.1       0  6123.6    0.05       0
Bank Sta=4547.9,4552
Exp/Cntr=0.3,0.1

Type RM Length L Ch R = 1,1957,0,0,0
BEGIN DESCRIPTION:
1134
END DESCRIPTION:
XS GIS Cut Line= 3
      2742776.02      6773711.00      2741876.00      6773711.00
      2741075.99      6774511.01
#Sta/Elev= 30
  4100.0  337.91  4102.5  337.91  4140.0  332.09  4170.0  328.58  4200.0  325.85
  4230.0  323.62  4250.0  322.66  4258.0  322.00  4258.3  321.50  4261.8  321.50
  4262.1  322.00  5820.3  322.00  5855.8  322.00  5862.7  322.00  5876.8  324.11
  5891.0  325.05  5919.3  326.29  5933.4  328.54  5961.7  332.49  5975.8  335.12
  5991.1  336.90  6018.2  340.70  6032.4  343.62  6046.5  346.06  6060.7  347.87
  6074.8  350.97  6107.0  355.14  6117.2  356.23  6127.9  357.05  6131.4  357.05
#Mann=7,-1,0
  4100.0    0.05       0  4258.0    0.03       0  4262.1    0.05       0
  5820.3    0.12       0  5855.8    0.05       0  5991.1     0.1       0
  6107.0    0.05       0
Bank Sta=4258,4262.1
Exp/Cntr=0.3,0.1

Chan Stop Cuts=-1