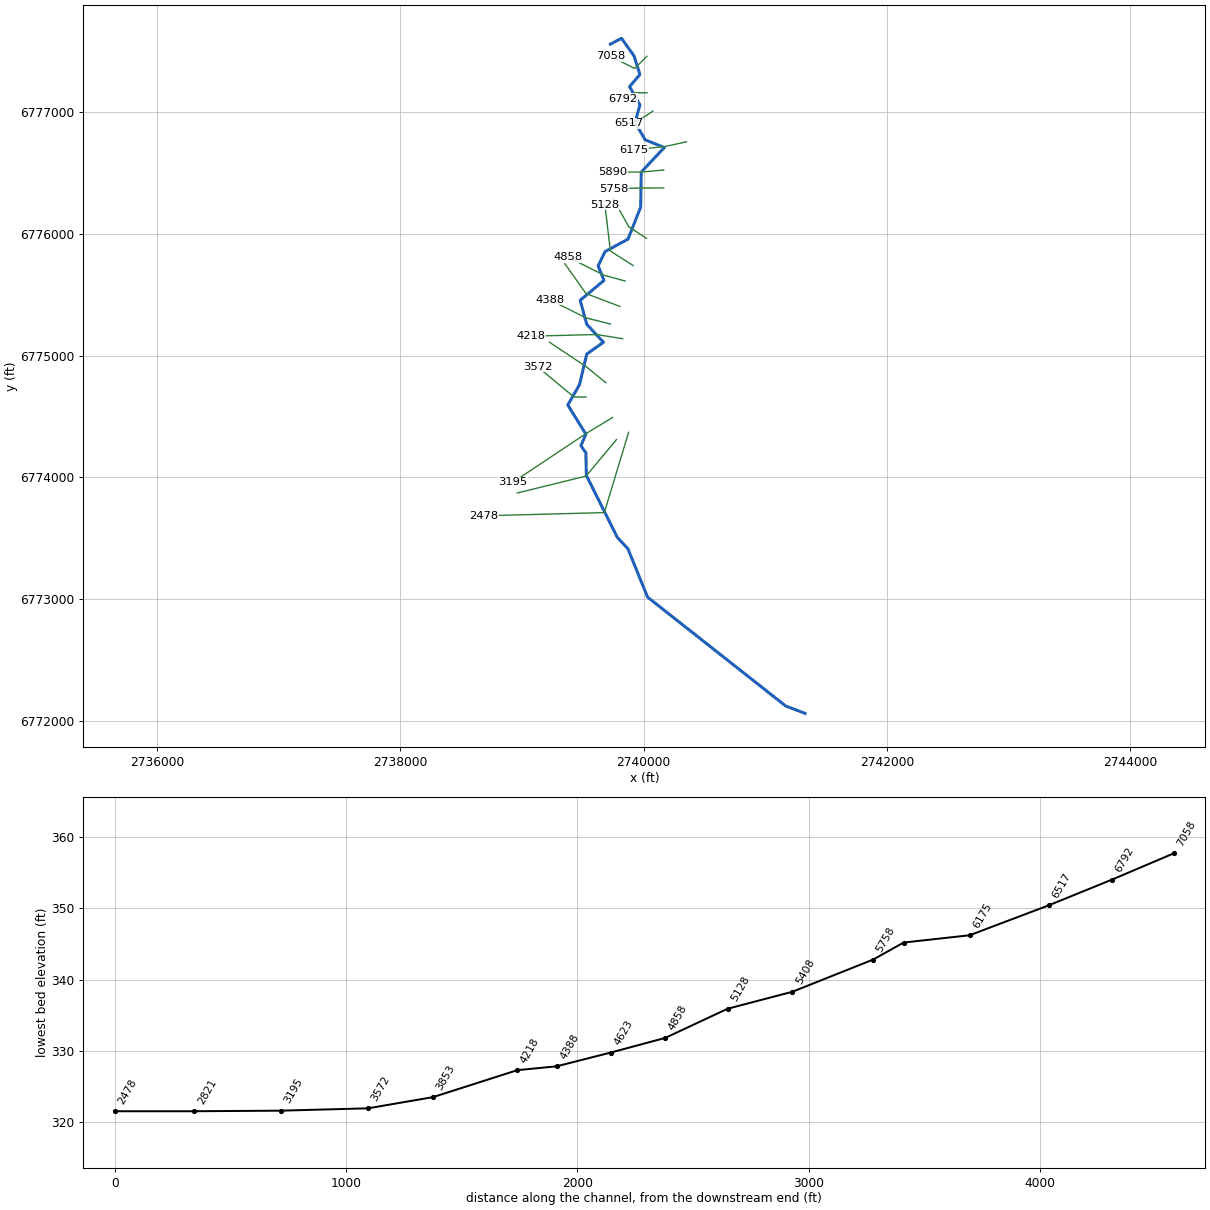
--- Caney Creek T 31.prj (project) ---

Proj Title=Caney Creek T 31 Base Level Engineering
Current Plan=p01
Default Exp/Contr=0.3,0.1
English Units
Geom File=g01
Flow File=f01
Plan File=p01
Y Axis Title=Elevation
X Axis Title(PF)=Main Channel Distance
X Axis Title(XS)=Station
BEGIN DESCRIPTION:
Caney Creek T 31
END DESCRIPTION:
DSS Export Rating Curves= 0
DSS Export Rating Curve Sorted= 0
DSS Export Volume Flow Curves= 0
DXF OffsetX= 0
DXF OffsetY= 0
DXF ScaleX= 1
DXF ScaleY= 10

--- Caney Creek T 31.p01 (plan) ---

Plan Title=Multiple Run
Short Identifier=Multiple
Geom File=g01
Flow File=f01
Subcritical Flow
K Sum by GR= 0
Std Step Tol= 0.01
Critical Tol= 0.01
Num of Std Step Trials= 20
Max Error Tol= 0.3
Flow Tol Ratio= 0.001
Split Flow NTrial= 30
Split Flow Tol= 0.02
Split Flow Ratio= 0.02
Log Output Level= 0
Friction Slope Method= 1
Unsteady Friction Slope Method= 2
Unsteady Bridges Friction Slope Method= 1
Parabolic Critical Depth
Global Vel Dist=  1 , 1 , 1
Global Log Level= 0
CheckData=True
Encroach Param= -1, 0, 0, 0
BEGIN DESCRIPTION:
Multiple Run
END DESCRIPTION:

--- Caney Creek T 31.f01 (steady flow) ---

Flow Title=Multiple
Number of Profiles=7
Profile Names=10-year,25-year,50-year,1pct_min,100-year,1pct_plu,500-year
River Rch & RM= Caney Creek T 31,Reach-1,7058
     376     492     584     346     690    1376     958
River Rch & RM= Caney Creek T 31,Reach-1,3195
     505     671     804     479     956    1907    1347
Boundary for River Rch & Prof#=Caney Creek T 31,Reach-1,1
Up Type=0
Dn Type=3
Dn Slope=0.005
Boundary for River Rch & Prof#=Caney Creek T 31,Reach-1,2
Up Type=0
Dn Type=3
Dn Slope=0.005
Boundary for River Rch & Prof#=Caney Creek T 31,Reach-1,3
Up Type=0
Dn Type=3
Dn Slope=0.005
Boundary for River Rch & Prof#=Caney Creek T 31,Reach-1,4
Up Type=0
Dn Type=3
Dn Slope=0.005
Boundary for River Rch & Prof#=Caney Creek T 31,Reach-1,5
Up Type=0
Dn Type=3
Dn Slope=0.005
Boundary for River Rch & Prof#=Caney Creek T 31,Reach-1,6
Up Type=0
Dn Type=3
Dn Slope=0.005
Boundary for River Rch & Prof#=Caney Creek T 31,Reach-1,7
Up Type=0
Dn Type=3
Dn Slope=0.005

--- Caney Creek T 31.g01 (geometry) ---

Geom Title=Existing Conditions
Program Version=4.10

River Reach=Caney Creek T 31,Reach-1
Reach XY= 30
        2739726.        6777561.      2739817.66      6777608.48
      2739920.47      6777463.42      2739968.66       6777310.9
      2739883.31      6777211.09      2739968.47      6777061.01
      2739928.26      6776916.56      2740012.35      6776774.26
      2740169.03      6776711.24      2739979.54      6776509.54
       2739974.8       6776221.5      2739870.58      6775958.32
      2739681.58      6775855.42      2739625.62       6775738.2
       2739673.2      6775619.19      2739477.73      6775455.38
      2739531.52      6775258.57      2739669.02      6775110.79
      2739531.42      6775013.67      2739472.17      6774762.58
      2739375.96      6774595.68      2739524.35      6774354.95
      2739483.59      6774261.01      2739524.45      6774201.41
      2739528.35      6774016.52      2739781.85      6773508.71
      2739870.15      6773413.29      2740031.26      6773016.47
      2741166.31      6772121.76        2741326.        6772061.

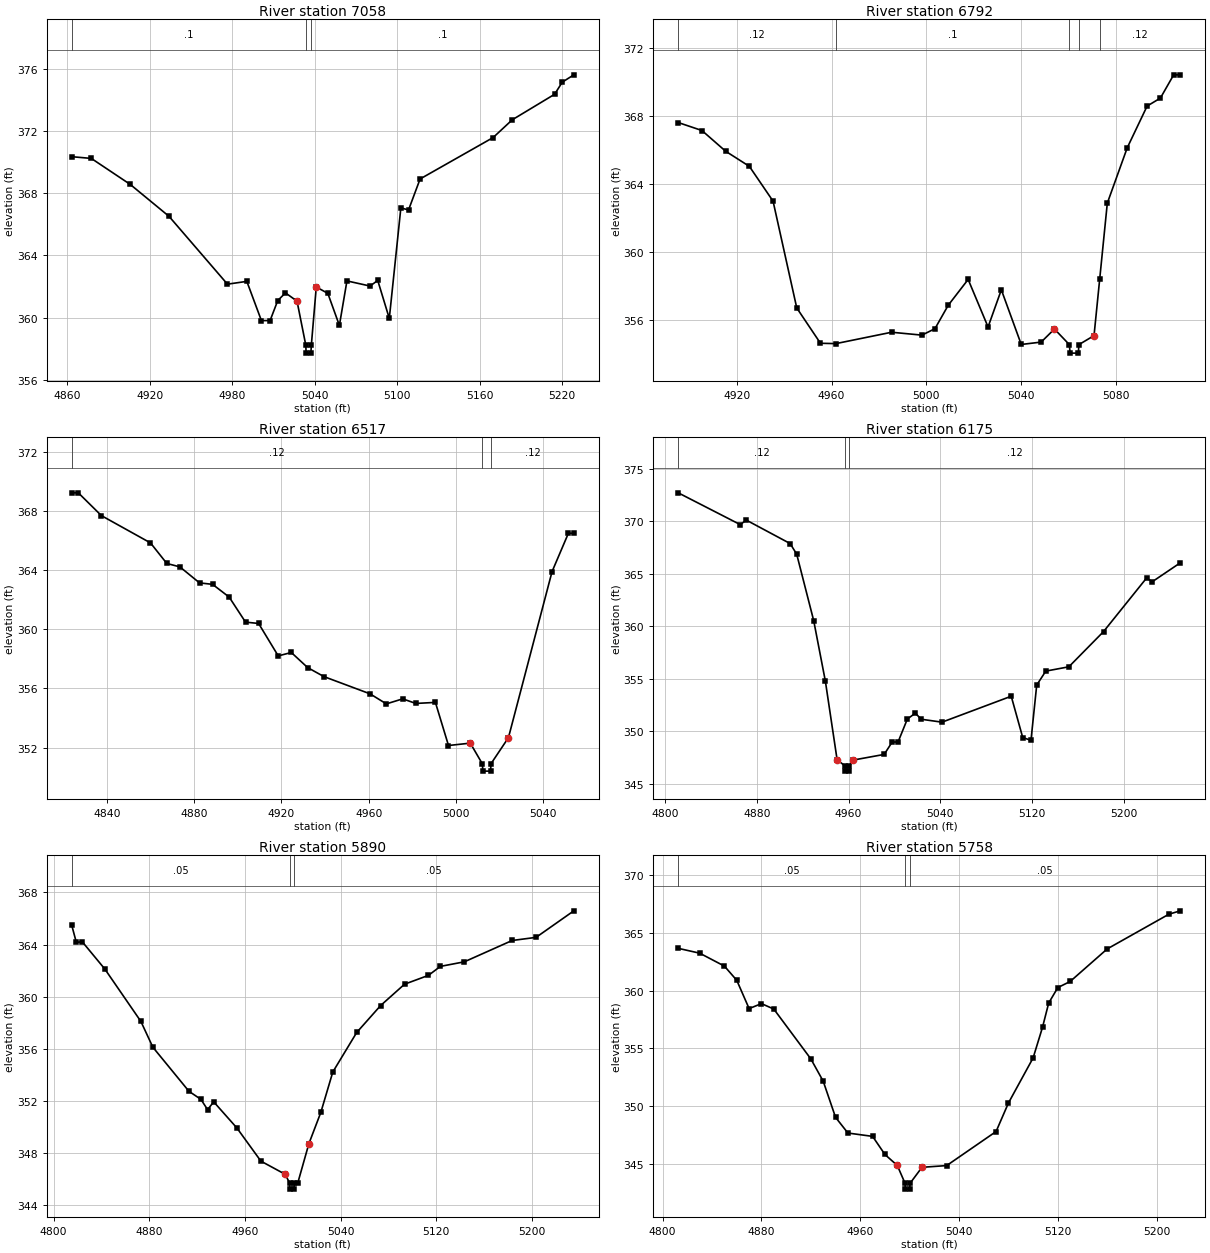
Type RM Length L Ch R = 1 ,7058    ,266,266,266
BEGIN DESCRIPTION:
Caney Creek T 31 19.0
END DESCRIPTION:
XS GIS Cut Line= 3
      2740026.02      6777461.02        2739926.        6777361.
      2739725.96      6777461.02
#Sta/Elev= 30
  4863.4  370.34  4877.6  370.23  4905.9  368.56  4934.1  366.51  4976.6  362.15
  4990.7  362.33  5001.3  359.81  5007.6  359.81  5013.2   361.1  5018.8  361.59
  5027.2  361.06  5033.6  358.22  5033.8  357.72  5037.3  357.72  5037.6  358.22
  5041.2  361.97  5049.6  361.56    5058   359.5  5063.5  362.36  5080.3  362.03
  5085.9  362.39  5094.3  359.95  5102.7  367.05  5108.3  366.92  5116.7  368.91
  5169.8  371.57  5183.7  372.71  5214.5  374.35  5220.1  375.13  5228.5   375.6
#Mann= 3 ,-1 , 0
  4863.4      .1       0  5033.6     .07       0  5037.6      .1       0
Bank Sta=5027.2,5041.2
XS Rating Curve= 0 ,0
Exp/Cntr=0.3,0.1

Type RM Length L Ch R = 1 ,6792    ,275,275,275
BEGIN DESCRIPTION:
Caney Creek T 31 18.0
END DESCRIPTION:
XS GIS Cut Line= 3
      2740025.96        6777161.        2739926.        6777161.
      2739825.97      6777110.99
#Sta/Elev= 30
  4895.3  367.63  4905.3  367.16  4915.3  365.94  4925.3  365.05  4935.3     363
  4945.3  356.71  4955.3  354.63  4961.8  354.61  4985.3  355.28  4998.1  355.11
  5003.6  355.49  5009.2  356.87  5017.6  358.39    5026  355.59  5031.6  357.78
    5040  354.56  5048.4   354.7    5054  355.47  5060.3  354.55  5060.6  354.05
  5064.1  354.05  5064.3  354.55  5070.7  355.08  5073.1  358.42  5076.3  362.88
  5084.7  366.14  5093.1   368.6  5098.7  369.07  5104.3  370.44  5107.1  370.44
#Mann= 5 ,-1 , 0
  4895.3     .12       0  4961.8      .1       0  5060.3     .07       0
  5064.3      .1       0  5073.1     .12       0
Bank Sta=5054,5070.7
XS Rating Curve= 0 ,0
Exp/Cntr=0.3,0.1

Type RM Length L Ch R = 1 ,6517    ,342,342,342
BEGIN DESCRIPTION:
Caney Creek T 31 17.0
END DESCRIPTION:
XS GIS Cut Line= 3
      2740076.03      6777011.02        2739926.        6776911.
      2739876.02        6776911.
#Sta/Elev= 30
  4823.8  369.21  4826.8  369.21  4837.4  367.67  4859.9  365.83  4867.4  364.44
  4873.4  364.21  4882.4  363.13  4888.4  363.03    4896  362.17  4903.5  360.48
  4909.5  360.39  4918.5   358.2  4924.5  358.43    4932  357.41  4939.5   356.8
  4960.6  355.64  4968.1  354.96  4975.6   355.3  4981.6  354.99  4990.6  355.06
  4996.6  352.15  5006.6  352.31  5012.1  350.92  5012.4  350.42  5015.9  350.42
  5016.1  350.92  5024.1  352.68  5044.1  363.89  5051.6  366.48  5054.1  366.48
#Mann= 3 ,-1 , 0
  4823.8     .12       0  5012.1     .07       0  5016.1     .12       0
Bank Sta=5006.6,5024.1
XS Rating Curve= 0 ,0
Exp/Cntr=0.3,0.1

Type RM Length L Ch R = 1 ,6175    ,285,285,285
BEGIN DESCRIPTION:
Caney Creek T 31 16.0
END DESCRIPTION:
XS GIS Cut Line= 3
      2740351.27      6776758.09      2740167.18      6776717.99
      2739919.41      6776693.32
#Sta/Elev= 30
  4811.6  372.71  4865.7  369.68  4870.8  370.12  4909.1  367.88  4914.8  366.87
  4929.6  360.55  4939.8  354.77    4950  347.31  4956.8  346.72    4957  346.22
  4960.5  346.22  4960.8  346.72  4963.9  347.27    4991  347.81    4998  348.99
  5003.1  348.99  5011.2  351.18  5018.2  351.74  5023.2  351.16  5041.4  350.88
  5101.7  353.35  5111.7  349.42  5118.9  349.15  5123.9  354.41  5131.8  355.74
  5151.9  356.15  5182.1   359.5  5219.6   364.6  5224.6  364.25    5249  366.05
#Mann= 3 ,-1 , 0
  4811.6     .12       0  4956.8     .07       0  4960.8     .12       0
Bank Sta=4950,4963.9
XS Rating Curve= 0 ,0
Exp/Cntr=0.3,0.1

Type RM Length L Ch R = 1 ,5890    ,132,132,132
BEGIN DESCRIPTION:
Caney Creek T 31 15.0
END DESCRIPTION:
XS GIS Cut Line= 3
      2740163.56      6776526.46      2739979.54      6776509.54
      2739744.44      6776510.01
#Sta/Elev= 30
  4815.2  365.47    4819  364.17    4824  364.21  4842.9  362.11    4873  358.09
    4883  356.11  4913.2  352.72  4923.2   352.1  4928.8  351.31  4933.9  351.91
  4953.3   349.9  4973.4  347.35  4993.5  346.35  4997.3   345.7  4997.5   345.2
    5001   345.2  5001.3   345.7  5004.3   345.7  5013.5  348.69  5023.5   351.1
  5033.5   354.2  5053.5  357.24  5073.5  359.31  5093.5  360.95  5113.5  361.63
  5123.5  362.32  5143.5  362.67  5183.5  364.31  5203.5  364.55  5235.1  366.59
#Mann= 3 ,-1 , 0
  4815.2     .05       0  4997.3     .03       0  5001.3     .05       0
Bank Sta=4993.5,5013.5
XS Rating Curve= 0 ,0
Exp/Cntr=0.3,0.1

Type RM Length L Ch R = 1 ,5758    ,350,350,350
BEGIN DESCRIPTION:
Caney Creek T 31 14.0
END DESCRIPTION:
XS GIS Cut Line= 3
      2740163.37      6776379.25      2739974.41      6776378.07
      2739756.81      6776373.93
#Sta/Elev= 30
  4812.6  363.67    4830  363.25    4850  362.13    4860   360.9    4870  358.45
    4880  358.88    4890  358.41    4920  354.09    4930  352.16    4940  349.03
    4950  347.67    4970  347.38    4980  345.81    4990  344.86  4996.3  343.31
  4996.5  342.81    5000  342.81  5000.3  343.31    5010   344.7    5030  344.85
    5070   347.8    5080  350.27    5100  354.18  5107.6  356.83  5112.6  358.93
    5120  360.27    5130   360.8    5160  363.62    5210  366.63  5219.2  366.92
#Mann= 3 ,-1 , 0
  4812.6     .05       0  4996.3     .05       0  5000.3     .05       0
Bank Sta=4990,5010
XS Rating Curve= 0 ,0
Exp/Cntr=0.3,0.1

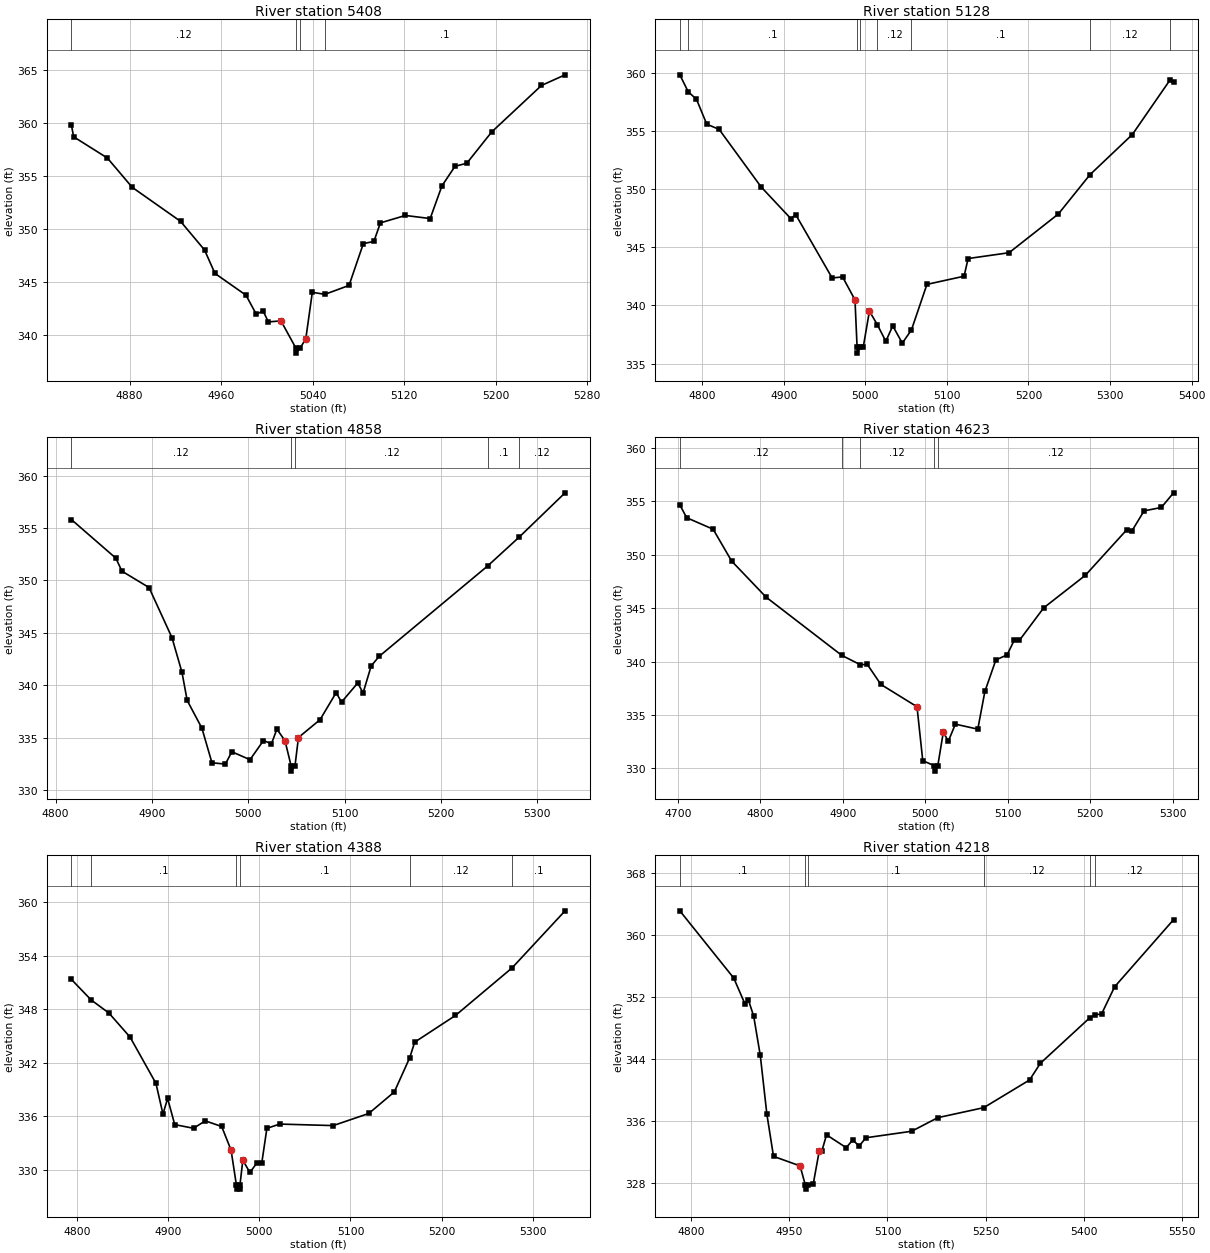
Type RM Length L Ch R = 1 ,5408    ,280,280,280
BEGIN DESCRIPTION:
Caney Creek T 31 13.0
END DESCRIPTION:
XS GIS Cut Line= 3
      2740022.28      6775964.62        2739876.        6776061.
      2739751.55      6776285.09
#Sta/Elev= 30
  4829.1   359.8  4831.1  358.66  4860.6  356.66  4882.3   353.9  4924.5   350.7
  4945.5     348  4954.6  345.79  4981.7  343.74  4990.7  341.95  4996.7  342.25
  5001.3  341.22  5012.3  341.32  5025.2  338.78  5025.4  338.28  5029.2  338.78
    5034  339.63  5039.7  344.01  5050.7  343.82  5071.8  344.66  5084.3   348.6
  5093.5   348.8  5099.2  350.55    5121  351.25  5142.7  350.96    5153  354.04
  5164.4  355.88  5174.7  356.17  5196.5  359.12    5240   363.5  5260.6   364.5
#Mann= 4 ,-1 , 0
  4829.1     .12       0  5025.2     .07       0  5029.2     .12       0
  5050.7      .1       0
Bank Sta=5012.3,5034
XS Rating Curve= 0 ,0
Exp/Cntr=0.3,0.1

Type RM Length L Ch R = 1 ,5128    ,270,270,270
BEGIN DESCRIPTION:
Caney Creek T 31 12.0
END DESCRIPTION:
XS GIS Cut Line= 3
      2739913.18      6775741.06        2739726.        6775861.
      2739680.51      6776241.18
#Sta/Elev= 30
  4772.6  359.82  4782.9  358.36    4793  357.72  4805.6  355.58  4820.8  355.13
  4872.3  350.18  4908.7  347.46  4914.6  347.81  4959.3  342.36  4972.1  342.45
  4987.3  340.48  4989.9   336.4  4990.2   335.9  4993.9   336.4  4997.4   336.4
    5005  339.51  5014.8  338.33  5025.1  336.92  5033.6  338.24  5045.3  336.76
  5056.5  337.89  5075.5  341.81    5121  342.51    5126  344.03  5176.2  344.53
  5236.6  347.86  5275.4  351.24  5327.3  354.69  5373.8  359.41  5377.8  359.18
#Mann= 8 ,-1 , 0
  4772.6     .12       0  4782.9      .1       0  4989.9     .07       0
  4993.9      .1       0  5014.8     .12       0  5056.5      .1       0
  5275.4     .12       0  5373.8      .1       0
Bank Sta=4987.3,5005
XS Rating Curve= 0 ,0
Exp/Cntr=0.3,0.1

Type RM Length L Ch R = 1 ,4858    ,235,235,235
BEGIN DESCRIPTION:
Caney Creek T 31 11.0
END DESCRIPTION:
XS GIS Cut Line= 3
      2739846.66      6775614.06        2739676.        6775661.
        2739376.        6775811.
#Sta/Elev= 30
  4816.3  355.82  4862.5  352.13  4868.8  350.89  4896.9  349.33  4920.7  344.55
  4931.1  341.24  4936.5  338.55  4951.8   335.9  4962.2   332.6  4976.1  332.47
  4982.9  333.65  5001.7  332.89  5015.7  334.72    5024  334.41  5029.6  335.81
    5038  334.71  5044.4   332.3  5044.7   331.8  5048.4   332.3    5052  335.01
  5074.4  336.71  5091.1  339.29  5096.7  338.39  5113.5  340.21  5119.1  339.27
  5127.5  341.85  5135.8  342.76  5248.5   351.4  5281.4  354.17  5328.7  358.37
#Mann= 5 ,-1 , 0
  4816.3     .12       0  5044.4     .07       0  5048.4     .12       0
  5248.5      .1       0  5281.4     .12       0
Bank Sta=5038,5052
XS Rating Curve= 0 ,0
Exp/Cntr=0.3,0.1

Type RM Length L Ch R = 1 ,4623    ,235,235,235
BEGIN DESCRIPTION:
Caney Creek T 31 10.0
END DESCRIPTION:
XS GIS Cut Line= 3
      2739803.76      6775405.22        2739526.        6775511.
      2739351.29      6775756.45
#Sta/Elev= 30
  4702.5  354.68  4710.8  353.48  4742.9   352.4  4765.3  349.42  4807.1  346.04
  4898.8  340.59  4921.2  339.72  4929.8  339.74  4946.2  337.87    4990  335.78
    4997  330.73  5011.2  330.25  5011.5  329.75  5015.2  330.25  5021.9   333.4
    5028  332.55  5036.5  334.15  5063.7  333.68  5072.3  337.21  5085.6  340.16
  5099.3  340.64  5107.9  342.02  5114.1  341.99  5143.6  345.04    5194  348.08
  5244.4  352.36  5250.6  352.25  5265.3  354.12  5286.2  354.44    5301  355.81
#Mann= 5 ,-1 , 0
  4702.5     .12       0  4898.8      .1       0  4921.2     .12       0
  5011.2     .07       0  5015.2     .12       0
Bank Sta=4990,5021.9
XS Rating Curve= 0 ,0
Exp/Cntr=0.3,0.1

Type RM Length L Ch R = 1 ,4388    ,170,170,170
BEGIN DESCRIPTION:
Caney Creek T 31 9.0
END DESCRIPTION:
XS GIS Cut Line= 3
      2739725.99        6775261.        2739526.        6775311.
      2739225.96      6775461.02
#Sta/Elev= 30
  4793.8  351.35  4815.5  349.04    4835  347.57  4858.2  344.87  4886.6  339.68
  4894.3  336.23  4899.4  337.99  4907.2  335.05  4927.8  334.64  4940.7  335.47
  4958.7  334.84    4969  332.19  4974.8  328.31    4975  327.81  4978.5  327.81
  4978.8  328.31  4981.9  331.06  4989.6  329.68  4997.4  330.75  5002.7  330.75
  5008.3  334.63  5022.3  335.11    5081  334.94  5120.1   336.3  5148.1  338.72
  5165.1  342.58  5170.4   344.3  5215.2   347.3  5277.3  352.64  5335.4  359.04
#Mann= 6 ,-1 , 0
  4793.8     .12       0  4815.5      .1       0  4974.8     .07       0
  4978.8      .1       0  5165.1     .12       0  5277.3      .1       0
Bank Sta=4969,4981.9
XS Rating Curve= 0 ,0
Exp/Cntr=0.3,0.1

Type RM Length L Ch R = 1 ,4218    ,365,365,365
BEGIN DESCRIPTION:
Caney Creek T 31 8.0
END DESCRIPTION:
XS GIS Cut Line= 3
      2739827.32      6775139.82      2739612.88      6775174.32
      2739076.05        6775161.
#Sta/Elev= 30
  4782.8   363.1  4865.2  354.44  4882.5  351.07  4887.6  351.61  4895.6  349.55
  4905.7  344.49  4915.8   336.9  4925.9  331.49  4966.5  330.26  4974.6  327.77
  4974.8  327.27  4978.6  327.77  4986.7  327.98  4995.9  332.24    5000  332.24
  5006.9  334.26  5036.9  332.61  5046.9  333.59  5056.9  332.82  5066.9  333.88
  5136.9  334.72  5176.9  336.47  5247.1  337.76    5317  341.32  5333.7  343.48
  5408.9  349.32  5417.6  349.73    5427  349.81    5447  353.32    5537  361.96
#Mann= 6 ,-1 , 0
  4782.8      .1       0  4974.6     .07       0  4978.6      .1       0
  5247.1     .12       0  5408.9      .1       0  5417.6     .12       0
Bank Sta=4966.5,4995.9
XS Rating Curve= 0 ,0
Exp/Cntr=0.3,0.1

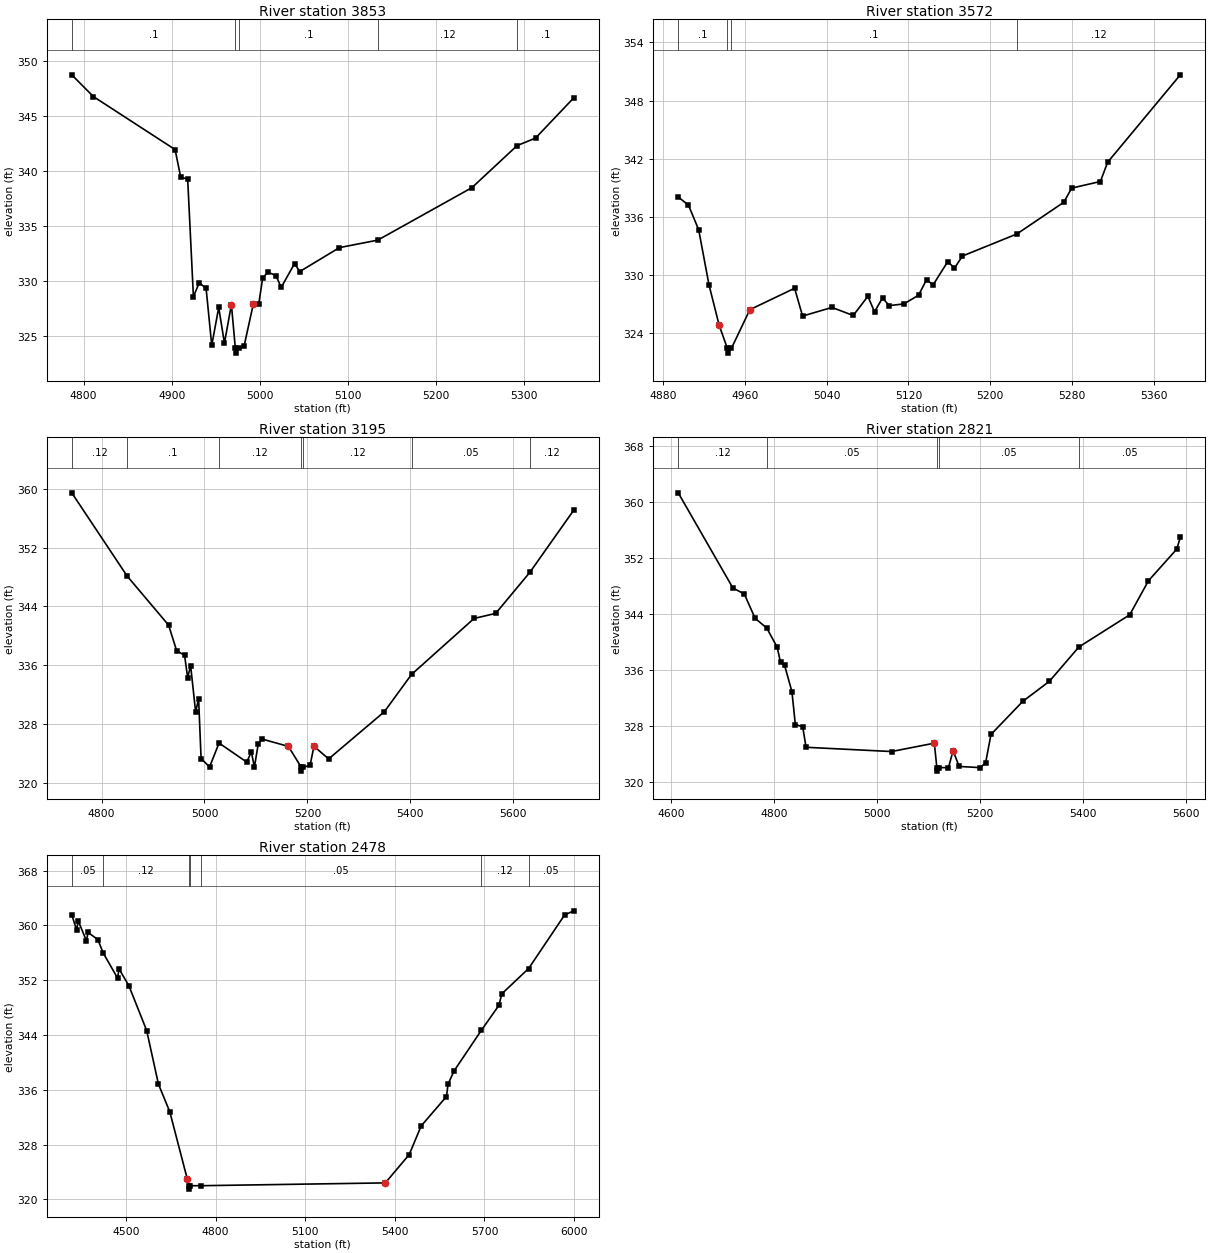
Type RM Length L Ch R = 1 ,3853    ,281,281,281
BEGIN DESCRIPTION:
Caney Creek T 31 7.0
END DESCRIPTION:
XS GIS Cut Line= 3
      2739688.07       6774778.9        2739526.        6774911.
      2739226.04      6775110.98
#Sta/Elev= 30
  4786.6  348.72  4811.1  346.75  4903.8  341.94  4910.2  339.44  4918.1  339.26
  4924.6  328.59  4931.2  329.87    4939  329.35  4945.4  324.18  4953.3  327.62
  4959.8  324.39  4967.7  327.88  4972.1  323.98  4972.4  323.48  4976.1  323.98
  4982.1  324.12  4992.5  327.91  4998.7  327.91  5003.2  330.31  5009.2  330.82
  5018.2  330.52  5024.2  329.44  5039.3   331.6  5045.3  330.88  5090.3  333.05
  5133.8  333.73  5240.6  338.49  5291.8   342.3  5312.7  342.98  5356.2  346.64
#Mann= 5 ,-1 , 0
  4786.6      .1       0  4972.1     .07       0  4976.1      .1       0
  5133.8     .12       0  5291.8      .1       0
Bank Sta=4967.7,4992.5
XS Rating Curve= 0 ,0
Exp/Cntr=0.3,0.1

Type RM Length L Ch R = 1 ,3572    ,377,377,377
BEGIN DESCRIPTION:
Caney Creek T 31 6.0
END DESCRIPTION:
XS GIS Cut Line= 3
      2739526.04        6774661.        2739426.        6774661.
      2739125.96      6774911.03
#Sta/Elev= 30
  4895.1  338.04  4905.1   337.2  4915.1  334.64  4925.1  328.99  4935.1  324.78
  4943.1  322.41  4943.4  321.91  4947.1  322.41  4965.1   326.4  5008.8  328.61
  5016.6  325.74  5045.3  326.63  5066.1   325.8  5080.4  327.78  5086.9  326.18
  5094.7  327.61  5101.2  326.82  5115.5  326.99  5129.9  327.89  5137.7  329.49
  5144.2  328.97  5158.5  331.37    5165  330.69  5172.8  331.94    5226  334.22
  5271.8  337.49  5279.6  338.96  5307.6  339.64  5314.7  341.63  5385.7  350.66
#Mann= 4 ,-1 , 0
  4895.1      .1       0  4943.1     .07       0  4947.1      .1       0
    5226     .12       0
Bank Sta=4935.1,4965.1
XS Rating Curve= 0 ,0
Exp/Cntr=0.3,0.1

Type RM Length L Ch R = 1 ,3195    ,374,374,374
BEGIN DESCRIPTION:
Caney Creek T 31 5.0
END DESCRIPTION:
XS GIS Cut Line= 3
      2739743.46      6774492.56        2739526.        6774361.
      2738925.98      6773960.98
#Sta/Elev= 30
  4742.2  359.44  4849.6  348.13  4930.4  341.43  4945.9  337.96  4961.3  337.34
  4967.3  334.31  4973.1  335.91  4982.8  329.63  4988.6  331.42  4993.4  323.29
  5009.9  322.15  5028.3   325.4    5082  322.81    5091  324.18    5097  322.14
  5104.5  325.31    5112  325.94  5163.1  324.94  5188.2  322.08  5188.4  321.58
  5192.2  322.08  5205.2  322.41  5212.7  324.96  5241.2  323.24  5349.4  329.66
  5402.3  334.74  5523.7  342.35  5565.7  343.04    5632  348.62  5717.5   357.1
#Mann= 7 ,-1 , 0
  4742.2     .12       0  4849.6      .1       0  5028.3     .12       0
  5188.2     .07       0  5192.2     .12       0  5402.3     .05       0
    5632     .12       0
Bank Sta=5163.1,5212.7
XS Rating Curve= 0 ,0
Exp/Cntr=0.3,0.1

Type RM Length L Ch R = 1 ,2821    ,343,343,343
BEGIN DESCRIPTION:
Caney Creek T 31 4.0
END DESCRIPTION:
XS GIS Cut Line= 3
        2739776.      6774311.01        2739526.        6774011.
      2738959.19      6773871.67
#Sta/Elev= 30
  4614.2  361.29  4720.3  347.68  4742.4  346.83  4763.3  343.35    4786  341.96
  4806.2  339.21  4812.7  337.04  4820.5  336.64  4834.8  332.86  4841.4  328.16
  4855.7  327.85  4862.2  324.91  5028.1   324.3  5111.1   325.5    5116     322
  5116.2   321.5    5120     322  5138.6     322  5147.5  324.43  5159.2  322.17
  5200.4     322  5210.7  322.72    5221  326.74  5282.8  331.48  5334.2  334.33
  5391.6  339.25  5490.2  343.85  5526.6  348.72  5581.4  353.23  5588.4  354.92
#Mann= 5 ,-1 , 0
  4614.2     .12       0    4786     .05       0    5116     .05       0
    5120     .05       0  5391.6     .05       0
Bank Sta=5111.1,5147.5
XS Rating Curve= 0 ,0
Exp/Cntr=0.3,0.1

Type RM Length L Ch R = 1 ,2478    ,0,0,0
BEGIN DESCRIPTION:
Caney Creek T 31 3.0
END DESCRIPTION:
XS GIS Cut Line= 3
      2739875.88      6774371.02        2739676.        6773711.
      2738685.07      6773684.66
#Sta/Elev= 30
  4318.4  361.56  4334.7  359.31  4339.9  360.67  4367.6  357.74  4372.8  358.97
  4405.7  357.94  4423.5  355.99  4471.6  352.32  4476.8  353.63  4509.7  351.19
  4569.2  344.65  4608.5  336.84  4646.7  332.77    4705     323  4710.5     322
  4710.7   321.5  4714.5     322  4750.8     322  5368.2  322.41  5448.2  326.55
  5488.2  330.73  5572.9  335.02  5578.2  336.83  5598.2  338.75  5689.4  344.67
  5748.3  348.32  5758.3  350.02  5847.9  353.71  5968.4  361.53  5999.3  362.13
#Mann= 7 ,-1 , 0
  4318.4     .05       0  4423.5     .12       0  4710.5     .03       0
  4714.5     .12       0  4750.8     .05       0  5689.4     .12       0
  5847.9     .05       0
Bank Sta=4705,5368.2
XS Rating Curve= 0 ,0
Exp/Cntr=0.3,0.1

Chan Stop Cuts=-1
Use User Specified Reach Order=0
Composite Channel Slope=5