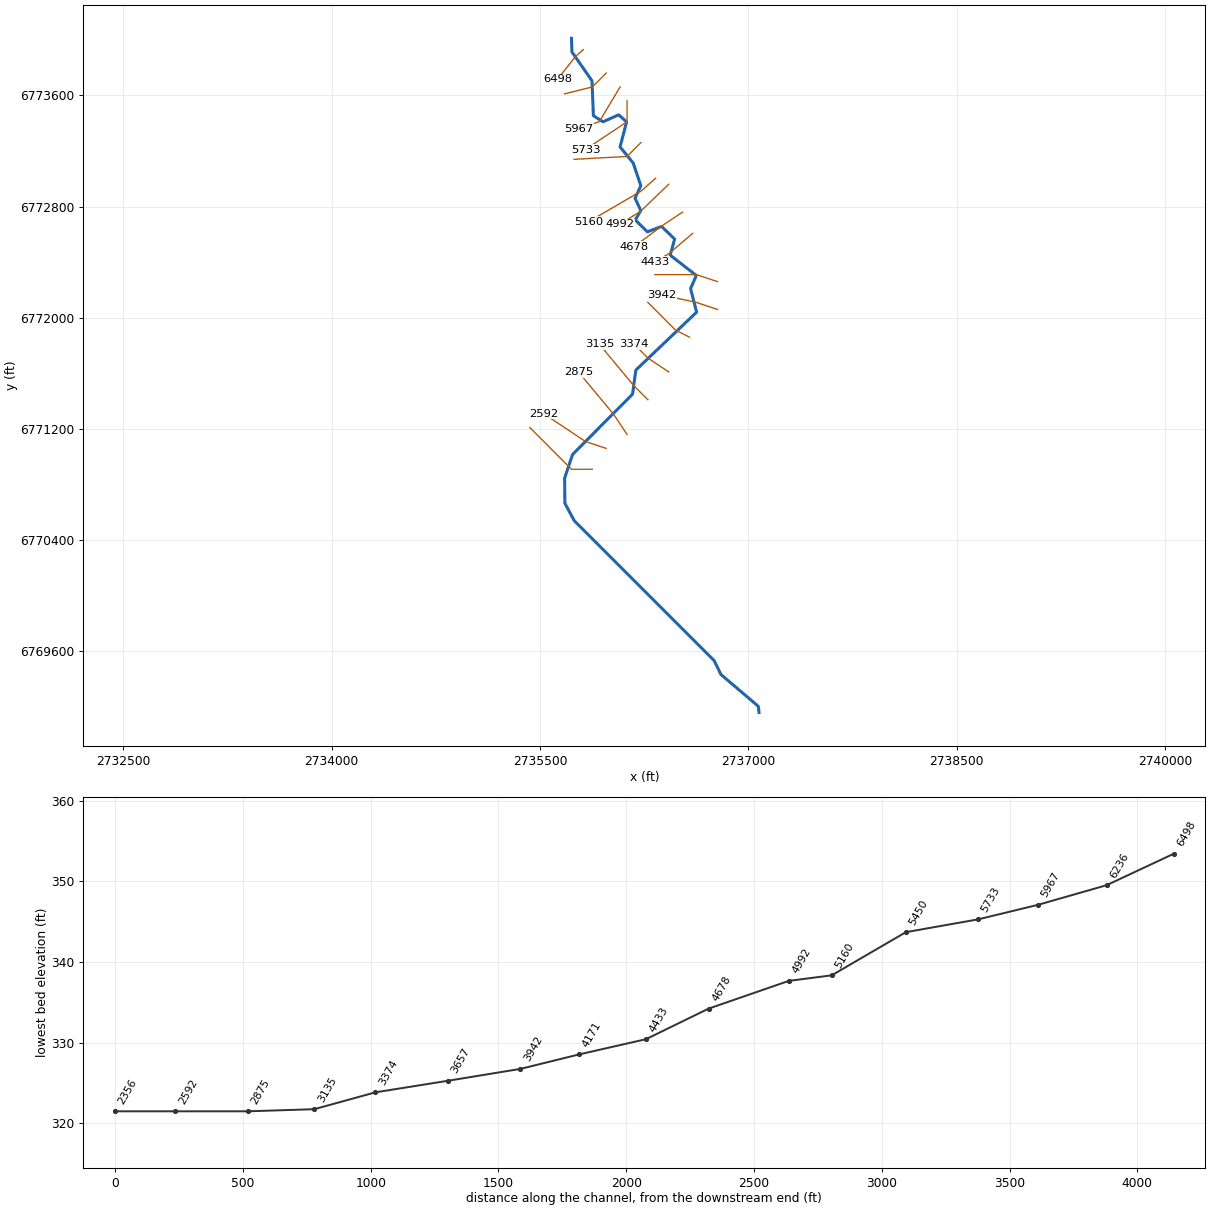
--- Caney Creek T 32.prj (project) ---

Proj Title=Caney Creek T 32 Base Level Engineering
Current Plan=p01
Default Exp/Contr=0.3,0.1
English Units
Geom File=g01
Flow File=f01
Plan File=p01
BEGIN DESCRIPTION:
Caney Creek T 32
END DESCRIPTION:

--- Caney Creek T 32.p01 (plan) ---

Plan Title=Multiple Run
Short Identifier=Multiple
Geom File=g01
Flow File=f01
Subcritical Flow
K Sum by GR= 0
Std Step Tol= 0.01
Critical Tol= 0.01
Num of Std Step Trials= 20
Max Error Tol= 0.3
Flow Tol Ratio= 0.001
Split Flow NTrial= 30
Split Flow Tol= 0.02
Split Flow Ratio= 0.02
Log Output Level= 0
Friction Slope Method= 1
Unsteady Friction Slope Method= 2
Unsteady Bridges Friction Slope Method= 1
Parabolic Critical Depth
Global Vel Dist=  1 , 1 , 1
Global Log Level= 0
CheckData=True
Encroach Param= -1, 0, 0, 0
BEGIN DESCRIPTION:
Multiple Run
END DESCRIPTION:

--- Caney Creek T 32.f01 (steady flow) ---

Flow Title=Multiple
Number of Profiles=7
Profile Names=10-year,25-year,50-year,1pct_min,100-year,1pct_plu,500-year
River Rch & RM= Caney Creek T 32,Reach-1,6498
     271     345     402     234     466     931     624
River Rch & RM= Caney Creek T 32,Reach-1,4171
     488     645     770     457     911    1818    1273
Boundary for River Rch & Prof#=Caney Creek T 32,Reach-1,1
Up Type=0
Dn Type=3
Dn Slope=0.005
Boundary for River Rch & Prof#=Caney Creek T 32,Reach-1,2
Up Type=0
Dn Type=3
Dn Slope=0.005
Boundary for River Rch & Prof#=Caney Creek T 32,Reach-1,3
Up Type=0
Dn Type=3
Dn Slope=0.005
Boundary for River Rch & Prof#=Caney Creek T 32,Reach-1,4
Up Type=0
Dn Type=3
Dn Slope=0.005
Boundary for River Rch & Prof#=Caney Creek T 32,Reach-1,5
Up Type=0
Dn Type=3
Dn Slope=0.005
Boundary for River Rch & Prof#=Caney Creek T 32,Reach-1,6
Up Type=0
Dn Type=3
Dn Slope=0.005
Boundary for River Rch & Prof#=Caney Creek T 32,Reach-1,7
Up Type=0
Dn Type=3
Dn Slope=0.005

--- Caney Creek T 32.g01 (geometry) ---

Geom Title=Existing Conditions

River Reach=Caney Creek T 32,Reach-1
Reach XY= 30
      2735726.00      6774011.00      2735729.39      6773912.41
      2735873.65      6773705.48      2735883.69      6773454.43
      2735953.08      6773410.51      2736065.55      6773460.47
      2736122.63      6773409.78      2736075.70      6773229.38
      2736170.46      6773113.42      2736225.19      6772950.29
      2736183.62      6772861.00      2736225.01      6772771.64
      2736185.15      6772704.23      2736272.56      6772618.82
      2736374.37      6772657.85      2736468.50      6772567.07
      2736436.95      6772450.63      2736624.67      6772304.94
      2736583.57      6772211.01      2736626.49      6772040.77
      2736189.37      6771624.32      2736165.52      6771451.20
      2735733.86      6771017.17      2735676.68      6770847.08
      2735678.35      6770666.52      2735745.78      6770540.91
      2736752.98      6769534.47      2736802.30      6769434.18
      2737071.08      6769205.67      2737076.00      6769161.00

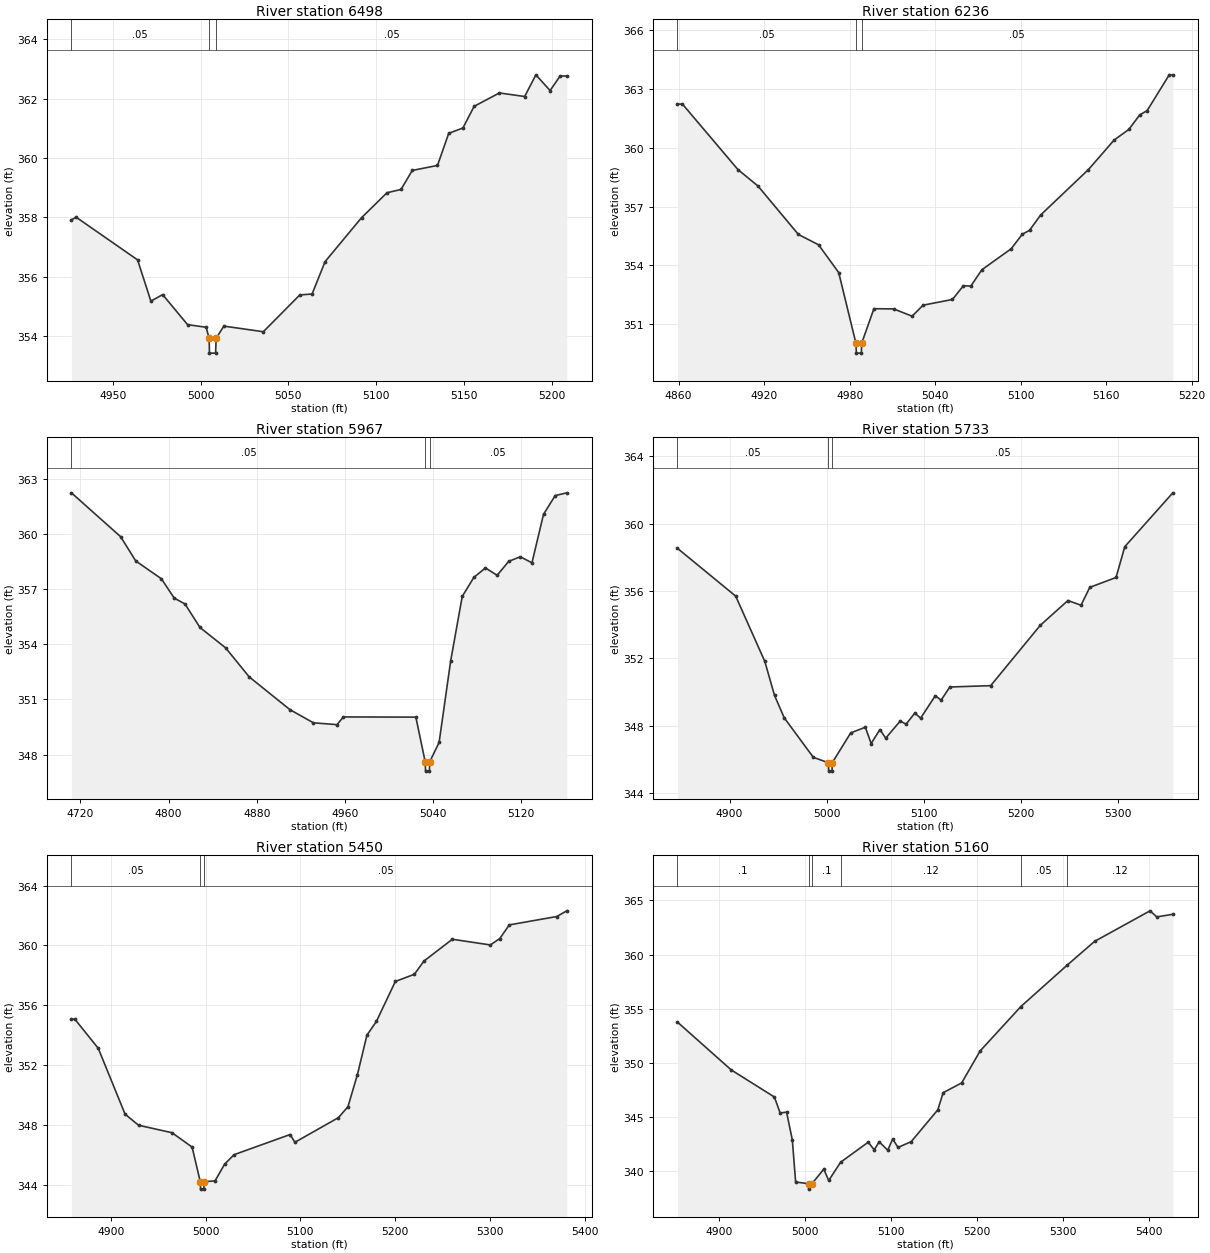
Type RM Length L Ch R = 1,6498,262,262,262
BEGIN DESCRIPTION:
Caney Creek T 32 20.0
END DESCRIPTION:
XS GIS Cut Line= 3
      2735811.17      6773929.26      2735755.61      6773880.84
      2735626.25      6773717.06
#Sta/Elev= 30
  4926.3  357.91  4928.9  358.01  4964.0  356.57  4971.6  355.18  4978.3  355.40
  4992.5  354.39  5003.1  354.30  5004.8  353.93  5005.0  353.43  5008.5  353.43
  5008.8  353.93  5013.2  354.34  5035.7  354.15  5056.5  355.39  5063.5  355.42
  5070.9  356.51  5091.7  357.99  5106.2  358.83  5114.2  358.94  5120.6  359.58
  5135.0  359.75  5141.4  360.83  5149.5  361.01  5155.9  361.74  5170.3  362.19
  5184.7  362.07  5191.1  362.80  5199.2  362.27  5204.9  362.76  5208.7  362.76
#Mann=3,-1,0
  4926.3    0.05       0  5004.8    0.03       0  5008.8    0.05       0
Bank Sta=5004.8,5008.8
Exp/Cntr=0.3,0.1

Type RM Length L Ch R = 1,6236,269,269,269
BEGIN DESCRIPTION:
Caney Creek T 32 19.0
END DESCRIPTION:
XS GIS Cut Line= 3
      2735975.97      6773760.97      2735876.00      6773661.00
      2735676.03      6773611.01
#Sta/Elev= 30
  4859.2  362.21  4862.7  362.21  4901.6  358.88  4915.7  358.04  4944.0  355.58
  4958.2  355.05  4972.3  353.64  4984.4  350.04  4984.7  349.54  4988.2  349.54
  4988.4  350.04  4997.0  351.80  5010.9  351.79  5023.8  351.42  5031.5  351.98
  5052.1  352.27  5059.8  352.97  5065.0  352.95  5072.7  353.78  5093.3  354.85
  5101.1  355.59  5106.2  355.79  5114.0  356.57  5147.5  358.88  5165.5  360.38
  5175.8  360.92  5183.5  361.66  5188.7  361.88  5204.2  363.70  5206.7  363.70
#Mann=3,-1,0
  4859.2    0.05       0  4984.4    0.03       0  4988.4    0.05       0
Bank Sta=4984.4,4988.4
Exp/Cntr=0.3,0.1

Type RM Length L Ch R = 1,5967,234,234,234
BEGIN DESCRIPTION:
Caney Creek T 32 18.0
END DESCRIPTION:
XS GIS Cut Line= 3
      2736076.02      6773661.04      2735926.00      6773411.00
      2735776.00      6773361.00
#Sta/Elev= 30
  4711.8  362.25  4756.5  359.86  4770.2  358.54  4793.5  357.57  4805.1  356.52
  4814.9  356.20  4828.5  354.92  4851.8  353.81  4873.2  352.23  4910.1  350.45
  4931.5  349.73  4952.9  349.63  4958.7  350.05  5024.5  350.04  5033.0  347.60
  5033.3  347.10  5036.8  347.10  5037.0  347.60  5045.6  348.66  5056.1  353.10
  5066.6  356.61  5077.2  357.65  5087.7  358.16  5098.3  357.76  5108.8  358.52
  5119.3  358.77  5129.9  358.44  5140.4  361.08  5151.0  362.10  5161.5  362.25
#Mann=3,-1,0
  4711.8    0.05       0  5033.0    0.03       0  5037.0    0.05       0
Bank Sta=5033,5037
Exp/Cntr=0.3,0.1

Type RM Length L Ch R = 1,5733,283,283,283
BEGIN DESCRIPTION:
Caney Creek T 32 17.0
END DESCRIPTION:
XS GIS Cut Line= 3
      2736126.00      6773560.99      2736126.00      6773411.00
      2735826.04      6773211.03
#Sta/Elev= 30
  4846.3  358.54  4906.3  355.70  4936.3  351.82  4946.3  349.80  4956.3  348.47
  4986.3  346.12  5001.8  345.80  5002.1  345.30  5005.6  345.30  5005.8  345.80
  5024.8  347.57  5039.9  347.91  5045.9  346.94  5054.9  347.77  5060.9  347.26
  5075.9  348.28  5081.9  348.09  5090.9  348.75  5096.9  348.45  5112.0  349.78
  5118.0  349.52  5127.0  350.30  5169.1  350.38  5220.1  353.96  5248.7  355.44
  5262.2  355.16  5271.2  356.22  5298.3  356.81  5307.3  358.64  5356.8  361.84
#Mann=3,-1,0
  4846.3    0.05       0  5001.8    0.03       0  5005.8    0.05       0
Bank Sta=5001.8,5005.8
Exp/Cntr=0.3,0.1

Type RM Length L Ch R = 1,5450,290,290,290
BEGIN DESCRIPTION:
Caney Creek T 32 16.0
END DESCRIPTION:
XS GIS Cut Line= 3
      2736226.03      6773261.03      2736126.00      6773161.00
      2735745.51      6773140.58
#Sta/Elev= 30
  4858.5  355.07  4862.1  355.07  4886.8  353.12  4915.1  348.72  4929.3  347.98
  4964.6  347.48  4985.8  346.52  4994.4  344.21  4994.7  343.71  4998.2  343.71
  4998.4  344.21  5010.0  344.26  5020.0  345.37  5030.0  346.01  5089.2  347.36
  5094.2  346.84  5140.2  348.49  5150.2  349.22  5160.2  351.37  5170.2  354.00
  5180.2  354.92  5200.2  357.59  5220.3  358.07  5230.3  358.95  5260.3  360.41
  5300.4  360.03  5310.4  360.46  5320.4  361.37  5370.5  361.93  5381.0  362.31
#Mann=3,-1,0
  4858.5    0.05       0  4994.4    0.03       0  4998.4    0.05       0
Bank Sta=4994.4,4998.4
Exp/Cntr=0.3,0.1

Type RM Length L Ch R = 1,5160,168,168,168
BEGIN DESCRIPTION:
Caney Creek T 32 15.0
END DESCRIPTION:
XS GIS Cut Line= 3
      2736331.55      6773004.07      2736226.00      6772911.00
      2735849.93      6772691.62
#Sta/Elev= 30
  4851.5  353.77  4914.0  349.36  4964.2  346.86  4970.9  345.39  4978.4  345.46
  4985.1  342.88  4988.9  339.02  5003.9  338.86  5004.1  338.36  5007.9  338.86
  5021.6  340.20  5027.4  339.16  5041.2  340.84  5073.3  342.69  5080.3  341.99
  5086.1  342.73  5096.0  341.95  5101.8  342.98  5108.0  342.21  5123.3  342.74
  5154.3  345.68  5160.5  347.26  5182.0  348.16  5203.5  351.11  5250.9  355.21
  5304.9  359.04  5336.6  361.22  5401.1  364.04  5409.0  363.48  5427.6  363.72
#Mann=6,-1,0
  4851.5     0.1       0  5003.9    0.07       0  5007.9     0.1       0
  5041.2    0.12       0  5250.9    0.05       0  5304.9    0.12       0
Bank Sta=5003.9,5007.9
Exp/Cntr=0.3,0.1

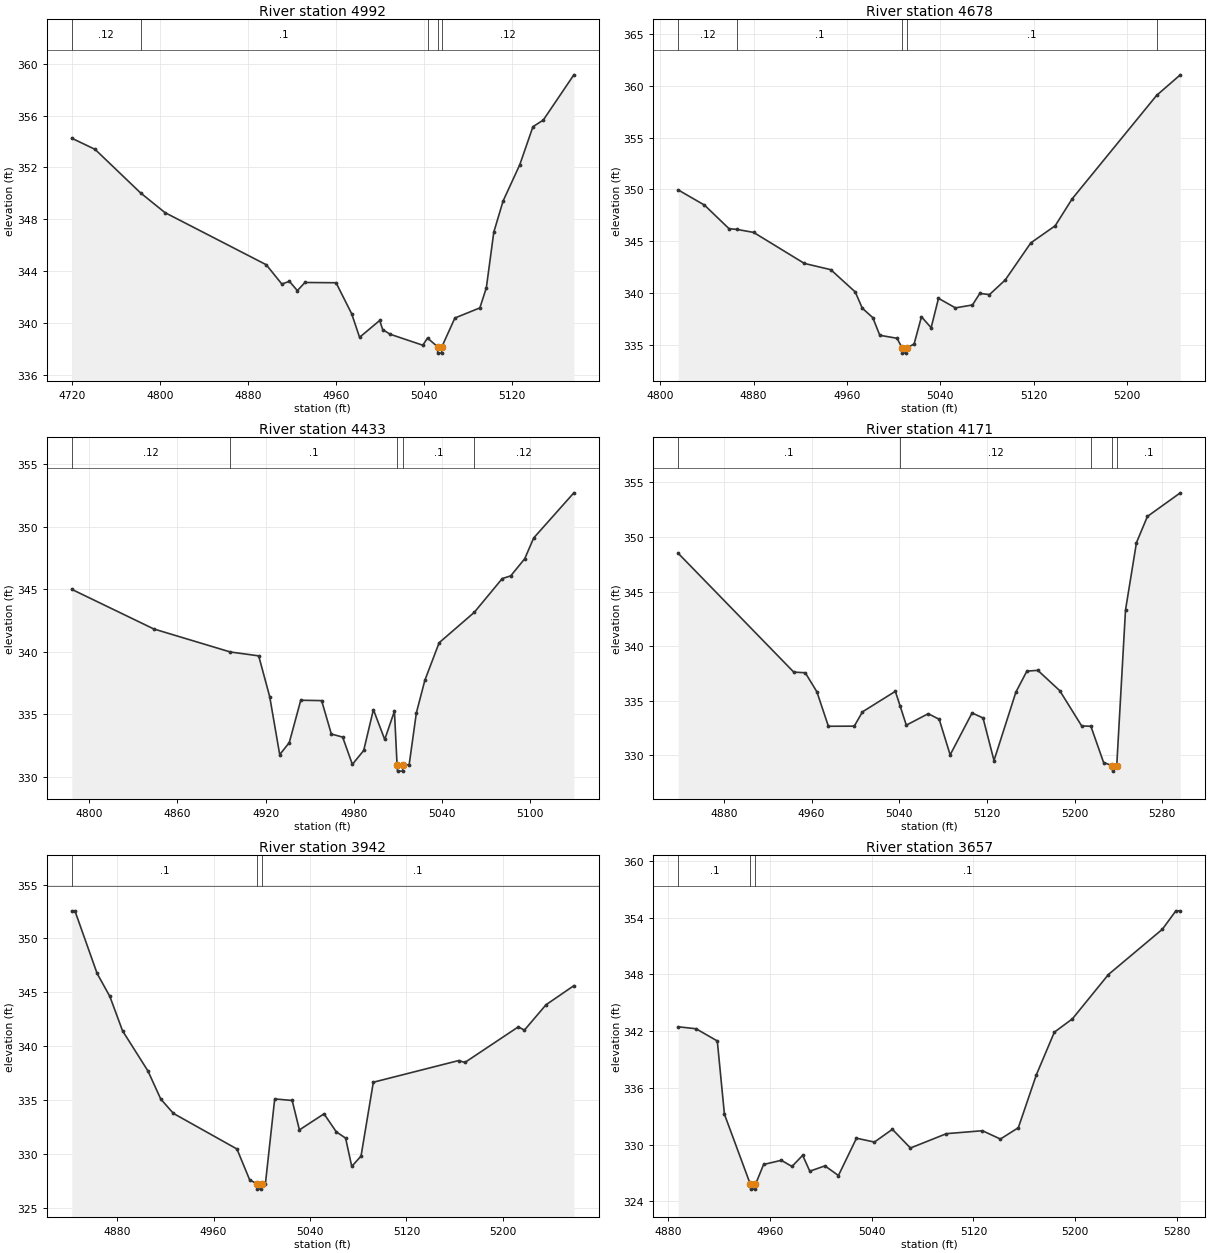
Type RM Length L Ch R = 1,4992,314,314,314
BEGIN DESCRIPTION:
Caney Creek T 32 14.0
END DESCRIPTION:
XS GIS Cut Line= 3
      2736426.01      6772961.01      2736223.93      6772767.05
      2736074.31      6772673.23
#Sta/Elev= 30
  4719.9  354.25  4741.1  353.39  4782.5  350.03  4804.7  348.51  4896.8  344.49
  4911.0  343.00  4917.9  343.21  4925.1  342.49  4932.0  343.12  4960.3  343.10
  4974.5  340.71  4981.7  338.89  5000.0  340.19  5002.7  339.49  5009.4  339.13
  5039.2  338.28  5043.5  338.83  5052.6  338.17  5052.8  337.67  5056.3  337.67
  5056.6  338.17  5068.4  340.38  5091.1  341.16  5097.0  342.71  5103.8  347.01
  5112.3  349.42  5127.4  352.20  5139.4  355.14  5148.8  355.65  5176.6  359.14
#Mann=5,-1,0
  4719.9    0.12       0  4782.5     0.1       0  5043.5    0.12       0
  5052.6    0.07       0  5056.6    0.12       0
Bank Sta=5052.6,5056.6
Exp/Cntr=0.3,0.1

Type RM Length L Ch R = 1,4678,245,245,245
BEGIN DESCRIPTION:
Caney Creek T 32 13.0
END DESCRIPTION:
XS GIS Cut Line= 3
      2736525.97      6772760.98      2736376.00      6772661.00
      2736176.04      6772511.03
#Sta/Elev= 30
  4815.5  349.95  4838.0  348.49  4859.0  346.22  4865.7  346.15  4880.1  345.86
  4923.6  342.87  4946.2  342.27  4967.2  340.12  4973.2  338.56  4982.2  337.65
  4988.2  335.95  5003.0  335.66  5007.3  334.73  5007.5  334.23  5011.0  334.23
  5011.3  334.73  5017.6  335.11  5023.9  337.73  5032.2  336.68  5038.5  339.51
  5053.0  338.59  5067.6  338.87  5073.9  339.98  5082.2  339.87  5095.7  341.28
  5117.6  344.85  5138.5  346.50  5153.0  349.09  5225.4  359.06  5245.7  361.04
#Mann=5,-1,0
  4815.5    0.12       0  4865.7     0.1       0  5007.3    0.07       0
  5011.3     0.1       0  5225.4    0.12       0
Bank Sta=5007.3,5011.3
Exp/Cntr=0.3,0.1

Type RM Length L Ch R = 1,4433,262,262,262
BEGIN DESCRIPTION:
Caney Creek T 32 12.0
END DESCRIPTION:
XS GIS Cut Line= 3
      2736598.54      6772607.74      2736426.00      6772461.00
      2736327.32      6772402.13
#Sta/Elev= 30
  4788.2  344.98  4844.0  341.81  4896.0  339.97  4915.3  339.66  4922.8  336.39
  4929.6  331.76  4936.1  332.72  4943.9  336.11  4958.1  336.08  4964.7  333.41
  4972.4  333.16  4979.0  330.98  4986.7  332.09  4993.3  335.36  5001.0  332.97
  5007.6  335.23  5009.4  330.94  5009.7  330.44  5013.2  330.44  5013.4  330.94
  5017.6  330.94  5022.5  335.09  5028.3  337.71  5038.0  340.71  5061.9  343.14
  5080.9  345.84  5086.7  346.06  5096.2  347.43  5102.3  349.09  5129.6  352.70
#Mann=5,-1,0
  4788.2    0.12       0  4896.0     0.1       0  5009.4    0.07       0
  5013.4     0.1       0  5061.9    0.12       0
Bank Sta=5009.4,5013.4
Exp/Cntr=0.3,0.1

Type RM Length L Ch R = 1,4171,229,229,229
BEGIN DESCRIPTION:
Caney Creek T 32 11.0
END DESCRIPTION:
XS GIS Cut Line= 3
      2736775.97      6772261.01      2736626.00      6772311.00
      2736325.98      6772311.00
#Sta/Elev= 30
  4838.4  348.50  4943.8  337.62  4954.3  337.56  4964.9  335.82  4975.4  332.66
  4999.0  332.67  5006.5  333.98  5036.5  335.86  5040.7  334.56  5046.5  332.76
  5066.5  333.81  5076.5  333.30  5086.5  330.04  5106.5  333.88  5116.5  333.42
  5126.5  329.52  5146.5  335.79  5156.5  337.71  5166.5  337.78  5186.5  335.92
  5206.5  332.69  5214.9  332.66  5226.5  329.34  5234.5  329.05  5234.7  328.55
  5238.5  329.05  5246.5  343.31  5256.5  349.48  5266.5  351.88  5296.5  354.04
#Mann=5,-1,0
  4838.4     0.1       0  5040.7    0.12       0  5214.9     0.1       0
  5234.5    0.07       0  5238.5     0.1       0
Bank Sta=5234.5,5238.5
Exp/Cntr=0.3,0.1

Type RM Length L Ch R = 1,3942,285,285,285
BEGIN DESCRIPTION:
Caney Creek T 32 10.0
END DESCRIPTION:
XS GIS Cut Line= 3
      2736775.97      6772061.01      2736626.00      6772111.00
      2736373.41      6772165.11
#Sta/Elev= 30
  4842.4  352.56  4845.0  352.56  4863.4  346.76  4874.0  344.62  4884.5  341.44
  4905.6  337.71  4916.2  335.11  4926.7  333.78  4979.4  330.48  4989.9  327.63
  4995.8  327.26  4996.1  326.76  4999.6  326.76  4999.8  327.26  5003.0  327.26
  5010.7  335.12  5025.2  334.98  5031.2  332.25  5051.6  333.74  5061.8  332.07
  5069.5  331.49  5074.6  328.87  5082.3  329.82  5092.5  336.67  5163.3  338.68
  5168.4  338.50  5212.7  341.80  5217.8  341.50  5235.7  343.85  5258.8  345.62
#Mann=3,-1,0
  4842.4     0.1       0  4995.8    0.07       0  4999.8     0.1       0
Bank Sta=4995.8,4999.8
Exp/Cntr=0.3,0.1

Type RM Length L Ch R = 1,3657,283,283,283
BEGIN DESCRIPTION:
Caney Creek T 32 9.0
END DESCRIPTION:
XS GIS Cut Line= 3
      2736575.98      6771861.01      2736476.00      6771911.00
      2736276.02      6772110.98
#Sta/Elev= 30
  4888.0  342.46  4902.0  342.25  4918.7  340.96  4924.3  333.21  4944.7  325.78
  4944.9  325.28  4948.4  325.28  4948.7  325.78  4955.1  327.89  4969.0  328.33
  4977.4  327.68  4985.8  328.86  4991.4  327.18  5003.3  327.74  5013.9  326.72
  5028.1  330.67  5042.2  330.26  5056.3  331.61  5070.5  329.63  5098.8  331.15
  5127.1  331.46  5141.2  330.58  5155.3  331.78  5169.5  337.39  5183.6  341.89
  5197.8  343.30  5226.1  347.99  5268.5  352.78  5279.1  354.73  5282.6  354.73
#Mann=3,-1,0
  4888.0     0.1       0  4944.7    0.07       0  4948.7     0.1       0
Bank Sta=4944.7,4948.7
Exp/Cntr=0.3,0.1

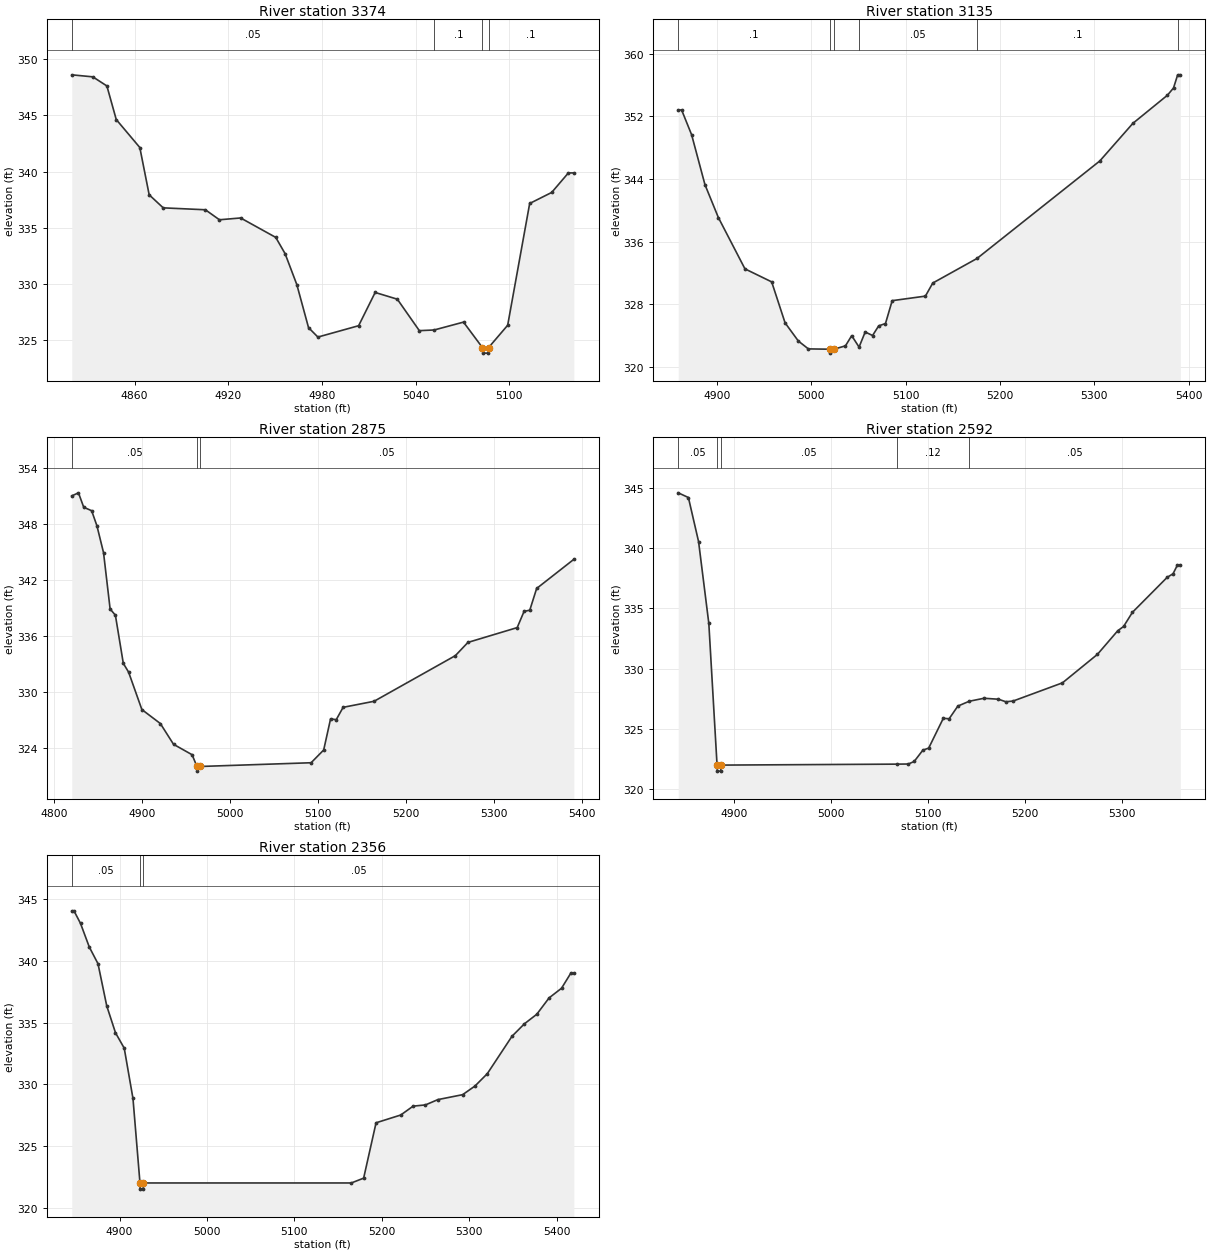
Type RM Length L Ch R = 1,3374,239,239,239
BEGIN DESCRIPTION:
Caney Creek T 32 8.0
END DESCRIPTION:
XS GIS Cut Line= 3
      2736425.99      6771611.01      2736276.00      6771711.00
      2736175.99      6771811.01
#Sta/Elev= 30
  4819.7  348.62  4833.2  348.44  4842.2  347.63  4848.2  344.64  4863.3  342.15
  4869.3  337.94  4878.3  336.78  4905.3  336.61  4914.3  335.72  4927.9  335.88
  4950.4  334.15  4956.4  332.70  4963.9  329.95  4971.4  326.12  4977.4  325.28
  5003.5  326.29  5014.1  329.25  5028.3  328.65  5042.4  325.85  5051.9  325.91
  5070.7  326.61  5082.8  324.35  5083.1  323.85  5086.6  323.85  5086.8  324.35
  5099.0  326.33  5113.1  337.17  5127.2  338.15  5137.9  339.89  5141.4  339.89
#Mann=4,-1,0
  4819.7    0.05       0  5051.9     0.1       0  5082.8    0.03       0
  5086.8     0.1       0
Bank Sta=5082.8,5086.8
Exp/Cntr=0.3,0.1

Type RM Length L Ch R = 1,3135,260,260,260
BEGIN DESCRIPTION:
Caney Creek T 32 7.0
END DESCRIPTION:
XS GIS Cut Line= 3
      2736276.02      6771410.98      2736176.00      6771511.00
      2735925.97      6771811.03
#Sta/Elev= 30
  4859.0  352.81  4862.6  352.81  4873.2  349.64  4887.3  343.28  4901.5  339.08
  4929.7  332.52  4958.0  330.86  4972.2  325.63  4986.3  323.30  4996.9  322.30
  5019.9  322.26  5020.2  321.76  5023.9  322.26  5036.2  322.69  5042.8  323.99
  5050.6  322.53  5057.1  324.46  5064.9  324.01  5071.4  325.24  5078.6  325.54
  5085.7  328.46  5120.9  329.04  5128.7  330.71  5175.6  333.85  5305.7  346.30
  5340.8  351.11  5377.3  354.69  5383.8  355.62  5388.2  357.30  5391.0  357.30
#Mann=6,-1,0
  4859.0     0.1       0  5019.9    0.07       0  5023.9     0.1       0
  5050.6    0.05       0  5175.6     0.1       0  5388.2    0.05       0
Bank Sta=5019.9,5023.9
Exp/Cntr=0.3,0.1

Type RM Length L Ch R = 1,2875,283,283,283
BEGIN DESCRIPTION:
Caney Creek T 32 6.0
END DESCRIPTION:
XS GIS Cut Line= 3
      2736126.02      6771160.96      2736026.00      6771311.00
      2735776.02      6771610.97
#Sta/Elev= 30
  4819.7  351.05  4827.3  351.38  4833.3  349.83  4842.3  349.46  4848.3  347.84
  4855.8  344.96  4863.3  338.91  4869.3  338.24  4878.3  333.07  4884.3  332.13
  4899.4  328.11  4920.4  326.61  4935.4  324.38  4956.5  323.26  4962.0  322.00
  4962.2  321.50  4966.0  322.00  5091.8  322.40  5106.1  323.77  5113.9  327.10
  5120.4  327.03  5128.2  328.35  5163.4  329.00  5255.8  333.90  5270.1  335.32
  5326.1  336.91  5333.9  338.65  5340.4  338.78  5348.2  341.11  5390.5  344.24
#Mann=3,-1,0
  4819.7    0.05       0  4962.0    0.03       0  4966.0    0.05       0
Bank Sta=4962,4966
Exp/Cntr=0.3,0.1

Type RM Length L Ch R = 1,2592,236,236,236
BEGIN DESCRIPTION:
Caney Creek T 32 5.0
END DESCRIPTION:
XS GIS Cut Line= 3
      2735975.97      6771061.01      2735826.00      6771111.00
      2735526.03      6771310.98
#Sta/Elev= 30
  4841.9  344.57  4852.4  344.18  4862.9  340.53  4873.5  333.74  4882.0  322.00
  4882.3  321.50  4885.8  321.50  4886.0  322.00  5068.2  322.08  5079.6  322.09
  5085.6  322.30  5094.6  323.24  5100.6  323.41  5115.7  325.88  5121.7  325.84
  5130.7  326.89  5142.4  327.29  5157.7  327.54  5172.7  327.46  5180.3  327.25
  5187.8  327.31  5238.8  328.82  5274.9  331.18  5295.9  333.14  5301.9  333.49
  5311.0  334.66  5347.0  337.57  5353.0  337.86  5357.5  338.58  5360.5  338.58
#Mann=5,-1,0
  4841.9    0.05       0  4882.0    0.03       0  4886.0    0.05       0
  5068.2    0.12       0  5142.4    0.05       0
Bank Sta=4882,4886
Exp/Cntr=0.3,0.1

Type RM Length L Ch R = 1,2356,0,0,0
BEGIN DESCRIPTION:
Caney Creek T 32 4.0
END DESCRIPTION:
XS GIS Cut Line= 3
      2735875.97      6770911.00      2735726.00      6770911.00
      2735426.02      6771210.98
#Sta/Elev= 30
  4845.4  344.07  4847.9  344.07  4855.4  343.05  4865.4  341.14  4875.4  339.78
  4885.4  336.36  4895.4  334.18  4905.4  332.93  4915.4  328.85  4923.4  322.00
  4923.6  321.50  4927.1  321.50  4927.4  322.00  5165.1  322.00  5179.2  322.39
  5193.4  326.88  5221.6  327.51  5235.8  328.23  5249.9  328.33  5264.1  328.76
  5292.4  329.16  5306.5  329.86  5320.6  330.86  5348.9  333.90  5363.1  334.91
  5377.2  335.68  5391.3  337.01  5405.5  337.79  5416.1  339.01  5419.6  339.01
#Mann=3,-1,0
  4845.4    0.05       0  4923.4    0.03       0  4927.4    0.05       0
Bank Sta=4923.4,4927.4
Exp/Cntr=0.3,0.1

Chan Stop Cuts=-1