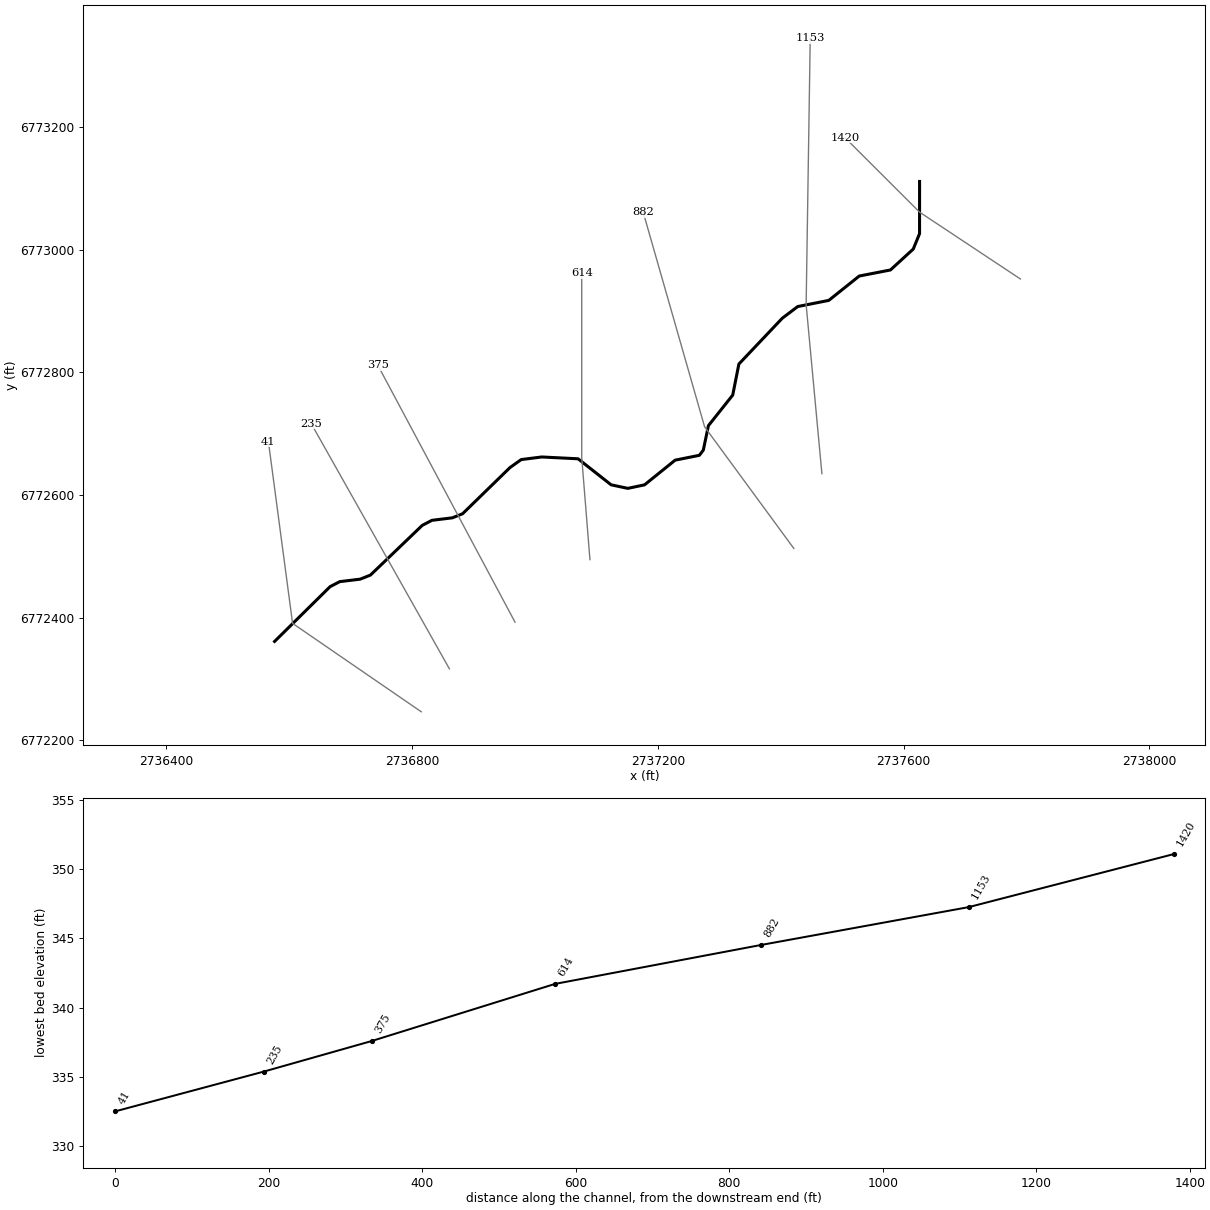
--- Caney Creek T 33.prj (project) ---

Proj Title=Caney Creek T 33 Base Level Engineering
Current Plan=p01
Default Exp/Contr=0.3,0.1
English Units
Geom File=g01
Flow File=f01
Plan File=p01
BEGIN DESCRIPTION:
Caney Creek T 33
END DESCRIPTION:

--- Caney Creek T 33.p01 (plan) ---

Plan Title=Multiple Run
Short Identifier=Multiple
Geom File=g01
Flow File=f01
Subcritical Flow
K Sum by GR= 0
Std Step Tol= 0.01
Critical Tol= 0.01
Num of Std Step Trials= 20
Max Error Tol= 0.3
Flow Tol Ratio= 0.001
Split Flow NTrial= 30
Split Flow Tol= 0.02
Split Flow Ratio= 0.02
Log Output Level= 0
Friction Slope Method= 1
Unsteady Friction Slope Method= 2
Unsteady Bridges Friction Slope Method= 1
Parabolic Critical Depth
Global Vel Dist=  1 , 1 , 1
Global Log Level= 0
CheckData=True
Encroach Param= -1, 0, 0, 0
BEGIN DESCRIPTION:
Multiple Run
END DESCRIPTION:

--- Caney Creek T 33.f01 (steady flow) ---

Flow Title=Multiple
Number of Profiles=7
Profile Names=10-year,25-year,50-year,1pct_min,100-year,1pct_plu,500-year
River Rch & RM= Caney Creek T 33,Reach-1,1420
     134     162     183     103     205     408     256
Boundary for River Rch & Prof#=Caney Creek T 33,Reach-1,1
Up Type=0
Dn Type=3
Dn Slope=0.005
Boundary for River Rch & Prof#=Caney Creek T 33,Reach-1,2
Up Type=0
Dn Type=3
Dn Slope=0.005
Boundary for River Rch & Prof#=Caney Creek T 33,Reach-1,3
Up Type=0
Dn Type=3
Dn Slope=0.005
Boundary for River Rch & Prof#=Caney Creek T 33,Reach-1,4
Up Type=0
Dn Type=3
Dn Slope=0.005
Boundary for River Rch & Prof#=Caney Creek T 33,Reach-1,5
Up Type=0
Dn Type=3
Dn Slope=0.005
Boundary for River Rch & Prof#=Caney Creek T 33,Reach-1,6
Up Type=0
Dn Type=3
Dn Slope=0.005
Boundary for River Rch & Prof#=Caney Creek T 33,Reach-1,7
Up Type=0
Dn Type=3
Dn Slope=0.005

--- Caney Creek T 33.g01 (geometry) ---

Geom Title=Existing Conditions

River Reach=Caney Creek T 33,Reach-1
Reach XY= 30
      2737626.00      6773111.00      2737625.95      6773025.89
      2737615.72      6773000.82      2737578.58      6772966.70
      2737527.76      6772956.80      2737478.19      6772917.10
      2737427.62      6772907.06      2737402.48      6772888.01
      2737331.83      6772813.31      2737321.82      6772762.71
      2737282.24      6772712.85      2737273.93      6772672.99
      2737267.54      6772664.50      2737228.10      6772656.60
      2737178.23      6772616.32      2737151.01      6772610.58
      2737123.82      6772616.38      2737070.03      6772658.81
      2737010.91      6772661.77      2736977.50      6772657.53
      2736959.26      6772644.56      2736882.04      6772569.18
      2736865.36      6772562.55      2736832.05      6772558.46
      2736816.33      6772550.20      2736732.04      6772469.17
      2736715.36      6772462.54      2736682.04      6772458.48
      2736666.30      6772450.28      2736576.00      6772361.00

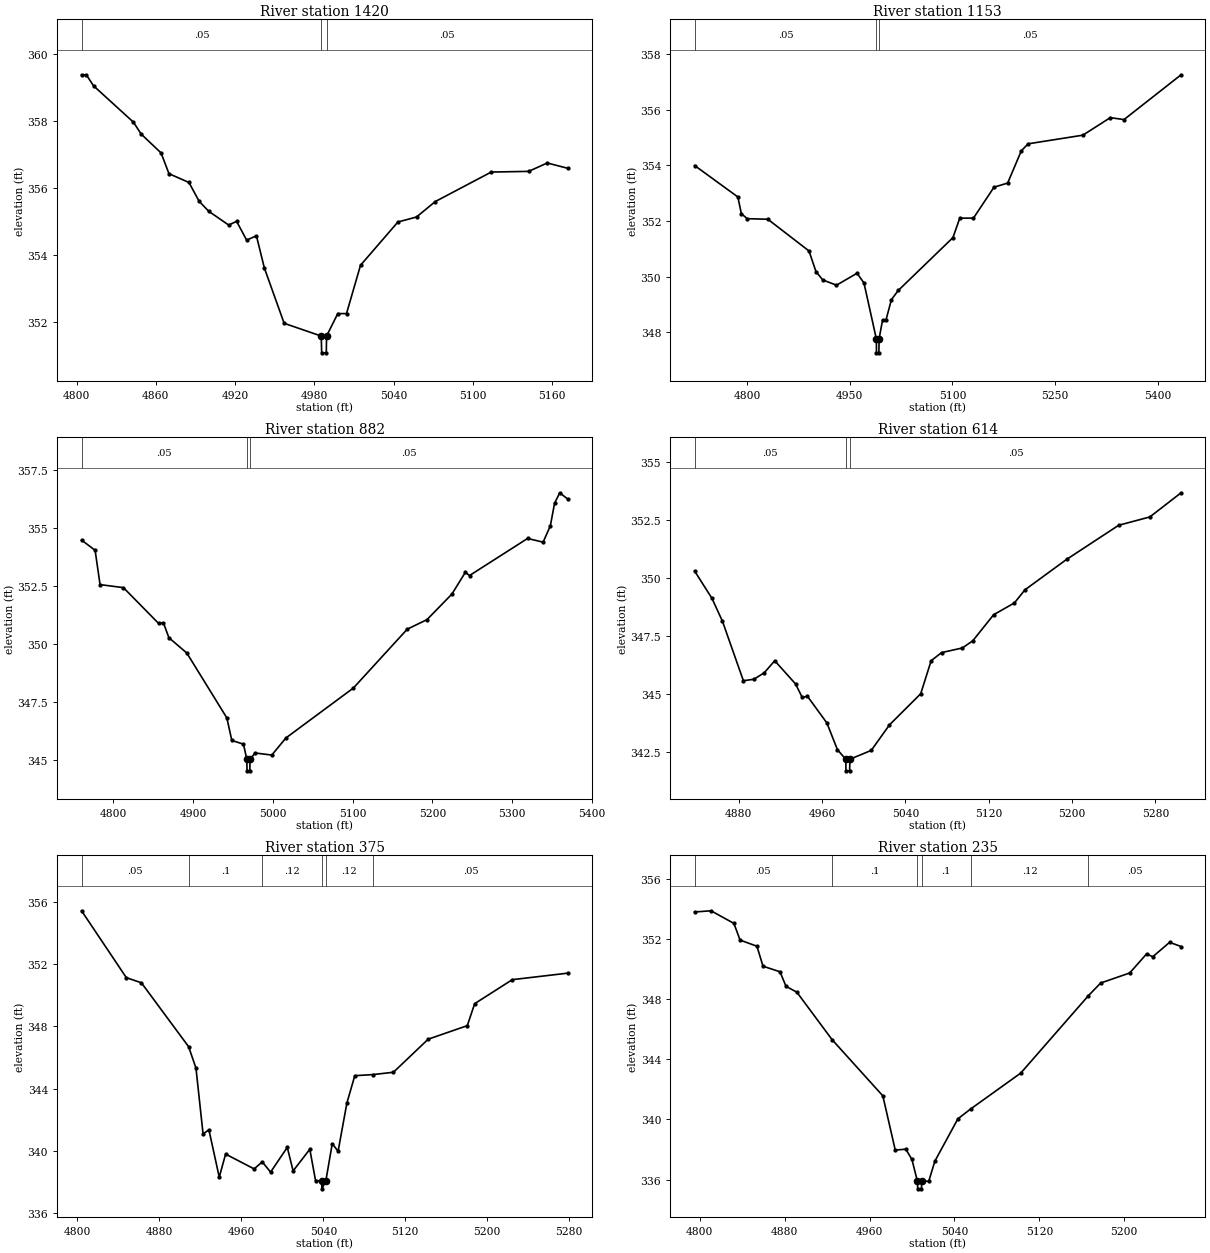
Type RM Length L Ch R = 1,1420,267,267,267
BEGIN DESCRIPTION:
Caney Creek T 33 5.0
END DESCRIPTION:
XS GIS Cut Line= 3
      2737790.14      6772951.99      2737626.00      6773061.00
      2737504.90      6773182.09
#Sta/Elev= 30
  4803.8  359.38  4807.4  359.38  4812.9  359.05  4843.0  357.97  4849.0  357.61
  4864.0  357.05  4870.0  356.43  4885.1  356.17  4892.8  355.61  4900.1  355.31
  4915.2  354.90  4921.2  355.01  4928.8  354.45  4936.2  354.58  4942.2  353.62
  4957.2  351.97  4985.3  351.59  4985.6  351.09  4989.1  351.09  4989.3  351.59
  4997.8  352.26  5004.4  352.26  5015.0  353.70  5043.3  354.99  5057.4  355.14
  5071.6  355.60  5114.0  356.48  5142.3  356.50  5156.4  356.75  5172.1  356.59
#Mann=3,-1,0
  4803.8    0.05       0  4985.3    0.04       0  4989.3    0.05       0
Bank Sta=4985.3,4989.3
Exp/Cntr=0.3,0.1

Type RM Length L Ch R = 1,1153,271,271,271
BEGIN DESCRIPTION:
Caney Creek T 33 4.0
END DESCRIPTION:
XS GIS Cut Line= 3
      2737466.99      6772634.48      2737441.33      6772910.19
      2737447.98      6773344.53
#Sta/Elev= 30
  4723.1  353.99  4786.3  352.86  4791.4  352.26  4800.0  352.08  4830.1  352.06
  4890.3  350.92  4900.5  350.18  4910.4  349.88  4930.5  349.69  4960.6  350.12
  4970.7  349.77  4988.8  347.76  4989.0  347.26  4992.5  347.26  4992.8  347.76
  4997.9  348.44  5002.9  348.44  5010.8  349.17  5020.8  349.50  5100.8  351.40
  5110.8  352.10  5130.8  352.10  5160.8  353.21  5180.8  353.36  5200.8  354.52
  5210.8  354.77  5290.8  355.08  5330.9  355.71  5350.9  355.64  5434.4  357.25
#Mann=3,-1,0
  4723.1    0.05       0  4988.8    0.04       0  4992.8    0.05       0
Bank Sta=4988.8,4992.8
Exp/Cntr=0.3,0.1

Type RM Length L Ch R = 1,882,268,268,268
BEGIN DESCRIPTION:
Caney Creek T 33 3.0
END DESCRIPTION:
XS GIS Cut Line= 3
      2737421.27      6772512.64      2737276.00      6772711.00
      2737175.99      6773061.03
#Sta/Elev= 30
  4760.0  354.47  4777.0  354.03  4783.2  352.55  4812.5  352.42  4856.5  350.88
  4862.7  350.90  4869.5  350.26  4892.0  349.60  4942.2  346.80  4948.4  345.83
  4963.0  345.67  4967.2  345.02  4967.5  344.52  4971.0  344.52  4971.2  345.02
  4977.7  345.29  4998.5  345.20  5016.3  345.94  5100.8  348.09  5168.4  350.63
  5193.1  351.04  5224.3  352.14  5241.2  353.08  5246.4  352.94  5319.2  354.54
  5338.7  354.38  5347.8  355.09  5353.0  356.05  5359.5  356.51  5369.9  356.23
#Mann=3,-1,0
  4760.0    0.05       0  4967.2    0.03       0  4971.2    0.05       0
Bank Sta=4967.2,4971.2
Exp/Cntr=0.3,0.1

Type RM Length L Ch R = 1,614,239,239,239
BEGIN DESCRIPTION:
Caney Creek T 33 2.0
END DESCRIPTION:
XS GIS Cut Line= 3
      2737089.38      6772494.39      2737076.00      6772661.00
      2737076.00      6772960.95
#Sta/Elev= 30
  4837.6  350.31  4854.3  349.13  4864.3  348.15  4884.4  345.59  4894.4  345.65
  4904.4  345.93  4914.5  346.45  4934.5  345.45  4940.9  344.87  4945.9  344.92
  4964.6  343.77  4974.7  342.62  4982.7  342.21  4982.9  341.71  4986.4  341.71
  4986.7  342.21  5007.2  342.59  5024.7  343.69  5054.7  345.03  5064.7  346.45
  5074.7  346.80  5094.7  347.00  5104.7  347.31  5124.7  348.43  5144.7  348.94
  5154.7  349.50  5194.7  350.81  5244.7  352.28  5274.7  352.64  5304.7  353.68
#Mann=3,-1,0
  4837.6    0.05       0  4982.7    0.03       0  4986.7    0.05       0
Bank Sta=4982.7,4986.7
Exp/Cntr=0.3,0.1

Type RM Length L Ch R = 1,375,140,140,140
BEGIN DESCRIPTION:
Mapping XS 1600da37
END DESCRIPTION:
XS GIS Cut Line= 2
      2736967.39      6772392.43      2736744.03      6772811.41
#Sta/Elev= 30
  4804.0  355.42  4847.7  351.13  4862.4  350.80  4908.5  346.70  4915.7  345.32
  4922.6  341.10  4928.3  341.37  4938.4  338.33  4944.6  339.81  4972.4  338.86
  4980.4  339.31  4988.5  338.65  5004.8  340.24  5010.5  338.73  5026.8  340.12
  5032.4  338.11  5038.4  338.08  5038.6  337.58  5042.4  338.08  5048.7  340.48
  5054.4  339.99  5063.0  343.09  5070.7  344.84  5088.4  344.91  5108.4  345.06
  5142.3  347.18  5180.5  348.05  5187.7  349.46  5224.4  351.00  5278.8  351.42
#Mann=6,-1,0
  4804.0    0.05       0  4908.5     0.1       0  4980.4    0.12       0
  5038.4    0.07       0  5042.4    0.12       0  5088.4    0.05       0
Bank Sta=5038.4,5042.4
Exp/Cntr=0.3,0.1

Type RM Length L Ch R = 1,235,194,194,194
BEGIN DESCRIPTION:
Mapping XS f5317a35
END DESCRIPTION:
XS GIS Cut Line= 2
      2736860.61      6772316.31      2736635.89      6772715.74
#Sta/Elev= 30
  4795.2  353.81  4810.6  353.89  4832.2  353.05  4838.0  351.94  4853.9  351.53
  4859.6  350.20  4875.6  349.83  4881.3  348.86  4891.5  348.47  4924.7  345.31
  4972.5  341.57  4984.2  337.96  4994.1  338.02  4999.9  337.34  5005.1  335.88
  5005.4  335.38  5008.9  335.38  5009.1  335.88  5015.8  335.89  5021.5  337.22
  5043.2  340.04  5055.3  340.70  5102.5  343.09  5166.2  348.24  5177.7  349.08
  5205.1  349.75  5221.0  351.02  5226.8  350.83  5242.7  351.79  5253.5  351.51
#Mann=6,-1,0
  4795.2    0.05       0  4924.7     0.1       0  5005.1    0.07       0
  5009.1     0.1       0  5055.3    0.12       0  5166.2    0.05       0
Bank Sta=5005.1,5009.1
Exp/Cntr=0.3,0.1

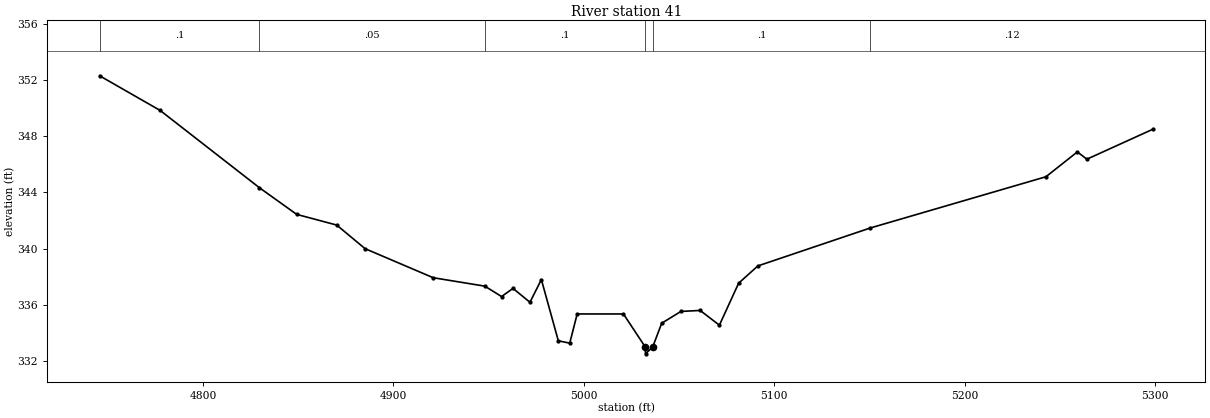
Type RM Length L Ch R = 1,41,0,0,0
BEGIN DESCRIPTION:
Caney Creek T 33 1.0
END DESCRIPTION:
XS GIS Cut Line= 3
      2736814.78      6772246.29      2736605.27      6772390.42
      2736565.96      6772686.63
#Sta/Elev= 30
  4745.7  352.30  4777.5  349.83  4829.6  344.33  4849.2  342.43  4870.2  341.67
  4885.1  339.99  4920.9  337.92  4948.0  337.32  4956.8  336.58  4962.8  337.16
  4971.7  336.17  4977.7  337.79  4986.6  333.43  4992.6  333.26  4996.5  335.34
  5020.8  335.34  5032.2  333.00  5032.4  332.50  5036.2  333.00  5040.9  334.68
  5051.0  335.52  5061.1  335.59  5071.2  334.54  5081.3  337.53  5091.4  338.76
  5150.4  341.46  5242.7  345.11  5259.2  346.88  5264.2  346.36  5298.8  348.49
#Mann=6,-1,0
  4745.7     0.1       0  4829.6    0.05       0  4948.0     0.1       0
  5032.2    0.07       0  5036.2     0.1       0  5150.4    0.12       0
Bank Sta=5032.2,5036.2
Exp/Cntr=0.3,0.1

Chan Stop Cuts=-1