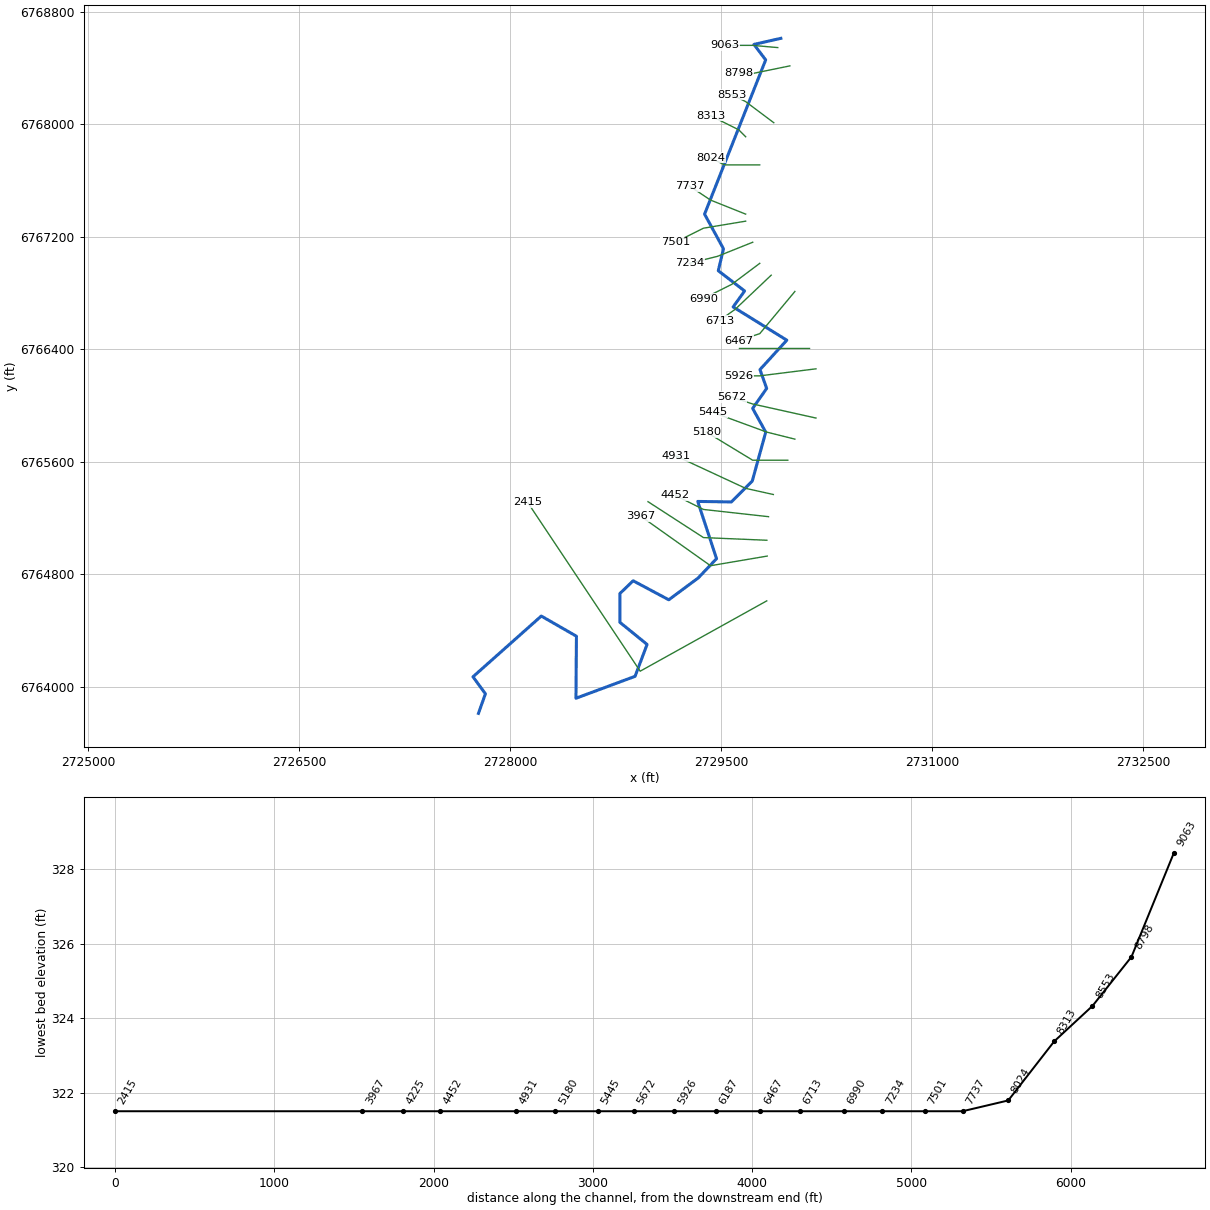
--- Caney Creek T 34.prj (project) ---

Proj Title=Caney Creek T 34 Base Level Engineering
Current Plan=p01
Default Exp/Contr=0.3,0.1
English Units
Geom File=g01
Flow File=f01
Plan File=p01
BEGIN DESCRIPTION:
Caney Creek T 34
END DESCRIPTION:

--- Caney Creek T 34.p01 (plan) ---

Plan Title=Multiple Run
Short Identifier=Multiple
Geom File=g01
Flow File=f01
Subcritical Flow
K Sum by GR= 0
Std Step Tol= 0.01
Critical Tol= 0.01
Num of Std Step Trials= 20
Max Error Tol= 0.3
Flow Tol Ratio= 0.001
Split Flow NTrial= 30
Split Flow Tol= 0.02
Split Flow Ratio= 0.02
Log Output Level= 0
Friction Slope Method= 1
Unsteady Friction Slope Method= 2
Unsteady Bridges Friction Slope Method= 1
Parabolic Critical Depth
Global Vel Dist=  1 , 1 , 1
Global Log Level= 0
CheckData=True
Encroach Param= -1, 0, 0, 0
BEGIN DESCRIPTION:
Multiple Run
END DESCRIPTION:

--- Caney Creek T 34.f01 (steady flow) ---

Flow Title=Multiple
Number of Profiles=7
Profile Names=10-year,25-year,50-year,1pct_min,100-year,1pct_plu,500-year
River Rch & RM= Caney Creek T 34,Reach-1,9063
     277     351     407     235     468     935     619
River Rch & RM= Caney Creek T 34,Reach-1,6187
     278     349     403     231     460     918     600
Boundary for River Rch & Prof#=Caney Creek T 34,Reach-1,1
Up Type=0
Dn Type=3
Dn Slope=0.005
Boundary for River Rch & Prof#=Caney Creek T 34,Reach-1,2
Up Type=0
Dn Type=3
Dn Slope=0.005
Boundary for River Rch & Prof#=Caney Creek T 34,Reach-1,3
Up Type=0
Dn Type=3
Dn Slope=0.005
Boundary for River Rch & Prof#=Caney Creek T 34,Reach-1,4
Up Type=0
Dn Type=3
Dn Slope=0.005
Boundary for River Rch & Prof#=Caney Creek T 34,Reach-1,5
Up Type=0
Dn Type=3
Dn Slope=0.005
Boundary for River Rch & Prof#=Caney Creek T 34,Reach-1,6
Up Type=0
Dn Type=3
Dn Slope=0.005
Boundary for River Rch & Prof#=Caney Creek T 34,Reach-1,7
Up Type=0
Dn Type=3
Dn Slope=0.005

--- Caney Creek T 34.g01 (geometry) ---

Geom Title=Existing Conditions

River Reach=Caney Creek T 34,Reach-1
Reach XY= 30
      2729926.00      6768611.00      2729734.96      6768567.69
      2729818.36      6768457.67      2729383.78      6767360.90
      2729518.20      6767114.42      2729481.39      6766958.56
      2729668.50      6766814.58      2729586.96      6766701.00
      2729968.53      6766464.62      2729777.74      6766255.37
      2729825.39      6766121.63      2729725.74      6765979.45
      2729818.69      6765810.91      2729722.84      6765462.65
      2729574.50      6765314.46      2729335.18      6765318.05
      2729468.92      6764911.00      2729339.21      6764774.63
      2729129.33      6764618.61      2728875.99      6764753.91
      2728781.81      6764663.32      2728781.70      6764458.46
      2728974.91      6764301.37      2728889.56      6764074.48
      2728469.29      6763918.46      2728472.63      6764359.72
      2728222.69      6764502.98      2727736.95      6764071.02
      2727825.42      6763950.39      2727776.00      6763811.00

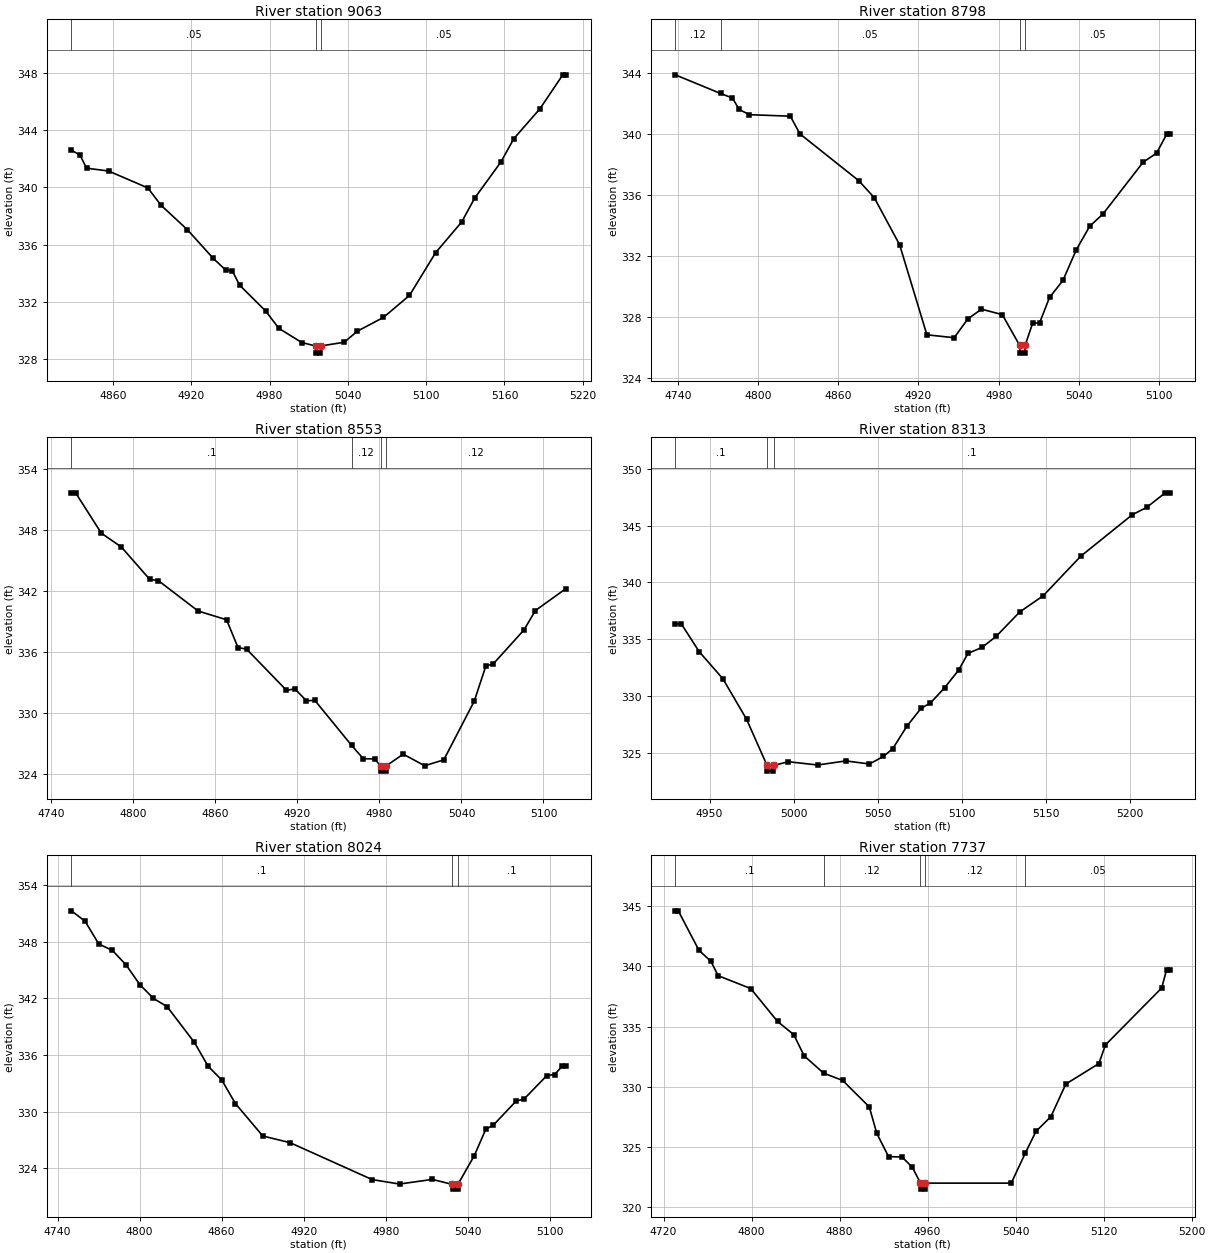
Type RM Length L Ch R = 1,9063,265,265,265
BEGIN DESCRIPTION:
Caney Creek T 34 21.0
END DESCRIPTION:
XS GIS Cut Line= 3
      2729904.42      6768545.14      2729726.00      6768561.00
      2729526.02      6768561.00
#Sta/Elev= 30
  4828.1  342.61  4834.7  342.26  4839.7  341.35  4856.6  341.15  4886.7  339.97
  4896.8  338.76  4916.9  337.06  4936.9  335.04  4946.4  334.23  4951.4  334.18
  4957.0  333.18  4977.1  331.36  4987.1  330.16  5004.7  329.17  5015.2  328.93
  5015.5  328.43  5019.0  328.43  5019.2  328.93  5037.2  329.19  5047.2  329.96
  5067.2  330.92  5087.2  332.46  5107.2  335.44  5127.2  337.59  5137.2  339.26
  5157.2  341.77  5167.2  343.41  5187.2  345.50  5204.7  347.87  5207.2  347.87
#Mann=3,-1,0
  4828.1    0.05       0  5015.2    0.03       0  5019.2    0.05       0
Bank Sta=5015.2,5019.2
Exp/Cntr=0.3,0.1

Type RM Length L Ch R = 1,8798,245,245,245
BEGIN DESCRIPTION:
Caney Creek T 34 20.0
END DESCRIPTION:
XS GIS Cut Line= 3
      2729990.27      6768415.11      2729726.00      6768361.00
      2729625.95      6768361.00
#Sta/Elev= 30
  4738.2  343.88  4772.0  342.66  4780.9  342.36  4786.0  341.61  4793.6  341.27
  4824.2  341.17  4831.4  340.01  4875.3  336.95  4886.9  335.84  4905.9  332.75
  4926.3  326.85  4946.7  326.66  4956.9  327.89  4967.1  328.53  4982.7  328.17
  4995.7  326.15  4996.0  325.65  4999.5  325.65  4999.7  326.15  5005.4  327.62
  5010.5  327.62  5018.0  329.30  5028.0  330.41  5038.0  332.42  5048.0  333.96
  5058.0  334.77  5088.0  338.16  5098.0  338.75  5105.5  339.98  5108.0  339.98
#Mann=4,-1,0
  4738.2    0.12       0  4772.0    0.05       0  4995.7    0.05       0
  4999.7    0.05       0
Bank Sta=4995.7,4999.7
Exp/Cntr=0.3,0.1

Type RM Length L Ch R = 1,8553,240,240,240
BEGIN DESCRIPTION:
Caney Creek T 34 19.0
END DESCRIPTION:
XS GIS Cut Line= 3
      2729876.00      6768011.00      2729676.00      6768161.00
      2729576.00      6768211.00
#Sta/Elev= 30
  4754.7  351.69  4757.8  351.69  4776.6  347.72  4791.2  346.37  4812.0  343.18
  4818.2  343.07  4847.4  340.07  4868.2  339.21  4876.6  336.47  4882.8  336.33
  4912.0  332.28  4918.2  332.41  4926.6  331.25  4932.8  331.28  4959.6  326.87
  4968.2  325.55  4976.6  325.53  4980.8  324.83  4981.1  324.33  4984.6  324.33
  4984.8  324.83  4997.4  326.00  5013.1  324.86  5027.1  325.44  5049.4  331.22
  5057.8  334.65  5063.4  334.89  5085.8  338.22  5094.1  340.12  5116.5  342.28
#Mann=4,-1,0
  4754.7     0.1       0  4959.6    0.12       0  4980.8    0.07       0
  4984.8    0.12       0
Bank Sta=4980.8,4984.8
Exp/Cntr=0.3,0.1

Type RM Length L Ch R = 1,8313,289,289,289
BEGIN DESCRIPTION:
Caney Creek T 34 18.0
END DESCRIPTION:
XS GIS Cut Line= 3
      2729676.01      6767910.99      2729626.00      6767961.00
      2729426.03      6768060.98
#Sta/Elev= 30
  4929.6  336.35  4933.2  336.35  4943.8  333.91  4957.9  331.52  4972.0  327.95
  4984.2  323.88  4984.4  323.38  4987.9  323.38  4988.2  323.88  4996.8  324.21
  5014.3  323.92  5031.1  324.28  5045.1  324.01  5053.4  324.67  5059.0  325.36
  5067.4  327.34  5075.8  328.91  5081.4  329.38  5089.8  330.72  5098.2  332.28
  5103.7  333.75  5112.1  334.28  5120.5  335.25  5134.5  337.40  5148.5  338.83
  5170.8  342.31  5201.6  345.98  5210.0  346.61  5221.1  347.90  5223.9  347.90
#Mann=3,-1,0
  4929.6     0.1       0  4984.2    0.07       0  4988.2     0.1       0
Bank Sta=4984.2,4988.2
Exp/Cntr=0.3,0.1

Type RM Length L Ch R = 1,8024,287,287,287
BEGIN DESCRIPTION:
Caney Creek T 34 17.0
END DESCRIPTION:
XS GIS Cut Line= 3
      2729775.98      6767711.00      2729526.00      6767711.00
      2729425.98      6767761.01
#Sta/Elev= 30
  4750.1  351.28  4760.1  350.18  4770.1  347.77  4780.1  347.08  4790.1  345.55
  4800.1  343.47  4810.1  342.00  4820.1  341.13  4840.1  337.33  4850.1  334.81
  4860.1  333.35  4870.1  330.85  4890.1  327.42  4910.1  326.71  4970.1  322.80
  4990.1  322.33  5014.1  322.82  5028.8  322.29  5029.1  321.79  5032.6  321.79
  5032.8  322.29  5044.8  325.34  5053.2  328.13  5058.8  328.58  5075.5  331.14
  5081.1  331.32  5097.9  333.83  5103.5  333.93  5109.1  334.82  5111.9  334.82
#Mann=3,-1,0
  4750.1     0.1       0  5028.8    0.07       0  5032.8     0.1       0
Bank Sta=5028.8,5032.8
Exp/Cntr=0.3,0.1

Type RM Length L Ch R = 1,7737,236,236,236
BEGIN DESCRIPTION:
Caney Creek T 34 16.0
END DESCRIPTION:
XS GIS Cut Line= 3
      2729675.98      6767361.01      2729426.00      6767461.00
      2729276.01      6767560.99
#Sta/Elev= 30
  4730.7  344.62  4733.4  344.62  4752.2  341.34  4763.0  340.43  4769.7  339.23
  4799.3  338.16  4823.6  335.43  4838.4  334.33  4847.8  332.57  4865.6  331.13
  4882.8  330.53  4907.0  328.33  4913.8  326.13  4924.5  324.20  4936.7  324.17
  4946.1  323.32  4953.5  322.00  4953.8  321.50  4957.3  321.50  4957.5  322.00
  5036.0  322.00  5048.8  324.50  5058.5  326.30  5072.0  327.52  5085.6  330.23
  5115.6  331.93  5121.6  333.48  5172.7  338.21  5177.2  339.74  5180.2  339.74
#Mann=5,-1,0
  4730.7     0.1       0  4865.6    0.12       0  4953.5    0.07       0
  4957.5    0.12       0  5048.8    0.05       0
Bank Sta=4953.5,4957.5
Exp/Cntr=0.3,0.1

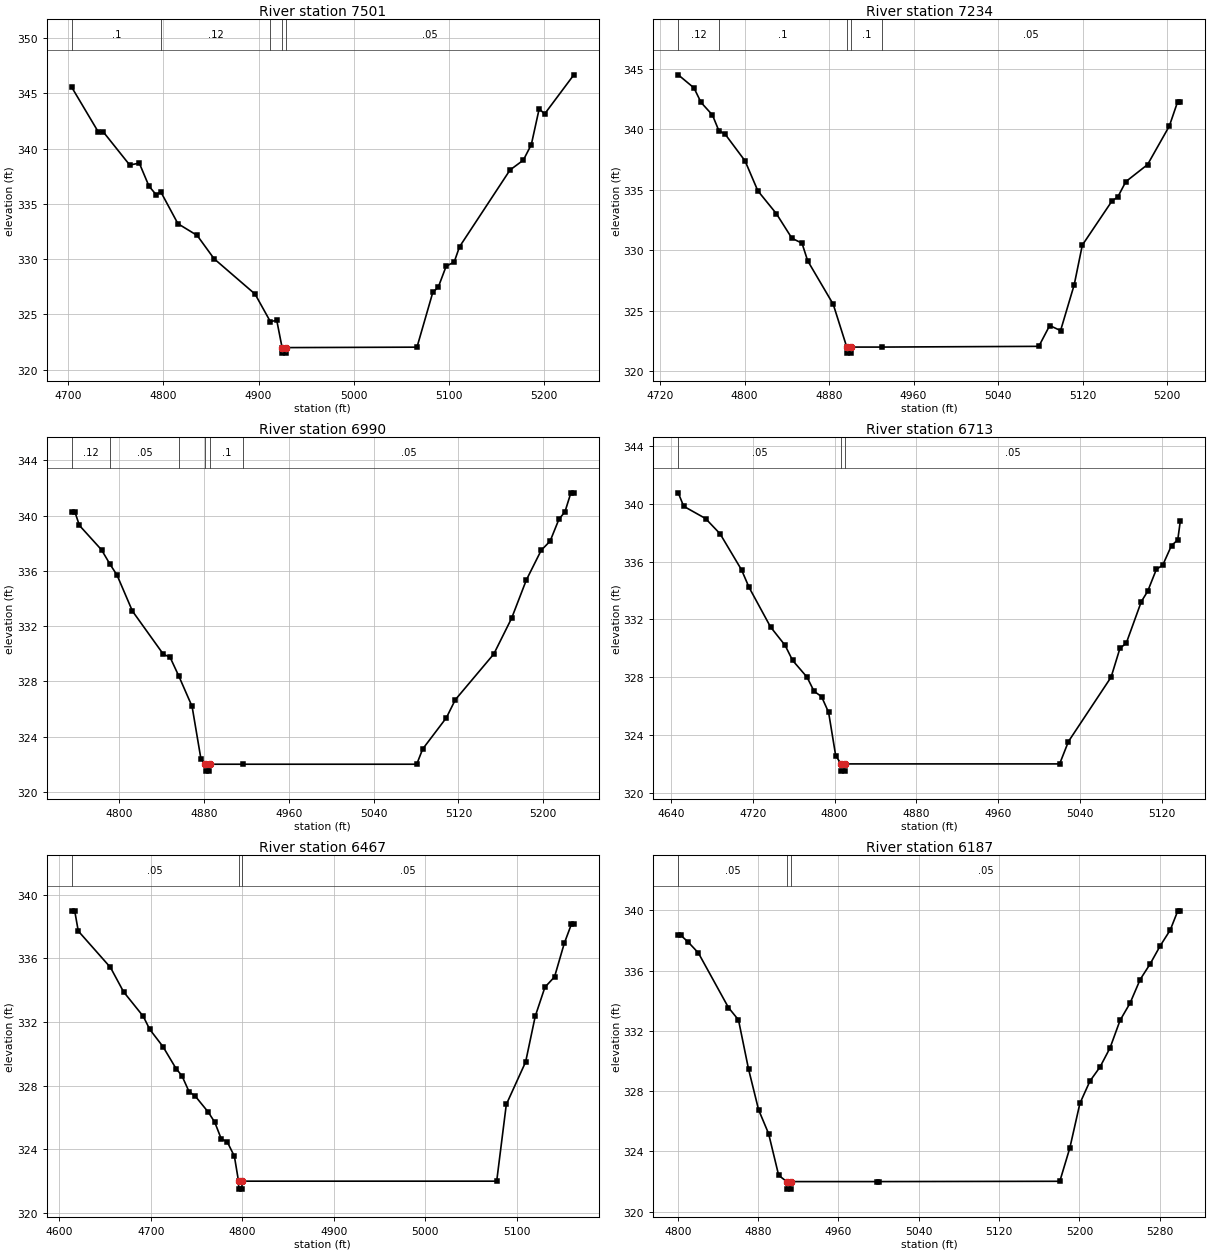
Type RM Length L Ch R = 1,7501,267,267,267
BEGIN DESCRIPTION:
Caney Creek T 34 15.0
END DESCRIPTION:
XS GIS Cut Line= 3
      2729676.04      6767311.01      2729376.00      6767261.00
      2729175.98      6767160.99
#Sta/Elev= 30
  4703.7  345.55  4731.6  341.51  4736.7  341.53  4764.6  338.52  4774.7  338.69
  4784.8  336.62  4792.4  335.83  4797.3  336.09  4815.3  333.21  4835.5  332.15
  4853.3  330.04  4896.4  326.84  4912.4  324.36  4919.2  324.46  4924.8  322.00
  4925.0  321.50  4928.5  321.50  4928.8  322.00  5066.6  322.04  5083.3  327.02
  5088.9  327.45  5097.3  329.37  5105.7  329.74  5111.3  331.12  5164.4  338.07
  5178.4  338.96  5186.8  340.37  5195.1  343.62  5200.7  343.13  5231.5  346.68
#Mann=5,-1,0
  4703.7     0.1       0  4797.3    0.12       0  4912.4    0.05       0
  4924.8    0.05       0  4928.8    0.05       0
Bank Sta=4924.8,4928.8
Exp/Cntr=0.3,0.1

Type RM Length L Ch R = 1,7234,244,244,244
BEGIN DESCRIPTION:
Caney Creek T 34 14.0
END DESCRIPTION:
XS GIS Cut Line= 3
      2729726.04      6767161.02      2729476.00      6767061.00
      2729275.96      6767010.99
#Sta/Elev= 30
  4737.1  344.48  4752.0  343.40  4758.7  342.20  4769.5  341.16  4775.5  339.88
  4781.6  339.57  4800.4  337.37  4812.5  334.90  4830.0  333.02  4844.8  330.98
  4854.3  330.58  4859.7  329.12  4883.9  325.53  4896.7  322.00  4896.9  321.50
  4900.4  321.50  4900.7  322.00  4929.9  322.00  5078.6  322.06  5088.9  323.78
  5099.2  323.36  5112.1  327.14  5119.8  330.42  5148.1  334.09  5153.3  334.38
  5161.0  335.66  5181.6  337.07  5202.2  340.25  5210.0  342.24  5212.6  342.24
#Mann=5,-1,0
  4737.1    0.12       0  4775.5     0.1       0  4896.7    0.05       0
  4900.7     0.1       0  4929.9    0.05       0
Bank Sta=4896.7,4900.7
Exp/Cntr=0.3,0.1

Type RM Length L Ch R = 1,6990,277,277,277
BEGIN DESCRIPTION:
Caney Creek T 34 13.0
END DESCRIPTION:
XS GIS Cut Line= 3
      2729775.97      6767010.97      2729576.00      6766861.00
      2729375.97      6766760.98
#Sta/Elev= 30
  4755.3  340.23  4758.4  340.23  4762.5  339.29  4783.4  337.52  4791.2  336.50
  4798.0  335.69  4812.5  333.09  4841.7  329.96  4848.0  329.75  4856.4  328.36
  4868.8  326.18  4877.1  322.40  4881.4  322.00  4881.6  321.50  4885.1  321.50
  4885.4  322.00  4917.2  322.00  5080.7  322.00  5086.3  323.10  5108.7  325.37
  5117.1  326.67  5153.4  329.98  5170.2  332.57  5184.1  335.34  5198.1  337.49
  5206.5  338.15  5214.9  339.75  5220.5  340.27  5226.1  341.65  5228.9  341.65
#Mann=6,-1,0
  4755.3    0.12       0  4791.2    0.05       0  4856.4     0.1       0
  4881.4    0.05       0  4885.4     0.1       0  4917.2    0.05       0
Bank Sta=4881.4,4885.4
Exp/Cntr=0.3,0.1

Type RM Length L Ch R = 1,6713,246,246,246
BEGIN DESCRIPTION:
Caney Creek T 34 12.0
END DESCRIPTION:
XS GIS Cut Line= 3
      2729857.65      6766926.97      2729601.67      6766684.33
      2729489.64      6766604.09
#Sta/Elev= 30
  4647.3  340.77  4652.6  339.84  4674.0  338.99  4688.2  337.93  4709.2  335.43
  4716.5  334.22  4737.5  331.48  4751.7  330.21  4759.0  329.17  4773.1  328.01
  4780.0  327.03  4787.3  326.66  4794.2  325.57  4801.1  322.58  4806.3  322.00
  4806.6  321.50  4810.1  321.50  4810.3  322.00  5019.9  322.00  5028.5  323.55
  5070.2  328.01  5078.8  330.00  5085.0  330.36  5099.7  333.24  5105.9  333.95
  5114.4  335.47  5120.6  335.76  5129.2  337.12  5135.3  337.51  5137.8  338.82
#Mann=3,-1,0
  4647.3    0.05       0  4806.3    0.05       0  4810.3    0.05       0
Bank Sta=4806.3,4810.3
Exp/Cntr=0.3,0.1

Type RM Length L Ch R = 1,6467,280,280,280
BEGIN DESCRIPTION:
Caney Creek T 34 11.0
END DESCRIPTION:
XS GIS Cut Line= 3
      2730025.99      6766810.99      2729776.00      6766511.00
      2729626.01      6766461.00
#Sta/Elev= 30
  4613.6  338.99  4616.8  338.99  4620.7  337.72  4655.9  335.43  4670.2  333.90
  4691.7  332.36  4698.8  331.54  4713.2  330.46  4727.5  329.08  4734.0  328.62
  4741.8  327.62  4748.3  327.36  4762.6  326.35  4769.8  325.71  4776.9  324.66
  4783.5  324.47  4791.3  323.56  4795.8  322.00  4796.0  321.50  4799.5  321.50
  4799.8  322.00  5077.9  322.00  5088.4  326.82  5109.5  329.49  5120.0  332.36
  5130.6  334.19  5141.1  334.84  5151.7  336.94  5159.6  338.16  5162.2  338.16
#Mann=3,-1,0
  4613.6    0.05       0  4795.8    0.05       0  4799.8    0.05       0
Bank Sta=4795.8,4799.8
Exp/Cntr=0.3,0.1

Type RM Length L Ch R = 1,6187,261,261,261
BEGIN DESCRIPTION:
Caney Creek T 34 10.0
END DESCRIPTION:
XS GIS Cut Line= 3
      2730126.04      6766411.00      2729926.00      6766411.00
      2729626.04      6766411.00
#Sta/Elev= 30
  4800.5  338.35  4803.0  338.35  4810.5  337.89  4820.5  337.18  4850.5  333.55
  4860.5  332.73  4870.5  329.47  4880.5  326.77  4890.5  325.18  4900.5  322.42
  4908.5  322.00  4908.8  321.50  4912.3  321.50  4912.5  322.00  4998.0  322.00
  5000.5  322.00  5180.5  322.02  5190.5  324.24  5200.5  327.19  5210.5  328.67
  5220.5  329.60  5230.5  330.87  5240.5  332.70  5250.5  333.85  5260.5  335.41
  5270.5  336.45  5280.5  337.65  5290.5  338.70  5298.0  339.97  5300.5  339.97
#Mann=3,-1,0
  4800.5    0.05       0  4908.5    0.05       0  4912.5    0.05       0
Bank Sta=4908.5,4912.5
Exp/Cntr=0.3,0.1

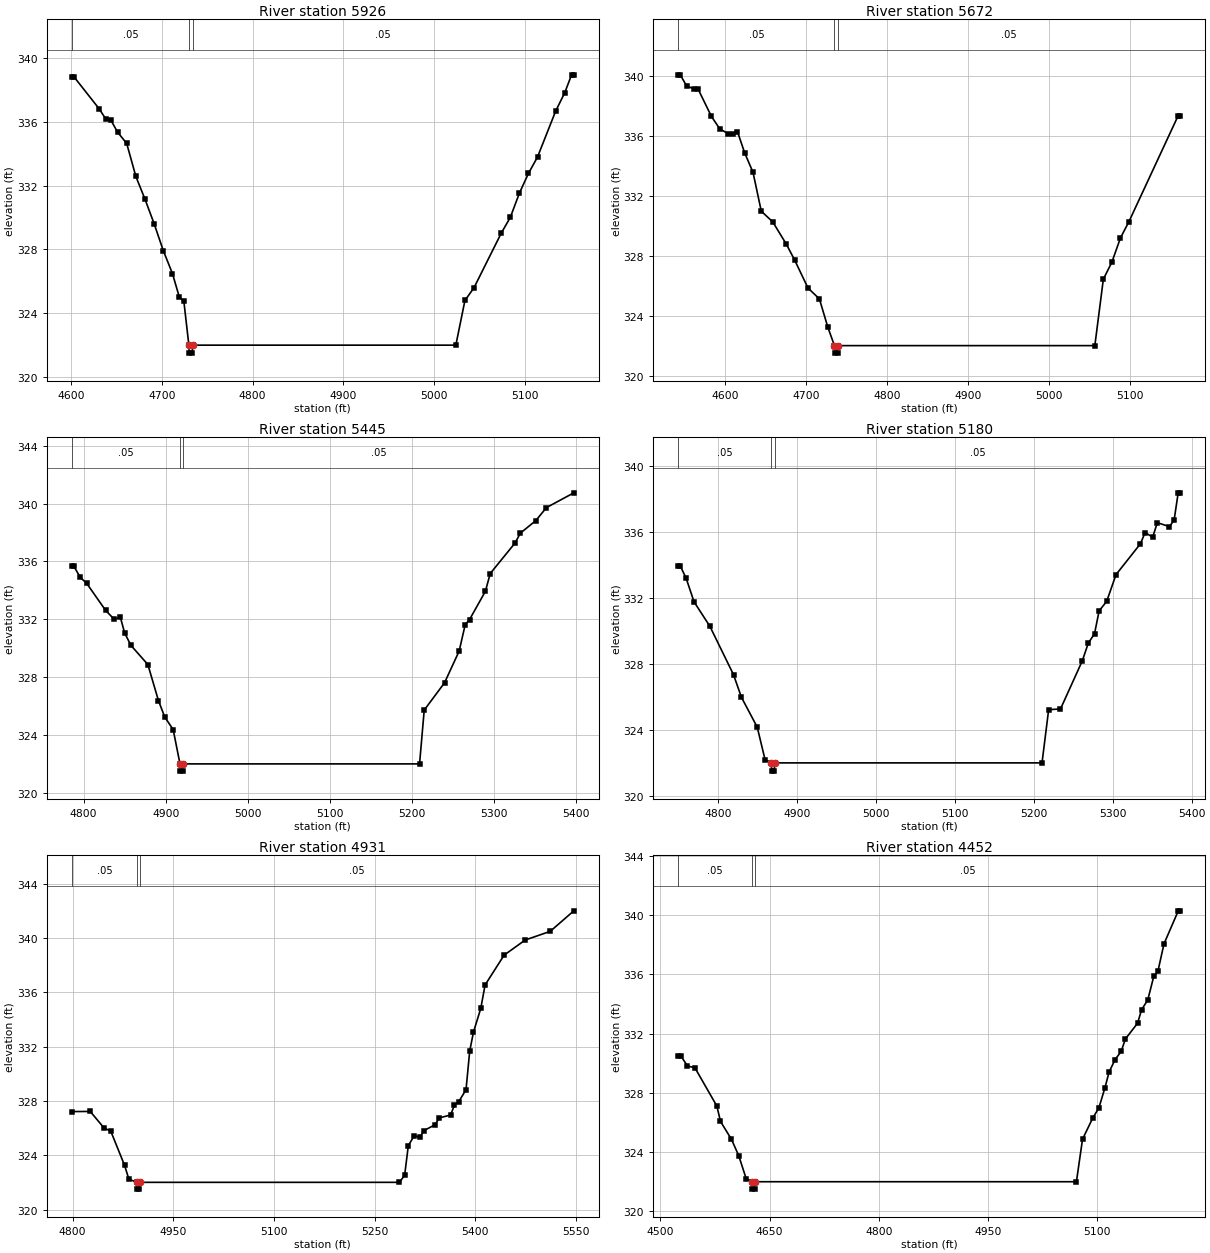
Type RM Length L Ch R = 1,5926,254,254,254
BEGIN DESCRIPTION:
Caney Creek T 34 9.0
END DESCRIPTION:
XS GIS Cut Line= 3
      2730176.03      6766261.00      2729776.00      6766211.00
      2729626.04      6766211.00
#Sta/Elev= 30
  4600.9  338.82  4603.4  338.82  4631.2  336.81  4638.7  336.15  4643.8  336.13
  4651.3  335.36  4661.4  334.65  4671.5  332.58  4681.5  331.16  4691.6  329.62
  4701.7  327.93  4711.8  326.49  4719.3  325.03  4724.4  324.74  4729.9  322.00
  4730.2  321.50  4733.7  321.50  4733.9  322.00  5024.0  322.00  5034.0  324.80
  5044.0  325.60  5074.0  329.02  5084.0  330.01  5094.0  331.53  5104.0  332.77
  5114.0  333.80  5134.0  336.68  5144.0  337.83  5151.5  338.95  5154.0  338.95
#Mann=3,-1,0
  4600.9    0.05       0  4729.9    0.05       0  4733.9    0.05       0
Bank Sta=4729.9,4733.9
Exp/Cntr=0.3,0.1

Type RM Length L Ch R = 1,5672,227,227,227
BEGIN DESCRIPTION:
Caney Creek T 34 8.0
END DESCRIPTION:
XS GIS Cut Line= 3
      2730175.97      6765911.01      2729726.00      6766011.00
      2729575.96      6766061.01
#Sta/Elev= 30
  4542.7  340.05  4545.2  340.05  4552.9  339.32  4561.9  339.11  4567.0  339.12
  4583.6  337.28  4593.9  336.45  4604.1  336.13  4610.5  336.10  4615.7  336.27
  4624.6  334.85  4634.9  333.55  4645.1  330.96  4659.2  330.25  4675.8  328.78
  4686.1  327.72  4702.7  325.84  4716.8  325.11  4727.1  323.24  4735.3  322.00
  4735.6  321.50  4739.1  321.50  4739.3  322.00  5056.4  322.00  5066.9  326.43
  5077.4  327.56  5088.0  329.18  5098.5  330.27  5159.1  337.32  5161.8  337.32
#Mann=3,-1,0
  4542.7    0.05       0  4735.3    0.05       0  4739.3    0.05       0
Bank Sta=4735.3,4739.3
Exp/Cntr=0.3,0.1

Type RM Length L Ch R = 1,5445,265,265,265
BEGIN DESCRIPTION:
Caney Creek T 34 7.0
END DESCRIPTION:
XS GIS Cut Line= 3
      2730026.04      6765760.99      2729826.00      6765811.00
      2729444.67      6765950.97
#Sta/Elev= 30
  4785.5  335.66  4788.1  335.66  4795.9  334.89  4803.6  334.49  4826.8  332.61
  4837.1  332.01  4844.8  332.13  4850.0  331.05  4857.7  330.19  4878.3  328.87
  4891.2  326.38  4898.9  325.24  4909.2  324.37  4917.5  322.00  4917.8  321.50
  4921.3  321.50  4921.5  322.00  5209.7  322.00  5215.4  325.72  5240.2  327.61
  5258.0  329.80  5265.4  331.63  5270.7  331.98  5290.0  333.93  5295.9  335.16
  5326.3  337.28  5332.6  337.95  5351.5  338.82  5364.5  339.72  5397.9  340.74
#Mann=3,-1,0
  4785.5    0.05       0  4917.5    0.03       0  4921.5    0.05       0
Bank Sta=4917.5,4921.5
Exp/Cntr=0.3,0.1

Type RM Length L Ch R = 1,5180,249,249,249
BEGIN DESCRIPTION:
Caney Creek T 34 6.0
END DESCRIPTION:
XS GIS Cut Line= 3
      2729976.00      6765611.00      2729726.00      6765611.00
      2729396.39      6765811.31
#Sta/Elev= 30
  4750.0  333.95  4752.5  333.95  4760.0  333.20  4770.0  331.77  4790.0  330.29
  4820.0  327.35  4830.0  325.98  4850.0  324.17  4860.0  322.18  4868.0  322.00
  4868.2  321.50  4871.7  321.50  4872.0  322.00  5210.6  322.00  5219.0  325.23
  5234.0  325.27  5261.6  328.19  5269.1  329.25  5277.1  329.84  5282.9  331.22
  5292.5  331.80  5304.3  333.42  5335.2  335.29  5341.1  335.97  5350.7  335.69
  5356.6  336.57  5372.0  336.33  5377.9  336.74  5383.0  338.38  5385.7  338.38
#Mann=3,-1,0
  4750.0    0.05       0  4868.0    0.03       0  4872.0    0.05       0
Bank Sta=4868,4872
Exp/Cntr=0.3,0.1

Type RM Length L Ch R = 1,4931,479,479,479
BEGIN DESCRIPTION:
Caney Creek T 34 5.0
END DESCRIPTION:
XS GIS Cut Line= 3
      2729872.84      6765367.25      2729676.00      6765411.00
      2729180.24      6765641.36
#Sta/Elev= 30
  4798.7  327.21  4826.2  327.22  4846.7  326.01  4856.9  325.76  4877.4  323.25
  4883.8  322.23  4895.9  322.00  4896.1  321.50  4899.6  321.50  4899.9  322.00
  5287.0  322.00  5294.8  322.52  5300.3  324.70  5309.1  325.44  5317.7  325.31
  5323.2  325.80  5340.5  326.25  5346.1  326.74  5363.4  326.96  5369.0  327.69
  5375.2  327.92  5386.3  328.82  5391.8  331.67  5397.4  333.06  5408.3  334.81
  5414.7  336.53  5443.1  338.73  5474.5  339.84  5511.8  340.48  5547.0  341.99
#Mann=3,-1,0
  4798.7    0.05       0  4895.9    0.03       0  4899.9    0.05       0
Bank Sta=4895.9,4899.9
Exp/Cntr=0.3,0.1

Type RM Length L Ch R = 1,4452,227,227,227
BEGIN DESCRIPTION:
Caney Creek T 34 4.0
END DESCRIPTION:
XS GIS Cut Line= 3
      2729838.63      6765209.59      2729376.00      6765261.00
      2729175.98      6765361.01
#Sta/Elev= 30
  4524.7  330.48  4528.5  330.48  4537.4  329.81  4547.5  329.70  4577.7  327.11
  4582.7  326.07  4597.8  324.86  4607.8  323.75  4617.9  322.21  4626.0  322.00
  4626.2  321.50  4629.7  321.50  4630.0  322.00  5071.2  322.00  5079.6  324.87
  5093.6  326.30  5102.0  326.98  5110.4  328.35  5116.0  329.40  5124.3  330.25
  5132.7  330.80  5138.3  331.63  5155.1  332.70  5160.7  333.62  5169.1  334.27
  5177.4  335.87  5183.0  336.20  5191.4  338.06  5211.0  340.29  5213.8  340.29
#Mann=3,-1,0
  4524.7    0.05       0  4626.0    0.05       0  4630.0    0.05       0
Bank Sta=4626,4630
Exp/Cntr=0.3,0.1

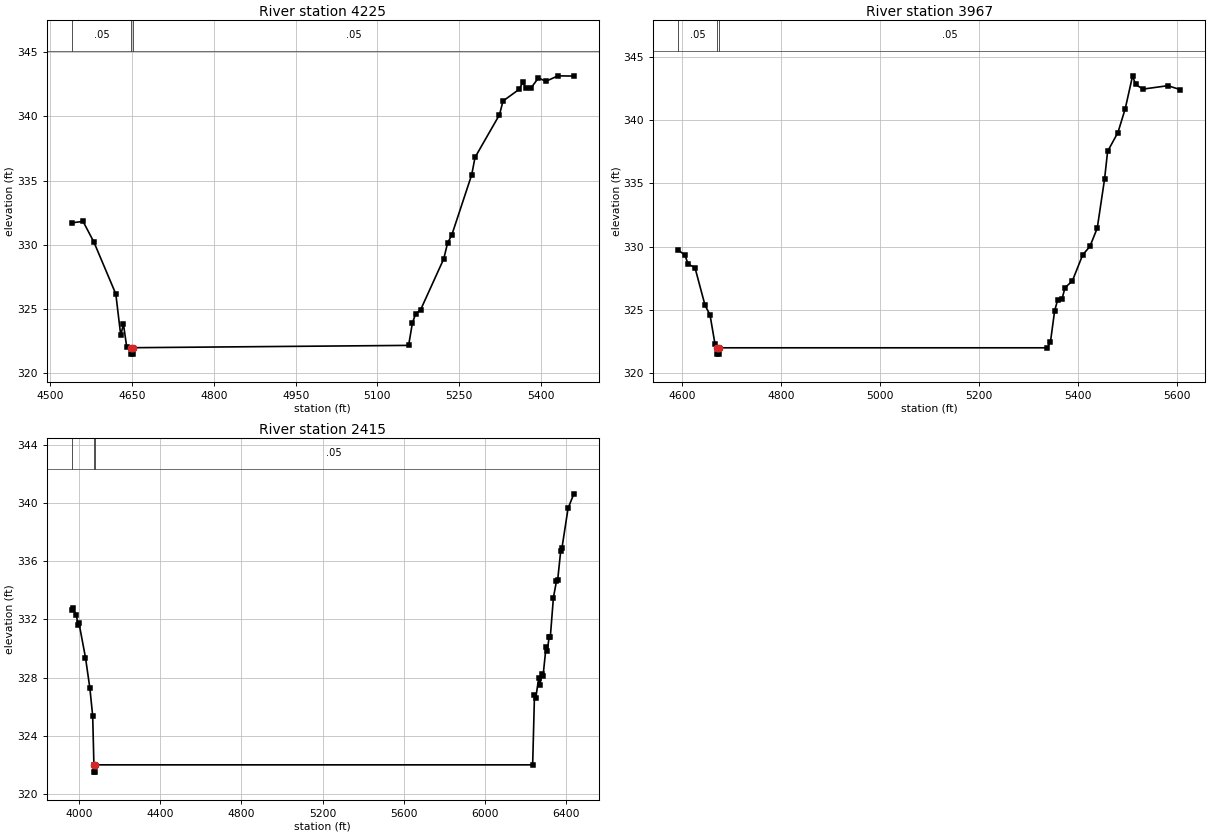
Type RM Length L Ch R = 1,4225,258,258,258
BEGIN DESCRIPTION:
Caney Creek T 34 3.0
END DESCRIPTION:
XS GIS Cut Line= 3
      2729826.71      6765042.06      2729376.00      6765061.00
      2728981.52      6765316.32
#Sta/Elev= 30
  4539.3  331.72  4560.0  331.83  4580.0  330.21  4620.1  326.18  4629.1  322.97
  4634.1  323.84  4640.1  322.05  4648.1  322.00  4648.4  321.50  4651.9  321.50
  4652.1  322.00  5157.2  322.18  5164.2  323.94  5170.1  324.63  5179.3  324.96
  5221.6  328.91  5228.6  330.13  5236.7  330.81  5273.0  335.47  5279.0  336.81
  5323.9  340.13  5330.4  341.20  5359.7  342.10  5366.7  342.65  5372.6  342.22
  5381.8  342.22  5395.4  343.00  5408.9  342.73  5431.1  343.16  5460.3  343.14
#Mann=3,-1,0
  4539.3    0.05       0  4648.1    0.03       0  4652.1    0.05       0
Bank Sta=4648.1,4652.1
Exp/Cntr=0.3,0.1

Type RM Length L Ch R = 1,3967,1552,1552,1552
BEGIN DESCRIPTION:
Caney Creek T 34 2.0
END DESCRIPTION:
XS GIS Cut Line= 3
      2729829.36      6764929.55      2729426.00      6764861.00
      2728931.90      6765211.61
#Sta/Elev= 30
  4591.5  329.72  4605.1  329.32  4611.4  328.61  4625.3  328.34  4645.6  325.37
  4655.8  324.59  4665.9  322.27  4669.7  322.00  4669.9  321.50  4673.4  321.50
  4673.7  322.00  5337.7  322.00  5344.0  322.47  5352.5  324.94  5358.6  325.79
  5367.3  325.85  5373.4  326.75  5388.2  327.28  5409.1  329.34  5423.8  330.01
  5438.6  331.46  5453.4  335.34  5459.5  337.52  5480.4  339.01  5495.2  340.90
  5510.0  343.49  5516.1  342.81  5530.9  342.44  5581.3  342.71  5606.5  342.40
#Mann=3,-1,0
  4591.5    0.05       0  4669.7    0.03       0  4673.7    0.05       0
Bank Sta=4669.7,4673.7
Exp/Cntr=0.3,0.1

Type RM Length L Ch R = 1,2415,0,0,0
BEGIN DESCRIPTION:
Caney Creek T 34 1.0
END DESCRIPTION:
XS GIS Cut Line= 3
      2729826.02      6764611.01      2728926.00      6764111.00
      2728126.00      6765311.00
#Sta/Elev= 30
  3965.2  332.66  3973.2  332.76  3988.1  332.30  3995.0  331.64  4000.7  331.74
  4032.7  329.37  4054.5  327.25  4068.2  325.35  4074.2  322.00  4074.4  321.50
  4077.9  321.50  4078.2  322.00  6234.2  322.00  6243.2  326.77  6249.2  326.57
  6264.2  327.97  6270.2  327.49  6279.3  328.27  6285.3  328.09  6300.3  330.12
  6306.3  329.85  6315.3  330.78  6321.3  330.81  6336.4  333.49  6351.4  334.62
  6357.4  334.70  6372.4  336.71  6378.4  336.89  6408.5  339.62  6437.0  340.62
#Mann=3,-1,0
  3965.2    0.05       0  4074.2    0.03       0  4078.2    0.05       0
Bank Sta=4074.2,4078.2
Exp/Cntr=0.3,0.1

Chan Stop Cuts=-1