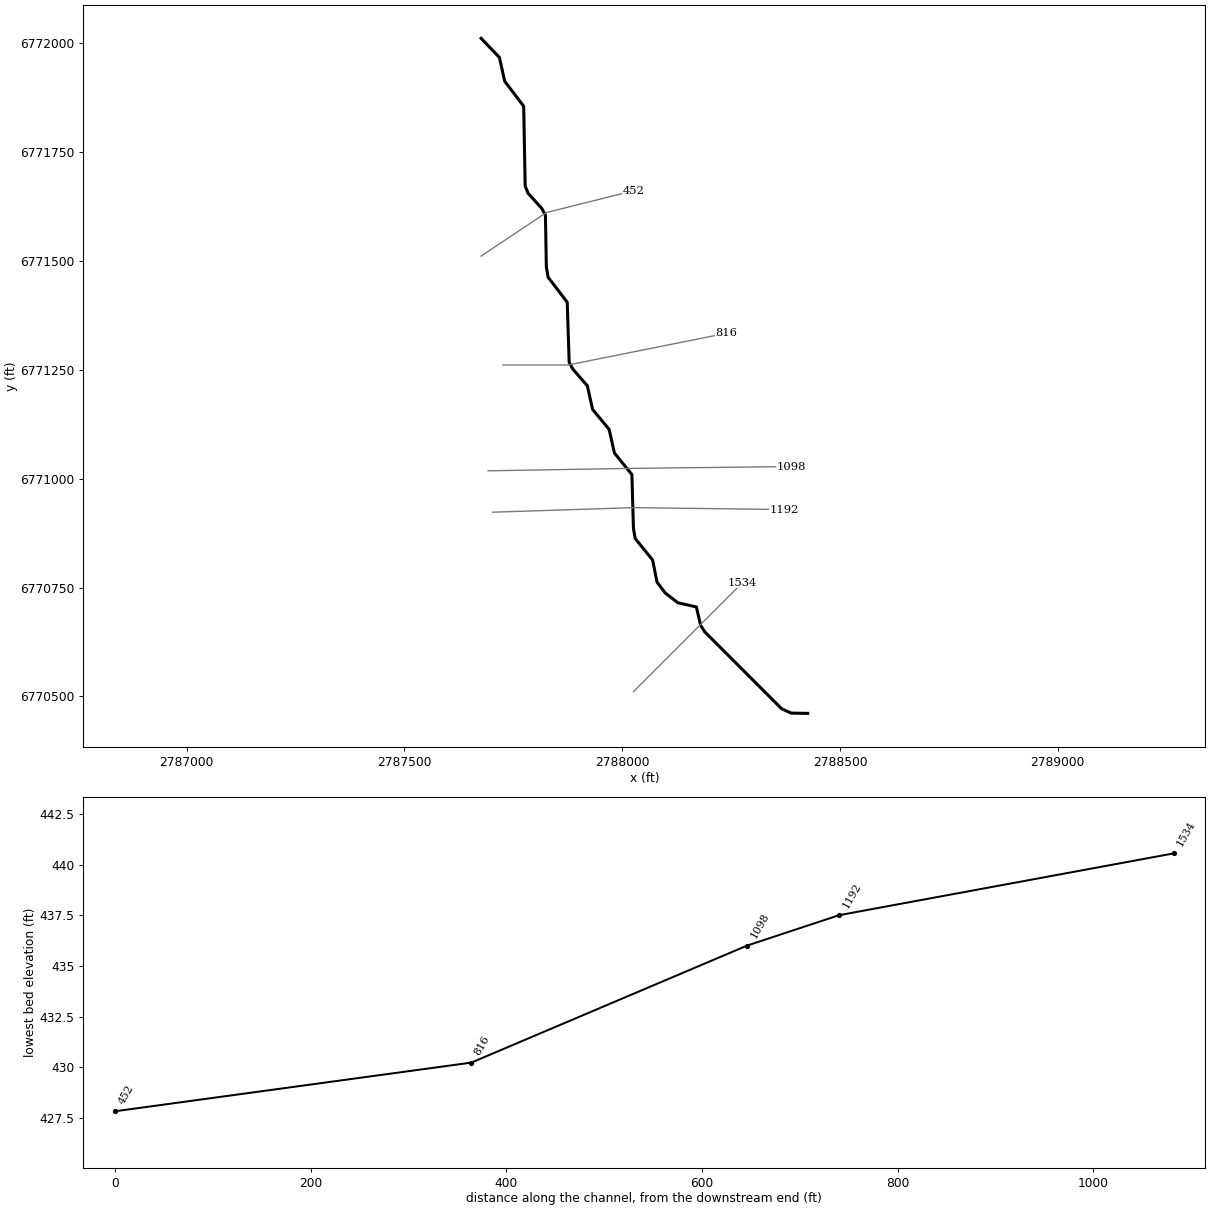
--- Caney Creek T 35.prj (project) ---

Proj Title=Caney Creek T 35 Base Level Engineering
Current Plan=p01
Default Exp/Contr=0.3,0.1
English Units
Geom File=g01
Flow File=f01
Plan File=p01
BEGIN DESCRIPTION:
Caney Creek T 35
END DESCRIPTION:

--- Caney Creek T 35.p01 (plan) ---

Plan Title=Multiple Run
Short Identifier=Multiple
Geom File=g01
Flow File=f01
Subcritical Flow
K Sum by GR= 0
Std Step Tol= 0.01
Critical Tol= 0.01
Num of Std Step Trials= 20
Max Error Tol= 0.3
Flow Tol Ratio= 0.001
Split Flow NTrial= 30
Split Flow Tol= 0.02
Split Flow Ratio= 0.02
Log Output Level= 0
Friction Slope Method= 1
Unsteady Friction Slope Method= 2
Unsteady Bridges Friction Slope Method= 1
Parabolic Critical Depth
Global Vel Dist=  1 , 1 , 1
Global Log Level= 0
CheckData=True
Encroach Param= -1, 0, 0, 0
BEGIN DESCRIPTION:
Multiple Run
END DESCRIPTION:

--- Caney Creek T 35.f01 (steady flow) ---

Flow Title=Multiple
Number of Profiles=7
Profile Names=10-year,25-year,50-year,1pct_min,100-year,1pct_plu,500-year
River Rch & RM= Caney Creek T 35,Reach-1,1534
     432     574     688     411     820    1636    1166
Boundary for River Rch & Prof#=Caney Creek T 35,Reach-1,1
Up Type=0
Dn Type=3
Dn Slope=0.005
Boundary for River Rch & Prof#=Caney Creek T 35,Reach-1,2
Up Type=0
Dn Type=3
Dn Slope=0.005
Boundary for River Rch & Prof#=Caney Creek T 35,Reach-1,3
Up Type=0
Dn Type=3
Dn Slope=0.005
Boundary for River Rch & Prof#=Caney Creek T 35,Reach-1,4
Up Type=0
Dn Type=3
Dn Slope=0.005
Boundary for River Rch & Prof#=Caney Creek T 35,Reach-1,5
Up Type=0
Dn Type=3
Dn Slope=0.005
Boundary for River Rch & Prof#=Caney Creek T 35,Reach-1,6
Up Type=0
Dn Type=3
Dn Slope=0.005
Boundary for River Rch & Prof#=Caney Creek T 35,Reach-1,7
Up Type=0
Dn Type=3
Dn Slope=0.005

--- Caney Creek T 35.g01 (geometry) ---

Geom Title=Existing Conditions

River Reach=Caney Creek T 35,Reach-1
Reach XY= 30
      2788426.00      6770461.00      2788387.84      6770461.59
      2788366.21      6770471.51      2788189.72      6770648.02
      2788180.12      6770663.01      2788170.35      6770705.37
      2788127.79      6770715.04      2788098.97      6770737.21
      2788079.88      6770762.43      2788069.85      6770813.15
      2788029.76      6770862.56      2788025.81      6770885.92
      2788022.24      6771009.44      2787982.12      6771058.82
      2787969.92      6771113.20      2787932.08      6771158.80
      2787919.88      6771213.18      2787886.80      6771251.33
      2787878.25      6771266.93      2787873.73      6771405.06
      2787829.79      6771462.57      2787825.82      6771485.93
      2787823.73      6771605.06      2787815.14      6771620.64
      2787784.14      6771654.94      2787777.22      6771671.51
      2787773.77      6771855.08      2787730.08      6771912.69
      2787718.09      6771967.15      2787676.00      6772011.00

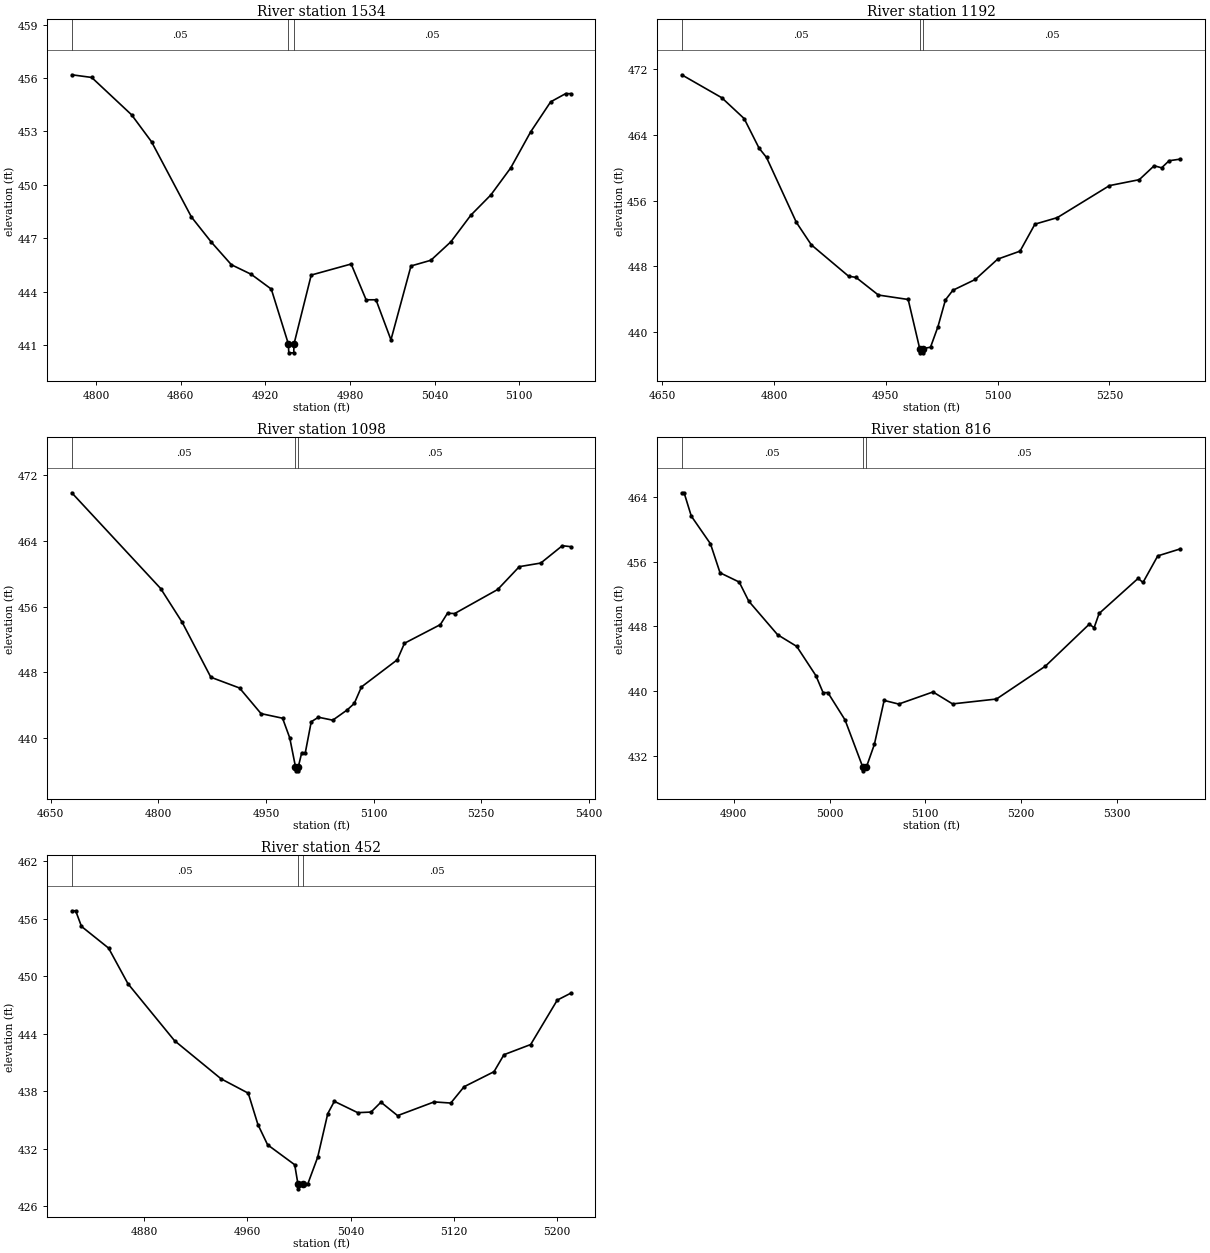
Type RM Length L Ch R = 1,1534,342,342,342
BEGIN DESCRIPTION:
Caney Creek T 35 4.0
END DESCRIPTION:
XS GIS Cut Line= 3
      2788026.02      6770511.02      2788176.00      6770661.00
      2788275.98      6770760.98
#Sta/Elev= 28
  4782.8  456.18  4796.9  456.03  4825.2  453.93  4839.3  452.42  4867.6  448.19
  4881.8  446.77  4895.9  445.51  4910.0  444.97  4924.2  444.14  4936.3  441.06
  4936.6  440.56  4940.1  440.56  4940.3  441.06  4952.5  444.93  4980.8  445.55
  4991.4  443.54  4998.4  443.54  5009.0  441.29  5023.2  445.44  5037.3  445.76
  5051.5  446.80  5065.6  448.29  5079.8  449.43  5093.9  450.95  5108.0  452.97
  5122.2  454.66  5132.8  455.12  5136.3  455.12
#Mann=3,-1,0
  4782.8    0.05       0  4936.3    0.03       0  4940.3    0.05       0
Bank Sta=4936.3,4940.3
Exp/Cntr=0.3,0.1

Type RM Length L Ch R = 1,1192,94,94,94
BEGIN DESCRIPTION:
Caney Creek T 35 3.0
END DESCRIPTION:
XS GIS Cut Line= 3
      2787702.22      6770922.95      2788025.96      6770933.38
      2788371.33      6770929.02
#Sta/Elev= 30
  4676.1  471.28  4729.9  468.49  4759.9  465.96  4779.9  462.37  4789.9  461.24
  4830.0  453.35  4850.0  450.63  4900.0  446.82  4910.0  446.67  4940.0  444.53
  4980.0  443.99  4995.5  438.01  4995.8  437.51  4999.3  437.51  4999.5  438.01
  5010.0  438.20  5020.0  440.70  5030.0  443.94  5040.0  445.11  5070.0  446.42
  5100.1  448.89  5130.1  449.86  5150.1  453.14  5180.1  453.93  5250.1  457.82
  5290.1  458.54  5310.1  460.23  5320.1  459.98  5330.1  460.84  5345.4  461.04
#Mann=3,-1,0
  4676.1    0.05       0  4995.5    0.05       0  4999.5    0.05       0
Bank Sta=4995.5,4999.5
Exp/Cntr=0.3,0.1

Type RM Length L Ch R = 1,1098,282,282,282
BEGIN DESCRIPTION:
Mapping XS a17b2b18
END DESCRIPTION:
XS GIS Cut Line= 3
      2787692.12      6771017.95      2788014.41      6771023.48
      2788387.55      6771027.71
#Sta/Elev= 30
  4679.2  469.88  4803.1  458.22  4833.1  454.11  4873.1  447.41  4913.1  446.10
  4943.1  442.98  4973.1  442.42  4983.1  440.03  4991.1  436.51  4991.4  436.01
  4994.9  436.01  4995.1  436.51  4999.8  438.21  5004.8  438.21  5013.1  441.99
  5023.1  442.54  5043.1  442.18  5063.1  443.42  5073.1  444.22  5083.1  446.23
  5133.1  449.54  5143.1  451.55  5193.1  453.82  5203.1  455.21  5213.1  455.17
  5273.1  458.10  5303.2  460.88  5333.2  461.32  5363.2  463.43  5374.7  463.32
#Mann=3,-1,0
  4679.2    0.05       0  4991.1    0.05       0  4995.1    0.05       0
Bank Sta=4991.1,4995.1
Exp/Cntr=0.3,0.1

Type RM Length L Ch R = 1,816,364,364,364
BEGIN DESCRIPTION:
Caney Creek T 35 2.0
END DESCRIPTION:
XS GIS Cut Line= 3
      2787726.01      6771261.00      2787876.00      6771261.00
      2788239.20      6771333.70
#Sta/Elev= 30
  4845.8  464.46  4848.3  464.46  4855.8  461.59  4875.8  458.18  4885.8  454.61
  4905.8  453.47  4915.8  451.11  4945.8  446.99  4965.8  445.55  4985.8  441.95
  4993.3  439.86  4998.3  439.86  5016.2  436.50  5034.6  430.73  5034.8  430.23
  5038.6  430.73  5046.8  433.48  5057.0  438.90  5072.2  438.45  5108.0  439.94
  5128.4  438.47  5174.2  439.07  5225.2  443.11  5271.0  448.28  5276.1  447.85
  5281.3  449.60  5322.0  453.92  5327.1  453.42  5342.5  456.69  5366.2  457.56
#Mann=3,-1,0
  4845.8    0.05       0  5034.6    0.03       0  5038.6    0.05       0
Bank Sta=5034.6,5038.6
Exp/Cntr=0.3,0.1

Type RM Length L Ch R = 1,452,0,0,0
BEGIN DESCRIPTION:
Caney Creek T 35 1.0
END DESCRIPTION:
XS GIS Cut Line= 3
      2787676.04      6771511.03      2787826.00      6771611.00
      2788026.01      6771661.00
#Sta/Elev= 30
  4824.0  456.81  4827.0  456.81  4831.5  455.18  4852.5  452.92  4867.5  449.21
  4903.6  443.27  4939.6  439.30  4960.7  437.80  4968.2  434.53  4975.7  432.42
  4996.7  430.34  4999.2  428.33  4999.5  427.83  5003.2  428.33  5006.8  428.33
  5014.5  431.13  5022.3  435.67  5027.4  436.95  5045.5  435.77  5055.8  435.83
  5063.5  436.86  5076.4  435.46  5104.7  436.89  5117.6  436.77  5127.9  438.47
  5151.1  440.04  5158.8  441.81  5179.5  442.87  5200.1  447.50  5210.4  448.21
#Mann=3,-1,0
  4824.0    0.05       0  4999.2    0.03       0  5003.2    0.05       0
Bank Sta=4999.2,5003.2
Exp/Cntr=0.3,0.1

Chan Stop Cuts=-1