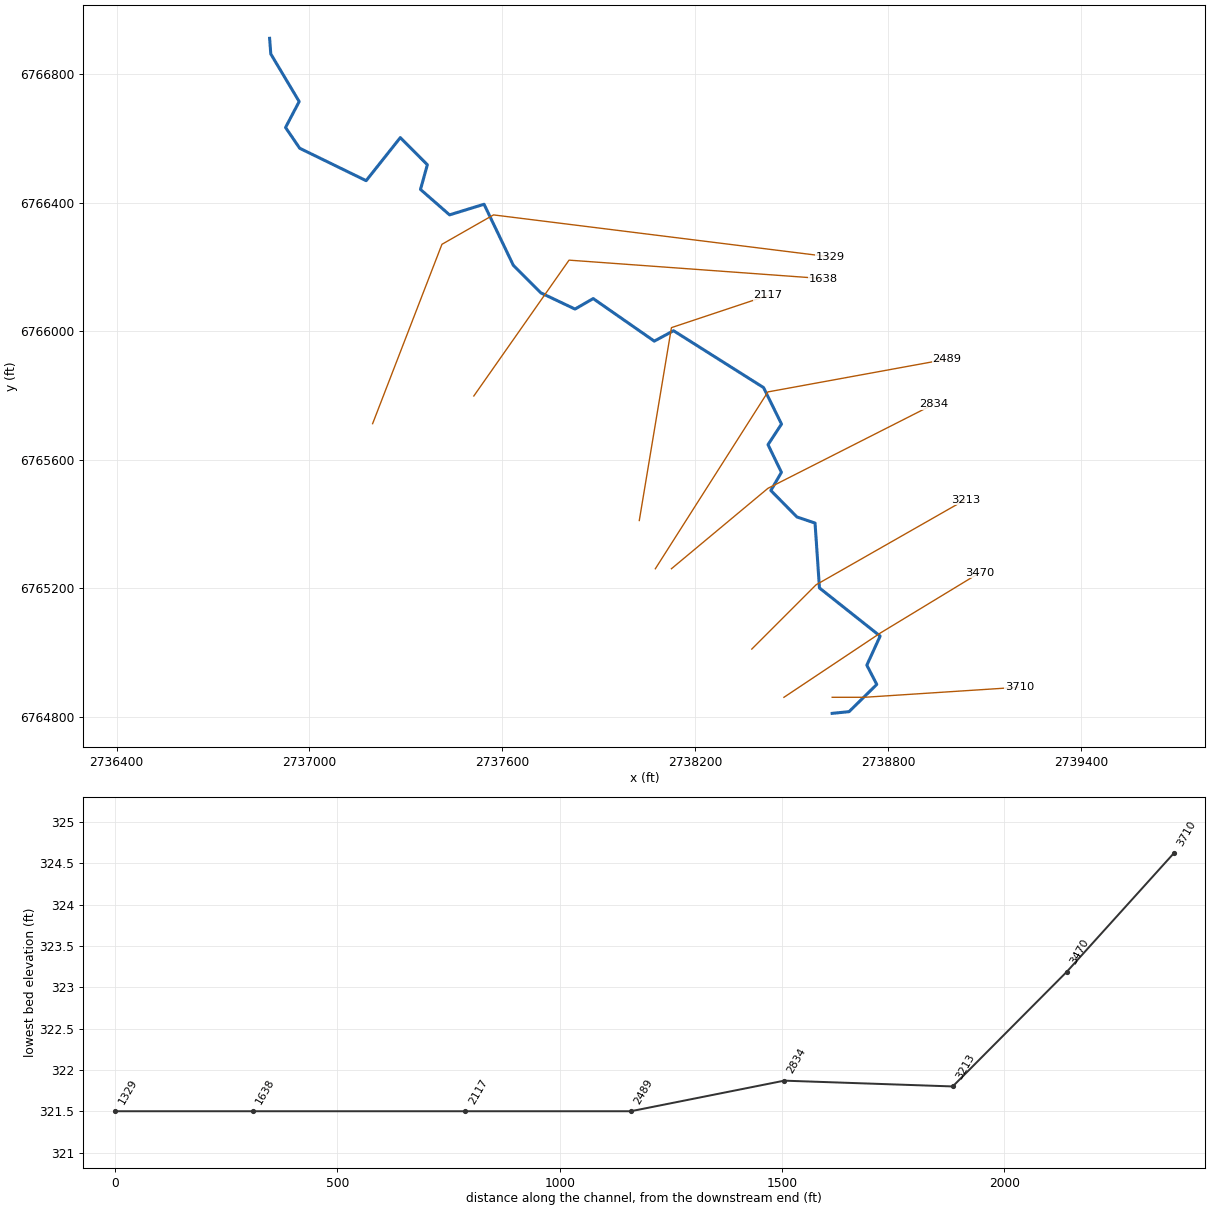
--- Caney Creek T 4.prj (project) ---

Proj Title=Caney Creek T 4 Base Level Engineering
Current Plan=p01
Default Exp/Contr=0.3,0.1
English Units
Geom File=g01
Flow File=f01
Plan File=p01
Y Axis Title=Elevation
X Axis Title(PF)=Main Channel Distance
X Axis Title(XS)=Station
BEGIN DESCRIPTION:
Caney Creek T 4
END DESCRIPTION:
DSS Export Rating Curves= 0
DSS Export Rating Curve Sorted= 0
DSS Export Volume Flow Curves= 0
DXF OffsetX= 0
DXF OffsetY= 0
DXF ScaleX= 1
DXF ScaleY= 10

--- Caney Creek T 4.p01 (plan) ---

Plan Title=Multiple Run
Program Version=4.10
Short Identifier=Multiple
Geom File=g01
Flow File=f01
Subcritical Flow
K Sum by GR= 0
Std Step Tol= 0.01
Critical Tol= 0.01
Num of Std Step Trials= 20
Max Error Tol= 0.3
Flow Tol Ratio= 0.001
Split Flow NTrial= 30
Split Flow Tol= 0.02
Split Flow Ratio= 0.02
Log Output Level= 0
Friction Slope Method= 1
Unsteady Friction Slope Method= 2
Unsteady Bridges Friction Slope Method= 1
Parabolic Critical Depth
Global Vel Dist= 1 , 1 , 1
Global Log Level= 0
CheckData=True
Encroach Param=-1 ,0,0, 0
BEGIN DESCRIPTION:
Multiple Run
END DESCRIPTION:
Computation Interval=1HOUR
Output Interval=1HOUR
Run HTab= 0
Run UNet= 0
Run PostProcess= 0
Run WQNet= 0
UNET Theta= 1
UNET Theta Warmup= 1
UNET ZTol= 0.02
UNET ZSATol= 0.05
UNET MxIter= 20
UNET MaxInSteps= 0
UNET DtIC= 0
UNET DtMin= 0
UNET MaxCRTS= 20
UNET WFStab= 2
UNET SFStab= 1
UNET WFX= 1
UNET SFX= 1
UNET DSS MLevel= 4
UNET DZMax Abort= 100
UNET Convert EG Bridges= 0
UNET Use Existing IB Tables=-1
UNET Froude Reduction=False
UNET Froude Limit= 1
UNET Froude Power= 10
UNET Time Slicing=0,0, 5
UNET Junction Losses=0
Instantaneous Interval=1HOUR
Write IC File= 0
Write IC File at Sim End=0
Echo Input=False
Echo Parameters=False
Echo Output=False
Write Detailed= 0
WQ AD Non Conservative
WQ ULTIMATE=-1
WQ Max Comp Step=1HOUR
WQ Output Interval=15MIN
WQ Output Selected Increments= 0
WQ Output face flow=0
WQ Output face velocity=0
WQ Output face area=0
WQ Output face dispersion=0
WQ Output cell volume=0
WQ Output cell surface area=0
WQ Output cell continuity=0
WQ Output cumulative cell continuity=0
WQ Output face conc=0
WQ Output face dconc_dx=0
WQ Output face courant=0
WQ Output face peclet=0
WQ Output face adv mass=0
WQ Output face disp mass=0
WQ Output cell mass=0
WQ Output cell source sink temp=0
WQ Output cell source sink nsm=0
WQ Output MaxMinRange=-1
WQ Daily Max Min Mean=-1
WQ Daily Range=0
WQ Daily Time=0
WQ Create Restart=0
WQ Fixed Restart=0
WQ System Summary=0
WQ Use Fixed Temperature=0
Sorting and Armoring Iterations= 10
XS Update Threshold= 0.02
Hydraulics Update Threshold= 0.02
Energy Slope Method= 1
Volume Change Method= 0
XS Weighting Method= 0
Number of US Weighted Cross Sections= 1
Number of DS Weighted Cross Sections= 1
Upstream XS Weight=0.25
Main XS Weight=0.5
Downstream XS Weight=0.25
Number of DS XS's Weighted with US Boundary= 1
Upstream Boundary Weight= 1
Weight of XSs Associated with US Boundary= 0
Number of US XS's Weighted with DS Boundary= 1
Downstream Boundary Weight= 0.5
Weight of XSs Associated with DS Boundary= 0.5
Sediment Output Level= 4
Mass or Volume Output= 0
Output Increment Type= 1
Profile and TS Output Increment= 10
XS Output Flag= 0
XS Output Increment= 10
Disregard all LS=0
Disregard all Conn=0
Disregard all Breaches=0
Disregard all Pumps=0

--- Caney Creek T 4.f01 (steady flow) ---

Flow Title=Multiple
Number of Profiles=7
Profile Names=10-year,25-year,50-year,1pct_min,100-year,1pct_plu,500-year
River Rch & RM= Caney Creek T 4,Reach-1,3710
     444     582     691     407     813    1622    1124
Boundary for River Rch & Prof#=Caney Creek T 4,Reach-1,1
Up Type=0
Dn Type=3
Dn Slope=0.005
Boundary for River Rch & Prof#=Caney Creek T 4,Reach-1,2
Up Type=0
Dn Type=3
Dn Slope=0.005
Boundary for River Rch & Prof#=Caney Creek T 4,Reach-1,3
Up Type=0
Dn Type=3
Dn Slope=0.005
Boundary for River Rch & Prof#=Caney Creek T 4,Reach-1,4
Up Type=0
Dn Type=3
Dn Slope=0.005
Boundary for River Rch & Prof#=Caney Creek T 4,Reach-1,5
Up Type=0
Dn Type=3
Dn Slope=0.005
Boundary for River Rch & Prof#=Caney Creek T 4,Reach-1,6
Up Type=0
Dn Type=3
Dn Slope=0.005
Boundary for River Rch & Prof#=Caney Creek T 4,Reach-1,7
Up Type=0
Dn Type=3
Dn Slope=0.005

--- Caney Creek T 4.g01 (geometry) ---

Geom Title=Existing Conditions

River Reach=Caney Creek T 4,Reach-1
Reach XY= 30
      2738626.00      6764811.00      2738678.56      6764816.31
      2738764.80      6764900.98      2738733.84      6764960.91
      2738775.27      6765051.36      2738586.47      6765201.18
      2738572.77      6765402.99      2738516.58      6765421.91
      2738435.29      6765504.31      2738468.16      6765560.91
      2738426.44      6765646.93      2738468.44      6765711.00
      2738412.54      6765824.56      2738132.55      6766001.41
      2738072.67      6765969.01      2737882.55      6766101.42
      2737826.08      6766068.76      2737719.93      6766119.11
      2737634.13      6766204.93      2737543.08      6766394.85
      2737435.78      6766361.80      2737345.36      6766440.95
      2737366.70      6766517.70      2737282.55      6766602.11
      2737176.30      6766468.20      2736969.57      6766569.02
      2736925.56      6766633.70      2736967.93      6766714.31
      2736879.60      6766862.49      2736876.00      6766911.00

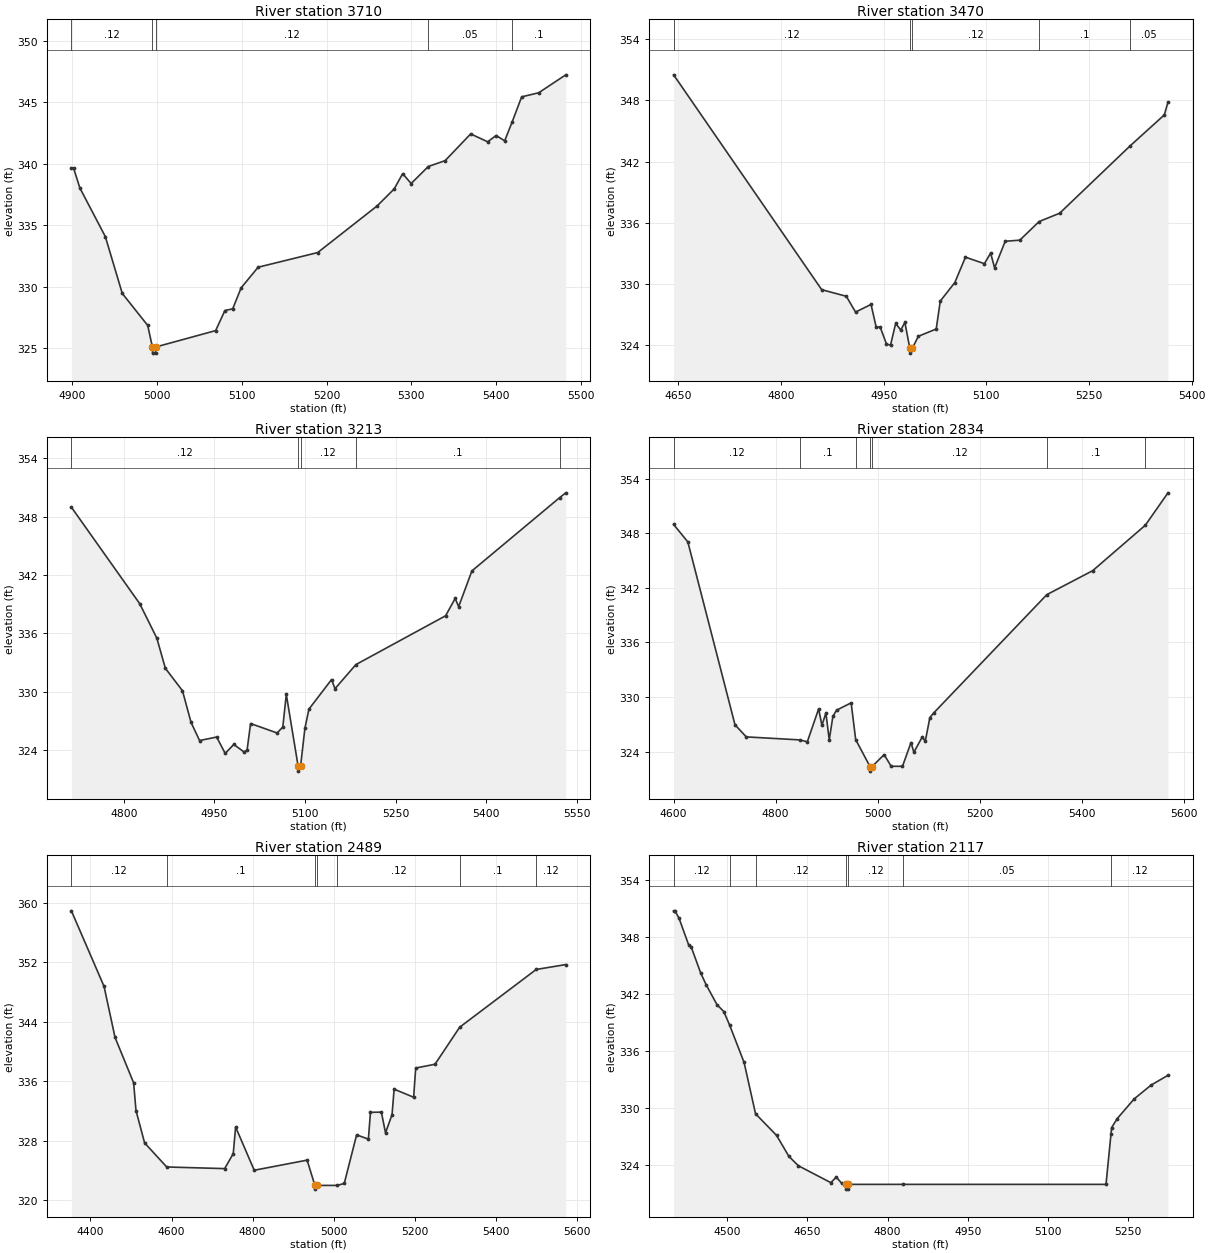
Type RM Length L Ch R = 1,3710,240,240,240
BEGIN DESCRIPTION:
Caney Creek T 4 7.0
END DESCRIPTION:
XS GIS Cut Line= 3
      2738626.01      6764861.00      2738726.00      6764861.00
      2739207.89      6764892.40
#Sta/Elev= 30
  4899.2  339.67  4901.7  339.67  4909.2  338.04  4939.2  334.09  4959.2  329.47
  4989.2  326.87  4994.7  325.12  4994.9  324.62  4998.4  324.62  4998.7  325.12
  5069.3  326.45  5080.2  328.08  5089.4  328.22  5099.4  329.93  5119.4  331.60
  5189.6  332.79  5259.7  336.58  5279.8  337.96  5289.8  339.20  5299.8  338.40
  5320.0  339.78  5339.9  340.26  5370.0  342.43  5390.0  341.79  5400.0  342.30
  5410.1  341.87  5419.0  343.42  5430.1  345.44  5450.1  345.77  5482.1  347.23
#Mann=5,-1,0
  4899.2    0.12       0  4994.7    0.07       0  4998.7    0.12       0
  5320.0    0.05       0  5419.0     0.1       0
Bank Sta=4994.7,4998.7
Exp/Cntr=0.3,0.1

Type RM Length L Ch R = 1,3470,257,257,257
BEGIN DESCRIPTION:
Caney Creek T 4 6.0
END DESCRIPTION:
XS GIS Cut Line= 3
      2738475.98      6764860.98      2738776.00      6765061.00
      2739085.34      6765248.86
#Sta/Elev= 30
  4642.9  350.51  4859.3  329.42  4895.3  328.77  4908.8  327.22  4931.4  327.97
  4938.9  325.76  4944.9  325.73  4953.9  324.10  4959.9  323.97  4967.4  326.10
  4974.9  325.46  4980.9  326.21  4988.0  323.69  4988.2  323.19  4992.0  323.69
  5000.5  324.84  5026.7  325.56  5032.6  328.30  5053.9  330.12  5069.4  332.61
  5097.1  331.97  5106.2  333.01  5112.0  331.56  5127.5  334.17  5148.8  334.28
  5177.1  336.11  5207.0  336.92  5310.1  343.54  5360.1  346.58  5365.4  347.84
#Mann=5,-1,0
  4642.9    0.12       0  4988.0    0.07       0  4992.0    0.12       0
  5177.1     0.1       0  5310.1    0.05       0
Bank Sta=4988,4992
Exp/Cntr=0.3,0.1

Type RM Length L Ch R = 1,3213,379,379,379
BEGIN DESCRIPTION:
Caney Creek T 4 5.0
END DESCRIPTION:
XS GIS Cut Line= 3
      2738376.02      6765011.02      2738576.00      6765211.00
      2739040.92      6765476.08
#Sta/Elev= 30
  4713.3  348.98  4826.4  339.04  4854.7  335.49  4868.8  332.39  4897.1  330.08
  4911.3  326.82  4925.4  324.95  4953.7  325.31  4967.8  323.62  4982.0  324.55
  4999.0  323.77  5004.0  323.96  5009.8  326.70  5053.7  325.73  5063.1  326.34
  5068.9  329.70  5088.5  322.30  5088.7  321.80  5092.5  322.30  5099.7  326.21
  5106.3  328.18  5143.8  331.23  5149.5  330.29  5184.0  332.77  5332.5  337.80
  5348.3  339.58  5354.1  338.74  5376.0  342.42  5521.1  349.96  5531.3  350.46
#Mann=5,-1,0
  4713.3    0.12       0  5088.5    0.07       0  5092.5    0.12       0
  5184.0     0.1       0  5521.1    0.05       0
Bank Sta=5088.5,5092.5
Exp/Cntr=0.3,0.1

Type RM Length L Ch R = 1,2834,345,345,345
BEGIN DESCRIPTION:
Caney Creek T 4 4.0
END DESCRIPTION:
XS GIS Cut Line= 3
      2738126.04      6765261.03      2738426.00      6765511.00
      2738942.52      6765772.93
#Sta/Elev= 30
  4599.9  348.96  4627.8  347.04  4720.3  326.96  4742.4  325.63  4847.4  325.30
  4862.1  325.09  4884.3  328.70  4890.8  326.90  4898.6  328.25  4905.1  325.30
  4912.3  327.88  4919.4  328.56  4948.1  329.37  4957.0  325.33  4985.1  322.37
  4985.4  321.87  4989.1  322.37  5012.8  323.68  5026.6  322.40  5048.8  322.40
  5065.5  325.01  5071.1  323.94  5087.8  325.65  5093.4  325.13  5102.5  327.75
  5110.0  328.26  5331.9  341.25  5421.8  343.88  5525.0  348.87  5569.5  352.43
#Mann=7,-1,0
  4599.9    0.12       0  4847.4     0.1       0  4957.0    0.12       0
  4985.1    0.07       0  4989.1    0.12       0  5331.9     0.1       0
  5525.0    0.12       0
Bank Sta=4985.1,4989.1
Exp/Cntr=0.3,0.1

Type RM Length L Ch R = 1,2489,372,372,372
BEGIN DESCRIPTION:
Caney Creek T 4 3.0
END DESCRIPTION:
XS GIS Cut Line= 3
      2738075.97      6765260.96      2738426.00      6765811.00
      2738982.90      6765912.84
#Sta/Elev= 30
  4353.3  358.94  4433.8  348.77  4460.9  341.90  4506.6  335.81  4512.5  332.07
  4533.7  327.72  4588.2  324.48  4731.0  324.26  4752.1  326.28  4758.0  329.85
  4803.8  324.04  4934.1  325.40  4953.3  322.00  4953.6  321.50  4957.3  322.00
  5008.0  322.00  5025.6  322.26  5056.1  328.80  5085.1  328.23  5090.2  331.83
  5117.1  331.86  5127.3  329.07  5143.4  331.53  5148.5  334.95  5196.6  333.86
  5201.7  337.79  5249.2  338.30  5310.0  343.28  5498.5  351.05  5571.4  351.71
#Mann=7,-1,0
  4353.3    0.12       0  4588.2     0.1       0  4953.3    0.07       0
  4957.3     0.1       0  5008.0    0.12       0  5310.0     0.1       0
  5498.5    0.12       0
Bank Sta=4953.3,4957.3
Exp/Cntr=0.3,0.1

Type RM Length L Ch R = 1,2117,479,479,479
BEGIN DESCRIPTION:
Caney Creek T 4 2.0
END DESCRIPTION:
XS GIS Cut Line= 3
      2738026.00      6765410.98      2738126.00      6766011.00
      2738425.98      6766110.99
#Sta/Elev= 30
  4399.8  350.74  4402.4  350.74  4410.0  349.95  4427.7  347.20  4432.8  346.93
  4450.5  344.20  4460.6  342.98  4480.9  340.88  4493.6  340.16  4504.5  338.74
  4531.6  334.81  4553.0  329.42  4592.4  327.14  4615.3  324.95  4633.0  323.96
  4693.8  322.18  4704.0  322.77  4714.1  322.11  4722.2  322.00  4722.5  321.50
  4726.0  321.50  4726.2  322.00  4829.5  322.00  5208.4  322.00  5217.8  327.34
  5218.9  327.96  5229.5  328.92  5261.1  330.98  5292.7  332.43  5324.3  333.46
#Mann=7,-1,0
  4399.8    0.12       0  4504.5     0.1       0  4553.0    0.12       0
  4722.2    0.03       0  4726.2    0.12       0  4829.5    0.05       0
  5217.8    0.12       0
Bank Sta=4722.2,4726.2
Exp/Cntr=0.3,0.1

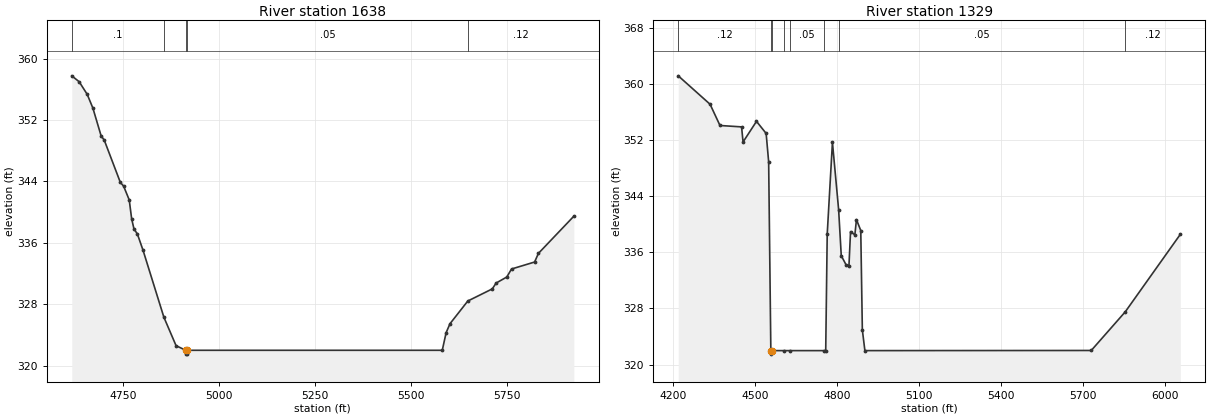
Type RM Length L Ch R = 1,1638,309,309,309
BEGIN DESCRIPTION:
Mapping XS 4bed52d0
END DESCRIPTION:
XS GIS Cut Line= 3
      2737511.23      6765798.36      2737807.49      6766221.00
      2738598.07      6766163.53
#Sta/Elev= 30
  4615.2  357.76  4634.5  356.99  4655.4  355.35  4670.2  353.56  4691.7  349.94
  4699.9  349.38  4741.7  343.89  4750.4  343.38  4765.0  341.59  4771.3  339.13
  4777.4  337.80  4786.2  337.16  4801.0  335.03  4855.3  326.31  4887.1  322.60
  4912.3  322.00  4912.5  321.50  4916.0  321.50  4916.3  322.00  5581.0  322.00
  5591.1  324.30  5601.1  325.46  5647.6  328.42  5711.4  330.00  5721.4  330.76
  5749.3  331.55  5761.5  332.59  5821.7  333.50  5831.7  334.63  5924.0  339.47
#Mann=5,-1,0
  4615.2     0.1       0  4855.3    0.05       0  4912.3    0.03       0
  4916.3    0.05       0  5647.6    0.12       0
Bank Sta=4912.3,4916.3
Exp/Cntr=0.3,0.1

Type RM Length L Ch R = 1,1329,0,0,0
BEGIN DESCRIPTION:
Caney Creek T 4 1.0
END DESCRIPTION:
XS GIS Cut Line= 4
      2737196.40      6765712.27      2737412.05      6766270.25
      2737572.43      6766361.72      2738619.49      6766231.23
#Sta/Elev= 30
  4218.3  361.12  4334.9  357.07  4371.1  354.05  4450.2  353.85  4455.6  351.70
  4504.8  354.64  4540.1  352.92  4549.3  348.87  4557.3  322.00  4557.5  321.50
  4561.3  322.00  4604.2  322.00  4626.5  322.00  4751.6  322.00  4758.2  322.00
  4763.7  338.59  4782.8  351.64  4805.5  342.05  4815.1  335.51  4833.2  334.18
  4843.3  334.11  4849.1  338.94  4864.9  338.48  4870.7  340.65  4886.5  339.10
  4892.3  324.95  4901.6  322.00  5730.3  322.02  5854.9  327.53  6056.3  338.55
#Mann=8,-1,0
  4218.3    0.12       0  4557.3    0.03       0  4561.3    0.12       0
  4604.2     0.1       0  4626.5    0.05       0  4751.6    0.12       0
  4805.5    0.05       0  5854.9    0.12       0
Bank Sta=4557.3,4561.3
Exp/Cntr=0.3,0.1

Chan Stop Cuts=-1