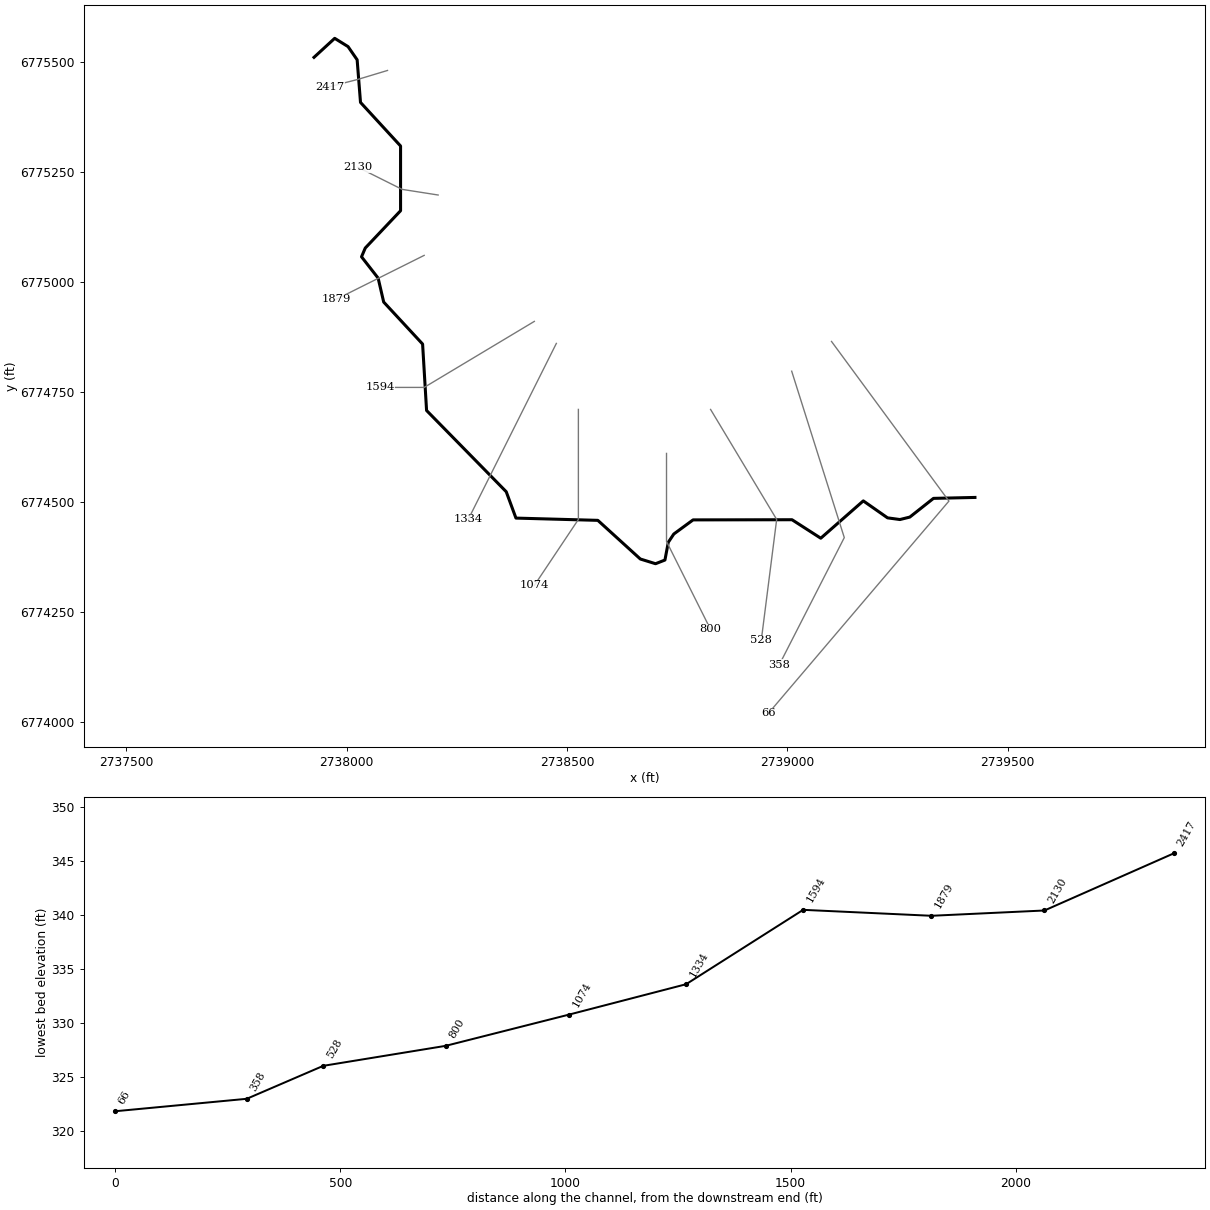
--- Caney Creek T 40.prj (project) ---

Proj Title=Caney Creek T 40 Base Level Engineering
Current Plan=p01
Default Exp/Contr=0.3,0.1
English Units
Geom File=g01
Flow File=f01
Plan File=p01
BEGIN DESCRIPTION:
Caney Creek T 40
END DESCRIPTION:

--- Caney Creek T 40.p01 (plan) ---

Plan Title=Multiple Run
Short Identifier=Multiple
Geom File=g01
Flow File=f01
Subcritical Flow
K Sum by GR= 0
Std Step Tol= 0.01
Critical Tol= 0.01
Num of Std Step Trials= 20
Max Error Tol= 0.3
Flow Tol Ratio= 0.001
Split Flow NTrial= 30
Split Flow Tol= 0.02
Split Flow Ratio= 0.02
Log Output Level= 0
Friction Slope Method= 1
Unsteady Friction Slope Method= 2
Unsteady Bridges Friction Slope Method= 1
Parabolic Critical Depth
Global Vel Dist=  1 , 1 , 1
Global Log Level= 0
CheckData=True
Encroach Param= -1, 0, 0, 0
BEGIN DESCRIPTION:
Multiple Run
END DESCRIPTION:

--- Caney Creek T 40.f01 (steady flow) ---

Flow Title=Multiple
Number of Profiles=7
Profile Names=10-year,25-year,50-year,1pct_min,100-year,1pct_plu,500-year
River Rch & RM= Caney Creek T 40,Reach-1,2417
     233     296     345     200     399     797     534
Boundary for River Rch & Prof#=Caney Creek T 40,Reach-1,1
Up Type=0
Dn Type=3
Dn Slope=0.005
Boundary for River Rch & Prof#=Caney Creek T 40,Reach-1,2
Up Type=0
Dn Type=3
Dn Slope=0.005
Boundary for River Rch & Prof#=Caney Creek T 40,Reach-1,3
Up Type=0
Dn Type=3
Dn Slope=0.005
Boundary for River Rch & Prof#=Caney Creek T 40,Reach-1,4
Up Type=0
Dn Type=3
Dn Slope=0.005
Boundary for River Rch & Prof#=Caney Creek T 40,Reach-1,5
Up Type=0
Dn Type=3
Dn Slope=0.005
Boundary for River Rch & Prof#=Caney Creek T 40,Reach-1,6
Up Type=0
Dn Type=3
Dn Slope=0.005
Boundary for River Rch & Prof#=Caney Creek T 40,Reach-1,7
Up Type=0
Dn Type=3
Dn Slope=0.005

--- Caney Creek T 40.g01 (geometry) ---

Geom Title=Existing Conditions

River Reach=Caney Creek T 40,Reach-1
Reach XY= 30
      2737926.00      6775511.00      2737972.95      6775554.18
      2738003.23      6775535.40      2738023.88      6775505.47
      2738031.54      6775408.58      2738122.46      6775309.53
      2738122.45      6775162.47      2738042.32      6775077.69
      2738033.84      6775057.77      2738071.54      6775009.35
      2738084.14      6774954.96      2738172.45      6774859.53
      2738181.47      6774708.55      2738362.26      6774523.95
      2738384.30      6774464.07      2738570.14      6774458.93
      2738666.59      6774371.09      2738701.08      6774360.39
      2738722.43      6774368.75      2738730.02      6774409.08
      2738742.54      6774427.89      2738786.29      6774459.99
      2739010.84      6774460.34      2739076.10      6774418.34
      2739172.59      6774503.15      2739227.63      6774464.61
      2739255.79      6774460.78      2739278.18      6774466.36
      2739331.86      6774508.87      2739426.00      6774511.00

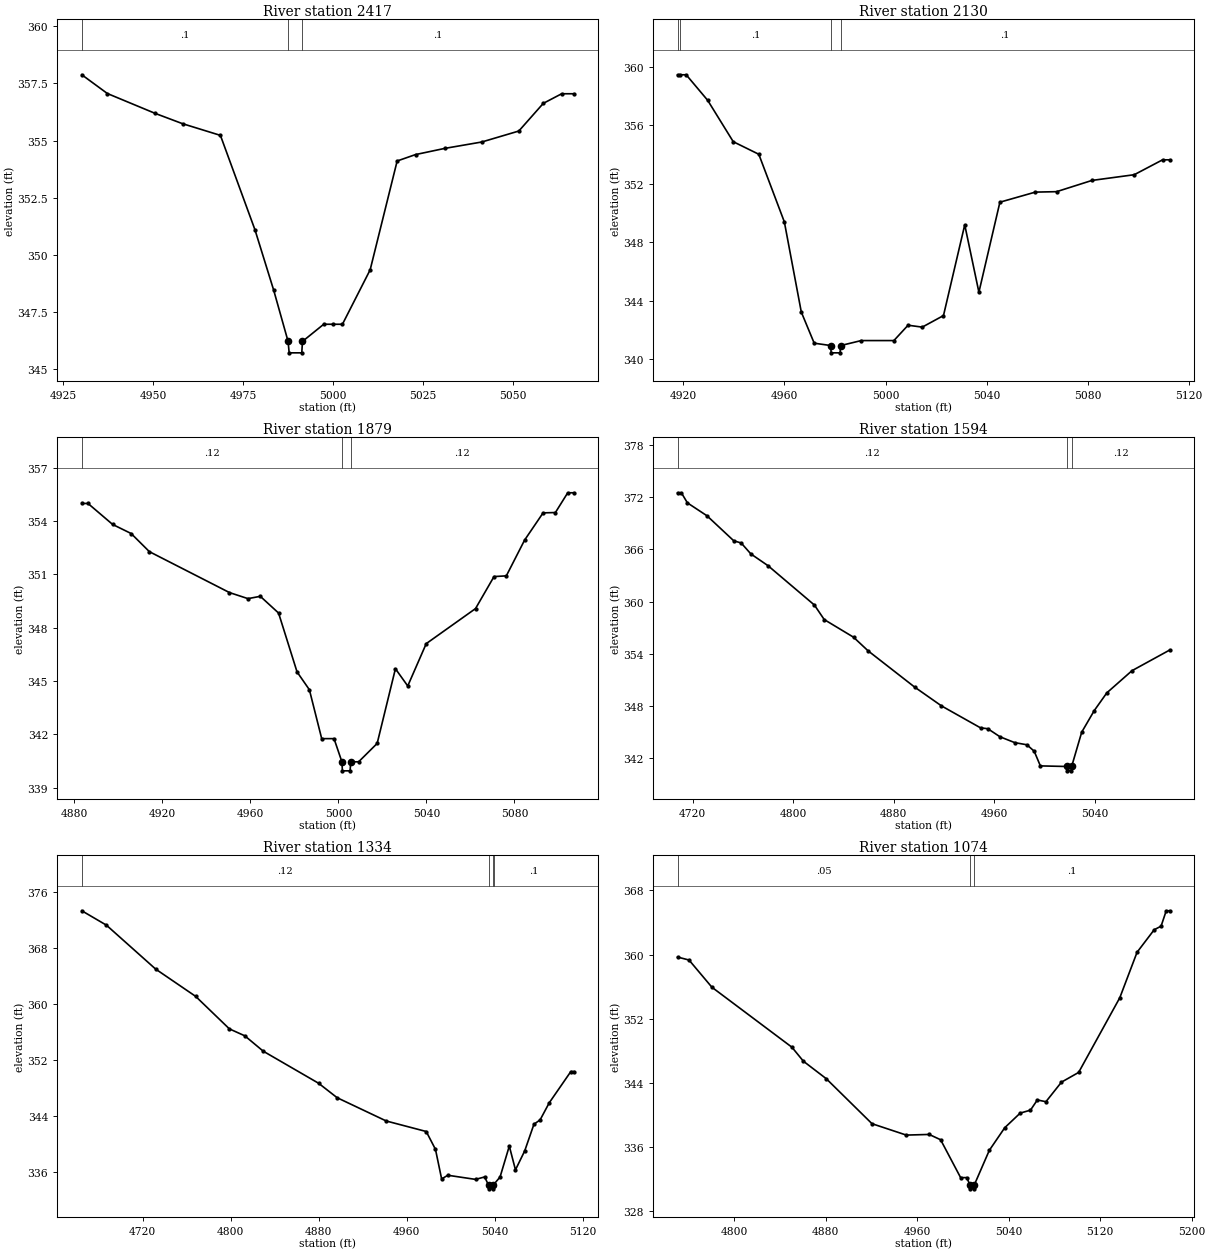
Type RM Length L Ch R = 1,2417,287,287,287
BEGIN DESCRIPTION:
Caney Creek T 40 9.0
END DESCRIPTION:
XS GIS Cut Line= 3
      2738092.81      6775481.19      2738026.00      6775461.00
      2737961.21      6775444.30
#Sta/Elev= 23
  4930.2  357.88  4937.3  357.06  4950.6  356.19  4958.2  355.74  4968.7  355.23
  4978.3  351.10  4983.5  348.46  4987.5  346.22  4987.8  345.72  4991.3  345.72
  4991.5  346.22  4997.4  346.97  5000.0  346.97  5002.6  346.97  5010.3  349.35
  5017.8  354.11  5022.9  354.39  5031.0  354.66  5041.3  354.94  5051.6  355.42
  5058.4  356.63  5063.5  357.05  5066.9  357.05
#Mann=3,-1,0
  4930.2     0.1       0  4987.5    0.07       0  4991.5     0.1       0
Bank Sta=4987.5,4991.5
Exp/Cntr=0.3,0.1

Type RM Length L Ch R = 1,2130,251,251,251
BEGIN DESCRIPTION:
Caney Creek T 40 8.0
END DESCRIPTION:
XS GIS Cut Line= 3
      2738207.72      6775198.16      2738126.00      6775211.00
      2738026.02      6775260.99
#Sta/Elev= 27
  4917.8  359.47  4918.8  359.47  4921.2  359.47  4929.7  357.72  4939.8  354.89
  4949.9  354.03  4960.0  349.40  4966.7  343.23  4971.8  341.10  4978.3  340.94
  4978.5  340.44  4982.0  340.44  4982.3  340.94  4990.4  341.28  5003.3  341.28
  5008.9  342.33  5014.5  342.20  5022.9  342.99  5031.3  349.20  5036.9  344.59
  5045.2  350.75  5059.2  351.44  5067.6  351.47  5081.6  352.24  5098.3  352.63
  5109.5  353.65  5112.3  353.65
#Mann=4,-1,0
  4917.8    0.12       0  4918.8     0.1       0  4978.3    0.07       0
  4982.3     0.1       0
Bank Sta=4978.3,4982.3
Exp/Cntr=0.3,0.1

Type RM Length L Ch R = 1,1879,285,285,285
BEGIN DESCRIPTION:
Caney Creek T 40 7.0
END DESCRIPTION:
XS GIS Cut Line= 3
      2738176.00      6775061.00      2738076.00      6775011.00
      2737976.00      6774961.00
#Sta/Elev= 30
  4883.4  354.98  4886.2  354.98  4897.4  353.80  4905.8  353.29  4914.1  352.27
  4950.5  349.97  4958.9  349.63  4964.5  349.76  4972.8  348.82  4981.2  345.51
  4986.8  344.51  4992.4  341.76  4998.0  341.76  5001.6  340.45  5001.8  339.95
  5005.3  339.95  5005.6  340.45  5009.2  340.46  5017.6  341.49  5025.9  345.69
  5031.5  344.72  5039.9  347.10  5062.3  349.07  5070.7  350.87  5076.3  350.91
  5084.6  352.92  5093.0  354.45  5098.6  354.47  5104.2  355.58  5107.0  355.58
#Mann=3,-1,0
  4883.4    0.12       0  5001.6    0.07       0  5005.6    0.12       0
Bank Sta=5001.6,5005.6
Exp/Cntr=0.3,0.1

Type RM Length L Ch R = 1,1594,260,260,260
BEGIN DESCRIPTION:
Caney Creek T 40 6.0
END DESCRIPTION:
XS GIS Cut Line= 3
      2738426.03      6774911.02      2738176.00      6774761.00
      2738075.99      6774761.00
#Sta/Elev= 30
  4708.1  372.52  4711.1  372.52  4715.9  371.36  4731.5  369.87  4752.8  366.99
  4758.7  366.74  4766.4  365.48  4780.1  364.12  4817.0  359.59  4824.8  357.92
  4848.1  355.89  4859.7  354.32  4896.7  350.15  4918.1  347.98  4949.2  345.45
  4955.0  345.35  4964.7  344.42  4976.4  343.75  4986.1  343.50  4991.9  342.76
  4996.8  341.07  5017.7  341.00  5017.9  340.50  5021.4  340.50  5021.7  341.00
  5029.7  344.95  5039.7  347.44  5049.7  349.48  5069.7  352.03  5099.7  354.41
#Mann=3,-1,0
  4708.1    0.12       0  5017.7    0.07       0  5021.7    0.12       0
Bank Sta=5017.7,5021.7
Exp/Cntr=0.3,0.1

Type RM Length L Ch R = 1,1334,260,260,260
BEGIN DESCRIPTION:
Caney Creek T 40 5.0
END DESCRIPTION:
XS GIS Cut Line= 3
      2738475.99      6774860.99      2738326.00      6774561.00
      2738276.00      6774461.00
#Sta/Elev= 30
  4664.8  373.34  4687.1  371.29  4731.9  365.01  4768.2  361.12  4798.9  356.47
  4812.9  355.48  4829.7  353.28  4880.0  348.70  4896.8  346.64  4941.5  343.31
  4977.8  341.81  4986.2  339.26  4991.8  335.03  4997.4  335.56  5022.6  334.97
  5030.9  335.32  5034.5  334.12  5034.8  333.62  5038.3  333.62  5038.5  334.12
  5039.3  334.27  5044.9  335.31  5053.3  339.73  5058.9  336.33  5067.3  339.04
  5075.7  342.85  5081.3  343.47  5089.6  345.91  5109.2  350.37  5112.0  350.37
#Mann=4,-1,0
  4664.8    0.12       0  5034.5    0.07       0  5038.5    0.12       0
  5039.3     0.1       0
Bank Sta=5034.5,5038.5
Exp/Cntr=0.3,0.1

Type RM Length L Ch R = 1,1074,274,274,274
BEGIN DESCRIPTION:
Caney Creek T 40 4.0
END DESCRIPTION:
XS GIS Cut Line= 3
      2738526.00      6774711.02      2738526.00      6774461.00
      2738426.00      6774311.00
#Sta/Elev= 30
  4750.4  359.70  4760.4  359.33  4780.4  355.94  4850.4  348.46  4860.4  346.72
  4880.4  344.54  4920.4  338.93  4950.4  337.51  4970.4  337.59  4980.4  336.93
  4997.9  332.21  5003.4  332.21  5005.9  331.31  5006.2  330.81  5009.7  330.81
  5009.9  331.31  5023.0  335.61  5036.5  338.43  5050.0  340.25  5059.0  340.62
  5065.0  341.89  5072.5  341.67  5086.1  344.11  5101.1  345.32  5137.1  354.63
  5152.2  360.30  5167.2  363.11  5173.2  363.55  5177.7  365.47  5180.7  365.47
#Mann=3,-1,0
  4750.4    0.05       0  5005.9    0.03       0  5009.9     0.1       0
Bank Sta=5005.9,5009.9
Exp/Cntr=0.3,0.1

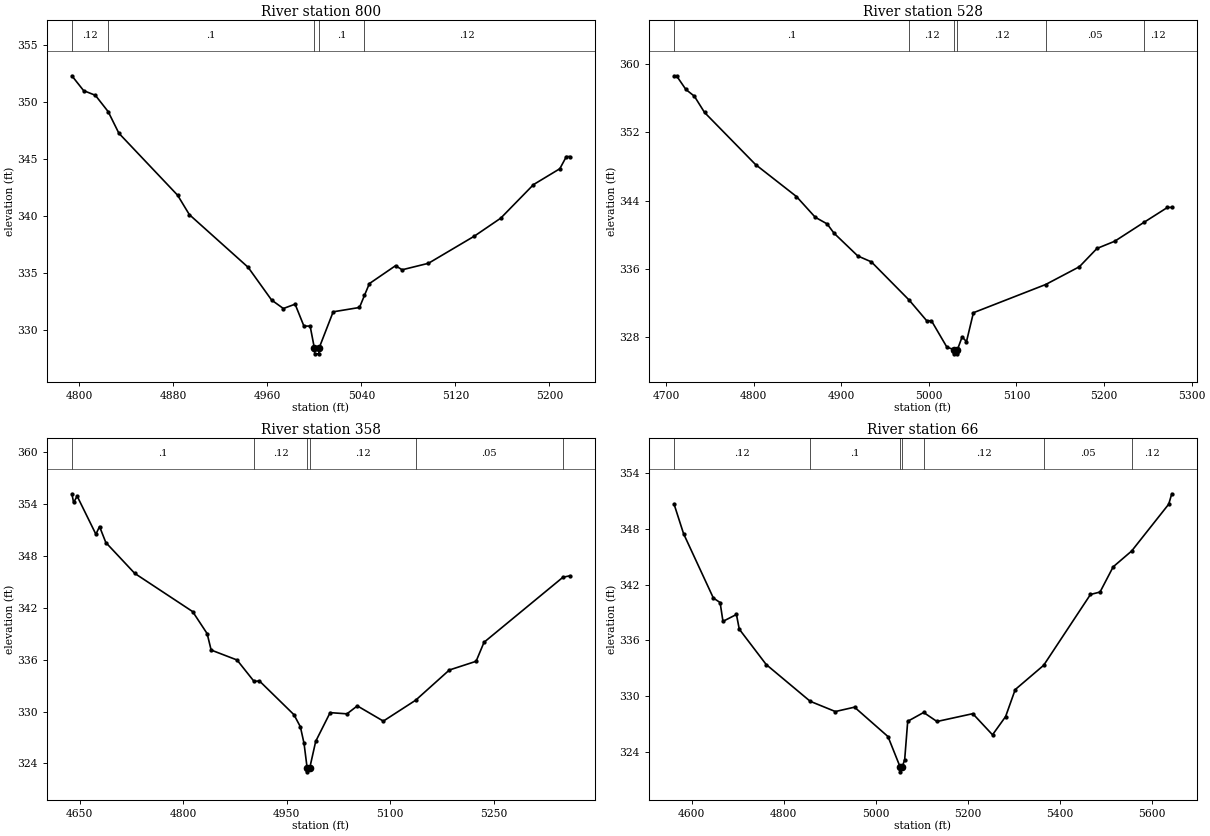
Type RM Length L Ch R = 1,800,272,272,272
BEGIN DESCRIPTION:
Caney Creek T 40 3.0
END DESCRIPTION:
XS GIS Cut Line= 3
      2738726.00      6774611.05      2738726.00      6774411.00
      2738826.02      6774210.96
#Sta/Elev= 30
  4793.6  352.27  4803.6  350.97  4813.6  350.56  4824.5  349.13  4833.6  347.24
  4883.6  341.81  4893.6  340.11  4943.6  335.50  4963.6  332.63  4973.6  331.89
  4983.6  332.27  4991.1  330.35  4996.4  330.35  5000.0  328.42  5000.3  327.92
  5003.8  327.92  5004.0  328.42  5016.0  331.60  5038.4  331.98  5042.6  333.03
  5046.8  334.07  5069.1  335.64  5074.7  335.28  5097.1  335.85  5136.2  338.23
  5158.6  339.80  5186.5  342.74  5208.9  344.13  5214.5  345.20  5217.3  345.20
#Mann=5,-1,0
  4793.6    0.12       0  4824.5     0.1       0  5000.0    0.07       0
  5004.0     0.1       0  5042.6    0.12       0
Bank Sta=5000,5004
Exp/Cntr=0.3,0.1

Type RM Length L Ch R = 1,528,170,170,170
BEGIN DESCRIPTION:
Caney Creek T 40 2.0
END DESCRIPTION:
XS GIS Cut Line= 3
      2738826.03      6774710.96      2738976.00      6774461.00
      2738941.06      6774186.31
#Sta/Elev= 30
  4708.9  358.60  4711.8  358.60  4722.5  357.00  4732.2  356.21  4743.8  354.31
  4802.1  348.21  4848.8  344.47  4870.2  342.05  4883.8  341.27  4891.6  340.19
  4918.8  337.52  4934.3  336.83  4977.6  332.34  4997.5  329.94  5002.9  329.94
  5020.6  326.84  5028.6  326.57  5028.9  326.07  5032.4  326.07  5032.6  326.57
  5037.9  328.05  5042.9  327.50  5050.8  330.88  5133.3  334.18  5171.8  336.26
  5191.9  338.40  5212.1  339.24  5245.5  341.45  5272.4  343.20  5277.3  343.20
#Mann=6,-1,0
  4708.9     0.1       0  4977.6    0.12       0  5028.6    0.07       0
  5032.6    0.12       0  5133.3    0.05       0  5245.5    0.12       0
Bank Sta=5028.6,5032.6
Exp/Cntr=0.3,0.1

Type RM Length L Ch R = 1,358,292,292,292
BEGIN DESCRIPTION:
Mapping XS a908878a
END DESCRIPTION:
XS GIS Cut Line= 3
      2739010.10      6774797.88      2739129.47      6774419.71
      2738981.79      6774130.50
#Sta/Elev= 30
  4638.9  355.19  4641.4  354.19  4646.6  354.91  4673.7  350.51  4679.0  351.40
  4688.1  349.55  4730.0  345.98  4813.9  341.56  4834.9  339.01  4840.7  337.11
  4878.2  335.96  4902.9  333.48  4910.6  333.54  4960.7  329.63  4970.0  328.23
  4975.3  326.31  4979.7  323.52  4979.9  323.02  4983.7  323.52  4992.2  326.55
  5013.1  329.87  5037.5  329.73  5052.5  330.65  5090.2  328.89  5137.1  331.31
  5185.8  334.80  5224.6  335.81  5236.1  338.01  5350.4  345.53  5360.2  345.70
#Mann=6,-1,0
  4638.9     0.1       0  4902.9    0.12       0  4979.7    0.07       0
  4983.7    0.12       0  5137.1    0.05       0  5350.4    0.12       0
Bank Sta=4979.7,4983.7
Exp/Cntr=0.3,0.1

Type RM Length L Ch R = 1,66,0,0,0
BEGIN DESCRIPTION:
Caney Creek T 40 1.0
END DESCRIPTION:
XS GIS Cut Line= 3
      2739100.49      6774865.41      2739366.94      6774502.70
      2738957.14      6774020.34
#Sta/Elev= 30
  4561.1  350.67  4582.0  347.46  4646.8  340.55  4661.5  340.06  4667.7  338.04
  4697.0  338.78  4703.2  337.20  4761.8  333.40  4857.5  329.45  4912.2  328.35
  4953.9  328.82  5026.7  325.66  5053.3  322.37  5053.5  321.87  5057.3  322.37
  5063.0  323.16  5069.6  327.30  5104.3  328.25  5133.3  327.28  5211.2  328.12
  5254.1  325.85  5282.6  327.81  5303.5  330.71  5365.4  333.32  5467.2  340.93
  5488.0  341.19  5516.6  343.90  5556.8  345.60  5637.4  350.63  5644.1  351.75
#Mann=7,-1,0
  4561.1    0.12       0  4857.5     0.1       0  5053.3    0.07       0
  5057.3     0.1       0  5104.3    0.12       0  5365.4    0.05       0
  5556.8    0.12       0
Bank Sta=5053.3,5057.3
Exp/Cntr=0.3,0.1

Chan Stop Cuts=-1