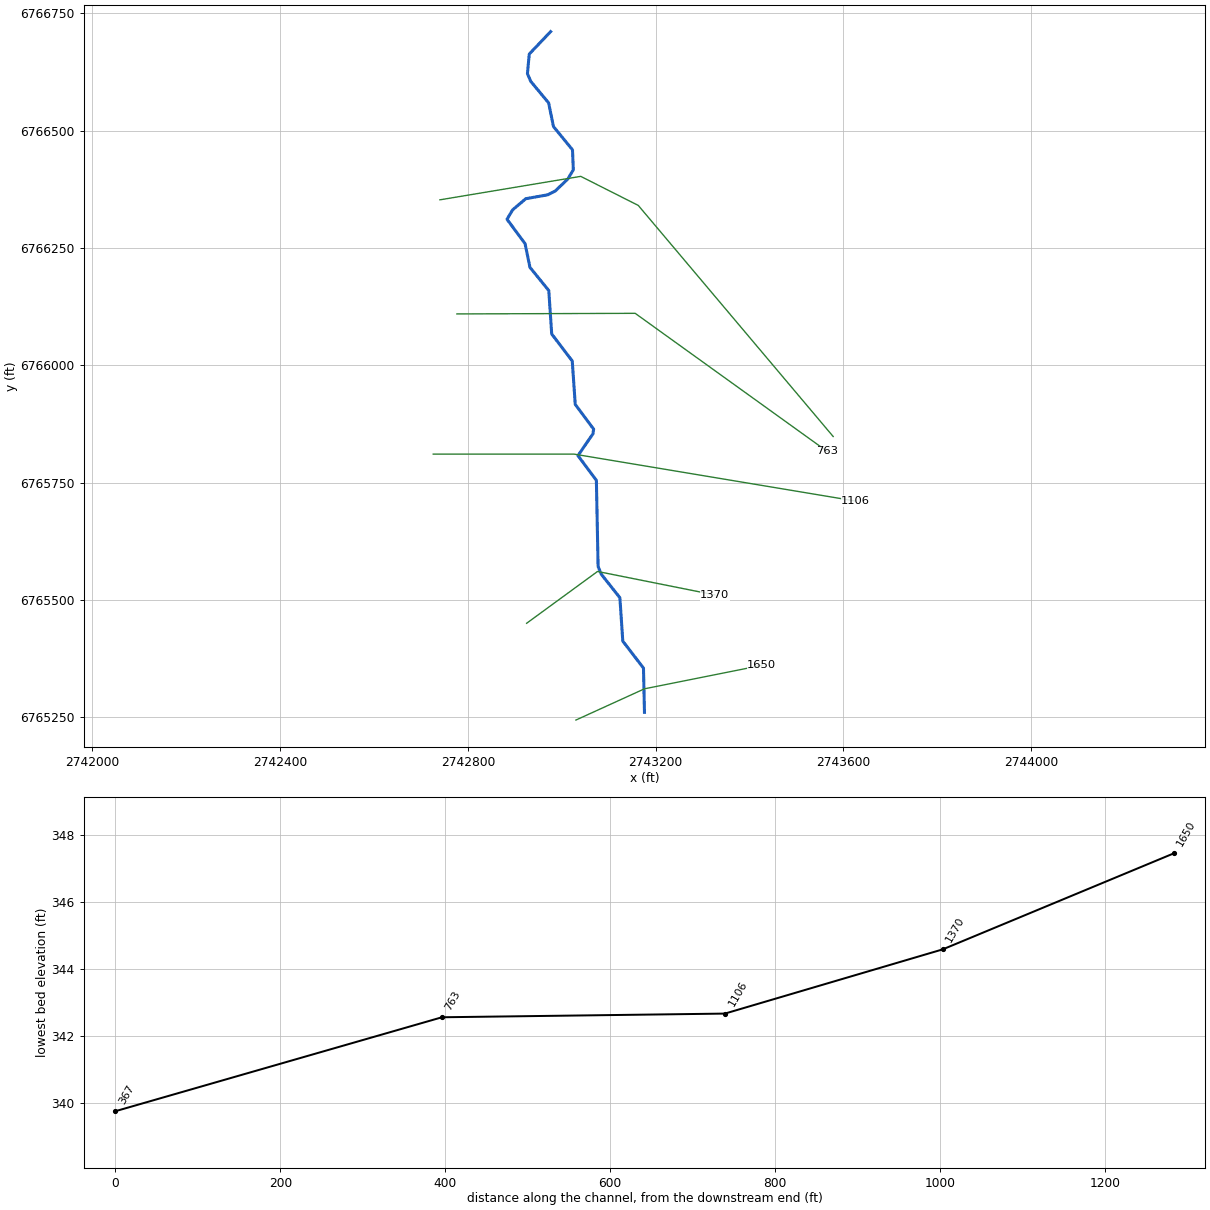
--- Caney Creek T 5.prj (project) ---

Proj Title=Caney Creek T 5 Base Level Engineering
Current Plan=p01
Default Exp/Contr=0.3,0.1
English Units
Geom File=g01
Flow File=f01
Plan File=p01
BEGIN DESCRIPTION:
Caney Creek T 5
END DESCRIPTION:

--- Caney Creek T 5.p01 (plan) ---

Plan Title=Multiple Run
Short Identifier=Multiple
Geom File=g01
Flow File=f01
Subcritical Flow
K Sum by GR= 0
Std Step Tol= 0.01
Critical Tol= 0.01
Num of Std Step Trials= 20
Max Error Tol= 0.3
Flow Tol Ratio= 0.001
Split Flow NTrial= 30
Split Flow Tol= 0.02
Split Flow Ratio= 0.02
Log Output Level= 0
Friction Slope Method= 1
Unsteady Friction Slope Method= 2
Unsteady Bridges Friction Slope Method= 1
Parabolic Critical Depth
Global Vel Dist=  1 , 1 , 1
Global Log Level= 0
CheckData=True
Encroach Param= -1, 0, 0, 0
BEGIN DESCRIPTION:
Multiple Run
END DESCRIPTION:

--- Caney Creek T 5.f01 (steady flow) ---

Flow Title=Multiple
Number of Profiles=7
Profile Names=10-year,25-year,50-year,1pct_min,100-year,1pct_plu,500-year
River Rch & RM= Caney Creek T 5,Reach-1,1650
     274     355     418     246     491     980     676
Boundary for River Rch & Prof#=Caney Creek T 5,Reach-1,1
Up Type=0
Dn Type=3
Dn Slope=0.005
Boundary for River Rch & Prof#=Caney Creek T 5,Reach-1,2
Up Type=0
Dn Type=3
Dn Slope=0.005
Boundary for River Rch & Prof#=Caney Creek T 5,Reach-1,3
Up Type=0
Dn Type=3
Dn Slope=0.005
Boundary for River Rch & Prof#=Caney Creek T 5,Reach-1,4
Up Type=0
Dn Type=3
Dn Slope=0.005
Boundary for River Rch & Prof#=Caney Creek T 5,Reach-1,5
Up Type=0
Dn Type=3
Dn Slope=0.005
Boundary for River Rch & Prof#=Caney Creek T 5,Reach-1,6
Up Type=0
Dn Type=3
Dn Slope=0.005
Boundary for River Rch & Prof#=Caney Creek T 5,Reach-1,7
Up Type=0
Dn Type=3
Dn Slope=0.005

--- Caney Creek T 5.g01 (geometry) ---

Geom Title=Existing Conditions

River Reach=Caney Creek T 5,Reach-1
Reach XY= 30
      2743176.00      6765261.00      2743173.90      6765355.13
      2743129.83      6765412.58      2743123.65      6765505.02
      2743084.14      6765554.94      2743077.22      6765571.50
      2743073.55      6765755.15      2743034.28      6765807.78
      2743066.23      6765854.27      2743067.72      6765864.22
      2743028.54      6765916.89      2743022.15      6766009.40
      2742978.35      6766066.97      2742972.17      6766159.42
      2742932.09      6766208.83      2742921.56      6766259.38
      2742883.20      6766311.30      2742895.13      6766331.41
      2742923.18      6766355.14      2742970.10      6766363.46
      2742986.08      6766371.65      2743013.02      6766397.43
      2743024.46      6766416.85      2743022.70      6766459.24
      2742982.15      6766508.80      2742971.80      6766559.28
      2742933.78      6766605.03      2742926.66      6766621.62
      2742930.60      6766663.36      2742976.00      6766711.00

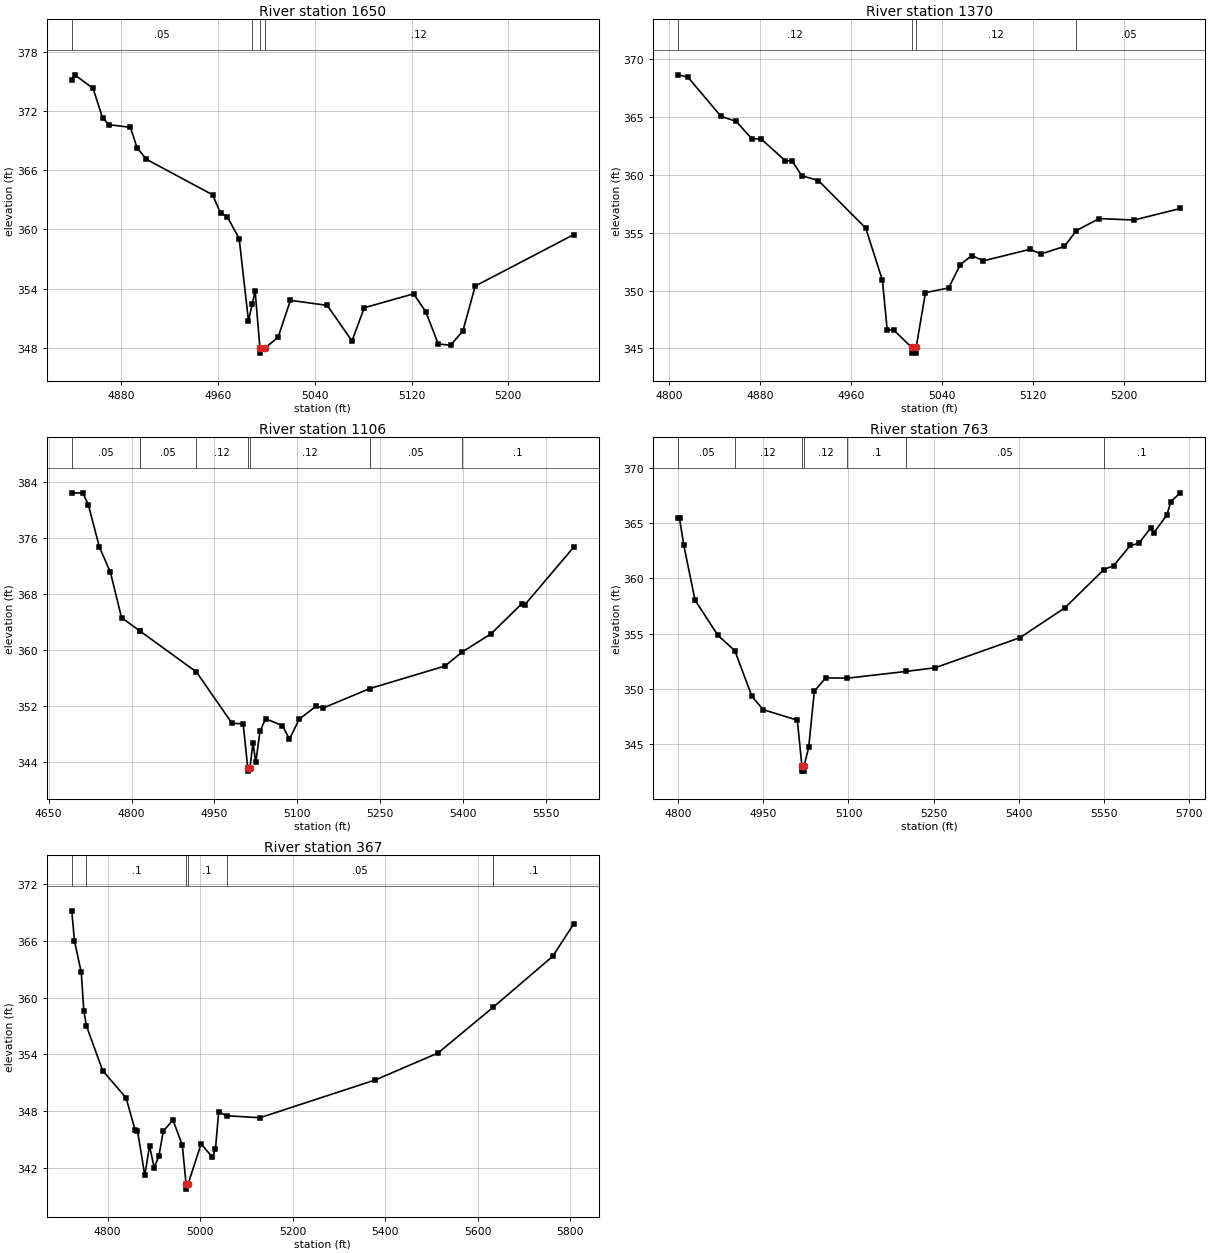
Type RM Length L Ch R = 1,1650,280,280,280
BEGIN DESCRIPTION:
Caney Creek T 5 4.0
END DESCRIPTION:
XS GIS Cut Line= 3
      2743029.99      6765244.46      2743176.00      6765311.00
      2743425.99      6765361.00
#Sta/Elev= 30
  4838.9  375.14  4841.3  375.66  4856.5  374.29  4864.4  371.28  4869.9  370.60
  4887.4  370.34  4892.9  368.28  4900.5  367.11  4955.4  363.50  4962.0  361.64
  4967.5  361.29  4977.4  359.06  4985.1  350.72  4988.3  352.48  4990.6  353.74
  4994.6  347.95  4994.9  347.45  4998.6  347.95  5009.6  349.06  5019.8  352.80
  5050.3  352.29  5070.7  348.68  5080.9  352.05  5121.7  353.46  5131.9  351.62
  5142.1  348.38  5152.3  348.25  5162.5  349.70  5172.7  354.25  5254.3  359.47
#Mann=4,-1,0
  4838.9    0.05       0  4988.3    0.12       0  4994.6    0.07       0
  4998.6    0.12       0
Bank Sta=4994.6,4998.6
Exp/Cntr=0.3,0.1

Type RM Length L Ch R = 1,1370,264,264,264
BEGIN DESCRIPTION:
Caney Creek T 5 3.0
END DESCRIPTION:
XS GIS Cut Line= 3
      2742924.93      6765450.58      2743076.00      6765561.00
      2743326.03      6765510.99
#Sta/Elev= 30
  4807.7  368.67  4816.1  368.48  4845.4  365.07  4858.6  364.65  4872.4  363.15
  4880.9  363.10  4901.8  361.25  4908.1  361.20  4916.4  359.94  4931.1  359.52
  4972.8  355.40  4987.5  350.88  4991.7  346.58  4997.4  346.58  5013.2  345.08
  5013.5  344.58  5017.0  344.58  5017.2  345.08  5025.4  349.82  5045.8  350.22
  5056.0  352.23  5066.2  353.03  5076.4  352.57  5117.2  353.56  5127.4  353.17
  5147.8  353.82  5158.3  355.19  5178.4  356.23  5209.0  356.10  5249.8  357.10
#Mann=4,-1,0
  4807.7    0.12       0  5013.2    0.07       0  5017.2    0.12       0
  5158.3    0.05       0
Bank Sta=5013.2,5017.2
Exp/Cntr=0.3,0.1

Type RM Length L Ch R = 1,1106,343,343,343
BEGIN DESCRIPTION:
Caney Creek T 5 2.0
END DESCRIPTION:
XS GIS Cut Line= 3
      2742726.01      6765811.00      2743026.00      6765811.00
      2743626.04      6765710.99
#Sta/Elev= 30
  4691.9  382.49  4711.9  382.46  4721.9  380.78  4741.9  374.72  4761.9  371.09
  4781.9  364.64  4815.0  362.72  4815.3  362.71  4917.5  356.85  4981.9  349.49
  5002.0  349.45  5010.2  343.16  5010.4  342.66  5014.2  343.16  5019.8  346.69
  5024.8  343.90  5032.4  348.38  5042.6  350.15  5073.0  349.18  5085.7  347.24
  5103.4  350.10  5133.8  351.95  5146.5  351.69  5230.8  354.47  5367.0  357.70
  5398.2  359.71  5450.6  362.32  5506.4  366.65  5511.5  366.46  5600.2  374.74
#Mann=8,-1,0
  4691.9    0.05       0  4815.0    0.12       0  4815.3    0.05       0
  4917.5    0.12       0  5010.2    0.07       0  5014.2    0.12       0
  5230.8    0.05       0  5398.2     0.1       0
Bank Sta=5010.2,5014.2
Exp/Cntr=0.3,0.1

Type RM Length L Ch R = 1,763,396,396,396
BEGIN DESCRIPTION:
Mapping XS 6429fb27
END DESCRIPTION:
XS GIS Cut Line= 3
      2742776.40      6766109.67      2743156.24      6766110.93
      2743565.28      6765816.72
#Sta/Elev= 30
  4800.4  365.41  4802.7  365.41  4810.0  363.03  4830.0  358.02  4870.0  354.85
  4900.1  353.44  4930.0  349.32  4950.0  348.11  5010.0  347.16  5018.0  343.05
  5018.3  342.55  5021.8  342.55  5022.0  343.05  5030.0  344.69  5040.0  349.79
  5060.0  350.99  5098.0  350.96  5201.2  351.57  5252.4  351.90  5401.7  354.62
  5480.8  357.32  5549.7  360.79  5566.7  361.14  5596.2  362.97  5610.9  363.15
  5631.8  364.54  5637.9  364.14  5660.4  365.72  5667.4  366.92  5684.1  367.73
#Mann=7,-1,0
  4800.4    0.05       0  4900.1    0.12       0  5018.0    0.07       0
  5022.0    0.12       0  5098.0     0.1       0  5201.2    0.05       0
  5549.7     0.1       0
Bank Sta=5018,5022
Exp/Cntr=0.3,0.1

Type RM Length L Ch R = 1,367,0,0,0
BEGIN DESCRIPTION:
Caney Creek T 5 1.0
END DESCRIPTION:
XS GIS Cut Line= 4
      2742740.21      6766352.73      2743040.22      6766402.73
      2743162.83      6766340.81      2743578.01      6765848.51
#Sta/Elev= 30
  4722.7  369.17  4728.6  365.97  4743.2  362.66  4748.8  358.57  4754.5  356.99
  4789.4  352.28  4840.1  349.39  4859.8  345.97  4864.8  345.92  4880.6  341.19
  4890.8  344.34  4900.9  341.99  4911.0  343.24  4920.6  345.87  4941.5  347.04
  4961.7  344.39  4969.9  340.24  4970.1  339.74  4973.9  340.24  5002.3  344.51
  5026.8  343.12  5033.3  343.97  5040.3  347.91  5057.3  347.50  5129.5  347.29
  5379.2  351.29  5514.4  354.13  5633.2  358.95  5762.7  364.37  5808.2  367.81
#Mann=6,-1,0
  4722.7    0.05       0  4754.5     0.1       0  4969.9    0.07       0
  4973.9     0.1       0  5057.3    0.05       0  5633.2     0.1       0
Bank Sta=4969.9,4973.9
Exp/Cntr=0.3,0.1

Chan Stop Cuts=-1