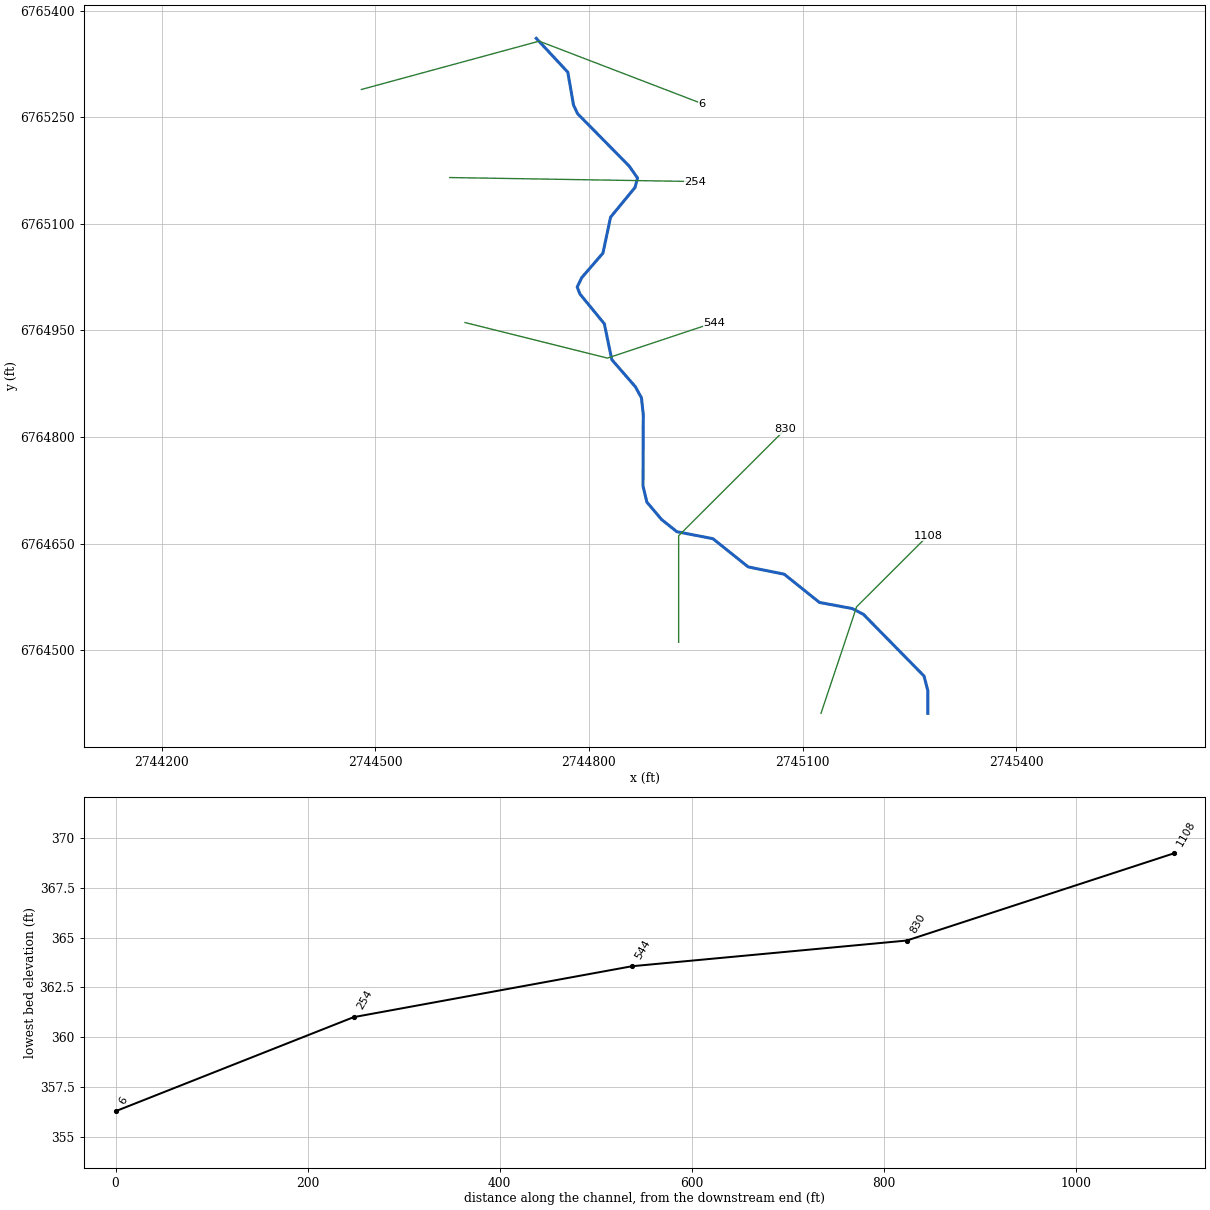
--- Caney Creek T 6.prj (project) ---

Proj Title=Caney Creek T 6 Base Level Engineering
Current Plan=p01
Default Exp/Contr=0.3,0.1
English Units
Geom File=g01
Flow File=f01
Plan File=p01
BEGIN DESCRIPTION:
Caney Creek T 6
END DESCRIPTION:

--- Caney Creek T 6.p01 (plan) ---

Plan Title=Multiple Run
Short Identifier=Multiple
Geom File=g01
Flow File=f01
Subcritical Flow
K Sum by GR= 0
Std Step Tol= 0.01
Critical Tol= 0.01
Num of Std Step Trials= 20
Max Error Tol= 0.3
Flow Tol Ratio= 0.001
Split Flow NTrial= 30
Split Flow Tol= 0.02
Split Flow Ratio= 0.02
Log Output Level= 0
Friction Slope Method= 1
Unsteady Friction Slope Method= 2
Unsteady Bridges Friction Slope Method= 1
Parabolic Critical Depth
Global Vel Dist=  1 , 1 , 1
Global Log Level= 0
CheckData=True
Encroach Param= -1, 0, 0, 0
BEGIN DESCRIPTION:
Multiple Run
END DESCRIPTION:

--- Caney Creek T 6.f01 (steady flow) ---

Flow Title=Multiple
Number of Profiles=7
Profile Names=10-year,25-year,50-year,1pct_min,100-year,1pct_plu,500-year
River Rch & RM= Caney Creek T 6,Reach-1,1108
     136     168     191     109     218     435     282
River Rch & RM= Caney Creek T 6,Reach-1,6
     339     443     527     312     622    1242     869
Boundary for River Rch & Prof#=Caney Creek T 6,Reach-1,1
Up Type=0
Dn Type=3
Dn Slope=0.005
Boundary for River Rch & Prof#=Caney Creek T 6,Reach-1,2
Up Type=0
Dn Type=3
Dn Slope=0.005
Boundary for River Rch & Prof#=Caney Creek T 6,Reach-1,3
Up Type=0
Dn Type=3
Dn Slope=0.005
Boundary for River Rch & Prof#=Caney Creek T 6,Reach-1,4
Up Type=0
Dn Type=3
Dn Slope=0.005
Boundary for River Rch & Prof#=Caney Creek T 6,Reach-1,5
Up Type=0
Dn Type=3
Dn Slope=0.005
Boundary for River Rch & Prof#=Caney Creek T 6,Reach-1,6
Up Type=0
Dn Type=3
Dn Slope=0.005
Boundary for River Rch & Prof#=Caney Creek T 6,Reach-1,7
Up Type=0
Dn Type=3
Dn Slope=0.005

--- Caney Creek T 6.g01 (geometry) ---

Geom Title=Existing Conditions

River Reach=Caney Creek T 6,Reach-1
Reach XY= 30
      2745276.00      6764411.00      2745276.08      6764442.89
      2745270.70      6764463.54      2745185.70      6764550.25
      2745169.97      6764558.51      2745123.81      6764567.10
      2745074.28      6764606.84      2745023.80      6764617.08
      2744974.23      6764656.80      2744923.42      6764666.71
      2744902.03      6764683.80      2744881.36      6764708.30
      2744875.93      6764730.89      2744876.33      6764831.14
      2744873.75      6764855.07      2744865.20      6764870.67
      2744832.09      6764908.83      2744821.58      6764959.36
      2744787.40      6765001.08      2744783.50      6765011.00
      2744789.87      6765024.23      2744819.64      6765058.72
      2744830.40      6765109.35      2744864.72      6765151.13
      2744868.22      6765164.40      2744856.68      6765181.01
      2744784.09      6765254.91      2744778.36      6765266.97
      2744770.30      6765313.35      2744726.00      6765361.00

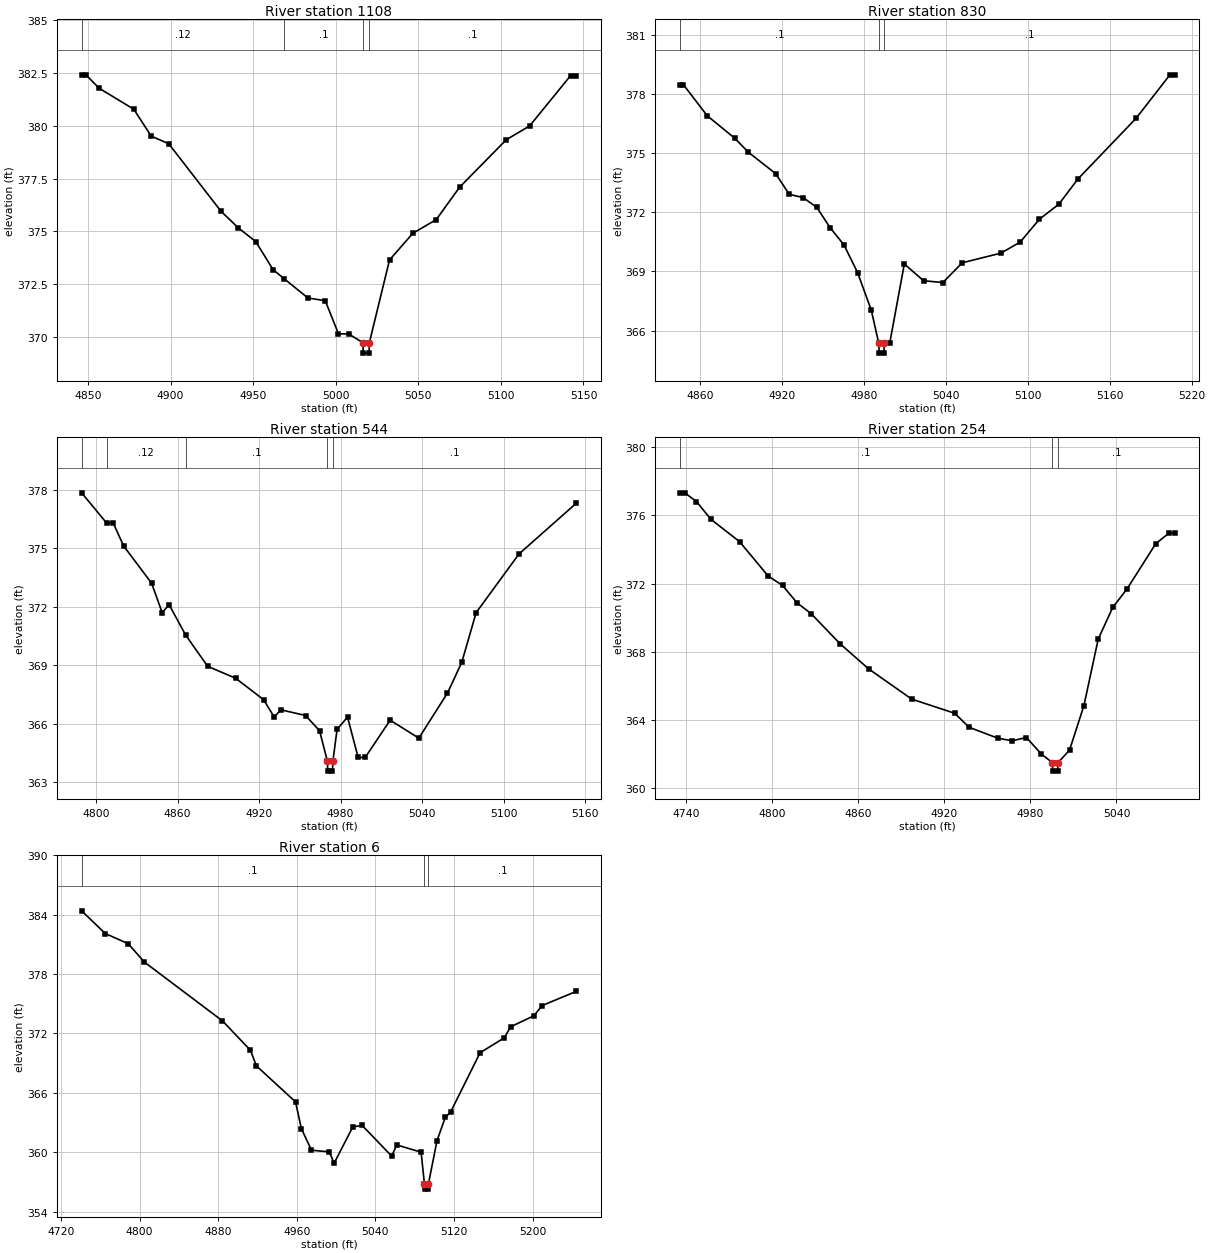
Type RM Length L Ch R = 1,1108,278,278,278
BEGIN DESCRIPTION:
Caney Creek T 6 4.0
END DESCRIPTION:
XS GIS Cut Line= 3
      2745126.01      6764411.03      2745176.00      6764561.00
      2745275.99      6764660.99
#Sta/Elev= 27
  4846.2  382.41  4848.8  382.41  4856.7  381.78  4877.8  380.78  4888.3  379.51
  4898.9  379.15  4930.5  375.96  4941.0  375.17  4951.6  374.52  4962.1  373.19
  4968.8  372.76  4983.2  371.85  4993.7  371.72  5001.7  370.15  5007.8  370.15
  5016.4  369.74  5016.7  369.24  5020.2  369.24  5020.4  369.74  5032.6  373.65
  5046.7  374.91  5060.9  375.56  5075.0  377.09  5103.3  379.34  5117.4  379.99
  5142.2  382.37  5145.7  382.37
#Mann=4,-1,0
  4846.2    0.12       0  4968.8     0.1       0  5016.4    0.07       0
  5020.4     0.1       0
Bank Sta=5016.4,5020.4
Exp/Cntr=0.3,0.1

Type RM Length L Ch R = 1,830,286,286,286
BEGIN DESCRIPTION:
Caney Creek T 6 3.0
END DESCRIPTION:
XS GIS Cut Line= 3
      2744926.00      6764510.99      2744926.00      6764661.00
      2745075.97      6764810.97
#Sta/Elev= 30
  4845.4  378.47  4847.9  378.47  4865.4  376.89  4885.4  375.76  4895.4  375.05
  4915.4  373.96  4925.4  372.91  4935.4  372.75  4945.4  372.26  4955.4  371.21
  4965.4  370.35  4975.4  368.94  4985.4  367.04  4990.9  365.36  4991.2  364.86
  4994.7  364.86  4994.9  365.36  4998.9  365.36  5009.6  369.38  5023.7  368.53
  5037.8  368.44  5052.0  369.44  5080.3  369.93  5094.4  370.49  5108.5  371.65
  5122.7  372.41  5136.8  373.70  5179.3  376.77  5204.0  378.97  5207.5  378.97
#Mann=3,-1,0
  4845.4     0.1       0  4990.9    0.07       0  4994.9     0.1       0
Bank Sta=4990.9,4994.9
Exp/Cntr=0.3,0.1

Type RM Length L Ch R = 1,544,290,290,290
BEGIN DESCRIPTION:
Caney Creek T 6 2.0
END DESCRIPTION:
XS GIS Cut Line= 3
      2744626.00      6764961.00      2744826.00      6764911.00
      2744976.03      6764961.01
#Sta/Elev= 30
  4789.3  377.83  4807.7  376.28  4812.5  376.29  4820.2  375.11  4840.8  373.20
  4848.6  371.69  4853.7  372.10  4865.9  370.54  4882.1  368.94  4902.7  368.33
  4923.3  367.23  4931.0  366.35  4936.2  366.71  4954.2  366.42  4964.5  365.64
  4970.3  364.07  4970.5  363.57  4974.0  363.57  4974.3  364.07  4977.4  365.71
  4985.1  366.34  4992.9  364.27  4998.1  364.27  5016.5  366.18  5037.6  365.26
  5058.7  367.57  5069.2  369.14  5079.8  371.69  5111.4  374.70  5153.6  377.30
#Mann=5,-1,0
  4789.3     0.1       0  4807.7    0.12       0  4865.9     0.1       0
  4970.3    0.07       0  4974.3     0.1       0
Bank Sta=4970.3,4974.3
Exp/Cntr=0.3,0.1

Type RM Length L Ch R = 1,254,248,248,248
BEGIN DESCRIPTION:
Mapping XS 95c22baa
END DESCRIPTION:
XS GIS Cut Line= 2
      2744604.49      6765165.09      2744949.24      6765159.47
#Sta/Elev= 30
  4735.8  377.32  4739.1  377.32  4747.3  376.81  4757.3  375.77  4777.3  374.46
  4797.3  372.44  4807.3  371.89  4817.3  370.88  4827.3  370.23  4847.3  368.48
  4867.3  367.00  4897.3  365.23  4927.3  364.40  4937.3  363.58  4957.3  362.94
  4967.3  362.79  4977.3  362.98  4987.3  362.04  4995.3  361.51  4995.6  361.01
  4999.1  361.01  4999.3  361.51  5007.3  362.24  5017.3  364.84  5027.3  368.75
  5037.4  370.60  5047.4  371.69  5067.4  374.34  5076.5  374.95  5080.6  374.95
#Mann=3,-1,0
  4735.8     0.1       0  4995.3    0.07       0  4999.3     0.1       0
Bank Sta=4995.3,4999.3
Exp/Cntr=0.3,0.1

Type RM Length L Ch R = 1,6,0,0,0
BEGIN DESCRIPTION:
Caney Creek T 6 1.0
END DESCRIPTION:
XS GIS Cut Line= 3
      2744480.28      6765289.00      2744730.08      6765357.03
      2744958.41      6765269.29
#Sta/Elev= 30
  4741.1  384.38  4765.1  382.09  4788.5  381.06  4804.9  379.21  4884.4  373.27
  4912.9  370.30  4919.0  368.72  4958.8  365.09  4964.7  362.40  4975.0  360.21
  4993.3  360.04  4998.0  358.88  5017.1  362.57  5026.6  362.71  5056.6  359.62
  5061.9  360.74  5086.6  360.01  5090.0  356.78  5090.3  356.28  5093.8  356.28
  5094.0  356.78  5102.8  361.18  5111.2  363.52  5116.6  364.06  5146.6  370.05
  5171.3  371.56  5177.7  372.67  5201.3  373.78  5209.9  374.82  5244.6  376.25
#Mann=3,-1,0
  4741.1     0.1       0  5090.0    0.07       0  5094.0     0.1       0
Bank Sta=5090,5094
Exp/Cntr=0.3,0.1

Chan Stop Cuts=-1