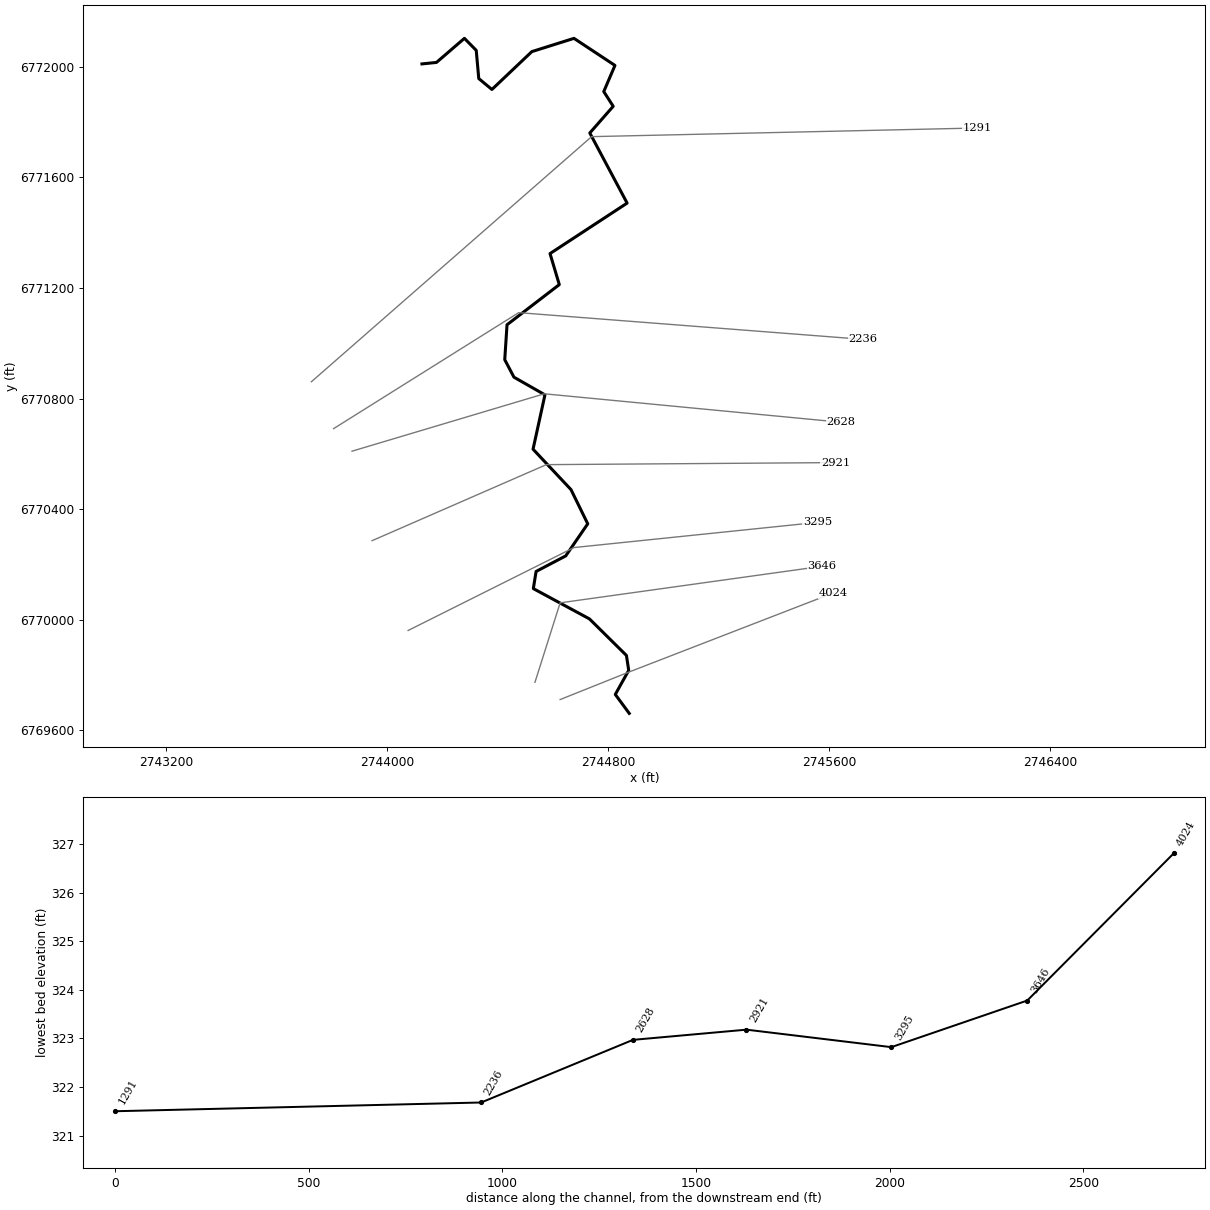
--- Caney Creek T 7.prj (project) ---

Proj Title=Caney Creek T 7 Base Level Engineering
Current Plan=p01
Default Exp/Contr=0.3,0.1
English Units
Geom File=g01
Flow File=f01
Plan File=p01
BEGIN DESCRIPTION:
Caney Creek T 7
END DESCRIPTION:

--- Caney Creek T 7.p01 (plan) ---

Plan Title=Multiple Run
Short Identifier=Multiple
Geom File=g01
Flow File=f01
Subcritical Flow
K Sum by GR= 0
Std Step Tol= 0.01
Critical Tol= 0.01
Num of Std Step Trials= 20
Max Error Tol= 0.3
Flow Tol Ratio= 0.001
Split Flow NTrial= 30
Split Flow Tol= 0.02
Split Flow Ratio= 0.02
Log Output Level= 0
Friction Slope Method= 1
Unsteady Friction Slope Method= 2
Unsteady Bridges Friction Slope Method= 1
Parabolic Critical Depth
Global Vel Dist=  1 , 1 , 1
Global Log Level= 0
CheckData=True
Encroach Param= -1, 0, 0, 0
BEGIN DESCRIPTION:
Multiple Run
END DESCRIPTION:

--- Caney Creek T 7.f01 (steady flow) ---

Flow Title=Multiple
Number of Profiles=7
Profile Names=10-year,25-year,50-year,1pct_min,100-year,1pct_plu,500-year
River Rch & RM= Caney Creek T 7,Reach-1,4024
     458     611     735     440     878    1752    1255
Boundary for River Rch & Prof#=Caney Creek T 7,Reach-1,1
Up Type=0
Dn Type=3
Dn Slope=0.005
Boundary for River Rch & Prof#=Caney Creek T 7,Reach-1,2
Up Type=0
Dn Type=3
Dn Slope=0.005
Boundary for River Rch & Prof#=Caney Creek T 7,Reach-1,3
Up Type=0
Dn Type=3
Dn Slope=0.005
Boundary for River Rch & Prof#=Caney Creek T 7,Reach-1,4
Up Type=0
Dn Type=3
Dn Slope=0.005
Boundary for River Rch & Prof#=Caney Creek T 7,Reach-1,5
Up Type=0
Dn Type=3
Dn Slope=0.005
Boundary for River Rch & Prof#=Caney Creek T 7,Reach-1,6
Up Type=0
Dn Type=3
Dn Slope=0.005
Boundary for River Rch & Prof#=Caney Creek T 7,Reach-1,7
Up Type=0
Dn Type=3
Dn Slope=0.005

--- Caney Creek T 7.g01 (geometry) ---

Geom Title=Existing Conditions

River Reach=Caney Creek T 7,Reach-1
Reach XY= 30
      2744876.00      6769661.00      2744825.54      6769729.46
      2744874.09      6769816.72      2744865.81      6769870.68
      2744732.06      6770002.86      2744528.99      6770112.46
      2744538.96      6770174.55      2744646.13      6770230.78
      2744725.83      6770346.88      2744665.24      6770470.68
      2744527.96      6770616.89      2744571.01      6770813.55
      2744458.87      6770877.46      2744425.51      6770940.77
      2744433.80      6771067.21      2744622.93      6771212.43
      2744589.40      6771324.73      2744868.33      6771507.34
      2744733.31      6771761.09      2744817.98      6771857.66
      2744783.84      6771910.91      2744824.31      6772005.54
      2744676.01      6772103.47      2744523.57      6772055.48
      2744379.13      6771918.50      2744331.52      6771958.01
      2744322.39      6772059.99      2744279.62      6772103.54
      2744178.52      6772016.35      2744126.00      6772011.00

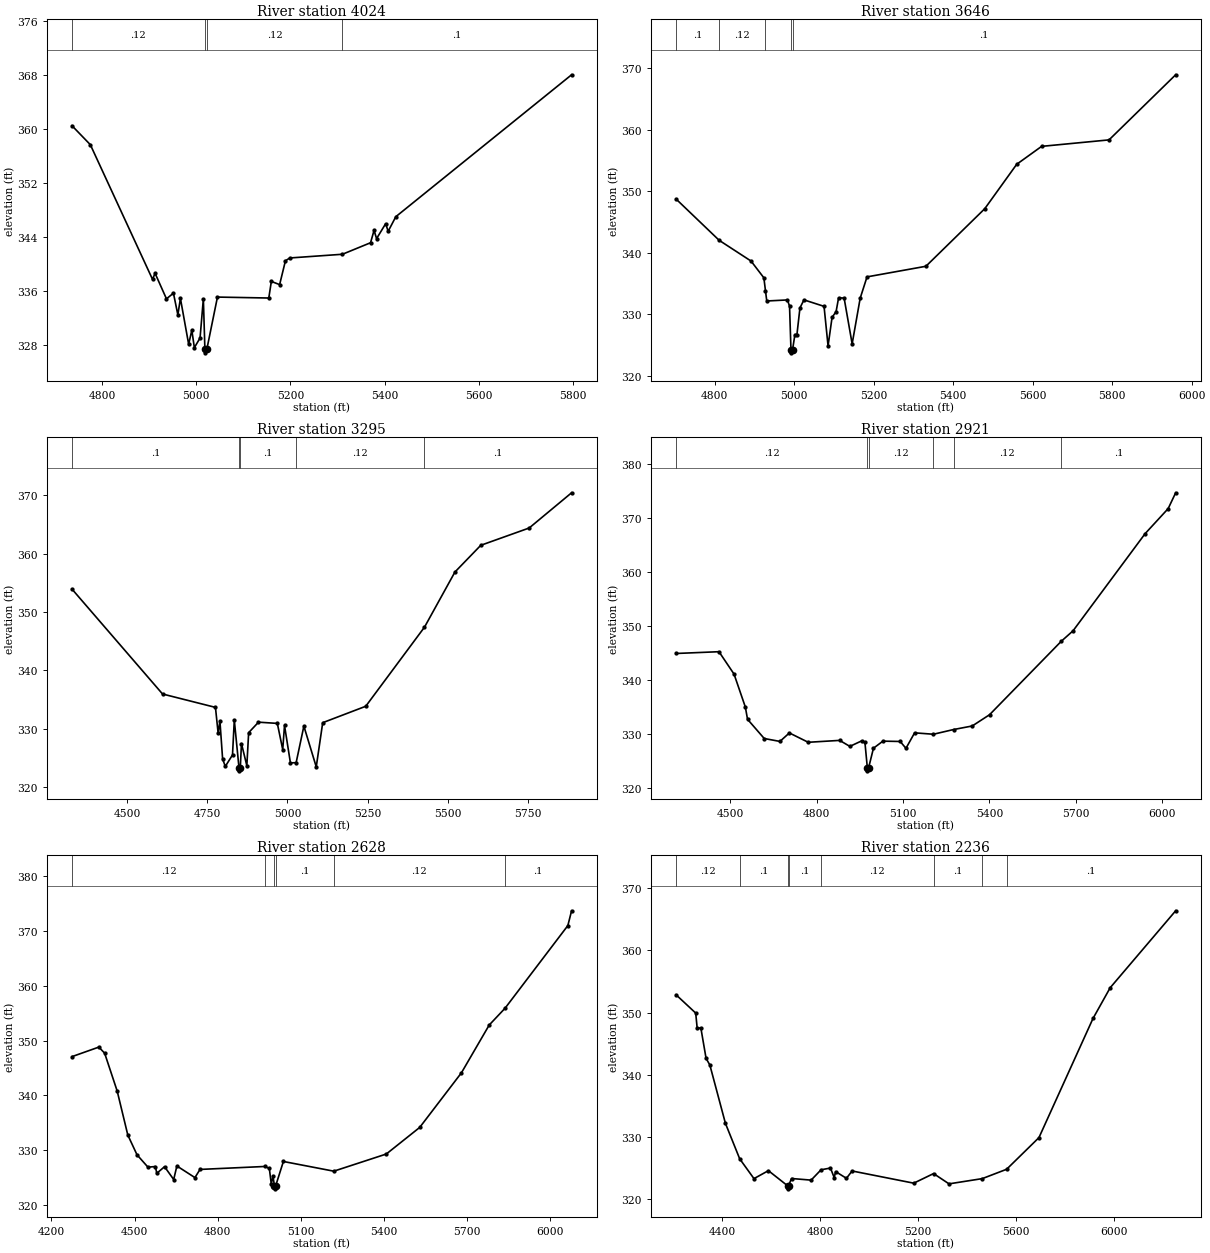
Type RM Length L Ch R = 1,4024,378,378,378
BEGIN DESCRIPTION:
Caney Creek T 7 7.0
END DESCRIPTION:
XS GIS Cut Line= 3
      2744626.01      6769711.00      2744876.00      6769811.00
      2745613.92      6770096.58
#Sta/Elev= 30
  4736.5  360.50  4775.5  357.68  4907.5  337.71  4912.9  338.61  4937.1  334.82
  4951.9  335.66  4961.3  332.44  4966.7  334.89  4984.2  328.08  4990.9  330.17
  4996.3  327.58  5008.4  329.01  5015.4  334.82  5018.7  327.31  5019.0  326.81
  5022.7  327.31  5045.3  335.08  5154.3  334.94  5159.7  337.40  5177.3  336.93
  5189.6  340.46  5198.8  340.88  5310.6  341.43  5370.3  343.14  5377.7  344.97
  5383.1  343.75  5402.3  345.96  5407.7  344.84  5423.9  347.00  5797.0  368.05
#Mann=4,-1,0
  4736.5    0.12       0  5018.7    0.07       0  5022.7    0.12       0
  5310.6     0.1       0
Bank Sta=5018.7,5022.7
Exp/Cntr=0.3,0.1

Type RM Length L Ch R = 1,3646,351,351,351
BEGIN DESCRIPTION:
Caney Creek T 7 6.0
END DESCRIPTION:
XS GIS Cut Line= 3
      2744534.89      6769773.49      2744626.00      6770061.00
      2745572.03      6770193.00
#Sta/Elev= 30
  4703.0  348.73  4811.5  342.03  4891.6  338.67  4923.9  335.95  4927.9  333.89
  4931.2  332.19  4983.2  332.36  4988.5  331.35  4992.1  324.28  4992.4  323.78
  4996.1  324.28  5002.0  326.74  5007.1  326.74  5014.7  331.07  5024.8  332.37
  5075.3  331.32  5085.4  324.90  5095.5  329.54  5105.6  330.46  5111.9  332.71
  5125.8  332.66  5146.0  325.24  5166.2  332.64  5183.4  336.10  5331.5  337.82
  5479.6  347.16  5559.9  354.36  5622.6  357.27  5792.2  358.32  5959.8  368.88
#Mann=5,-1,0
  4703.0     0.1       0  4811.5    0.12       0  4927.9     0.1       0
  4992.1    0.07       0  4996.1     0.1       0
Bank Sta=4992.1,4996.1
Exp/Cntr=0.3,0.1

Type RM Length L Ch R = 1,3295,374,374,374
BEGIN DESCRIPTION:
Caney Creek T 7 5.0
END DESCRIPTION:
XS GIS Cut Line= 3
      2744076.04      6769961.02      2744676.00      6770261.00
      2745557.53      6770352.11
#Sta/Elev= 30
  4328.4  353.93  4610.7  335.97  4775.6  333.68  4784.0  329.24  4789.5  331.35
  4797.9  324.84  4806.3  323.58  4828.7  325.54  4834.3  331.50  4849.0  323.32
  4849.3  322.82  4853.0  323.32  4856.6  327.49  4873.4  323.70  4879.0  329.35
  4909.7  331.15  4968.4  330.94  4985.2  326.46  4990.8  330.59  5009.2  324.18
  5027.0  324.22  5051.1  330.47  5089.7  323.50  5109.8  331.06  5243.9  333.87
  5427.0  347.41  5521.9  356.85  5602.4  361.42  5753.2  364.38  5885.4  370.41
#Mann=5,-1,0
  4328.4     0.1       0  4849.0    0.07       0  4853.0     0.1       0
  5027.0    0.12       0  5427.0     0.1       0
Bank Sta=4849,4853
Exp/Cntr=0.3,0.1

Type RM Length L Ch R = 1,2921,293,293,293
BEGIN DESCRIPTION:
Caney Creek T 7 4.0
END DESCRIPTION:
XS GIS Cut Line= 3
      2743945.54      6770285.89      2744576.00      6770561.00
      2745622.01      6770568.42
#Sta/Elev= 30
  4312.4  344.92  4461.4  345.25  4513.7  341.10  4552.9  335.00  4560.5  332.73
  4618.4  329.17  4672.9  328.63  4705.7  330.20  4771.1  328.47  4880.2  328.82
  4915.6  327.71  4956.6  328.73  4967.9  328.45  4976.4  323.68  4976.7  323.18
  4980.4  323.68  4997.5  327.37  5030.3  328.68  5090.3  328.62  5110.3  327.35
  5140.3  330.22  5205.7  329.96  5275.3  330.83  5340.3  331.49  5400.3  333.57
  5648.9  347.16  5690.3  349.13  5940.3  367.12  6020.3  371.76  6046.3  374.69
#Mann=6,-1,0
  4312.4    0.12       0  4976.4    0.07       0  4980.4    0.12       0
  5205.7     0.1       0  5275.3    0.12       0  5648.9     0.1       0
Bank Sta=4976.4,4980.4
Exp/Cntr=0.3,0.1

Type RM Length L Ch R = 1,2628,392,392,392
BEGIN DESCRIPTION:
Caney Creek T 7 3.0
END DESCRIPTION:
XS GIS Cut Line= 3
      2743872.96      6770609.71      2744568.63      6770817.34
      2745642.02      6770714.48
#Sta/Elev= 30
  4274.0  347.08  4371.1  348.82  4392.0  347.71  4437.4  340.79  4475.7  332.78
  4508.9  329.18  4548.5  326.92  4575.2  327.04  4580.4  325.80  4608.3  327.01
  4641.4  324.67  4652.9  327.14  4718.1  325.02  4736.4  326.51  4971.0  327.05
  4986.8  326.68  4993.7  323.88  5000.0  325.25  5005.4  323.47  5005.6  322.97
  5009.4  323.47  5037.5  327.96  5219.6  326.19  5409.2  329.32  5529.8  334.17
  5680.5  344.13  5780.9  352.85  5837.9  355.90  6064.8  370.98  6078.3  373.68
#Mann=6,-1,0
  4274.0    0.12       0  4971.0     0.1       0  5005.4    0.07       0
  5009.4     0.1       0  5219.6    0.12       0  5837.9     0.1       0
Bank Sta=5005.4,5009.4
Exp/Cntr=0.3,0.1

Type RM Length L Ch R = 1,2236,945,945,945
BEGIN DESCRIPTION:
Caney Creek T 7 2.0
END DESCRIPTION:
XS GIS Cut Line= 3
      2743806.28      6770691.27      2744476.00      6771111.00
      2745722.68      6771014.31
#Sta/Elev= 30
  4211.7  352.85  4292.0  349.91  4297.9  347.54  4313.2  347.49  4334.4  342.63
  4349.8  341.57  4413.4  332.20  4471.7  326.50  4530.0  323.32  4589.0  324.60
  4667.1  322.18  4667.4  321.68  4671.1  322.18  4683.4  323.34  4763.4  323.08
  4804.0  324.74  4842.4  325.02  4857.7  323.49  4863.6  324.45  4907.7  323.37
  4930.8  324.55  5182.6  322.59  5263.6  324.13  5326.7  322.48  5462.4  323.32
  5561.9  324.82  5694.1  329.91  5914.8  349.04  5985.0  353.98  6252.5  366.34
#Mann=8,-1,0
  4211.7    0.12       0  4471.7     0.1       0  4667.1    0.07       0
  4671.1     0.1       0  4804.0    0.12       0  5263.6     0.1       0
  5462.4    0.12       0  5561.9     0.1       0
Bank Sta=4667.1,4671.1
Exp/Cntr=0.3,0.1

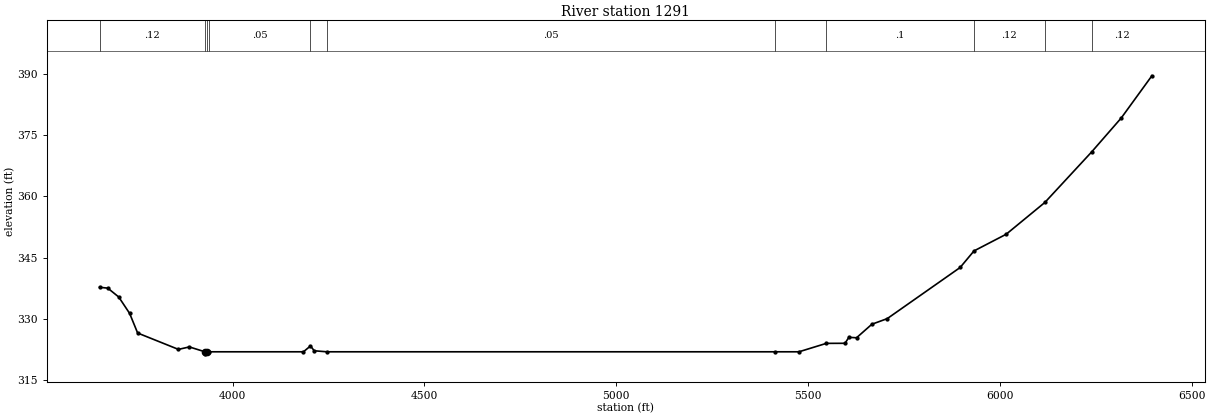
Type RM Length L Ch R = 1,1291,0,0,0
BEGIN DESCRIPTION:
Caney Creek T 7 1.0
END DESCRIPTION:
XS GIS Cut Line= 3
      2743726.01      6770861.01      2744739.77      6771747.81
      2746135.82      6771779.11
#Sta/Elev= 30
  3653.1  337.78  3674.4  337.57  3702.9  335.41  3731.4  331.39  3752.3  326.59
  3858.6  322.59  3887.1  323.19  3927.8  322.00  3928.0  321.50  3931.8  322.00
  3938.0  322.00  4184.5  322.00  4202.9  323.43  4212.6  322.25  4245.3  322.00
  5413.6  322.00  5476.3  322.00  5547.6  324.06  5596.4  324.08  5606.4  325.54
  5626.4  325.43  5666.4  328.74  5706.4  330.11  5896.5  342.62  5932.6  346.67
  6016.5  350.75  6117.4  358.53  6239.1  370.86  6316.6  379.20  6396.4  389.51
#Mann=11,-1,0
  3653.1    0.12       0  3927.8    0.03       0  3931.8    0.12       0
  3938.0    0.05       0  4202.9    0.12       0  4245.3    0.05       0
  5413.6    0.12       0  5547.6     0.1       0  5932.6    0.12       0
  6117.4     0.1       0  6239.1    0.12       0
Bank Sta=3927.8,3931.8
Exp/Cntr=0.3,0.1

Chan Stop Cuts=-1