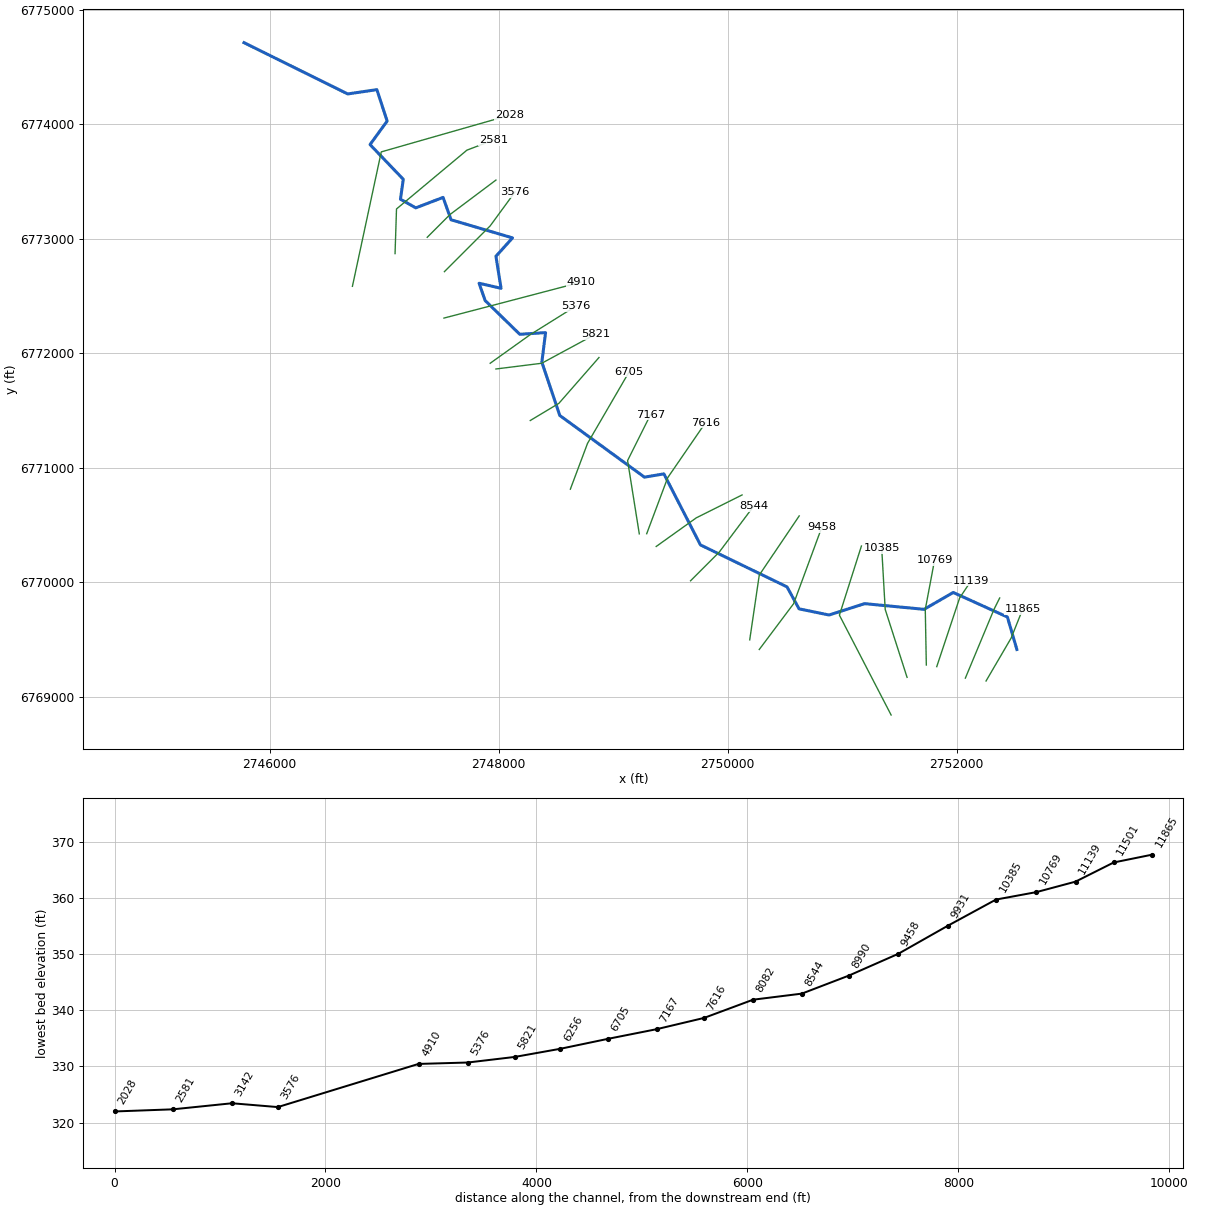
--- Caney Creek T 8.prj (project) ---

Proj Title=Caney Creek T 8 Base Level Engineering
Current Plan=p01
Default Exp/Contr=0.3,0.1
English Units
Geom File=g01
Flow File=f01
Plan File=p01
Y Axis Title=Elevation
X Axis Title(PF)=Main Channel Distance
X Axis Title(XS)=Station
BEGIN DESCRIPTION:
Caney Creek T 8
END DESCRIPTION:
DSS Export Rating Curves= 0
DSS Export Rating Curve Sorted= 0
DSS Export Volume Flow Curves= 0
DXF OffsetX= 0
DXF OffsetY= 0
DXF ScaleX= 1
DXF ScaleY= 10

--- Caney Creek T 8.p01 (plan) ---

Plan Title=Multiple Run
Program Version=4.10
Short Identifier=Multiple
Geom File=g01
Flow File=f01
Subcritical Flow
K Sum by GR= 0
Std Step Tol= 0.01
Critical Tol= 0.01
Num of Std Step Trials= 20
Max Error Tol= 0.3
Flow Tol Ratio= 0.001
Split Flow NTrial= 30
Split Flow Tol= 0.02
Split Flow Ratio= 0.02
Log Output Level= 0
Friction Slope Method= 1
Unsteady Friction Slope Method= 2
Unsteady Bridges Friction Slope Method= 1
Parabolic Critical Depth
Global Vel Dist= 1 , 1 , 1
Global Log Level= 0
CheckData=True
Encroach Param=-1 ,0,0, 0
BEGIN DESCRIPTION:
Multiple Run
END DESCRIPTION:
Computation Interval=1HOUR
Output Interval=1HOUR
Run HTab= 0
Run UNet= 0
Run PostProcess= 0
Run WQNet= 0
UNET Theta= 1
UNET Theta Warmup= 1
UNET ZTol= 0.02
UNET ZSATol= 0.05
UNET MxIter= 20
UNET MaxInSteps= 0
UNET DtIC= 0
UNET DtMin= 0
UNET MaxCRTS= 20
UNET WFStab= 2
UNET SFStab= 1
UNET WFX= 1
UNET SFX= 1
UNET DSS MLevel= 4
UNET DZMax Abort= 100
UNET Convert EG Bridges= 0
UNET Use Existing IB Tables=-1
UNET Froude Reduction=False
UNET Froude Limit= 1
UNET Froude Power= 10
UNET Time Slicing=0,0, 5
UNET Junction Losses=0
Instantaneous Interval=1HOUR
Write IC File= 0
Write IC File at Sim End=0
Echo Input=False
Echo Parameters=False
Echo Output=False
Write Detailed= 0
WQ AD Non Conservative
WQ ULTIMATE=-1
WQ Max Comp Step=1HOUR
WQ Output Interval=15MIN
WQ Output Selected Increments= 0
WQ Output face flow=0
WQ Output face velocity=0
WQ Output face area=0
WQ Output face dispersion=0
WQ Output cell volume=0
WQ Output cell surface area=0
WQ Output cell continuity=0
WQ Output cumulative cell continuity=0
WQ Output face conc=0
WQ Output face dconc_dx=0
WQ Output face courant=0
WQ Output face peclet=0
WQ Output face adv mass=0
WQ Output face disp mass=0
WQ Output cell mass=0
WQ Output cell source sink temp=0
WQ Output cell source sink nsm=0
WQ Output MaxMinRange=-1
WQ Daily Max Min Mean=-1
WQ Daily Range=0
WQ Daily Time=0
WQ Create Restart=0
WQ Fixed Restart=0
WQ System Summary=0
WQ Use Fixed Temperature=0
Sorting and Armoring Iterations= 10
XS Update Threshold= 0.02
Hydraulics Update Threshold= 0.02
Energy Slope Method= 1
Volume Change Method= 0
XS Weighting Method= 0
Number of US Weighted Cross Sections= 1
Number of DS Weighted Cross Sections= 1
Upstream XS Weight=0.25
Main XS Weight=0.5
Downstream XS Weight=0.25
Number of DS XS's Weighted with US Boundary= 1
Upstream Boundary Weight= 1
Weight of XSs Associated with US Boundary= 0
Number of US XS's Weighted with DS Boundary= 1
Downstream Boundary Weight= 0.5
Weight of XSs Associated with DS Boundary= 0.5
Sediment Output Level= 4
Mass or Volume Output= 0
Output Increment Type= 1
Profile and TS Output Increment= 10
XS Output Flag= 0
XS Output Increment= 10
Disregard all LS=0
Disregard all Conn=0
Disregard all Breaches=0
Disregard all Pumps=0

--- Caney Creek T 8.f01 (steady flow) ---

Flow Title=Multiple
Number of Profiles=7
Profile Names=10-year,25-year,50-year,1pct_min,100-year,1pct_plu,500-year
River Rch & RM= Caney Creek T 8,Reach-1,11865
     612     830    1009     610    1218    2430    1776
River Rch & RM= Caney Creek T 8,Reach-1,9931
     667     911    1114     677    1351    2695    1991
River Rch & RM= Caney Creek T 8,Reach-1,7167
     773    1062    1302     793    1582    3157    2343
River Rch & RM= Caney Creek T 8,Reach-1,3576
     770    1052    1286     780    1557    3106    2287
Boundary for River Rch & Prof#=Caney Creek T 8,Reach-1,1
Up Type=0
Dn Type=3
Dn Slope=0.005
Boundary for River Rch & Prof#=Caney Creek T 8,Reach-1,2
Up Type=0
Dn Type=3
Dn Slope=0.005
Boundary for River Rch & Prof#=Caney Creek T 8,Reach-1,3
Up Type=0
Dn Type=3
Dn Slope=0.005
Boundary for River Rch & Prof#=Caney Creek T 8,Reach-1,4
Up Type=0
Dn Type=3
Dn Slope=0.005
Boundary for River Rch & Prof#=Caney Creek T 8,Reach-1,5
Up Type=0
Dn Type=3
Dn Slope=0.005
Boundary for River Rch & Prof#=Caney Creek T 8,Reach-1,6
Up Type=0
Dn Type=3
Dn Slope=0.005
Boundary for River Rch & Prof#=Caney Creek T 8,Reach-1,7
Up Type=0
Dn Type=3
Dn Slope=0.005

--- Caney Creek T 8.g01 (geometry) ---

Geom Title=Existing Conditions

River Reach=Caney Creek T 8,Reach-1
Reach XY= 30
      2752526.00      6769411.00      2752443.22      6769694.52
      2751970.29      6769909.06      2751715.52      6769761.94
      2751196.13      6769811.39      2750885.59      6769712.21
      2750623.69      6769766.09      2750518.32      6769957.90
      2749762.24      6770324.47      2749443.13      6770944.97
      2749273.70      6770916.09      2748533.86      6771454.83
      2748377.10      6771920.64      2748409.61      6772178.64
      2748184.31      6772164.08      2747881.83      6772458.70
      2747829.12      6772609.86      2748020.82      6772565.56
      2747976.13      6772845.24      2748121.08      6773005.96
      2747584.32      6773164.16      2747514.46      6773359.51
      2747276.08      6773268.30      2747142.25      6773343.87
      2747166.87      6773517.74      2746876.58      6773820.98
      2747026.04      6774026.34      2746936.16      6774300.72
      2746681.56      6774263.26      2745776.00      6774711.00

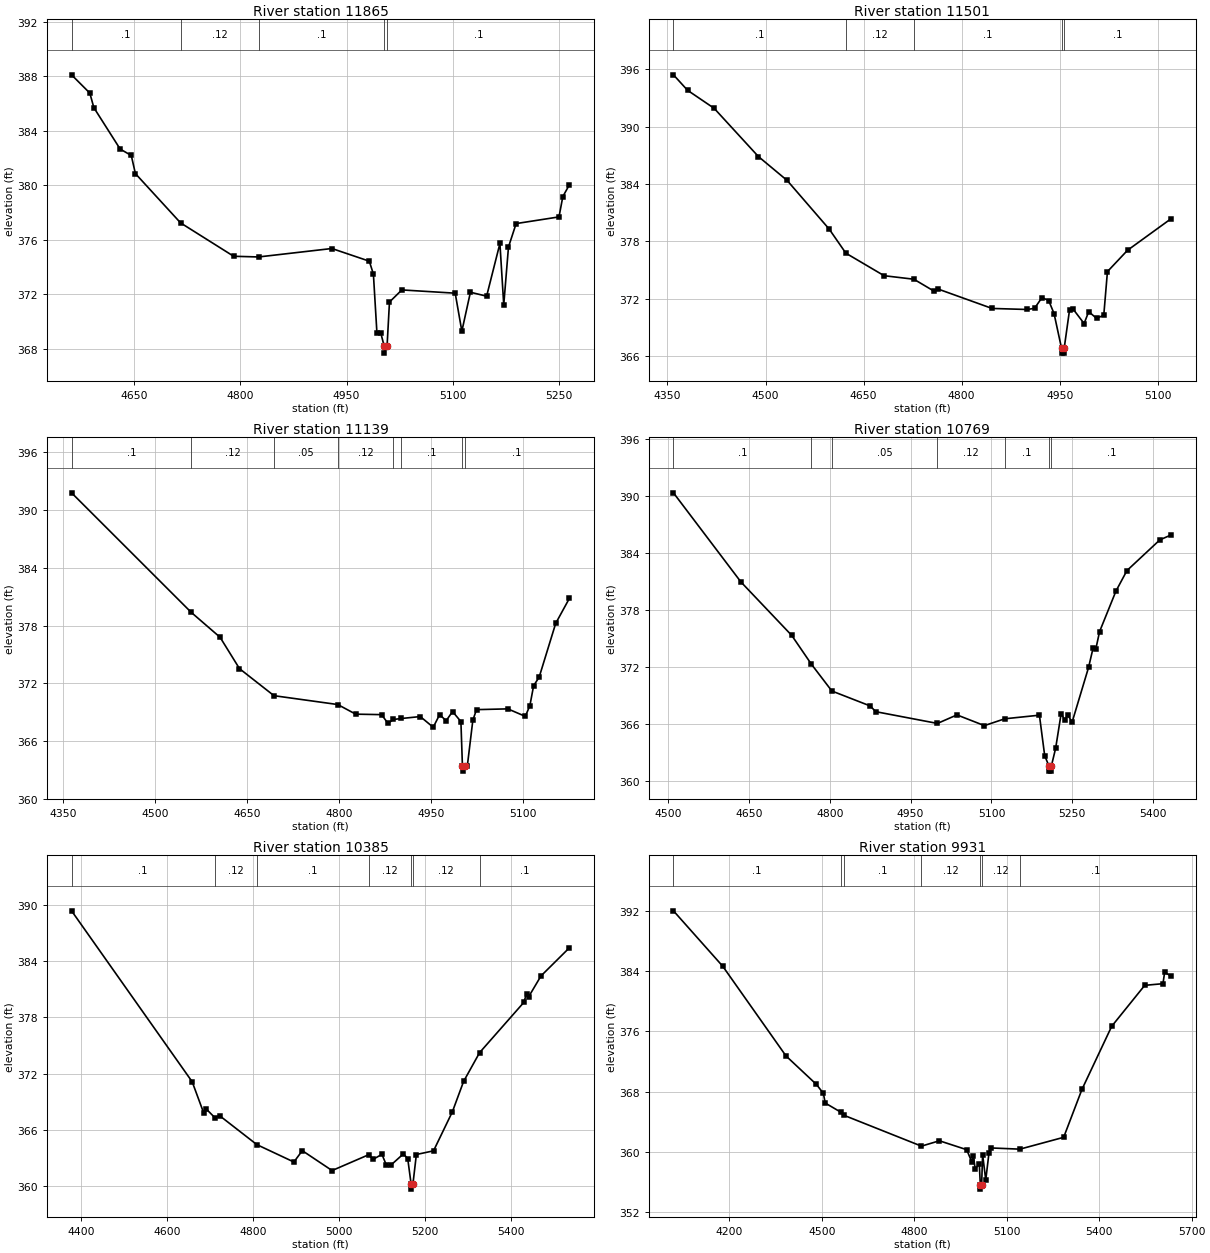
Type RM Length L Ch R = 1,11865,364,364,364
BEGIN DESCRIPTION:
Caney Creek T 8 22.0
END DESCRIPTION:
XS GIS Cut Line= 3
      2752256.73      6769135.95      2752476.00      6769511.00
      2752576.00      6769760.99
#Sta/Elev= 30
  4561.4  388.11  4587.2  386.77  4592.9  385.70  4630.1  382.66  4645.8  382.19
  4651.6  380.86  4715.5  377.24  4790.5  374.79  4825.6  374.74  4929.3  375.36
  4982.2  374.43  4988.0  373.48  4993.0  369.14  4998.5  369.14  5003.3  368.18
  5003.5  367.68  5007.3  368.18  5010.7  371.43  5028.2  372.32  5103.6  372.08
  5113.0  369.29  5125.1  372.15  5148.0  371.86  5166.8  375.73  5172.2  371.22
  5178.9  375.47  5189.7  377.19  5250.3  377.68  5255.7  379.17  5265.1  380.05
#Mann=5,-1,0
  4561.4     0.1       0  4715.5    0.12       0  4825.6     0.1       0
  5003.3    0.07       0  5007.3     0.1       0
Bank Sta=5003.3,5007.3
Exp/Cntr=0.3,0.1

Type RM Length L Ch R = 1,11501,362,362,362
BEGIN DESCRIPTION:
Caney Creek T 8 21.0
END DESCRIPTION:
XS GIS Cut Line= 3
      2752076.01      6769161.02      2752326.00      6769761.00
      2752376.01      6769861.02
#Sta/Elev= 30
  4359.1  395.44  4380.7  393.82  4421.4  391.93  4489.1  386.88  4533.0  384.38
  4597.4  379.28  4622.9  376.76  4681.4  374.40  4727.0  374.03  4758.3  372.76
  4763.7  373.01  4846.6  370.97  4900.7  370.86  4911.6  370.99  4923.0  372.11
  4933.2  371.80  4941.4  370.44  4952.9  366.79  4953.2  366.29  4956.7  366.29
  4956.9  366.79  4965.2  370.85  4970.6  370.90  4987.4  369.39  4994.5  370.64
  5006.4  369.93  5017.5  370.26  5023.1  374.83  5053.8  377.06  5120.9  380.39
#Mann=5,-1,0
  4359.1     0.1       0  4622.9    0.12       0  4727.0     0.1       0
  4952.9    0.07       0  4956.9     0.1       0
Bank Sta=4952.9,4956.9
Exp/Cntr=0.3,0.1

Type RM Length L Ch R = 1,11139,370,370,370
BEGIN DESCRIPTION:
Caney Creek T 8 20.0
END DESCRIPTION:
XS GIS Cut Line= 3
      2751826.00      6769260.99      2752026.00      6769861.00
      2752125.98      6770010.97
#Sta/Elev= 30
  4363.2  391.80  4558.5  379.38  4605.6  376.79  4637.3  373.53  4693.6  370.72
  4797.7  369.80  4827.0  368.80  4869.2  368.75  4879.7  367.84  4888.6  368.25
  4901.7  368.35  4932.4  368.55  4953.5  367.44  4964.0  368.75  4974.6  368.12
  4985.1  369.07  4998.7  368.03  5001.2  363.38  5001.4  362.88  5005.2  363.38
  5009.2  363.43  5018.2  368.18  5024.2  369.27  5075.3  369.35  5103.8  368.57
  5111.3  369.69  5117.4  371.76  5126.4  372.64  5153.4  378.23  5175.9  380.85
#Mann=8,-1,0
  4363.2     0.1       0  4558.5    0.12       0  4693.6    0.05       0
  4797.7    0.12       0  4888.6    0.05       0  4901.7     0.1       0
  5001.2    0.07       0  5005.2     0.1       0
Bank Sta=5001.2,5005.2
Exp/Cntr=0.3,0.1

Type RM Length L Ch R = 1,10769,384,384,384
BEGIN DESCRIPTION:
Caney Creek T 8 19.0
END DESCRIPTION:
XS GIS Cut Line= 3
      2751735.10      6769275.81      2751726.00      6769761.00
      2751807.24      6770191.94
#Sta/Elev= 30
  4510.0  390.37  4635.2  380.97  4729.5  375.33  4765.9  372.30  4803.9  369.47
  4875.2  367.89  4885.3  367.29  4999.8  366.05  5036.0  366.95  5086.9  365.82
  5124.7  366.54  5189.0  366.92  5198.8  362.65  5207.0  361.52  5207.2  361.02
  5210.7  361.02  5211.0  361.52  5219.1  363.43  5229.3  367.08  5236.3  366.39
  5241.4  366.96  5249.7  366.19  5280.2  371.96  5288.7  374.03  5293.8  373.94
  5300.6  375.73  5331.1  380.02  5351.4  382.17  5412.5  385.41  5433.8  385.94
#Mann=7,-1,0
  4510.0     0.1       0  4765.9    0.12       0  4803.9    0.05       0
  4999.8    0.12       0  5124.7     0.1       0  5207.0    0.07       0
  5211.0     0.1       0
Bank Sta=5207,5211
Exp/Cntr=0.3,0.1

Type RM Length L Ch R = 1,10385,454,454,454
BEGIN DESCRIPTION:
Caney Creek T 8 18.0
END DESCRIPTION:
XS GIS Cut Line= 3
      2751566.92      6769167.81      2751376.00      6769761.00
      2751345.38      6770297.27
#Sta/Elev= 30
  4377.0  389.35  4658.1  371.13  4684.9  367.81  4690.2  368.26  4710.6  367.32
  4722.2  367.51  4808.9  364.43  4895.1  362.58  4914.7  363.79  4984.1  361.67
  5069.6  363.36  5080.3  362.88  5100.3  363.40  5110.3  362.28  5120.4  362.22
  5150.4  363.45  5160.4  362.93  5168.4  360.19  5168.7  359.69  5172.4  360.19
  5180.5  363.38  5220.5  363.77  5264.5  367.94  5290.6  371.17  5327.9  374.24
  5430.9  379.59  5437.3  380.53  5442.3  380.20  5470.9  382.41  5537.3  385.42
#Mann=7,-1,0
  4377.0     0.1       0  4710.6    0.12       0  4808.9     0.1       0
  5069.6    0.12       0  5168.4    0.07       0  5172.4    0.12       0
  5327.9     0.1       0
Bank Sta=5168.4,5172.4
Exp/Cntr=0.3,0.1

Type RM Length L Ch R = 1,9931,473,473,473
BEGIN DESCRIPTION:
Caney Creek T 8 17.0
END DESCRIPTION:
XS GIS Cut Line= 3
      2751427.59      6768838.91      2750976.00      6769711.00
      2751168.24      6770315.07
#Sta/Elev= 30
  4018.1  391.96  4178.1  384.61  4383.4  372.72  4482.2  368.94  4504.7  367.76
  4510.6  366.48  4561.4  365.26  4572.7  364.83  4823.0  360.76  4881.3  361.47
  4969.8  360.29  4986.3  358.68  4991.9  359.42  4997.4  357.71  5010.7  358.44
  5014.2  355.56  5014.5  355.06  5018.3  355.56  5021.5  359.65  5031.7  356.27
  5042.2  359.87  5048.5  360.52  5142.5  360.36  5284.6  361.93  5343.8  368.27
  5440.5  376.65  5547.7  382.08  5606.9  382.30  5612.2  383.79  5634.1  383.31
#Mann=7,-1,0
  4018.1     0.1       0  4561.4    0.12       0  4572.7     0.1       0
  4823.0    0.12       0  5014.2    0.07       0  5018.3    0.12       0
  5142.5     0.1       0
Bank Sta=5014.2,5018.3
Exp/Cntr=0.3,0.1

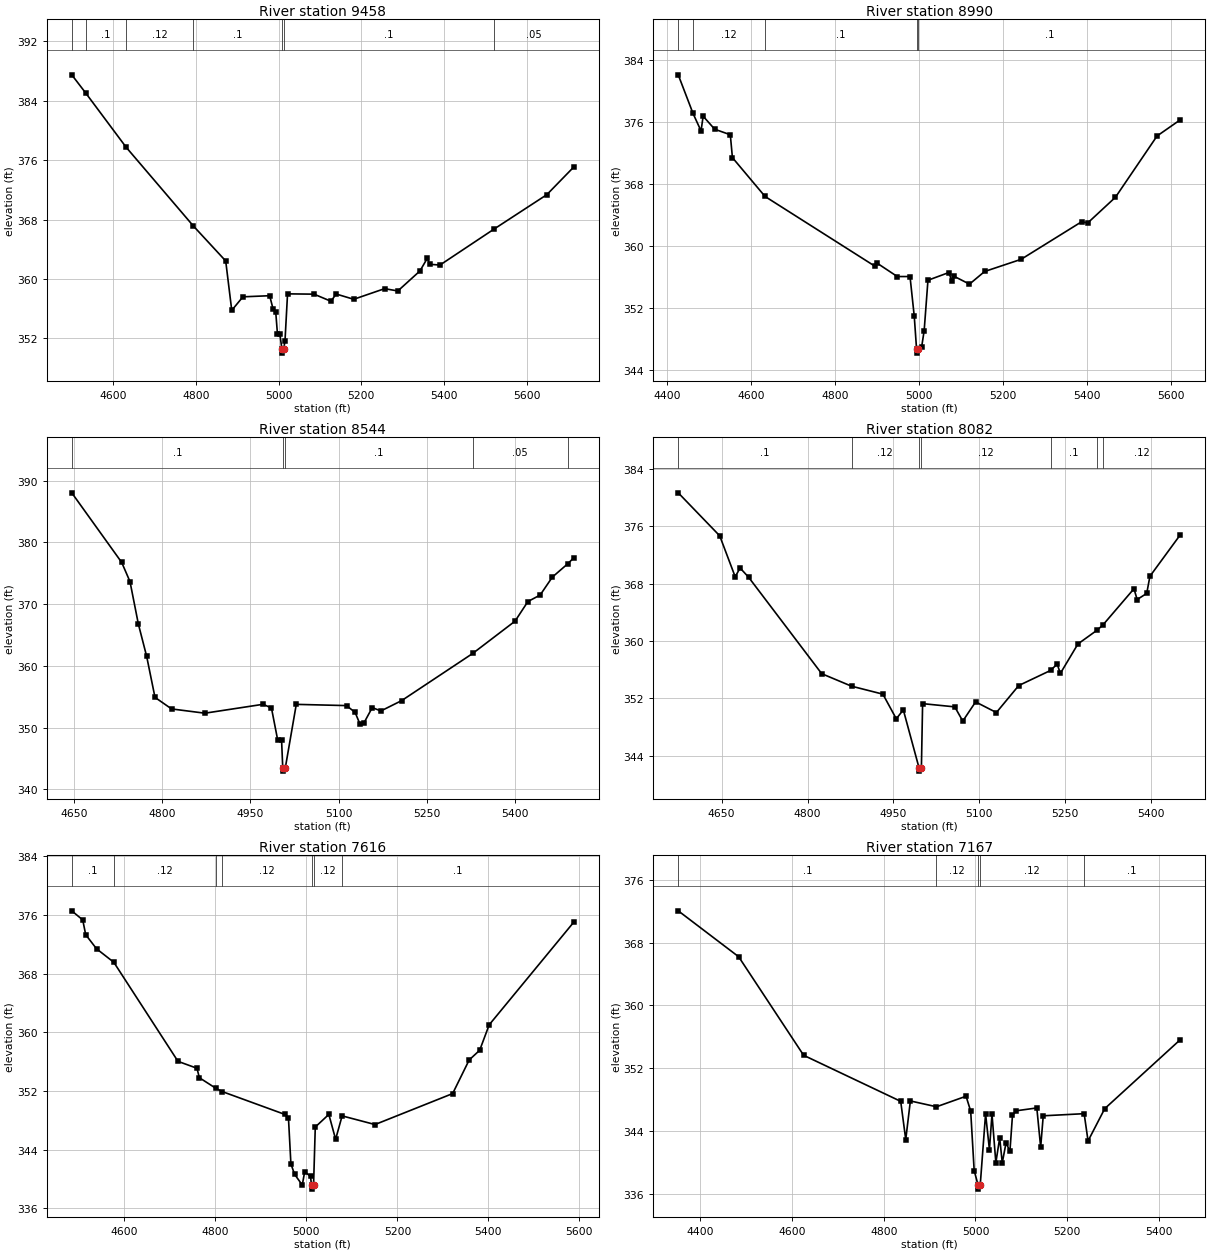
Type RM Length L Ch R = 1,9458,468,468,468
BEGIN DESCRIPTION:
Caney Creek T 8 16.0
END DESCRIPTION:
XS GIS Cut Line= 3
      2750276.00      6769411.00      2750576.00      6769811.00
      2750822.70      6770479.96
#Sta/Elev= 30
  4500.5  387.50  4533.8  385.08  4631.7  377.76  4794.1  367.16  4872.4  362.44
  4887.0  355.79  4914.0  357.61  4978.6  357.76  4987.0  355.94  4993.2  355.61
  4997.4  352.63  5003.2  352.63  5008.3  350.53  5008.6  350.03  5012.4  350.53
  5015.7  351.72  5021.8  358.01  5085.8  357.97  5126.8  357.01  5139.1  357.99
  5181.7  357.28  5256.3  358.71  5288.3  358.40  5341.6  361.09  5359.7  362.82
  5365.0  361.99  5390.1  361.89  5521.2  366.75  5648.1  371.36  5713.5  375.10
#Mann=7,-1,0
  4500.5    0.12       0  4533.8     0.1       0  4631.7    0.12       0
  4794.1     0.1       0  5008.3    0.07       0  5012.4     0.1       0
  5521.2    0.05       0
Bank Sta=5008.3,5012.4
Exp/Cntr=0.3,0.1

Type RM Length L Ch R = 1,8990,446,446,446
BEGIN DESCRIPTION:
Caney Creek T 8 15.0
END DESCRIPTION:
XS GIS Cut Line= 3
      2750192.71      6769494.98      2750276.00      6770061.00
      2750624.93      6770577.58
#Sta/Elev= 30
  4427.2  382.06  4462.4  377.08  4481.5  374.82  4486.5  376.72  4514.1  375.04
  4551.2  374.33  4556.2  371.38  4633.9  366.37  4894.7  357.40  4899.8  357.80
  4948.8  356.04  4979.1  356.04  4989.2  350.91  4994.7  346.66  4995.0  346.16
  4998.9  346.66  5006.8  346.96  5012.8  349.07  5021.8  355.56  5071.7  356.56
  5078.7  355.42  5084.8  356.05  5120.7  355.06  5156.7  356.69  5243.6  358.26
  5387.5  363.10  5402.4  362.96  5468.3  366.27  5567.3  374.17  5622.7  376.26
#Mann=5,-1,0
  4427.2     0.1       0  4462.4    0.12       0  4633.9     0.1       0
  4994.7    0.07       0  4998.9     0.1       0
Bank Sta=4994.7,4998.9
Exp/Cntr=0.3,0.1

Type RM Length L Ch R = 1,8544,462,462,462
BEGIN DESCRIPTION:
Caney Creek T 8 14.0
END DESCRIPTION:
XS GIS Cut Line= 3
      2749675.97      6770010.97      2749926.00      6770261.00
      2750226.00      6770661.00
#Sta/Elev= 30
  4646.2  388.01  4731.1  376.74  4745.2  373.63  4759.4  366.77  4773.5  361.54
  4787.7  354.89  4815.9  353.02  4872.5  352.33  4971.5  353.77  4985.7  353.17
  4996.3  347.98  5002.9  347.98  5004.9  343.45  5005.3  342.95  5009.2  343.45
  5027.9  353.76  5113.3  353.56  5127.9  352.46  5136.3  350.54  5142.5  350.68
  5157.1  353.24  5171.7  352.69  5207.1  354.37  5327.8  362.00  5399.8  367.23
  5421.7  370.41  5442.5  371.46  5463.3  374.37  5489.4  376.52  5499.8  377.50
#Mann=5,-1,0
  4646.2     0.1       0  5004.9    0.07       0  5009.2     0.1       0
  5327.8    0.05       0  5489.4    0.12       0
Bank Sta=5004.9,5009.2
Exp/Cntr=0.3,0.1

Type RM Length L Ch R = 1,8082,466,466,466
BEGIN DESCRIPTION:
Caney Creek T 8 13.0
END DESCRIPTION:
XS GIS Cut Line= 3
      2749376.00      6770311.00      2749726.00      6770561.00
      2750125.97      6770760.99
#Sta/Elev= 30
  4574.1  380.63  4646.6  374.64  4673.6  368.94  4682.2  370.16  4697.0  368.88
  4824.8  355.44  4876.9  353.70  4931.7  352.59  4955.1  349.16  4967.4  350.40
  4994.7  342.37  4995.0  341.87  4999.0  342.37  5001.1  351.27  5057.3  350.82
  5071.3  348.84  5093.7  351.51  5130.0  350.03  5169.1  353.79  5224.6  355.89
  5236.2  356.78  5241.8  355.48  5272.5  359.58  5306.3  361.52  5316.1  362.22
  5370.4  367.27  5376.0  365.77  5392.7  366.62  5398.3  369.01  5451.4  374.79
#Mann=7,-1,0
  4574.1     0.1       0  4876.9    0.12       0  4994.7    0.07       0
  4999.0    0.12       0  5224.6     0.1       0  5306.3    0.05       0
  5316.1    0.12       0
Bank Sta=4994.7,4999
Exp/Cntr=0.3,0.1

Type RM Length L Ch R = 1,7616,449,449,449
BEGIN DESCRIPTION:
Caney Creek T 8 12.0
END DESCRIPTION:
XS GIS Cut Line= 3
      2749292.91      6770422.37      2749476.00      6770911.00
      2749805.50      6771390.61
#Sta/Elev= 30
  4484.2  376.54  4508.3  375.30  4514.8  373.29  4538.6  371.37  4576.6  369.53
  4717.7  356.03  4759.4  355.09  4764.7  353.80  4801.4  352.34  4815.0  351.91
  4952.6  348.80  4960.6  348.25  4965.9  342.07  4974.0  340.64  4990.9  339.18
  4996.2  340.99  5009.0  340.36  5011.3  339.12  5011.7  338.62  5015.7  339.12
  5019.5  347.08  5049.3  348.80  5064.2  345.41  5078.5  348.60  5150.8  347.42
  5321.5  351.64  5357.8  356.22  5380.9  357.54  5401.8  361.01  5587.9  375.01
#Mann=7,-1,0
  4484.2     0.1       0  4576.6    0.12       0  4801.4     0.1       0
  4815.0    0.12       0  5011.3    0.07       0  5015.7    0.12       0
  5078.5     0.1       0
Bank Sta=5011.3,5015.7
Exp/Cntr=0.3,0.1

Type RM Length L Ch R = 1,7167,462,462,462
BEGIN DESCRIPTION:
Caney Creek T 8 11.0
END DESCRIPTION:
XS GIS Cut Line= 3
      2749228.15      6770420.84      2749126.00      6771061.00
      2749326.01      6771461.02
#Sta/Elev= 30
  4351.5  372.03  4483.3  366.19  4625.1  353.65  4836.9  347.79  4847.9  342.93
  4858.0  347.84  4915.0  347.10  4979.5  348.44  4989.6  346.55  4997.2  338.99
  5005.8  337.12  5006.3  336.62  5010.4  337.12  5022.1  346.20  5030.5  341.65
  5036.1  346.15  5044.5  339.99  5052.9  343.13  5058.5  339.97  5066.8  342.52
  5075.2  341.42  5080.8  346.01  5089.2  346.59  5133.9  346.95  5142.3  341.95
  5147.9  345.95  5237.2  346.22  5245.7  342.75  5282.1  346.86  5447.0  355.64
#Mann=5,-1,0
  4351.5     0.1       0  4915.0    0.12       0  5005.8    0.07       0
  5010.4    0.12       0  5237.2     0.1       0
Bank Sta=5005.8,5010.4
Exp/Cntr=0.3,0.1

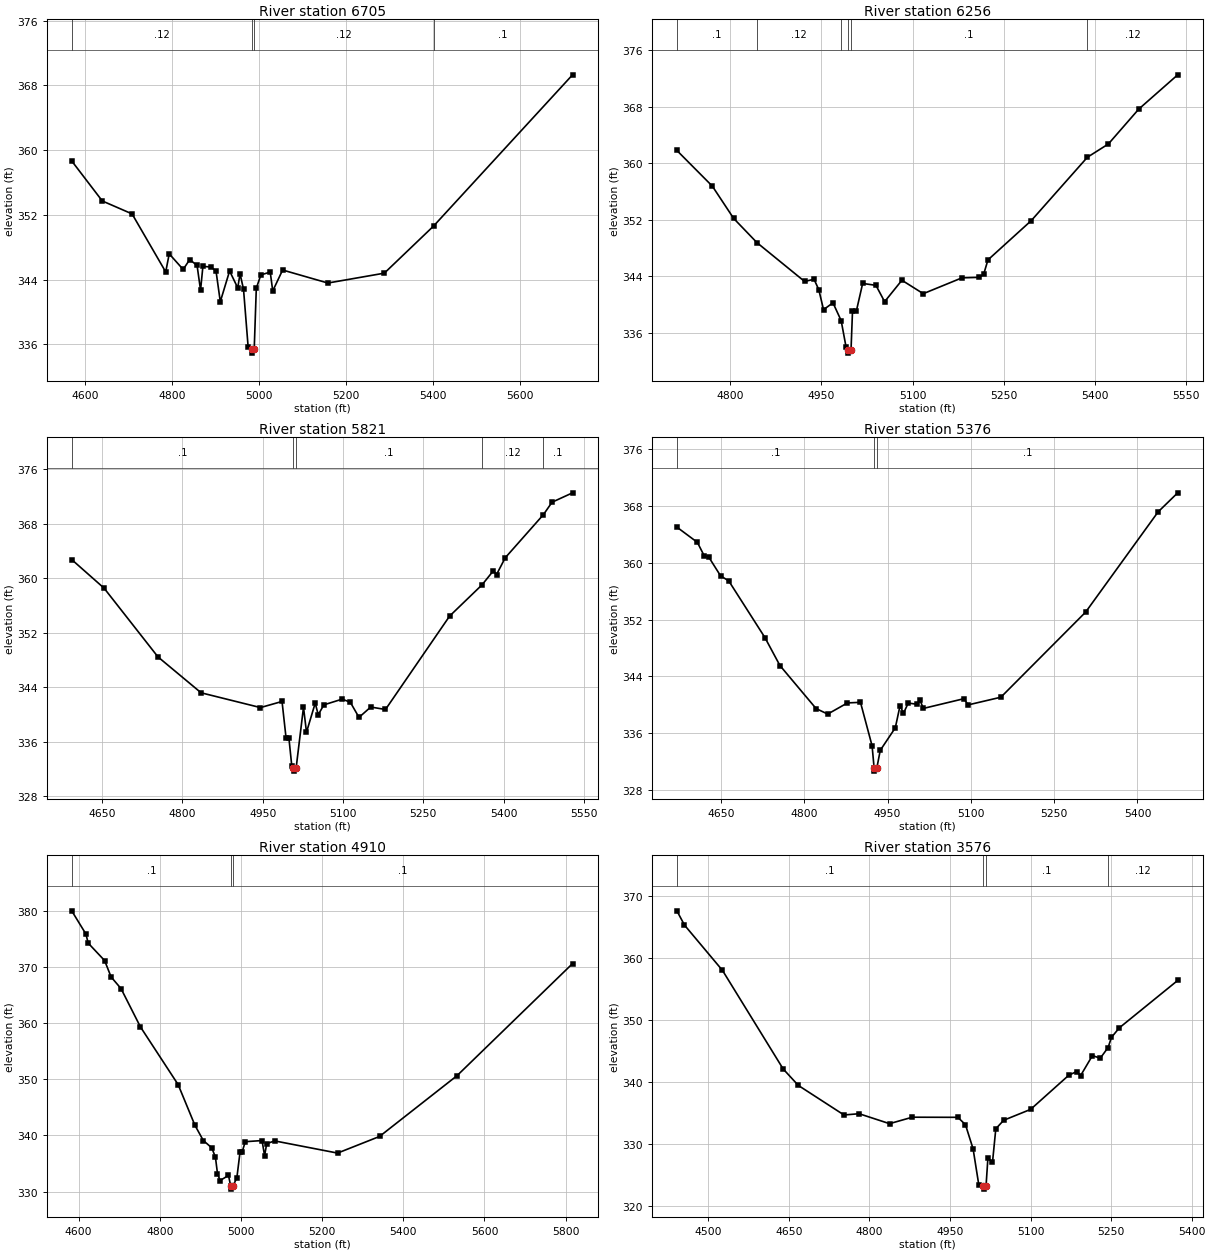
Type RM Length L Ch R = 1,6705,449,449,449
BEGIN DESCRIPTION:
Caney Creek T 8 10.0
END DESCRIPTION:
XS GIS Cut Line= 3
      2748626.01      6770811.03      2748776.00      6771211.00
      2749140.22      6771837.33
#Sta/Elev= 30
  4569.0  358.67  4639.3  353.72  4707.8  352.12  4785.2  344.94  4793.2  347.18
  4825.3  345.25  4840.4  346.47  4857.3  345.74  4865.3  342.69  4870.7  345.63
  4889.4  345.55  4900.9  345.04  4910.7  341.26  4932.1  345.06  4950.8  342.97
  4956.1  344.72  4964.1  342.80  4974.8  335.61  4984.0  335.40  4984.5  334.90
  4988.7  335.40  4993.5  342.93  5004.0  344.57  5025.5  344.93  5031.3  342.59
  5054.0  345.18  5158.1  343.57  5287.9  344.79  5401.2  350.62  5720.7  369.32
#Mann=4,-1,0
  4569.0    0.12       0  4984.0    0.07       0  4988.7    0.12       0
  5401.2     0.1       0
Bank Sta=4984,4988.7
Exp/Cntr=0.3,0.1

Type RM Length L Ch R = 1,6256,435,435,435
BEGIN DESCRIPTION:
Caney Creek T 8 9.0
END DESCRIPTION:
XS GIS Cut Line= 3
      2748276.02      6771411.01      2748526.00      6771561.00
      2748875.98      6771960.97
#Sta/Elev= 30
  4712.7  361.81  4771.0  356.76  4806.0  352.20  4844.3  348.77  4922.6  343.28
  4938.1  343.59  4945.9  342.12  4953.7  339.29  4969.2  340.26  4982.7  337.73
  4990.6  334.06  4994.0  333.64  4994.6  333.14  4998.9  333.64  5001.3  339.04
  5007.5  339.04  5018.0  343.00  5039.8  342.73  5054.1  340.42  5082.5  343.45
  5117.6  341.55  5181.2  343.79  5209.7  343.86  5216.8  344.29  5223.9  346.33
  5295.1  351.89  5387.3  360.85  5421.8  362.73  5471.7  367.66  5535.7  372.51
#Mann=6,-1,0
  4712.7     0.1       0  4844.3    0.12       0  4982.7     0.1       0
  4994.0    0.07       0  4998.9     0.1       0  5387.3    0.12       0
Bank Sta=4994,4998.9
Exp/Cntr=0.3,0.1

Type RM Length L Ch R = 1,5821,445,445,445
BEGIN DESCRIPTION:
Caney Creek T 8 8.0
END DESCRIPTION:
XS GIS Cut Line= 3
      2747976.03      6771861.00      2748376.00      6771911.00
      2748844.71      6772164.19
#Sta/Elev= 30
  4593.1  362.74  4653.5  358.55  4754.3  348.45  4834.9  343.18  4945.8  341.01
  4986.1  341.91  4993.7  336.49  4999.0  336.49  5004.3  332.45  5007.4  332.18
  5008.1  331.68  5012.5  332.18  5026.2  341.06  5031.8  337.39  5048.1  341.67
  5053.7  339.96  5064.3  341.41  5098.5  342.25  5113.7  341.79  5129.9  339.57
  5151.8  341.09  5179.4  340.73  5299.3  354.45  5359.8  359.03  5381.2  361.12
  5386.9  360.54  5403.1  363.00  5474.5  369.34  5490.6  371.16  5528.9  372.54
#Mann=5,-1,0
  4593.1     0.1       0  5007.4    0.07       0  5012.5     0.1       0
  5359.8    0.12       0  5474.5     0.1       0
Bank Sta=5007.4,5012.5
Exp/Cntr=0.3,0.1

Type RM Length L Ch R = 1,5376,466,466,466
BEGIN DESCRIPTION:
Caney Creek T 8 7.0
END DESCRIPTION:
XS GIS Cut Line= 3
      2747925.99      6771910.99      2748276.00      6772161.00
      2748675.97      6772410.98
#Sta/Elev= 30
  4570.7  364.99  4607.6  362.85  4619.9  360.96  4628.5  360.73  4649.4  358.14
  4664.1  357.43  4729.2  349.47  4756.3  345.53  4821.4  339.48  4842.3  338.71
  4877.9  340.28  4901.3  340.36  4922.2  334.25  4925.8  331.19  4926.4  330.69
  4930.9  331.19  4936.9  333.61  4964.0  336.78  4972.6  339.91  4978.7  338.82
  4987.3  340.26  5003.8  340.08  5008.5  340.68  5014.4  339.50  5087.5  340.87
  5095.2  340.00  5154.1  341.08  5306.8  353.05  5437.2  367.13  5472.5  369.81
#Mann=3,-1,0
  4570.7     0.1       0  4925.8    0.07       0  4930.9     0.1       0
Bank Sta=4925.8,4930.9
Exp/Cntr=0.3,0.1

Type RM Length L Ch R = 1,4910,1334,1334,1334
BEGIN DESCRIPTION:
Caney Creek T 8 6.0
END DESCRIPTION:
XS GIS Cut Line= 3
      2747522.18      6772305.61      2747926.00      6772411.00
      2748716.01      6772618.29
#Sta/Elev= 30
  4582.9  380.01  4617.8  375.89  4623.5  374.26  4664.0  371.15  4679.9  368.24
  4704.5  366.15  4752.2  359.34  4845.2  349.05  4886.6  341.80  4907.2  339.10
  4927.9  337.80  4937.0  336.15  4942.1  333.22  4948.6  331.97  4969.2  332.88
  4974.9  330.94  4975.5  330.44  4980.0  330.94  4989.9  332.49  4997.7  337.05
  5002.8  337.05  5010.6  338.89  5051.9  339.09  5058.2  336.40  5063.4  338.54
  5083.0  339.03  5238.0  336.86  5341.4  339.82  5532.4  350.65  5817.0  370.61
#Mann=3,-1,0
  4582.9     0.1       0  4974.9    0.07       0  4980.0     0.1       0
Bank Sta=4974.9,4980
Exp/Cntr=0.3,0.1

Type RM Length L Ch R = 1,3576,434,434,434
BEGIN DESCRIPTION:
Caney Creek T 8 5.0
END DESCRIPTION:
XS GIS Cut Line= 3
      2747525.98      6772710.98      2747926.00      6773111.00
      2748142.73      6773407.03
#Sta/Elev= 30
  4441.5  367.57  4455.7  365.27  4526.4  357.98  4639.5  342.10  4667.8  339.45
  4752.7  334.70  4780.9  334.90  4837.5  333.30  4879.9  334.34  4964.8  334.32
  4978.9  333.13  4993.1  329.24  5003.7  323.46  5011.8  323.26  5012.6  322.76
  5017.2  323.26  5020.7  327.79  5029.2  327.05  5035.4  332.48  5050.1  333.85
  5100.2  335.60  5171.3  341.10  5185.9  341.69  5193.1  341.01  5215.3  344.26
  5229.9  343.84  5244.5  345.56  5250.8  347.20  5265.4  348.73  5374.1  356.36
#Mann=4,-1,0
  4441.5     0.1       0  5011.8    0.07       0  5017.2     0.1       0
  5244.5    0.12       0
Bank Sta=5011.8,5017.2
Exp/Cntr=0.3,0.1

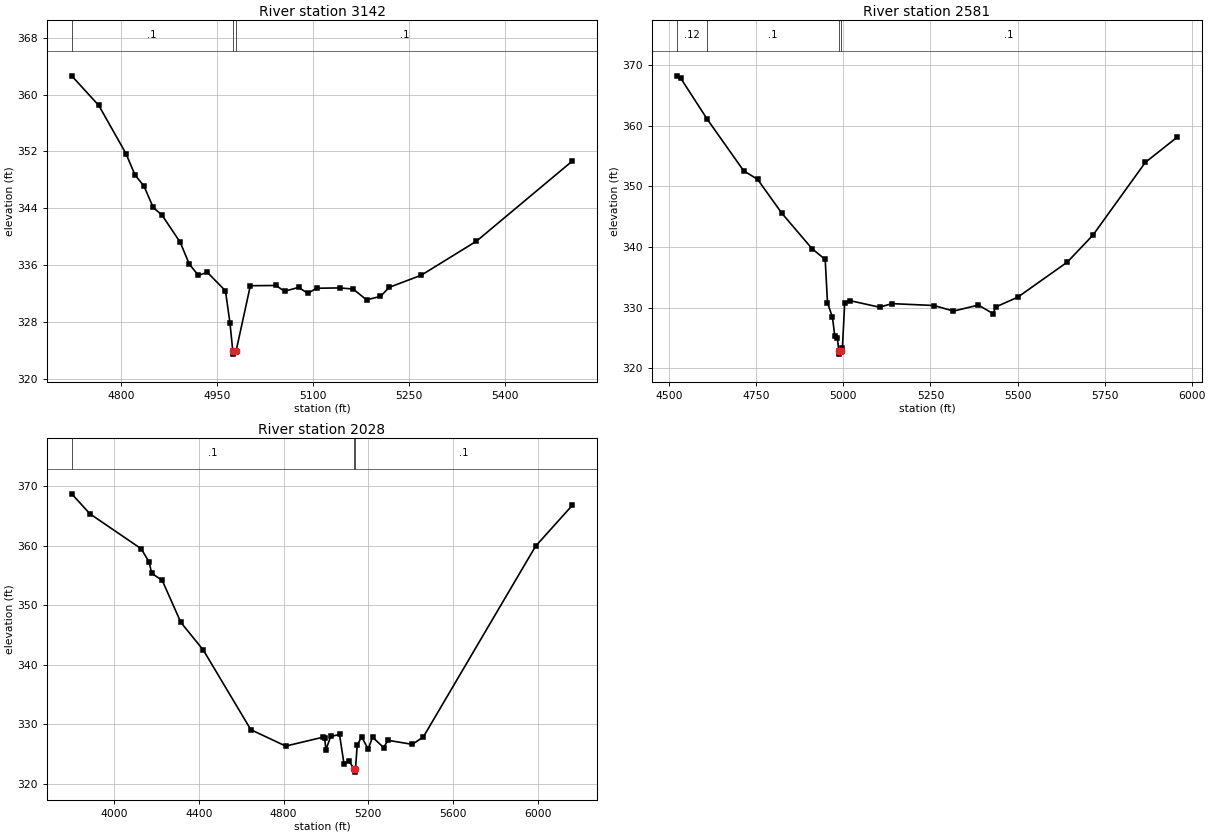
Type RM Length L Ch R = 1,3142,561,561,561
BEGIN DESCRIPTION:
Caney Creek T 8 4.0
END DESCRIPTION:
XS GIS Cut Line= 3
      2747376.01      6773011.01      2747576.00      6773211.00
      2747975.98      6773510.98
#Sta/Elev= 30
  4722.6  362.65  4765.0  358.47  4807.4  351.70  4821.6  348.68  4835.7  347.10
  4849.9  344.13  4864.0  343.00  4892.3  339.19  4906.4  336.13  4920.6  334.54
  4934.7  334.96  4963.0  332.36  4970.1  327.80  4974.4  323.94  4975.2  323.44
  4979.8  323.94  5001.9  333.08  5041.9  333.11  5055.4  332.30  5077.3  332.84
  5091.9  332.01  5105.4  332.72  5141.9  332.77  5162.7  332.61  5183.6  331.09
  5205.4  331.57  5219.0  332.85  5269.0  334.55  5355.4  339.35  5505.4  350.65
#Mann=3,-1,0
  4722.6     0.1       0  4974.4    0.07       0  4979.8     0.1       0
Bank Sta=4974.4,4979.8
Exp/Cntr=0.3,0.1

Type RM Length L Ch R = 1,2581,553,553,553
BEGIN DESCRIPTION:
Mapping XS 7aec2db9
END DESCRIPTION:
XS GIS Cut Line= 4
      2747094.99      6772868.61      2747107.72      6773258.63
      2747722.54      6773772.13      2747952.71      6773860.15
#Sta/Elev= 30
  4521.0  368.21  4533.4  367.77  4608.8  361.07  4713.5  352.57  4753.5  351.16
  4823.5  345.55  4909.9  339.73  4947.7  337.96  4954.3  330.84  4968.6  328.41
  4975.1  325.40  4982.9  324.94  4986.7  322.86  4987.4  322.36  4992.1  322.86
  4997.2  323.45  5003.7  330.82  5018.0  331.18  5103.9  330.09  5139.1  330.68
  5260.1  330.37  5316.1  329.45  5387.6  330.44  5430.1  329.02  5437.1  330.12
  5500.9  331.75  5642.7  337.51  5716.8  341.98  5867.2  353.96  5958.7  358.11
#Mann=4,-1,0
  4521.0    0.12       0  4608.8     0.1       0  4986.7    0.07       0
  4992.1     0.1       0
Bank Sta=4986.7,4992.1
Exp/Cntr=0.3,0.1

Type RM Length L Ch R = 1,2028,0,0,0
BEGIN DESCRIPTION:
Caney Creek T 8 3.0
END DESCRIPTION:
XS GIS Cut Line= 3
      2746722.75      6772583.10      2746974.53      6773757.10
      2748092.86      6774076.69
#Sta/Elev= 30
  3799.3  368.76  3885.2  365.40  4127.2  359.53  4165.3  357.28  4176.6  355.41
  4226.7  354.21  4314.6  347.15  4421.0  342.48  4645.1  329.11  4809.7  326.36
  4985.9  327.85  4993.8  327.69  4999.4  325.75  5022.3  327.97  5063.7  328.31
  5084.7  323.42  5107.9  323.86  5133.8  322.48  5134.6  321.98  5139.2  322.48
  5147.1  326.47  5167.9  327.92  5199.1  325.87  5219.9  327.85  5271.9  326.11
  5292.7  327.33  5407.1  326.65  5459.1  327.87  5989.6  359.96  6163.1  366.84
#Mann=3,-1,0
  3799.3     0.1       0  5133.8    0.07       0  5139.2     0.1       0
Bank Sta=5133.8,5139.2
Exp/Cntr=0.3,0.1

Chan Stop Cuts=-1