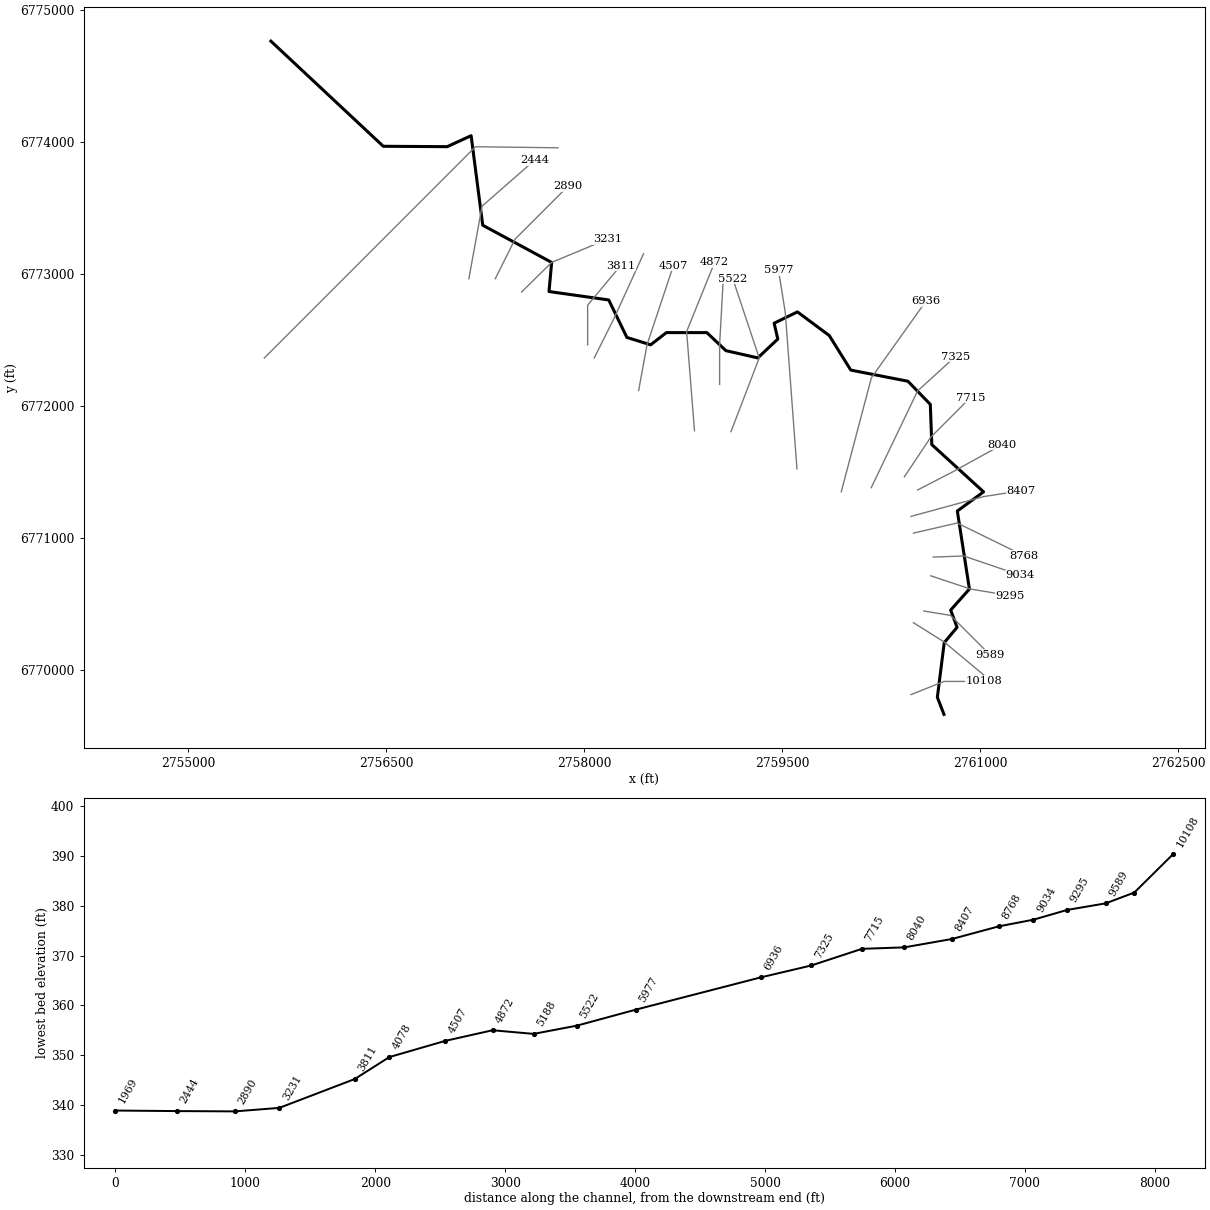
--- Caney Creek T 9.prj (project) ---

Proj Title=Caney Creek T 9 Base Level Engineering
Current Plan=p01
Default Exp/Contr=0.3,0.1
English Units
Geom File=g01
Flow File=f01
Plan File=p01
BEGIN DESCRIPTION:
Caney Creek T 9
END DESCRIPTION:

--- Caney Creek T 9.p01 (plan) ---

Plan Title=Multiple Run
Short Identifier=Multiple
Geom File=g01
Flow File=f01
Subcritical Flow
K Sum by GR= 0
Std Step Tol= 0.01
Critical Tol= 0.01
Num of Std Step Trials= 20
Max Error Tol= 0.3
Flow Tol Ratio= 0.001
Split Flow NTrial= 30
Split Flow Tol= 0.02
Split Flow Ratio= 0.02
Log Output Level= 0
Friction Slope Method= 1
Unsteady Friction Slope Method= 2
Unsteady Bridges Friction Slope Method= 1
Parabolic Critical Depth
Global Vel Dist=  1 , 1 , 1
Global Log Level= 0
CheckData=True
Encroach Param= -1, 0, 0, 0
BEGIN DESCRIPTION:
Multiple Run
END DESCRIPTION:

--- Caney Creek T 9.f01 (steady flow) ---

Flow Title=Multiple
Number of Profiles=7
Profile Names=10-year,25-year,50-year,1pct_min,100-year,1pct_plu,500-year
River Rch & RM= Caney Creek T 9,Reach-1,10108
     546     737     894     540    1077    2148    1563
River Rch & RM= Caney Creek T 9,Reach-1,3231
     714     979    1200     731    1459    2911    2161
Boundary for River Rch & Prof#=Caney Creek T 9,Reach-1,1
Up Type=0
Dn Type=3
Dn Slope=0.005
Boundary for River Rch & Prof#=Caney Creek T 9,Reach-1,2
Up Type=0
Dn Type=3
Dn Slope=0.005
Boundary for River Rch & Prof#=Caney Creek T 9,Reach-1,3
Up Type=0
Dn Type=3
Dn Slope=0.005
Boundary for River Rch & Prof#=Caney Creek T 9,Reach-1,4
Up Type=0
Dn Type=3
Dn Slope=0.005
Boundary for River Rch & Prof#=Caney Creek T 9,Reach-1,5
Up Type=0
Dn Type=3
Dn Slope=0.005
Boundary for River Rch & Prof#=Caney Creek T 9,Reach-1,6
Up Type=0
Dn Type=3
Dn Slope=0.005
Boundary for River Rch & Prof#=Caney Creek T 9,Reach-1,7
Up Type=0
Dn Type=3
Dn Slope=0.005

--- Caney Creek T 9.g01 (geometry) ---

Geom Title=Existing Conditions

River Reach=Caney Creek T 9,Reach-1
Reach XY= 30
      2760726.00      6769661.00      2760675.89      6769790.92
      2760728.07      6770205.14      2760825.24      6770320.78
      2760776.76      6770451.22      2760918.68      6770610.90
      2760827.20      6771201.75      2761025.96      6771346.93
      2760633.81      6771704.81      2760622.46      6772009.54
      2760452.87      6772184.83      2760019.95      6772269.16
      2759856.72      6772531.07      2759615.51      6772710.06
      2759439.12      6772624.24      2759466.85      6772504.27
      2759315.38      6772361.60      2759073.55      6772416.47
      2758929.41      6772553.18      2758622.60      6772553.17
      2758503.28      6772460.62      2758323.45      6772516.73
      2758185.83      6772800.56      2757733.28      6772864.31
      2757753.31      6773084.89      2757231.19      6773366.44
      2757143.17      6774044.91      2756962.09      6773961.67
      2756477.46      6773964.54      2755626.00      6774761.00

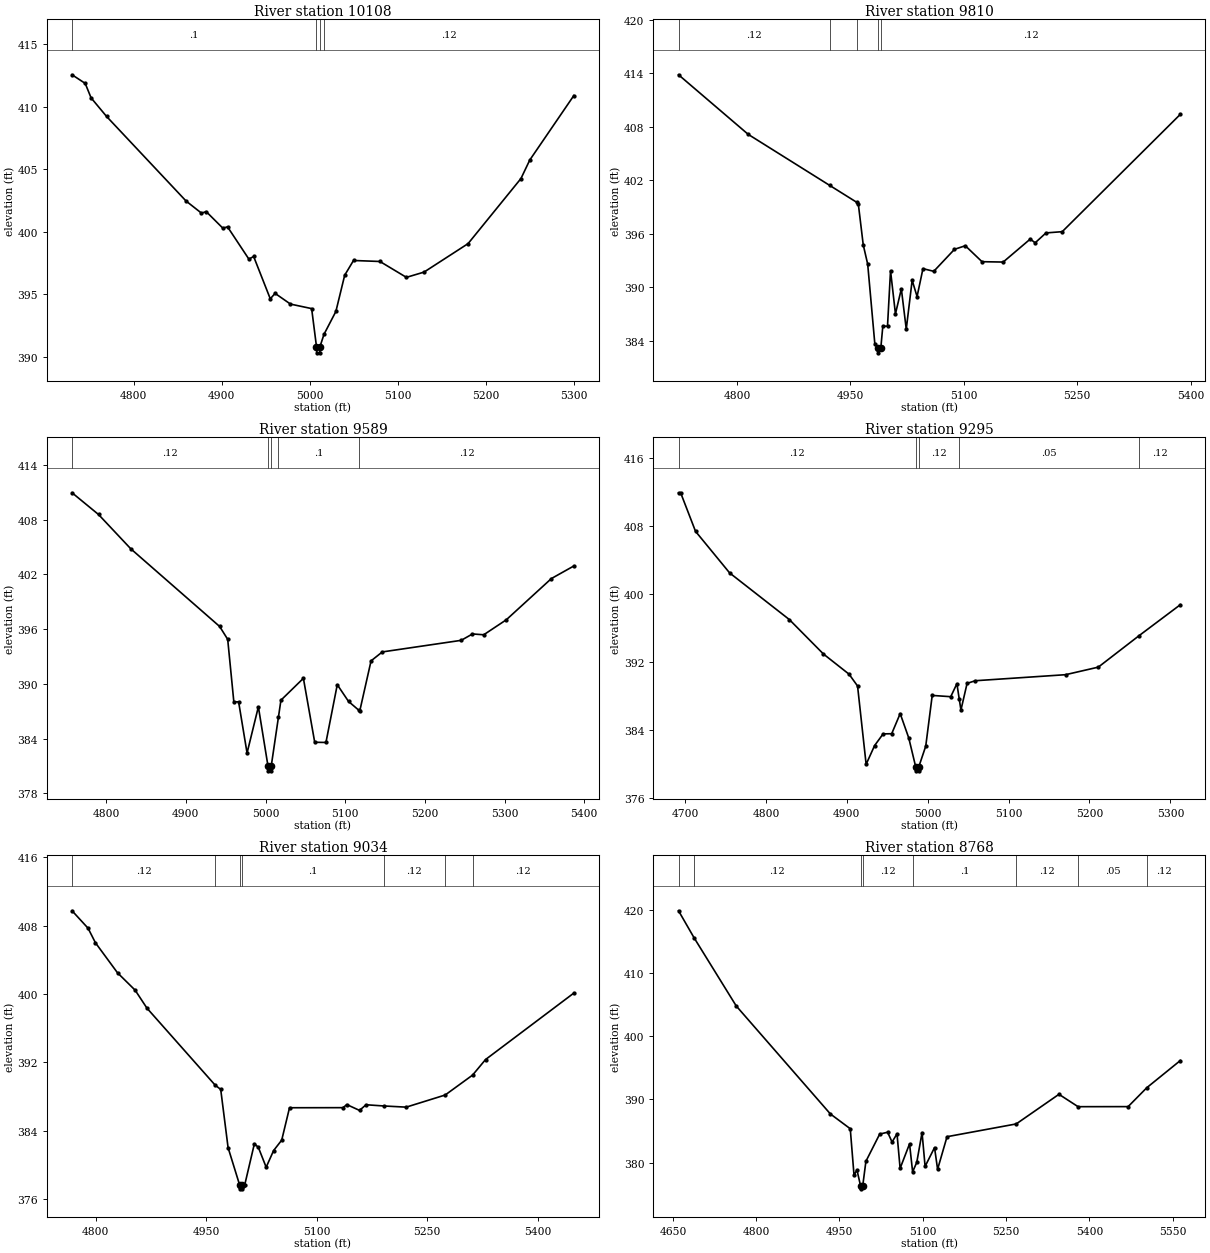
Type RM Length L Ch R = 1,10108,298,298,298
BEGIN DESCRIPTION:
Caney Creek T 9 22.0
END DESCRIPTION:
XS GIS Cut Line= 3
      2760475.96      6769810.98      2760726.00      6769911.00
      2761025.99      6769911.00
#Sta/Elev= 30
  4730.3  412.57  4745.2  411.88  4751.9  410.72  4769.4  409.24  4859.6  402.47
  4877.1  401.50  4882.5  401.62  4901.3  400.30  4906.7  400.40  4930.9  397.82
  4936.3  398.03  4955.2  394.64  4960.6  395.08  4978.1  394.22  5002.1  393.86
  5007.6  390.82  5007.9  390.32  5011.4  390.32  5011.6  390.82  5016.1  391.80
  5029.6  393.63  5039.6  396.53  5049.6  397.71  5079.6  397.63  5109.6  396.36
  5129.6  396.78  5179.6  399.06  5239.6  404.27  5249.6  405.75  5299.6  410.91
#Mann=4,-1,0
  4730.3     0.1       0  5007.6    0.07       0  5011.6     0.1       0
  5016.1    0.12       0
Bank Sta=5007.6,5011.6
Exp/Cntr=0.3,0.1

Type RM Length L Ch R = 1,9810,221,221,221
BEGIN DESCRIPTION:
Caney Creek T 9 21.0
END DESCRIPTION:
XS GIS Cut Line= 3
      2760494.42      6770355.93      2760726.00      6770211.00
      2761026.00      6769961.00
#Sta/Elev= 30
  4722.7  413.84  4814.9  407.15  4922.7  401.42  4958.5  399.52  4960.5  399.33
  4967.0  394.75  4972.9  392.58  4982.3  383.67  4986.2  383.13  4986.5  382.63
  4990.2  383.13  4992.9  385.62  4999.1  385.62  5003.1  391.85  5009.6  387.00
  5017.4  389.81  5023.9  385.29  5031.7  390.77  5038.2  388.95  5046.0  392.08
  5060.3  391.78  5087.7  394.25  5102.0  394.65  5124.1  392.86  5152.1  392.82
  5187.9  395.40  5194.4  394.98  5208.7  396.09  5230.2  396.23  5386.4  409.40
#Mann=5,-1,0
  4722.7    0.12       0  4922.7     0.1       0  4958.5    0.12       0
  4986.2    0.07       0  4990.2    0.12       0
Bank Sta=4986.2,4990.2
Exp/Cntr=0.3,0.1

Type RM Length L Ch R = 1,9589,294,294,294
BEGIN DESCRIPTION:
Caney Creek T 9 20.0
END DESCRIPTION:
XS GIS Cut Line= 3
      2760573.25      6770444.42      2760776.00      6770411.00
      2761075.97      6770111.03
#Sta/Elev= 30
  4757.2  410.93  4790.4  408.55  4830.9  404.79  4942.4  396.28  4952.5  394.87
  4960.2  388.02  4966.2  388.02  4976.8  382.41  4991.0  387.48  5003.1  380.96
  5003.4  380.46  5006.9  380.46  5007.1  380.96  5016.2  386.36  5019.3  388.20
  5047.5  390.60  5061.7  383.59  5075.8  383.57  5090.0  389.90  5104.1  388.07
  5117.3  387.08  5118.2  387.01  5132.4  392.51  5146.5  393.49  5245.5  394.76
  5259.7  395.46  5273.8  395.37  5302.1  397.01  5358.7  401.53  5386.9  402.91
#Mann=5,-1,0
  4757.2    0.12       0  5003.1    0.07       0  5007.1    0.12       0
  5016.2     0.1       0  5117.3    0.12       0
Bank Sta=5003.1,5007.1
Exp/Cntr=0.3,0.1

Type RM Length L Ch R = 1,9295,261,261,261
BEGIN DESCRIPTION:
Caney Creek T 9 19.0
END DESCRIPTION:
XS GIS Cut Line= 3
      2760626.04      6770710.99      2760926.00      6770611.00
      2761225.97      6770561.00
#Sta/Elev= 30
  4692.0  411.90  4694.6  411.90  4713.0  407.36  4755.2  402.46  4829.0  396.97
  4871.2  392.91  4902.8  390.54  4913.3  389.15  4923.9  379.93  4934.4  382.14
  4944.9  383.51  4955.5  383.53  4966.0  385.90  4976.6  383.03  4985.1  379.66
  4985.4  379.16  4988.9  379.16  4989.1  379.66  4997.6  382.07  5005.6  388.04
  5028.5  387.89  5036.1  389.42  5039.0  387.62  5041.1  386.32  5048.7  389.46
  5058.9  389.77  5170.4  390.48  5210.9  391.37  5261.5  395.09  5312.3  398.72
#Mann=5,-1,0
  4692.0    0.12       0  4985.1    0.07       0  4989.1    0.12       0
  5039.0    0.05       0  5261.5    0.12       0
Bank Sta=4985.1,4989.1
Exp/Cntr=0.3,0.1

Type RM Length L Ch R = 1,9034,266,266,266
BEGIN DESCRIPTION:
Caney Creek T 9 18.0
END DESCRIPTION:
XS GIS Cut Line= 3
      2760644.32      6770853.13      2760876.00      6770861.00
      2761301.49      6770716.41
#Sta/Elev= 30
  4768.1  409.73  4789.8  407.69  4799.8  405.99  4829.8  402.47  4853.7  400.44
  4869.8  398.33  4962.2  389.34  4969.9  388.82  4979.9  382.01  4995.4  377.69
  4995.7  377.19  4999.2  377.19  4999.4  377.69  5002.6  377.69  5015.6  382.47
  5021.0  382.04  5031.6  379.72  5041.7  381.67  5052.7  382.89  5063.3  386.68
  5135.9  386.69  5141.1  387.05  5158.3  386.37  5167.2  387.03  5190.9  386.89
  5221.7  386.75  5274.6  388.17  5311.8  390.50  5329.4  392.32  5449.3  400.10
#Mann=7,-1,0
  4768.1    0.12       0  4962.2     0.1       0  4995.4    0.07       0
  4999.4     0.1       0  5190.9    0.12       0  5274.6     0.1       0
  5311.8    0.12       0
Bank Sta=4995.4,4999.4
Exp/Cntr=0.3,0.1

Type RM Length L Ch R = 1,8768,361,361,361
BEGIN DESCRIPTION:
Caney Creek T 9 17.0
END DESCRIPTION:
XS GIS Cut Line= 3
      2760494.71      6771034.28      2760826.00      6771111.00
      2761332.34      6770863.17
#Sta/Elev= 30
  4660.1  419.86  4688.0  415.60  4764.1  404.79  4933.6  387.71  4969.4  385.37
  4976.2  377.99  4981.4  378.87  4987.9  376.36  4988.1  375.86  4991.9  376.36
  4997.6  380.22  5022.4  384.52  5036.7  384.82  5044.7  383.26  5053.6  384.57
  5059.2  379.10  5076.2  382.98  5081.7  378.55  5089.2  380.05  5098.7  384.76
  5104.2  379.41  5121.2  382.39  5126.7  378.95  5143.7  384.11  5268.3  386.13
  5345.3  390.82  5379.7  388.86  5469.9  388.87  5503.6  391.87  5563.9  396.16
#Mann=8,-1,0
  4660.1     0.1       0  4688.0    0.12       0  4987.9    0.07       0
  4991.9    0.12       0  5081.7     0.1       0  5268.3    0.12       0
  5379.7    0.05       0  5503.6    0.12       0
Bank Sta=4987.9,4991.9
Exp/Cntr=0.3,0.1

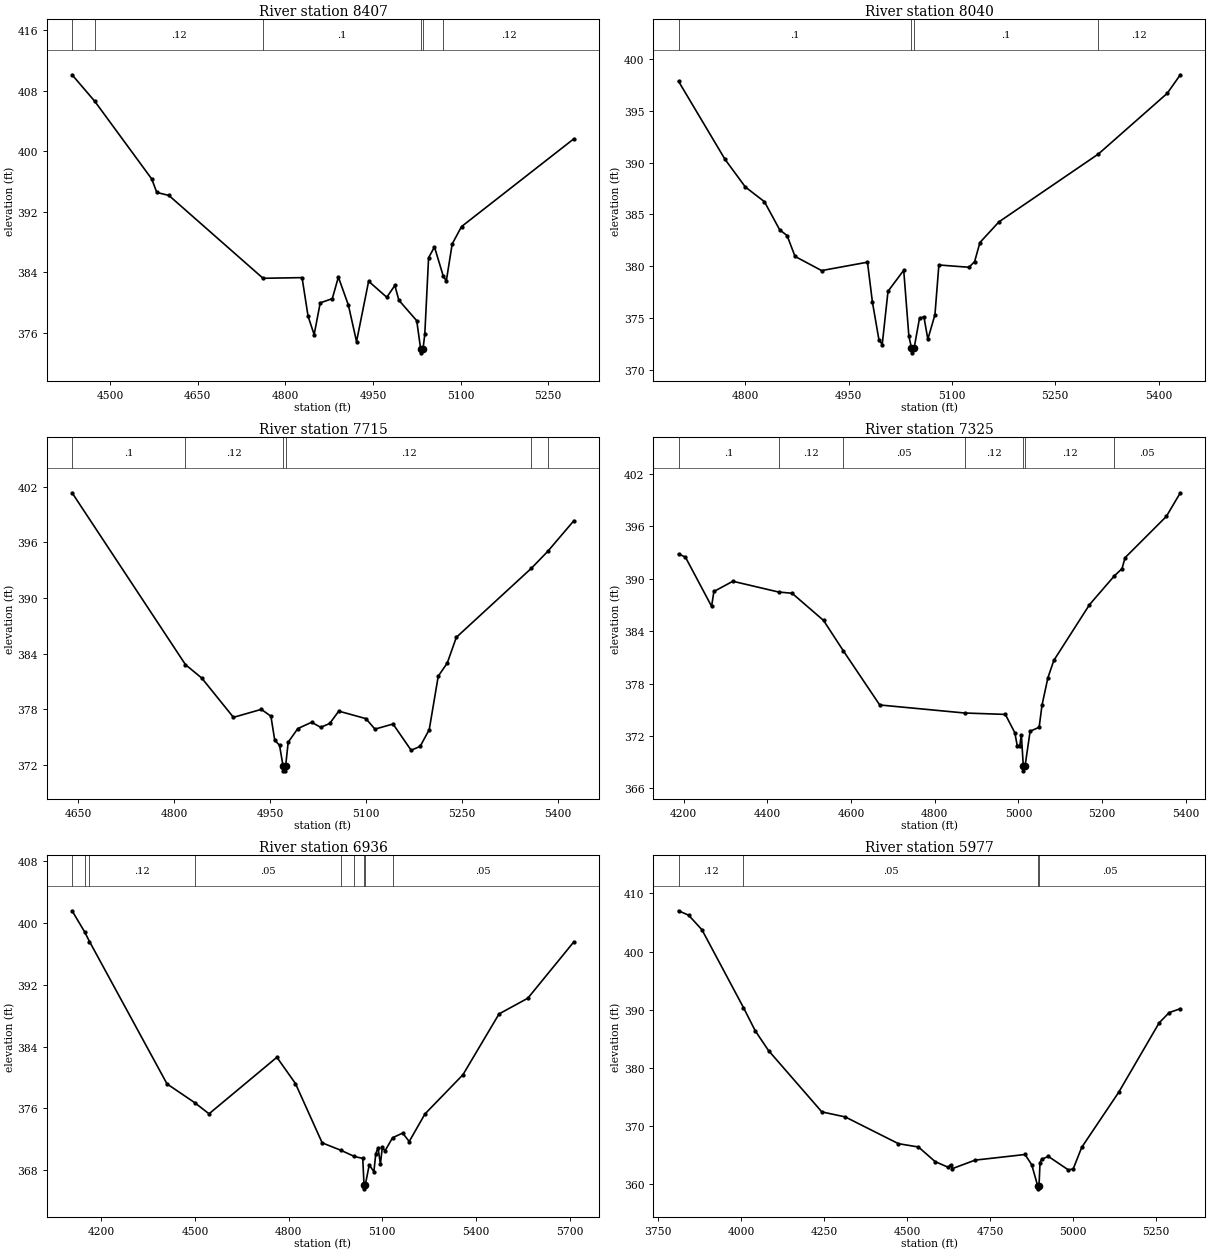
Type RM Length L Ch R = 1,8407,367,367,367
BEGIN DESCRIPTION:
Caney Creek T 9 16.0
END DESCRIPTION:
XS GIS Cut Line= 3
      2760476.00      6771161.00      2761026.00      6771311.00
      2761311.88      6771355.43
#Sta/Elev= 30
  4434.6  410.10  4473.5  406.59  4571.1  396.31  4579.7  394.54  4600.4  394.14
  4761.7  383.18  4828.5  383.27  4838.8  378.16  4849.2  375.73  4859.6  379.93
  4880.3  380.49  4890.7  383.34  4907.9  379.62  4921.8  374.81  4942.5  382.79
  4973.6  380.67  4987.4  382.23  4994.3  380.28  5024.9  377.57  5031.6  373.82
  5031.9  373.32  5035.6  373.82  5038.7  375.77  5045.2  385.91  5055.3  387.32
  5070.1  383.53  5075.5  382.80  5085.6  387.72  5101.6  390.02  5294.0  401.63
#Mann=6,-1,0
  4434.6     0.1       0  4473.5    0.12       0  4761.7     0.1       0
  5031.6    0.07       0  5035.6     0.1       0  5070.1    0.12       0
Bank Sta=5031.6,5035.6
Exp/Cntr=0.3,0.1

Type RM Length L Ch R = 1,8040,325,325,325
BEGIN DESCRIPTION:
Caney Creek T 9 15.0
END DESCRIPTION:
XS GIS Cut Line= 3
      2760526.04      6771361.02      2760789.63      6771497.00
      2761167.39      6771705.34
#Sta/Elev= 30
  4703.4  397.85  4770.9  390.31  4800.3  387.65  4828.0  386.23  4850.2  383.51
  4860.9  382.96  4872.4  380.95  4911.0  379.58  4977.5  380.39  4984.7  376.53
  4994.1  372.92  4998.9  372.44  5007.3  377.58  5030.1  379.61  5037.6  373.23
  5041.3  372.14  5041.5  371.64  5045.3  372.14  5053.0  374.98  5059.4  375.11
  5065.1  372.95  5075.4  375.32  5081.1  380.12  5124.7  379.90  5132.9  380.44
  5140.7  382.29  5168.2  384.28  5312.5  390.83  5412.4  396.69  5431.4  398.48
#Mann=4,-1,0
  4703.4     0.1       0  5041.3    0.07       0  5045.3     0.1       0
  5312.5    0.12       0
Bank Sta=5041.3,5045.3
Exp/Cntr=0.3,0.1

Type RM Length L Ch R = 1,7715,390,390,390
BEGIN DESCRIPTION:
Caney Creek T 9 14.0
END DESCRIPTION:
XS GIS Cut Line= 3
      2760425.99      6771460.99      2760626.00      6771761.00
      2760925.97      6772060.97
#Sta/Elev= 30
  4640.2  401.34  4817.6  382.80  4843.0  381.36  4892.6  377.12  4936.2  377.98
  4951.2  377.24  4957.2  374.64  4964.7  374.11  4970.2  371.85  4970.5  371.35
  4974.0  371.35  4974.2  371.85  4978.2  374.44  4993.3  375.91  5014.9  376.59
  5029.1  376.04  5043.2  376.46  5057.3  377.79  5099.8  376.98  5113.9  375.85
  5142.2  376.40  5170.5  373.57  5184.6  373.99  5198.8  375.79  5212.9  381.56
  5227.0  382.98  5241.2  385.75  5358.6  393.20  5384.4  395.04  5425.0  398.33
#Mann=6,-1,0
  4640.2     0.1       0  4817.6    0.12       0  4970.2    0.07       0
  4974.2    0.12       0  5358.6     0.1       0  5384.4    0.12       0
Bank Sta=4970.2,4974.2
Exp/Cntr=0.3,0.1

Type RM Length L Ch R = 1,7325,389,389,389
BEGIN DESCRIPTION:
Caney Creek T 9 13.0
END DESCRIPTION:
XS GIS Cut Line= 3
      2760175.07      6771378.55      2760526.00      6772111.00
      2760812.18      6772371.55
#Sta/Elev= 30
  4187.8  392.84  4204.3  392.47  4266.8  386.84  4272.3  388.54  4317.6  389.71
  4426.8  388.48  4459.1  388.34  4534.3  385.23  4581.2  381.78  4668.6  375.55
  4871.6  374.63  4968.8  374.47  4991.4  372.38  4997.2  370.91  5003.4  370.91
  5007.1  372.14  5011.8  368.51  5012.1  368.01  5015.8  368.51  5028.0  372.54
  5049.6  373.00  5056.4  375.52  5070.6  378.68  5084.8  380.66  5169.9  387.03
  5229.4  390.33  5247.6  391.15  5255.0  392.41  5353.7  397.14  5387.0  399.84
#Mann=7,-1,0
  4187.8     0.1       0  4426.8    0.12       0  4581.2    0.05       0
  4871.6    0.12       0  5011.8    0.07       0  5015.8    0.12       0
  5229.4    0.05       0
Bank Sta=5011.8,5015.8
Exp/Cntr=0.3,0.1

Type RM Length L Ch R = 1,6936,959,959,959
BEGIN DESCRIPTION:
Caney Creek T 9 12.0
END DESCRIPTION:
XS GIS Cut Line= 3
      2759947.64      6771347.05      2760176.00      6772211.00
      2760589.66      6772791.46
#Sta/Elev= 30
  4106.8  401.53  4147.2  398.79  4162.6  397.56  4410.8  379.17  4499.0  376.76
  4545.3  375.31  4762.5  382.61  4821.9  379.22  4907.5  371.56  4968.5  370.58
  5010.5  369.80  5037.3  369.55  5041.5  366.12  5041.7  365.62  5045.5  366.12
  5058.2  368.72  5073.0  367.82  5079.1  370.16  5086.4  370.93  5093.9  368.78
  5100.0  370.99  5108.6  370.52  5132.8  372.22  5165.2  372.82  5186.1  371.73
  5236.5  375.29  5358.2  380.36  5473.7  388.21  5565.9  390.24  5713.2  397.52
#Mann=9,-1,0
  4106.8    0.12       0  4147.2     0.1       0  4162.6    0.12       0
  4499.0    0.05       0  4968.5     0.1       0  5010.5    0.12       0
  5041.5    0.07       0  5045.5    0.12       0  5132.8    0.05       0
Bank Sta=5041.5,5045.5
Exp/Cntr=0.3,0.1

Type RM Length L Ch R = 1,5977,455,455,455
BEGIN DESCRIPTION:
Caney Creek T 9 11.0
END DESCRIPTION:
XS GIS Cut Line= 3
      2759612.15      6771520.72      2759523.56      6772705.61
      2759472.47      6773024.04
#Sta/Elev= 30
  3811.8  407.02  3842.2  406.26  3882.3  403.75  4007.2  390.37  4042.7  386.37
  4082.8  382.96  4243.3  372.41  4313.5  371.55  4473.9  366.94  4534.1  366.37
  4584.2  363.86  4624.3  362.86  4630.6  363.32  4635.7  362.64  4704.6  364.11
  4855.0  365.08  4875.0  363.33  4893.1  359.67  4893.3  359.17  4897.1  359.67
  4900.1  363.70  4905.2  364.26  4925.2  364.75  4985.3  362.43  5000.0  362.60
  5025.7  366.32  5137.1  375.80  5258.7  387.73  5289.0  389.50  5322.5  390.17
#Mann=4,-1,0
  3811.8    0.12       0  4007.2    0.05       0  4893.1    0.04       0
  4897.1    0.05       0
Bank Sta=4893.1,4897.1
Exp/Cntr=0.3,0.1

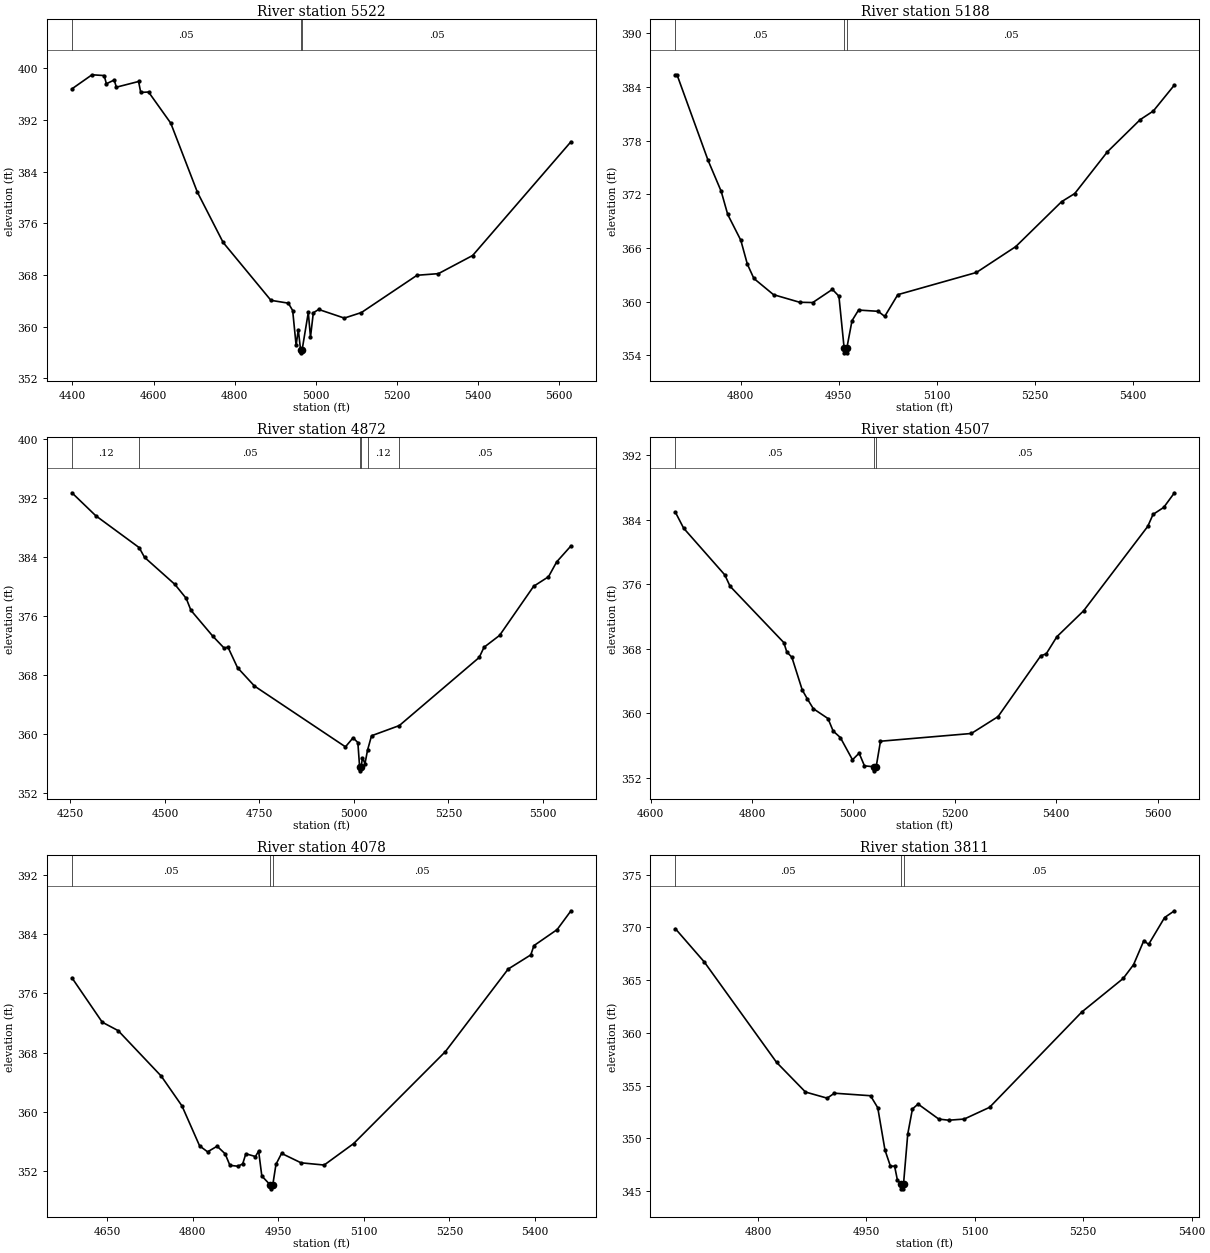
Type RM Length L Ch R = 1,5522,334,334,334
BEGIN DESCRIPTION:
Caney Creek T 9 10.0
END DESCRIPTION:
XS GIS Cut Line= 3
      2759112.08      6771802.96      2759326.00      6772361.00
      2759126.00      6772961.01
#Sta/Elev= 30
  4398.8  396.82  4448.3  399.00  4478.3  398.88  4483.7  397.61  4503.0  398.19
  4508.3  397.08  4563.1  397.96  4568.4  396.27  4587.7  396.33  4642.4  391.51
  4707.9  380.84  4771.5  373.04  4889.3  364.08  4932.2  363.64  4942.9  362.50
  4951.4  357.10  4956.7  359.54  4962.3  356.45  4962.6  355.95  4966.3  356.45
  4981.4  362.20  4986.8  358.39  4993.8  362.15  5007.0  362.67  5070.2  361.33
  5112.4  362.19  5249.4  367.96  5302.1  368.21  5386.5  371.02  5628.9  388.64
#Mann=3,-1,0
  4398.8    0.05       0  4962.3    0.04       0  4966.3    0.05       0
Bank Sta=4962.3,4966.3
Exp/Cntr=0.3,0.1

Type RM Length L Ch R = 1,5188,316,316,316
BEGIN DESCRIPTION:
Caney Creek T 9 9.0
END DESCRIPTION:
XS GIS Cut Line= 3
      2759026.00      6772161.01      2759026.00      6772461.00
      2759051.53      6772923.21
#Sta/Elev= 30
  4700.4  385.36  4702.9  385.36  4750.4  375.79  4770.4  372.34  4780.4  369.75
  4800.4  366.87  4810.4  364.20  4820.4  362.60  4850.4  360.79  4890.4  359.94
  4910.4  359.91  4940.4  361.38  4950.4  360.62  4958.4  354.79  4958.6  354.29
  4962.1  354.29  4962.4  354.79  4970.4  357.88  4980.4  359.07  5010.4  358.93
  5020.4  358.36  5040.4  360.79  5160.6  363.27  5220.7  366.16  5290.8  371.18
  5310.9  372.09  5360.9  376.76  5411.0  380.35  5431.0  381.31  5463.3  384.22
#Mann=3,-1,0
  4700.4    0.05       0  4958.4    0.04       0  4962.4    0.05       0
Bank Sta=4958.4,4962.4
Exp/Cntr=0.3,0.1

Type RM Length L Ch R = 1,4872,365,365,365
BEGIN DESCRIPTION:
Caney Creek T 9 8.0
END DESCRIPTION:
XS GIS Cut Line= 3
      2758835.72      6771809.53      2758776.00      6772561.00
      2758988.65      6773086.13
#Sta/Elev= 30
  4253.9  392.67  4317.0  389.56  4431.7  385.25  4446.0  383.93  4526.2  380.27
  4556.3  378.37  4568.7  376.76  4626.5  373.26  4656.6  371.64  4666.7  371.77
  4692.0  368.99  4736.9  366.50  4977.6  358.27  4997.7  359.49  5010.4  358.85
  5015.1  355.52  5015.3  355.02  5019.1  355.52  5022.5  356.79  5029.3  356.00
  5036.0  357.82  5046.6  359.77  5120.1  361.15  5331.4  370.37  5344.2  371.75
  5385.4  373.36  5475.5  380.01  5514.8  381.30  5536.4  383.31  5574.3  385.48
#Mann=6,-1,0
  4253.9    0.12       0  4431.7    0.05       0  5015.1    0.04       0
  5019.1    0.05       0  5036.0    0.12       0  5120.1    0.05       0
Bank Sta=5015.1,5019.1
Exp/Cntr=0.3,0.1

Type RM Length L Ch R = 1,4507,429,429,429
BEGIN DESCRIPTION:
Caney Creek T 9 7.0
END DESCRIPTION:
XS GIS Cut Line= 3
      2758412.52      6772114.95      2758476.00      6772461.00
      2758676.01      6773061.02
#Sta/Elev= 30
  4649.0  384.93  4665.3  382.95  4746.5  377.16  4756.8  375.76  4862.9  368.77
  4868.7  367.62  4878.8  366.95  4899.2  362.90  4909.3  361.79  4921.1  360.58
  4950.0  359.36  4960.2  357.81  4974.3  357.01  4998.3  354.25  5011.4  355.07
  5021.9  353.50  5041.0  353.38  5041.2  352.88  5045.0  353.38  5053.5  356.55
  5232.7  357.51  5285.4  359.60  5369.8  367.15  5380.3  367.37  5401.4  369.50
  5454.1  372.71  5580.6  383.17  5591.1  384.66  5612.2  385.53  5633.3  387.34
#Mann=3,-1,0
  4649.0    0.05       0  5041.0    0.04       0  5045.0    0.05       0
Bank Sta=5041,5045
Exp/Cntr=0.3,0.1

Type RM Length L Ch R = 1,4078,267,267,267
BEGIN DESCRIPTION:
Caney Creek T 9 6.0
END DESCRIPTION:
XS GIS Cut Line= 3
      2758076.01      6772361.02      2758226.00      6772661.00
      2758449.77      6773151.04
#Sta/Elev= 30
  4588.7  378.11  4641.8  372.12  4669.7  370.98  4745.2  364.84  4781.5  360.82
  4812.3  355.44  4826.3  354.63  4843.0  355.39  4857.0  354.37  4865.4  352.81
  4879.4  352.69  4887.8  353.01  4893.3  354.37  4910.1  354.00  4915.7  354.73
  4921.3  351.37  4936.4  350.14  4936.6  349.64  4940.4  350.14  4946.1  352.95
  4955.9  354.42  4990.0  353.15  5030.5  352.85  5082.0  355.74  5242.9  368.16
  5352.8  379.29  5392.4  381.20  5397.9  382.45  5438.5  384.61  5462.8  387.15
#Mann=3,-1,0
  4588.7    0.05       0  4936.4    0.04       0  4940.4    0.05       0
Bank Sta=4936.4,4940.4
Exp/Cntr=0.3,0.1

Type RM Length L Ch R = 1,3811,580,580,580
BEGIN DESCRIPTION:
Caney Creek T 9 5.0
END DESCRIPTION:
XS GIS Cut Line= 3
      2758026.00      6772460.99      2758026.00      6772761.00
      2758275.99      6773060.99
#Sta/Elev= 30
  4685.6  369.87  4725.6  366.72  4825.6  357.21  4865.6  354.40  4895.6  353.82
  4905.6  354.29  4955.6  354.05  4965.6  352.91  4975.6  348.90  4983.1  347.38
  4988.9  347.38  4992.8  346.06  4997.3  345.73  4997.5  345.23  5001.0  345.23
  5001.3  345.73  5007.1  350.42  5013.6  352.80  5021.4  353.26  5050.0  351.84
  5063.7  351.73  5085.2  351.84  5120.3  352.95  5247.9  361.98  5305.2  365.16
  5319.5  366.46  5333.8  368.75  5340.3  368.38  5362.5  370.93  5376.1  371.57
#Mann=3,-1,0
  4685.6    0.05       0  4997.3    0.04       0  5001.3    0.05       0
Bank Sta=4997.3,5001.3
Exp/Cntr=0.3,0.1

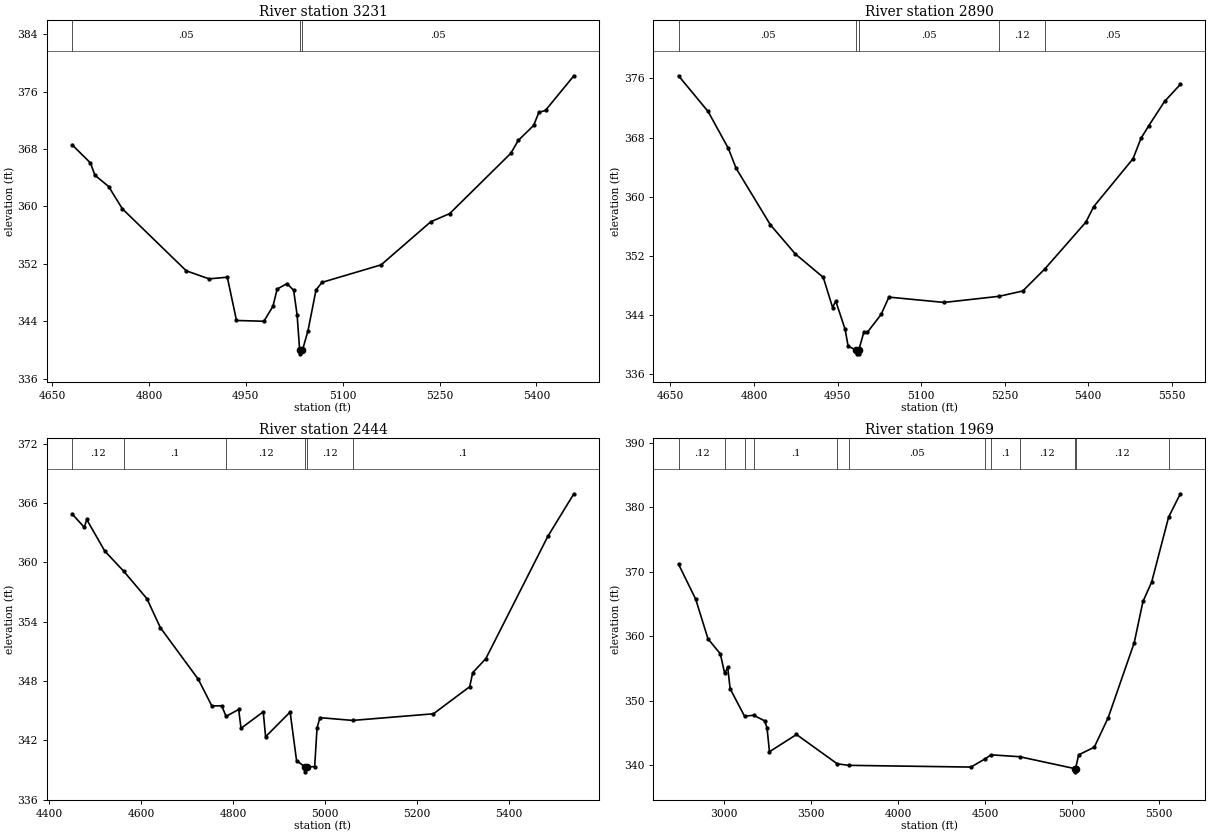
Type RM Length L Ch R = 1,3231,341,341,341
BEGIN DESCRIPTION:
Caney Creek T 9 4.0
END DESCRIPTION:
XS GIS Cut Line= 3
      2757525.97      6772860.97      2757753.31      6773084.89
      2758175.99      6773261.00
#Sta/Elev= 30
  4680.9  368.59  4709.2  366.07  4716.3  364.34  4737.5  362.77  4758.7  359.67
  4857.7  351.02  4893.0  349.90  4921.3  350.13  4935.5  344.10  4977.9  343.99
  4992.0  346.08  4998.4  348.47  5013.7  349.24  5024.0  348.30  5029.4  344.85
  5033.3  339.95  5033.6  339.45  5037.6  339.95  5046.2  342.67  5058.7  348.37
  5067.9  349.41  5159.4  351.85  5236.4  357.86  5265.6  358.99  5360.4  367.41
  5371.8  369.19  5395.6  371.28  5403.7  373.09  5414.0  373.38  5457.9  378.20
#Mann=3,-1,0
  4680.9    0.05       0  5033.3    0.04       0  5037.6    0.05       0
Bank Sta=5033.3,5037.6
Exp/Cntr=0.3,0.1

Type RM Length L Ch R = 1,2890,446,446,446
BEGIN DESCRIPTION:
Caney Creek T 9 3.0
END DESCRIPTION:
XS GIS Cut Line= 3
      2757326.01      6772961.02      2757476.00      6773261.00
      2757876.02      6773661.02
#Sta/Elev= 30
  4664.5  376.35  4717.6  371.52  4753.9  366.54  4767.9  363.84  4829.4  356.20
  4874.1  352.27  4924.4  349.09  4941.2  345.01  4946.8  345.89  4963.6  342.07
  4969.1  339.77  4983.8  339.25  4984.1  338.75  4987.7  338.75  4988.1  339.25
  4997.1  341.64  5003.4  341.64  5028.2  344.07  5042.3  346.42  5141.3  345.70
  5240.2  346.53  5282.7  347.25  5322.4  350.24  5395.9  356.55  5410.0  358.65
  5480.7  365.14  5494.9  367.88  5509.0  369.61  5537.3  372.88  5565.6  375.18
#Mann=5,-1,0
  4664.5    0.05       0  4983.8    0.04       0  4988.1    0.05       0
  5240.2    0.12       0  5322.4    0.05       0
Bank Sta=4983.8,4988.1
Exp/Cntr=0.3,0.1

Type RM Length L Ch R = 1,2444,475,475,475
BEGIN DESCRIPTION:
Caney Creek T 9 2.0
END DESCRIPTION:
XS GIS Cut Line= 3
      2757125.99      6772960.95      2757226.00      6773511.00
      2757626.02      6773861.02
#Sta/Elev= 30
  4449.9  364.90  4476.6  363.53  4481.7  364.33  4521.1  361.13  4562.3  359.09
  4612.6  356.32  4641.8  353.39  4724.4  348.16  4753.6  345.48  4775.2  345.49
  4784.6  344.42  4812.0  345.12  4817.1  343.21  4865.4  344.88  4870.5  342.36
  4923.8  344.86  4937.8  339.95  4956.0  339.31  4956.3  338.81  4960.3  339.31
  4977.2  339.34  4982.3  343.25  4988.6  344.29  5059.7  344.01  5235.3  344.68
  5314.1  347.42  5320.7  348.84  5349.2  350.26  5484.0  362.63  5540.5  366.93
#Mann=6,-1,0
  4449.9    0.12       0  4562.3     0.1       0  4784.6    0.12       0
  4956.0    0.07       0  4960.3    0.12       0  5059.7     0.1       0
Bank Sta=4956,4960.3
Exp/Cntr=0.3,0.1

Type RM Length L Ch R = 1,1969,0,0,0
BEGIN DESCRIPTION:
Caney Creek T 9 1.0
END DESCRIPTION:
XS GIS Cut Line= 3
      2755575.97      6772360.97      2757176.00      6773961.00
      2757801.07      6773953.17
#Sta/Elev= 30
  2736.8  371.17  2835.8  365.72  2906.5  359.57  2977.3  357.25  3002.4  354.20
  3019.7  355.16  3033.8  351.83  3116.6  347.56  3168.8  347.71  3231.8  346.85
  3246.0  345.78  3260.1  342.04  3415.7  344.72  3649.9  340.17  3715.5  339.93
  4419.8  339.66  4501.2  340.94  4535.7  341.56  4699.6  341.27  5017.4  339.42
  5017.8  338.92  5021.7  339.42  5039.6  341.56  5129.6  342.75  5209.6  347.34
  5359.6  359.00  5409.6  365.38  5459.6  368.38  5557.3  378.49  5624.7  382.11
#Mann=12,-1,0
  2736.8    0.12       0  3002.4     0.1       0  3116.6    0.12       0
  3168.8     0.1       0  3649.9    0.12       0  3715.5    0.05       0
  4501.2    0.12       0  4535.7     0.1       0  4699.6    0.12       0
  5017.4    0.07       0  5021.7    0.12       0  5557.3     0.1       0
Bank Sta=5017.4,5021.7
Exp/Cntr=0.3,0.1

Chan Stop Cuts=-1