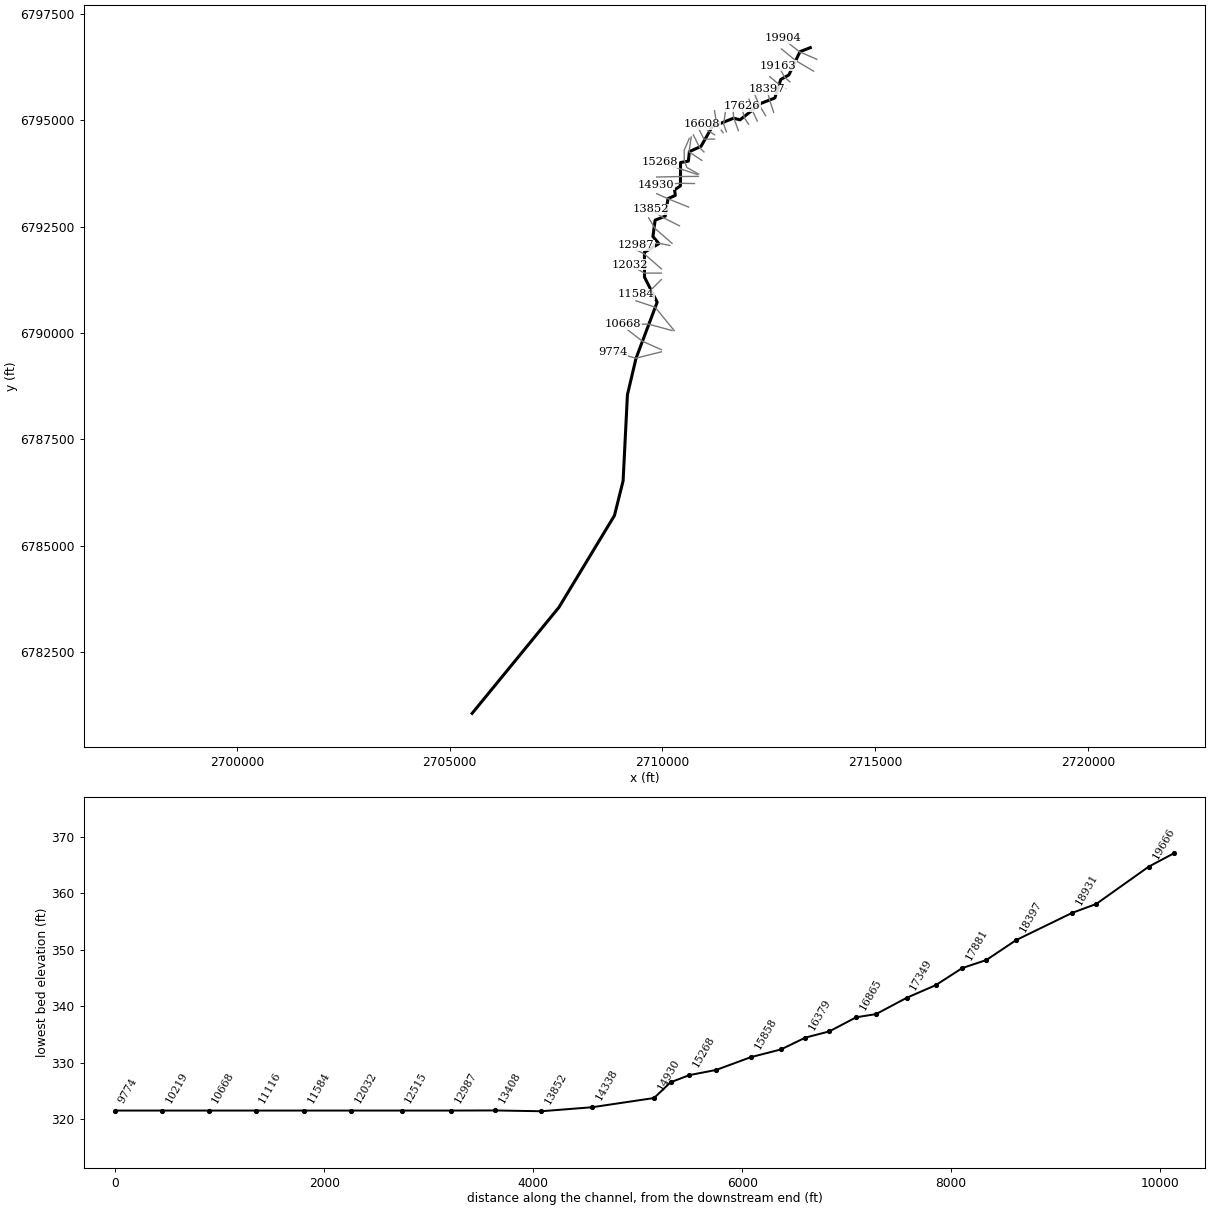
--- Cedar Branch.prj (project) ---

Proj Title=Cedar Branch Base Level Engineering
Current Plan=p01
Default Exp/Contr=0.3,0.1
English Units
Geom File=g01
Flow File=f01
Plan File=p01
Y Axis Title=Elevation
X Axis Title(PF)=Main Channel Distance
X Axis Title(XS)=Station
BEGIN DESCRIPTION:
Cedar Branch
END DESCRIPTION:
DSS Export Rating Curves= 0
DSS Export Rating Curve Sorted= 0
DSS Export Volume Flow Curves= 0
DXF OffsetX= 0
DXF OffsetY= 0
DXF ScaleX= 1
DXF ScaleY= 10

--- Cedar Branch.p01 (plan) ---

Plan Title=Multiple Run
Short Identifier=Multiple
Geom File=g01
Flow File=f01
Subcritical Flow
K Sum by GR= 0
Std Step Tol= 0.01
Critical Tol= 0.01
Num of Std Step Trials= 20
Max Error Tol= 0.3
Flow Tol Ratio= 0.001
Split Flow NTrial= 30
Split Flow Tol= 0.02
Split Flow Ratio= 0.02
Log Output Level= 0
Friction Slope Method= 1
Unsteady Friction Slope Method= 2
Unsteady Bridges Friction Slope Method= 1
Parabolic Critical Depth
Global Vel Dist=  1 , 1 , 1
Global Log Level= 0
CheckData=True
Encroach Param= -1, 0, 0, 0
BEGIN DESCRIPTION:
Multiple Run
END DESCRIPTION:

--- Cedar Branch.f01 (steady flow) ---

Flow Title=Multiple
Number of Profiles=7
Profile Names=10-year,25-year,50-year,1pct_min,100-year,1pct_plu,500-year
River Rch & RM= Cedar Branch,Reach-1,19904
     214     268     309     178     354     707     464
River Rch & RM= Cedar Branch,Reach-1,16145
     453     599     715     425     848    1692    1189
River Rch & RM= Cedar Branch,Reach-1,15268
     712     965    1171     705    1406    2806    2027
River Rch & RM= Cedar Branch,Reach-1,14338
     775    1057    1288     778    1553    3098    2257
River Rch & RM= Cedar Branch,Reach-1,12987
     886    1212    1479     895    1785    3562    2600
River Rch & RM= Cedar Branch,Reach-1,11116
    1120    1546    1900    1155    2304    4597    3391
River Rch & RM= Cedar Branch,Reach-1,9289
    1242    1714    2106    1279    2552    5092    3751
River Rch & RM= Cedar Branch,Reach-1,6007
    1221    1669    2036    1226    2447    4882    3537
Boundary for River Rch & Prof#=Cedar Branch,Reach-1,1
Up Type=0
Dn Type=3
Dn Slope=0.005
Boundary for River Rch & Prof#=Cedar Branch,Reach-1,2
Up Type=0
Dn Type=3
Dn Slope=0.005
Boundary for River Rch & Prof#=Cedar Branch,Reach-1,3
Up Type=0
Dn Type=3
Dn Slope=0.005
Boundary for River Rch & Prof#=Cedar Branch,Reach-1,4
Up Type=0
Dn Type=3
Dn Slope=0.005
Boundary for River Rch & Prof#=Cedar Branch,Reach-1,5
Up Type=0
Dn Type=3
Dn Slope=0.005
Boundary for River Rch & Prof#=Cedar Branch,Reach-1,6
Up Type=0
Dn Type=3
Dn Slope=0.005
Boundary for River Rch & Prof#=Cedar Branch,Reach-1,7
Up Type=0
Dn Type=3
Dn Slope=0.005

--- Cedar Branch.g01 (geometry) ---

Geom Title=Existing Conditions

River Reach=Cedar Branch,Reach-1
Reach XY= 30
      2713476.00      6796711.00      2713233.85      6796617.19
      2712972.50      6796069.46      2712781.73      6795963.55
      2712642.72      6795527.63      2712319.55      6795403.25
      2711824.41      6795014.68      2711672.59      6795053.19
      2711169.93      6794852.85      2710906.42      6794390.42
      2710633.80      6794267.21      2710609.57      6794043.38
      2710426.00      6794011.00      2710422.55      6793462.25
      2710285.03      6793368.01      2710303.49      6793237.05
      2710131.34      6793163.74      2710065.64      6792750.84
      2709827.88      6792655.31      2709776.56      6792271.61
      2709917.18      6792104.00      2709577.04      6791900.56
      2709578.26      6791316.94      2709875.97      6790726.42
      2709378.26      6789405.06      2709177.22      6788550.50
      2709075.48      6786526.22      2708872.38      6785712.50
      2707567.84      6783554.95      2705526.00      6781061.00

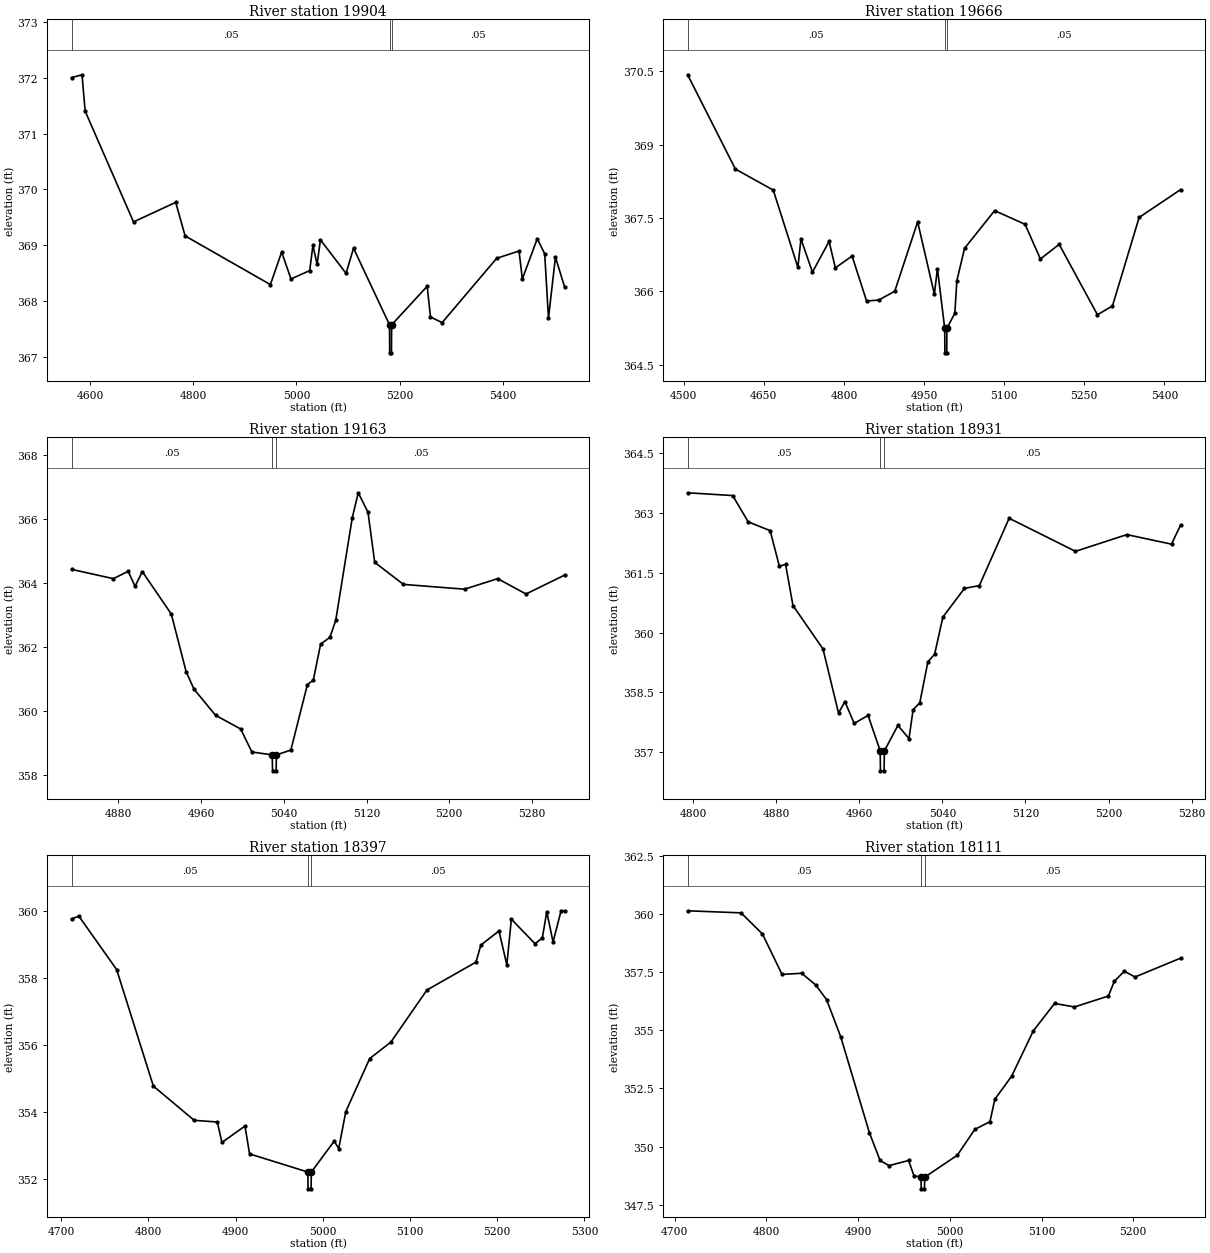
Type RM Length L Ch R = 1,19904,238,238,238
BEGIN DESCRIPTION:
Cedar Branch 49.0
END DESCRIPTION:
XS GIS Cut Line= 3
      2713630.08      6796438.38      2713226.00      6796611.00
      2712821.47      6796930.36
#Sta/Elev= 30
  4564.5  372.00  4584.6  372.05  4590.7  371.40  4684.4  369.42  4766.1  369.77
  4784.3  369.17  4949.5  368.30  4971.3  368.88  4989.4  368.40  5025.6  368.55
  5031.9  369.00  5040.0  368.66  5046.4  369.10  5096.1  368.50  5110.5  368.95
  5180.3  367.58  5180.5  367.08  5184.0  367.08  5184.3  367.58  5253.2  368.27
  5259.6  367.72  5282.1  367.62  5387.8  368.77  5431.1  368.90  5437.5  368.40
  5466.4  369.12  5480.8  368.85  5488.1  367.70  5501.6  368.79  5519.3  368.26
#Mann=3,-1,0
  4564.5    0.05       0  5180.3    0.04       0  5184.3    0.05       0
Bank Sta=5180.3,5184.3
Exp/Cntr=0.3,0.1

Type RM Length L Ch R = 1,19666,503,503,503
BEGIN DESCRIPTION:
Cedar Branch 48.0
END DESCRIPTION:
XS GIS Cut Line= 3
      2713554.10      6796158.19      2713126.00      6796411.00
      2712797.72      6796682.53
#Sta/Elev= 30
  4507.2  370.43  4596.7  368.50  4667.6  368.07  4713.7  366.49  4719.5  367.07
  4741.0  366.39  4772.1  367.02  4783.9  366.48  4815.2  366.72  4842.4  365.80
  4865.0  365.82  4895.1  366.00  4938.0  367.42  4969.3  365.94  4975.1  366.46
  4988.7  365.24  4989.0  364.74  4992.5  364.74  4992.7  365.24  5007.6  365.55
  5011.5  366.22  5025.9  366.88  5082.2  367.65  5139.2  367.37  5167.9  366.66
  5203.0  366.96  5274.7  365.52  5302.9  365.70  5352.8  367.51  5430.4  368.08
#Mann=3,-1,0
  4507.2    0.05       0  4988.7    0.04       0  4992.7    0.05       0
Bank Sta=4988.7,4992.7
Exp/Cntr=0.3,0.1

Type RM Length L Ch R = 1,19163,232,232,232
BEGIN DESCRIPTION:
Cedar Branch 47.0
END DESCRIPTION:
XS GIS Cut Line= 3
      2712997.91      6795906.46      2712876.00      6796011.00
      2712721.99      6796287.05
#Sta/Elev= 30
  4834.8  364.43  4875.2  364.14  4889.5  364.37  4896.1  363.90  4903.2  364.36
  4931.2  363.03  4945.5  361.23  4953.1  360.68  4974.0  359.86  4998.3  359.43
  5009.1  358.71  5028.8  358.62  5029.1  358.12  5032.6  358.12  5032.8  358.62
  5046.8  358.77  5062.8  360.82  5068.5  360.96  5075.6  362.09  5084.5  362.30
  5090.2  362.83  5106.2  366.05  5112.0  366.83  5121.4  366.22  5127.9  364.65
  5155.7  363.96  5214.8  363.81  5246.8  364.14  5274.2  363.66  5311.5  364.25
#Mann=3,-1,0
  4834.8    0.05       0  5028.8    0.05       0  5032.8    0.05       0
Bank Sta=5028.8,5032.8
Exp/Cntr=0.3,0.1

Type RM Length L Ch R = 1,18931,534,534,534
BEGIN DESCRIPTION:
Cedar Branch 46.0
END DESCRIPTION:
XS GIS Cut Line= 3
      2712900.19      6795743.98      2712726.00      6795861.00
      2712522.14      6796029.76
#Sta/Elev= 30
  4794.8  363.51  4838.2  363.44  4853.1  362.78  4874.2  362.56  4883.1  361.67
  4889.1  361.71  4896.2  360.68  4925.1  359.59  4940.1  357.98  4946.2  358.27
  4955.1  357.72  4968.5  357.92  4980.2  357.03  4980.4  356.53  4983.9  356.53
  4984.2  357.03  4997.2  357.67  5007.9  357.34  5011.8  358.06  5018.3  358.24
  5026.1  359.27  5032.6  359.46  5040.5  360.39  5061.3  361.11  5075.6  361.18
  5104.3  362.87  5168.1  362.04  5217.6  362.46  5260.6  362.22  5269.3  362.70
#Mann=3,-1,0
  4794.8    0.05       0  4980.2    0.04       0  4984.2    0.05       0
Bank Sta=4980.2,4984.2
Exp/Cntr=0.3,0.1

Type RM Length L Ch R = 1,18397,286,286,286
BEGIN DESCRIPTION:
Cedar Branch 45.0
END DESCRIPTION:
XS GIS Cut Line= 3
      2712614.91      6795192.00      2712526.00      6795461.00
      2712455.40      6795733.80
#Sta/Elev= 30
  4712.1  359.76  4720.4  359.84  4763.7  358.25  4805.8  354.78  4852.6  353.76
  4879.1  353.71  4884.4  353.10  4910.8  353.59  4916.1  352.76  4982.9  352.22
  4983.1  351.72  4986.6  351.72  4986.9  352.22  5013.1  353.14  5018.3  352.92
  5026.4  354.02  5053.8  355.60  5078.1  356.09  5119.4  357.64  5175.6  358.47
  5181.3  358.98  5202.0  359.40  5211.0  358.39  5216.2  359.75  5243.3  359.02
  5251.7  359.19  5256.8  359.97  5264.0  359.07  5273.2  360.00  5277.2  360.00
#Mann=3,-1,0
  4712.1    0.05       0  4982.9    0.04       0  4986.9    0.05       0
Bank Sta=4982.9,4986.9
Exp/Cntr=0.3,0.1

Type RM Length L Ch R = 1,18111,230,230,230
BEGIN DESCRIPTION:
Cedar Branch 44.0
END DESCRIPTION:
XS GIS Cut Line= 3
      2712425.98      6795111.03      2712276.00      6795361.00
      2712179.82      6795587.51
#Sta/Elev= 30
  4714.0  360.15  4772.3  360.06  4795.6  359.15  4817.0  357.41  4838.4  357.46
  4853.9  356.95  4865.6  356.32  4881.1  354.71  4912.2  350.60  4923.9  349.40
  4933.6  349.18  4955.0  349.40  4960.8  348.75  4968.5  348.68  4968.8  348.18
  4972.3  348.18  4972.5  348.68  5008.2  349.63  5027.2  350.74  5043.7  351.07
  5049.1  352.04  5067.4  353.03  5091.0  354.98  5114.2  356.16  5135.9  356.01
  5172.9  356.48  5179.3  357.11  5190.2  357.55  5201.9  357.30  5251.6  358.11
#Mann=3,-1,0
  4714.0    0.05       0  4968.5    0.04       0  4972.5    0.05       0
Bank Sta=4968.5,4972.5
Exp/Cntr=0.3,0.1

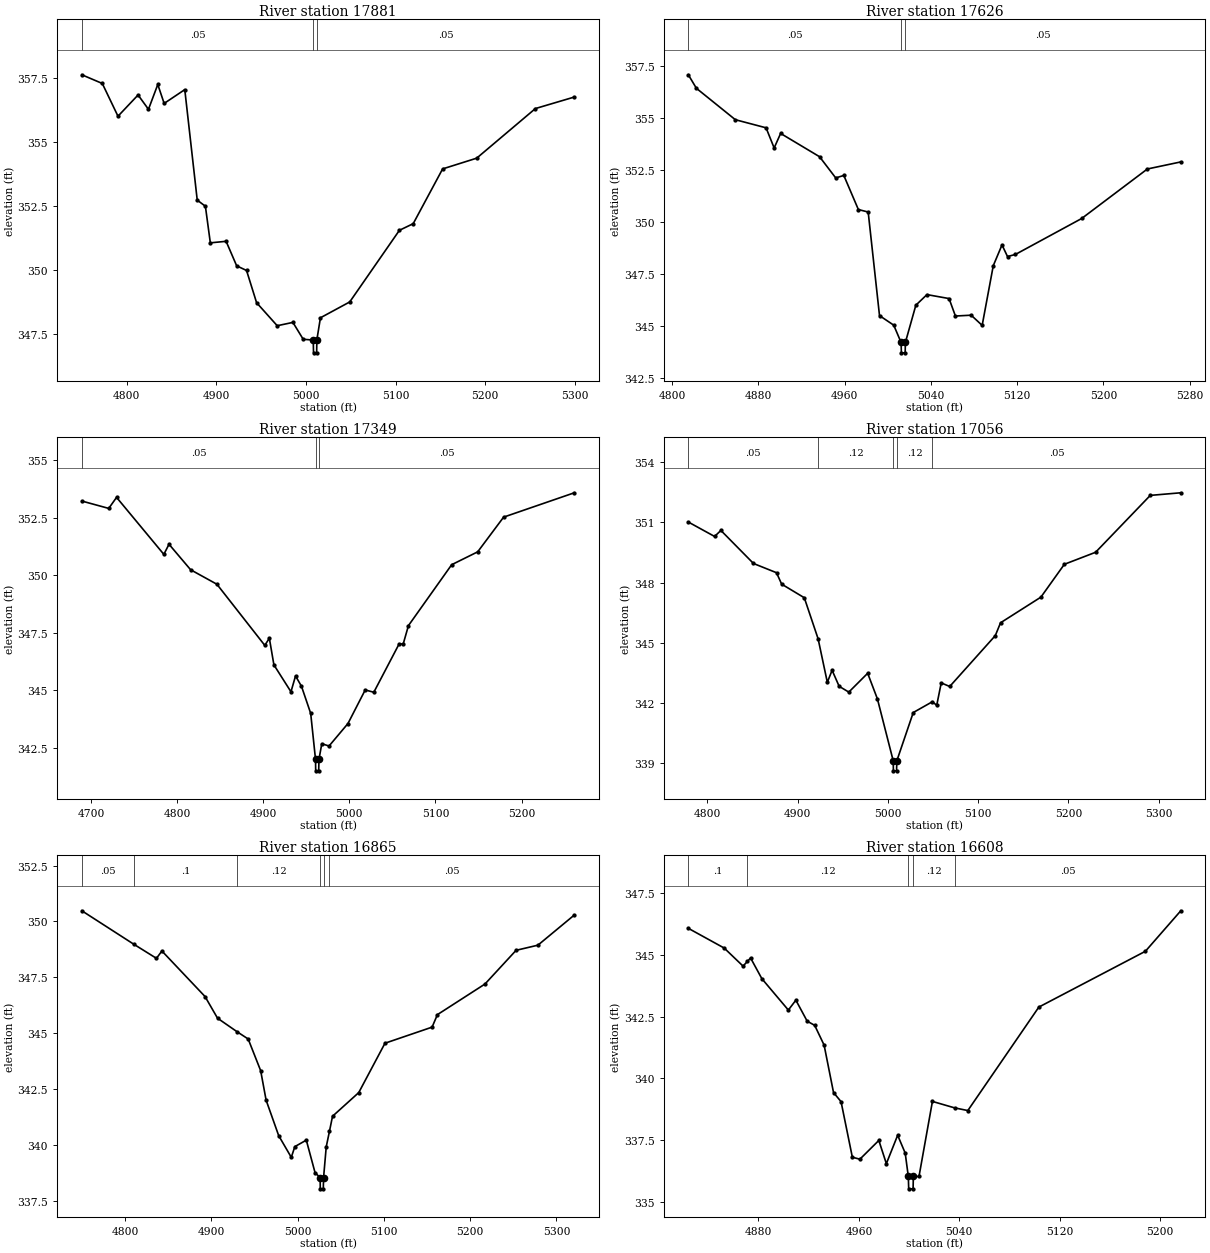
Type RM Length L Ch R = 1,17881,255,255,255
BEGIN DESCRIPTION:
Cedar Branch 43.0
END DESCRIPTION:
XS GIS Cut Line= 3
      2712229.86      6794983.96      2712126.00      6795211.00
      2712038.33      6795497.52
#Sta/Elev= 30
  4750.1  357.63  4772.9  357.29  4790.4  356.01  4812.8  356.84  4824.4  356.28
  4834.8  357.25  4841.9  356.51  4864.9  357.05  4878.8  352.73  4887.9  352.49
  4893.4  351.06  4911.0  351.12  4922.8  350.16  4933.8  349.98  4945.0  348.72
  4968.0  347.82  4985.5  347.95  4997.0  347.29  5008.2  347.26  5008.5  346.76
  5012.0  346.76  5012.2  347.26  5016.2  348.13  5048.9  348.75  5104.3  351.55
  5119.7  351.81  5152.5  353.95  5190.5  354.37  5256.0  356.31  5299.4  356.76
#Mann=3,-1,0
  4750.1    0.05       0  5008.2    0.04       0  5012.2    0.05       0
Bank Sta=5008.2,5012.2
Exp/Cntr=0.3,0.1

Type RM Length L Ch R = 1,17626,277,277,277
BEGIN DESCRIPTION:
Cedar Branch 42.0
END DESCRIPTION:
XS GIS Cut Line= 3
      2712026.00      6794910.99      2711926.00      6795061.00
      2711865.17      6795330.64
#Sta/Elev= 30
  4815.1  357.09  4822.6  356.44  4858.7  354.93  4887.2  354.54  4894.7  353.57
  4900.7  354.27  4936.8  353.15  4951.8  352.13  4959.3  352.25  4972.8  350.61
  4981.9  350.49  4992.4  345.51  5005.6  345.05  5012.4  344.22  5012.7  343.72
  5016.2  343.72  5016.4  344.22  5026.1  346.01  5036.4  346.52  5056.9  346.33
  5062.8  345.49  5077.4  345.53  5087.6  345.04  5097.9  347.91  5106.0  348.91
  5111.1  348.35  5118.4  348.45  5179.9  350.18  5240.8  352.56  5271.8  352.90
#Mann=3,-1,0
  4815.1    0.05       0  5012.4    0.04       0  5016.4    0.05       0
Bank Sta=5012.4,5016.4
Exp/Cntr=0.3,0.1

Type RM Length L Ch R = 1,17349,293,293,293
BEGIN DESCRIPTION:
Cedar Branch 41.0
END DESCRIPTION:
XS GIS Cut Line= 3
      2711786.24      6794761.71      2711676.00      6795061.00
      2711652.27      6795312.74
#Sta/Elev= 30
  4689.4  353.23  4720.6  352.91  4729.7  353.39  4784.6  350.91  4790.6  351.35
  4815.7  350.24  4846.2  349.61  4901.8  346.95  4907.1  347.26  4912.4  346.10
  4932.2  344.93  4937.5  345.62  4944.4  345.17  4955.1  343.99  4960.7  341.99
  4960.9  341.49  4964.4  341.49  4964.7  341.99  4968.0  342.67  4976.4  342.57
  4998.4  343.55  5018.4  345.01  5028.4  344.91  5057.6  347.00  5062.6  347.02
  5068.6  347.81  5118.8  350.46  5149.0  351.02  5179.1  352.53  5261.2  353.59
#Mann=3,-1,0
  4689.4    0.05       0  4960.7    0.04       0  4964.7    0.05       0
Bank Sta=4960.7,4964.7
Exp/Cntr=0.3,0.1

Type RM Length L Ch R = 1,17056,191,191,191
BEGIN DESCRIPTION:
Cedar Branch 40.0
END DESCRIPTION:
XS GIS Cut Line= 3
      2711503.70      6794733.58      2711439.14      6794914.49
      2711489.14      6795264.45
#Sta/Elev= 30
  4778.9  351.02  4808.0  350.30  4815.0  350.60  4851.1  348.95  4876.6  348.49
  4882.3  347.92  4907.4  347.24  4922.7  345.19  4932.9  343.02  4938.2  343.62
  4946.0  342.82  4956.7  342.53  4977.6  343.47  4988.4  342.19  5005.9  339.10
  5006.1  338.60  5009.6  338.60  5009.9  339.10  5028.1  341.51  5049.3  342.05
  5054.1  341.87  5059.1  342.99  5068.5  342.81  5119.0  345.35  5124.8  345.99
  5169.5  347.27  5195.5  348.91  5230.1  349.51  5290.7  352.35  5324.5  352.48
#Mann=5,-1,0
  4778.9    0.05       0  4922.7    0.12       0  5005.9    0.07       0
  5009.9    0.12       0  5049.3    0.05       0
Bank Sta=5005.9,5009.9
Exp/Cntr=0.3,0.1

Type RM Length L Ch R = 1,16865,257,257,257
BEGIN DESCRIPTION:
Cedar Branch 39.0
END DESCRIPTION:
XS GIS Cut Line= 3
      2711426.03      6794710.96      2711276.00      6794911.00
      2711224.17      6795227.64
#Sta/Elev= 30
  4749.9  350.48  4809.8  348.99  4836.4  348.35  4842.7  348.68  4892.7  346.64
  4907.2  345.67  4930.0  345.06  4942.7  344.74  4957.2  343.32  4963.5  342.00
  4978.1  340.41  4992.7  339.44  4996.8  339.92  5010.1  340.21  5020.2  338.76
  5026.1  338.53  5026.3  338.03  5029.8  338.03  5030.1  338.53  5033.2  339.91
  5036.9  340.60  5040.5  341.28  5070.9  342.34  5101.3  344.55  5155.9  345.27
  5162.1  345.83  5217.2  347.20  5253.3  348.71  5278.6  348.94  5320.8  350.29
#Mann=6,-1,0
  4749.9    0.05       0  4809.8     0.1       0  4930.0    0.12       0
  5026.1    0.07       0  5030.1    0.12       0  5036.9    0.05       0
Bank Sta=5026.1,5030.1
Exp/Cntr=0.3,0.1

Type RM Length L Ch R = 1,16608,229,229,229
BEGIN DESCRIPTION:
Cedar Branch 38.0
END DESCRIPTION:
XS GIS Cut Line= 3
      2711226.03      6794660.98      2711076.00      6794761.00
      2710926.03      6794910.97
#Sta/Elev= 30
  4824.1  346.08  4852.7  345.28  4867.7  344.55  4871.2  344.74  4873.7  344.88
  4882.7  344.04  4903.8  342.77  4909.8  343.17  4918.8  342.32  4924.8  342.15
  4932.3  341.35  4939.8  339.43  4945.8  339.06  4954.8  336.81  4960.8  336.73
  4975.9  337.49  4981.9  336.55  4990.9  337.70  4996.9  336.98  4999.4  336.03
  4999.7  335.53  5003.2  335.53  5003.4  336.03  5007.9  336.03  5018.6  339.07
  5036.2  338.81  5046.8  338.70  5103.4  342.89  5188.3  345.15  5216.5  346.79
#Mann=5,-1,0
  4824.1     0.1       0  4871.2    0.12       0  4999.4    0.07       0
  5003.4    0.12       0  5036.2    0.05       0
Bank Sta=4999.4,5003.4
Exp/Cntr=0.3,0.1

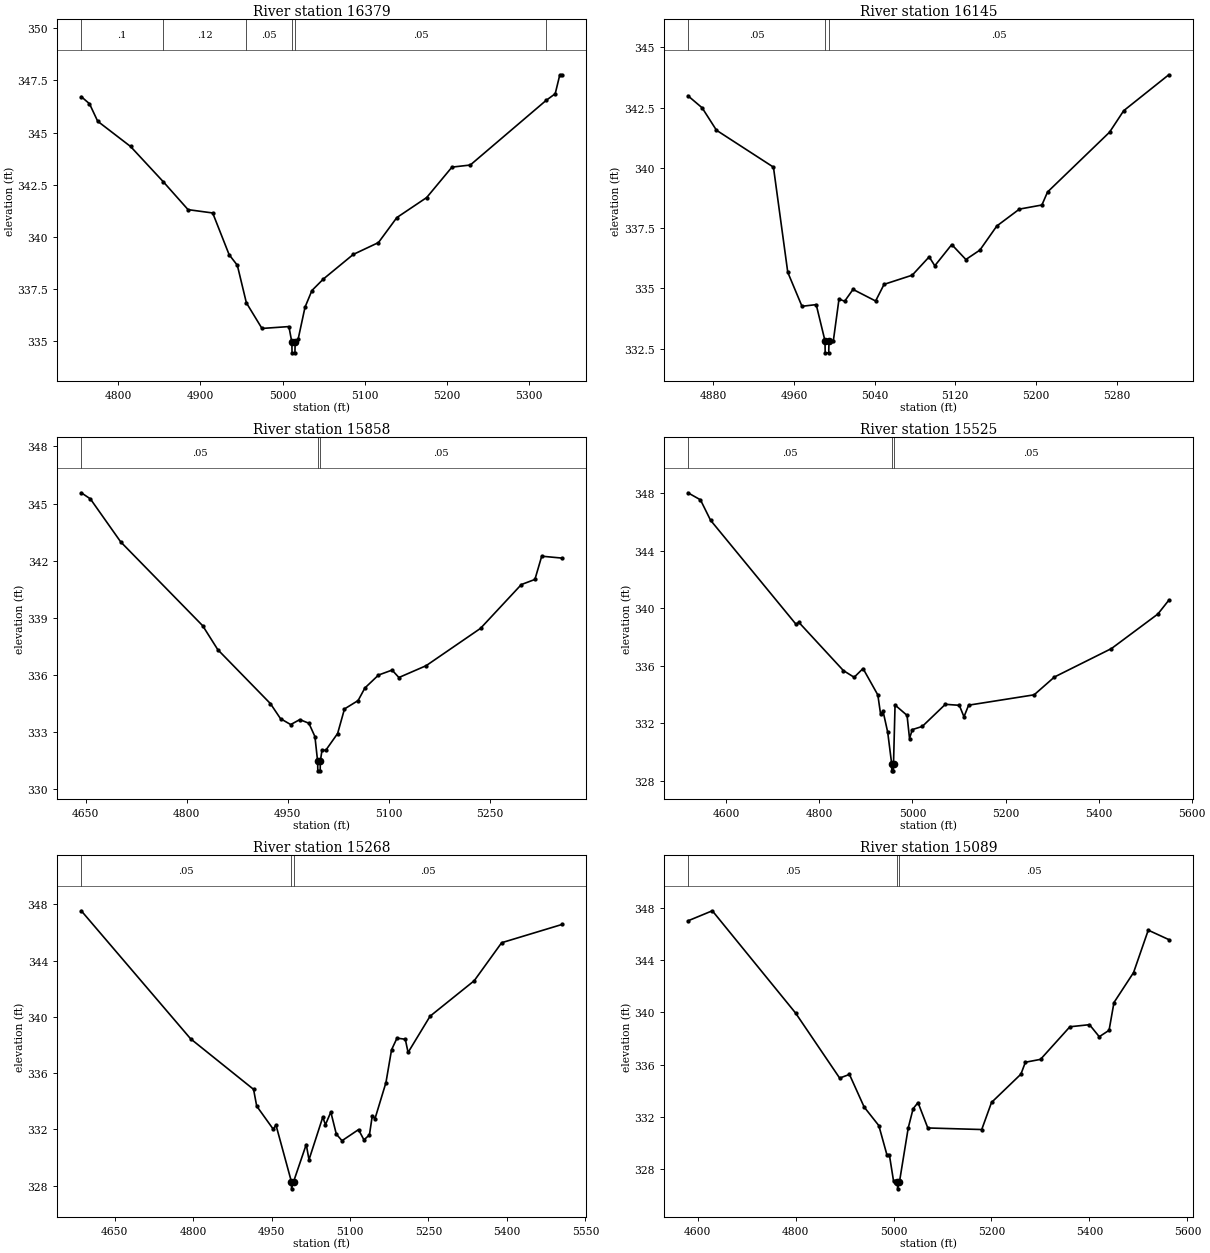
Type RM Length L Ch R = 1,16379,234,234,234
BEGIN DESCRIPTION:
Cedar Branch 37.0
END DESCRIPTION:
XS GIS Cut Line= 3
      2711226.01      6794561.00      2710976.00      6794561.00
      2710826.01      6794860.99
#Sta/Elev= 30
  4755.0  346.72  4765.0  346.38  4775.0  345.54  4815.0  344.33  4854.8  342.64
  4885.0  341.30  4915.0  341.14  4935.0  339.14  4945.0  338.63  4956.0  336.83
  4975.0  335.60  5007.8  335.69  5011.4  334.93  5011.6  334.43  5015.1  334.43
  5015.4  334.93  5019.0  335.08  5027.4  336.62  5035.8  337.42  5049.7  337.97
  5086.1  339.15  5116.8  339.72  5139.2  340.92  5175.5  341.88  5206.3  343.34
  5228.6  343.44  5320.9  346.54  5332.0  346.86  5337.6  347.77  5340.4  347.77
#Mann=6,-1,0
  4755.0     0.1       0  4854.8    0.12       0  4956.0    0.05       0
  5011.4    0.05       0  5015.4    0.05       0  5320.9    0.12       0
Bank Sta=5011.4,5015.4
Exp/Cntr=0.3,0.1

Type RM Length L Ch R = 1,16145,287,287,287
BEGIN DESCRIPTION:
Cedar Branch 36.0
END DESCRIPTION:
XS GIS Cut Line= 3
      2710975.98      6794261.02      2710876.00      6794361.00
      2710726.00      6794661.00
#Sta/Elev= 30
  4854.9  342.99  4869.0  342.49  4883.2  341.56  4939.7  340.03  4953.9  335.67
  4968.0  334.26  4982.1  334.33  4990.8  332.83  4991.0  332.33  4994.5  332.33
  4994.8  332.83  4999.1  332.83  5004.7  334.56  5010.3  334.47  5018.6  334.96
  5041.0  334.48  5049.4  335.17  5077.3  335.55  5094.1  336.31  5099.7  335.94
  5116.5  336.82  5130.5  336.20  5144.4  336.59  5161.2  337.59  5183.6  338.29
  5205.9  338.46  5211.5  339.00  5273.0  341.48  5287.0  342.37  5331.7  343.86
#Mann=3,-1,0
  4854.9    0.05       0  4990.8    0.05       0  4994.8    0.05       0
Bank Sta=4990.8,4994.8
Exp/Cntr=0.3,0.1

Type RM Length L Ch R = 1,15858,333,333,333
BEGIN DESCRIPTION:
Cedar Branch 35.0
END DESCRIPTION:
XS GIS Cut Line= 3
      2710925.99      6794061.01      2710626.00      6794261.00
      2710676.00      6794611.00
#Sta/Elev= 30
  4643.4  345.57  4656.9  345.25  4702.0  342.99  4823.7  338.59  4846.2  337.33
  4924.3  334.50  4939.3  333.71  4954.4  333.40  4967.9  333.66  4981.4  333.47
  4990.4  332.77  4994.4  331.47  4994.7  330.97  4998.2  330.97  4998.4  331.47
  5000.9  332.05  5006.5  332.05  5024.1  332.93  5034.3  334.22  5054.5  334.66
  5064.6  335.32  5084.8  336.00  5105.0  336.26  5115.1  335.87  5155.5  336.49
  5236.3  338.45  5296.9  340.75  5317.1  341.02  5327.2  342.24  5357.5  342.14
#Mann=3,-1,0
  4643.4    0.05       0  4994.4    0.04       0  4998.4    0.05       0
Bank Sta=4994.4,4998.4
Exp/Cntr=0.3,0.1

Type RM Length L Ch R = 1,15525,257,257,257
BEGIN DESCRIPTION:
Cedar Branch 34.0
END DESCRIPTION:
XS GIS Cut Line= 5
      2710849.69      6793740.17      2710573.26      6793894.71
      2710513.24      6794066.79      2710511.94      6794301.01
      2710630.73      6794576.63
#Sta/Elev= 30
  4517.5  348.05  4544.4  347.56  4566.1  346.14  4750.0  338.89  4755.7  339.04
  4851.5  335.68  4874.7  335.21  4893.8  335.82  4925.6  333.98  4931.5  332.65
  4936.8  332.85  4946.8  331.39  4955.3  329.20  4955.5  328.70  4959.0  328.70
  4959.3  329.20  4962.6  333.28  4988.4  332.56  4993.7  330.95  4999.7  331.57
  5021.1  331.79  5070.7  333.33  5100.7  333.26  5110.7  332.46  5120.7  333.27
  5261.5  333.99  5305.1  335.23  5427.7  337.21  5527.3  339.61  5550.8  340.57
#Mann=3,-1,0
  4517.5    0.05       0  4955.3    0.04       0  4959.3    0.05       0
Bank Sta=4955.3,4959.3
Exp/Cntr=0.3,0.1

Type RM Length L Ch R = 1,15268,179,179,179
BEGIN DESCRIPTION:
Mapping XS 3e294460
END DESCRIPTION:
XS GIS Cut Line= 2
      2710818.41      6793729.33      2709946.65      6794021.14
#Sta/Elev= 30
  4586.2  347.54  4795.3  338.44  4915.6  334.85  4921.6  333.66  4953.2  332.02
  4958.4  332.32  4988.0  328.28  4988.2  327.78  4992.0  328.28  5016.3  330.93
  5021.6  329.85  5047.9  332.87  5053.1  332.34  5063.3  333.24  5073.8  331.67
  5084.7  331.20  5116.3  331.99  5126.6  331.26  5137.1  331.61  5142.6  332.98
  5147.8  332.77  5168.7  335.33  5179.4  337.66  5189.8  338.49  5205.7  338.41
  5211.0  337.47  5253.1  340.05  5337.5  342.57  5389.9  345.27  5505.5  346.57
#Mann=3,-1,0
  4586.2    0.05       0  4988.0    0.04       0  4992.0    0.05       0
Bank Sta=4988,4992
Exp/Cntr=0.3,0.1

Type RM Length L Ch R = 1,15089,159,159,159
BEGIN DESCRIPTION:
Cedar Branch 33.0
END DESCRIPTION:
XS GIS Cut Line= 3
      2710845.80      6793684.86      2710438.07      6793681.72
      2709864.13      6793670.22
#Sta/Elev= 30
  4580.2  346.98  4630.0  347.75  4800.0  339.94  4890.0  334.97  4910.0  335.25
  4940.0  332.76  4970.0  331.34  4986.5  329.11  4991.5  329.11  5000.0  327.11
  5008.0  327.01  5008.3  326.51  5012.0  327.01  5030.0  331.16  5040.0  332.63
  5050.0  333.10  5070.0  331.16  5180.1  331.04  5200.1  333.11  5260.1  335.27
  5269.2  336.18  5300.1  336.40  5360.1  338.89  5400.1  339.05  5420.1  338.13
  5440.1  338.62  5450.1  340.74  5490.1  343.03  5520.1  346.27  5562.0  345.55
#Mann=3,-1,0
  4580.2    0.05       0  5008.0    0.05       0  5012.0    0.05       0
Bank Sta=5008,5012
Exp/Cntr=0.3,0.1

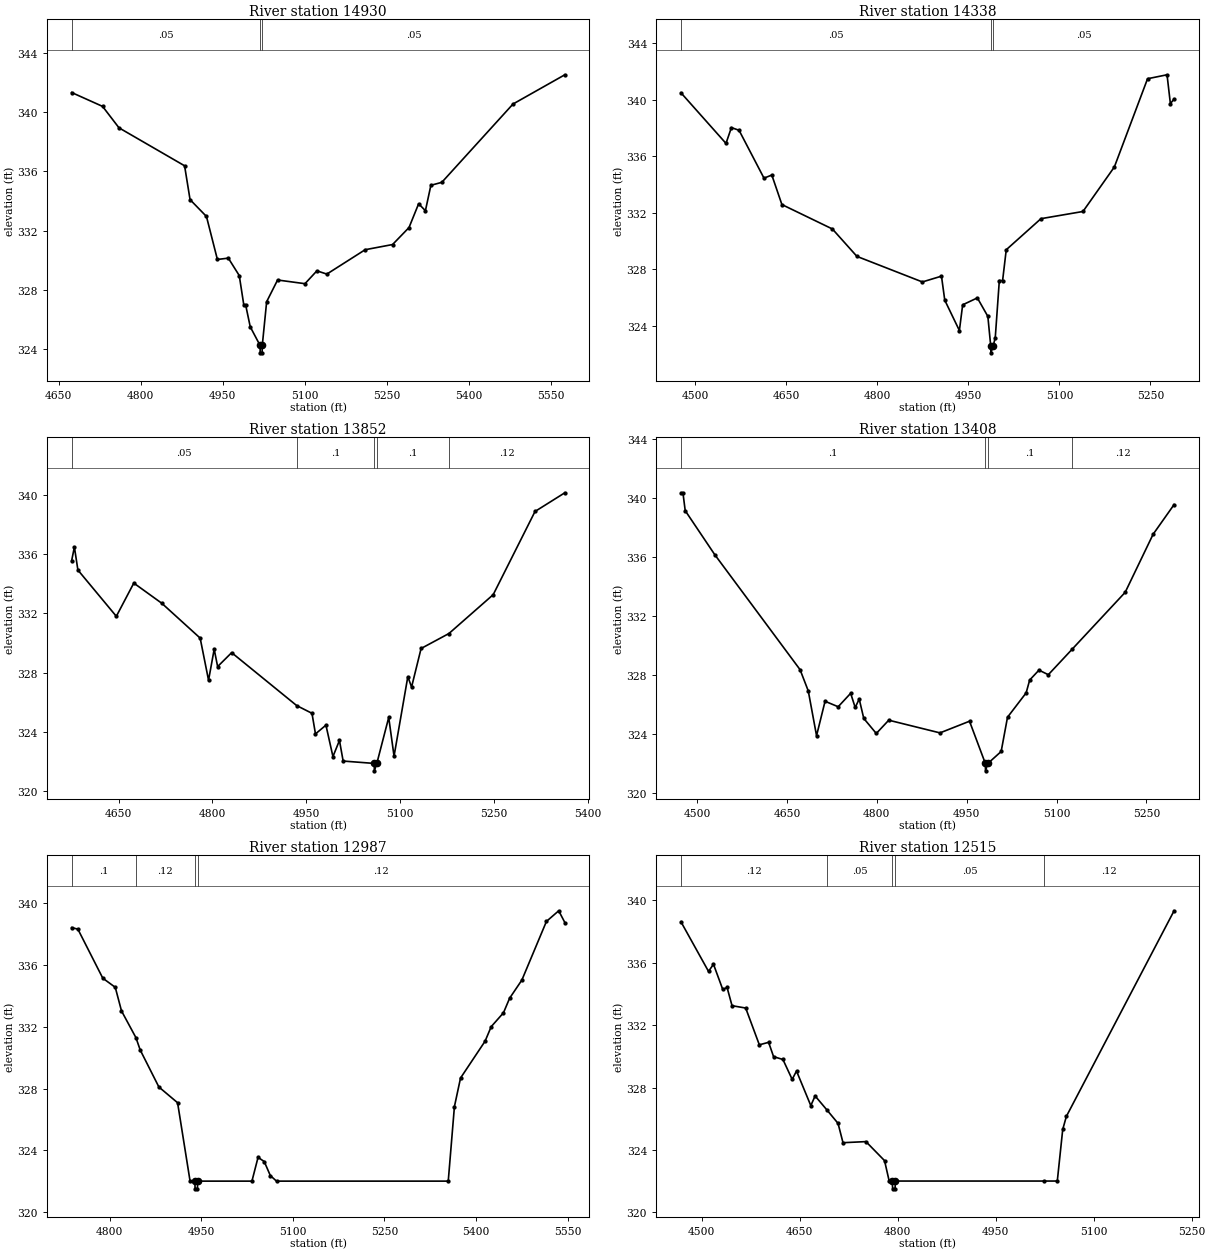
Type RM Length L Ch R = 1,14930,592,592,592
BEGIN DESCRIPTION:
Cedar Branch 32.0
END DESCRIPTION:
XS GIS Cut Line= 3
      2710752.59      6793516.48      2710434.20      6793522.61
      2709851.34      6793492.20
#Sta/Elev= 30
  4673.7  341.34  4730.3  340.40  4760.3  338.95  4880.3  336.38  4890.3  334.09
  4920.3  332.95  4940.3  330.04  4960.3  330.13  4980.3  328.95  4988.7  326.94
  4992.1  326.94  5000.4  325.48  5018.4  324.22  5018.6  323.72  5022.1  323.72
  5022.4  324.22  5030.4  327.18  5050.4  328.65  5100.5  328.40  5122.3  329.27
  5140.5  329.05  5210.6  330.70  5260.7  331.05  5290.8  332.20  5308.4  333.81
  5320.8  333.34  5330.8  335.06  5350.8  335.26  5481.0  340.56  5575.8  342.54
#Mann=3,-1,0
  4673.7    0.05       0  5018.4    0.05       0  5022.4    0.05       0
Bank Sta=5018.4,5022.4
Exp/Cntr=0.3,0.1

Type RM Length L Ch R = 1,14338,486,486,486
BEGIN DESCRIPTION:
Cedar Branch 31.0
END DESCRIPTION:
XS GIS Cut Line= 3
      2710614.87      6792963.50      2710126.00      6793161.00
      2709866.24      6793278.87
#Sta/Elev= 30
  4476.4  340.51  4550.7  336.92  4559.6  338.04  4572.2  337.85  4613.3  334.46
  4626.2  334.68  4642.8  332.59  4726.0  330.86  4766.4  328.92  4874.2  327.11
  4905.7  327.52  4911.1  325.82  4935.2  323.67  4940.6  325.49  4964.8  325.98
  4982.1  324.67  4986.8  322.59  4987.1  322.09  4990.9  322.59  4994.3  323.16
  5001.0  327.21  5006.4  327.21  5012.4  329.39  5069.6  331.59  5138.8  332.10
  5190.5  335.25  5245.2  341.50  5277.3  341.78  5282.8  339.74  5288.9  340.06
#Mann=3,-1,0
  4476.4    0.05       0  4986.8    0.03       0  4990.9    0.05       0
Bank Sta=4986.8,4990.9
Exp/Cntr=0.3,0.1

Type RM Length L Ch R = 1,13852,444,444,444
BEGIN DESCRIPTION:
Cedar Branch 30.0
END DESCRIPTION:
XS GIS Cut Line= 3
      2710401.37      6792522.20      2710026.00      6792711.00
      2709715.81      6792908.30
#Sta/Elev= 30
  4575.1  335.55  4579.5  336.47  4585.1  334.92  4646.5  331.80  4674.4  334.04
  4719.1  332.68  4780.4  330.33  4793.8  327.49  4802.8  329.58  4808.3  328.41
  4830.7  329.35  4934.6  325.78  4959.0  325.26  4964.6  323.87  4981.3  324.46
  4992.5  322.34  5002.9  323.43  5008.8  322.04  5058.4  321.88  5058.7  321.38
  5062.6  321.88  5081.6  324.98  5090.1  322.37  5112.1  327.73  5118.1  327.03
  5133.3  329.63  5177.8  330.64  5248.5  333.26  5315.3  338.87  5362.9  340.13
#Mann=5,-1,0
  4575.1    0.05       0  4934.6     0.1       0  5058.4    0.07       0
  5062.6     0.1       0  5177.8    0.12       0
Bank Sta=5058.4,5062.6
Exp/Cntr=0.3,0.1

Type RM Length L Ch R = 1,13408,421,421,421
BEGIN DESCRIPTION:
Cedar Branch 29.0
END DESCRIPTION:
XS GIS Cut Line= 3
      2710226.03      6792110.98      2709826.00      6792461.00
      2709676.00      6792711.01
#Sta/Elev= 30
  4473.0  340.35  4476.4  340.35  4480.2  339.14  4529.5  336.16  4671.9  328.37
  4685.6  326.93  4699.4  323.90  4713.6  326.23  4735.5  325.86  4756.3  326.77
  4763.9  325.81  4770.6  326.38  4778.2  325.07  4799.1  324.05  4819.9  324.95
  4905.4  324.09  4954.7  324.88  4981.1  322.02  4981.4  321.52  4985.3  322.02
  5007.5  322.83  5018.1  325.15  5049.2  326.80  5055.1  327.67  5070.6  328.34
  5086.2  328.03  5126.3  329.77  5214.5  333.61  5261.1  337.54  5296.1  339.55
#Mann=4,-1,0
  4473.0     0.1       0  4981.1    0.07       0  4985.3     0.1       0
  5126.3    0.12       0
Bank Sta=4981.1,4985.3
Exp/Cntr=0.3,0.1

Type RM Length L Ch R = 1,12987,472,472,472
BEGIN DESCRIPTION:
Cedar Branch 28.0
END DESCRIPTION:
XS GIS Cut Line= 3
      2710175.99      6792061.00      2709926.00      6792111.00
      2709376.01      6792061.00
#Sta/Elev= 30
  4738.0  338.43  4748.2  338.33  4789.0  335.15  4809.4  334.56  4819.6  333.03
  4843.2  331.30  4850.2  330.50  4880.8  328.10  4911.4  327.08  4931.8  322.01
  4939.6  322.00  4940.1  321.50  4943.8  321.50  4944.4  322.00  5033.1  322.00
  5043.1  323.54  5053.2  323.27  5063.2  322.36  5073.3  322.00  5354.4  322.00
  5364.5  326.83  5374.5  328.68  5414.7  331.07  5424.7  332.01  5444.8  332.91
  5454.8  333.85  5474.9  335.03  5515.1  338.83  5535.2  339.52  5545.2  338.76
#Mann=4,-1,0
  4738.0     0.1       0  4843.2    0.12       0  4939.6    0.07       0
  4944.4    0.12       0
Bank Sta=4939.6,4944.4
Exp/Cntr=0.3,0.1

Type RM Length L Ch R = 1,12515,483,483,483
BEGIN DESCRIPTION:
Cedar Branch 27.0
END DESCRIPTION:
XS GIS Cut Line= 3
      2709976.02      6791510.99      2709576.00      6791861.00
      2709376.03      6791960.98
#Sta/Elev= 30
  4467.9  338.64  4510.2  335.45  4517.8  335.91  4532.0  334.29  4538.6  334.42
  4546.2  333.25  4567.1  333.10  4588.0  330.74  4602.2  330.90  4609.8  329.98
  4624.1  329.80  4638.3  328.52  4644.9  329.06  4666.8  326.84  4673.4  327.46
  4691.3  326.57  4708.5  325.70  4716.1  324.46  4751.2  324.53  4779.7  323.31
  4786.8  322.00  4791.5  322.00  4792.1  321.50  4795.8  321.50  4796.3  322.00
  5024.4  322.00  5044.2  322.00  5052.5  325.31  5058.1  326.15  5223.0  339.34
#Mann=5,-1,0
  4467.9    0.12       0  4691.3    0.05       0  4791.5    0.05       0
  4796.3    0.05       0  5024.4    0.12       0
Bank Sta=4791.5,4796.3
Exp/Cntr=0.3,0.1

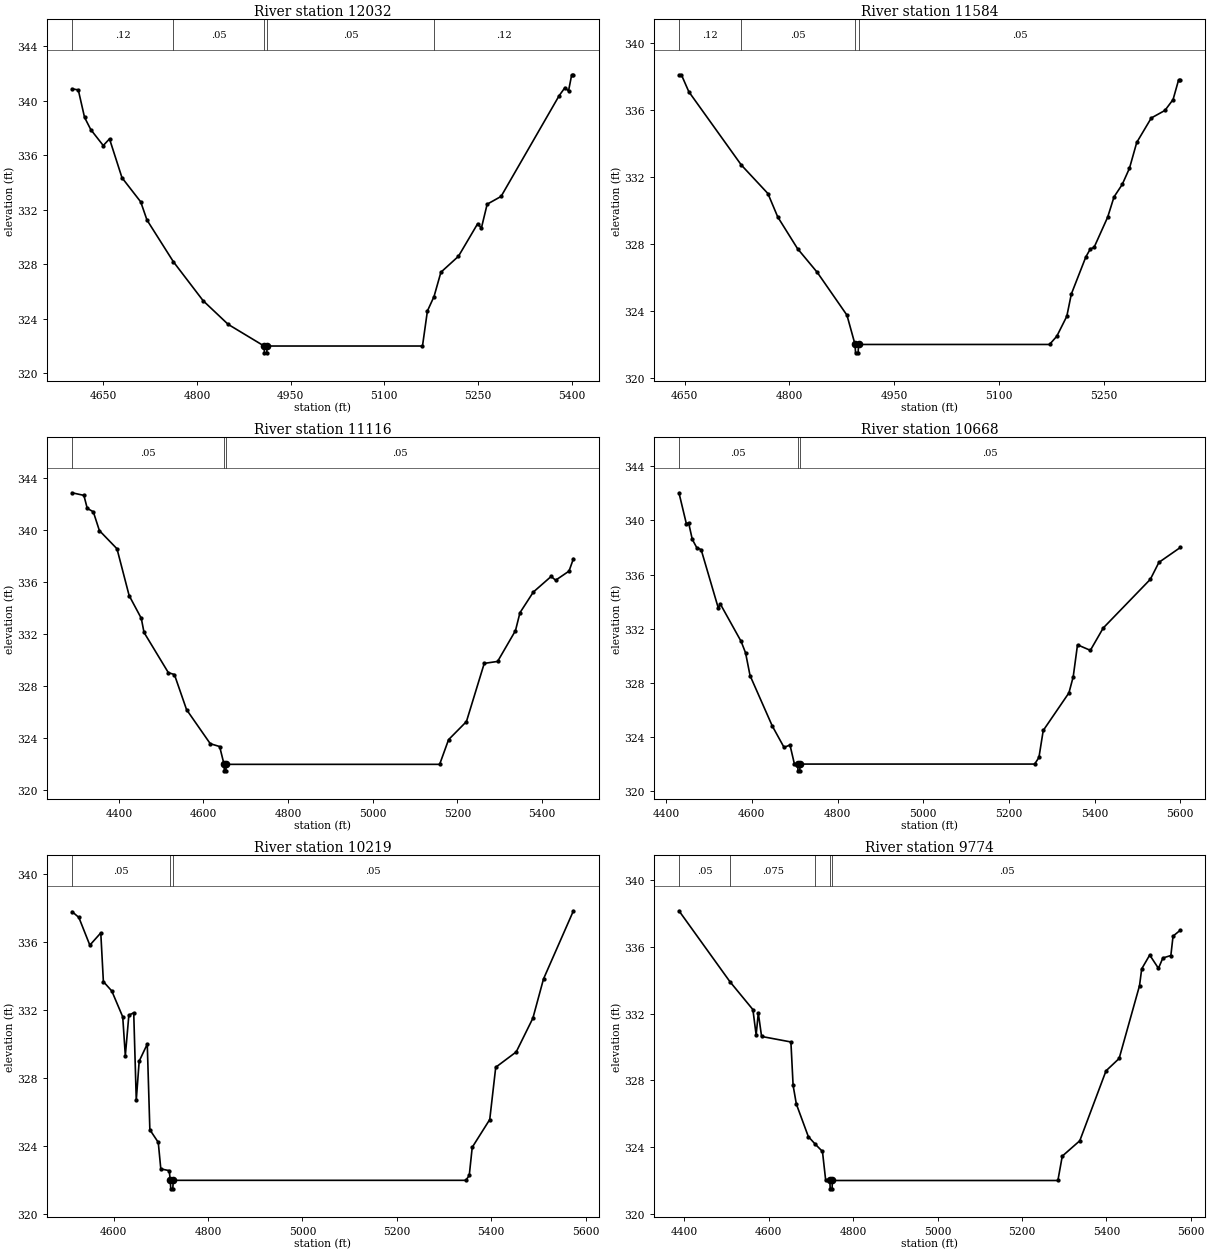
Type RM Length L Ch R = 1,12032,448,448,448
BEGIN DESCRIPTION:
Cedar Branch 26.0
END DESCRIPTION:
XS GIS Cut Line= 3
      2709976.02      6791411.00      2709576.00      6791411.00
      2709226.03      6791610.98
#Sta/Elev= 30
  4599.8  340.86  4609.8  340.78  4619.8  338.77  4629.8  337.87  4649.8  336.70
  4659.8  337.19  4679.8  334.34  4709.8  332.57  4719.8  331.24  4762.1  328.18
  4809.8  325.32  4849.8  323.59  4907.4  322.00  4908.0  321.50  4911.7  321.50
  4912.3  322.00  5161.1  322.00  5169.0  324.57  5179.6  325.63  5190.6  327.41
  5218.7  328.58  5249.6  330.98  5255.4  330.64  5264.7  332.40  5287.0  332.97
  5379.9  340.35  5389.3  340.95  5395.0  340.70  5400.1  341.89  5402.9  341.89
#Mann=5,-1,0
  4599.8    0.12       0  4762.1    0.05       0  4907.4    0.03       0
  4912.3    0.05       0  5179.6    0.12       0
Bank Sta=4907.4,4912.3
Exp/Cntr=0.3,0.1

Type RM Length L Ch R = 1,11584,468,468,468
BEGIN DESCRIPTION:
Cedar Branch 25.0
END DESCRIPTION:
XS GIS Cut Line= 3
      2709975.99      6791260.99      2709726.00      6791011.00
      2709376.04      6790911.01
#Sta/Elev= 30
  4641.9  338.10  4645.4  338.10  4656.0  337.09  4731.2  332.71  4769.2  331.01
  4783.3  329.61  4811.6  327.72  4839.9  326.30  4882.3  323.75  4893.9  322.00
  4894.6  321.50  4898.3  321.50  4898.9  322.00  5172.2  322.00  5182.6  322.49
  5196.9  323.68  5203.4  325.01  5224.2  327.23  5230.7  327.71  5235.9  327.79
  5255.4  329.60  5264.5  330.81  5276.2  331.55  5286.6  332.52  5297.0  334.06
  5317.8  335.52  5337.3  335.97  5349.0  336.62  5356.8  337.78  5359.4  337.78
#Mann=4,-1,0
  4641.9    0.12       0  4731.2    0.05       0  4893.9    0.03       0
  4898.9    0.05       0
Bank Sta=4893.9,4898.9
Exp/Cntr=0.3,0.1

Type RM Length L Ch R = 1,11116,448,448,448
BEGIN DESCRIPTION:
Cedar Branch 24.0
END DESCRIPTION:
XS GIS Cut Line= 3
      2710275.98      6790061.02      2709826.00      6790611.00
      2709376.04      6790760.99
#Sta/Elev= 30
  4289.4  342.90  4317.4  342.70  4325.3  341.70  4339.6  341.44  4354.0  339.99
  4395.6  338.59  4424.3  334.99  4453.0  333.24  4459.5  332.15  4516.9  329.06
  4531.3  328.91  4560.0  326.21  4616.0  323.59  4638.2  323.37  4648.6  322.00
  4649.3  321.50  4653.0  321.50  4653.6  322.00  5158.1  322.00  5179.2  323.90
  5221.4  325.29  5263.5  329.77  5295.1  329.92  5337.3  332.29  5347.9  333.67
  5379.5  335.26  5421.6  336.46  5432.2  336.17  5463.8  336.87  5474.3  337.83
#Mann=3,-1,0
  4289.4    0.05       0  4648.6    0.03       0  4653.6    0.05       0
Bank Sta=4648.6,4653.6
Exp/Cntr=0.3,0.1

Type RM Length L Ch R = 1,10668,449,449,449
BEGIN DESCRIPTION:
Cedar Branch 23.0
END DESCRIPTION:
XS GIS Cut Line= 3
      2710226.01      6790061.00      2709676.00      6790211.00
      2709076.00      6790211.00
#Sta/Elev= 30
  4429.9  342.04  4447.2  339.75  4452.4  339.83  4461.0  338.60  4471.4  337.99
  4481.7  337.84  4521.5  333.55  4526.7  333.81  4575.0  331.06  4585.4  330.21
  4595.8  328.54  4647.6  324.82  4675.2  323.23  4689.0  323.41  4699.4  322.00
  4706.8  322.00  4707.8  321.50  4711.8  321.50  4712.7  322.00  5260.0  322.00
  5270.0  322.49  5280.0  324.48  5340.0  327.26  5350.0  328.45  5360.0  330.81
  5390.0  330.40  5420.0  332.05  5530.0  335.65  5550.0  336.90  5600.0  338.00
#Mann=3,-1,0
  4429.9    0.05       0  4706.8    0.03       0  4712.7    0.05       0
Bank Sta=4706.8,4712.7
Exp/Cntr=0.3,0.1

Type RM Length L Ch R = 1,10219,445,445,445
BEGIN DESCRIPTION:
Cedar Branch 22.0
END DESCRIPTION:
XS GIS Cut Line= 3
      2709976.03      6789610.99      2709526.00      6789811.00
      2709075.97      6790161.02
#Sta/Elev= 30
  4511.7  337.78  4526.1  337.44  4549.4  335.81  4572.6  336.53  4578.1  333.67
  4595.9  333.12  4619.1  331.60  4624.6  329.32  4632.1  331.70  4642.4  331.84
  4647.8  326.71  4654.0  329.00  4671.1  330.00  4676.6  324.97  4694.4  324.23
  4699.8  322.67  4717.6  322.57  4719.9  322.00  4720.9  321.50  4725.2  321.50
  4726.2  322.00  5346.2  322.00  5353.5  322.29  5359.8  323.94  5396.9  325.57
  5409.6  328.64  5453.0  329.54  5488.3  331.52  5510.9  333.83  5574.3  337.83
#Mann=3,-1,0
  4511.7    0.05       0  4719.9    0.03       0  4726.2    0.05       0
Bank Sta=4719.9,4726.2
Exp/Cntr=0.3,0.1

Type RM Length L Ch R = 1,9774,485,485,485
BEGIN DESCRIPTION:
Cedar Branch 21.0
END DESCRIPTION:
XS GIS Cut Line= 3
      2709976.02      6789561.00      2709376.00      6789411.00
      2708825.97      6789561.01
#Sta/Elev= 30
  4386.9  338.16  4507.8  333.91  4562.2  332.24  4569.9  330.72  4575.0  332.04
  4582.8  330.63  4652.3  330.30  4657.5  327.70  4665.2  326.58  4693.6  324.63
  4710.6  324.16  4727.1  323.74  4734.8  322.00  4744.5  322.00  4745.5  321.50
  4749.8  321.50  4750.8  322.00  5285.2  322.00  5295.6  323.46  5337.1  324.38
  5399.3  328.57  5430.4  329.31  5478.7  333.67  5483.9  334.68  5502.9  335.51
  5523.6  334.71  5534.0  335.33  5553.0  335.48  5558.2  336.64  5575.5  337.00
#Mann=5,-1,0
  4386.9    0.05       0  4507.8   0.075       0  4710.6    0.05       0
  4744.5    0.03       0  4750.8    0.05       0
Bank Sta=4744.5,4750.8
Exp/Cntr=0.3,0.1