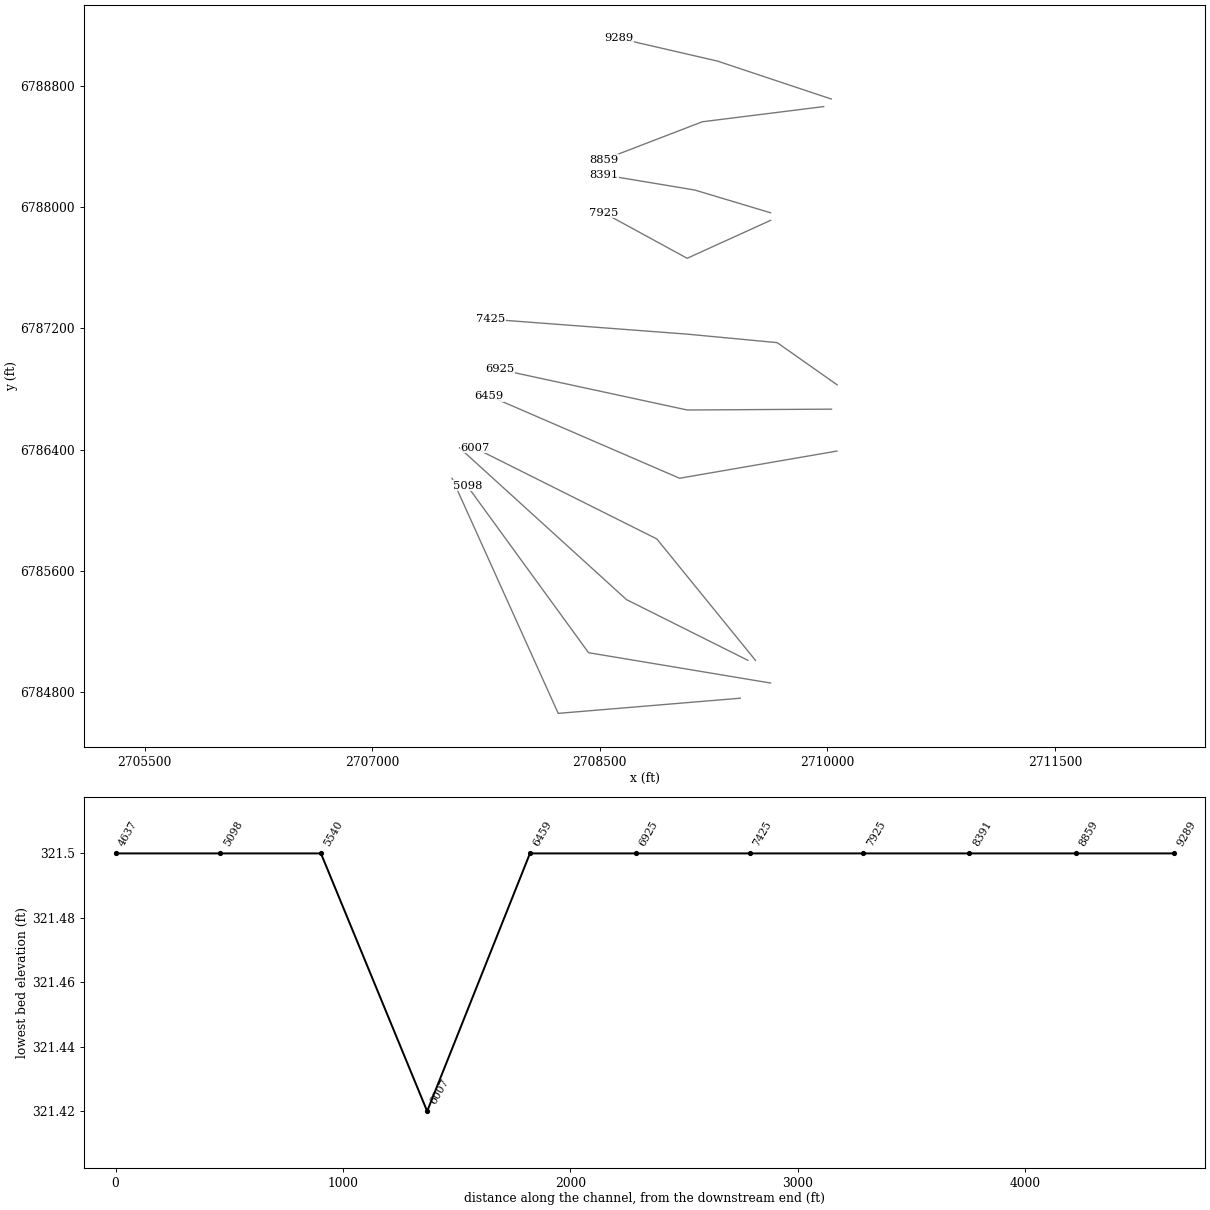
HEC-RAS study Cedar Branch.prj: Cedar Branch Base Level Engineering

--- Cedar Branch.g01 (geometry) --- (continued)

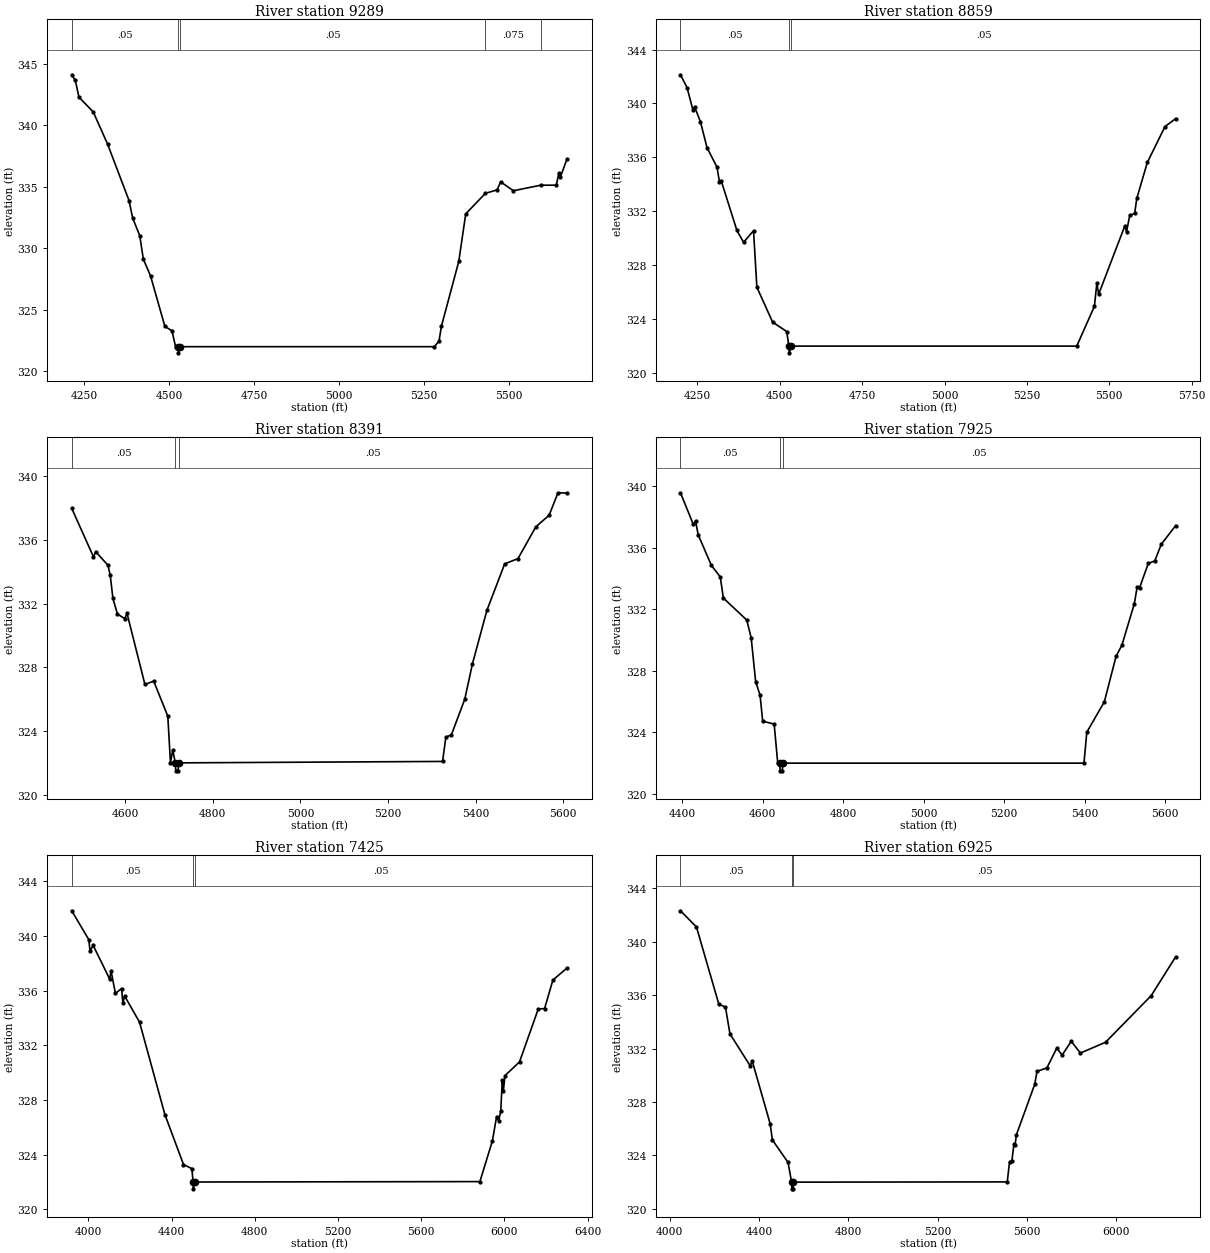
Type RM Length L Ch R = 1,9289,430,430,430
BEGIN DESCRIPTION:
Cedar Branch 20.0
END DESCRIPTION:
XS GIS Cut Line= 3
      2710026.02      6788710.99      2709276.00      6788961.00
      2708625.97      6789111.01
#Sta/Elev= 30
  4213.4  344.09  4224.0  343.63  4234.5  342.28  4276.7  341.07  4318.8  338.47
  4382.1  333.87  4392.6  332.47  4413.7  331.01  4424.2  329.11  4445.3  327.76
  4487.5  323.66  4508.6  323.28  4519.1  322.00  4526.4  322.00  4527.4  321.50
  4532.9  322.00  5281.1  322.00  5294.8  322.45  5301.6  323.64  5352.9  328.93
  5373.4  332.79  5431.3  334.46  5465.8  334.74  5476.1  335.39  5513.7  334.67
  5594.3  335.12  5640.3  335.12  5647.1  336.08  5652.3  335.80  5671.1  337.22
#Mann=5,-1,0
  4213.4    0.05       0  4526.4    0.03       0  4532.9    0.05       0
  5431.3   0.075       0  5594.3    0.05       0
Bank Sta=4526.4,4532.9
Exp/Cntr=0.3,0.1

Type RM Length L Ch R = 1,8859,468,468,468
BEGIN DESCRIPTION:
Cedar Branch 19.0
END DESCRIPTION:
XS GIS Cut Line= 3
      2709975.99      6788661.00      2709176.00      6788561.00
      2708526.03      6788311.01
#Sta/Elev= 30
  4198.7  342.13  4218.8  341.17  4236.5  339.51  4241.5  339.76  4259.2  338.65
  4279.3  336.72  4309.5  335.28  4317.1  334.16  4322.1  334.28  4370.0  330.58
  4390.2  329.70  4420.4  330.56  4430.5  326.37  4478.3  323.78  4521.2  323.08
  4527.6  322.00  4528.7  321.50  4535.0  322.00  5401.3  322.00  5454.9  324.95
  5462.4  326.69  5467.8  325.85  5547.1  330.91  5552.4  330.48  5562.1  331.70
  5577.1  331.84  5583.5  332.96  5615.6  335.63  5669.2  338.29  5701.3  338.87
#Mann=3,-1,0
  4198.7    0.05       0  4527.6    0.03       0  4535.0    0.05       0
Bank Sta=4527.6,4535
Exp/Cntr=0.3,0.1

Type RM Length L Ch R = 1,8391,466,466,466
BEGIN DESCRIPTION:
Cedar Branch 18.0
END DESCRIPTION:
XS GIS Cut Line= 3
      2709626.04      6787960.99      2709126.00      6788111.00
      2708526.03      6788210.99
#Sta/Elev= 30
  4477.9  337.97  4527.5  334.93  4532.8  335.25  4560.6  334.40  4565.8  333.77
  4571.9  332.32  4582.3  331.34  4598.9  331.05  4604.1  331.38  4645.0  326.92
  4665.0  327.13  4697.2  324.93  4703.3  322.01  4708.5  322.81  4714.3  322.00
  4715.5  321.50  4720.7  321.50  4721.8  322.00  5324.4  322.09  5332.0  323.61
  5344.6  323.76  5375.1  325.99  5392.8  328.23  5425.8  331.58  5466.3  334.49
  5496.7  334.82  5537.3  336.81  5567.7  337.54  5588.0  338.95  5608.2  338.93
#Mann=3,-1,0
  4477.9    0.05       0  4714.3    0.03       0  4721.8    0.05       0
Bank Sta=4714.3,4721.8
Exp/Cntr=0.3,0.1

Type RM Length L Ch R = 1,7925,500,500,500
BEGIN DESCRIPTION:
Cedar Branch 17.0
END DESCRIPTION:
XS GIS Cut Line= 3
      2709626.04      6787911.02      2709076.00      6787661.00
      2708525.99      6787961.00
#Sta/Elev= 30
  4395.7  339.59  4427.6  337.53  4433.1  337.76  4439.7  336.86  4472.6  334.86
  4494.6  334.12  4502.3  332.74  4560.5  331.31  4571.5  330.14  4582.5  327.31
  4593.5  326.42  4600.1  324.73  4628.6  324.54  4637.4  322.01  4642.3  322.00
  4643.5  321.50  4648.9  321.50  4650.0  322.00  5398.6  322.00  5405.7  324.01
  5449.4  326.00  5478.3  328.94  5493.0  329.68  5523.9  332.38  5531.0  333.49
  5536.7  333.40  5558.5  334.99  5574.7  335.16  5590.8  336.24  5626.4  337.45
#Mann=3,-1,0
  4395.7    0.05       0  4642.3    0.03       0  4650.0    0.05       0
Bank Sta=4642.3,4650
Exp/Cntr=0.3,0.1

Type RM Length L Ch R = 1,7425,500,500,500
BEGIN DESCRIPTION:
Cedar Branch 16.0
END DESCRIPTION:
XS GIS Cut Line= 4
      2710064.97      6786826.69      2709669.29      6787105.04
      2709076.00      6787161.00      2707779.12      6787259.25
#Sta/Elev= 30
  3920.3  341.85  4002.3  339.74  4008.4  338.89  4023.2  339.32  4102.4  336.86
  4109.4  337.44  4130.3  335.80  4159.9  336.16  4166.1  335.09  4174.7  335.61
  4246.2  333.70  4368.1  326.94  4457.6  323.28  4497.8  322.98  4503.8  322.00
  4505.0  321.50  4511.9  322.00  5882.5  322.03  5942.7  325.01  5962.8  326.79
  5972.8  326.46  5982.8  327.19  5990.3  329.46  5995.3  328.63  6002.9  329.78
  6073.1  330.79  6163.3  334.67  6193.4  334.69  6233.5  336.78  6300.6  337.65
#Mann=3,-1,0
  3920.3    0.05       0  4503.8    0.03       0  4511.9    0.05       0
Bank Sta=4503.8,4511.9
Exp/Cntr=0.3,0.1

Type RM Length L Ch R = 1,6925,466,466,466
BEGIN DESCRIPTION:
Cedar Branch 15.0
END DESCRIPTION:
XS GIS Cut Line= 3
      2710027.50      6786666.49      2709076.00      6786661.00
      2707839.40      6786927.93
#Sta/Elev= 30
  4048.5  342.31  4120.0  341.10  4220.0  335.33  4250.0  335.09  4270.0  333.10
  4360.0  330.72  4370.0  331.05  4450.0  326.37  4460.0  325.16  4530.0  323.48
  4546.0  322.00  4547.2  321.50  4552.9  321.50  4554.1  322.00  5511.5  322.02
  5521.8  323.54  5532.0  323.56  5541.1  324.84  5546.2  324.75  5552.5  325.55
  5634.3  329.32  5644.7  330.29  5688.9  330.55  5733.1  332.03  5757.1  331.51
  5798.0  332.54  5838.9  331.66  5951.4  332.47  6156.0  335.96  6265.1  338.86
#Mann=3,-1,0
  4048.5    0.05       0  4546.0    0.03       0  4554.1    0.05       0
Bank Sta=4546,4554.1
Exp/Cntr=0.3,0.1

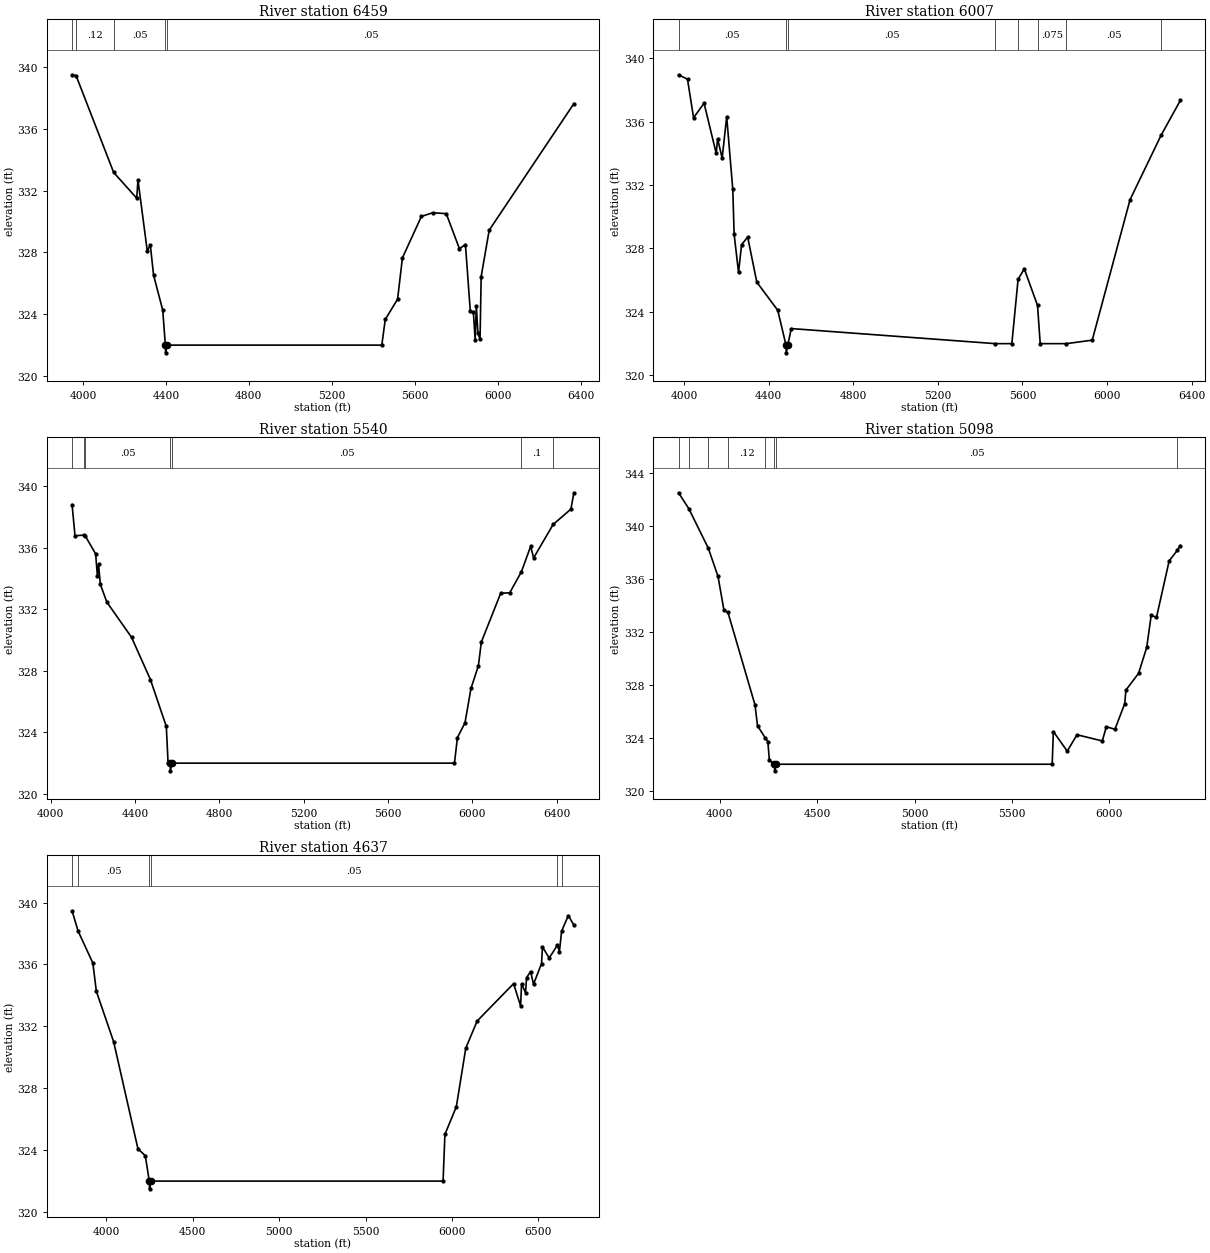
Type RM Length L Ch R = 1,6459,452,452,452
BEGIN DESCRIPTION:
Cedar Branch 14.0
END DESCRIPTION:
XS GIS Cut Line= 3
      2710063.24      6786390.23      2709026.00      6786211.00
      2707771.19      6786753.57
#Sta/Elev= 30
  3947.8  339.50  3967.0  339.45  4148.3  333.18  4259.6  331.51  4265.5  332.69
  4310.3  328.11  4325.3  328.47  4340.8  326.53  4385.1  324.26  4397.6  322.00
  4398.8  321.50  4405.7  322.00  5441.5  322.00  5458.0  323.66  5517.4  324.97
  5540.9  327.65  5632.3  330.33  5686.8  330.57  5752.2  330.51  5815.7  328.24
  5844.6  328.51  5868.1  324.21  5882.9  324.14  5891.6  322.34  5897.1  324.55
  5904.7  322.79  5915.1  322.37  5920.6  326.44  5959.2  329.44  6367.5  337.63
#Mann=5,-1,0
  3947.8    0.05       0  3967.0    0.12       0  4148.3    0.05       0
  4397.6    0.03       0  4405.7    0.05       0
Bank Sta=4397.6,4405.7
Exp/Cntr=0.3,0.1

Type RM Length L Ch R = 1,6007,467,467,467
BEGIN DESCRIPTION:
Cedar Branch 13.0
END DESCRIPTION:
XS GIS Cut Line= 3
      2709526.02      6785010.97      2708876.00      6785811.00
      2707675.96      6786411.02
#Sta/Elev= 30
  3974.1  338.95  4016.5  338.67  4045.2  336.24  4094.8  337.16  4152.3  333.99
  4158.7  334.92  4180.3  333.70  4201.8  336.31  4230.6  331.72  4237.0  328.89
  4257.8  326.49  4272.2  328.24  4301.0  328.72  4344.1  325.88  4443.2  324.10
  4482.0  321.92  4483.3  321.42  4490.7  321.92  4507.1  322.95  5472.0  322.00
  5550.0  322.00  5579.5  326.05  5608.7  326.72  5671.4  324.41  5684.1  322.00
  5807.9  322.00  5930.1  322.22  6109.0  331.08  6255.8  335.14  6346.6  337.33
#Mann=8,-1,0
  3974.1    0.05       0  4482.0    0.03       0  4490.7    0.05       0
  5472.0   0.075       0  5579.5    0.05       0  5671.4   0.075       0
  5807.9    0.05       0  6255.8     0.1       0
Bank Sta=4482,4490.7
Exp/Cntr=0.3,0.1

Type RM Length L Ch R = 1,5540,442,442,442
BEGIN DESCRIPTION:
Cedar Branch 12.0
END DESCRIPTION:
XS GIS Cut Line= 3
      2709475.96      6785011.02      2708676.00      6785411.00
      2707576.00      6786411.00
#Sta/Elev= 30
  4100.9  338.79  4114.8  336.77  4158.3  336.81  4163.4  336.76  4212.7  335.59
  4221.0  334.17  4226.6  334.91  4235.0  333.62  4265.8  332.46  4383.2  330.17
  4472.6  327.43  4548.1  324.38  4556.5  322.00  4566.1  322.00  4567.3  321.50
  4574.8  322.00  5915.3  322.00  5929.5  323.66  5965.3  324.62  5993.7  326.85
  6028.8  328.32  6043.0  329.87  6134.9  333.04  6177.5  333.06  6233.0  334.43
  6276.8  336.08  6291.0  335.33  6383.4  337.50  6468.0  338.50  6481.9  339.56
#Mann=7,-1,0
  4100.9    0.05       0  4158.3    0.12       0  4163.4    0.05       0
  4566.1    0.03       0  4574.8    0.05       0  6233.0     0.1       0
  6383.4    0.12       0
Bank Sta=4566.1,4574.8
Exp/Cntr=0.3,0.1

Type RM Length L Ch R = 1,5098,461,461,461
BEGIN DESCRIPTION:
Cedar Branch 11.0
END DESCRIPTION:
XS GIS Cut Line= 3
      2709626.00      6784861.00      2708426.00      6785061.00
      2707626.00      6786161.00
#Sta/Elev= 30
  3787.9  342.53  3840.3  341.34  3941.0  338.33  3990.7  336.20  4021.1  333.65
  4041.7  333.48  4180.7  326.48  4193.4  324.91  4234.3  323.97  4246.6  323.71
  4254.2  322.31  4280.3  322.00  4281.6  321.50  4289.0  322.00  5706.6  322.00
  5712.7  324.47  5783.8  322.99  5834.1  324.23  5963.9  323.76  5984.8  324.84
  6028.8  324.64  6079.0  326.58  6085.2  327.61  6150.1  328.87  6191.9  330.83
  6215.1  333.27  6242.1  333.10  6307.0  337.37  6349.2  338.18  6364.6  338.54
#Mann=8,-1,0
  3787.9    0.05       0  3840.3    0.12       0  3941.0    0.05       0
  4041.7    0.12       0  4234.3    0.05       0  4280.3    0.03       0
  4289.0    0.05       0  6349.2     0.1       0
Bank Sta=4280.3,4289
Exp/Cntr=0.3,0.1

Type RM Length L Ch R = 1,4637,0,0,0
BEGIN DESCRIPTION:
Cedar Branch 10.0
END DESCRIPTION:
XS GIS Cut Line= 3
      2709425.98      6784761.00      2708226.00      6784661.00
      2707525.99      6786211.03
#Sta/Elev= 30
  3801.1  339.47  3835.6  338.17  3921.5  336.09  3941.6  334.27  4041.9  331.00
  4182.4  324.09  4225.0  323.64  4248.2  322.00  4249.5  321.50  4257.0  322.00
  5948.9  322.00  5959.6  325.02  6025.7  326.81  6080.5  330.60  6146.4  332.35
  6357.0  334.76  6397.8  333.32  6403.2  334.74  6426.4  334.18  6431.9  335.14
  6455.0  335.54  6472.6  334.73  6518.9  336.06  6524.3  337.13  6563.3  336.42
  6611.0  337.25  6622.3  336.83  6635.3  338.16  6674.0  339.16  6706.0  338.55
#Mann=6,-1,0
  3801.1    0.12       0  3835.6    0.05       0  4248.2    0.03       0
  4257.0    0.05       0  6611.0     0.1       0  6635.3    0.05       0
Bank Sta=4248.2,4257
Exp/Cntr=0.3,0.1

Chan Stop Cuts=-1