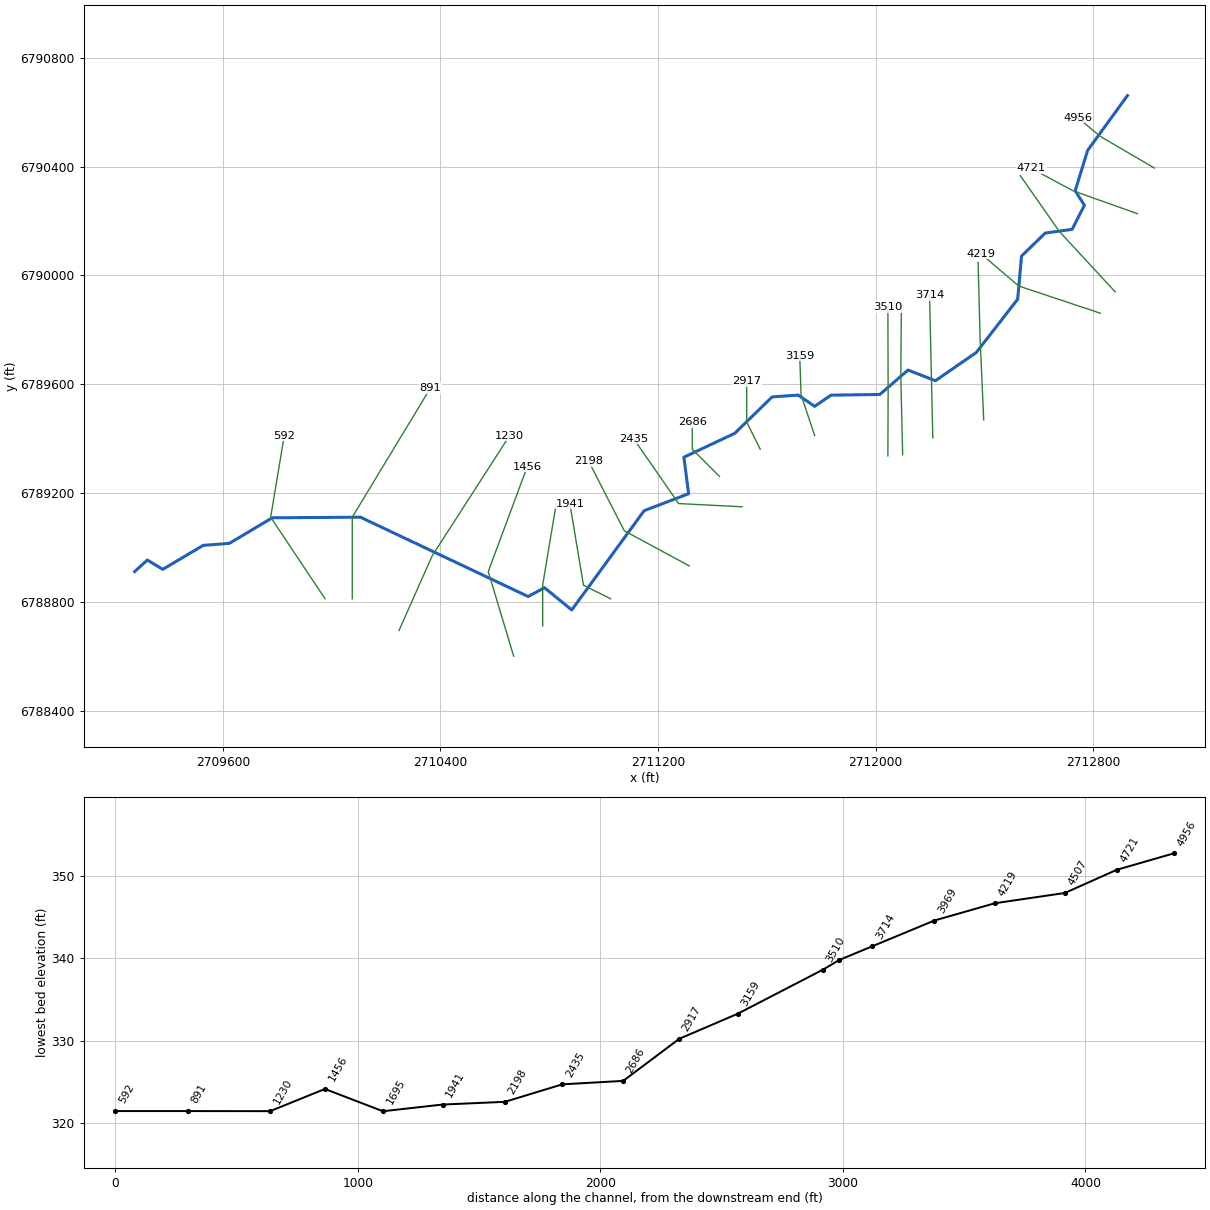
--- Cedar Branch T1.prj (project) ---

Proj Title=Cedar Branch T1 Base Level Engineering
Current Plan=p01
Default Exp/Contr=0.3,0.1
English Units
Geom File=g01
Flow File=f01
Plan File=p01
BEGIN DESCRIPTION:
Cedar Branch T1
END DESCRIPTION:

--- Cedar Branch T1.p01 (plan) ---

Plan Title=Multiple Run
Short Identifier=Multiple
Geom File=g01
Flow File=f01
Subcritical Flow
K Sum by GR= 0
Std Step Tol= 0.01
Critical Tol= 0.01
Num of Std Step Trials= 20
Max Error Tol= 0.3
Flow Tol Ratio= 0.001
Split Flow NTrial= 30
Split Flow Tol= 0.02
Split Flow Ratio= 0.02
Log Output Level= 0
Friction Slope Method= 1
Unsteady Friction Slope Method= 2
Unsteady Bridges Friction Slope Method= 1
Parabolic Critical Depth
Global Vel Dist=  1 , 1 , 1
Global Log Level= 0
CheckData=True
Encroach Param= -1, 0, 0, 0
BEGIN DESCRIPTION:
Multiple Run
END DESCRIPTION:

--- Cedar Branch T1.f01 (steady flow) ---

Flow Title=Multiple
Number of Profiles=7
Profile Names=10-year,25-year,50-year,1pct_min,100-year,1pct_plu,500-year
River Rch & RM= Cedar Branch T1,Reach-1,4956
     296     379     442     257     513    1024     689
Boundary for River Rch & Prof#=Cedar Branch T1,Reach-1,1
Up Type=0
Dn Type=3
Dn Slope=0.005
Boundary for River Rch & Prof#=Cedar Branch T1,Reach-1,2
Up Type=0
Dn Type=3
Dn Slope=0.005
Boundary for River Rch & Prof#=Cedar Branch T1,Reach-1,3
Up Type=0
Dn Type=3
Dn Slope=0.005
Boundary for River Rch & Prof#=Cedar Branch T1,Reach-1,4
Up Type=0
Dn Type=3
Dn Slope=0.005
Boundary for River Rch & Prof#=Cedar Branch T1,Reach-1,5
Up Type=0
Dn Type=3
Dn Slope=0.005
Boundary for River Rch & Prof#=Cedar Branch T1,Reach-1,6
Up Type=0
Dn Type=3
Dn Slope=0.005
Boundary for River Rch & Prof#=Cedar Branch T1,Reach-1,7
Up Type=0
Dn Type=3
Dn Slope=0.005

--- Cedar Branch T1.g01 (geometry) ---

Geom Title=Existing Conditions

River Reach=Cedar Branch T1,Reach-1
Reach XY= 30
      2712926.00      6790661.00      2712779.61      6790459.50
      2712733.79      6790310.90      2712767.78      6790257.73
      2712722.66      6790169.17      2712623.62      6790155.46
      2712536.47      6790070.82      2712522.46      6789912.47
      2712370.38      6789716.62      2712219.95      6789612.67
      2712119.28      6789651.83      2712015.57      6789562.06
      2711836.44      6789559.62      2711776.00      6789518.56
      2711715.51      6789559.74      2711619.83      6789553.24
      2711482.06      6789419.14      2711295.27      6789331.47
      2711312.63      6789197.21      2711149.13      6789134.82
      2710882.95      6788769.85      2710782.67      6788851.67
      2710722.77      6788819.25      2710105.97      6789110.94
      2709781.93      6789108.76      2709624.42      6789014.83
      2709527.58      6789007.17      2709379.23      6788919.12
      2709322.66      6788953.49      2709276.00      6788911.00

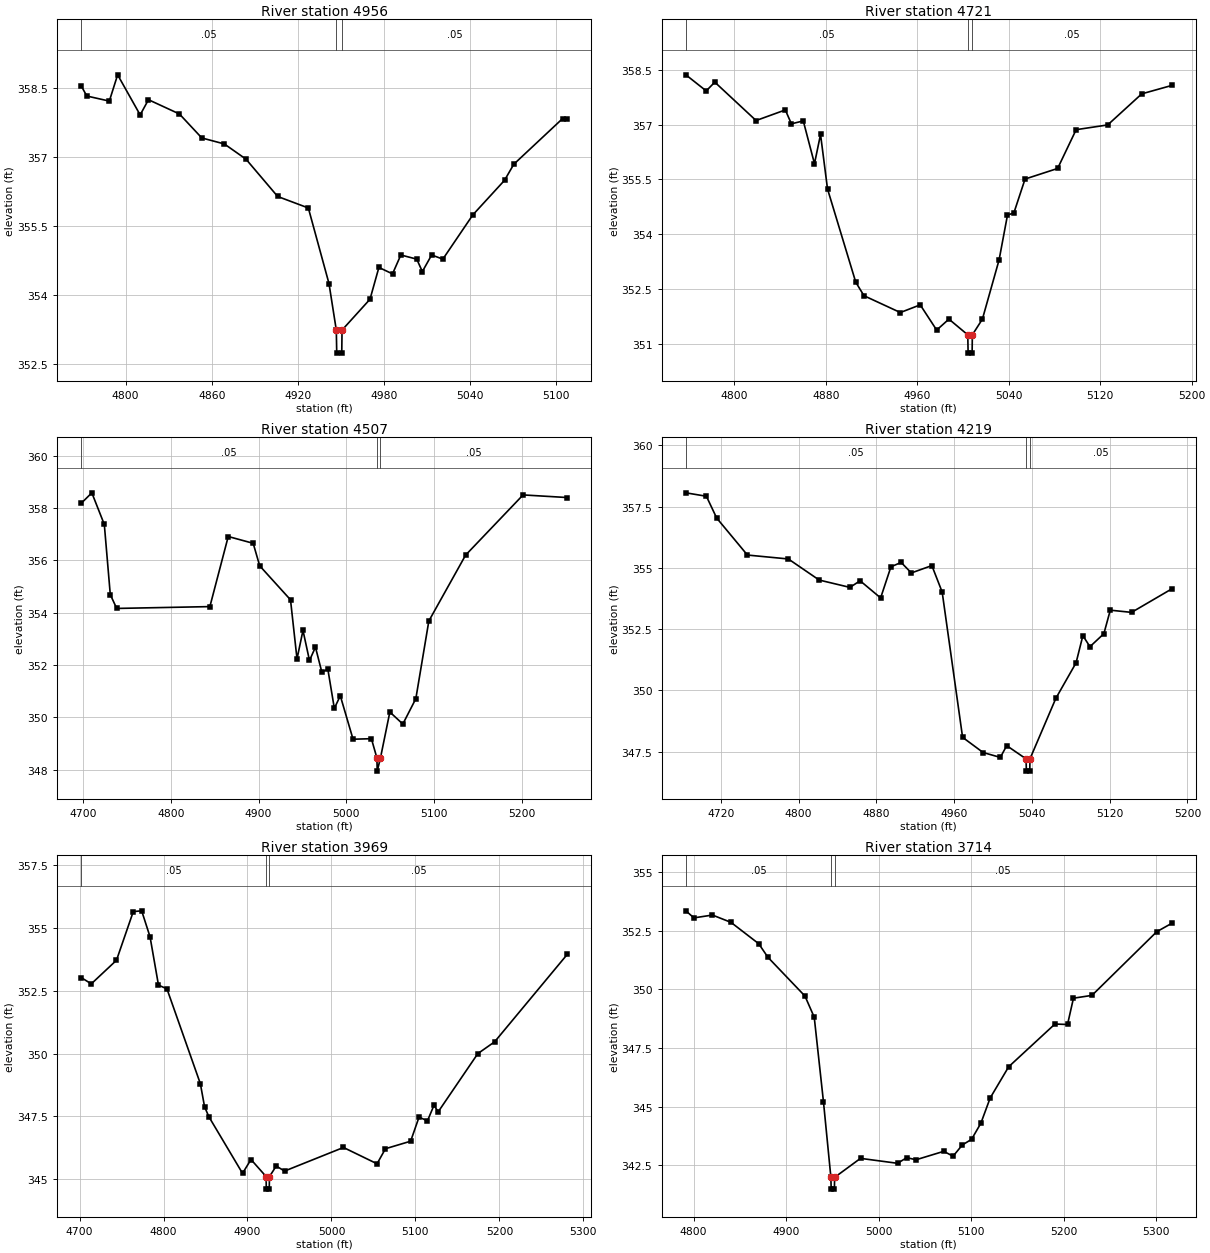
Type RM Length L Ch R = 1,4956,235,235,235
BEGIN DESCRIPTION:
Cedar Branch T1 18.0
END DESCRIPTION:
XS GIS Cut Line= 3
      2713025.16      6790394.46      2712826.00      6790511.00
      2712742.83      6790580.13
#Sta/Elev= 30
  4769.0  358.54  4772.9  358.32  4788.6  358.21  4794.4  358.78  4810.1  357.91
  4815.9  358.24  4837.5  357.93  4853.1  357.41  4868.8  357.28  4883.9  356.95
  4906.0  356.14  4927.4  355.89  4941.8  354.25  4946.9  353.24  4947.2  352.74
  4950.7  352.74  4950.9  353.24  4970.4  353.91  4976.6  354.60  4986.1  354.46
  4991.9  354.87  5003.0  354.78  5006.9  354.51  5013.4  354.87  5021.2  354.78
  5042.1  355.74  5064.2  356.49  5070.7  356.84  5104.7  357.83  5107.9  357.83
#Mann=3,-1,0
  4769.0    0.05       0  4946.9    0.05       0  4950.9    0.05       0
Bank Sta=4946.9,4950.9
Exp/Cntr=0.3,0.1

Type RM Length L Ch R = 1,4721,214,214,214
BEGIN DESCRIPTION:
Cedar Branch T1 17.0
END DESCRIPTION:
XS GIS Cut Line= 3
      2712962.75      6790226.80      2712726.00      6790311.00
      2712572.82      6790393.16
#Sta/Elev= 30
  4757.5  358.36  4775.3  357.92  4782.8  358.16  4818.9  357.11  4844.5  357.40
  4849.8  357.02  4860.2  357.10  4870.0  355.93  4875.3  356.73  4881.4  355.24
  4906.1  352.69  4913.3  352.32  4945.1  351.86  4962.5  352.07  4976.9  351.38
  4987.6  351.68  5004.1  351.25  5004.4  350.75  5007.9  350.75  5008.1  351.25
  5016.9  351.68  5031.5  353.30  5038.8  354.52  5044.5  354.59  5054.2  355.51
  5082.7  355.80  5098.9  356.86  5126.5  356.99  5156.3  357.84  5182.6  358.07
#Mann=3,-1,0
  4757.5    0.05       0  5004.1    0.04       0  5008.1    0.05       0
Bank Sta=5004.1,5008.1
Exp/Cntr=0.3,0.1

Type RM Length L Ch R = 1,4507,288,288,288
BEGIN DESCRIPTION:
Cedar Branch T1 16.0
END DESCRIPTION:
XS GIS Cut Line= 3
      2712881.09      6789939.18      2712676.00      6790161.00
      2712531.94      6790366.79
#Sta/Elev= 30
  4698.1  358.18  4710.2  358.58  4724.4  357.37  4731.2  354.69  4738.5  354.16
  4844.6  354.23  4865.5  356.91  4893.9  356.65  4901.3  355.79  4936.4  354.49
  4943.8  352.23  4950.6  353.32  4958.0  352.17  4964.8  352.68  4972.1  351.72
  4978.9  351.84  4986.3  350.34  4993.1  350.82  5007.6  349.16  5028.5  349.18
  5034.8  348.44  5035.1  347.94  5038.8  348.44  5049.5  350.20  5064.3  349.74
  5079.1  350.71  5093.9  353.68  5135.8  356.20  5201.2  358.50  5251.4  358.40
#Mann=3,-1,0
  4698.1    0.05       0  5034.8    0.04       0  5038.8    0.05       0
Bank Sta=5034.8,5038.8
Exp/Cntr=0.3,0.1

Type RM Length L Ch R = 1,4219,250,250,250
BEGIN DESCRIPTION:
Cedar Branch T1 15.0
END DESCRIPTION:
XS GIS Cut Line= 3
      2712826.03      6789860.99      2712526.00      6789961.00
      2712386.42      6790080.18
#Sta/Elev= 30
  4684.1  358.06  4705.2  357.92  4715.8  357.03  4747.4  355.52  4789.5  355.36
  4821.2  354.50  4852.8  354.20  4863.3  354.47  4884.4  353.77  4895.0  355.04
  4905.5  355.22  4916.0  354.79  4937.1  355.09  4947.7  354.01  4968.7  348.08
  4989.8  347.46  5007.5  347.26  5014.1  347.74  5034.0  347.20  5034.3  346.70
  5037.8  346.70  5038.0  347.20  5064.6  349.67  5085.4  351.12  5092.4  352.23
  5099.7  351.78  5114.0  352.31  5120.6  353.27  5142.5  353.18  5183.9  354.14
#Mann=3,-1,0
  4684.1    0.05       0  5034.0    0.04       0  5038.0    0.05       0
Bank Sta=5034,5038
Exp/Cntr=0.3,0.1

Type RM Length L Ch R = 1,3969,255,255,255
BEGIN DESCRIPTION:
Cedar Branch T1 14.0
END DESCRIPTION:
XS GIS Cut Line= 3
      2712397.51      6789469.04      2712384.28      6789766.75
      2712376.91      6790047.35
#Sta/Elev= 30
  4702.0  353.03  4714.0  352.78  4744.0  353.72  4764.0  355.66  4774.0  355.69
  4784.0  354.65  4794.0  352.73  4804.1  352.58  4843.9  348.80  4848.9  347.88
  4854.1  347.48  4894.1  345.23  4904.2  345.78  4922.2  345.10  4922.4  344.60
  4925.9  344.60  4926.2  345.10  4934.2  345.52  4944.2  345.32  5014.3  346.26
  5054.3  345.61  5064.3  346.21  5094.3  346.51  5104.3  347.47  5114.3  347.32
  5122.1  347.94  5127.1  347.68  5174.3  350.00  5194.3  350.47  5280.7  353.95
#Mann=3,-1,0
  4702.0    0.05       0  4922.2    0.05       0  4926.2    0.05       0
Bank Sta=4922.2,4926.2
Exp/Cntr=0.3,0.1

Type RM Length L Ch R = 1,3714,137,137,137
BEGIN DESCRIPTION:
Mapping XS 2d300810
END DESCRIPTION:
XS GIS Cut Line= 2
      2712210.41      6789402.33      2712198.39      6789927.30
#Sta/Elev= 30
  4791.6  353.34  4800.3  353.04  4820.3  353.16  4840.3  352.85  4870.3  351.94
  4880.3  351.36  4920.3  349.71  4930.3  348.81  4940.3  345.20  4948.3  341.99
  4948.6  341.49  4952.1  341.49  4952.3  341.99  4980.3  342.80  5020.3  342.59
  5030.3  342.83  5040.3  342.74  5070.3  343.10  5080.3  342.89  5090.3  343.37
  5100.3  343.61  5110.4  344.30  5120.4  345.37  5140.4  346.70  5190.4  348.52
  5204.0  348.50  5210.4  349.62  5230.4  349.74  5300.4  352.45  5316.7  352.81
#Mann=3,-1,0
  4791.6    0.05       0  4948.3    0.05       0  4952.3    0.05       0
Bank Sta=4948.3,4952.3
Exp/Cntr=0.3,0.1

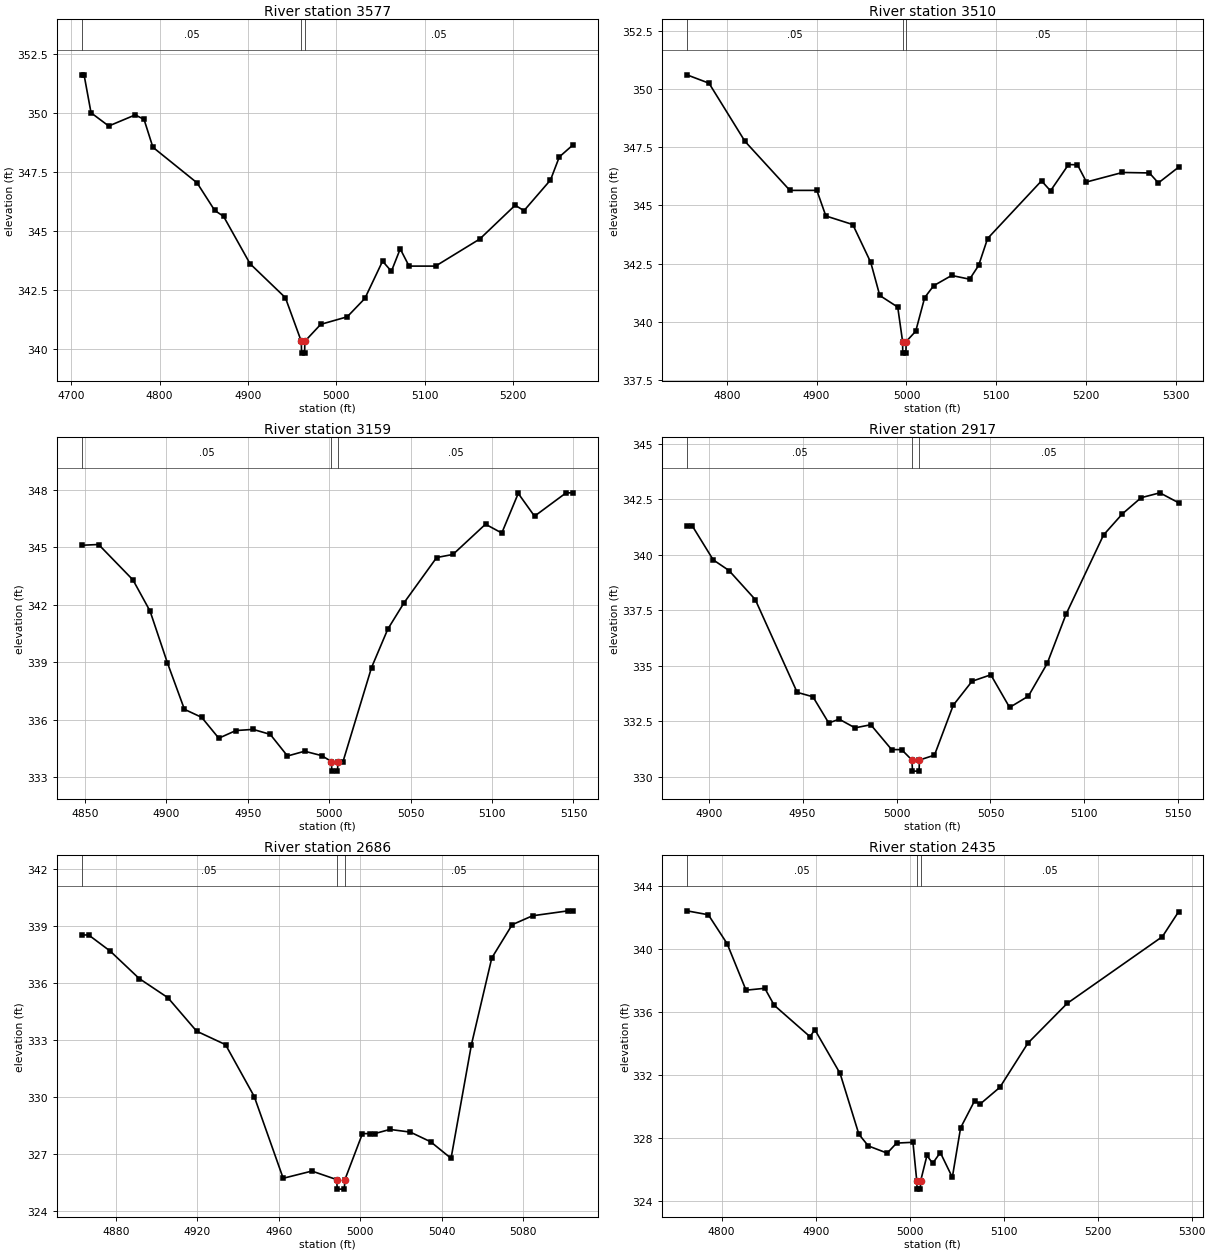
Type RM Length L Ch R = 1,3577,67,67,67
BEGIN DESCRIPTION:
Cedar Branch T1 13.0
END DESCRIPTION:
XS GIS Cut Line= 3
      2712099.55      6789340.24      2712092.69      6789628.45
      2712094.86      6789896.85
#Sta/Elev= 30
  4711.7  351.62  4714.6  351.62  4722.5  350.01  4742.5  349.45  4772.5  349.92
  4782.5  349.73  4792.5  348.55  4842.5  347.04  4862.5  345.87  4872.5  345.62
  4902.5  343.61  4942.5  342.17  4960.5  340.32  4960.8  339.82  4964.3  339.82
  4964.5  340.32  4982.5  341.04  5012.5  341.36  5032.5  342.14  5052.5  343.72
  5062.5  343.29  5072.5  344.24  5082.5  343.51  5112.5  343.51  5162.6  344.66
  5202.6  346.09  5212.6  345.86  5242.6  347.16  5252.6  348.14  5268.4  348.66
#Mann=3,-1,0
  4711.7    0.05       0  4960.5    0.05       0  4964.5    0.05       0
Bank Sta=4960.5,4964.5
Exp/Cntr=0.3,0.1

Type RM Length L Ch R = 1,3510,351,351,351
BEGIN DESCRIPTION:
Cedar Branch T1 12.0
END DESCRIPTION:
XS GIS Cut Line= 3
      2712045.20      6789336.39      2712046.16      6789580.69
      2712045.17      6789883.59
#Sta/Elev= 30
  4755.7  350.62  4780.3  350.26  4820.3  347.76  4870.3  345.65  4900.3  345.65
  4910.3  344.55  4940.3  344.18  4960.3  342.55  4970.3  341.13  4990.3  340.63
  4995.7  339.15  4995.9  338.65  4999.4  338.65  4999.7  339.15  5010.3  339.59
  5020.3  341.04  5030.3  341.55  5050.3  341.99  5070.3  341.83  5080.3  342.42
  5090.3  343.58  5150.3  346.06  5160.3  345.63  5180.3  346.76  5190.3  346.75
  5200.3  346.01  5240.3  346.42  5270.3  346.40  5280.3  345.97  5302.9  346.65
#Mann=3,-1,0
  4755.7    0.05       0  4995.7    0.05       0  4999.7    0.05       0
Bank Sta=4995.7,4999.7
Exp/Cntr=0.3,0.1

Type RM Length L Ch R = 1,3159,242,242,242
BEGIN DESCRIPTION:
Cedar Branch T1 11.0
END DESCRIPTION:
XS GIS Cut Line= 3
      2711775.99      6789411.02      2711726.00      6789561.00
      2711721.17      6789704.83
#Sta/Elev= 30
  4847.9  345.11  4858.4  345.15  4879.5  343.30  4890.0  341.67  4900.6  338.98
  4911.1  336.54  4921.7  336.12  4932.2  335.03  4942.7  335.43  4953.3  335.49
  4963.8  335.23  4974.4  334.10  4984.9  334.35  4995.4  334.12  5001.4  333.81
  5001.6  333.31  5005.1  333.31  5005.4  333.81  5008.5  333.81  5026.0  338.72
  5036.0  340.73  5046.0  342.11  5066.0  344.47  5076.0  344.63  5096.0  346.21
  5106.0  345.75  5116.1  347.82  5126.1  346.63  5145.5  347.85  5149.9  347.85
#Mann=3,-1,0
  4847.9    0.05       0  5001.4    0.05       0  5005.4    0.05       0
Bank Sta=5001.4,5005.4
Exp/Cntr=0.3,0.1

Type RM Length L Ch R = 1,2917,231,231,231
BEGIN DESCRIPTION:
Cedar Branch T1 10.0
END DESCRIPTION:
XS GIS Cut Line= 3
      2711576.02      6789360.97      2711526.00      6789461.00
      2711526.00      6789610.96
#Sta/Elev= 30
  4888.4  341.32  4891.2  341.32  4902.4  339.78  4910.8  339.30  4924.8  337.99
  4947.1  333.81  4955.5  333.61  4963.9  332.43  4969.5  332.60  4977.9  332.21
  4986.3  332.35  4997.4  331.23  5002.7  331.23  5008.2  330.76  5008.5  330.26
  5012.0  330.26  5012.2  330.76  5020.2  330.98  5030.2  333.23  5040.2  334.31
  5050.2  334.60  5060.2  333.13  5070.2  333.64  5080.2  335.11  5090.2  337.32
  5110.2  340.90  5120.2  341.85  5130.2  342.58  5140.2  342.80  5150.2  342.35
#Mann=3,-1,0
  4888.4    0.05       0  5008.2    0.03       0  5012.2    0.05       0
Bank Sta=5008.2,5012.2
Exp/Cntr=0.3,0.1

Type RM Length L Ch R = 1,2686,251,251,251
BEGIN DESCRIPTION:
Cedar Branch T1 9.0
END DESCRIPTION:
XS GIS Cut Line= 3
      2711425.98      6789261.02      2711326.00      6789361.00
      2711326.00      6789461.01
#Sta/Elev= 27
  4863.2  338.53  4866.7  338.53  4877.3  337.68  4891.5  336.24  4905.6  335.23
  4919.7  333.47  4933.9  332.76  4948.0  330.03  4962.2  325.73  4976.3  326.11
  4988.5  325.66  4988.7  325.16  4992.2  325.16  4992.5  325.66  5001.1  328.08
  5004.6  328.08  5007.1  328.08  5014.6  328.30  5024.6  328.16  5034.6  327.65
  5044.6  326.78  5054.6  332.76  5064.6  337.32  5074.6  339.07  5084.6  339.54
  5102.1  339.80  5104.6  339.80
#Mann=3,-1,0
  4863.2    0.05       0  4988.5    0.03       0  4992.5    0.05       0
Bank Sta=4988.5,4992.5
Exp/Cntr=0.3,0.1

Type RM Length L Ch R = 1,2435,237,237,237
BEGIN DESCRIPTION:
Cedar Branch T1 8.0
END DESCRIPTION:
XS GIS Cut Line= 3
      2711508.79      6789149.22      2711276.00      6789161.00
      2711110.57      6789399.32
#Sta/Elev= 30
  4763.0  342.45  4785.8  342.20  4805.8  340.36  4825.9  337.40  4845.9  337.52
  4855.9  336.44  4894.0  334.44  4899.1  334.89  4926.0  332.10  4946.0  328.23
  4956.0  327.49  4976.1  327.03  4986.1  327.67  5003.5  327.72  5007.6  325.24
  5007.9  324.74  5011.4  324.74  5011.6  325.24  5018.4  326.88  5024.5  326.38
  5032.6  327.07  5045.4  325.49  5054.2  328.64  5069.0  330.35  5075.1  330.16
  5096.0  331.22  5125.8  334.03  5167.6  336.56  5268.9  340.81  5286.2  342.40
#Mann=3,-1,0
  4763.0    0.05       0  5007.6    0.03       0  5011.6    0.05       0
Bank Sta=5007.6,5011.6
Exp/Cntr=0.3,0.1

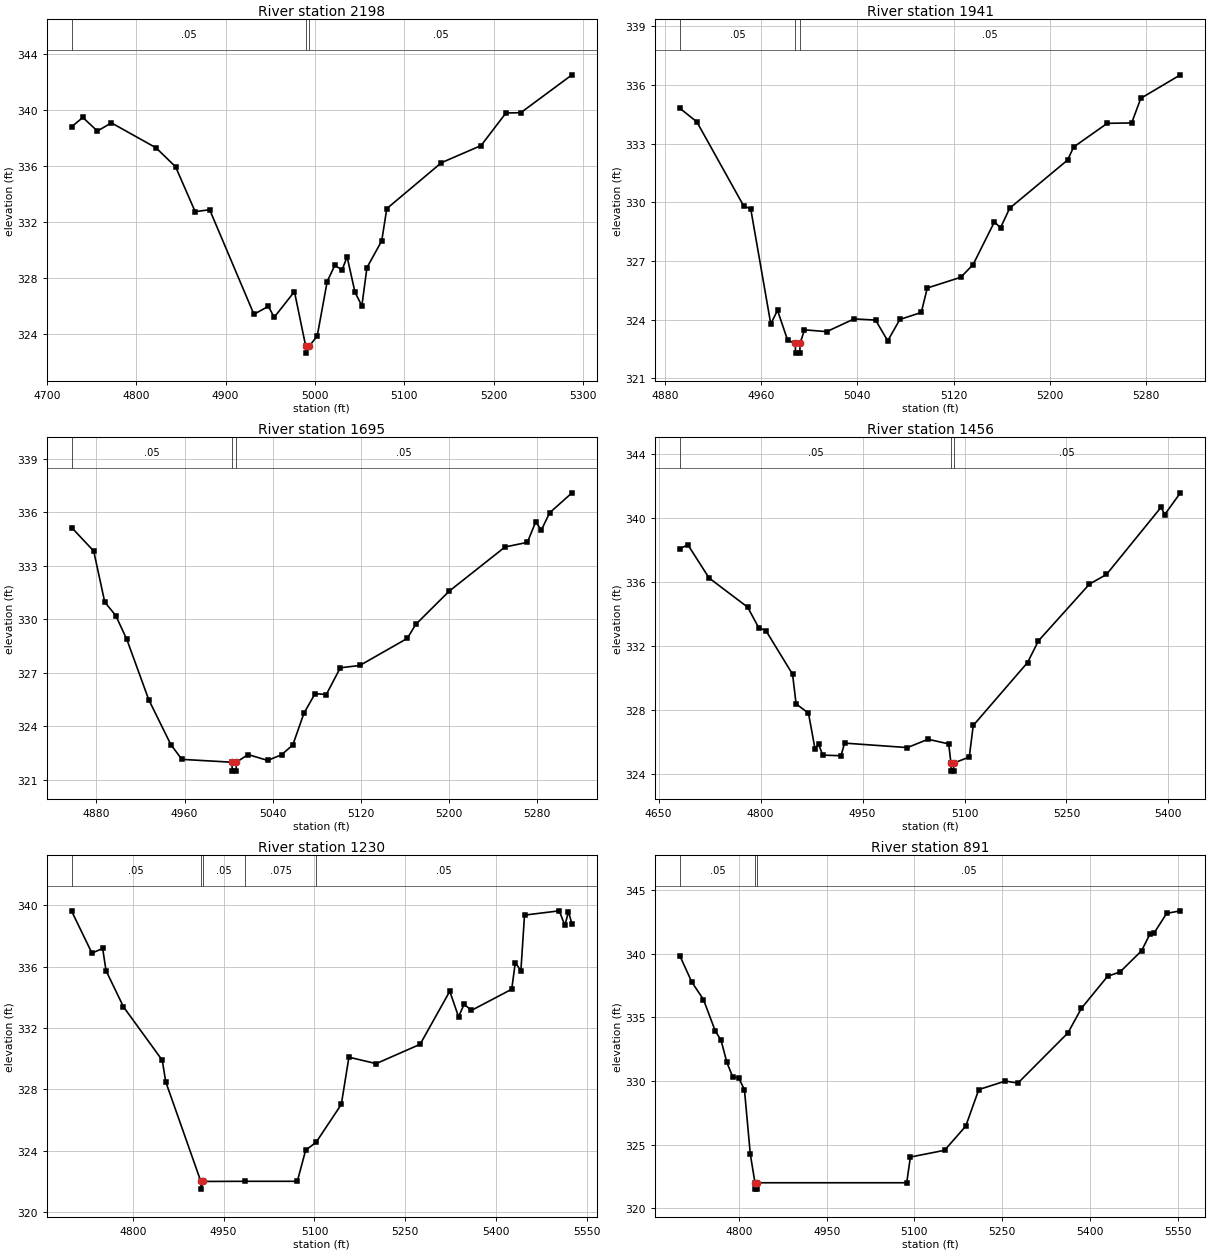
Type RM Length L Ch R = 1,2198,257,257,257
BEGIN DESCRIPTION:
Cedar Branch T1 7.0
END DESCRIPTION:
XS GIS Cut Line= 3
      2711315.15      6788931.76      2711076.00      6789061.00
      2710944.88      6789317.05
#Sta/Elev= 30
  4727.9  338.82  4740.4  339.48  4756.6  338.51  4772.4  339.09  4822.2  337.31
  4844.1  335.95  4866.0  332.74  4882.2  332.88  4931.7  325.40  4947.9  325.97
  4954.3  325.18  4977.0  327.02  4989.6  323.12  4989.9  322.62  4993.6  323.12
  5002.5  323.85  5013.6  327.74  5022.2  328.91  5030.2  328.56  5035.9  329.51
  5044.7  326.98  5052.4  326.00  5058.1  328.74  5074.6  330.65  5080.3  332.96
  5141.3  336.24  5185.7  337.47  5213.5  339.80  5230.1  339.82  5287.4  342.53
#Mann=3,-1,0
  4727.9    0.05       0  4989.6    0.03       0  4993.6    0.05       0
Bank Sta=4989.6,4993.6
Exp/Cntr=0.3,0.1

Type RM Length L Ch R = 1,1941,246,246,246
BEGIN DESCRIPTION:
Cedar Branch T1 6.0
END DESCRIPTION:
XS GIS Cut Line= 3
      2711025.97      6788811.01      2710926.00      6788861.00
      2710876.00      6789160.99
#Sta/Elev= 30
  4892.6  334.80  4906.5  334.12  4945.7  329.79  4951.3  329.68  4968.0  323.78
  4973.6  324.48  4982.0  322.95  4988.4  322.79  4988.6  322.29  4992.1  322.29
  4992.4  322.79  4996.0  323.48  5014.5  323.39  5037.3  324.04  5055.1  323.98
  5065.2  322.92  5075.3  324.01  5093.1  324.37  5098.1  325.62  5126.0  326.17
  5136.2  326.82  5153.9  329.00  5159.0  328.70  5166.6  329.70  5214.7  332.16
  5219.8  332.83  5247.7  334.04  5268.0  334.06  5275.6  335.32  5308.5  336.52
#Mann=3,-1,0
  4892.6    0.05       0  4988.4    0.03       0  4992.4    0.05       0
Bank Sta=4988.4,4992.4
Exp/Cntr=0.3,0.1

Type RM Length L Ch R = 1,1695,239,239,239
BEGIN DESCRIPTION:
Cedar Branch T1 5.0
END DESCRIPTION:
XS GIS Cut Line= 3
      2710776.00      6788711.02      2710776.00      6788861.00
      2710826.00      6789160.99
#Sta/Elev= 30
  4857.6  335.15  4877.6  333.83  4887.6  330.97  4897.6  330.21  4907.6  328.88
  4927.6  325.48  4947.6  322.97  4957.6  322.14  5003.1  321.98  5003.3  321.48
  5006.8  321.48  5007.1  321.98  5017.7  322.41  5035.5  322.08  5048.1  322.40
  5058.3  322.95  5068.4  324.73  5078.5  325.83  5088.7  325.78  5101.4  327.28
  5119.1  327.41  5162.2  328.93  5169.8  329.71  5200.2  331.58  5250.9  334.06
  5271.2  334.32  5278.8  335.48  5283.8  335.00  5291.4  335.98  5311.7  337.10
#Mann=3,-1,0
  4857.6    0.05       0  5003.1    0.05       0  5007.1    0.05       0
Bank Sta=5003.1,5007.1
Exp/Cntr=0.3,0.1

Type RM Length L Ch R = 1,1456,226,226,226
BEGIN DESCRIPTION:
Cedar Branch T1 4.0
END DESCRIPTION:
XS GIS Cut Line= 3
      2710669.41      6788600.10      2710576.00      6788911.00
      2710719.40      6789296.68
#Sta/Elev= 30
  4681.5  338.07  4692.9  338.32  4724.2  336.24  4780.9  334.42  4797.3  333.13
  4807.7  332.96  4847.0  330.23  4852.2  328.38  4870.4  327.80  4880.0  325.58
  4885.3  325.87  4891.3  325.18  4918.3  325.14  4923.5  325.93  5016.0  325.65
  5046.3  326.17  5076.7  325.88  5080.0  324.68  5080.3  324.18  5083.8  324.18
  5084.0  324.68  5107.0  325.06  5112.8  327.03  5192.7  330.96  5208.8  332.32
  5283.8  335.86  5308.8  336.46  5389.2  340.66  5394.5  340.20  5417.6  341.56
#Mann=3,-1,0
  4681.5    0.05       0  5080.0    0.05       0  5084.0    0.05       0
Bank Sta=5080,5084
Exp/Cntr=0.3,0.1

Type RM Length L Ch R = 1,1230,339,339,339
BEGIN DESCRIPTION:
Cedar Branch T1 3.0
END DESCRIPTION:
XS GIS Cut Line= 3
      2710247.89      6788694.33      2710369.95      6788969.15
      2710654.35      6789410.56
#Sta/Elev= 30
  4699.3  339.60  4732.8  336.87  4750.4  337.18  4756.0  335.73  4784.8  333.37
  4848.8  329.89  4854.5  328.49  4912.5  321.99  4912.7  321.49  4916.5  321.99
  4985.7  322.00  5071.7  322.00  5085.5  324.03  5102.7  324.54  5144.3  327.01
  5156.9  330.09  5201.8  329.67  5274.4  330.93  5323.4  334.39  5337.8  332.72
  5347.0  333.54  5359.1  333.14  5425.6  334.52  5431.5  336.26  5440.7  335.72
  5446.7  339.35  5504.1  339.63  5513.3  338.68  5519.3  339.57  5525.1  338.76
#Mann=5,-1,0
  4699.3    0.05       0  4912.5    0.07       0  4916.5    0.05       0
  4985.7   0.075       0  5102.7    0.05       0
Bank Sta=4912.5,4916.5
Exp/Cntr=0.3,0.1

Type RM Length L Ch R = 1,891,299,299,299
BEGIN DESCRIPTION:
Cedar Branch T1 2.0
END DESCRIPTION:
XS GIS Cut Line= 3
      2710076.00      6788810.96      2710076.00      6789111.00
      2710363.42      6789585.73
#Sta/Elev= 30
  4699.5  339.79  4719.5  337.77  4739.5  336.39  4759.5  333.94  4769.5  333.20
  4779.5  331.45  4789.5  330.31  4799.5  330.25  4809.5  329.31  4819.5  324.25
  4827.5  322.00  4827.8  321.50  4831.3  321.50  4831.5  322.00  5086.8  322.00
  5093.1  324.02  5151.5  324.55  5187.7  326.45  5210.0  329.32  5255.5  329.99
  5276.9  329.83  5362.3  333.77  5385.3  335.70  5430.1  338.22  5451.4  338.56
  5488.3  340.23  5502.2  341.52  5509.6  341.62  5531.0  343.16  5554.5  343.36
#Mann=3,-1,0
  4699.5    0.05       0  4827.5    0.05       0  4831.5    0.05       0
Bank Sta=4827.5,4831.5
Exp/Cntr=0.3,0.1

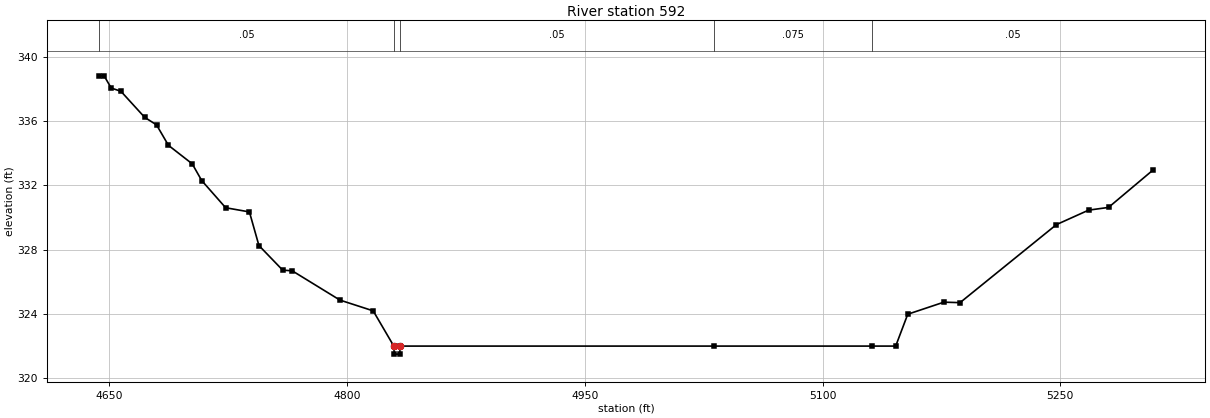
Type RM Length L Ch R = 1,592,0,0,0
BEGIN DESCRIPTION:
Cedar Branch T1 1.0
END DESCRIPTION:
XS GIS Cut Line= 3
      2709976.02      6788810.97      2709776.00      6789111.00
      2709826.00      6789410.98
#Sta/Elev= 30
  4643.6  338.80  4646.6  338.80  4651.1  338.04  4657.2  337.84  4672.2  336.22
  4679.7  335.75  4687.2  334.48  4702.2  333.33  4708.2  332.29  4723.3  330.60
  4738.3  330.34  4744.3  328.25  4759.3  326.72  4765.3  326.68  4795.4  324.86
  4816.4  324.19  4829.4  322.00  4829.7  321.50  4833.2  321.50  4833.4  322.00
  5031.6  322.00  5131.2  322.00  5146.1  322.00  5153.7  323.98  5176.5  324.73
  5186.7  324.70  5247.5  329.55  5267.8  330.45  5280.4  330.62  5308.3  332.93
#Mann=5,-1,0
  4643.6    0.05       0  4829.4    0.03       0  4833.4    0.05       0
  5031.6   0.075       0  5131.2    0.05       0
Bank Sta=4829.4,4833.4
Exp/Cntr=0.3,0.1

Chan Stop Cuts=-1