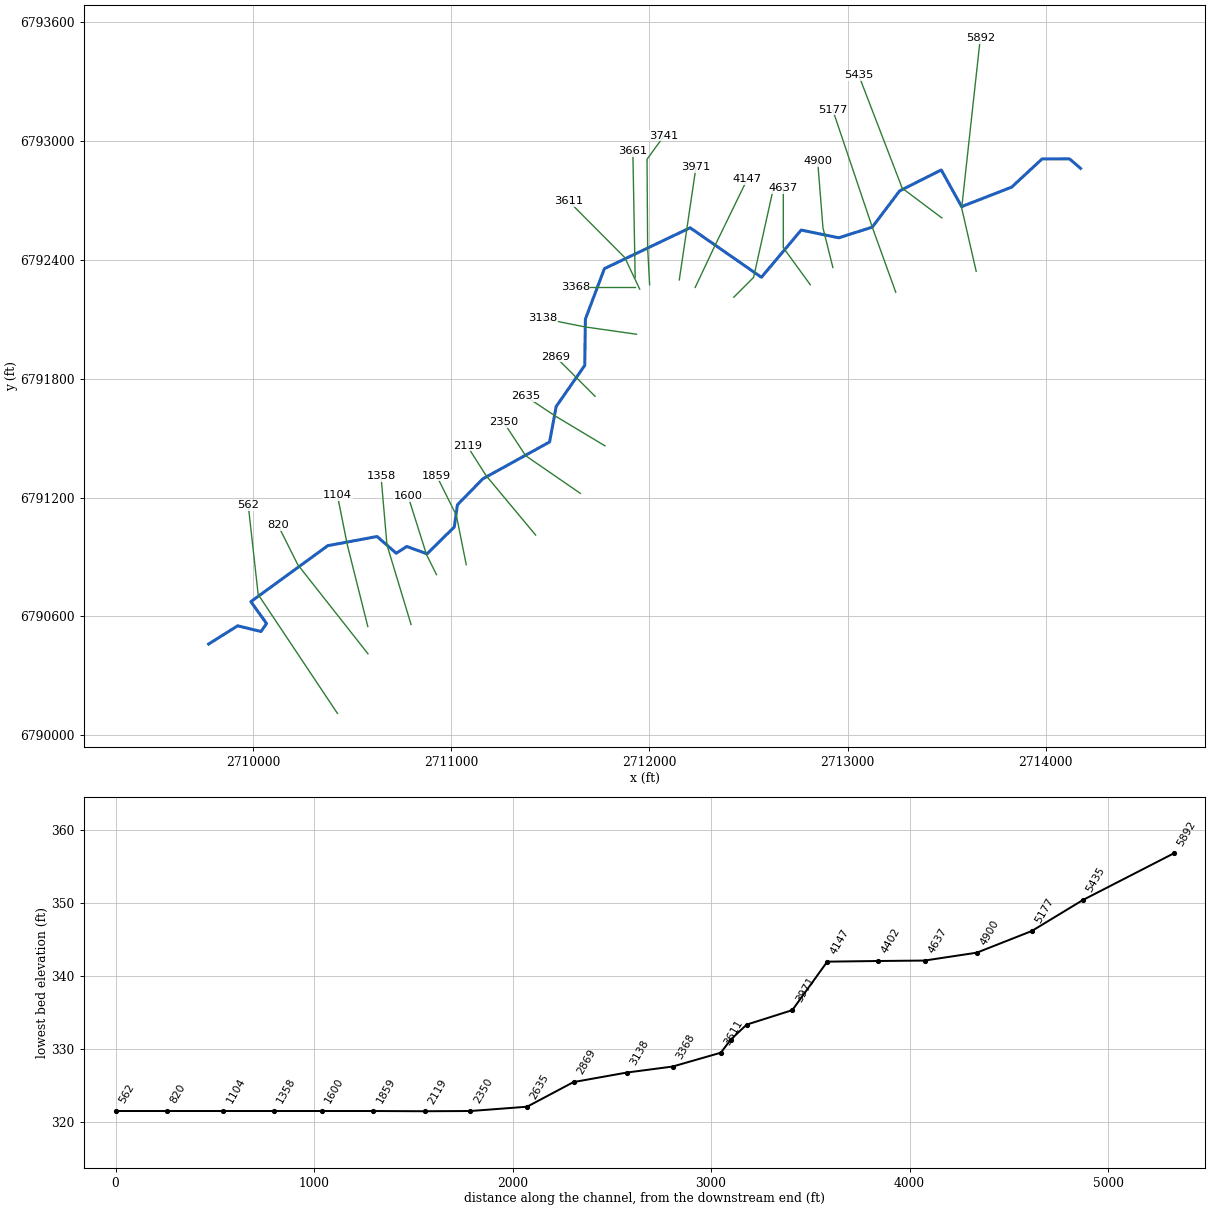
--- Cedar Branch T2.prj (project) ---

Proj Title=Cedar Branch T2 Base Level Engineering
Current Plan=p01
Default Exp/Contr=0.3,0.1
English Units
Geom File=g01
Flow File=f01
Plan File=p01
BEGIN DESCRIPTION:
Cedar Branch T2
END DESCRIPTION:

--- Cedar Branch T2.p01 (plan) ---

Plan Title=Multiple Run
Short Identifier=Multiple
Geom File=g01
Flow File=f01
Subcritical Flow
K Sum by GR= 0
Std Step Tol= 0.01
Critical Tol= 0.01
Num of Std Step Trials= 20
Max Error Tol= 0.3
Flow Tol Ratio= 0.001
Split Flow NTrial= 30
Split Flow Tol= 0.02
Split Flow Ratio= 0.02
Log Output Level= 0
Friction Slope Method= 1
Unsteady Friction Slope Method= 2
Unsteady Bridges Friction Slope Method= 1
Parabolic Critical Depth
Global Vel Dist=  1 , 1 , 1
Global Log Level= 0
CheckData=True
Encroach Param= -1, 0, 0, 0
BEGIN DESCRIPTION:
Multiple Run
END DESCRIPTION:

--- Cedar Branch T2.f01 (steady flow) ---

Flow Title=Multiple
Number of Profiles=7
Profile Names=10-year,25-year,50-year,1pct_min,100-year,1pct_plu,500-year
River Rch & RM= Cedar Branch T2,Reach-1,5892
     229     288     333     192     383     765     505
River Rch & RM= Cedar Branch T2,Reach-1,3741
     351     453     533     312     622    1241     845
Boundary for River Rch & Prof#=Cedar Branch T2,Reach-1,1
Up Type=0
Dn Type=3
Dn Slope=0.005
Boundary for River Rch & Prof#=Cedar Branch T2,Reach-1,2
Up Type=0
Dn Type=3
Dn Slope=0.005
Boundary for River Rch & Prof#=Cedar Branch T2,Reach-1,3
Up Type=0
Dn Type=3
Dn Slope=0.005
Boundary for River Rch & Prof#=Cedar Branch T2,Reach-1,4
Up Type=0
Dn Type=3
Dn Slope=0.005
Boundary for River Rch & Prof#=Cedar Branch T2,Reach-1,5
Up Type=0
Dn Type=3
Dn Slope=0.005
Boundary for River Rch & Prof#=Cedar Branch T2,Reach-1,6
Up Type=0
Dn Type=3
Dn Slope=0.005
Boundary for River Rch & Prof#=Cedar Branch T2,Reach-1,7
Up Type=0
Dn Type=3
Dn Slope=0.005

--- Cedar Branch T2.g01 (geometry) ---

Geom Title=Existing Conditions

River Reach=Cedar Branch T2,Reach-1
Reach XY= 30
      2714176.00      6792861.00      2714120.21      6792909.12
      2713981.85      6792908.96      2713828.43      6792766.52
      2713575.67      6792668.19      2713472.98      6792853.25
      2713262.76      6792747.39      2713124.72      6792564.52
      2712955.79      6792510.79      2712766.00      6792549.77
      2712565.51      6792311.49      2712205.87      6792561.41
      2711773.16      6792355.17      2711677.20      6792100.50
      2711673.94      6791866.86      2711529.76      6791659.44
      2711496.58      6791480.59      2711159.32      6791294.36
      2711031.52      6791163.43      2711015.48      6791051.21
      2710878.29      6790916.11      2710775.91      6790953.16
      2710722.66      6790919.02      2710626.00      6791003.44
      2710377.50      6790957.38      2709989.27      6790674.68
      2710068.46      6790564.10      2710040.05      6790524.14
      2709922.69      6790552.95      2709776.00      6790461.00

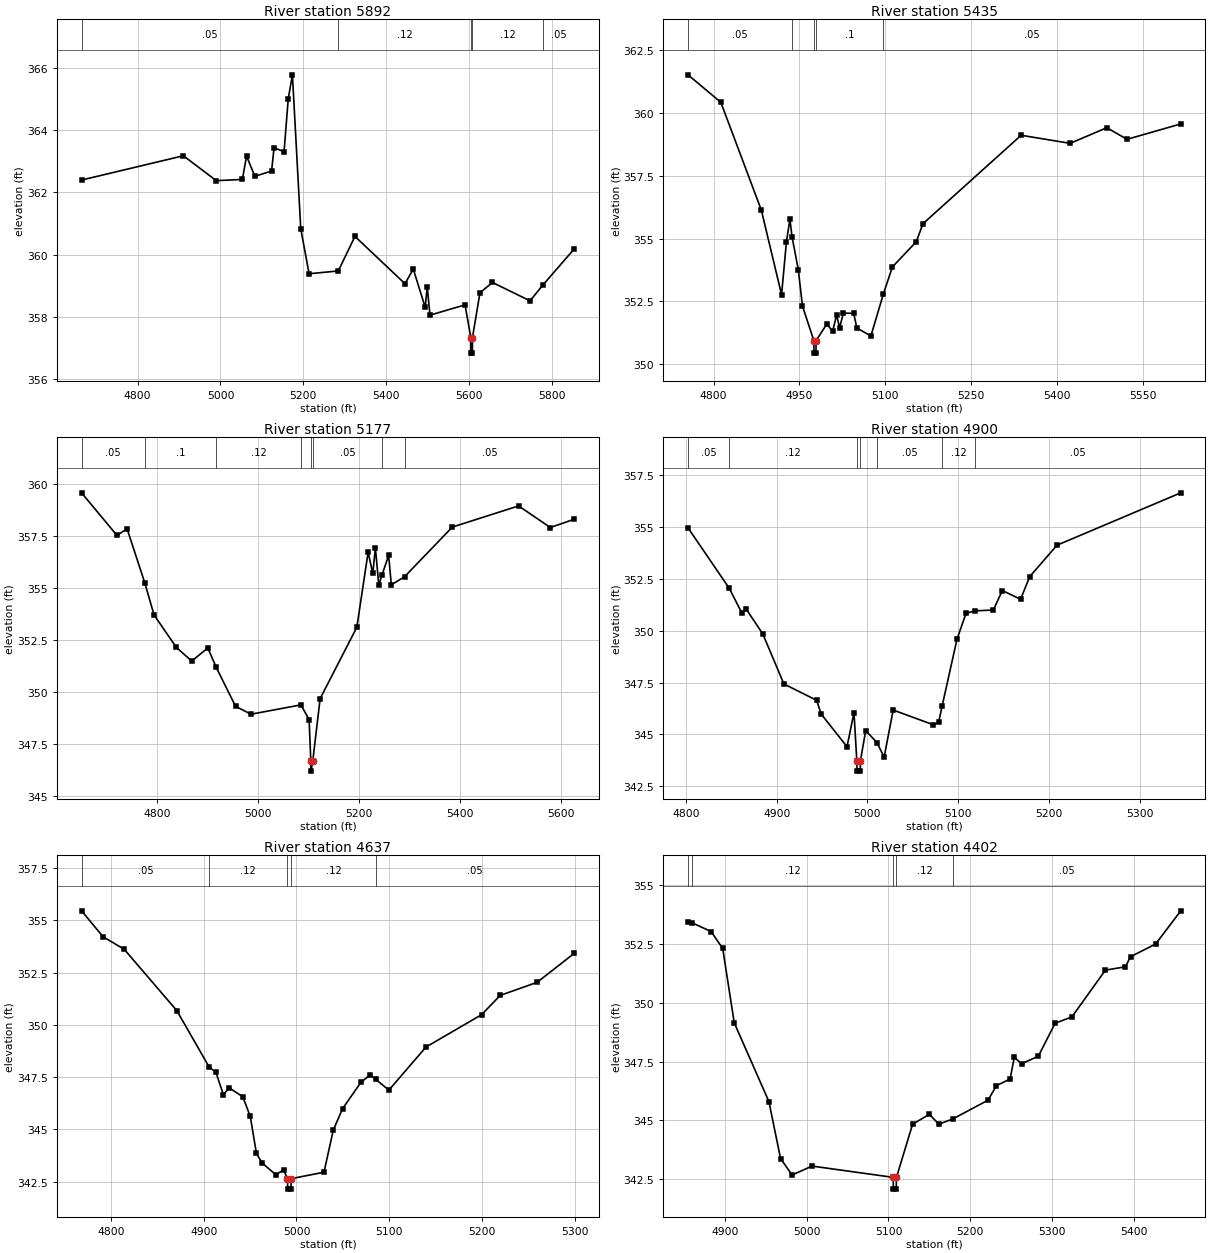
Type RM Length L Ch R = 1,5892,457,457,457
BEGIN DESCRIPTION:
Cedar Branch T2 21.0
END DESCRIPTION:
XS GIS Cut Line= 3
      2713649.15      6792341.49      2713576.00      6792661.00
      2713669.80      6793517.30
#Sta/Elev= 30
  4664.8  362.40  4910.5  363.18  4990.0  362.38  5052.9  362.42  5063.0  363.17
  5083.1  362.52  5123.4  362.69  5129.4  363.44  5153.5  363.31  5163.6  365.01
  5173.7  365.78  5193.8  360.84  5213.9  359.39  5284.4  359.48  5324.6  360.59
  5445.3  359.07  5465.4  359.54  5494.1  358.31  5499.1  358.97  5505.6  358.06
  5590.3  358.39  5604.2  357.34  5604.5  356.84  5608.0  356.84  5608.2  357.34
  5626.3  358.78  5656.5  359.11  5747.1  358.52  5778.3  359.03  5854.0  360.19
#Mann=5,-1,0
  4664.8    0.05       0  5284.4    0.12       0  5604.2    0.04       0
  5608.2    0.12       0  5778.3    0.05       0
Bank Sta=5604.2,5608.2
Exp/Cntr=0.3,0.1

Type RM Length L Ch R = 1,5435,258,258,258
BEGIN DESCRIPTION:
Cedar Branch T2 20.0
END DESCRIPTION:
XS GIS Cut Line= 3
      2713475.99      6792611.01      2713276.00      6792761.00
      2713056.36      6793331.39
#Sta/Elev= 30
  4755.2  361.50  4812.5  360.41  4883.3  356.13  4918.7  352.77  4927.1  354.85
  4933.3  355.77  4936.9  355.08  4947.9  353.77  4955.2  352.32  4975.1  350.95
  4975.3  350.45  4978.8  350.45  4979.1  350.95  4997.9  351.61  5007.9  351.31
  5014.8  351.96  5020.2  351.46  5026.6  352.04  5044.8  352.03  5050.2  351.45
  5074.8  351.13  5096.4  352.78  5112.3  353.87  5154.0  354.87  5165.9  355.59
  5337.4  359.10  5423.1  358.78  5487.1  359.40  5522.5  358.94  5616.4  359.55
#Mann=5,-1,0
  4755.2    0.05       0  4936.9     0.1       0  4975.1    0.07       0
  4979.1     0.1       0  5096.4    0.05       0
Bank Sta=4975.1,4979.1
Exp/Cntr=0.3,0.1

Type RM Length L Ch R = 1,5177,277,277,277
BEGIN DESCRIPTION:
Cedar Branch T2 19.0
END DESCRIPTION:
XS GIS Cut Line= 3
      2713243.32      6792235.99      2713126.00      6792561.00
      2712924.81      6793157.76
#Sta/Elev= 30
  4650.7  359.59  4720.8  357.54  4740.8  357.86  4775.9  355.25  4794.2  353.71
  4838.2  352.15  4868.8  351.49  4900.6  352.12  4917.2  351.19  4955.5  349.31
  4986.2  348.93  5084.9  349.38  5101.1  348.67  5104.4  346.69  5104.7  346.19
  5108.4  346.69  5122.9  349.68  5195.6  353.12  5217.9  356.73  5227.1  355.71
  5232.3  356.94  5239.0  355.15  5245.2  355.62  5258.5  356.58  5263.8  355.16
  5290.0  355.55  5384.5  357.94  5515.7  358.96  5578.6  357.92  5626.0  358.32
#Mann=8,-1,0
  4650.7    0.05       0  4775.9     0.1       0  4917.2    0.12       0
  5084.9    0.05       0  5104.4    0.07       0  5108.4    0.05       0
  5245.2    0.12       0  5290.0    0.05       0
Bank Sta=5104.4,5108.4
Exp/Cntr=0.3,0.1

Type RM Length L Ch R = 1,4900,263,263,263
BEGIN DESCRIPTION:
Cedar Branch T2 18.0
END DESCRIPTION:
XS GIS Cut Line= 3
      2712926.01      6792360.98      2712876.00      6792561.00
      2712849.37      6792897.07
#Sta/Elev= 30
  4802.2  354.97  4847.8  352.04  4861.5  350.86  4866.6  351.03  4884.7  349.84
  4907.9  347.43  4944.0  346.64  4949.1  345.97  4977.5  344.40  4985.2  346.05
  4988.3  343.72  4988.6  343.22  4992.1  343.22  4992.3  343.72  4998.1  345.18
  5010.7  344.59  5018.4  343.89  5028.4  346.17  5072.6  345.46  5078.6  345.59
  5082.3  346.35  5098.7  349.58  5108.7  350.84  5118.4  350.96  5138.8  351.00
  5148.8  351.94  5168.9  351.52  5178.9  352.61  5209.0  354.13  5345.5  356.66
#Mann=7,-1,0
  4802.2    0.05       0  4847.8    0.12       0  4988.3    0.07       0
  4992.3    0.12       0  5010.7    0.05       0  5082.3    0.12       0
  5118.4    0.05       0
Bank Sta=4988.3,4992.3
Exp/Cntr=0.3,0.1

Type RM Length L Ch R = 1,4637,235,235,235
BEGIN DESCRIPTION:
Cedar Branch T2 17.0
END DESCRIPTION:
XS GIS Cut Line= 3
      2712812.11      6792273.76      2712676.00      6792461.00
      2712676.00      6792761.01
#Sta/Elev= 30
  4768.2  355.46  4791.4  354.22  4814.2  353.62  4871.0  350.68  4905.9  347.98
  4913.1  347.73  4921.2  346.66  4927.4  346.99  4942.1  346.56  4950.2  345.62
  4956.8  343.85  4963.0  343.39  4977.7  342.83  4986.2  343.06  4990.3  342.64
  4990.6  342.14  4994.1  342.14  4994.3  342.64  5029.7  342.95  5039.7  344.96
  5049.7  345.99  5069.7  347.26  5079.7  347.61  5085.6  347.39  5099.7  346.88
  5139.7  348.94  5199.7  350.49  5219.7  351.41  5259.7  352.04  5299.7  353.43
#Mann=5,-1,0
  4768.2    0.05       0  4905.9    0.12       0  4990.3    0.07       0
  4994.3    0.12       0  5085.6    0.05       0
Bank Sta=4990.3,4994.3
Exp/Cntr=0.3,0.1

Type RM Length L Ch R = 1,4402,255,255,255
BEGIN DESCRIPTION:
Cedar Branch T2 16.0
END DESCRIPTION:
XS GIS Cut Line= 3
      2712426.04      6792211.04      2712526.00      6792311.00
      2712625.99      6792760.95
#Sta/Elev= 30
  4855.0  353.43  4859.4  353.41  4883.2  353.03  4897.4  352.31  4911.5  349.15
  4953.9  345.80  4968.1  343.38  4982.2  342.68  5006.6  343.06  5105.8  342.58
  5106.0  342.08  5109.5  342.08  5109.8  342.58  5129.5  344.84  5150.0  345.26
  5161.6  344.84  5178.4  345.06  5221.7  345.86  5232.0  346.48  5248.6  346.76
  5253.8  347.68  5262.7  347.41  5283.2  347.73  5303.7  349.13  5324.2  349.40
  5365.2  351.39  5389.5  351.53  5395.9  351.96  5426.6  352.50  5457.3  353.91
#Mann=5,-1,0
  4855.0    0.05       0  4859.4    0.12       0  5105.8    0.07       0
  5109.8    0.12       0  5178.4    0.05       0
Bank Sta=5105.8,5109.8
Exp/Cntr=0.3,0.1

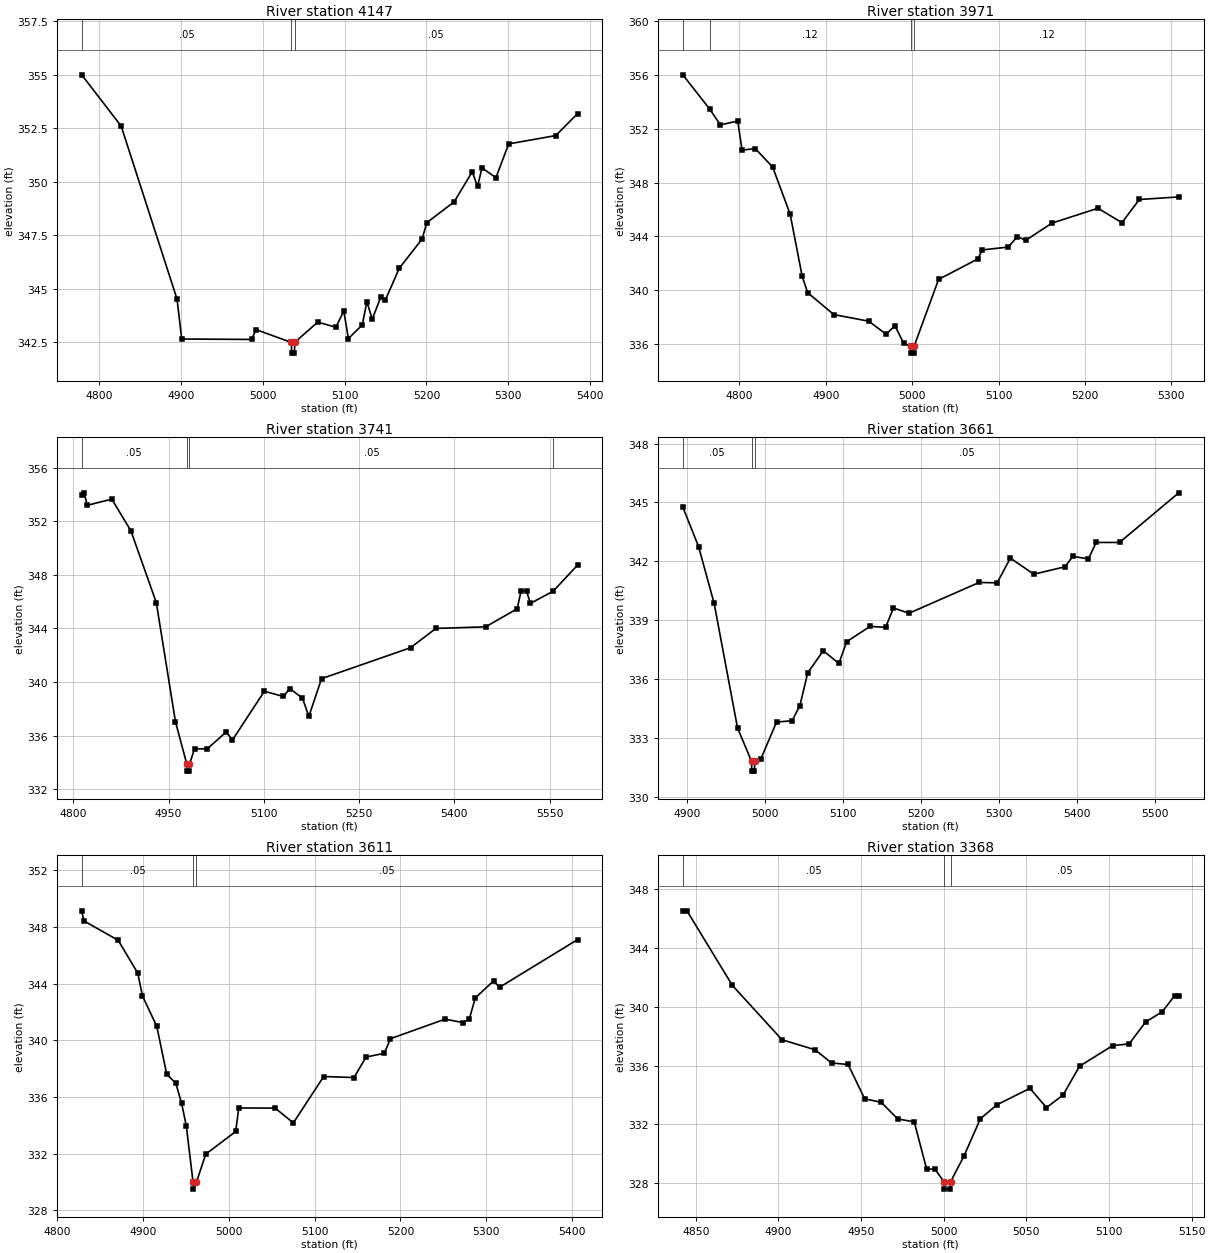
Type RM Length L Ch R = 1,4147,176,176,176
BEGIN DESCRIPTION:
Cedar Branch T2 15.0
END DESCRIPTION:
XS GIS Cut Line= 3
      2712231.27      6792260.40      2712326.00      6792461.00
      2712494.20      6792806.83
#Sta/Elev= 30
  4778.4  355.00  4826.7  352.60  4895.0  344.51  4900.7  342.65  4986.1  342.63
  4991.6  343.09  5034.8  342.49  5035.1  341.99  5038.6  341.99  5038.8  342.49
  5067.0  343.44  5089.2  343.20  5098.9  343.96  5104.5  342.67  5121.5  343.31
  5127.1  344.39  5133.7  343.58  5144.0  344.60  5149.6  344.46  5166.6  345.95
  5194.7  347.33  5200.4  348.09  5233.8  349.06  5256.0  350.47  5262.4  349.78
  5267.9  350.65  5284.9  350.19  5300.5  351.77  5358.1  352.16  5384.8  353.19
#Mann=3,-1,0
  4778.4    0.05       0  5034.8    0.05       0  5038.8    0.05       0
Bank Sta=5034.8,5038.8
Exp/Cntr=0.3,0.1

Type RM Length L Ch R = 1,3971,230,230,230
BEGIN DESCRIPTION:
Mapping XS 89e60ff9
END DESCRIPTION:
XS GIS Cut Line= 2
      2712150.96      6792298.02      2712235.03      6792866.13
#Sta/Elev= 30
  4734.4  355.99  4765.5  353.45  4777.9  352.28  4798.0  352.56  4803.0  350.40
  4818.3  350.52  4838.5  349.14  4858.7  345.65  4872.6  341.05  4878.9  339.83
  4909.3  338.20  4949.7  337.71  4969.9  336.74  4980.0  337.38  4990.1  336.07
  4998.2  335.84  4998.5  335.34  5002.0  335.34  5002.2  335.84  5030.6  340.81
  5076.1  342.33  5081.2  343.00  5111.4  343.21  5121.6  343.98  5131.7  343.72
  5162.0  344.99  5215.2  346.09  5242.9  345.02  5263.1  346.74  5308.7  346.93
#Mann=4,-1,0
  4734.4    0.05       0  4765.5    0.12       0  4998.2    0.07       0
  5002.2    0.12       0
Bank Sta=4998.2,5002.2
Exp/Cntr=0.3,0.1

Type RM Length L Ch R = 1,3741,80,80,80
BEGIN DESCRIPTION:
Cedar Branch T2 14.0
END DESCRIPTION:
XS GIS Cut Line= 4
      2712001.28      6792273.62      2711991.39      6792460.06
      2711988.24      6792907.11      2712074.61      6793026.10
#Sta/Elev= 30
  4813.3  353.99  4817.1  354.12  4822.1  353.19  4860.7  353.65  4890.8  351.28
  4930.8  345.92  4960.9  337.04  4978.9  333.85  4979.2  333.35  4982.7  333.35
  4982.9  333.85  4990.9  335.02  5010.9  335.01  5040.9  336.28  5050.6  335.67
  5100.9  339.31  5130.9  338.92  5140.9  339.51  5160.9  338.80  5170.9  337.43
  5190.9  340.25  5331.0  342.56  5371.0  344.00  5449.4  344.12  5499.0  345.47
  5505.2  346.82  5513.7  346.79  5519.8  345.87  5555.7  346.78  5594.1  348.73
#Mann=4,-1,0
  4813.3    0.05       0  4978.9    0.05       0  4982.9    0.05       0
  5555.7    0.12       0
Bank Sta=4978.9,4982.9
Exp/Cntr=0.3,0.1

Type RM Length L Ch R = 1,3661,50,50,50
BEGIN DESCRIPTION:
Mapping XS 0f57eb7f
END DESCRIPTION:
XS GIS Cut Line= 2
      2711928.34      6792310.82      2711916.70      6792946.92
#Sta/Elev= 30
  4894.6  344.76  4914.8  342.75  4934.8  339.85  4964.8  333.50  4982.8  331.80
  4983.0  331.30  4986.5  331.30  4986.8  331.80  4994.8  331.93  5014.8  333.80
  5034.8  333.87  5044.8  334.64  5054.8  336.31  5074.8  337.44  5094.8  336.79
  5104.8  337.90  5134.8  338.68  5154.8  338.63  5164.8  339.62  5184.8  339.35
  5274.8  340.92  5297.9  340.90  5314.8  342.16  5344.9  341.34  5384.9  341.72
  5394.9  342.25  5414.9  342.12  5424.9  342.96  5454.9  342.96  5530.8  345.49
#Mann=3,-1,0
  4894.6    0.05       0  4982.8    0.05       0  4986.8    0.05       0
Bank Sta=4982.8,4986.8
Exp/Cntr=0.3,0.1

Type RM Length L Ch R = 1,3611,243,243,243
BEGIN DESCRIPTION:
Cedar Branch T2 13.0
END DESCRIPTION:
XS GIS Cut Line= 3
      2711951.22      6792251.86      2711876.00      6792411.00
      2711592.41      6792696.03
#Sta/Elev= 30
  4828.5  349.15  4831.0  348.44  4871.0  347.07  4893.8  344.76  4899.3  343.14
  4916.0  341.00  4927.6  337.61  4938.2  336.98  4944.9  335.57  4950.4  333.98
  4958.3  330.00  4958.5  329.50  4962.3  330.00  4973.1  331.97  5008.0  333.57
  5011.6  335.23  5054.0  335.22  5075.2  334.18  5110.6  337.45  5145.9  337.38
  5160.1  338.83  5181.3  339.09  5188.4  340.12  5252.0  341.50  5273.2  341.26
  5280.3  341.50  5287.3  343.00  5308.6  344.20  5315.6  343.75  5406.6  347.12
#Mann=3,-1,0
  4828.5    0.05       0  4958.3    0.05       0  4962.3    0.05       0
Bank Sta=4958.3,4962.3
Exp/Cntr=0.3,0.1

Type RM Length L Ch R = 1,3368,230,230,230
BEGIN DESCRIPTION:
Cedar Branch T2 12.0
END DESCRIPTION:
XS GIS Cut Line= 3
      2711926.00      6792261.00      2711776.00      6792261.00
      2711626.00      6792261.00
#Sta/Elev= 30
  4842.2  346.51  4844.7  346.51  4872.2  341.44  4902.2  337.75  4922.2  337.07
  4932.2  336.17  4942.2  336.07  4952.2  333.74  4962.2  333.50  4972.2  332.37
  4982.2  332.17  4989.7  328.96  4994.7  328.96  5000.2  328.10  5000.5  327.60
  5004.0  327.60  5004.2  328.10  5012.2  329.83  5022.2  332.38  5032.2  333.33
  5052.2  334.45  5062.2  333.14  5072.2  333.99  5082.2  335.95  5102.2  337.35
  5112.2  337.47  5122.2  338.96  5132.2  339.65  5139.7  340.74  5142.2  340.74
#Mann=3,-1,0
  4842.2    0.05       0  5000.2    0.03       0  5004.2    0.05       0
Bank Sta=5000.2,5004.2
Exp/Cntr=0.3,0.1

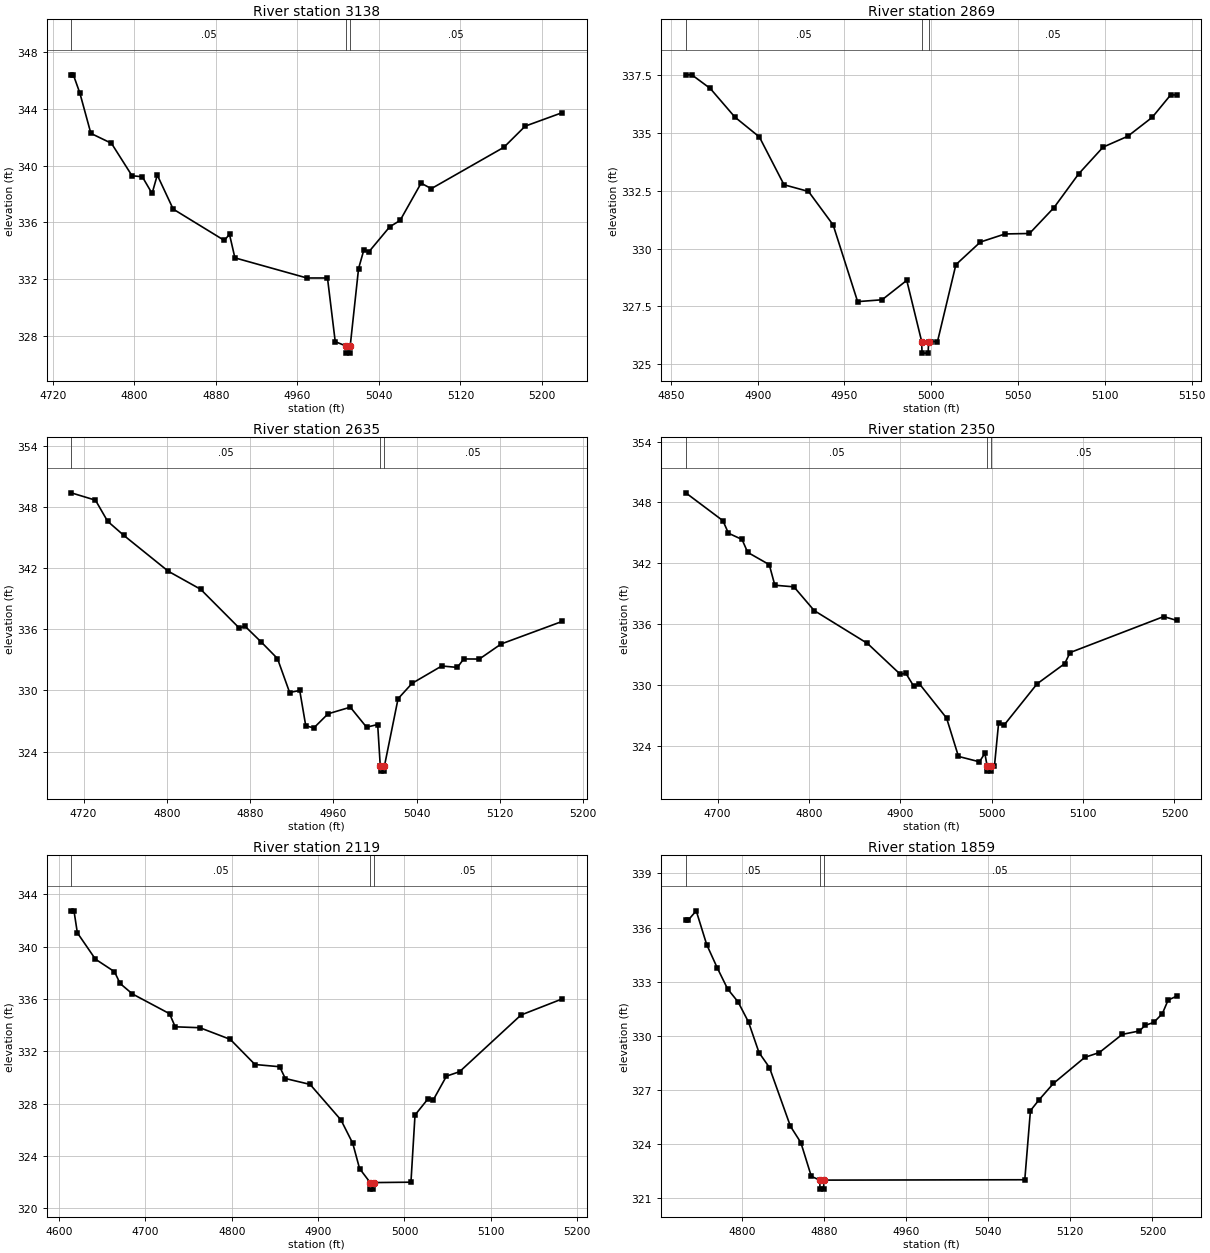
Type RM Length L Ch R = 1,3138,269,269,269
BEGIN DESCRIPTION:
Cedar Branch T2 11.0
END DESCRIPTION:
XS GIS Cut Line= 3
      2711935.11      6792024.19      2711676.00      6792061.00
      2711459.94      6792103.98
#Sta/Elev= 30
  4737.9  346.41  4740.0  346.41  4746.4  345.12  4757.2  342.28  4777.4  341.58
  4797.6  339.29  4807.7  339.22  4817.3  338.04  4822.4  339.34  4838.0  336.94
  4888.2  334.73  4893.3  335.16  4898.6  333.50  4969.3  332.08  4989.5  332.08
  4997.1  327.59  5007.8  327.28  5008.1  326.78  5011.6  326.78  5011.8  327.28
  5020.0  332.74  5025.2  334.06  5030.3  333.94  5050.6  335.69  5060.8  336.14
  5081.4  338.77  5091.4  338.38  5162.7  341.30  5183.6  342.79  5219.9  343.74
#Mann=3,-1,0
  4737.9    0.05       0  5007.8    0.03       0  5011.8    0.05       0
Bank Sta=5007.8,5011.8
Exp/Cntr=0.3,0.1

Type RM Length L Ch R = 1,2869,234,234,234
BEGIN DESCRIPTION:
Cedar Branch T2 10.0
END DESCRIPTION:
XS GIS Cut Line= 3
      2711726.00      6791711.00      2711626.00      6791811.00
      2711526.04      6791910.96
#Sta/Elev= 28
  4858.6  337.52  4862.1  337.52  4872.7  336.93  4886.9  335.69  4901.0  334.83
  4915.2  332.76  4929.3  332.47  4943.5  331.02  4957.6  327.70  4971.7  327.78
  4985.9  328.62  4994.5  325.97  4994.7  325.47  4998.2  325.47  4998.5  325.97
  5000.0  325.97  5003.6  325.97  5014.2  329.30  5028.3  330.28  5042.5  330.63
  5056.6  330.65  5070.7  331.77  5084.9  333.23  5099.0  334.39  5113.2  334.86
  5127.3  335.68  5137.9  336.65  5141.4  336.65
#Mann=3,-1,0
  4858.6    0.05       0  4994.5    0.03       0  4998.5    0.05       0
Bank Sta=4994.5,4998.5
Exp/Cntr=0.3,0.1

Type RM Length L Ch R = 1,2635,285,285,285
BEGIN DESCRIPTION:
Cedar Branch T2 9.0
END DESCRIPTION:
XS GIS Cut Line= 3
      2711775.98      6791461.01      2711526.00      6791611.00
      2711376.00      6791711.00
#Sta/Elev= 30
  4708.1  349.38  4731.4  348.66  4743.1  346.59  4758.6  345.21  4801.4  341.69
  4832.5  339.92  4869.4  336.14  4875.2  336.29  4890.8  334.74  4906.3  333.13
  4918.0  329.80  4927.7  330.00  4933.5  326.53  4941.3  326.33  4954.9  327.71
  4976.3  328.36  4991.9  326.40  5002.6  326.66  5005.1  322.59  5005.4  322.09
  5008.9  322.09  5009.1  322.59  5022.2  329.19  5035.7  330.70  5064.2  332.40
  5079.2  332.26  5085.3  333.09  5100.3  333.08  5121.3  334.56  5179.9  336.77
#Mann=3,-1,0
  4708.1    0.05       0  5005.1    0.03       0  5009.1    0.05       0
Bank Sta=5005.1,5009.1
Exp/Cntr=0.3,0.1

Type RM Length L Ch R = 1,2350,231,231,231
BEGIN DESCRIPTION:
Cedar Branch T2 8.0
END DESCRIPTION:
XS GIS Cut Line= 3
      2711651.85      6791221.11      2711376.00      6791411.00
      2711264.80      6791580.25
#Sta/Elev= 30
  4665.1  348.94  4705.8  346.19  4711.8  344.96  4726.7  344.34  4732.9  343.07
  4756.5  341.86  4762.6  339.83  4783.5  339.67  4805.7  337.33  4864.0  334.09
  4899.9  331.05  4906.0  331.15  4914.8  329.85  4920.9  330.10  4950.6  326.73
  4963.6  322.95  4986.5  322.42  4992.5  323.25  4995.0  322.00  4995.2  321.50
  4998.7  321.50  4999.0  322.00  5003.0  322.00  5007.5  326.20  5013.5  326.03
  5049.7  330.11  5079.9  332.10  5085.8  333.19  5188.3  336.74  5202.5  336.36
#Mann=3,-1,0
  4665.1    0.05       0  4995.0    0.03       0  4999.0    0.05       0
Bank Sta=4995,4999
Exp/Cntr=0.3,0.1

Type RM Length L Ch R = 1,2119,260,260,260
BEGIN DESCRIPTION:
Cedar Branch T2 7.0
END DESCRIPTION:
XS GIS Cut Line= 3
      2711425.98      6791011.02      2711176.00      6791311.00
      2711080.48      6791461.22
#Sta/Elev= 30
  4614.1  342.73  4617.3  342.73  4621.2  341.05  4642.1  339.04  4664.2  338.08
  4670.7  337.18  4685.0  336.38  4728.0  334.87  4734.5  333.87  4763.1  333.80
  4798.3  332.91  4826.9  330.99  4855.5  330.82  4862.0  329.92  4890.7  329.47
  4926.5  326.75  4940.1  324.97  4948.0  323.04  4960.3  321.97  4960.5  321.47
  4964.0  321.47  4964.3  321.97  5007.5  322.00  5012.2  327.13  5027.4  328.38
  5033.4  328.29  5048.6  330.10  5063.8  330.44  5134.9  334.77  5182.6  336.00
#Mann=3,-1,0
  4614.1    0.05       0  4960.3    0.03       0  4964.3    0.05       0
Bank Sta=4960.3,4964.3
Exp/Cntr=0.3,0.1

Type RM Length L Ch R = 1,1859,259,259,259
BEGIN DESCRIPTION:
Cedar Branch T2 6.0
END DESCRIPTION:
XS GIS Cut Line= 3
      2711076.01      6790860.97      2711026.00      6791111.00
      2710926.00      6791311.01
#Sta/Elev= 30
  4745.1  336.43  4747.7  336.43  4755.3  336.93  4765.5  335.06  4775.7  333.78
  4785.9  332.60  4796.1  331.88  4806.3  330.76  4816.5  329.07  4826.7  328.24
  4847.1  324.99  4857.3  324.08  4867.5  322.21  4875.7  322.00  4876.0  321.50
  4879.5  321.50  4879.7  322.00  5075.6  322.02  5081.1  325.85  5089.5  326.45
  5103.5  327.36  5134.2  328.81  5148.2  329.07  5170.6  330.08  5187.4  330.27
  5192.9  330.58  5201.3  330.74  5209.7  331.23  5215.3  331.98  5223.7  332.20
#Mann=3,-1,0
  4745.1    0.05       0  4875.7    0.05       0  4879.7    0.05       0
Bank Sta=4875.7,4879.7
Exp/Cntr=0.3,0.1

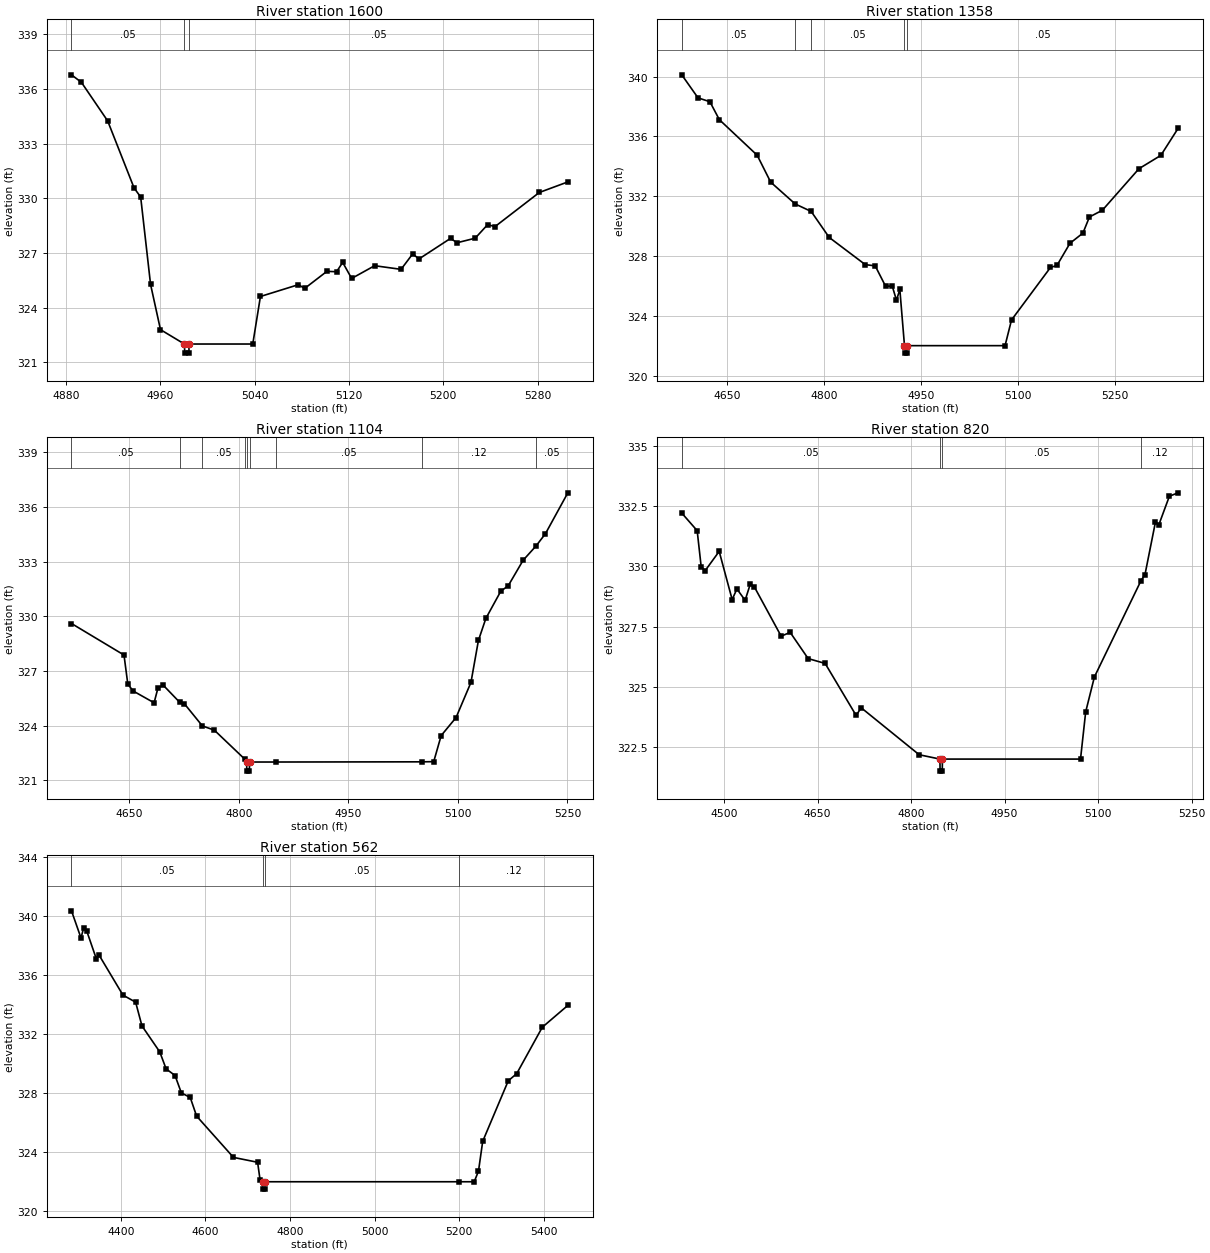
Type RM Length L Ch R = 1,1600,242,242,242
BEGIN DESCRIPTION:
Cedar Branch T2 5.0
END DESCRIPTION:
XS GIS Cut Line= 3
      2710926.00      6790811.01      2710876.00      6790911.00
      2710782.72      6791205.90
#Sta/Elev= 30
  4884.6  336.78  4893.0  336.37  4915.3  334.25  4937.7  330.57  4943.3  330.07
  4951.7  325.27  4960.1  322.79  4980.4  322.00  4980.7  321.50  4984.2  321.50
  4984.4  322.00  5038.4  322.00  5044.9  324.61  5077.2  325.26  5082.4  325.05
  5101.3  325.99  5109.5  325.97  5114.7  326.48  5122.3  325.60  5141.8  326.30
  5164.2  326.10  5174.1  326.95  5179.4  326.67  5206.2  327.80  5211.7  327.56
  5227.1  327.81  5237.6  328.55  5244.0  328.45  5281.5  330.32  5305.7  330.90
#Mann=3,-1,0
  4884.6    0.05       0  4980.4    0.05       0  4984.4    0.05       0
Bank Sta=4980.4,4984.4
Exp/Cntr=0.3,0.1

Type RM Length L Ch R = 1,1358,254,254,254
BEGIN DESCRIPTION:
Cedar Branch T2 4.0
END DESCRIPTION:
XS GIS Cut Line= 3
      2710797.51      6790559.40      2710676.00      6790961.00
      2710645.88      6791307.62
#Sta/Elev= 30
  4580.4  340.12  4605.5  338.58  4623.9  338.32  4638.5  337.12  4697.0  334.74
  4717.9  332.94  4755.8  331.48  4780.5  330.98  4808.4  329.24  4864.2  327.42
  4879.5  327.34  4895.5  325.98  4905.9  325.98  4912.4  325.04  4917.6  325.76
  4924.8  322.00  4925.1  321.50  4928.6  321.50  4928.8  322.00  5080.3  322.00
  5090.3  323.72  5150.5  327.23  5160.6  327.37  5180.7  328.85  5200.7  329.53
  5210.8  330.61  5230.8  331.06  5287.4  333.84  5321.2  334.73  5347.9  336.54
#Mann=5,-1,0
  4580.4    0.05       0  4755.8   0.075       0  4780.5    0.05       0
  4924.8    0.05       0  4928.8    0.05       0
Bank Sta=4924.8,4928.8
Exp/Cntr=0.3,0.1

Type RM Length L Ch R = 1,1104,284,284,284
BEGIN DESCRIPTION:
Cedar Branch T2 3.0
END DESCRIPTION:
XS GIS Cut Line= 3
      2710579.25      6790549.23      2710476.00      6790961.00
      2710425.99      6791211.03
#Sta/Elev= 30
  4571.0  329.60  4642.9  327.87  4648.1  326.28  4655.3  325.90  4684.1  325.25
  4689.3  326.05  4696.5  326.22  4719.3  325.27  4725.3  325.21  4750.2  323.98
  4766.5  323.75  4807.9  322.17  4810.8  322.00  4811.0  321.50  4814.5  321.50
  4814.8  322.00  4850.6  322.00  5050.8  322.01  5066.9  322.02  5077.1  323.45
  5097.5  324.44  5117.9  326.37  5128.1  328.67  5138.3  329.88  5158.7  331.37
  5168.9  331.67  5189.3  333.07  5207.1  333.86  5219.9  334.53  5250.5  336.77
#Mann=9,-1,0
  4571.0    0.05       0  4719.3   0.075       0  4750.2    0.05       0
  4807.9   0.075       0  4810.8    0.05       0  4814.8   0.075       0
  4850.6    0.05       0  5050.8    0.12       0  5207.1    0.05       0
Bank Sta=4810.8,4814.8
Exp/Cntr=0.3,0.1

Type RM Length L Ch R = 1,820,258,258,258
BEGIN DESCRIPTION:
Cedar Branch T2 2.0
END DESCRIPTION:
XS GIS Cut Line= 3
      2710580.22      6790411.53      2710226.00      6790861.00
      2710125.99      6791061.02
#Sta/Elev= 30
  4432.3  332.21  4457.0  331.48  4463.4  329.99  4469.8  329.82  4492.3  330.62
  4513.1  328.62  4520.7  329.06  4533.9  328.59  4542.0  329.25  4548.4  329.16
  4591.7  327.10  4606.1  327.26  4635.0  326.17  4662.2  325.97  4711.9  323.81
  4720.0  324.13  4813.0  322.18  4846.3  322.00  4846.5  321.50  4850.0  321.50
  4850.3  322.00  5071.7  322.00  5080.0  323.96  5094.0  325.41  5168.6  329.40
  5175.1  329.66  5191.8  331.83  5197.4  331.73  5214.2  332.91  5228.2  333.05
#Mann=4,-1,0
  4432.3    0.05       0  4846.3    0.05       0  4850.3    0.05       0
  5168.6    0.12       0
Bank Sta=4846.3,4850.3
Exp/Cntr=0.3,0.1

Type RM Length L Ch R = 1,562,0,0,0
BEGIN DESCRIPTION:
Cedar Branch T2 1.0
END DESCRIPTION:
XS GIS Cut Line= 3
      2710426.00      6790111.01      2710026.00      6790711.00
      2709976.00      6791161.03
#Sta/Elev= 30
  4283.2  340.36  4305.7  338.52  4311.7  339.17  4319.2  339.00  4341.8  337.12
  4347.8  337.39  4404.9  334.65  4434.9  334.17  4449.9  332.56  4492.0  330.80
  4507.0  329.65  4528.1  329.20  4543.1  328.02  4564.1  327.71  4579.1  326.45
  4666.3  323.65  4723.4  323.32  4729.4  322.09  4736.4  322.00  4736.6  321.50
  4740.1  321.50  4740.4  322.00  5200.7  322.00  5235.7  322.00  5245.8  322.72
  5255.8  324.74  5316.2  328.84  5336.3  329.33  5396.7  332.47  5457.1  333.95
#Mann=4,-1,0
  4283.2    0.05       0  4736.4    0.03       0  4740.4    0.05       0
  5200.7    0.12       0
Bank Sta=4736.4,4740.4
Exp/Cntr=0.3,0.1

Chan Stop Cuts=-1