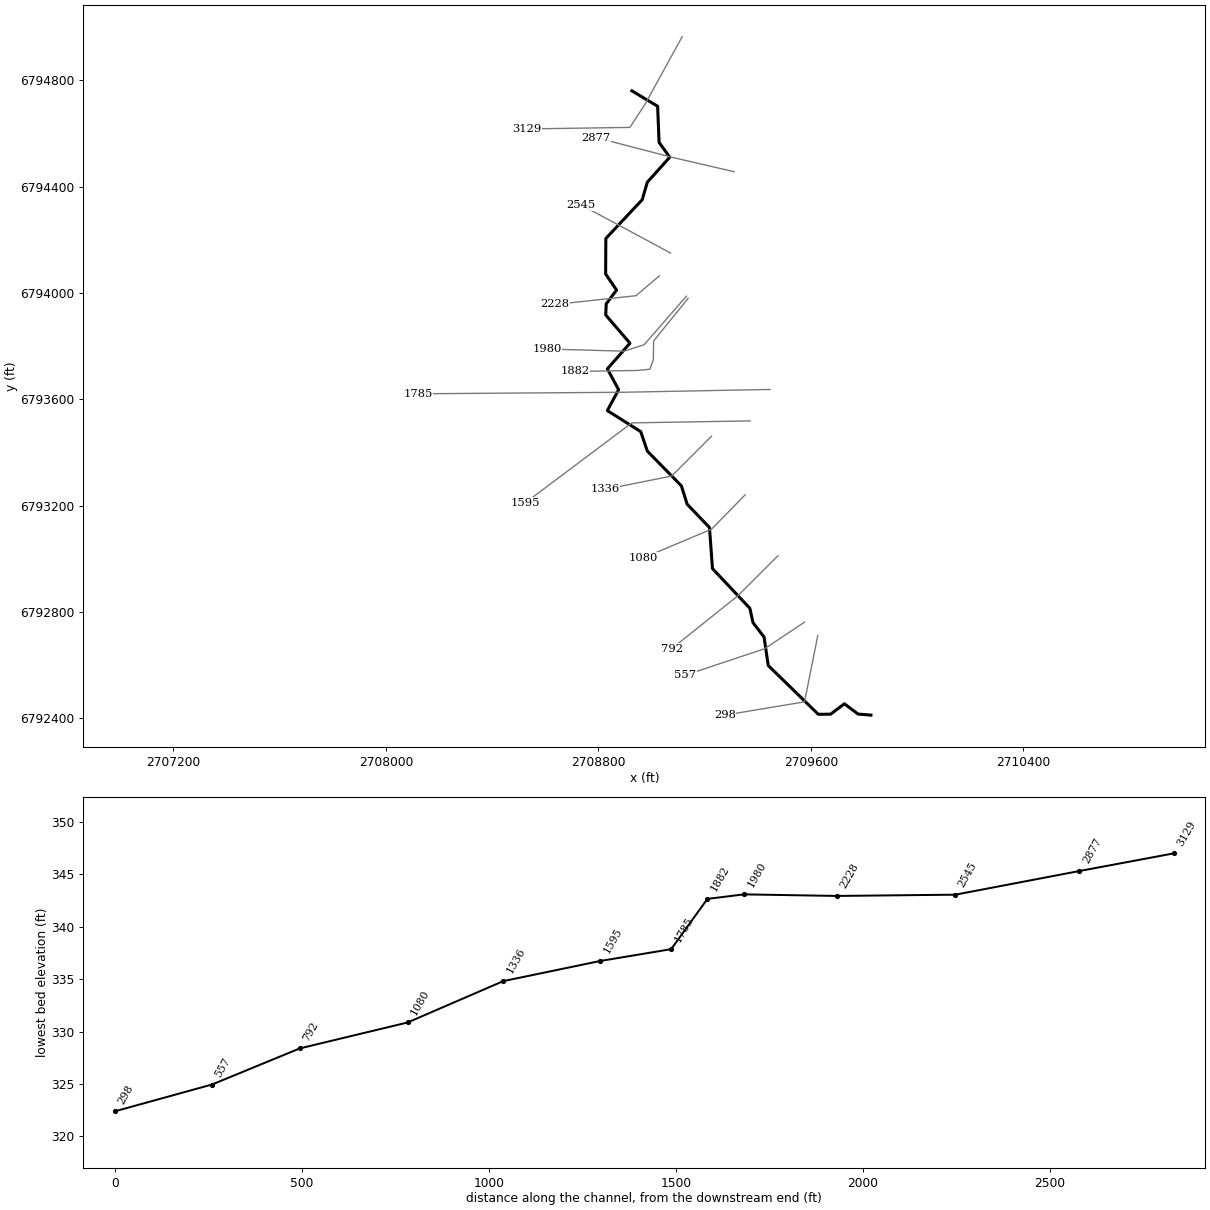
--- Cedar Branch T3.prj (project) ---

Proj Title=Cedar Branch T3 Base Level Engineering
Current Plan=p01
Default Exp/Contr=0.3,0.1
English Units
Geom File=g01
Flow File=f01
Plan File=p01
BEGIN DESCRIPTION:
Cedar Branch T3
END DESCRIPTION:

--- Cedar Branch T3.p01 (plan) ---

Plan Title=Multiple Run
Short Identifier=Multiple
Geom File=g01
Flow File=f01
Subcritical Flow
K Sum by GR= 0
Std Step Tol= 0.01
Critical Tol= 0.01
Num of Std Step Trials= 20
Max Error Tol= 0.3
Flow Tol Ratio= 0.001
Split Flow NTrial= 30
Split Flow Tol= 0.02
Split Flow Ratio= 0.02
Log Output Level= 0
Friction Slope Method= 1
Unsteady Friction Slope Method= 2
Unsteady Bridges Friction Slope Method= 1
Parabolic Critical Depth
Global Vel Dist=  1 , 1 , 1
Global Log Level= 0
CheckData=True
Encroach Param= -1, 0, 0, 0
BEGIN DESCRIPTION:
Multiple Run
END DESCRIPTION:

--- Cedar Branch T3.f01 (steady flow) ---

Flow Title=Multiple
Number of Profiles=7
Profile Names=10-year,25-year,50-year,1pct_min,100-year,1pct_plu,500-year
River Rch & RM= Cedar Branch T3,Reach-1,3129
     188     230     261     147     294     587     372
Boundary for River Rch & Prof#=Cedar Branch T3,Reach-1,1
Up Type=0
Dn Type=3
Dn Slope=0.005
Boundary for River Rch & Prof#=Cedar Branch T3,Reach-1,2
Up Type=0
Dn Type=3
Dn Slope=0.005
Boundary for River Rch & Prof#=Cedar Branch T3,Reach-1,3
Up Type=0
Dn Type=3
Dn Slope=0.005
Boundary for River Rch & Prof#=Cedar Branch T3,Reach-1,4
Up Type=0
Dn Type=3
Dn Slope=0.005
Boundary for River Rch & Prof#=Cedar Branch T3,Reach-1,5
Up Type=0
Dn Type=3
Dn Slope=0.005
Boundary for River Rch & Prof#=Cedar Branch T3,Reach-1,6
Up Type=0
Dn Type=3
Dn Slope=0.005
Boundary for River Rch & Prof#=Cedar Branch T3,Reach-1,7
Up Type=0
Dn Type=3
Dn Slope=0.005

--- Cedar Branch T3.g01 (geometry) ---

Geom Title=Existing Conditions

River Reach=Cedar Branch T3,Reach-1
Reach XY= 30
      2708926.00      6794761.00      2709023.04      6794702.86
      2709028.48      6794566.87      2709068.67      6794510.90
      2708984.20      6794417.05      2708965.22      6794351.32
      2708828.05      6794205.14      2708827.37      6794071.44
      2708868.41      6794010.99      2708829.58      6793959.35
      2708827.67      6793917.05      2708918.89      6793811.00
      2708833.85      6793714.41      2708876.21      6793636.00
      2708833.72      6793557.34      2708959.50      6793478.05
      2708984.17      6793404.97      2709112.37      6793274.21
      2709134.18      6793204.96      2709218.17      6793117.18
      2709229.54      6792962.47      2709370.17      6792813.30
      2709382.14      6792758.83      2709423.67      6792705.03
      2709439.40      6792597.70      2709627.65      6792414.16
      2709674.35      6792414.55      2709726.03      6792453.65
      2709777.36      6792415.00      2709826.00      6792411.00

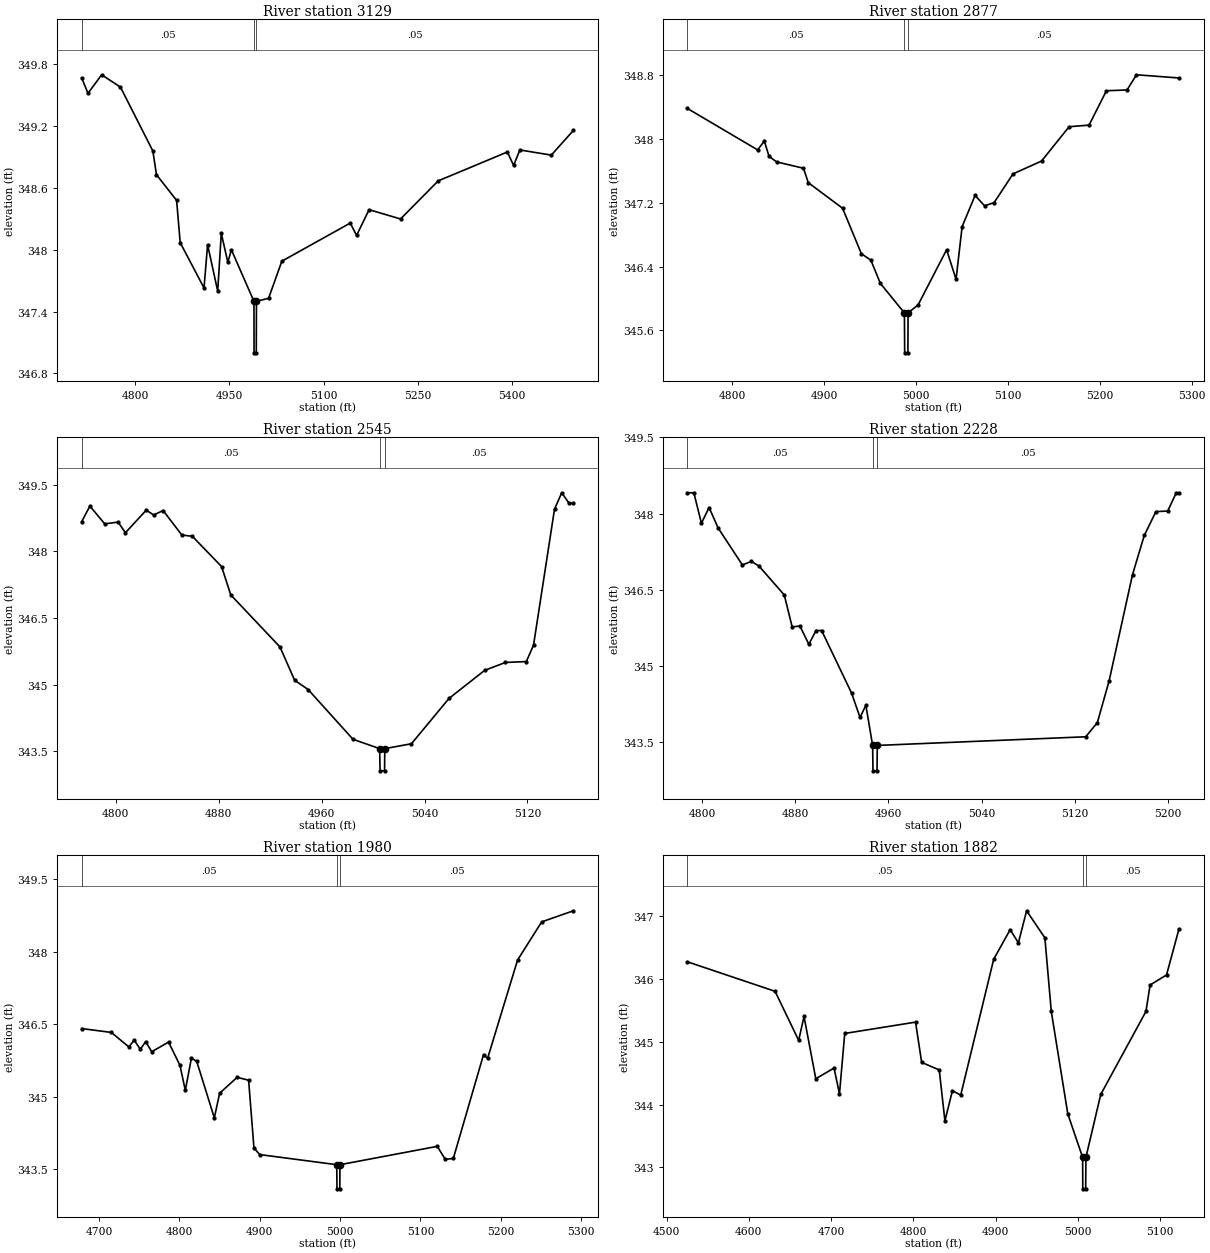
Type RM Length L Ch R = 1,3129,252,252,252
BEGIN DESCRIPTION:
Cedar Branch T3 10.0
END DESCRIPTION:
XS GIS Cut Line= 4
      2709115.62      6794965.11      2708976.00      6794711.00
      2708918.84      6794623.29      2708530.81      6794617.50
#Sta/Elev= 30
  4714.8  349.67  4724.8  349.52  4746.6  349.70  4776.5  349.58  4828.1  348.96
  4833.8  348.73  4865.9  348.48  4871.6  348.07  4909.5  347.63  4915.2  348.05
  4931.3  347.60  4937.0  348.16  4947.4  347.88  4953.1  348.00  4989.0  347.50
  4989.2  347.00  4992.7  347.00  4993.0  347.50  5012.3  347.53  5033.4  347.89
  5142.3  348.26  5152.3  348.14  5172.3  348.39  5222.3  348.30  5282.3  348.67
  5392.3  348.95  5402.3  348.82  5412.3  348.97  5462.3  348.92  5497.5  349.16
#Mann=3,-1,0
  4714.8    0.05       0  4989.0    0.04       0  4993.0    0.05       0
Bank Sta=4989,4993
Exp/Cntr=0.3,0.1

Type RM Length L Ch R = 1,2877,332,332,332
BEGIN DESCRIPTION:
Cedar Branch T3 9.0
END DESCRIPTION:
XS GIS Cut Line= 3
      2709310.64      6794456.58      2709076.00      6794511.00
      2708791.33      6794585.01
#Sta/Elev= 30
  4751.2  348.38  4827.8  347.86  4835.1  347.97  4840.2  347.78  4848.4  347.71
  4877.7  347.63  4882.9  347.45  4920.2  347.13  4940.7  346.56  4951.0  346.48
  4961.3  346.19  4987.5  345.82  4987.8  345.32  4991.3  345.32  4991.5  345.82
  5002.4  345.92  5033.4  346.61  5043.7  346.24  5050.3  346.90  5064.4  347.29
  5074.7  347.16  5085.1  347.20  5105.7  347.56  5136.7  347.72  5166.7  348.15
  5188.4  348.17  5207.3  348.60  5229.7  348.61  5240.0  348.80  5286.2  348.76
#Mann=3,-1,0
  4751.2    0.05       0  4987.5    0.04       0  4991.5    0.05       0
Bank Sta=4987.5,4991.5
Exp/Cntr=0.3,0.1

Type RM Length L Ch R = 1,2545,317,317,317
BEGIN DESCRIPTION:
Mapping XS 1a0e460a
END DESCRIPTION:
XS GIS Cut Line= 2
      2709071.72      6794150.35      2708735.14      6794331.43
#Sta/Elev= 30
  4773.5  348.67  4779.9  349.02  4791.4  348.62  4801.8  348.66  4807.5  348.42
  4823.7  348.93  4829.4  348.82  4836.8  348.92  4851.3  348.37  4859.5  348.34
  4882.2  347.66  4889.4  347.02  4927.6  345.85  4939.0  345.10  4949.5  344.89
  4984.4  343.77  5005.1  343.56  5005.4  343.06  5008.9  343.06  5009.1  343.56
  5029.8  343.67  5059.0  344.69  5086.6  345.32  5102.8  345.50  5119.1  345.52
  5124.7  345.89  5141.0  348.95  5146.6  349.32  5152.4  349.08  5155.7  349.08
#Mann=3,-1,0
  4773.5    0.05       0  5005.1    0.04       0  5009.1    0.05       0
Bank Sta=5005.1,5009.1
Exp/Cntr=0.3,0.1

Type RM Length L Ch R = 1,2228,248,248,248
BEGIN DESCRIPTION:
Mapping XS 0483dc78
END DESCRIPTION:
XS GIS Cut Line= 3
      2709029.60      6794064.54      2708941.54      6793989.78
      2708636.32      6793956.84
#Sta/Elev= 30
  4787.1  348.41  4792.8  348.41  4799.3  347.81  4805.9  348.12  4813.6  347.72
  4834.5  346.99  4842.2  347.06  4848.7  346.97  4870.5  346.40  4877.3  345.77
  4883.9  345.79  4891.6  345.43  4897.8  345.70  4902.6  345.70  4928.3  344.47
  4935.6  343.99  4940.6  344.23  4946.4  343.44  4946.7  342.94  4950.2  342.94
  4950.4  343.44  5129.5  343.61  5139.5  343.89  5149.6  344.71  5169.7  346.80
  5179.8  347.57  5189.8  348.04  5199.9  348.05  5207.3  348.41  5209.6  348.41
#Mann=3,-1,0
  4787.1    0.05       0  4946.4    0.03       0  4950.4    0.05       0
Bank Sta=4946.4,4950.4
Exp/Cntr=0.3,0.1

Type RM Length L Ch R = 1,1980,98,98,98
BEGIN DESCRIPTION:
Cedar Branch T3 8.0
END DESCRIPTION:
XS GIS Cut Line= 4
      2709131.56      6793988.01      2708972.23      6793805.18
      2708896.82      6793781.00      2708606.53      6793789.02
#Sta/Elev= 30
  4678.3  346.41  4715.2  346.33  4737.0  346.03  4743.7  346.17  4751.3  345.98
  4757.9  346.14  4765.5  345.93  4786.4  346.13  4800.6  345.65  4807.3  345.13
  4814.9  345.80  4821.5  345.73  4843.4  344.56  4850.0  345.07  4871.8  345.40
  4886.1  345.34  4892.7  343.94  4899.8  343.80  4995.8  343.59  4996.1  343.09
  4999.6  343.09  4999.8  343.59  5120.9  343.97  5130.9  343.70  5140.9  343.72
  5178.5  345.87  5183.5  345.79  5220.9  347.83  5250.9  348.62  5290.4  348.85
#Mann=3,-1,0
  4678.3    0.05       0  4995.8    0.04       0  4999.8    0.05       0
Bank Sta=4995.8,4999.8
Exp/Cntr=0.3,0.1

Type RM Length L Ch R = 1,1882,97,97,97
BEGIN DESCRIPTION:
Mapping XS 66132245
END DESCRIPTION:
XS GIS Cut Line= 6
      2709137.72      6793979.59      2709008.21      6793819.93
      2709006.64      6793747.95      2708993.46      6793713.01
      2708946.53      6793708.31      2708710.93      6793704.66
#Sta/Elev= 30
  4525.1  346.27  4631.9  345.80  4660.6  345.02  4667.1  345.40  4681.4  344.41
  4703.6  344.58  4710.2  344.17  4716.6  345.13  4802.7  345.31  4810.1  344.67
  4831.5  344.55  4838.4  343.74  4847.5  344.22  4857.6  344.15  4897.7  346.31
  4917.7  346.78  4927.7  346.57  4937.7  347.08  4959.9  346.65  4967.7  345.48
  4987.8  343.85  5005.8  343.16  5006.0  342.66  5009.5  342.66  5009.8  343.16
  5027.8  344.16  5082.8  345.48  5087.8  345.90  5107.8  346.06  5122.9  346.79
#Mann=3,-1,0
  4525.1    0.05       0  5005.8    0.04       0  5009.8    0.05       0
Bank Sta=5005.8,5009.8
Exp/Cntr=0.3,0.1

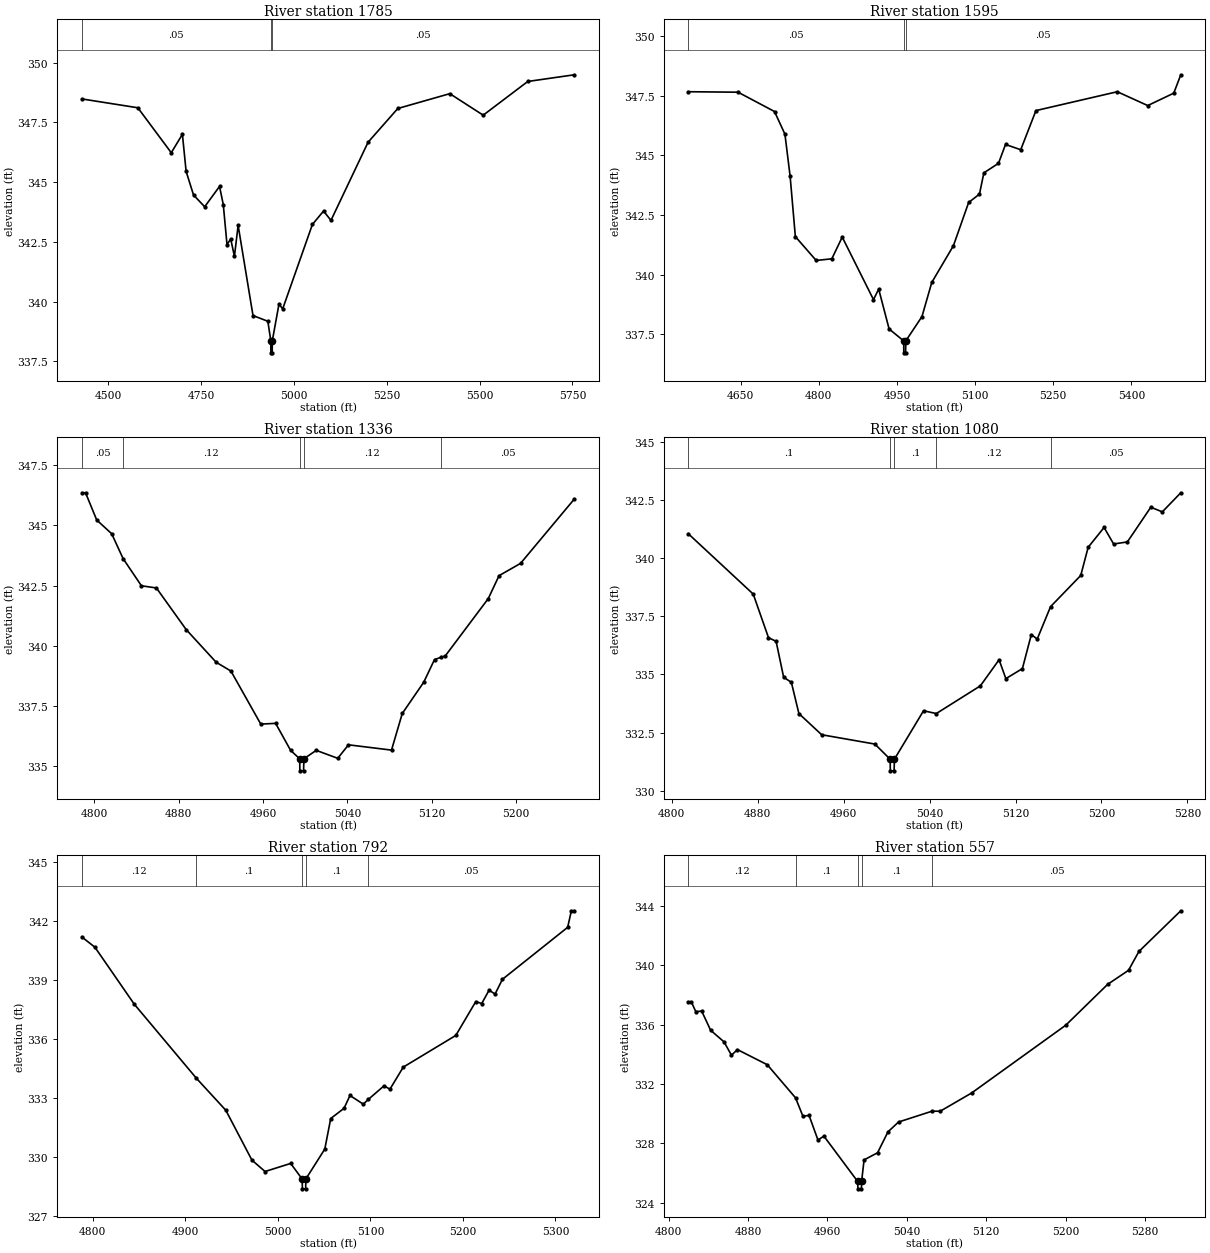
Type RM Length L Ch R = 1,1785,190,190,190
BEGIN DESCRIPTION:
Cedar Branch T3 7.0
END DESCRIPTION:
XS GIS Cut Line= 3
      2709446.78      6793636.94      2708895.55      6793626.38
      2708120.60      6793620.54
#Sta/Elev= 30
  4428.8  348.48  4579.6  348.11  4669.6  346.23  4699.6  347.00  4709.6  345.45
  4729.6  344.46  4759.6  343.97  4799.6  344.82  4809.7  344.06  4819.7  342.39
  4829.7  342.62  4839.7  341.90  4849.7  343.19  4889.7  339.42  4929.7  339.18
  4937.7  338.36  4937.9  337.86  4941.4  337.86  4941.7  338.36  4959.7  339.90
  4969.7  339.70  5049.7  343.23  5079.7  343.79  5099.7  343.40  5199.7  346.67
  5279.7  348.08  5419.7  348.70  5509.7  347.80  5629.7  349.21  5755.1  349.49
#Mann=3,-1,0
  4428.8    0.05       0  4937.7    0.05       0  4941.7    0.05       0
Bank Sta=4937.7,4941.7
Exp/Cntr=0.3,0.1

Type RM Length L Ch R = 1,1595,259,259,259
BEGIN DESCRIPTION:
Cedar Branch T3 6.0
END DESCRIPTION:
XS GIS Cut Line= 3
      2709371.44      6793518.52      2708926.00      6793511.00
      2708526.00      6793211.00
#Sta/Elev= 30
  4549.4  347.67  4644.9  347.65  4714.9  346.84  4734.9  345.89  4744.9  344.12
  4754.9  341.60  4794.9  340.60  4824.9  340.67  4844.9  341.58  4904.9  338.96
  4914.9  339.40  4934.9  337.73  4962.9  337.23  4963.1  336.73  4966.6  336.73
  4966.9  337.23  4998.0  338.25  5016.8  339.68  5058.4  341.22  5087.6  343.03
  5108.4  343.38  5116.8  344.27  5144.9  344.67  5158.4  345.46  5187.6  345.24
  5216.8  346.88  5373.0  347.67  5431.4  347.09  5481.4  347.61  5494.9  348.38
#Mann=3,-1,0
  4549.4    0.05       0  4962.9    0.05       0  4966.9    0.05       0
Bank Sta=4962.9,4966.9
Exp/Cntr=0.3,0.1

Type RM Length L Ch R = 1,1336,256,256,256
BEGIN DESCRIPTION:
Cedar Branch T3 5.0
END DESCRIPTION:
XS GIS Cut Line= 3
      2709225.98      6793460.98      2709076.00      6793311.00
      2708825.96      6793260.99
#Sta/Elev= 30
  4788.1  346.35  4791.6  346.35  4802.2  345.22  4816.4  344.65  4827.2  343.62
  4844.6  342.49  4858.8  342.40  4887.1  340.67  4915.4  339.32  4929.5  338.95
  4957.8  336.75  4971.9  336.78  4986.1  335.66  4994.7  335.31  4994.9  334.81
  4998.4  334.81  4998.7  335.31  5010.4  335.66  5030.8  335.33  5041.0  335.89
  5081.8  335.67  5092.0  337.19  5112.4  338.49  5122.6  339.43  5128.7  339.52
  5132.8  339.58  5173.6  341.96  5183.8  342.91  5204.2  343.42  5255.2  346.09
#Mann=5,-1,0
  4788.1    0.05       0  4827.2    0.12       0  4994.7    0.07       0
  4998.7    0.12       0  5128.7    0.05       0
Bank Sta=4994.7,4998.7
Exp/Cntr=0.3,0.1

Type RM Length L Ch R = 1,1080,288,288,288
BEGIN DESCRIPTION:
Cedar Branch T3 4.0
END DESCRIPTION:
XS GIS Cut Line= 3
      2709352.38      6793240.08      2709226.00      6793111.00
      2708970.18      6793003.08
#Sta/Elev= 30
  4815.5  341.04  4875.9  338.45  4890.1  336.58  4897.2  336.42  4904.2  334.88
  4911.4  334.66  4918.4  333.32  4939.6  332.41  4989.1  332.01  5003.3  331.36
  5003.5  330.86  5007.0  330.86  5007.3  331.36  5034.4  333.44  5046.3  333.32
  5087.3  334.51  5104.7  335.63  5111.0  334.82  5126.4  335.25  5134.7  336.71
  5140.2  336.52  5152.6  337.91  5180.7  339.25  5187.6  340.46  5202.4  341.31
  5211.3  340.60  5224.1  340.69  5245.9  342.18  5256.6  341.98  5273.8  342.80
#Mann=5,-1,0
  4815.5     0.1       0  5003.3    0.07       0  5007.3     0.1       0
  5046.3    0.12       0  5152.6    0.05       0
Bank Sta=5003.3,5007.3
Exp/Cntr=0.3,0.1

Type RM Length L Ch R = 1,792,235,235,235
BEGIN DESCRIPTION:
Cedar Branch T3 3.0
END DESCRIPTION:
XS GIS Cut Line= 3
      2709476.00      6793011.00      2709326.00      6792861.00
      2709075.99      6792660.99
#Sta/Elev= 30
  4788.1  341.18  4802.2  340.66  4844.7  337.77  4912.0  334.00  4943.7  332.38
  4971.9  329.85  4986.1  329.27  5013.8  329.68  5026.2  328.89  5026.5  328.39
  5030.0  328.39  5030.2  328.89  5050.7  330.41  5057.1  331.96  5071.5  332.48
  5077.9  333.13  5092.3  332.69  5097.7  332.93  5114.7  333.62  5121.1  333.45
  5135.5  334.57  5192.3  336.18  5213.9  337.90  5220.3  337.80  5228.3  338.48
  5234.7  338.28  5242.7  339.03  5313.2  341.67  5317.2  342.51  5320.4  342.51
#Mann=5,-1,0
  4788.1    0.12       0  4912.0     0.1       0  5026.2    0.07       0
  5030.2     0.1       0  5097.7    0.05       0
Bank Sta=5026.2,5030.2
Exp/Cntr=0.3,0.1

Type RM Length L Ch R = 1,557,259,259,259
BEGIN DESCRIPTION:
Cedar Branch T3 2.0
END DESCRIPTION:
XS GIS Cut Line= 3
      2709575.98      6792760.98      2709426.00      6792661.00
      2709125.98      6792560.99
#Sta/Elev= 30
  4819.7  337.54  4822.7  337.54  4827.2  336.88  4833.2  336.91  4842.2  335.62
  4855.7  334.84  4863.2  333.94  4869.2  334.32  4899.3  333.30  4927.8  331.07
  4935.3  329.82  4941.4  329.89  4950.4  328.23  4956.4  328.49  4990.4  325.44
  4990.7  324.94  4994.2  324.94  4994.4  325.44  4996.9  326.89  5010.5  327.37
  5021.0  328.78  5031.6  329.44  5065.4  330.17  5073.7  330.17  5105.4  331.40
  5200.2  335.96  5242.4  338.71  5263.5  339.66  5274.0  340.93  5316.2  343.67
#Mann=5,-1,0
  4819.7    0.12       0  4927.8     0.1       0  4990.4    0.07       0
  4994.4     0.1       0  5065.4    0.05       0
Bank Sta=4990.4,4994.4
Exp/Cntr=0.3,0.1

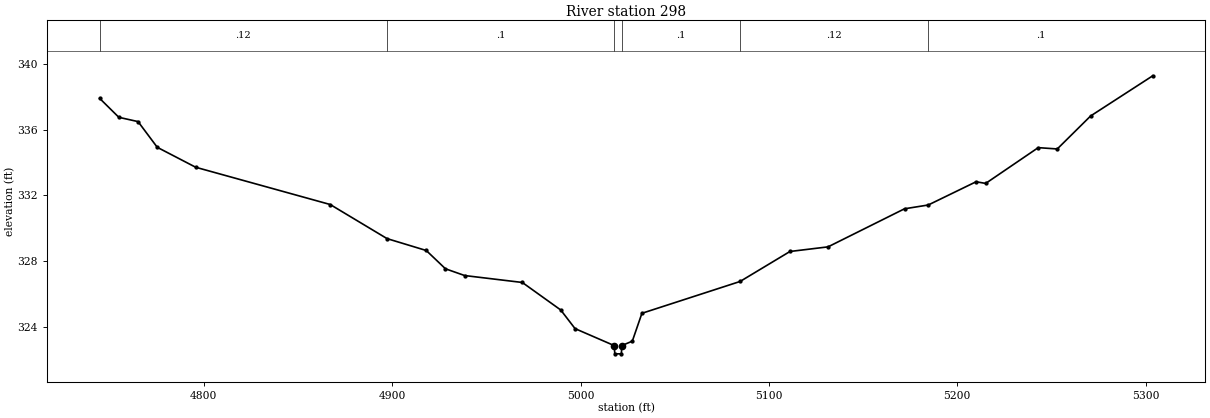
Type RM Length L Ch R = 1,298,0,0,0
BEGIN DESCRIPTION:
Cedar Branch T3 1.0
END DESCRIPTION:
XS GIS Cut Line= 3
      2709626.00      6792711.00      2709576.00      6792461.00
      2709275.99      6792411.00
#Sta/Elev= 30
  4744.7  337.89  4754.9  336.74  4765.1  336.48  4775.3  334.92  4795.7  333.71
  4867.1  331.45  4897.3  329.38  4918.1  328.66  4928.3  327.55  4938.5  327.14
  4969.1  326.72  4989.5  325.05  4997.1  323.92  5017.9  322.89  5018.2  322.39
  5021.7  322.39  5021.9  322.89  5027.5  323.16  5032.6  324.85  5084.7  326.78
  5111.2  328.60  5131.4  328.88  5172.0  331.19  5184.6  331.42  5210.0  332.83
  5215.1  332.73  5243.0  334.90  5253.1  334.82  5270.8  336.82  5303.8  339.26
#Mann=6,-1,0
  4744.7    0.12       0  4897.3     0.1       0  5017.9    0.07       0
  5021.9     0.1       0  5084.7    0.12       0  5184.6     0.1       0
Bank Sta=5017.9,5021.9
Exp/Cntr=0.3,0.1

Chan Stop Cuts=-1