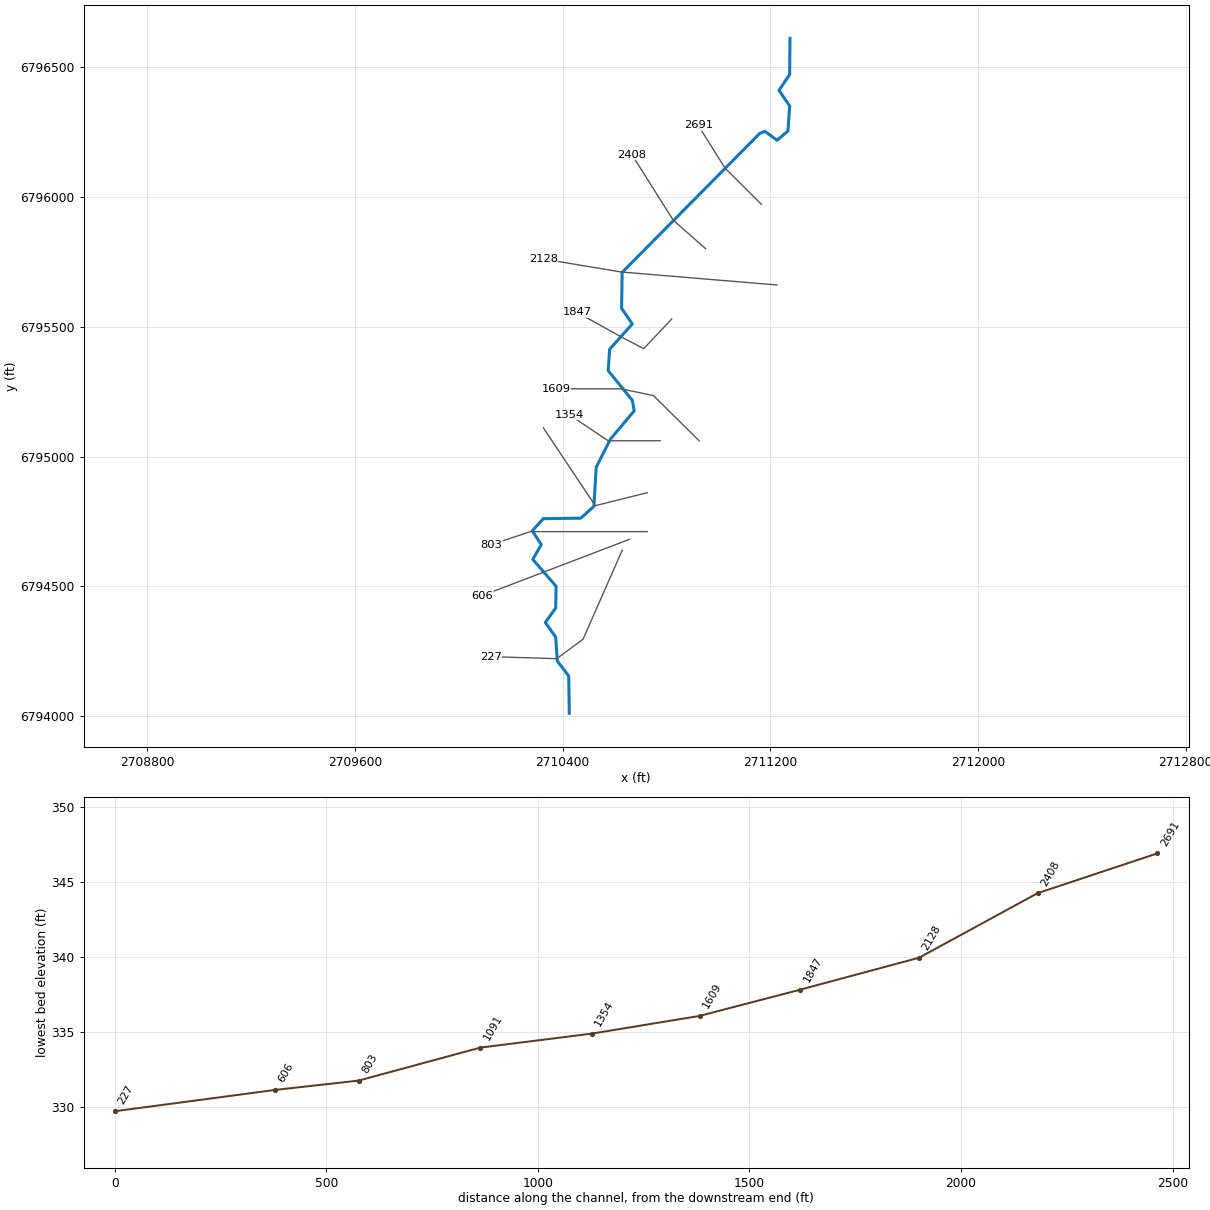
--- Cedar Branch T4.prj (project) ---

Proj Title=Cedar Branch T4 Base Level Engineering
Current Plan=p01
Default Exp/Contr=0.3,0.1
English Units
Geom File=g01
Flow File=f01
Plan File=p01
BEGIN DESCRIPTION:
Cedar Branch T4
END DESCRIPTION:

--- Cedar Branch T4.p01 (plan) ---

Plan Title=Multiple Run
Short Identifier=Multiple
Geom File=g01
Flow File=f01
Subcritical Flow
K Sum by GR= 0
Std Step Tol= 0.01
Critical Tol= 0.01
Num of Std Step Trials= 20
Max Error Tol= 0.3
Flow Tol Ratio= 0.001
Split Flow NTrial= 30
Split Flow Tol= 0.02
Split Flow Ratio= 0.02
Log Output Level= 0
Friction Slope Method= 1
Unsteady Friction Slope Method= 2
Unsteady Bridges Friction Slope Method= 1
Parabolic Critical Depth
Global Vel Dist=  1 , 1 , 1
Global Log Level= 0
CheckData=True
Encroach Param= -1, 0, 0, 0
BEGIN DESCRIPTION:
Multiple Run
END DESCRIPTION:

--- Cedar Branch T4.f01 (steady flow) ---

Flow Title=Multiple
Number of Profiles=7
Profile Names=10-year,25-year,50-year,1pct_min,100-year,1pct_plu,500-year
River Rch & RM= Cedar Branch T4,Reach-1,2691
     263     334     388     225     448     894     596
River Rch & RM= Cedar Branch T4,Reach-1,803
     407     533     632     372     743    1482    1026
Boundary for River Rch & Prof#=Cedar Branch T4,Reach-1,1
Up Type=0
Dn Type=3
Dn Slope=0.005
Boundary for River Rch & Prof#=Cedar Branch T4,Reach-1,2
Up Type=0
Dn Type=3
Dn Slope=0.005
Boundary for River Rch & Prof#=Cedar Branch T4,Reach-1,3
Up Type=0
Dn Type=3
Dn Slope=0.005
Boundary for River Rch & Prof#=Cedar Branch T4,Reach-1,4
Up Type=0
Dn Type=3
Dn Slope=0.005
Boundary for River Rch & Prof#=Cedar Branch T4,Reach-1,5
Up Type=0
Dn Type=3
Dn Slope=0.005
Boundary for River Rch & Prof#=Cedar Branch T4,Reach-1,6
Up Type=0
Dn Type=3
Dn Slope=0.005
Boundary for River Rch & Prof#=Cedar Branch T4,Reach-1,7
Up Type=0
Dn Type=3
Dn Slope=0.005

--- Cedar Branch T4.g01 (geometry) ---

Geom Title=Existing Conditions

River Reach=Cedar Branch T4,Reach-1
Reach XY= 30
      2711276.00      6796611.00      2711274.66      6796471.41
      2711233.56      6796411.00      2711274.74      6796350.50
      2711268.24      6796254.20      2711226.25      6796218.46
      2711179.35      6796252.83      2711159.34      6796244.61
      2710629.53      6795709.53      2710627.38      6795571.44
      2710668.67      6795510.90      2710581.43      6795413.43
      2710575.79      6795331.06      2710668.52      6795217.04
      2710676.10      6795176.36      2710584.16      6795067.05
      2710529.76      6794959.44      2710520.66      6794808.26
      2710470.38      6794762.92      2710326.00      6794761.00
      2710283.50      6794714.33      2710318.11      6794661.00
      2710285.30      6794604.34      2710375.05      6794500.52
      2710373.64      6794416.90      2710333.56      6794361.00
      2710373.45      6794305.11      2710379.85      6794212.60
      2710423.78      6794155.08      2710426.00      6794011.00

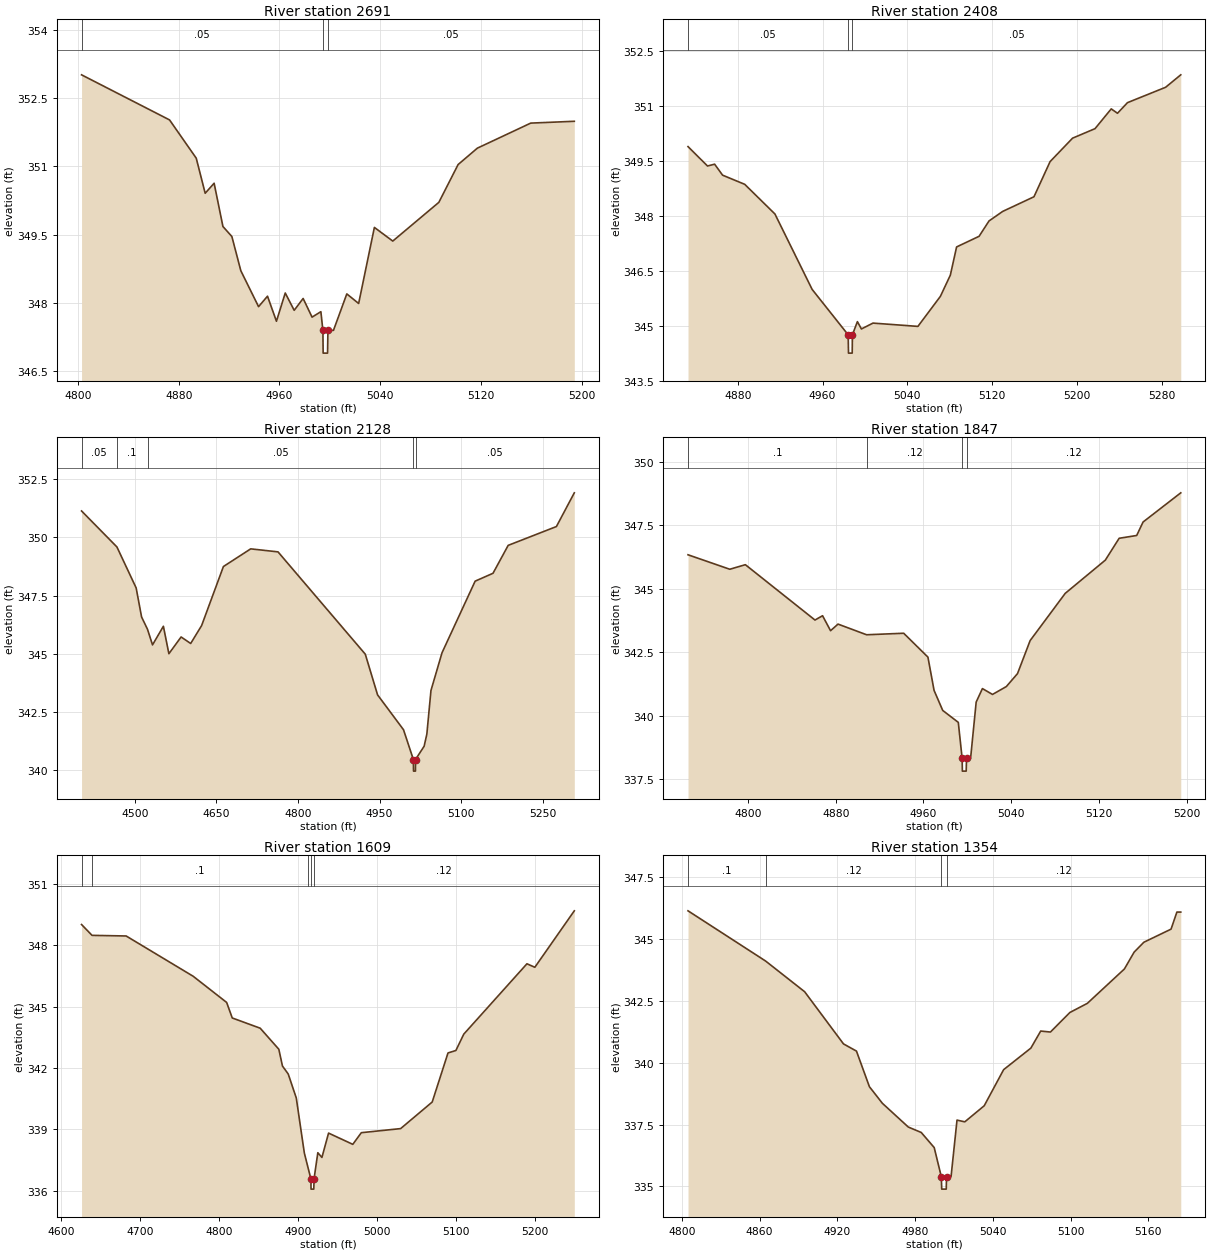
Type RM Length L Ch R = 1,2691,283,283,283
BEGIN DESCRIPTION:
Cedar Branch T4 9.0
END DESCRIPTION:
XS GIS Cut Line= 3
      2711165.70      6795971.84      2711026.00      6796111.00
      2710922.64      6796275.43
#Sta/Elev= 30
  4802.8  353.01  4872.7  352.02  4893.9  351.18  4901.0  350.41  4908.1  350.63
  4915.1  349.68  4922.2  349.46  4929.3  348.71  4943.4  347.92  4950.5  348.15
  4957.6  347.60  4964.6  348.22  4971.7  347.84  4978.8  348.10  4985.9  347.69
  4992.9  347.81  4994.5  347.40  4994.7  346.90  4998.2  346.90  4998.5  347.40
  5002.9  347.40  5013.5  348.20  5022.9  347.99  5035.4  349.66  5050.0  349.36
  5086.6  350.21  5101.9  351.04  5117.2  351.40  5159.6  351.95  5194.2  351.99
#Mann=3,-1,0
  4802.8    0.05       0  4994.5    0.04       0  4998.5    0.05       0
Bank Sta=4994.5,4998.5
Exp/Cntr=0.3,0.1

Type RM Length L Ch R = 1,2408,280,280,280
BEGIN DESCRIPTION:
Cedar Branch T4 8.0
END DESCRIPTION:
XS GIS Cut Line= 3
      2710951.20      6795800.65      2710826.00      6795911.00
      2710667.04      6796163.08
#Sta/Elev= 30
  4833.1  349.89  4851.5  349.36  4858.2  349.41  4865.7  349.11  4886.6  348.86
  4915.1  348.05  4950.2  345.99  4984.2  344.75  4984.5  344.25  4988.0  344.25
  4988.2  344.75  4992.9  345.11  4996.7  344.91  5007.6  345.07  5050.0  344.98
  5071.2  345.80  5080.6  346.38  5086.5  347.15  5107.7  347.44  5117.1  347.86
  5130.0  348.12  5159.5  348.52  5174.7  349.48  5195.9  350.12  5217.1  350.38
  5232.4  350.92  5238.3  350.80  5247.7  351.09  5283.7  351.51  5298.0  351.85
#Mann=3,-1,0
  4833.1    0.05       0  4984.2    0.04       0  4988.2    0.05       0
Bank Sta=4984.2,4988.2
Exp/Cntr=0.3,0.1

Type RM Length L Ch R = 1,2128,281,281,281
BEGIN DESCRIPTION:
Cedar Branch T4 7.0
END DESCRIPTION:
XS GIS Cut Line= 3
      2711226.02      6795661.00      2710626.00      6795711.00
      2710326.03      6795760.99
#Sta/Elev= 30
  4402.0  351.14  4467.1  349.59  4502.4  347.83  4512.4  346.58  4523.3  346.05
  4532.5  345.38  4552.5  346.18  4562.6  345.00  4585.1  345.72  4602.7  345.44
  4622.8  346.21  4662.9  348.75  4713.1  349.51  4763.3  349.38  4923.8  344.98
  4946.4  343.23  4994.1  341.73  5012.2  340.45  5012.5  339.95  5016.0  339.95
  5016.2  340.45  5032.0  341.02  5037.0  341.54  5044.6  343.42  5064.9  345.04
  5125.8  348.12  5158.7  348.46  5186.6  349.66  5275.3  350.47  5308.2  351.92
#Mann=5,-1,0
  4402.0    0.05       0  4467.1     0.1       0  4523.3    0.05       0
  5012.2    0.04       0  5016.2    0.05       0
Bank Sta=5012.2,5016.2
Exp/Cntr=0.3,0.1

Type RM Length L Ch R = 1,1847,238,238,238
BEGIN DESCRIPTION:
Cedar Branch T4 6.0
END DESCRIPTION:
XS GIS Cut Line= 4
      2710820.56      6795530.14      2710712.83      6795415.97
      2710626.00      6795461.00      2710455.90      6795555.55
#Sta/Elev= 30
  4745.3  346.34  4783.4  345.77  4797.6  345.95  4861.1  343.77  4868.0  343.94
  4875.3  343.35  4882.1  343.61  4908.2  343.19  4942.0  343.25  4964.1  342.31
  4969.7  341.00  4977.6  340.21  4991.8  339.74  4995.3  338.32  4995.5  337.82
  4999.0  337.82  4999.3  338.32  5003.0  338.32  5008.1  340.54  5013.8  341.07
  5023.0  340.84  5035.6  341.15  5045.8  341.66  5057.3  342.96  5089.3  344.82
  5125.9  346.13  5138.5  346.99  5154.5  347.10  5160.3  347.63  5194.7  348.78
#Mann=4,-1,0
  4745.3     0.1       0  4908.2    0.12       0  4995.3    0.07       0
  4999.3    0.12       0
Bank Sta=4995.3,4999.3
Exp/Cntr=0.3,0.1

Type RM Length L Ch R = 1,1609,255,255,255
BEGIN DESCRIPTION:
Cedar Branch T4 5.0
END DESCRIPTION:
XS GIS Cut Line= 4
      2710926.00      6795061.00      2710750.07      6795234.98
      2710626.00      6795261.00      2710376.00      6795261.00
#Sta/Elev= 30
  4625.8  349.01  4639.1  348.48  4682.3  348.45  4767.2  346.48  4809.6  345.20
  4816.7  344.44  4852.1  343.94  4875.7  342.91  4880.3  342.09  4887.6  341.70
  4897.8  340.53  4908.0  337.84  4912.3  337.18  4916.3  336.57  4916.5  336.07
  4920.0  336.07  4920.3  336.57  4925.1  337.85  4930.3  337.62  4938.7  338.81
  4969.4  338.26  4980.2  338.83  5030.0  339.03  5070.0  340.33  5090.0  342.73
  5100.0  342.85  5110.0  343.65  5190.0  347.09  5200.0  346.92  5250.0  349.68
#Mann=5,-1,0
  4625.8    0.05       0  4639.1     0.1       0  4912.3    0.12       0
  4916.3    0.07       0  4920.3    0.12       0
Bank Sta=4916.3,4920.3
Exp/Cntr=0.3,0.1

Type RM Length L Ch R = 1,1354,263,263,263
BEGIN DESCRIPTION:
Cedar Branch T4 4.0
END DESCRIPTION:
XS GIS Cut Line= 3
      2710776.04      6795061.00      2710576.00      6795061.00
      2710426.02      6795160.99
#Sta/Elev= 30
  4804.7  346.14  4864.6  344.11  4894.7  342.87  4924.7  340.76  4934.7  340.47
  4944.7  339.03  4954.7  338.36  4974.7  337.40  4984.7  337.18  4994.7  336.57
  5000.2  335.39  5000.5  334.89  5004.0  334.89  5004.2  335.39  5007.7  335.39
  5012.3  337.68  5018.3  337.61  5033.3  338.26  5048.3  339.72  5069.3  340.59
  5076.9  341.28  5084.4  341.24  5099.4  342.03  5112.9  342.40  5141.5  343.79
  5149.0  344.47  5156.5  344.87  5177.5  345.40  5182.0  346.09  5185.0  346.09
#Mann=4,-1,0
  4804.7     0.1       0  4864.6    0.12       0  5000.2    0.07       0
  5004.2    0.12       0
Bank Sta=5000.2,5004.2
Exp/Cntr=0.3,0.1

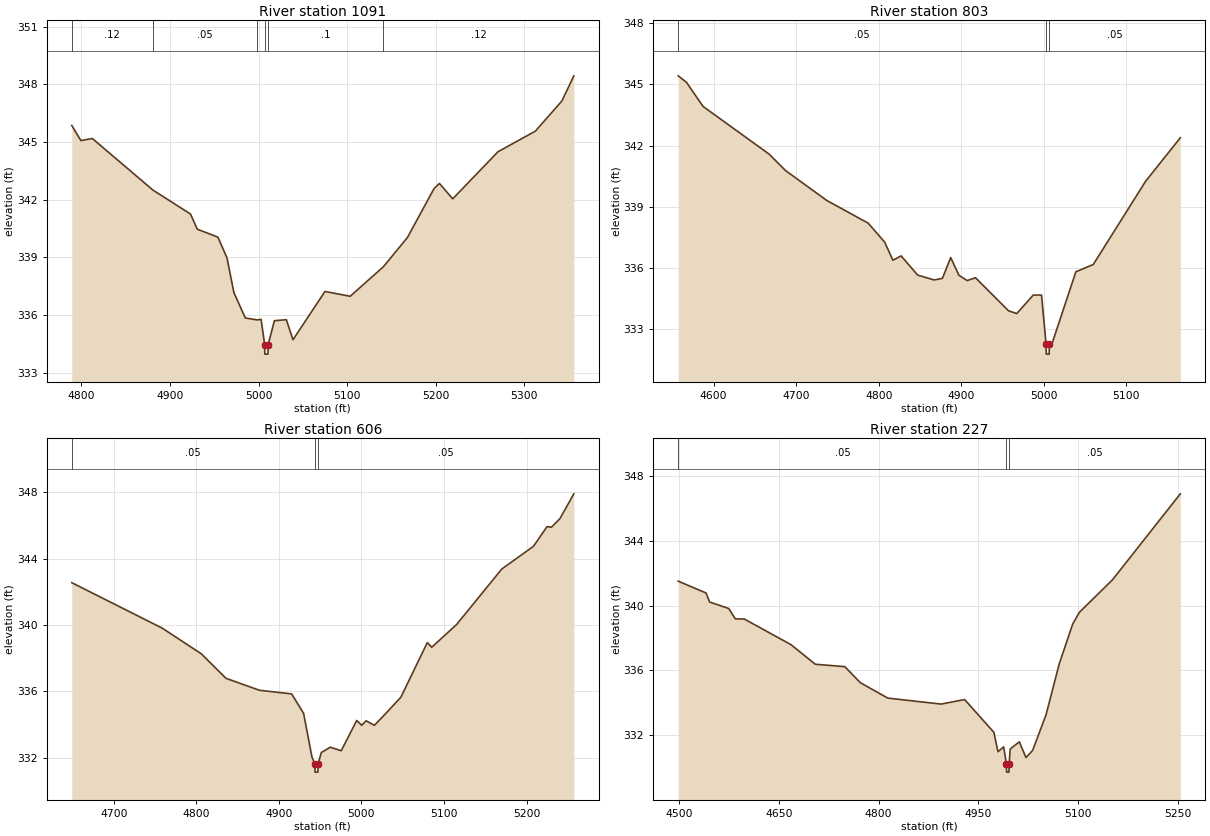
Type RM Length L Ch R = 1,1091,288,288,288
BEGIN DESCRIPTION:
Cedar Branch T4 3.0
END DESCRIPTION:
XS GIS Cut Line= 3
      2710726.01      6794861.00      2710526.00      6794811.00
      2710326.01      6795110.98
#Sta/Elev= 30
  4789.2  345.86  4799.5  345.07  4812.4  345.18  4880.7  342.50  4923.2  341.25
  4930.9  340.46  4954.1  340.05  4964.4  338.97  4972.2  337.16  4985.1  335.84
  4998.8  335.74  5002.9  335.77  5006.9  334.46  5007.1  333.96  5010.6  333.96
  5010.9  334.46  5017.9  335.70  5031.4  335.75  5038.9  334.71  5075.0  337.22
  5103.5  336.97  5141.0  338.51  5168.1  340.03  5198.2  342.58  5204.2  342.84
  5219.2  342.04  5270.3  344.49  5312.4  345.56  5342.4  347.13  5355.9  348.44
#Mann=6,-1,0
  4789.2    0.12       0  4880.7    0.05       0  4998.8     0.1       0
  5006.9    0.07       0  5010.9     0.1       0  5141.0    0.12       0
Bank Sta=5006.9,5010.9
Exp/Cntr=0.3,0.1

Type RM Length L Ch R = 1,803,197,197,197
BEGIN DESCRIPTION:
Cedar Branch T4 2.0
END DESCRIPTION:
XS GIS Cut Line= 3
      2710726.01      6794711.00      2710276.00      6794711.00
      2710126.02      6794661.01
#Sta/Elev= 30
  4557.2  345.42  4567.2  345.10  4587.2  343.92  4667.2  341.58  4687.2  340.77
  4737.2  339.30  4787.2  338.19  4807.2  337.26  4817.2  336.37  4827.2  336.58
  4847.2  335.64  4867.2  335.40  4877.2  335.48  4887.2  336.50  4897.2  335.63
  4907.2  335.37  4917.2  335.51  4957.2  333.89  4967.2  333.75  4987.2  334.66
  4997.2  334.66  5002.7  332.26  5003.0  331.76  5006.5  331.76  5006.7  332.26
  5009.8  332.26  5038.8  335.80  5059.9  336.16  5123.2  340.24  5165.3  342.38
#Mann=3,-1,0
  4557.2    0.05       0  5002.7    0.04       0  5006.7    0.05       0
Bank Sta=5002.7,5006.7
Exp/Cntr=0.3,0.1

Type RM Length L Ch R = 1,606,379,379,379
BEGIN DESCRIPTION:
Mapping XS 515f9c35
END DESCRIPTION:
XS GIS Cut Line= 2
      2710658.34      6794681.61      2710090.30      6794464.54
#Sta/Elev= 30
  4649.2  342.55  4758.8  339.81  4806.0  338.27  4836.0  336.79  4876.5  336.07
  4915.5  335.85  4930.0  334.68  4940.2  332.03  4943.6  331.64  4943.8  331.14
  4947.3  331.14  4947.6  331.64  4951.4  332.32  4962.2  332.64  4975.6  332.43
  4994.3  334.25  5000.4  333.96  5005.7  334.23  5015.7  333.96  5025.1  334.44
  5047.8  335.65  5079.8  338.94  5085.2  338.66  5115.3  340.03  5170.0  343.37
  5208.4  344.74  5224.8  345.92  5230.2  345.89  5240.5  346.41  5257.3  347.90
#Mann=3,-1,0
  4649.2    0.05       0  4943.6    0.05       0  4947.6    0.05       0
Bank Sta=4943.6,4947.6
Exp/Cntr=0.3,0.1

Type RM Length L Ch R = 1,227,0,0,0
BEGIN DESCRIPTION:
Cedar Branch T4 1.0
END DESCRIPTION:
XS GIS Cut Line= 4
      2710629.88      6794639.44      2710478.82      6794296.52
      2710377.33      6794221.55      2710124.35      6794229.54
#Sta/Elev= 30
  4499.1  341.51  4540.8  340.78  4546.3  340.22  4575.0  339.82  4584.8  339.18
  4598.4  339.17  4668.4  337.59  4705.0  336.38  4749.3  336.23  4772.6  335.24
  4813.8  334.29  4893.8  333.92  4929.2  334.20  4973.1  332.18  4979.3  330.98
  4987.8  331.28  4992.0  330.22  4992.2  329.72  4995.7  329.72  4996.0  330.22
  4997.7  331.15  5011.3  331.59  5021.3  330.62  5031.3  331.06  5051.4  333.25
  5071.4  336.42  5091.4  338.85  5101.4  339.58  5151.4  341.60  5253.1  346.90
#Mann=3,-1,0
  4499.1    0.05       0  4992.0    0.04       0  4996.0    0.05       0
Bank Sta=4992,4996
Exp/Cntr=0.3,0.1

Chan Stop Cuts=-1