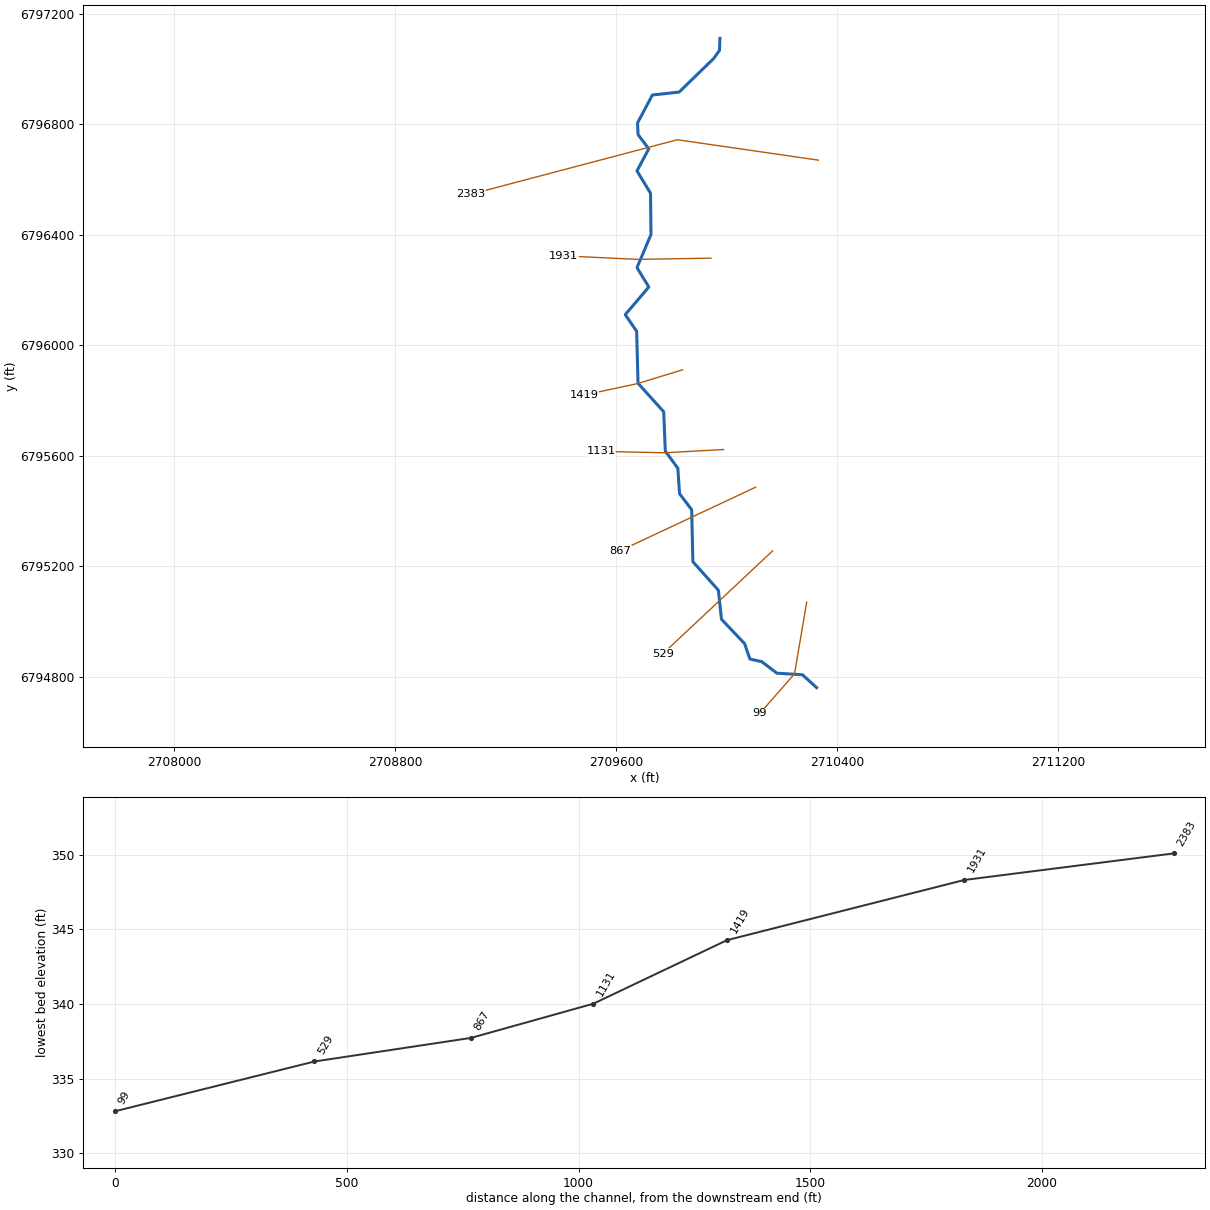
--- Cedar Branch T5.prj (project) ---

Proj Title=Cedar Branch T5 Base Level Engineering
Current Plan=p01
Default Exp/Contr=0.3,0.1
English Units
Geom File=g01
Flow File=f01
Plan File=p01
BEGIN DESCRIPTION:
Cedar Branch T5
END DESCRIPTION:

--- Cedar Branch T5.p01 (plan) ---

Plan Title=Multiple Run
Short Identifier=Multiple
Geom File=g01
Flow File=f01
Subcritical Flow
K Sum by GR= 0
Std Step Tol= 0.01
Critical Tol= 0.01
Num of Std Step Trials= 20
Max Error Tol= 0.3
Flow Tol Ratio= 0.001
Split Flow NTrial= 30
Split Flow Tol= 0.02
Split Flow Ratio= 0.02
Log Output Level= 0
Friction Slope Method= 1
Unsteady Friction Slope Method= 2
Unsteady Bridges Friction Slope Method= 1
Parabolic Critical Depth
Global Vel Dist=  1 , 1 , 1
Global Log Level= 0
CheckData=True
Encroach Param= -1, 0, 0, 0
BEGIN DESCRIPTION:
Multiple Run
END DESCRIPTION:

--- Cedar Branch T5.f01 (steady flow) ---

Flow Title=Multiple
Number of Profiles=7
Profile Names=10-year,25-year,50-year,1pct_min,100-year,1pct_plu,500-year
River Rch & RM= Cedar Branch T5,Reach-1,2383
     163     198     223     126     251     500     315
Boundary for River Rch & Prof#=Cedar Branch T5,Reach-1,1
Up Type=0
Dn Type=3
Dn Slope=0.005
Boundary for River Rch & Prof#=Cedar Branch T5,Reach-1,2
Up Type=0
Dn Type=3
Dn Slope=0.005
Boundary for River Rch & Prof#=Cedar Branch T5,Reach-1,3
Up Type=0
Dn Type=3
Dn Slope=0.005
Boundary for River Rch & Prof#=Cedar Branch T5,Reach-1,4
Up Type=0
Dn Type=3
Dn Slope=0.005
Boundary for River Rch & Prof#=Cedar Branch T5,Reach-1,5
Up Type=0
Dn Type=3
Dn Slope=0.005
Boundary for River Rch & Prof#=Cedar Branch T5,Reach-1,6
Up Type=0
Dn Type=3
Dn Slope=0.005
Boundary for River Rch & Prof#=Cedar Branch T5,Reach-1,7
Up Type=0
Dn Type=3
Dn Slope=0.005

--- Cedar Branch T5.g01 (geometry) ---

Geom Title=Existing Conditions

River Reach=Cedar Branch T5,Reach-1
Reach XY= 30
      2709976.00      6797111.00      2709974.32      6797067.14
      2709952.96      6797037.54      2709828.37      6796916.55
      2709731.44      6796905.75      2709677.83      6796804.90
      2709679.60      6796762.64      2709718.38      6796711.00
      2709675.79      6796631.21      2709724.76      6796550.50
      2709726.45      6796400.81      2709675.83      6796281.13
      2709718.63      6796210.91      2709633.34      6796111.10
      2709674.61      6796050.57      2709679.55      6795862.47
      2709772.44      6795759.53      2709778.27      6795616.94
      2709823.64      6795555.02      2709829.86      6795462.60
      2709873.74      6795405.06      2709878.07      6795216.86
      2709970.46      6795113.42      2709981.54      6795008.58
      2710065.09      6794920.40      2710084.48      6794864.51
      2710127.84      6794854.72      2710181.93      6794813.29
      2710274.60      6794807.61      2710326.00      6794761.00

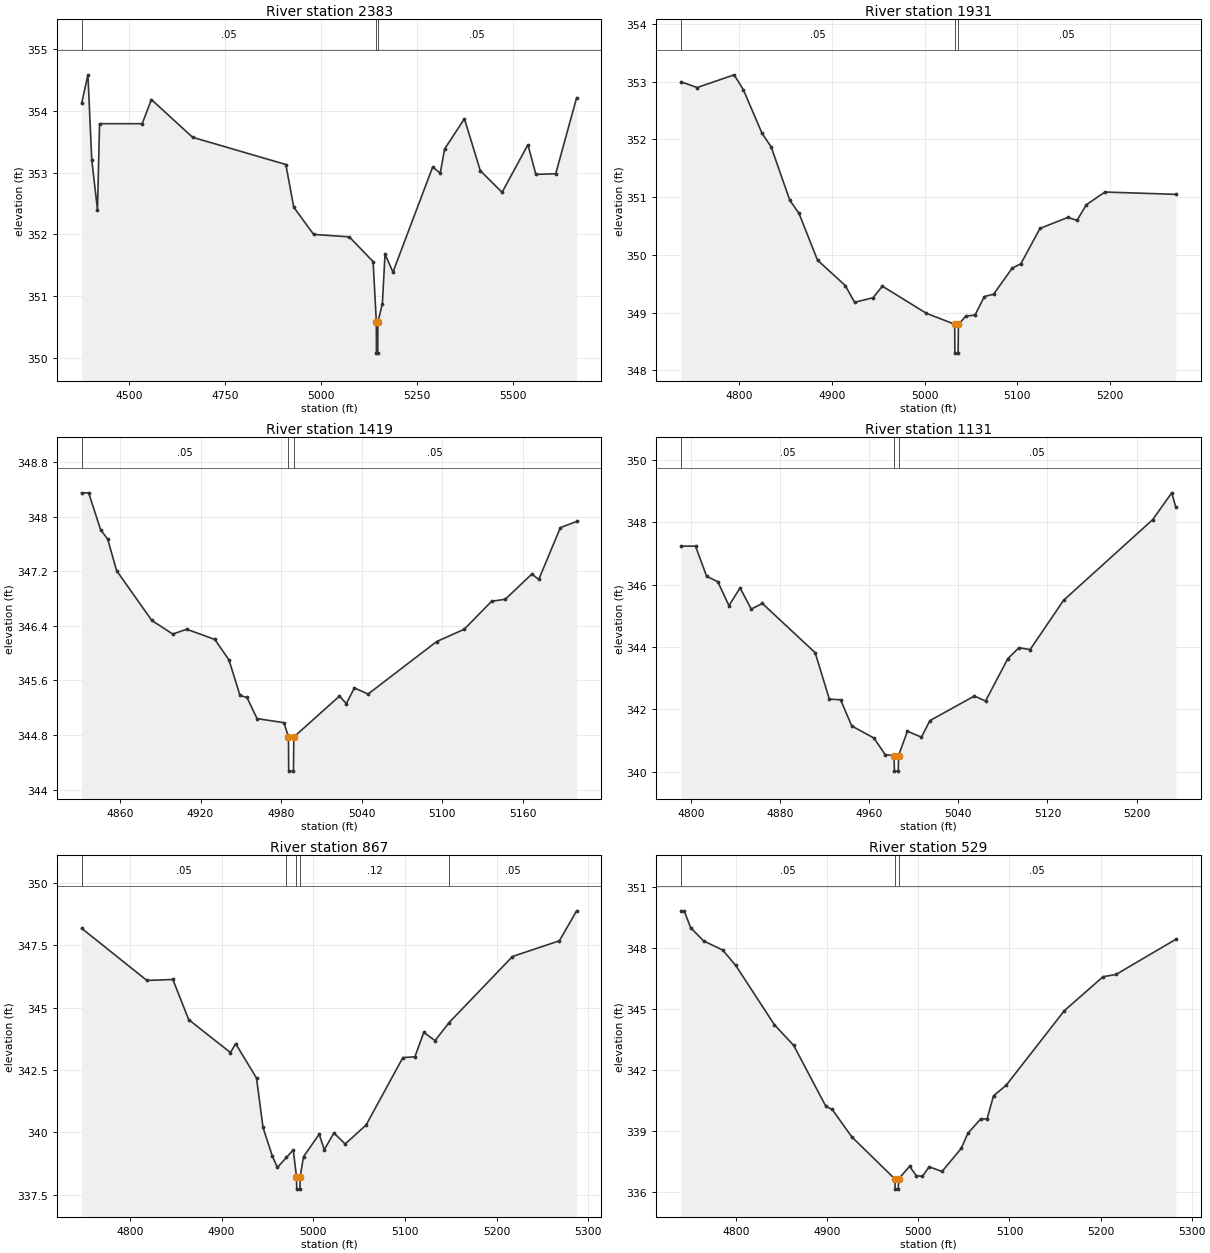
Type RM Length L Ch R = 1,2383,452,452,452
BEGIN DESCRIPTION:
2502
END DESCRIPTION:
XS GIS Cut Line= 3
      2710332.11      6796670.14      2709822.00      6796743.99
      2709073.27      6796546.38
#Sta/Elev= 30
  4376.0  354.12  4392.3  354.58  4402.4  353.20  4417.2  352.40  4422.6  353.79
  4533.7  353.79  4557.7  354.18  4665.1  353.57  4908.0  353.13  4928.7  352.44
  4980.4  352.00  5073.5  351.96  5135.5  351.56  5143.9  350.58  5144.1  350.08
  5147.6  350.08  5147.9  350.58  5159.6  350.88  5166.5  351.68  5187.2  351.39
  5290.7  353.09  5310.4  352.99  5321.7  353.38  5373.4  353.87  5414.8  353.03
  5471.5  352.68  5538.9  353.45  5559.6  352.97  5611.3  352.98  5665.8  354.21
#Mann=3,-1,0
  4376.0    0.05       0  5143.9   0.035       0  5147.9    0.05       0
Bank Sta=5143.9,5147.9
Exp/Cntr=0.3,0.1

Type RM Length L Ch R = 1,1931,512,512,512
BEGIN DESCRIPTION:
2092
END DESCRIPTION:
XS GIS Cut Line= 3
      2709943.50      6796315.35      2709676.00      6796311.00
      2709409.44      6796323.83
#Sta/Elev= 30
  4736.8  353.00  4754.3  352.90  4794.3  353.12  4804.3  352.86  4824.3  352.11
  4834.3  351.87  4854.3  350.95  4864.3  350.72  4884.3  349.91  4914.3  349.47
  4924.3  349.18  4944.3  349.26  4954.3  349.46  5001.8  348.99  5032.4  348.80
  5032.6  348.30  5036.1  348.30  5036.4  348.80  5044.4  348.94  5054.4  348.96
  5064.4  349.28  5074.4  349.32  5094.4  349.77  5103.9  349.85  5124.5  350.46
  5154.5  350.65  5164.5  350.60  5174.5  350.87  5194.6  351.09  5271.2  351.05
#Mann=3,-1,0
  4736.8    0.05       0  5032.4   0.035       0  5036.4    0.05       0
Bank Sta=5032.4,5036.4
Exp/Cntr=0.3,0.1

Type RM Length L Ch R = 1,1419,288,288,288
BEGIN DESCRIPTION:
2091
END DESCRIPTION:
XS GIS Cut Line= 3
      2709840.90      6795911.23      2709676.00      6795861.00
      2709484.12      6795819.97
#Sta/Elev= 30
  4831.5  348.35  4836.7  348.35  4845.6  347.81  4850.9  347.67  4857.5  347.21
  4883.7  346.48  4899.3  346.28  4909.8  346.35  4930.7  346.20  4941.2  345.90
  4949.4  345.38  4954.6  345.35  4962.1  345.04  4982.2  344.98  4985.5  344.77
  4985.7  344.27  4989.2  344.27  4989.5  344.77  5023.5  345.37  5028.6  345.26
  5034.6  345.49  5044.8  345.40  5095.9  346.17  5116.4  346.35  5136.8  346.76
  5147.0  346.79  5166.8  347.16  5171.9  347.08  5188.0  347.84  5200.1  347.93
#Mann=3,-1,0
  4831.5    0.05       0  4985.5   0.035       0  4989.5    0.05       0
Bank Sta=4985.5,4989.5
Exp/Cntr=0.3,0.1

Type RM Length L Ch R = 1,1131,264,264,264
BEGIN DESCRIPTION:
2090
END DESCRIPTION:
XS GIS Cut Line= 3
      2709989.03      6795622.79      2709776.00      6795611.00
      2709545.21      6795616.04
#Sta/Elev= 30
  4791.1  347.24  4804.2  347.24  4814.2  346.27  4824.2  346.10  4834.2  345.33
  4844.2  345.90  4854.2  345.22  4864.2  345.40  4911.6  343.82  4924.3  342.33
  4934.4  342.31  4944.4  341.47  4964.4  341.08  4974.4  340.55  4982.4  340.52
  4982.7  340.02  4986.2  340.02  4986.4  340.52  4994.4  341.30  5007.0  341.11
  5014.5  341.64  5054.5  342.43  5064.5  342.27  5084.5  343.63  5094.5  343.98
  5104.5  343.92  5134.5  345.50  5214.5  348.09  5231.6  348.95  5235.3  348.48
#Mann=3,-1,0
  4791.1    0.05       0  4982.4    0.04       0  4986.4    0.05       0
Bank Sta=4982.4,4986.4
Exp/Cntr=0.3,0.1

Type RM Length L Ch R = 1,867,338,338,338
BEGIN DESCRIPTION:
2246
END DESCRIPTION:
XS GIS Cut Line= 2
      2710105.15      6795486.34      2709616.16      6795257.00
#Sta/Elev= 30
  4747.3  348.18  4818.5  346.09  4846.8  346.13  4864.1  344.52  4909.7  343.20
  4915.3  343.56  4938.1  342.18  4945.2  340.20  4955.4  339.05  4960.9  338.60
  4970.7  339.00  4978.2  339.30  4981.7  338.23  4982.0  337.73  4985.5  337.73
  4985.7  338.23  4989.4  339.03  5006.5  339.93  5012.1  339.31  5022.5  339.98
  5034.9  339.54  5057.7  340.30  5097.8  343.00  5110.9  343.03  5120.6  344.01
  5132.9  343.68  5148.2  344.40  5217.4  347.05  5268.6  347.68  5287.4  348.88
#Mann=5,-1,0
  4747.3    0.05       0  4970.7    0.12       0  4981.7    0.07       0
  4985.7    0.12       0  5148.2    0.05       0
Bank Sta=4981.7,4985.7
Exp/Cntr=0.3,0.1

Type RM Length L Ch R = 1,529,430,430,430
BEGIN DESCRIPTION:
2245
END DESCRIPTION:
XS GIS Cut Line= 2
      2710166.34      6795255.68      2709769.95      6794883.98
#Sta/Elev= 30
  4739.3  349.84  4742.9  349.84  4750.0  349.01  4764.2  348.36  4785.2  347.91
  4799.4  347.16  4841.9  344.24  4863.1  343.22  4898.5  340.22  4905.4  340.07
  4926.9  338.72  4974.2  336.65  4974.5  336.15  4978.0  336.15  4978.2  336.65
  4990.4  337.27  4997.7  336.81  5004.5  336.78  5011.8  337.25  5026.0  337.02
  5047.0  338.15  5054.3  338.89  5068.5  339.61  5075.4  339.60  5082.5  340.74
  5096.4  341.26  5160.3  344.93  5202.8  346.60  5217.0  346.71  5282.7  348.44
#Mann=3,-1,0
  4739.3    0.05       0  4974.2    0.04       0  4978.2    0.05       0
Bank Sta=4974.2,4978.2
Exp/Cntr=0.3,0.1

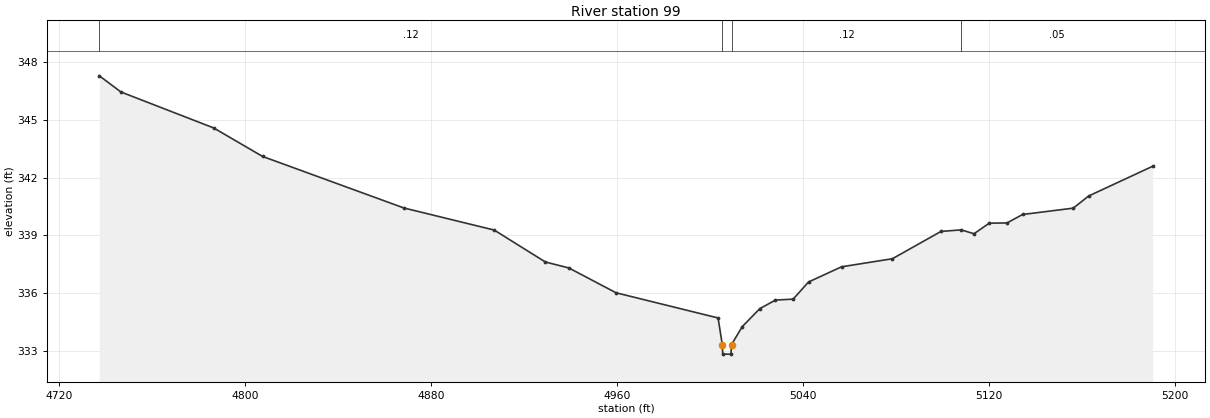
Type RM Length L Ch R = 1,99,0,0,0
BEGIN DESCRIPTION:
2089
END DESCRIPTION:
XS GIS Cut Line= 3
      2710289.95      6795070.18      2710246.03      6794811.08
      2710120.61      6794667.82
#Sta/Elev= 30
  4737.2  347.29  4746.5  346.45  4786.4  344.58  4807.4  343.10  4868.2  340.42
  4907.1  339.27  4929.1  337.61  4939.2  337.30  4959.5  336.01  5003.4  334.70
  5005.2  333.32  5005.4  332.82  5008.9  332.82  5009.2  333.32  5013.8  334.25
  5021.4  335.19  5028.1  335.63  5035.7  335.68  5042.3  336.57  5056.5  337.36
  5078.4  337.78  5099.3  339.20  5108.0  339.28  5113.5  339.08  5120.1  339.63
  5127.7  339.64  5134.4  340.08  5156.2  340.41  5162.8  341.04  5190.4  342.59
#Mann=4,-1,0
  4737.2    0.12       0  5005.2    0.07       0  5009.2    0.12       0
  5108.0    0.05       0
Bank Sta=5005.2,5009.2
Exp/Cntr=0.3,0.1

Chan Stop Cuts=-1