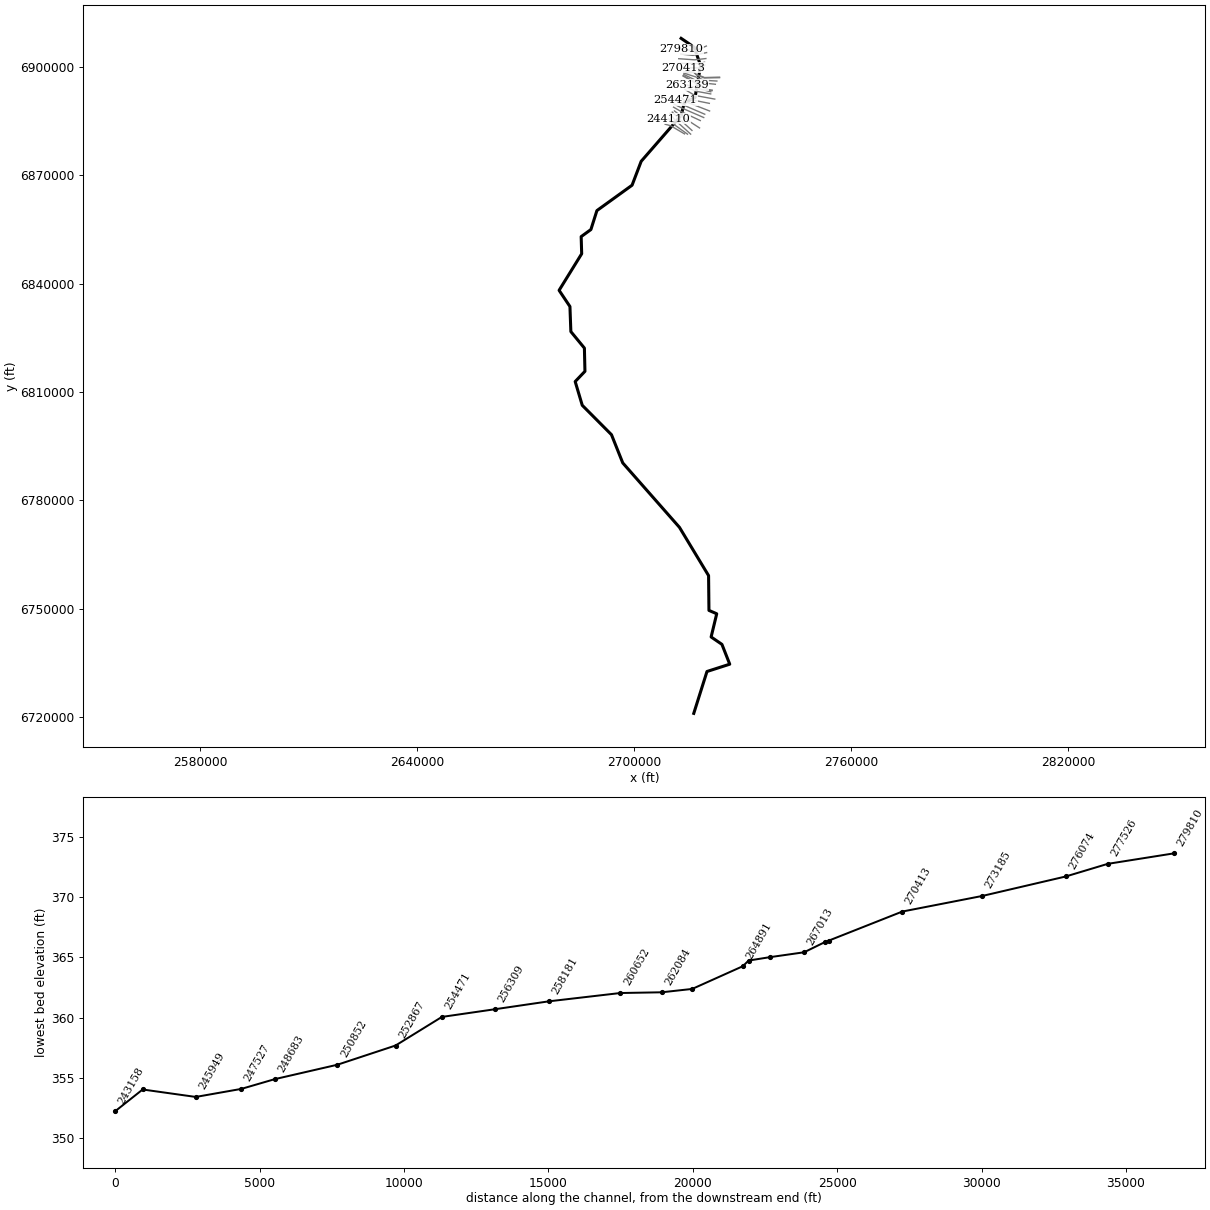
--- Cedar Creek.prj (project) ---

Proj Title=Cedar Creek Base Level Engineering
Current Plan=p01
Default Exp/Contr=0.3,0.1
English Units
Geom File=g01
Flow File=f01
Plan File=p01
Y Axis Title=Elevation
X Axis Title(PF)=Main Channel Distance
X Axis Title(XS)=Station
BEGIN DESCRIPTION:
Cedar Creek
END DESCRIPTION:
DSS Export Rating Curves= 0
DSS Export Rating Curve Sorted= 0
DSS Export Volume Flow Curves= 0
DXF OffsetX= 0
DXF OffsetY= 0
DXF ScaleX= 1
DXF ScaleY= 10

--- Cedar Creek.p01 (plan) ---

Plan Title=Multiple Run
Program Version=4.10
Short Identifier=Multiple
Geom File=g01
Flow File=f01
Subcritical Flow
K Sum by GR= 0
Std Step Tol= 0.01
Critical Tol= 0.01
Num of Std Step Trials= 20
Max Error Tol= 0.3
Flow Tol Ratio= 0.001
Split Flow NTrial= 30
Split Flow Tol= 0.02
Split Flow Ratio= 0.02
Log Output Level= 0
Friction Slope Method= 1
Unsteady Friction Slope Method= 2
Unsteady Bridges Friction Slope Method= 1
Parabolic Critical Depth
Global Vel Dist= 1 , 1 , 1
Global Log Level= 0
CheckData=True
Encroach Param=-1 ,0,0, 0
BEGIN DESCRIPTION:
Multiple Run
END DESCRIPTION:
Computation Interval=1HOUR
Output Interval=1HOUR
Run HTab= 0
Run UNet= 0
Run PostProcess= 0
Run WQNet= 0
UNET Theta= 1
UNET Theta Warmup= 1
UNET ZTol= 0.02
UNET ZSATol= 0.05
UNET MxIter= 20
UNET MaxInSteps= 0
UNET DtIC= 0
UNET DtMin= 0
UNET MaxCRTS= 20
UNET WFStab= 2
UNET SFStab= 1
UNET WFX= 1
UNET SFX= 1
UNET DSS MLevel= 4
UNET DZMax Abort= 100
UNET Convert EG Bridges= 0
UNET Use Existing IB Tables=-1
UNET Froude Reduction=False
UNET Froude Limit= 1
UNET Froude Power= 10
UNET Time Slicing=0,0, 5
UNET Junction Losses=0
Instantaneous Interval=1HOUR
Write IC File= 0
Write IC File at Sim End=0
Echo Input=False
Echo Parameters=False
Echo Output=False
Write Detailed= 0
WQ AD Non Conservative
WQ ULTIMATE=-1
WQ Max Comp Step=1HOUR
WQ Output Interval=15MIN
WQ Output Selected Increments= 0
WQ Output face flow=0
WQ Output face velocity=0
WQ Output face area=0
WQ Output face dispersion=0
WQ Output cell volume=0
WQ Output cell surface area=0
WQ Output cell continuity=0
WQ Output cumulative cell continuity=0
WQ Output face conc=0
WQ Output face dconc_dx=0
WQ Output face courant=0
WQ Output face peclet=0
WQ Output face adv mass=0
WQ Output face disp mass=0
WQ Output cell mass=0
WQ Output cell source sink temp=0
WQ Output cell source sink nsm=0
WQ Output MaxMinRange=-1
WQ Daily Max Min Mean=-1
WQ Daily Range=0
WQ Daily Time=0
WQ Create Restart=0
WQ Fixed Restart=0
WQ System Summary=0
WQ Use Fixed Temperature=0
Sorting and Armoring Iterations= 10
XS Update Threshold= 0.02
Hydraulics Update Threshold= 0.02
Energy Slope Method= 1
Volume Change Method= 0
XS Weighting Method= 0
Number of US Weighted Cross Sections= 1
Number of DS Weighted Cross Sections= 1
Upstream XS Weight=0.25
Main XS Weight=0.5
Downstream XS Weight=0.25
Number of DS XS's Weighted with US Boundary= 1
Upstream Boundary Weight= 1
Weight of XSs Associated with US Boundary= 0
Number of US XS's Weighted with DS Boundary= 1
Downstream Boundary Weight= 0.5
Weight of XSs Associated with DS Boundary= 0.5
Sediment Output Level= 4
Mass or Volume Output= 0
Output Increment Type= 1
Profile and TS Output Increment= 10
XS Output Flag= 0
XS Output Increment= 10
Disregard all LS=0
Disregard all Conn=0
Disregard all Breaches=0
Disregard all Pumps=0

--- Cedar Creek.f01 (steady flow) ---

Flow Title=Multiple
Program Version=4.10
Number of Profiles= 7
Profile Names=10-year,25-year,50-year,1pct_min,100-year,1pct_plu,500-year
River Rch & RM=Cedar Creek,Reach-1         ,279810
   15500   22300   28300   21800   34900   48000   53000
River Rch & RM=Cedar Creek,Reach-1         ,263139
   16100   23100   29300   22400   35900   49500   54100
River Rch & RM=Cedar Creek,Reach-1         ,226945
   17500   25200   32000   24700   39600   54500   60400
River Rch & RM=Cedar Creek,Reach-1         ,209090
   18700   27300   34700   27000   43200   59500   66900
River Rch & RM=Cedar Creek,Reach-1         ,201898
   19100   27800   35400   27500   44100   60700   68300
River Rch & RM=Cedar Creek,Reach-1         ,172446
   19400   28100   35800   27800   44600   61400   69200
River Rch & RM=Cedar Creek,Reach-1         ,151305
   30400   41900   51200   38300   61400   84500   88000
River Rch & RM=Cedar Creek,Reach-1         ,133831
   33900   45500   54400   39800   63700   87700   86700
River Rch & RM=Cedar Creek,Reach-1         ,124900
   35300   47600   57200   42000   67300   92600   92500
River Rch & RM=Cedar Creek,Reach-1         ,100855
   39600   54800   67200   50500   80900  111000  117000
River Rch & RM=Cedar Creek,Reach-1         ,72600
   44200   62900   78900   60500   97000  133000  146000
River Rch & RM=Cedar Creek,Reach-1         ,57008
   44300   63000   79100   60700   97300  134000  147000
River Rch & RM=Cedar Creek,Reach-1         ,54245
     970    1500    2040    1710    2740    3770    5090
River Rch & RM=Cedar Creek,Reach-1         ,44146
    3730    5300    6690    5200    8330   11460   13160
River Rch & RM=Cedar Creek,Reach-1         ,19339
    7360   10250   13240   10290   17640   24270   25600
Boundary for River Rch & Prof#=Cedar Creek,Reach-1         , 1
Up Type= 0
Dn Type= 3
Dn Slope=0.0004
Boundary for River Rch & Prof#=Cedar Creek,Reach-1         , 2
Up Type= 0
Dn Type= 3
Dn Slope=0.0004
Boundary for River Rch & Prof#=Cedar Creek,Reach-1         , 3
Up Type= 0
Dn Type= 3
Dn Slope=0.0004
Boundary for River Rch & Prof#=Cedar Creek,Reach-1         , 4
Up Type= 0
Dn Type= 3
Dn Slope=0.0004
Boundary for River Rch & Prof#=Cedar Creek,Reach-1         , 5
Up Type= 0
Dn Type= 3
Dn Slope=0.0004
Boundary for River Rch & Prof#=Cedar Creek,Reach-1         , 6
Up Type= 0
Dn Type= 3
Dn Slope=0.0004
Boundary for River Rch & Prof#=Cedar Creek,Reach-1         , 7
Up Type= 0
Dn Type= 3
Dn Slope=0.0004
DSS Import GetInterval= 0
DSS Import GetPeak= 0
DSS Import FillOption= 0

--- Cedar Creek.g01 (geometry) ---

Geom Title=Cedar Creek
Program Version=4.10

River Reach=Cedar Creek     ,Reach-1
Reach XY= 30
        2713026.        6907911.      2716618.18      6905467.19
      2718424.01      6900405.72      2716872.56      6891512.25
      2713889.11      6890074.24      2713065.66      6886600.76
      2701983.48      6873867.06        2699460.      6867243.86
      2689734.13      6860217.08        2688073.      6854968.59
      2685379.13      6853009.37      2685522.91      6848262.64
      2679275.61      6838142.66      2682273.94      6833655.15
      2682529.75      6826712.55      2686274.95      6822150.57
      2686423.83      6815716.44      2683725.63      6812883.88
      2685681.46      6806308.55      2693765.22      6798170.68
      2696883.82      6790354.81      2712565.24      6772520.68
      2720623.94      6759155.15       2720727.2       6749521.5
      2722876.48      6748590.84      2721327.96      6742166.88
      2724318.38       6740117.5       2726475.8      6734629.26
      2720181.59      6732605.39        2716526.        6721011.

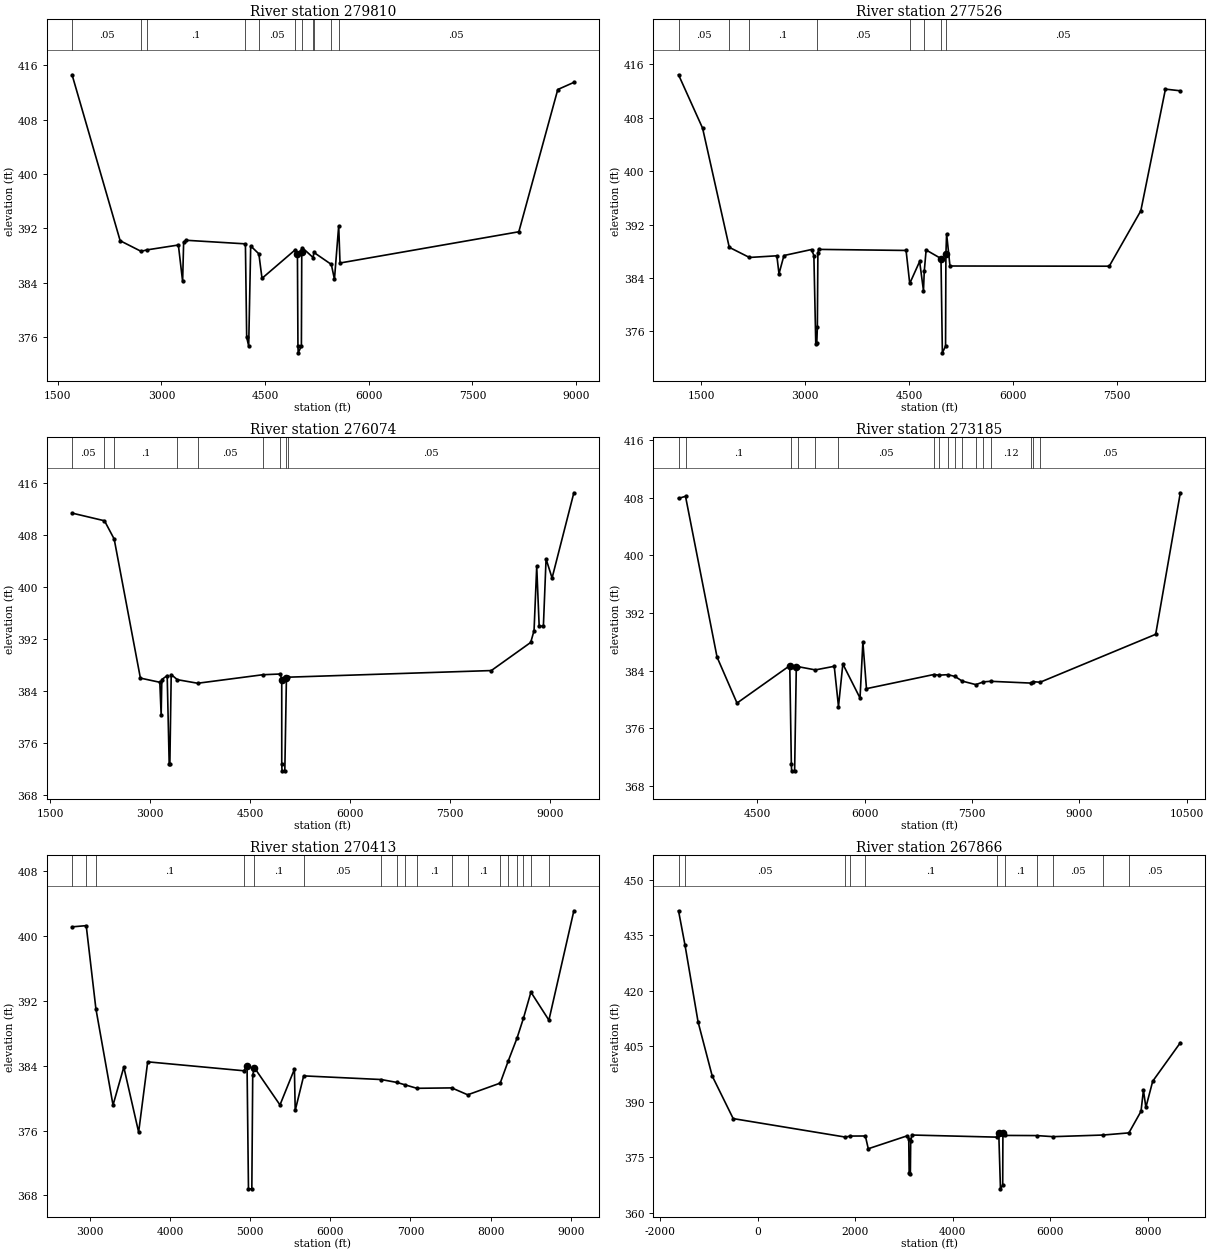
Type RM Length L Ch R = 1 ,279810  ,2284,2284,2284
BEGIN DESCRIPTION:
Cedar Creek 114.0
END DESCRIPTION:
XS GIS Cut Line= 3
      2719996.74      6905774.62        2716976.        6904461.
       2713034.9      6904923.91
#Sta/Elev= 30
    1706  414.61    2402  390.17  2704.6  388.61  2788.8  388.82  3244.4  389.54
  3305.9  384.19  3320.7  389.91  3352.7  390.24  4214.7  389.71  4233.2  375.95
  4262.1  374.66  4291.2   389.4  4409.4  388.24  4454.8  384.63  4938.7  388.86
  4967.6  388.26    4975  374.66    4979  373.66    5025  374.66  5030.2  388.45
  5039.1  389.13  5194.7  387.69  5205.3  388.45  5458.2  386.68  5503.4   384.5
  5564.8  392.36    5584  386.89  8171.7  391.49  8735.5  412.44  8968.2  413.49
#Mann= 11 ,-1 , 0
    1706     .05       0  2704.6     .12       0  2788.8      .1       0
  4214.7     .12       0  4409.4     .05       0  4938.7     .04       0
  5039.1     .05       0  5194.7     .05       0  5205.3     .12       0
  5458.2      .1       0  5564.8     .05       0
Bank Sta=4967.6,5030.2
XS Rating Curve= 0 ,0
Exp/Cntr=0.3,0.1

Type RM Length L Ch R = 1 ,277526  ,1452,1452,1452
BEGIN DESCRIPTION:
Cedar Creek 113.0
END DESCRIPTION:
XS GIS Cut Line= 3
      2720075.99        6903961.      2716325.57        6903186.
      2712932.35      6903557.94
#Sta/Elev= 30
  1170.6  414.45  1517.8  406.45  1902.9   388.6  2193.8  387.08    2590  387.33
  2620.6  384.63  2692.1  387.37  3090.3  388.27  3124.3  387.37  3151.6  374.09
  3166.6  374.33  3174.5  376.67  3182.2  387.74  3192.4  388.29  4455.1  388.13
  4507.9  383.18  4650.9  386.48  4706.3   382.1  4717.5     385  4744.5   388.2
    4959  386.92    4979  372.79    5025  373.79    5030  387.56  5040.1  390.63
  5088.7   385.8  7387.7  385.77  7843.5  394.07  8198.9   412.3  8413.8  412.05
#Mann= 8 ,-1 , 0
  1170.6     .05       0  1902.9     .12       0  2193.8      .1       0
  3166.6     .05       0  4507.9      .1       0  4717.5     .05       0
    4959     .04       0    5030     .05       0
Bank Sta=4959,5030
XS Rating Curve= 0 ,0
Exp/Cntr=0.3,0.1

Type RM Length L Ch R = 1 ,276074  ,2889,2889,2889
BEGIN DESCRIPTION:
Cedar Creek 112.0
END DESCRIPTION:
XS GIS Cut Line= 3
      2719875.96        6902311.        2716726.        6901961.
      2712369.61      6902273.11
#Sta/Elev= 30
  1825.5  411.32  2312.4  410.14  2457.9  407.34  2851.7  385.98  3143.5  385.34
  3163.6   380.3  3173.7  385.76  3254.2  386.37  3284.4  372.74  3294.4  372.82
  3314.6  386.52  3406.9  385.74  3712.2  385.19  4692.2   386.5  4954.6  386.61
  4974.7  385.71    4975  372.74    4979  371.74    5021  371.74    5045  385.93
  5063.6  386.12  8122.8  387.14  8714.4  391.46  8764.5  393.28  8804.6  403.14
  8841.4  393.93  8904.8  393.98  8944.9  404.28  9035.2  401.35  9362.4  414.44
#Mann= 9 ,-1 , 0
  1825.5     .05       0  2312.4     .12       0  2457.9      .1       0
  3406.9     .12       0  3712.2     .05       0  4692.2      .1       0
  4954.6     .04       0    5045     .12       0  5063.6     .05       0
Bank Sta=4974.7,5045
XS Rating Curve= 0 ,0
Exp/Cntr=0.3,0.1

Type RM Length L Ch R = 1 ,273185  ,2772,2772,2772
BEGIN DESCRIPTION:
Cedar Creek 111.0
END DESCRIPTION:
XS GIS Cut Line= 3
      2719520.16       6901311.5        2717976.        6900911.
      2712561.86        6900999.
#Sta/Elev= 30
  3399.1  407.91  3496.5   408.2  3937.1   385.9    4216  379.52    4953  384.71
    4975  371.12    4979  370.12    5021  370.12  5044.4  384.58  5064.4  384.58
  5310.5  384.12  5574.4  384.62  5633.6  379.04  5694.4  384.94  5934.5  380.22
  5974.5  387.98  6024.5  381.52    6965  383.48  7040.7  383.39  7163.1  383.46
  7262.2  383.21  7361.2  382.57  7552.8  382.08  7658.4  382.46  7757.5  382.54
  8325.8  382.29    8350  382.49  8450.8  382.41   10065  389.06 10409.2  408.69
#Mann= 17 ,-1 , 0
  3399.1     .12       0  3496.5      .1       0    4975     .04       0
  5064.4      .1       0  5310.5     .12       0  5633.6     .05       0
    6965     .12       0  7040.7      .1       0  7163.1     .05       0
  7262.2     .12       0  7361.2      .1       0  7552.8     .12       0
  7658.4     .05       0  7757.5     .12       0  8325.8     .05       0
    8350     .12       0  8450.8     .05       0
Bank Sta=4953,5044.4
XS Rating Curve= 0 ,0
Exp/Cntr=0.3,0.1

Type RM Length L Ch R = 1 ,270413  ,2547,2547,2547
BEGIN DESCRIPTION:
Cedar Creek 110.0
END DESCRIPTION:
XS GIS Cut Line= 4
      2719609.62      6900519.07      2718510.69      6899552.08
      2717768.14      6899704.83      2713729.44      6899744.99
#Sta/Elev= 30
  2778.1  401.08  2954.6  401.23  3075.3     391  3289.1  379.13  3423.7  383.81
  3608.7   375.8  3721.6  384.46  4920.5  383.36  4961.3  383.96    4979  368.82
    5021  368.82  5032.1  382.84  5052.1  383.75  5372.2  379.15  5552.2  383.55
  5562.2  378.47  5667.8  382.73  6634.4  382.28  6832.5  381.92  6931.5  381.63
  7080.3   381.2  7515.4  381.25  7714.3   380.4  8119.9  381.84  8218.9  384.53
  8330.5   387.4  8410.5  389.85  8503.3  393.04  8727.5  389.59  9038.9  403.06
#Mann= 18 ,-1 , 0
  2778.1      .1       0  2954.6     .05       0  3075.3      .1       0
  4920.5     .04       0  5052.1      .1       0  5667.8     .05       0
  6634.4     .12       0  6832.5     .05       0  6931.5     .12       0
  7080.3      .1       0  7515.4     .12       0  7714.3      .1       0
  8119.9     .12       0  8218.9     .05       0  8330.5     .12       0
  8410.5     .05       0  8503.3     .12       0  8727.5     .05       0
Bank Sta=4961.3,5052.1
XS Rating Curve= 0 ,0
Exp/Cntr=0.3,0.1

Type RM Length L Ch R = 1 ,267866  ,123,123,123
BEGIN DESCRIPTION:
Cedar Creek108.6
END DESCRIPTION:
XS GIS Cut Line= 6
      2723656.57      6897170.14      2719478.11      6897055.77
      2719075.34      6897250.22      2717306.47       6897871.4
        2716565.      6898599.05       2713819.5      6898548.81
#Sta/Elev= 30
 -1624.4  441.58 -1490.9  432.24 -1223.7  411.54  -933.6  396.91  -503.4  385.39
  1798.7  380.39  1897.1  380.67  2207.5  380.69  2267.6  377.24  3064.8  380.73
  3097.5  379.87  3106.5  370.56  3130.8  370.47  3137.8  379.21    3164  380.95
    4902  380.38  4944.4  381.46    4979   366.4    5025   367.4  5029.3  381.51
  5071.7  380.84  5720.9   380.8  6059.5  380.51  7086.3  380.95  7613.5  381.53
  7861.9  387.36  7911.9  393.08  7961.9  388.42  8101.9   395.5  8668.5   405.9
#Mann= 11 ,-1 , 0
 -1624.4     .12       0 -1490.9     .05       0  1798.7     .12       0
  1897.1     .05       0  2207.5      .1       0    4902     .04       0
  5071.7      .1       0  5720.9     .12       0  6059.5     .05       0
  7086.3     .12       0  7613.5     .05       0
Bank Sta=4944.4,5029.3
XS Rating Curve= 0 ,0
Exp/Cntr=0.3,0.1

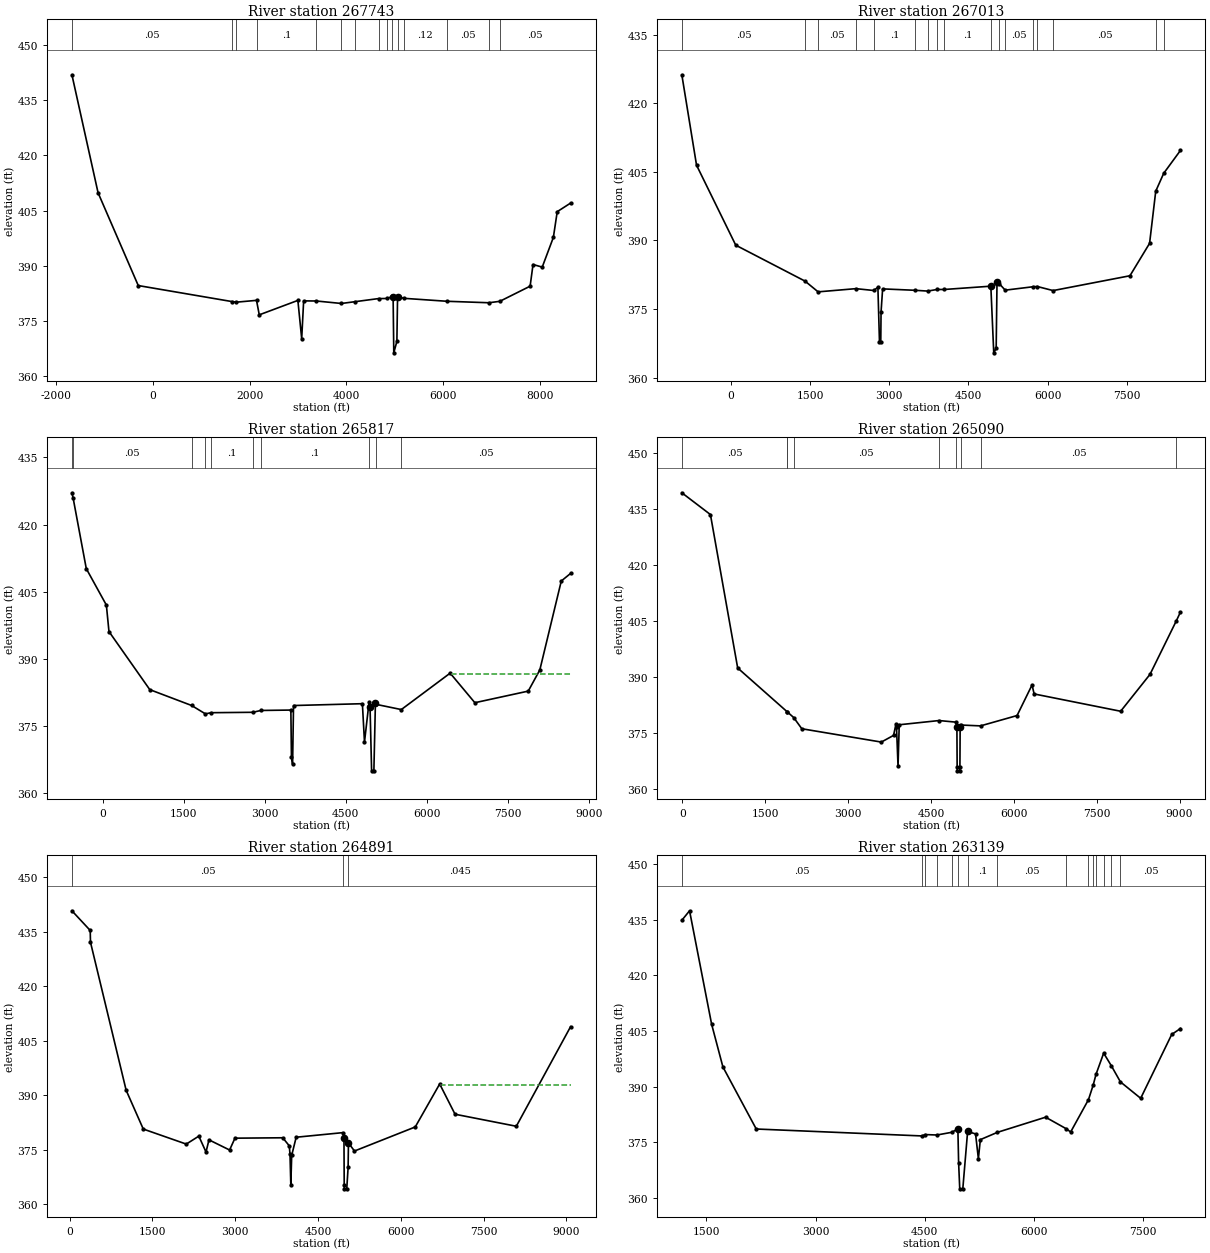
Type RM Length L Ch R = 1 ,267743  ,730,730,730
BEGIN DESCRIPTION:
Cedar Creek108.5
END DESCRIPTION:
XS GIS Cut Line= 6
      2723656.49      6897010.41      2719447.04      6896944.66
      2717271.75      6897758.55      2716609.19      6898443.79
      2716474.64      6898500.22      2713810.56      6898449.83
#Sta/Elev= 30
 -1671.1  441.96 -1130.5  409.84  -300.4   384.6    1628  380.26  1726.9  380.08
  2142.8  380.57  2199.9  376.63  2997.6  380.56  3076.4  370.14  3116.7  380.43
  3378.2380.3998  3896.4379.7241    4188380.2279  4664.6381.0565  4847.2381.0789
  4951.2  381.72  4965.4  381.36    4979  366.29  5043.1  369.42  5057.2  381.59
  5184.8  381.13  6080.6  380.32  6944.3  379.92  7169.3  380.31  7795.9  384.43
  7855.9  390.33    8046  389.62    8276   397.7    8356  404.71  8631.5  407.04
#Mann= 15 ,-1 , 0
 -1671.1     .05       0    1628     .12       0  1726.9     .05       0
  2142.8      .1       0  3378.2     .05       0  3896.4     .12       0
    4188      .1       0  4664.6     .12       0  4847.2      .1       0
  4951.2     .04       0  5057.2      .1       0  5184.8     .12       0
  6080.6     .05       0  6944.3     .12       0  7169.3     .05       0
Bank Sta=4965.4,5057.2
XS Rating Curve= 0 ,0
Exp/Cntr=0.3,0.1

Type RM Length L Ch R = 1 ,267013  ,1196,1196,1196
BEGIN DESCRIPTION:
Cedar Creek 108.0
END DESCRIPTION:
XS GIS Cut Line= 4
      2722915.65      6896089.62        2719501.      6896288.17
      2717165.66      6897200.88      2713813.56      6898262.94
#Sta/Elev= 30
  -928.5  426.21  -649.9  406.45    92.9  388.96  1404.7  381.11  1652.8  378.76
  2367.8  379.46  2704.9  379.06    2785  379.76  2814.8   367.8  2839.3  367.75
  2844.7  374.35  2874.5  379.41  3492.2   379.1  3727.2  378.93  3906.5  379.28
  4041.9  379.28  4923.8     380    4979  365.43    5025  366.43  5040.9  381.01
  5084.5  380.54  5195.9  379.13  5718.2  379.87    5803  379.93  6103.3  379.04
  7558.5  382.28  7930.3  389.36  8047.1  400.77  8198.2  404.68  8515.6  409.68
#Mann= 17 ,-1 , 0
  -928.5     .05       0  1404.7      .1       0  1652.8     .05       0
  2367.8     .12       0  2704.9      .1       0  3492.2     .12       0
  3727.2     .05       0  3906.5     .12       0  4041.9      .1       0
  4923.8     .04       0  5084.5     .12       0  5195.9     .05       0
  5718.2     .12       0    5803      .1       0  6103.3     .05       0
  8047.1    .075       0  8198.2     .05       0
Bank Sta=4923.8,5040.9
XS Rating Curve= 0 ,0
Exp/Cntr=0.3,0.1

Type RM Length L Ch R = 1 ,265817  ,727,727,727
BEGIN DESCRIPTION:
Cedar Creek 107.0
END DESCRIPTION:
XS GIS Cut Line= 4
      2722500.89      6895193.36      2719160.78      6895547.18
      2717082.82      6896312.75      2713781.03      6897904.86
#Sta/Elev= 30
  -573.7   427.1  -551.6  425.95  -307.3  410.16    64.7  402.03   112.9  396.12
   869.2  383.15  1644.1  379.61  1899.5  377.74  2005.4     378  2778.6  378.09
  2927.2   378.5  3482.9  378.59  3493.6   368.2  3514.9  366.49  3532.3   379.6
  4808.1  380.01    4847  371.44  4932.3  380.43  4949.7  379.37    4979  365.02
    5021  365.02  5049.6  380.23  5055.1  379.88  5529.3   378.7  6434.2  386.83
    6892  380.23    7881  382.82  8095.6  387.55  8493.2   407.4  8665.2  409.09
#Mann= 10 ,-1 , 0
  -573.7      .1       0  -551.6     .05       0  1644.1      .1       0
  1899.5     .05       0  2005.4      .1       0  2778.6     .12       0
  2927.2      .1       0  4932.3     .04       0  5055.1      .1       0
  5529.3     .05       0
#XS Ineff= 2 , 0
                         6452.53          386.68
Permanent Ineff=
       F       F
Bank Sta=4949.7,5049.6
XS Rating Curve= 0 ,0
Exp/Cntr=0.3,0.1

Type RM Length L Ch R = 1 ,265090  ,199,199,199
BEGIN DESCRIPTION:
Cedar Creek 106.0
END DESCRIPTION:
XS GIS Cut Line= 4
      2721617.79      6893579.78      2720615.22      6893709.98
        2717126.        6895661.      2713614.35       6897611.9
#Sta/Elev= 30
    -8.4  439.27   509.3  433.43  1002.6  392.31  1896.2   380.6    1900  380.55
  2016.1  379.03  2163.5  376.02  3602.5  372.45    3824  374.24  3867.4  377.27
  3877.4  376.48    3905  365.98  3926.7  377.09  4647.3  378.22  4954.6  377.79
  4970.5  376.52    4975  365.74    4979  364.74    5021  364.74    5025  365.74
 5029.32  376.59  5035.7  377.02  5398.3  376.79  6059.5  379.56  6330.7  387.76
  6368.4  385.35  7934.5  380.71  8465.3  390.59  8941.6  404.93  9017.4  407.31
#Mann= 9 ,-1 , 0
    -8.4     .05       0  1896.2     .12       0    1900      .1       0
  2016.1     .05       0  4647.3      .1       0  4954.6     .04       0
  5035.7    .045       0  5398.3     .05       0  8941.6    .075       0
#XS Ineff= 2 , 0
                         6330.24          387.73
Permanent Ineff=
       F       F
Bank Sta=4970.5,5029.32
XS Rating Curve= 0 ,0
Exp/Cntr=0.3,0.1

Type RM Length L Ch R = 1 ,264891  ,1752,1752,1752
BEGIN DESCRIPTION:
Cedar Creek 105.0
END DESCRIPTION:
XS GIS Cut Line= 4
      2721578.72      6893414.85      2720567.48      6893540.71
        2717126.        6895461.      2713570.11      6897455.14
#Sta/Elev= 30
    40.1  440.83   371.8  435.41   376.8  432.16  1023.2   391.4  1333.4  380.73
  2112.7  376.59    2340  378.78  2470.3   374.4    2524  377.76  2897.7  374.96
  2994.8  378.22  3860.9  378.33  3979.7   376.1  3992.4  373.78  4007.2  365.38
  4023.2  373.47  4104.3  378.48  4954.4  379.75  4970.4  378.28    4975  365.27
    4979  364.27    5021  364.27  5045.7  370.21  5051.5  376.93  5160.6  374.68
  6262.2  381.31    6705  393.14  6983.6  384.81  8093.7   381.5    9077  408.91
#Mann= 3 ,-1 , 0
    40.1     .05       0  4954.4     .04       0  5051.5    .045       0
#XS Ineff= 2 , 0
                         6714.04          392.99
Permanent Ineff=
       F       F
Bank Sta=4970.4,5051.5
XS Rating Curve= 0 ,0
Exp/Cntr=0.3,0.1

Type RM Length L Ch R = 1 ,263139  ,1055,1055,1055
BEGIN DESCRIPTION:
Cedar Creek 104.0
END DESCRIPTION:
XS GIS Cut Line= 3
      2721235.47      6893108.85        2717526.        6894111.
      2714650.97      6894986.01
#Sta/Elev= 30
  1162.5  434.87  1268.7  437.44  1572.2  406.77  1726.6  395.29  2184.5  378.53
  4458.9  376.66  4507.8  377.03  4665.3  376.91  4871.7  377.65  4953.2  378.61
  4963.5  369.42    4979  362.38    5021  362.38  5087.1  377.86  5196.1  377.21
  5234.9  370.53  5261.8  375.66  5495.9  377.63  6157.8  381.72  6442.3  378.59
    6502  377.72  6746.8  386.46  6811.8  390.41    6851  393.33  6955.3  399.01
  7059.5  395.64  7185.5  391.25  7463.6  386.82    7890  404.06  8010.2  405.66
#Mann= 15 ,-1 , 0
  1162.5     .05       0  4458.9     .12       0  4507.8     .05       0
  4665.3     .12       0  4871.7      .1       0  4953.2     .04       0
  5087.1      .1       0  5495.9     .05       0  6442.3      .1       0
  6746.8     .05       0  6811.8     .12       0    6851     .05       0
  6955.3     .12       0  7059.5      .1       0  7185.5     .05       0
Bank Sta=4953.2,5087.1
XS Rating Curve= 0 ,0
Exp/Cntr=0.3,0.1

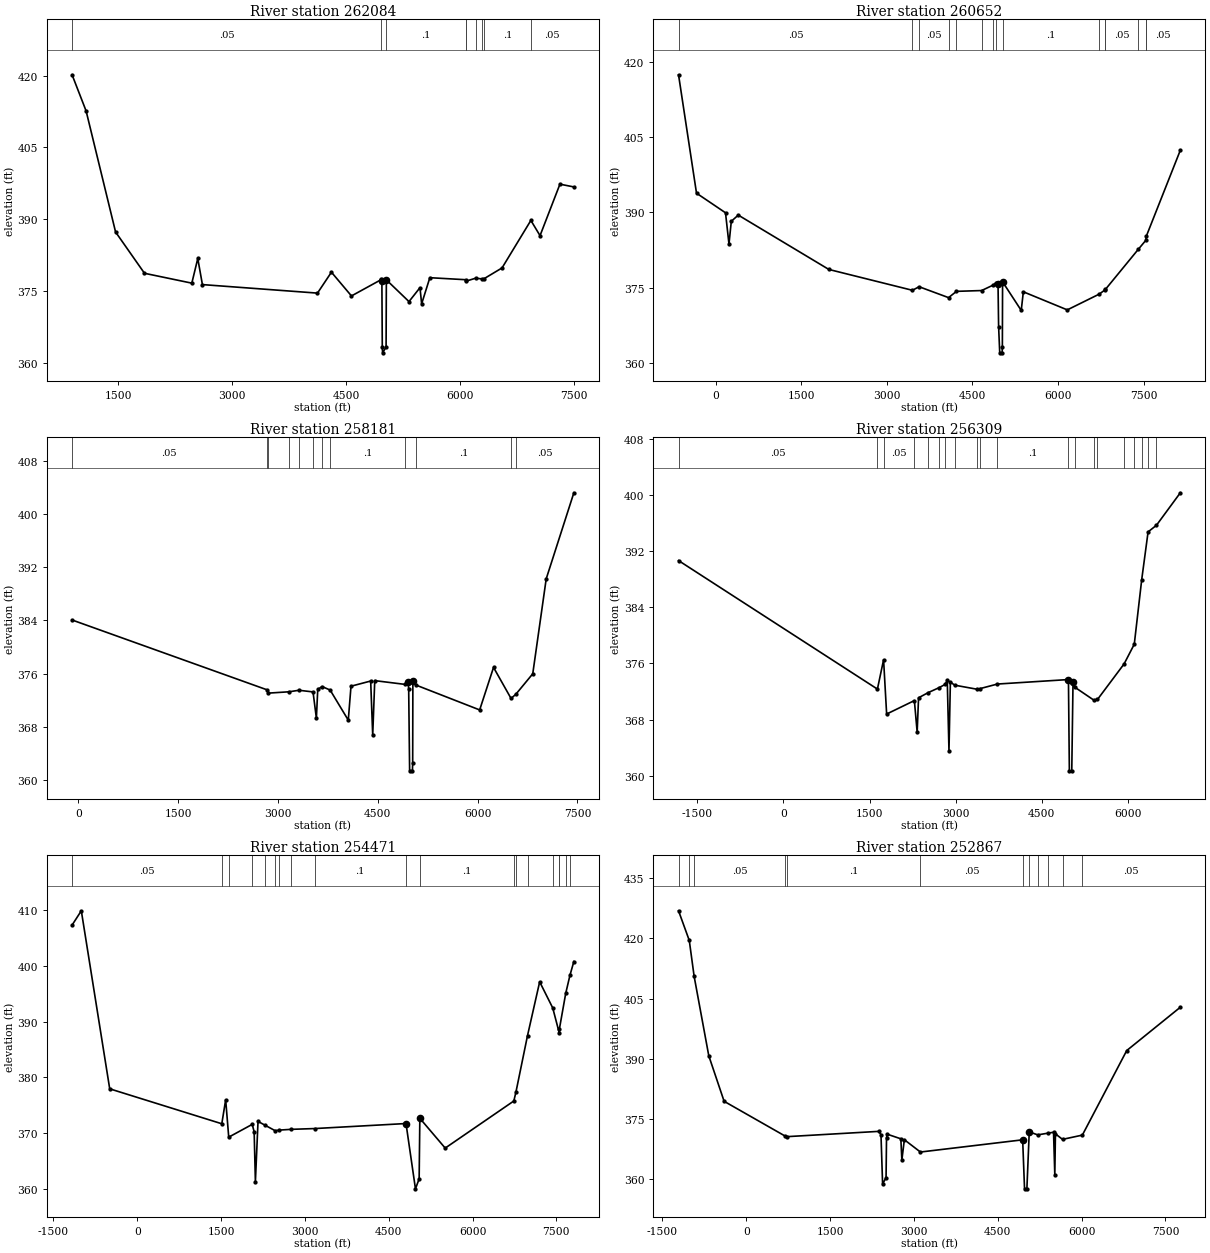
Type RM Length L Ch R = 1 ,262084  ,1432,1432,1432
BEGIN DESCRIPTION:
Cedar Creek 103.0
END DESCRIPTION:
XS GIS Cut Line= 3
      2721213.77      6892522.91        2717176.        6893261.
      2714860.44      6894204.83
#Sta/Elev= 30
   891.5  420.16  1076.4   412.6  1464.2  387.33  1844.8  378.71  2467.9  376.65
  2546.2   381.8  2607.2  376.35  4121.9  374.57  4305.5  378.94  4569.2  373.98
  4964.5  377.42  4969.6  377.11    4975   363.3    4979   362.1    5025   363.3
  5028.6  377.34  5326.4   372.8  5471.3  375.71  5492.9  372.33  5600.9  377.79
  6072.4  377.37    6074  377.05  6202.4  377.68  6288.3  377.54  6317.6  377.61
  6551.3  379.83  6930.8  389.75  7051.4  386.57  7313.4  397.32  7496.7  396.74
#Mann= 9 ,-1 , 0
   891.5     .05       0  4964.5     .04       0  5028.6      .1       0
  6072.4     .05       0    6074      .1       0  6202.4     .05       0
  6288.3     .12       0  6317.6      .1       0  6930.8     .05       0
Bank Sta=4969.6,5028.6
XS Rating Curve= 0 ,0
Exp/Cntr=0.3,0.1

Type RM Length L Ch R = 1 ,260652  ,2471,2471,2471
BEGIN DESCRIPTION:
Cedar Creek 102.0
END DESCRIPTION:
XS GIS Cut Line= 3
      2722336.03      6891090.91        2716776.        6892111.
      2714090.25      6893748.86
#Sta/Elev= 30
  -653.1  417.39  -337.9  393.82   170.4  389.92   231.4   383.7   272.1  388.22
   394.1  389.46  1982.4  378.64    3448  374.49  3565.2   375.2  4081.5  373.03
  4220.7  374.28  4661.2  374.44  4863.4375.5233    4915     376  4948.9  375.83
  4959.1  367.28    4979  362.04    5021  362.04    5025  363.24  5028.8  376.18
    5356  370.48  5392.8  374.19  6163.4  370.59  6723.8  373.73    6817  374.51
  6833.1  374.68  7408.7  382.65  7540.7  384.44  7547.5  385.21  8145.5  402.37
#Mann= 15 ,-1 , 0
  -653.1     .05       0    3448     .12       0  3565.2     .05       0
  4081.5     .12       0  4220.7     .05       0  4661.2     .05       0
  4863.4      .1       0    4915     .04       0  5028.8      .1       0
  6723.8     .12       0    6817      .1       0  6833.1     .05       0
  7408.7      .1       0  7540.7     .12       0  7547.5     .05       0
Bank Sta=4948.9,5028.8
XS Rating Curve= 0 ,0
Exp/Cntr=0.3,0.1

Type RM Length L Ch R = 1 ,258181  ,1872,1872,1872
BEGIN DESCRIPTION:
Cedar Creek 101.0
END DESCRIPTION:
XS GIS Cut Line= 3
      2720825.98        6889911.        2715826.        6890911.
      2713826.01      6892310.99
#Sta/Elev= 30
   -93.4  384.06    2830  373.57    2856  373.05  3165.9  373.25  3316.5  373.48
  3527.4  373.23  3577.9  369.27  3598.3   373.6  3663.1  374.04  3784.6  373.51
  4057.2  368.98    4098  374.09  4393.7  374.87  4424.3  366.72  4454.9  374.93
  4913.8  374.36  4954.6  374.75  4964.8  373.69    4979  361.35    5021  361.35
    5025  362.55  5027.8   374.9  5069.7  374.28  6031.4  370.52  6239.8  376.92
  6502.9  372.25  6574.5  372.87  6829.2  375.96  7031.5  390.26  7446.9  403.21
#Mann= 12 ,-1 , 0
   -93.4     .05       0    2830     .12       0    2856     .05       0
  3165.9     .12       0  3316.5     .05       0  3527.4     .12       0
  3663.1     .05       0  3784.6      .1       0  4913.8     .04       0
  5069.7      .1       0  6502.9     .12       0  6574.5     .05       0
Bank Sta=4954.6,5027.8
XS Rating Curve= 0 ,0
Exp/Cntr=0.3,0.1

Type RM Length L Ch R = 1 ,256309  ,1838,1838,1838
BEGIN DESCRIPTION:
Cedar Creek 100.0
END DESCRIPTION:
XS GIS Cut Line= 3
      2720901.99      6887794.47       2714542.8      6890277.41
      2713040.92       6891461.1
#Sta/Elev= 30
 -1827.4  390.68  1636.3  372.35  1743.6  376.53  1796.8  368.79  2279.9  370.71
  2328.3  366.22  2352.8  371.11  2521.3  371.85  2709.1  372.55  2816.3  373.02
  2852.6   373.6  2882.4  363.54  2906.9  373.36  2981.2  372.91  3377.7  372.32
  3429.3  372.43  3726.2  373.07  4963.1  373.71    4979  360.69    5021  360.69
  5042.7   373.3  5071.6  372.63  5400.9   370.8    5469  370.87    5933  375.95
  6109.7  378.75  6239.2  387.97    6350  394.77  6496.2  395.72  6911.6  400.35
#Mann= 20 ,-1 , 0
 -1827.4     .05       0  1636.3     .12       0  1743.6     .05       0
  2279.9      .1       0  2521.3      .1       0  2709.1     .12       0
  2816.3      .1       0  2981.2     .12       0  3377.7     .05       0
  3429.3     .12       0  3726.2      .1       0  4963.1     .04       0
  5071.6      .1       0  5400.9     .12       0    5469      .1       0
    5933     .05       0  6109.7     .12       0  6239.2     .05       0
    6350     .12       0  6496.2     .05       0
Bank Sta=4963.1,5042.7
XS Rating Curve= 0 ,0
Exp/Cntr=0.3,0.1

Type RM Length L Ch R = 1 ,254471  ,1604,1604,1604
BEGIN DESCRIPTION:
Cedar Creek 99.0
END DESCRIPTION:
XS GIS Cut Line= 3
      2719568.59      6886898.66      2713906.06      6889340.66
      2711471.42      6890752.81
#Sta/Elev= 30
 -1167.1   407.3 -1001.7  409.87  -493.3  377.97  1512.9  371.71  1582.1  376.01
  1636.8  369.31  2057.6   371.6  2091.9  370.26  2114.1  361.33  2161.1  372.13
  2286.6  371.45  2468.9  370.46  2533.5  370.57  2753.5  370.71  3173.7  370.85
    4810  371.75    4979  360.05  5045.1  361.84  5057.4  372.69  5511.3  367.35
  6739.6  375.79  6776.9  377.36  6984.4   387.5  7202.2  397.14    7436  392.46
    7552  388.01  7556.4  388.76  7668.1  395.06  7743.8   398.3  7814.1  400.78
#Mann= 19 ,-1 , 0
 -1167.1     .05       0  1512.9     .12       0  1636.8     .05       0
  2057.6     .12       0  2286.6     .05       0  2468.9     .12       0
  2533.5     .05       0  2753.5     .12       0  3173.7      .1       0
    4810     .04       0  5057.4      .1       0  6739.6     .05       0
  6776.9     .12       0  6984.4     .05       0    7436      .1       0
    7552     .05       0  7556.4     .12       0  7668.1     .05       0
  7743.8      .1       0
Bank Sta=4810,5057.4
XS Rating Curve= 0 ,0
Exp/Cntr=0.3,0.1

Type RM Length L Ch R = 1 ,252867  ,2015,2015,2015
BEGIN DESCRIPTION:
Cedar Creek 98.5
END DESCRIPTION:
XS GIS Cut Line= 3
      2719280.91      6885981.93        2713576.        6888461.
       2711095.2      6889662.46
#Sta/Elev= 30
 -1210.7  426.86 -1018.4  419.47  -931.8  410.56  -669.6  390.78  -395.3  379.45
   698.8  370.78   733.8  370.66    2371  371.97  2410.9  371.15  2439.8  358.87
  2501.8  360.46  2510.1  370.43  2523.6  371.26  2766.4  370.12  2784.4  364.82
  2828.9  369.89  3116.5  366.83 4945.51  369.87    4979  357.67    5021  357.67
  5063.3  371.84  5215.4   371.1  5404.8  371.54  5497.9  371.75  5520.5  361.16
  5531.8  371.35  5658.5  369.98  6013.3  371.04  6807.3  392.08    7766  402.86
#Mann= 12 ,-1 , 0
 -1210.7     .05       0 -1018.4     .12       0  -931.8     .05       0
   698.8     .12       0   733.8      .1       0  3116.5     .05       0
 4945.51     .04       0  5063.3      .1       0  5215.4     .05       0
  5404.8      .1       0  5658.5     .12       0  6013.3     .05       0
Bank Sta=4945.51,5063.3
XS Rating Curve= 0 ,0
Exp/Cntr=0.3,0.1

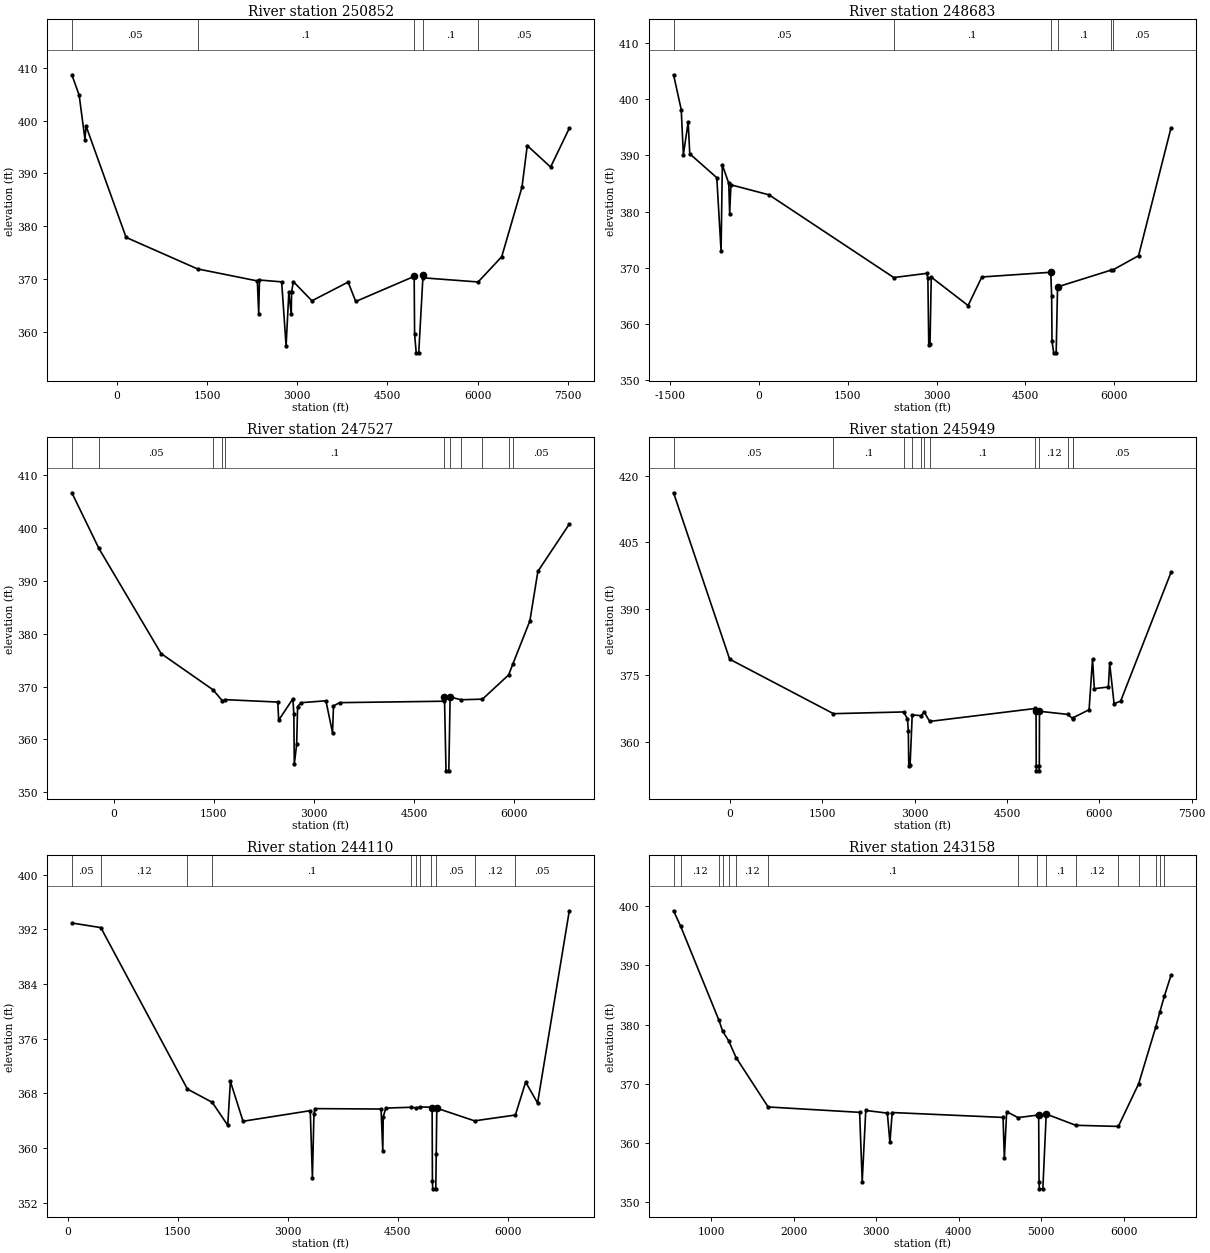
Type RM Length L Ch R = 1 ,250852  ,2169,2169,2169
BEGIN DESCRIPTION:
Cedar Creek 98.0
END DESCRIPTION:
XS GIS Cut Line= 3
      2718331.18      6885144.42      2713126.31      6887585.79
       2710940.7      6888851.01
#Sta/Elev= 30
    -749  408.65  -627.4  404.79  -530.6  396.41  -513.3  398.97   153.2   377.9
  1341.4  371.94  2336.2  369.67    2359  363.39  2371.5  369.84  2740.7  369.49
  2814.7  357.41  2860.3  367.53  2900.4  363.33    2906  367.58  2934.8  369.54
  3244.1  365.91  3846.4  369.45  3973.1  365.78  4945.1  370.53    4952  359.59
    4979  356.07    5021  356.07  5092.8  370.87  5099.4  370.25  6008.7  369.47
  6400.9  374.24  6738.1   387.4    6826  395.26  7214.5   391.2  7525.4  398.54
#Mann= 5 ,-1 , 0
    -749     .05       0  1341.4      .1       0  4945.1     .04       0
  5099.4      .1       0  6008.7     .05       0
Bank Sta=4945.1,5092.8
XS Rating Curve= 0 ,0
Exp/Cntr=0.3,0.1

Type RM Length L Ch R = 1 ,248683  ,1156,1156,1156
BEGIN DESCRIPTION:
Cedar Creek 97.0
END DESCRIPTION:
XS GIS Cut Line= 3
      2718125.01      6883099.67      2712719.81      6886603.17
      2711175.99      6887811.01
#Sta/Elev= 30
   -1441  404.32 -1311.1  398.13 -1275.3  390.09 -1194.1  395.91   -1167  390.26
  -710.8  386.02  -638.3  372.99  -617.2  388.29  -508.4  385.02  -493.2  379.64
  -472.1  384.75   171.4  382.97  2278.3  368.26    2833     369  2854.2  368.21
  2869.3  356.29  2890.4   356.4  2911.5  368.33  3533.9  363.28  3765.5  368.36
  4929.7   369.2  4944.8  364.92  4950.8  356.95    4979  354.87    5021  354.87
 5044.54   366.6  5941.8  369.56  5974.5  369.59  6412.5  372.14  6960.5  394.87
#Mann= 6 ,-1 , 0
   -1441     .05       0  2278.3      .1       0  4929.7     .04       0
 5044.54      .1       0  5941.8     .12       0  5974.5     .05       0
Bank Sta=4929.7,5044.54
XS Rating Curve= 0 ,0
Exp/Cntr=0.3,0.1

Type RM Length L Ch R = 1 ,247527  ,1578,1578,1578
BEGIN DESCRIPTION:
Cedar Creek 96.0
END DESCRIPTION:
XS GIS Cut Line= 3
      2716026.02      6882410.98      2711867.86      6886204.95
      2710565.28      6887486.33
#Sta/Elev= 30
  -628.9  406.66  -223.9  396.14   709.2  376.24  1486.9  369.39  1628.4  367.29
  1663.8  367.53  2457.6  367.07  2471.2  363.64    2684  367.69  2698.2  364.83
    2705  355.28  2740.7  359.09  2754.9   366.2  2804.3  366.95  3179.2  367.31
  3278.5  361.26  3292.7  366.33  3384.6  366.96  4948.7  367.23  4956.1  368.04
    4979  354.06    5021  354.06    5041  368.01  5207.7  367.51  5525.6  367.62
    5918  372.21  5981.7  374.29  6236.1  382.43  6356.2  391.79  6827.2  400.74
#Mann= 11 ,-1 , 0
  -628.9     .12       0  -223.9     .05       0  1486.9      .1       0
  1628.4     .12       0  1663.8      .1       0  4948.7     .04       0
    5041      .1       0  5207.7     .12       0  5525.6     .05       0
    5918     .12       0  5981.7     .05       0
Bank Sta=4956.1,5041
XS Rating Curve= 0 ,0
Exp/Cntr=0.3,0.1

Type RM Length L Ch R = 1 ,245949  ,1839,1839,1839
BEGIN DESCRIPTION:
Cedar Creek 94.0
END DESCRIPTION:
XS GIS Cut Line= 3
      2715664.46      6881392.13        2711276.        6885361.
      2709942.21      6887065.77
#Sta/Elev= 30
  -917.1  416.23    -5.5  378.62  1680.5  366.31  2818.8   366.7    2883  365.18
  2896.8  362.47  2904.2  354.59  2925.2  354.62  2960.2  366.04  3102.4  365.86
  3153.5  366.66  3244.6  364.56  4957.6  367.48  4971.8  366.96    4975  354.59
    4979  353.39    5021  353.39    5025  354.59  5027.9  366.85  5484.3  366.15
  5567.9   365.2  5574.3   365.4  5833.6   367.2  5889.7  378.66  5918.6  371.96
  6146.5  372.34    6168  377.69  6239.6  368.58  6345.7  369.13  7164.4  398.24
#Mann= 12 ,-1 , 0
  -917.1     .05       0  1680.5      .1       0  2818.8     .12       0
  2960.2     .05       0  3102.4     .12       0  3153.5     .05       0
  3244.6      .1       0  4957.6     .04       0  5027.9     .12       0
  5484.3     .05       0  5567.9     .12       0  5574.3     .05       0
Bank Sta=4971.8,5027.9
XS Rating Curve= 0 ,0
Exp/Cntr=0.3,0.1

Type RM Length L Ch R = 1 ,244110  ,952,952,952
BEGIN DESCRIPTION:
Cedar Creek 92.0
END DESCRIPTION:
XS GIS Cut Line= 3
      2714794.42      6881379.89        2710776.        6884261.
      2709575.97      6885661.04
#Sta/Elev= 30
    54.5  392.91   449.7  392.24  1631.7  368.61  1970.1  366.67  2181.7  363.31
  2218.2  369.73  2390.5   363.9  3307.9  365.45  3337.3  355.62  3358.2  364.97
    3373  365.75  4274.4  365.69  4297.7  359.48  4303.9  364.57  4339.5  365.83
    4681 365.945  4757.3  365.85  4799.1     366  4956.1  365.95  4970.8  365.91
    4975  355.21    4979  354.01    5021  354.01    5027  359.11  5034.7  365.81
  5549.7  363.96  6107.1  364.81  6247.5  369.63    6410  366.57    6843   394.7
#Mann= 11 ,-1 , 0
    54.5     .05       0   449.7     .12       0  1631.7     .05       0
  1970.1      .1       0    4681     .12       0  4757.3      .1       0
  4799.1     .05       0  4956.1     .04       0    5027     .05       0
  5549.7     .12       0  6107.1     .05       0
Bank Sta=4970.8,5034.7
XS Rating Curve= 0 ,0
Exp/Cntr=0.3,0.1

Type RM Length L Ch R = 1 ,243158  ,1087,1087,1087
BEGIN DESCRIPTION:
Cedar Creek 91.0
END DESCRIPTION:
XS GIS Cut Line= 3
      2713969.77      6881455.85        2710126.        6883711.
      2708607.01      6884128.11
#Sta/Elev= 30
   543.3  399.24   628.7  396.65  1094.4  380.69  1138.9  378.86  1210.8  377.27
  1301.1  374.41  1690.2  366.05  2799.5  365.14  2830.9   353.4  2873.9  365.46
  3135.6  365.01    3167  360.05  3194.3  365.11  4538.6  364.28  4554.3  357.38
  4582.4  365.26  4719.3  364.25  4949.6  364.66  4970.5  364.74    4975   353.4
    4979   352.2    5021   352.2    5062  364.85  5420.6  362.95  5936.6  362.76
  6183.2  369.99  6389.8  379.55  6438.4  382.05  6493.2  384.74    6575  388.33
#Mann= 16 ,-1 , 0
   543.3     .05       0   628.7     .12       0  1094.4      .1       0
  1138.9     .12       0  1210.8      .1       0  1301.1     .12       0
  1690.2      .1       0  4719.3     .12       0  4949.6     .04       0
    5062      .1       0  5420.6     .12       0  5936.6     .05       0
  6183.2     .12       0  6389.8      .1       0  6438.4     .12       0
  6493.2     .05       0
Bank Sta=4970.5,5062
XS Rating Curve= 0 ,0
Exp/Cntr=0.3,0.1