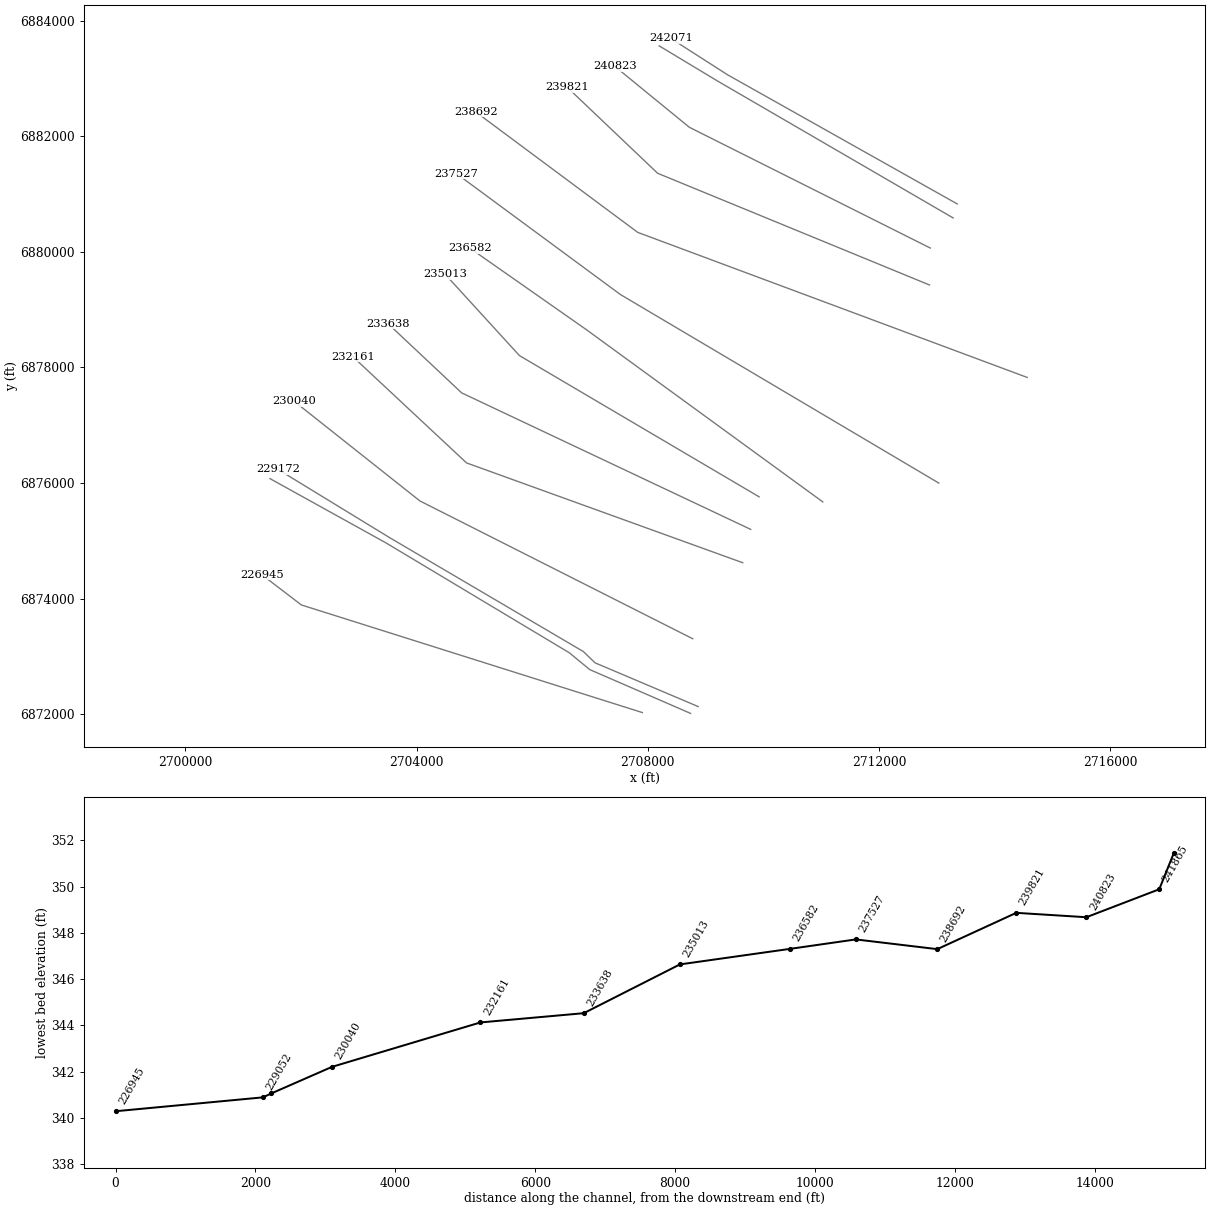
HEC-RAS study Cedar Creek.prj: Cedar Creek Base Level Engineering

--- Cedar Creek.g01 (geometry) --- (continued)

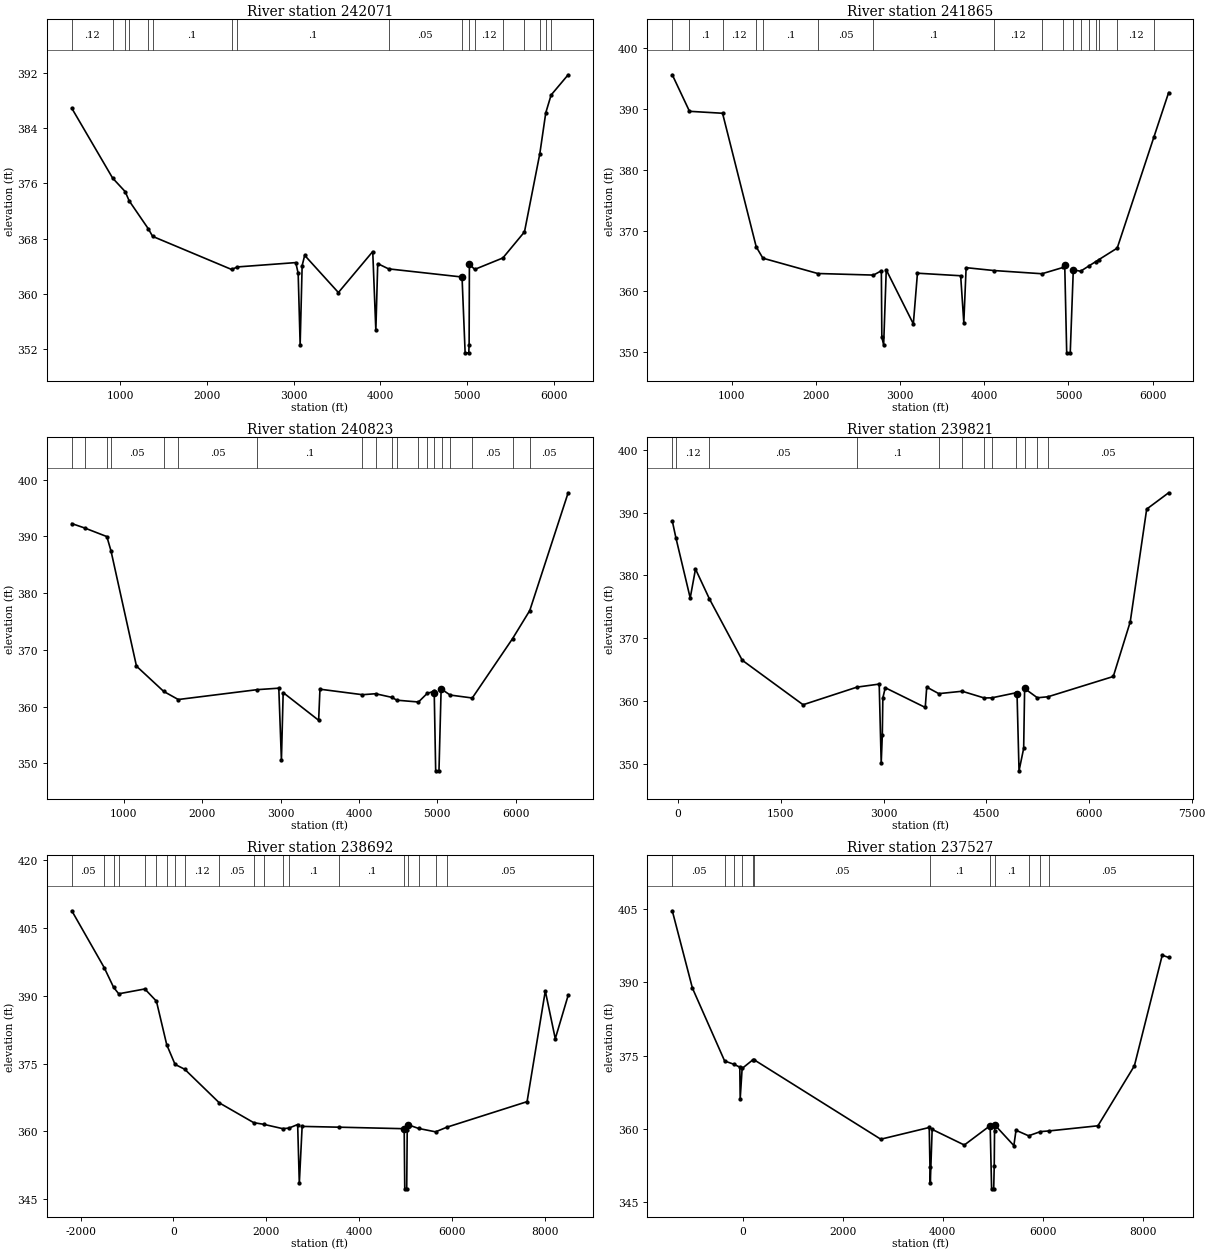
Type RM Length L Ch R = 1 ,242071  ,206,206,206
BEGIN DESCRIPTION:
Cedar Creek 90.0
END DESCRIPTION:
XS GIS Cut Line= 3
      2713352.38      6880828.87      2709378.61       6883063.3
      2708395.78      6883693.46
#Sta/Elev= 30
   441.1  386.89     912  376.77  1056.6  374.81  1103.6  373.46  1324.3  369.41
  1373.6  368.32  2285.2  363.52  2351.3  363.89  3025.2  364.52  3052.7  362.96
  3075.6  352.64  3098.6  364.08  3127.8  365.57  3516.7  360.18  3913.1  366.12
  3948.9  354.69  3970.6  364.37  4095.8  363.61 4943.35  362.43    4979  351.44
    5021  351.44    5025  352.64  5028.2  364.31    5089  363.53  5414.2  365.19
  5663.7  368.97  5840.7  380.31  5909.5  386.24  5971.1  388.81  6167.5  391.74
#Mann= 17 ,-1 , 0
   441.1     .12       0     912      .1       0  1056.6     .12       0
  1103.6      .1       0  1324.3     .12       0  1373.6      .1       0
  2285.2     .05       0  2351.3      .1       0  4095.8     .05       0
 4943.35     .04       0  5028.2      .1       0    5089     .12       0
  5414.2     .05       0  5663.7     .12       0  5840.7     .05       0
  5909.5     .12       0  5971.1     .05       0
Bank Sta=4943.35,5028.2
XS Rating Curve= 0 ,0
Exp/Cntr=0.3,0.1

Type RM Length L Ch R = 1 ,241865  ,1042,1042,1042
BEGIN DESCRIPTION:
Cedar Creek 89.0
END DESCRIPTION:
XS GIS Cut Line= 3
      2713282.97       6880585.8      2709215.07      6882949.74
      2708196.11      6883563.26
#Sta/Elev= 30
   295.1  395.63   499.6  389.62   892.1   389.3  1292.1  367.32  1371.1  365.46
  2022.7  362.94  2684.5  362.68  2777.9  363.39  2783.7  352.47  2805.2  351.19
  2836.1  363.54  3157.8  354.65  3206.6  362.99  3719.8  362.57  3757.1  354.86
  3784.5   363.9  4113.1  363.43  4685.3   362.9  4934.1  363.93  4955.6  364.36
    4979  349.89    5021  349.89  5057.3  363.56  5143.1  363.31  5242.2  364.18
  5325.6  364.91  5359.5  365.21  5578.9  367.12    6016  385.45  6189.4   392.7
#Mann= 17 ,-1 , 0
   295.1     .12       0   499.6      .1       0   892.1     .12       0
  1292.1     .05       0  1371.1      .1       0  2022.7     .05       0
  2684.5      .1       0  4113.1     .12       0  4685.3      .1       0
  4934.1     .04       0  5057.3      .1       0  5143.1     .12       0
  5242.2      .1       0  5325.6     .12       0  5359.5     .05       0
  5578.9     .12       0    6016     .05       0
Bank Sta=4955.6,5057.3
XS Rating Curve= 0 ,0
Exp/Cntr=0.3,0.1

Type RM Length L Ch R = 1 ,240823  ,1002,1002,1002
BEGIN DESCRIPTION:
Cedar Creek 88.0
END DESCRIPTION:
XS GIS Cut Line= 3
      2712886.85      6880065.24      2708718.14      6882154.83
      2707425.97      6883211.02
#Sta/Elev= 30
   336.9  392.26   503.9  391.47   784.1  389.97   836.7  387.46  1162.1  367.13
  1509.2  362.68    1695  361.25  2703.9362.9912  2977.7  363.25  3011.1  350.53
  3033.4  362.47  3485.9  357.59  3502.7  363.07  4044.8   362.1  4212.2  362.27
  4423.3  361.62  4482.5361.1355  4759.5360.8122  4871.6  362.34  4954.7  362.69
  4960.6  362.38    4979  348.68    5021  348.68  5048.6  363.18  5055.1  363.07
    5163  362.04  5445.8361.5203  5960.6     372  6179.4  376.94  6668.9  397.69
#Mann= 19 ,-1 , 0
   336.9     .12       0   503.9     .05       0   784.1     .12       0
   836.7     .05       0  1509.2     .12       0    1695     .05       0
  2703.9      .1       0  4044.8     .12       0  4212.2     .05       0
  4423.3     .12       0  4482.5      .1       0  4759.5     .12       0
  4871.6      .1       0  4954.7     .04       0  5055.1     .05       0
    5163     .12       0  5445.8     .05       0  5960.6     .12       0
  6179.4     .05       0
Bank Sta=4960.6,5048.6
XS Rating Curve= 0 ,0
Exp/Cntr=0.3,0.1

Type RM Length L Ch R = 1 ,239821  ,1129,1129,1129
BEGIN DESCRIPTION:
Cedar Creek 87.0
END DESCRIPTION:
XS GIS Cut Line= 3
      2712872.92      6879426.37      2708169.86      6881358.83
      2706602.14      6882849.95
#Sta/Elev= 30
   -84.6  388.69   -32.5  386.03   177.2  376.41   254.5  381.02   458.8  376.24
   937.1  366.49  1825.7   359.4  2613.8  362.21    2937  362.69  2966.4  350.07
  2982.5  354.61  2990.4   360.5  3025.7  362.11  3609.5  358.97  3631.1  362.21
  3807.6  361.17  4148.6  361.55  4470.5  360.48    4581   360.5  4936.9  361.31
  4950.1  361.05    4979  348.87  5046.7  352.45  5060.7  361.99  5246.6  360.51
  5401.1  360.67  6355.4   363.9  6602.9  372.61  6843.2  390.57  7163.6  393.17
#Mann= 12 ,-1 , 0
   -84.6     .05       0   -32.5     .12       0   458.8     .05       0
  2613.8      .1       0  3807.6     .12       0  4148.6     .05       0
  4470.5     .12       0    4581      .1       0  4936.9     .04       0
  5060.7      .1       0  5246.6     .12       0  5401.1     .05       0
Bank Sta=4950.1,5060.7
XS Rating Curve= 0 ,0
Exp/Cntr=0.3,0.1

Type RM Length L Ch R = 1 ,238692  ,1165,1165,1165
BEGIN DESCRIPTION:
Cedar Creek 86.0
END DESCRIPTION:
XS GIS Cut Line= 3
      2714562.41      6877827.25      2707825.81      6880336.08
      2705019.86      6882422.09
#Sta/Elev= 30
 -2188.6  408.76 -1491.1   396.2 -1288.7  391.84 -1178.4  390.41  -616.5  391.48
  -366.9  388.78  -144.8  379.15    34.1  374.81     242  373.73   988.9  366.29
    1727  361.93  1938.3  361.57  2348.5  360.61  2484.7  360.72  2673.5  361.52
  2709.2   348.5  2769.9   361.1  3552.8  360.93  4966.8  360.59    4979   347.3
    5021   347.3  5032.2  360.41    5053  361.46  5276.2  360.65  5642.2   359.9
  5887.1  360.93  7612.4  366.57  8004.6  391.04  8219.4  380.48  8496.4  390.06
#Mann= 20 ,-1 , 0
 -2188.6     .05       0 -1491.1     .05       0 -1288.7      .1       0
 -1178.4     .12       0  -616.5      .1       0  -366.9     .12       0
  -144.8      .1       0    34.1     .12       0     242     .12       0
   988.9     .05       0    1727     .12       0  1938.3     .05       0
  2348.5     .05       0  2484.7      .1       0  3552.8      .1       0
  4966.8     .04       0    5053      .1       0  5276.2     .05       0
  5642.2     .12       0  5887.1     .05       0
Bank Sta=4966.8,5053
XS Rating Curve= 0 ,0
Exp/Cntr=0.3,0.1

Type RM Length L Ch R = 1 ,237527  ,945,945,945
BEGIN DESCRIPTION:
Cedar Creek 85.0
END DESCRIPTION:
XS GIS Cut Line= 3
      2713034.61      6875998.99        2707526.        6879261.
      2704689.66       6881352.7
#Sta/Elev= 30
 -1406.9  404.65 -1004.1  388.82    -360   373.9  -166.4  373.19   -56.6  372.63
   -48.8  366.15    -9.9  372.37   202.9  374.12   223.5  374.18  2762.7  357.88
  3731.7  360.28  3746.6  352.11  3753.1  348.92  3790.2  359.89  4433.6  356.69
  4950.2  360.66    4979  347.72    5021  347.72  5031.7  352.43  5037.9  359.58
  5044.8  360.79  5424.3  356.57  5467.3  359.71  5719.1  358.58  5956.6  359.44
  6121.7  359.57  7105.4  360.63  7834.2   372.9  8391.7  395.56  8519.3  395.09
#Mann= 12 ,-1 , 0
 -1406.9     .05       0    -360      .1       0  -166.4     .12       0
    -9.9     .05       0   202.9     .12       0   223.5     .05       0
  3746.6      .1       0  4950.2     .04       0  5044.8      .1       0
  5719.1     .12       0  5956.6      .1       0  6121.7     .05       0
Bank Sta=4950.2,5044.8
XS Rating Curve= 0 ,0
Exp/Cntr=0.3,0.1

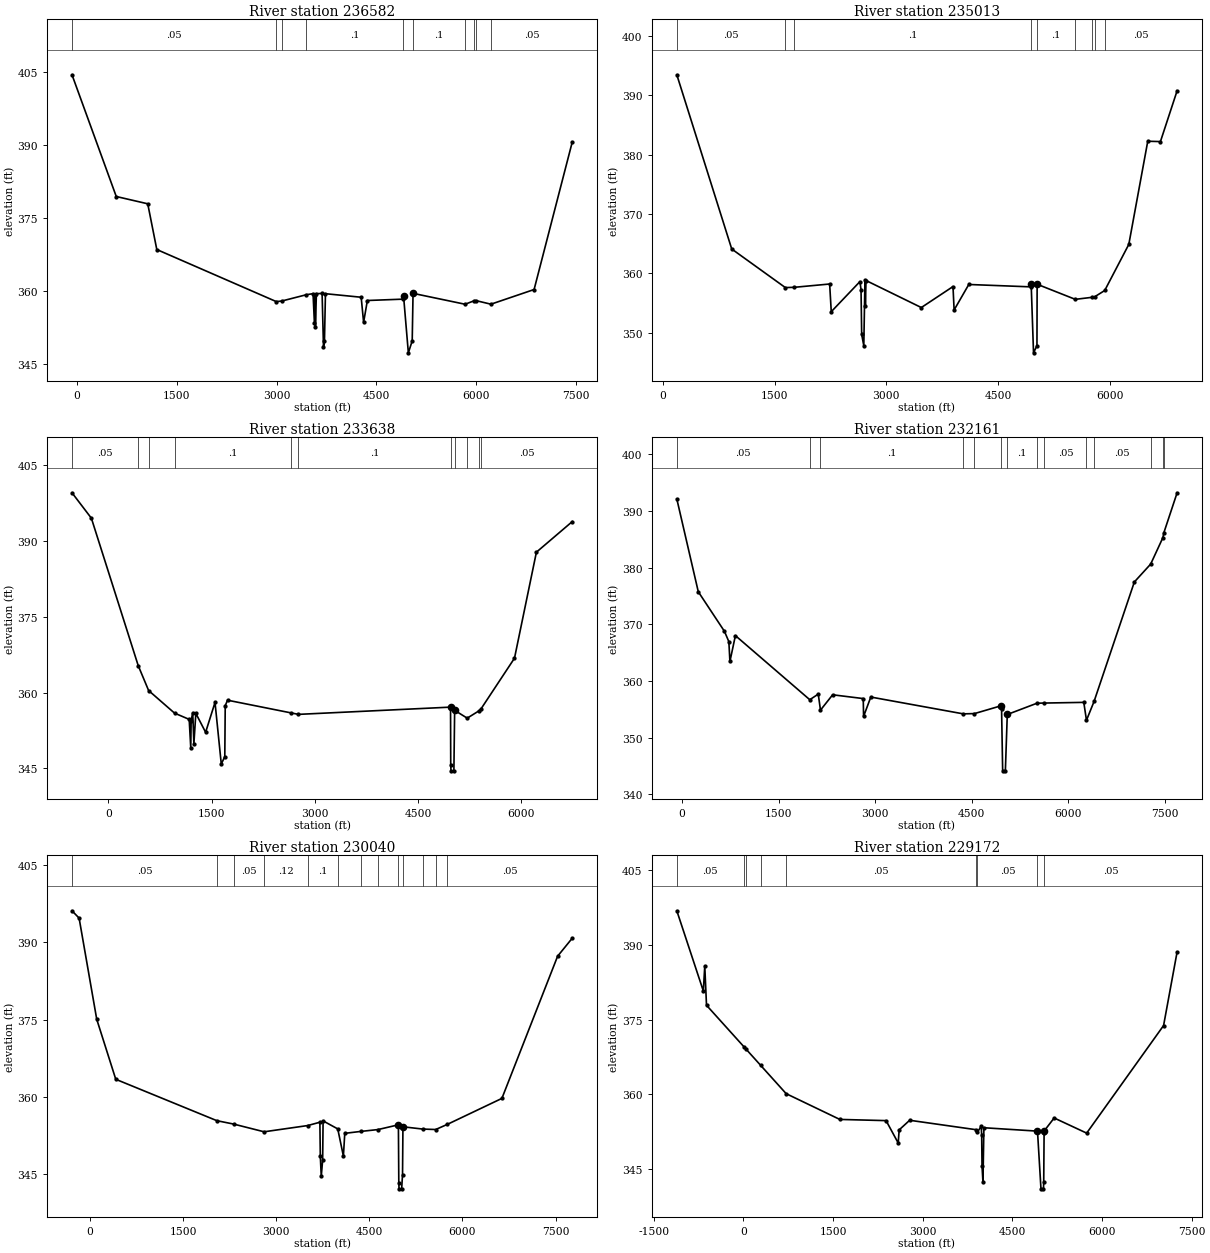
Type RM Length L Ch R = 1 ,236582  ,1569,1569,1569
BEGIN DESCRIPTION:
Cedar Creek 84.0
END DESCRIPTION:
XS GIS Cut Line= 3
      2711027.22      6875673.48        2706926.        6878661.
      2704925.99        6880061.
#Sta/Elev= 30
   -73.7  404.53   591.3  379.48  1064.2  377.98  1200.2  368.57  2994.3  357.86
    3074  357.96  3447.2  359.27  3547.4  359.49  3568.2  353.35  3576.7  359.24
  3582.9   352.7  3597.6  359.49  3683.4  359.53  3704.2  348.51  3718.9   349.8
  3733.6  359.48  4270.3  358.75  4306.9  353.59  4363.3  358.08    4901  358.36
  4907.2  358.95    4979  347.31  5036.9  349.78  5049.5  359.55  5831.3  357.31
    5972  358.05  5996.4  358.05  6219.7  357.32  6867.9  360.34  7441.6  390.72
#Mann= 10 ,-1 , 0
   -73.7     .05       0  2994.3     .12       0    3074     .05       0
  3447.2      .1       0    4901     .04       0  5049.5      .1       0
  5831.3     .12       0    5972      .1       0  5996.4     .12       0
  6219.7     .05       0
Bank Sta=4907.2,5049.5
XS Rating Curve= 0 ,0
Exp/Cntr=0.3,0.1

Type RM Length L Ch R = 1 ,235013  ,1375,1375,1375
BEGIN DESCRIPTION:
Cedar Creek 83.0
END DESCRIPTION:
XS GIS Cut Line= 3
      2709925.96      6875761.02      2705778.64      6878204.69
      2704491.81      6879613.69
#Sta/Elev= 30
   186.3  393.42   924.1  364.11  1644.3  357.62  1760.9  357.66  2239.8  358.22
  2261.3  353.56  2646.9  358.63  2661.4  357.27  2670.1  349.73  2698.5  347.84
  2714.1  358.91  2719.9  354.53  2728.1  358.81  3471.4  354.26    3897  357.79
    3912  353.85  4109.3  358.14  4941.4  357.74  4947.2  358.28    4979  346.64
    5025  347.84  5027.5  358.18  5540.3  355.64  5771.3  355.99  5799.5  356.06
  5935.7  357.13  6259.1  364.88  6513.8  382.24    6684  382.18  6908.2  390.73
#Mann= 9 ,-1 , 0
   186.3     .05       0  1644.3     .12       0  1760.9      .1       0
  4941.4    .045       0    5025      .1       0  5540.3     .12       0
  5771.3     .05       0  5799.5     .12       0  5935.7     .05       0
Bank Sta=4947.2,5027.5
XS Rating Curve= 0 ,0
Exp/Cntr=0.3,0.1

Type RM Length L Ch R = 1 ,233638  ,1477,1477,1477
BEGIN DESCRIPTION:
Cedar Creek 82.0
END DESCRIPTION:
XS GIS Cut Line= 3
      2709780.23      6875197.91      2704779.54      6877559.54
      2703510.19      6878752.71
#Sta/Elev= 30
  -530.3  399.48  -248.7  394.46   432.6  365.31   583.5   360.4   959.9  355.94
  1173.3   354.7  1196.1  349.11  1201.6  354.43  1224.4  356.03  1241.6  349.88
  1269.9  355.89  1412.1  352.15  1548.7  358.05  1639.7  345.88  1690.8  347.33
  1697.2   357.4  1730.4  358.49  2654.3  355.98  2761.7  355.69  4972.3  357.12
    4975  345.73    4979  344.53    5021  344.53    5032  356.49  5214.6  354.94
  5384.9  356.38  5411.2  356.69  5901.9  366.79  6220.4  387.74  6742.1  393.79
#Mann= 11 ,-1 , 0
  -530.3     .05       0   432.6     .12       0   583.5     .05       0
   959.9      .1       0  2654.3     .12       0  2761.7      .1       0
  4972.3     .04       0    5032     .12       0  5214.6     .05       0
  5384.9     .12       0  5411.2     .05       0
Bank Sta=4972.3,5032
XS Rating Curve= 0 ,0
Exp/Cntr=0.3,0.1

Type RM Length L Ch R = 1 ,232161  ,2121,2121,2121
BEGIN DESCRIPTION:
Cedar Creek 81.0
END DESCRIPTION:
XS GIS Cut Line= 3
      2709641.32      6874621.53      2704863.67      6876348.22
       2702899.6      6878182.78
#Sta/Elev= 30
   -80.1  392.14   253.3  375.75   659.2  368.77   727.9  366.94   744.3  363.44
   829.4  368.01  1984.2  356.69    2116  357.68  2150.4 354.847  2339.3  357.56
  2814.4  356.89  2819.7  353.74  2931.7  357.16  4368.1  354.19  4541.5  354.24
    4955  355.62  4962.2     355    4979  344.13    5021  344.13 5050.76  354.08
    5512  356.07  5625.7   356.1  6238.6  356.22  6280.3  353.06    6398  356.38
  7023.6  377.48  7277.2  380.64  7467.4  385.32  7481.4  386.16  7687.6  393.23
#Mann= 14 ,-1 , 0
   -80.1     .05       0  1984.2     .12       0  2150.4      .1       0
  4368.1     .12       0  4541.5      .1       0    4955     .04       0
 5050.76      .1       0    5512     .12       0  5625.7     .05       0
  6280.3     .12       0    6398     .05       0  7277.2     .12       0
  7467.4     .05       0  7481.4     .12       0
Bank Sta=4955,5050.76
XS Rating Curve= 0 ,0
Exp/Cntr=0.3,0.1

Type RM Length L Ch R = 1 ,230040  ,868,868,868
BEGIN DESCRIPTION:
Cedar Creek 80.0
END DESCRIPTION:
XS GIS Cut Line= 3
      2708776.71      6873306.01      2704056.16      6875690.78
      2701884.39      6877411.89
#Sta/Elev= 30
  -289.9  396.07  -175.3  394.65   108.9  375.04   415.4  363.43  2044.3  355.41
  2312.5  354.76  2804.9  353.26  3507.8  354.47  3703.5  355.11  3710.6  348.51
  3725.8  344.62  3748.1  347.76  3755.4  355.37  3991.5  353.82  4082.4  348.55
  4104.7  352.96    4361  353.33  4638.8  353.69  4968.5  354.61    4975  343.41
    4979  342.21    5021  342.21  5035.2  344.98  5041.6  354.23  5359.3  353.79
  5569.4   353.7  5757.3   354.7    6636  359.73  7533.4  387.27  7769.9  390.77
#Mann= 13 ,-1 , 0
  -289.9     .05       0  2044.3     .12       0  2312.5     .05       0
  2804.9     .12       0  3507.8      .1       0  3991.5     .12       0
    4361      .1       0  4638.8     .12       0  4968.5     .04       0
  5041.6     .12       0  5359.3     .05       0  5569.4     .12       0
  5757.3     .05       0
Bank Sta=4968.5,5041.6
XS Rating Curve= 0 ,0
Exp/Cntr=0.3,0.1

Type RM Length L Ch R = 1 ,229172  ,120,120,120
BEGIN DESCRIPTION:
Cedar Creek 79.5
END DESCRIPTION:
XS GIS Cut Line= 5
      2708870.67      6872133.09      2707085.96      6872890.03
      2706884.57      6873084.48       2703530.4       6875056.7
      2701601.03      6876235.98
#Sta/Elev= 30
 -1113.9  396.86    -670  380.75  -646.3  385.79  -617.2   377.9     5.2  369.62
    45.5  369.08   288.2  365.85   715.6  360.16  1613.4  354.99  2387.4  354.75
  2590.5  350.25  2606.2  352.89  2781.9  354.82  3886.2  352.94  3916.5  352.42
  3979.9  353.67  3986.9  351.82  3992.7  345.68  4008.4  342.36    4024  353.32
 4920.89  352.64    4979  341.06    5021  341.06    5025  342.36  5031.4  352.36
  5037.3  352.75  5199.7  355.28  5743.6  352.24  7030.5  373.83  7256.9  388.61
#Mann= 9 ,-1 , 0
 -1113.9     .05       0     5.2     .12       0    45.5     .05       0
   288.2     .12       0   715.6     .05       0  3886.2     .12       0
  3916.5     .05       0 4920.89     .04       0  5037.3     .05       0
Bank Sta=4920.89,5037.3
XS Rating Curve= 0 ,0
Exp/Cntr=0.3,0.1

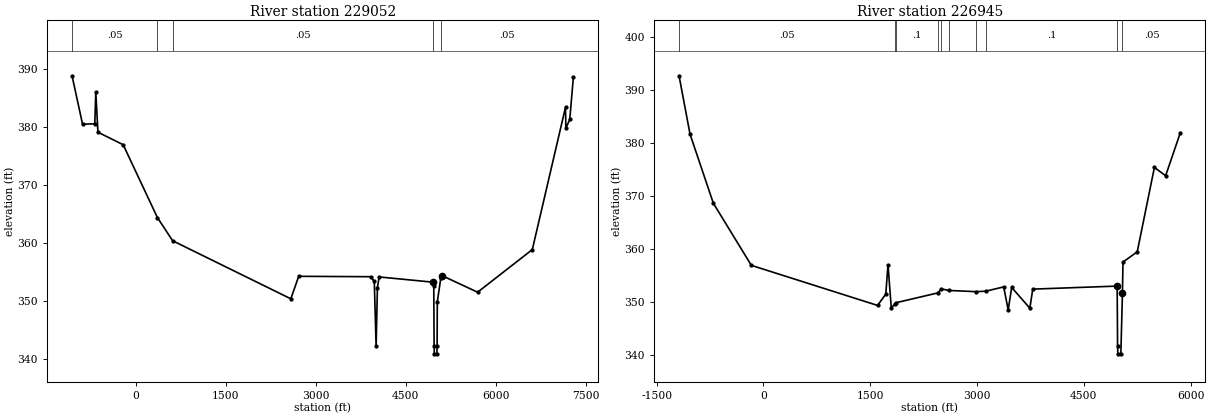
Type RM Length L Ch R = 1 ,229052  ,2107,2107,2107
BEGIN DESCRIPTION:
Cedar Creek 79.0
END DESCRIPTION:
XS GIS Cut Line= 5
      2708738.73      6872015.03      2706995.68      6872771.98
      2706641.51      6873063.64        2703476.        6874961.
      2701462.36      6876076.75
#Sta/Elev= 30
 -1057.3  388.84  -882.2  380.49  -678.2  380.56  -661.8  386.01  -625.9  379.11
  -205.4  376.95   365.2  364.38   618.9  360.39  2587.5  350.38    2719  354.26
  3919.8  354.19  3978.1  353.39  4008.7  342.19  4030.1  352.31  4059.7  354.15
  4963.2  353.24  4969.1  352.64    4975  342.19    4979  340.89    5021  340.89
    5025  342.19  5027.9  349.86  5087.4  354.01  5103.4  354.39  5699.9  351.52
  6611.1  358.87    7164  383.42  7169.7  379.81    7235  381.31  7294.5  388.57
#Mann= 5 ,-1 , 0
 -1057.3     .05       0   365.2     .12       0   618.9     .05       0
  4963.2     .04       0  5087.4     .05       0
Bank Sta=4963.2,5103.4
XS Rating Curve= 0 ,0
Exp/Cntr=0.3,0.1

Type RM Length L Ch R = 1 ,226945  ,1652,1652,1652
BEGIN DESCRIPTION:
Cedar Creek 78.0
END DESCRIPTION:
XS GIS Cut Line= 3
      2707905.41      6872028.92       2702005.4      6873891.16
      2701325.99      6874411.01
#Sta/Elev= 30
 -1185.5  392.62 -1031.6  381.65  -703.7  368.63  -169.7  356.94  1603.2   349.4
  1718.6  351.53    1750  357.05  1796.1   348.9  1843.5  349.65  1868.6  349.93
  2448.2  351.75  2501.3  352.51  2605.2  352.22  2987.3  351.99  3123.7  352.08
  3375.4  352.89  3438.3  348.56  3487.4  352.79  3742.4  348.88  3783.7  352.47
  4969.3  353.04    4975  341.69    4979  340.29    5021  340.29  5043.5  351.78
    5051  357.56  5251.2  359.49  5492.3  375.37  5650.2  373.81  5856.9  381.92
#Mann= 10 ,-1 , 0
 -1185.5     .05       0  1843.5     .12       0  1868.6      .1       0
  2448.2     .05       0  2501.3      .1       0  2605.2     .05       0
  2987.3     .12       0  3123.7      .1       0  4969.3     .04       0
  5043.5     .05       0
Bank Sta=4969.3,5043.5
XS Rating Curve= 0 ,0
Exp/Cntr=0.3,0.1