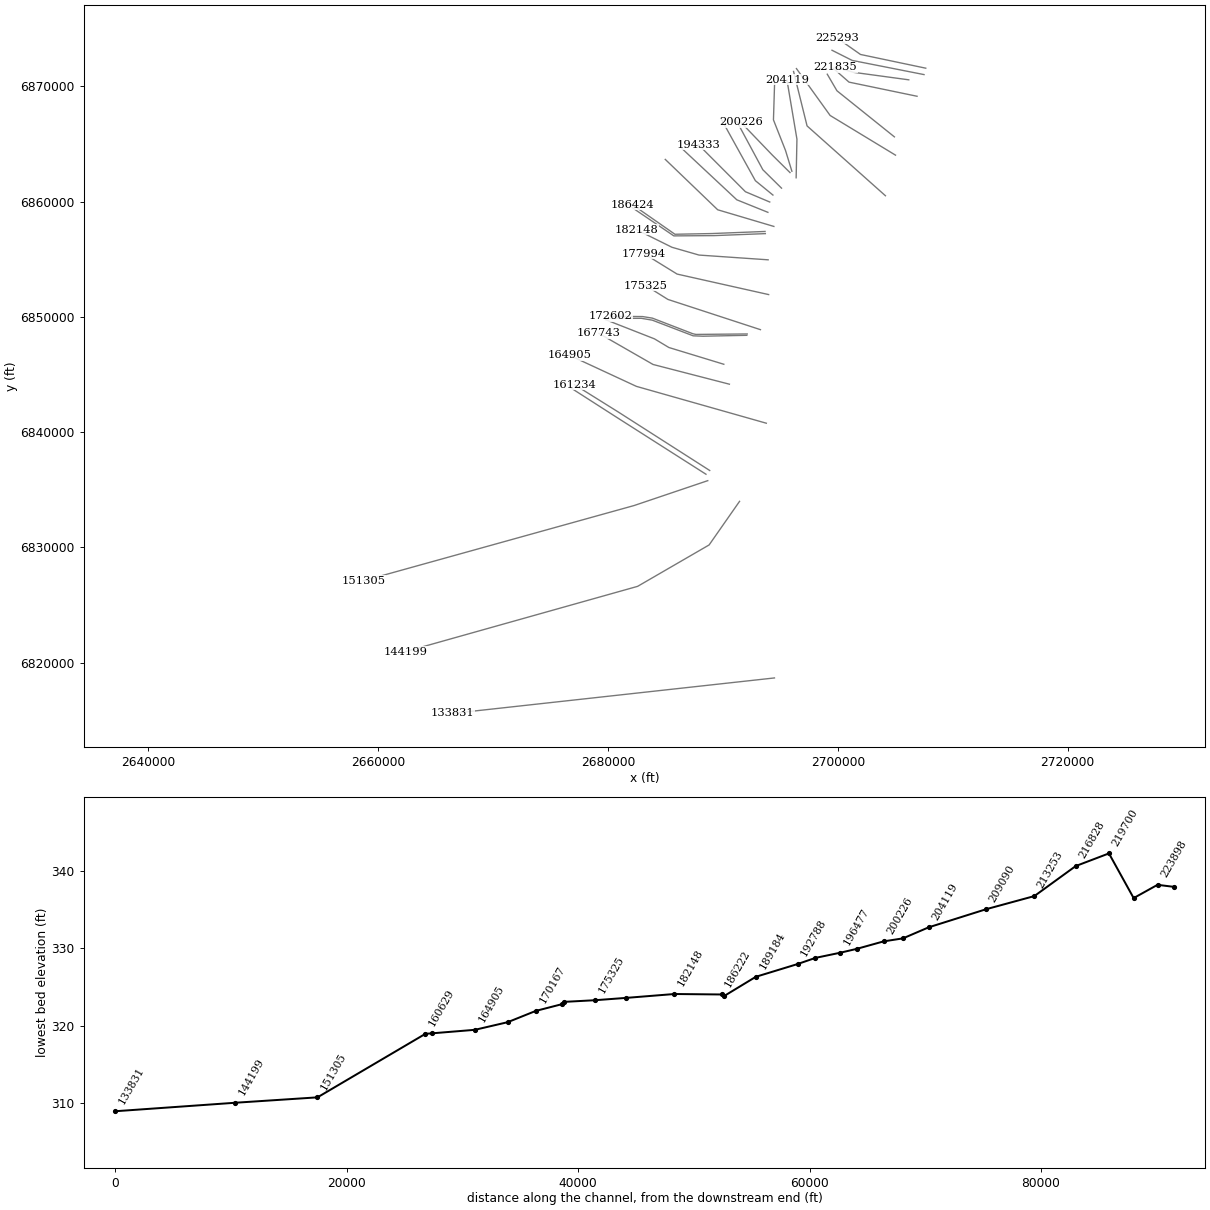
HEC-RAS study Cedar Creek.prj: Cedar Creek Base Level Engineering

--- Cedar Creek.g01 (geometry) --- (continued)

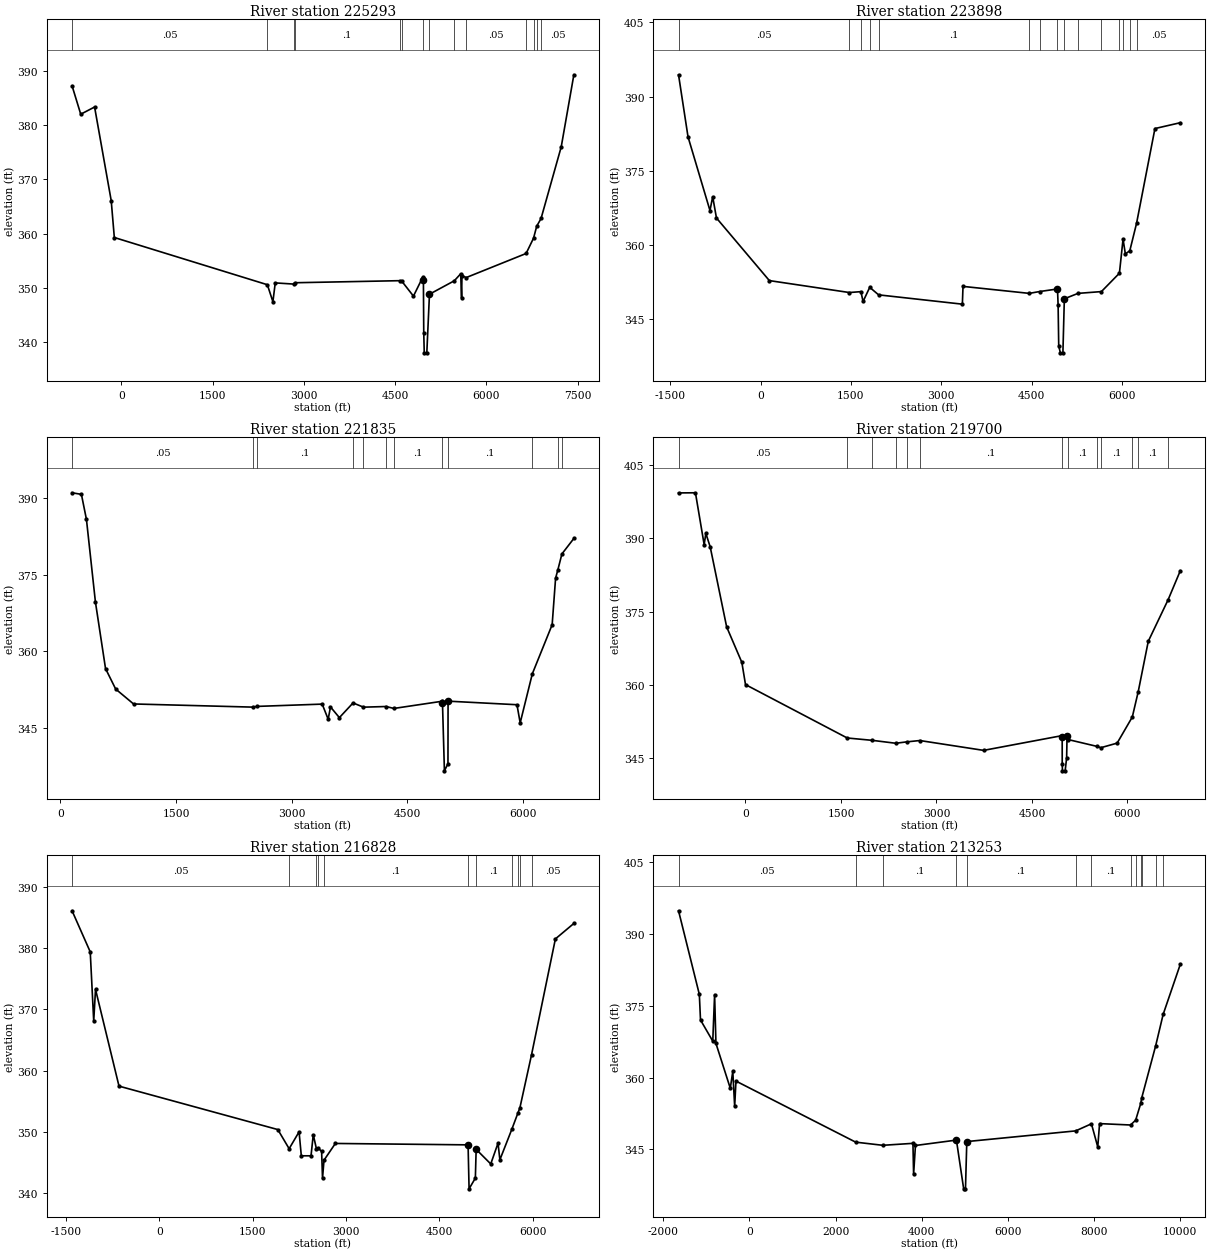
Type RM Length L Ch R = 1 ,225293  ,1395,1395,1395
BEGIN DESCRIPTION:
Cedar Creek 77.0
END DESCRIPTION:
XS GIS Cut Line= 3
      2707655.42      6871570.58        2701976.        6872761.
      2699976.04      6874160.98
#Sta/Elev= 30
  -807.3  387.27  -664.9  382.03  -437.3  383.36  -164.2  366.08  -113.1  359.27
  2401.1350.5545  2492.3  347.42  2530.9  350.89  2839.9  350.67    2856  350.92
  4572.2   351.3  4609.6  351.21  4801.4  348.45  4954.7  351.95  4964.9  351.49
  4970.6   341.6    4979  337.98    5021  337.98 5064.43   348.8  5472.4  351.28
  5577.5  352.57  5592.3  348.11  5598.4  352.23  5669.4  351.88    6652  356.32
  6774.9  359.16  6826.6  361.36  6897.8  362.78  7229.3  376.01  7436.8  389.31
#Mann= 14 ,-1 , 0
  -807.3     .05       0  2401.1      .1       0  2839.9     .12       0
    2856      .1       0  4572.2     .12       0  4609.6      .1       0
  4954.7     .04       0 5064.43      .1       0  5472.4     .12       0
  5669.4     .05       0    6652     .12       0  6774.9      .1       0
  6826.6     .12       0  6897.8     .05       0
Bank Sta=4964.9,5064.43
XS Rating Curve= 0 ,0
Exp/Cntr=0.3,0.1

Type RM Length L Ch R = 1 ,223898  ,2063,2063,2063
BEGIN DESCRIPTION:
Cedar Creek 76.0
END DESCRIPTION:
XS GIS Cut Line= 3
      2707502.61      6871015.04      2701252.82      6872244.56
      2699495.83      6873126.07
#Sta/Elev= 30
 -1363.8   394.4 -1206.3  381.87  -841.6  366.98  -796.5  369.77  -733.7  365.47
   144.9  352.83  1474.3  350.42  1665.5   350.6  1701.6  348.61  1812.1  351.47
  1959.9  349.95  3350.9  348.07  3361.7  351.66    4462  350.25  4633.5  350.62
  4931.2  351.14  4941.4  347.88  4951.6  339.64    4979  338.24    5021  338.24
 5044.89  349.16  5272.1  350.25  5660.5  350.61  5959.6  354.32  6020.1  361.21
  6058.3  358.22  6132.2  358.86  6244.3  364.39  6549.7  383.54  6971.5  384.72
#Mann= 15 ,-1 , 0
 -1363.8     .05       0  1474.3     .12       0  1665.5     .05       0
  1812.1     .12       0  1959.9      .1       0    4462     .12       0
  4633.5      .1       0  4931.2     .04       0 5044.89      .1       0
  5272.1     .05       0  5660.5      .1       0  5959.6     .12       0
  6020.1     .05       0  6132.2     .12       0  6244.3     .05       0
Bank Sta=4931.2,5044.89
XS Rating Curve= 0 ,0
Exp/Cntr=0.3,0.1

Type RM Length L Ch R = 1 ,221835  ,2135,2135,2135
BEGIN DESCRIPTION:
Cedar Creek 75.0
END DESCRIPTION:
XS GIS Cut Line= 3
      2706175.99        6870561.        2701376.        6871211.
      2699775.98      6871661.01
#Sta/Elev= 30
   151.4  391.07   272.5  390.76   337.9  385.84   454.1  369.65   585.3  356.58
   716.5  352.57   948.6  349.64  2493.9  349.02  2548.6  349.16  3394.4  349.61
    3472  346.64  3501.7  349.06  3617.2  346.96  3794.4  349.84  3929.8  349.01
  4222.7  349.14  4323.6  348.76  4944.7  350.16  4953.9  349.86    4979  336.52
    5025  337.92  5026.4  350.19  5919.7  349.49  5961.3  345.93  6118.6  355.55
  6375.9  365.19  6420.4  374.31    6449   375.9  6502.3  379.07  6657.3  382.11
#Mann= 12 ,-1 , 0
   151.4     .05       0  2493.9     .12       0  2548.6      .1       0
  3794.4     .12       0  3929.8      .1       0  4222.7     .12       0
  4323.6      .1       0  4944.7     .04       0    5025      .1       0
  6118.6     .12       0    6449     .05       0  6502.3     .12       0
Bank Sta=4953.9,5026.4
XS Rating Curve= 0 ,0
Exp/Cntr=0.3,0.1

Type RM Length L Ch R = 1 ,219700  ,2872,2872,2872
BEGIN DESCRIPTION:
Cedar Creek 74.0
END DESCRIPTION:
XS GIS Cut Line= 3
      2706896.04      6869134.57        2700976.        6870361.
      2699594.44      6871569.54
#Sta/Elev= 30
 -1051.3  399.35  -785.7  399.38  -648.9  388.74  -622.3  391.04  -553.6  388.26
  -295.5  371.85   -56.9  364.57      .6  360.01  1598.7  349.05  1991.1  348.57
  2360.4  347.97  2535.4  348.26  2738.6  348.53  3740.4  346.51  4969.4  349.53
  4974.5  349.17    4975  343.71    4979  342.31    5021  342.31  5044.3  344.97
  5050.9  349.48  5065.2  348.74  5517.5  347.34  5581.9  347.06  5837.8     348
  6075.9353.3616  6168.8  358.56  6326.6   368.9  6639.1  377.45    6830  383.39
#Mann= 13 ,-1 , 0
 -1051.3     .05       0  1598.7     .12       0  1991.1      .1       0
  2360.4     .12       0  2535.4     .05       0  2738.6      .1       0
  4969.4     .04       0  5065.2      .1       0  5517.5     .12       0
  5581.9      .1       0  6075.9     .12       0  6168.8      .1       0
  6639.1     .05       0
Bank Sta=4974.5,5050.9
XS Rating Curve= 0 ,0
Exp/Cntr=0.3,0.1

Type RM Length L Ch R = 1 ,216828  ,3575,3575,3575
BEGIN DESCRIPTION:
Cedar Creek 72.0
END DESCRIPTION:
XS GIS Cut Line= 3
      2704925.98      6865611.01        2699926.        6869611.
      2699084.38      6871047.27
#Sta/Elev= 30
 -1404.1  386.13   -1112  379.41   -1056   368.1 -1027.1  373.28  -649.4  357.46
  1903.9  350.36  2085.9  347.23  2245.7  349.99  2281.7  346.07  2437.8  346.07
  2473.8  349.52    2524  347.25  2549.2  347.37  2608.2  346.78  2622.6  342.39
  2646.4  345.35  2829.1  348.09    4963  347.86    4979  340.67  5080.1  342.43
  5092.8  347.13  5327.3  344.74  5444.6  348.14  5474.2  345.42  5665.7  350.39
  5764.4  353.07  5796.6  353.94  5983.2  362.59  6366.7  381.53  6663.7  384.06
#Mann= 11 ,-1 , 0
 -1404.1     .05       0  2085.9     .12       0    2524      .1       0
  2549.2     .12       0  2646.4      .1       0    4963     .04       0
  5092.8      .1       0  5665.7     .12       0  5764.4     .05       0
  5796.6     .12       0  5983.2     .05       0
Bank Sta=4963,5092.8
XS Rating Curve= 0 ,0
Exp/Cntr=0.3,0.1

Type RM Length L Ch R = 1 ,213253  ,4163,4163,4163
BEGIN DESCRIPTION:
Cedar Creek 71.0
END DESCRIPTION:
XS GIS Cut Line= 3
      2705022.38      6864024.32      2699333.48      6867467.04
      2696400.98      6871536.03
#Sta/Elev= 30
 -1649.5  394.84   -1166  377.39 -1138.8  372.04  -853.7  367.62    -811  377.34
    -780  367.15  -446.4  357.78  -388.2  361.31  -344.6  353.99  -314.5  359.28
  2468.4  346.53  3099.3  345.87  3799.7  346.28  3815.2  339.82  3857.9  345.83
  4810.4  346.96    4979  336.78    5021  336.78  5051.8  346.65    7583  348.88
  7949.1  350.36  8096.3  345.53  8138.1   350.4  8858.1  350.11  8976.7  351.11
  9095.4  354.61  9116.3  355.71  9443.3  366.68  9615.8  373.19 10015.6  383.68
#Mann= 13 ,-1 , 0
 -1649.5     .05       0  2468.4     .12       0  3099.3      .1       0
  4810.4     .04       0  5051.8      .1       0    7583     .12       0
  7949.1      .1       0  8858.1     .12       0  8976.7     .05       0
  9095.4     .12       0  9116.3     .05       0  9443.3     .12       0
  9615.8     .05       0
Bank Sta=4810.4,5051.8
XS Rating Curve= 0 ,0
Exp/Cntr=0.3,0.1

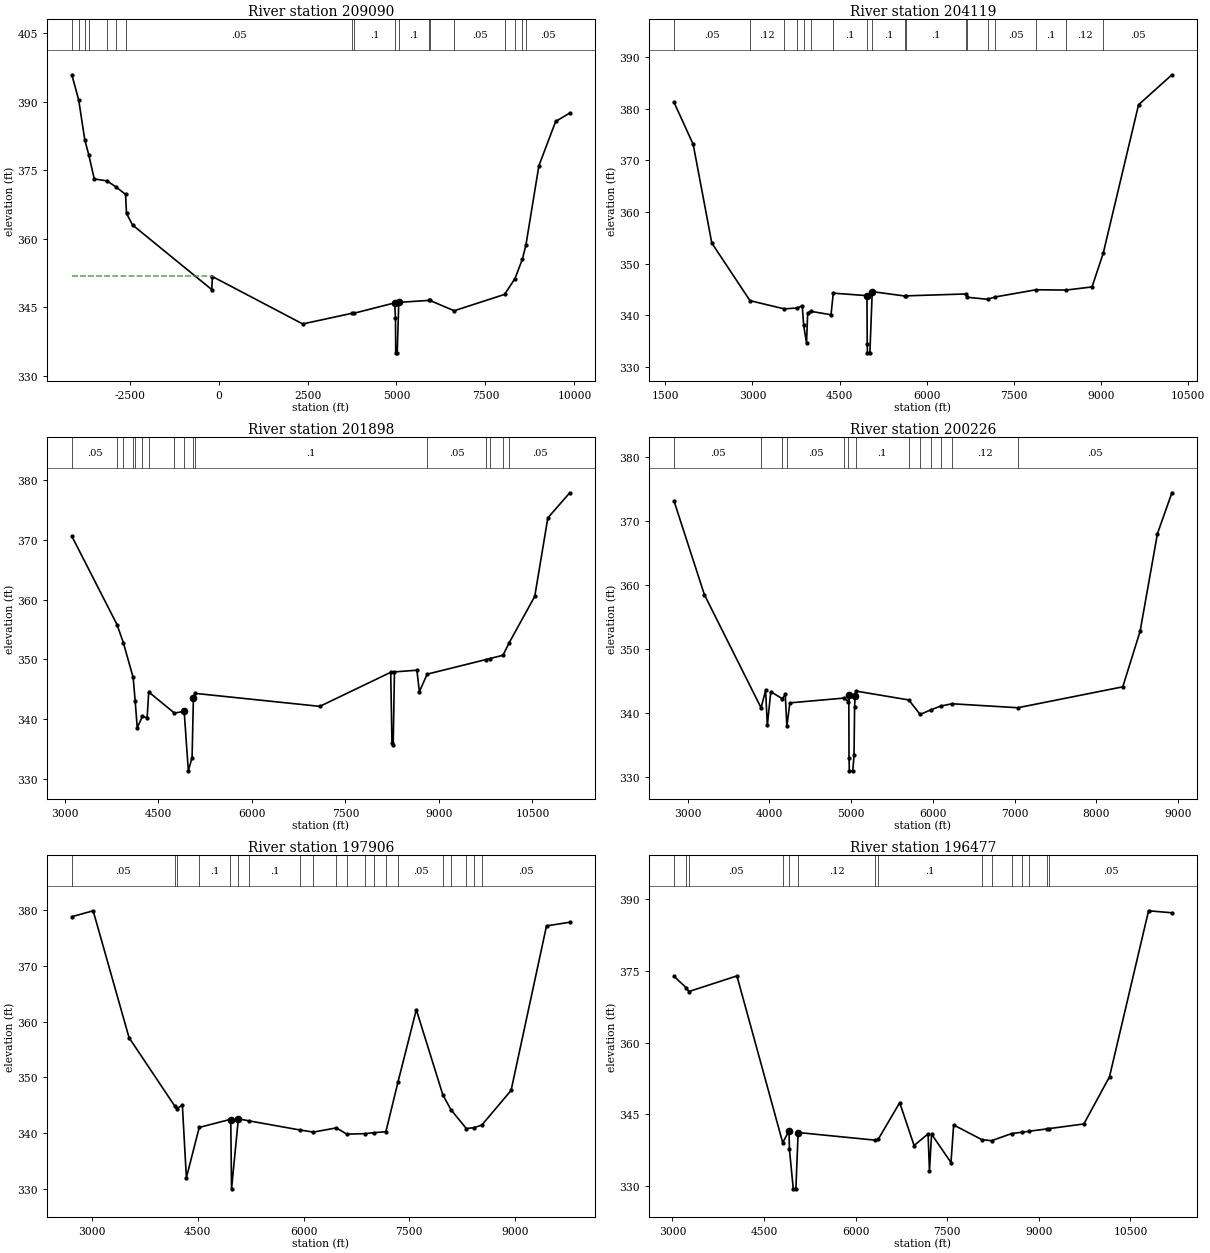
Type RM Length L Ch R = 1 ,209090  ,4971,4971,4971
BEGIN DESCRIPTION:
Cedar Creek 70.0
END DESCRIPTION:
XS GIS Cut Line= 3
      2704144.88      6860502.31        2697326.        6866561.
      2696150.99      6871286.02
#Sta/Elev= 30
 -4121.6  395.91 -3928.9  390.35   -3758  381.63 -3648.2  378.45 -3493.2  373.13
   -3134  372.69   -2880  371.37   -2614  369.75 -2585.9  365.57 -2416.1  363.05
  -191.7  348.92  -170.8  351.77  2364.8   341.4  3749.3  343.73  3805.2  343.74
  4950.3  346.01  4972.1  342.64    4979  335.08    5021  335.08  5064.6  346.12
  5925.4  346.56  5936.7  346.55  6621.8  344.29  8037.3  347.86    8330  351.32
  8538.8  355.58    8639  358.73  9001.1  375.99  9472.3  385.69    9869  387.54
#Mann= 18 ,-1 , 0
 -4121.6     .05       0 -3928.9     .12       0   -3758      .1       0
 -3648.2     .12       0   -3134     .05       0   -2880     .12       0
   -2614     .05       0  3749.3     .12       0  3805.2      .1       0
  4950.3     .04       0  5064.6      .1       0  5925.4     .12       0
  5936.7      .1       0  6621.8     .05       0  8037.3     .12       0
    8330      .1       0  8538.8     .12       0    8639     .05       0
#XS Ineff= 2 , 0
         -160.32  351.84
Permanent Ineff=
       F       F
Bank Sta=4950.3,5064.6
XS Rating Curve= 0 ,0
Exp/Cntr=0.3,0.1

Type RM Length L Ch R = 1 ,204119  ,2221,2221,2221
BEGIN DESCRIPTION:
Cedar Creek 68.0
END DESCRIPTION:
XS GIS Cut Line= 3
        2696376.      6862060.95       2696444.3      6865411.42
      2695574.44      6870556.75
#Sta/Elev= 30
  1649.9  381.22    1980  373.07  2300.1  353.98  2957.6  342.83  3546.6  341.24
  3773.7  341.42  3856.6  341.84  3881.5338.0432  3930.4  334.63  3950.4  340.46
  4002.9  340.77    4352   340.1  4390.9  344.28  4970.6   343.8    4975  334.53
    4979  332.73    5021  332.73  5061.5  344.58  5627.6  343.72  5643.9  343.76
  6683.7  344.13  6697.8  343.49  7046.6  343.09  7174.4  343.54    7882  344.94
  8398.6  344.88  8844.4  345.49    9037  351.99  9645.6  380.75 10219.4  386.55
#Mann= 18 ,-1 , 0
  1649.9     .05       0  2957.6     .12       0  3546.6     .05       0
  3773.7     .12       0  3881.5     .05       0  4002.9     .12       0
  4390.9      .1       0  4970.6     .04       0  5061.5      .1       0
  5627.6     .12       0  5643.9      .1       0  6683.7     .12       0
  6697.8      .1       0  7046.6     .12       0  7174.4     .05       0
    7882      .1       0  8398.6     .12       0    9037     .05       0
Bank Sta=4970.6,5061.5
XS Rating Curve= 0 ,0
Exp/Cntr=0.3,0.1

Type RM Length L Ch R = 1 ,201898  ,1672,1672,1672
BEGIN DESCRIPTION:
Cedar Creek 67.0
END DESCRIPTION:
XS GIS Cut Line= 4
      2696005.31      6862628.76      2695449.15      6864434.87
        2694401.        6867086.      2694502.38      6870332.31
#Sta/Elev= 30
  3110.2  370.63    3835  355.81  3936.7  352.76  4093.2  346.96  4126.2     343
  4158.9  338.52  4241.8  340.42  4317.6  340.18  4343.4  344.52  4755.3  340.99
  4912.2  341.27  4978.7   331.3  5038.9  333.52  5060.4  343.59  5085.8  344.29
  7088.3  342.11    8226  347.82    8246  336.04    8266  335.65    8286  347.89
  8646.2  348.17  8686.2  344.57  8810.8  347.51  9751.4  349.95  9819.9  350.13
 10027.7  350.68 10125.7  352.75 10537.1  360.55 10747.2   373.7 11098.7  377.92
#Mann= 16 ,-1 , 0
  3110.2     .05       0    3835      .1       0  3936.7     .12       0
  4093.2     .05       0  4126.2     .12       0  4241.8      .1       0
  4343.4     .05       0  4755.3     .12       0  4912.2     .04       0
  5060.4     .12       0  5085.8      .1       0  8810.8     .05       0
  9751.4     .12       0  9819.9     .05       0 10027.7     .12       0
 10125.7     .05       0
Bank Sta=4912.2,5060.4
XS Rating Curve= 0 ,0
Exp/Cntr=0.3,0.1

Type RM Length L Ch R = 1 ,200226  ,2320,2320,2320
BEGIN DESCRIPTION:
Cedar Creek 66.0
END DESCRIPTION:
XS GIS Cut Line= 3
      2695840.89      6862511.27      2694299.52      6864033.88
      2691575.99      6866861.01
#Sta/Elev= 30
  2833.4  373.11  3204.4  358.48  3898.9  340.76  3953.9   343.5  3975.1  338.03
  4017.6  343.29  4158.3  342.19  4194.3  342.85  4214.3  337.87  4250.9  341.54
  4912.7  342.29  4965.1  341.75  4972.2  342.74  4974.6  332.91  4978.7  330.91
  5021.4  330.91  5035.9  333.39  5042.9  340.93  5050.1  342.62    5057  343.39
  5705.3     342  5844.9  339.73  5977.8  340.46  6094.1  341.03  6234.5   341.4
  7040.8  340.78  8324.5  344.05  8536.7  352.75  8748.7  368.01  8925.6   374.4
#Mann= 13 ,-1 , 0
  2833.4     .05       0  3898.9      .1       0  4158.3     .12       0
  4214.3     .05       0  4912.7      .1       0  4965.1     .04       0
    5057      .1       0  5705.3     .12       0  5844.9     .05       0
  5977.8     .12       0  6094.1      .1       0  6234.5     .12       0
  7040.8     .05       0
Bank Sta=4972.2,5050.1
XS Rating Curve= 0 ,0
Exp/Cntr=0.3,0.1

Type RM Length L Ch R = 1 ,197906  ,1429,1429,1429
BEGIN DESCRIPTION:
Cedar Creek 65.0
END DESCRIPTION:
XS GIS Cut Line= 3
       2695103.1       6861161.4        2693476.        6862761.
       2691205.1      6866967.11
#Sta/Elev= 30
  2713.9  378.86  3015.7  379.92  3524.7  357.12  4173.9  344.81  4199.2  344.38
  4281.3  344.94  4337.9  331.94  4520.4  340.98  4953.2   342.4  4967.4  342.32
  4978.7  329.94  5075.2  342.52  5230.4  342.15  5952.2  340.51  6140.1  340.14
  6466.2   340.9  6612.4  339.77  6872.2  339.86  7000.1  340.03  7167.8  340.21
  7341.2  349.23  7599.4  362.14  7975.1  346.85  8090.3  344.17  8308.4  340.78
  8418.1  340.94  8527.9  341.39  8943.5  347.63  9446.1   377.2  9775.6  377.86
#Mann= 20 ,-1 , 0
  2713.9     .05       0  4173.9      .1       0  4199.2     .12       0
  4520.4      .1       0  4953.2     .04       0  5075.2      .1       0
  5230.4      .1       0  5952.2     .12       0  6140.1      .1       0
  6466.2     .12       0  6612.4      .1       0  6872.2     .12       0
  7000.1      .1       0  7167.8     .12       0  7341.2     .05       0
  7975.1     .12       0  8090.3     .12       0  8308.4      .1       0
  8418.1     .12       0  8527.9     .05       0
Bank Sta=4967.4,5075.2
XS Rating Curve= 0 ,0
Exp/Cntr=0.3,0.1

Type RM Length L Ch R = 1 ,196477  ,2144,2144,2144
BEGIN DESCRIPTION:
Cedar Creek 64.0
END DESCRIPTION:
XS GIS Cut Line= 3
      2694355.57      6860561.92        2692826.        6861811.
      2689825.98      6867211.03
#Sta/Elev= 30
  3026.1  373.89  3229.1  371.46  3267.6   370.7  4056.1  373.98  4805.8339.0877
    4909  341.58  4915.4  337.71  4978.7  329.44  5021.4  329.44  5058.1  341.22
  6320.5  339.62  6372.6  339.88  6721.4  347.46  6957.1   338.5  7185.8  340.94
  7208.7  333.15    7243  340.88  7561.1  334.94  7604.5   342.8  8067.7  339.72
  8225.3  339.51  8552.5  340.99    8726  341.29  8836.5  341.48  9132.9  341.98
  9168.1  342.04  9736.9  343.01 10156.7  352.89 10796.2   387.6 11178.3  387.18
#Mann= 15 ,-1 , 0
  3026.1     .05       0  3229.1     .12       0  3267.6     .05       0
  4805.8     .12       0  4915.4     .04       0  5058.1     .12       0
  6320.5     .12       0  6372.6      .1       0  8067.7     .12       0
  8225.3     .05       0  8552.5     .12       0    8726     .05       0
  8836.5      .1       0  9132.9     .12       0  9168.1     .05       0
Bank Sta=4909,5058.1
XS Rating Curve= 0 ,0
Exp/Cntr=0.3,0.1

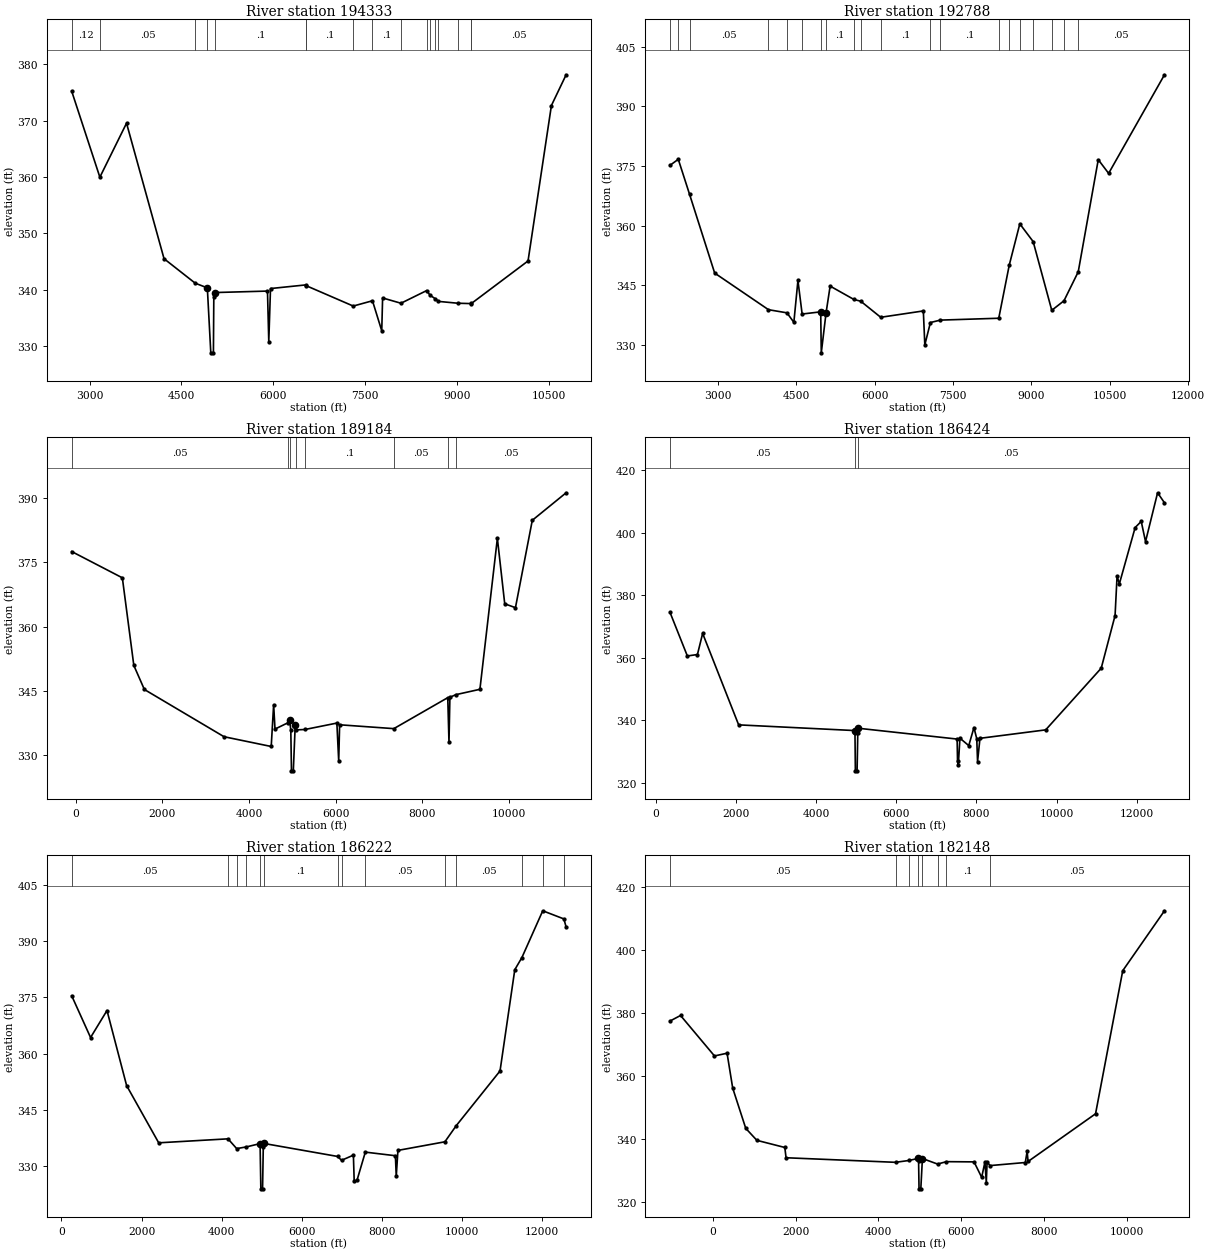
Type RM Length L Ch R = 1 ,194333  ,1545,1545,1545
BEGIN DESCRIPTION:
Cedar Creek 63.0
END DESCRIPTION:
XS GIS Cut Line= 3
      2694077.81      6859958.62      2691964.17       6860849.7
      2687871.67      6864936.45
#Sta/Elev= 30
  2706.2  375.24  3166.3  359.97    3602  369.56  4214.7  345.49  4724.1  341.14
  4922.1  340.31  4978.7  328.77  5021.4  328.77  5027.9  338.67  5049.1  339.48
  5904.7  339.74  5925.9  330.77  5954.2  340.19  6534.3  340.84  6540.8  340.68
  7305.8  337.08  7619.9  338.02  7771.5  332.69  7785.6  338.52  8085.3  337.58
  8505.4  339.83  8560.1  339.01  8648.7  338.36  8695.5  337.91    9016  337.58
  9222.1  337.52  9236.7  337.54 10161.5  345.09 10543.3   372.7 10783.6  378.16
#Mann= 17 ,-1 , 0
  2706.2     .12       0  3166.3     .05       0  4724.1      .1       0
  4922.1     .04       0  5049.1      .1       0  6534.3     .12       0
  6540.8      .1       0  7305.8     .12       0  7619.9      .1       0
  8085.3     .05       0  8505.4      .1       0  8560.1     .05       0
  8648.7      .1       0  8695.5     .12       0    9016      .1       0
  9222.1     .12       0  9236.7     .05       0
Bank Sta=4922.1,5049.1
XS Rating Curve= 0 ,0
Exp/Cntr=0.3,0.1

Type RM Length L Ch R = 1 ,192788  ,3604,3604,3604
BEGIN DESCRIPTION:
Cedar Creek 62.0
END DESCRIPTION:
XS GIS Cut Line= 3
      2693918.08      6859062.79      2691213.55      6860149.26
      2686425.99      6864611.01
#Sta/Elev= 30
  2085.4  375.19  2242.8  376.69    2458   367.9    2939  348.05  3968.7  338.83
  4321.9  338.04  4453.9  335.65  4531.9  346.19  4612.3  337.74  4967.4  338.29
  4978.6  327.97  5070.2  338.05  5147.9  344.77  5603.9   341.4  5734.1  340.96
  6115.6  336.92  6931.1  338.52  6959.4  329.97  7066.4   335.6    7256  336.21
  8373.9  336.68  8575.9  350.12  8776.9  360.44  9032.3  355.97  9388.2  338.67
  9621.9  341.08  9894.4  348.36 10277.7   376.6 10476.1  373.15 11544.3  397.97
#Mann= 20 ,-1 , 0
  2085.4     .05       0  2242.8      .1       0    2458     .05       0
  3968.7     .12       0  4321.9     .05       0  4612.3     .12       0
  4967.4     .04       0  5070.2      .1       0  5603.9     .12       0
  5734.1      .1       0  6115.6      .1       0  7066.4     .12       0
    7256      .1       0  8373.9     .12       0  8575.9     .12       0
  8776.9      .1       0  9032.3     .12       0  9388.2      .1       0
  9621.9     .05       0  9894.4     .05       0
Bank Sta=4967.4,5070.2
XS Rating Curve= 0 ,0
Exp/Cntr=0.3,0.1

Type RM Length L Ch R = 1 ,189184  ,2760,2760,2760
BEGIN DESCRIPTION:
Cedar Creek 61.0
END DESCRIPTION:
XS GIS Cut Line= 3
      2694437.53      6857839.64        2689549.      6859284.82
      2684986.55      6863655.63
#Sta/Elev= 30
   -95.6  377.56  1073.9  371.42  1338.8  350.95  1582.2  345.33  3422.2  334.29
  4511.1  332.01  4567.2  341.78  4598.5  336.08  4907.4   337.6  4936.6   338.1
  4963.5  335.81  4978.6  326.32  5021.4  326.32  5065.1  336.92  5079.2  335.88
  5290.3  335.98  6027.1  337.48  6069.6   328.6  6090.6  337.08  7342.4  336.18
  8587.5  343.42  8615.7  332.98  8636.8  343.49    8770  344.11  9329.9  345.37
  9733.1  380.64  9902.9  365.35 10150.4  364.44 10539.4  384.86 11320.3  391.29
#Mann= 8 ,-1 , 0
   -95.6     .05       0  4907.4     .12       0  4936.6     .04       0
  5079.2     .12       0  5290.3      .1       0  7342.4     .05       0
  8587.5     .12       0    8770     .05       0
Bank Sta=4936.6,5065.1
XS Rating Curve= 0 ,0
Exp/Cntr=0.3,0.1

Type RM Length L Ch R = 1 ,186424  ,202,202,202
BEGIN DESCRIPTION:
Cedar Creek 59.0
END DESCRIPTION:
XS GIS Cut Line= 4
      2693668.94        6857403.      2689024.78       6857221.5
      2685828.65      6857159.94      2682134.05      6859726.82
#Sta/Elev= 30
   352.3  374.44   784.1  360.54  1035.8     361  1165.9  367.75  2064.8  338.51
  4958.8  336.69  4968.8  336.01  4978.6  323.81  5021.5  323.81  5038.8  335.83
  5048.8  337.43  7519.2  333.97  7529.3   326.8  7549.3  325.81  7589.3  334.25
  7809.3  331.88  7939.3  337.66  8009.3  334.05  8029.3  326.79  8089.4  334.21
  9730.1  336.91 11116.5  356.63 11462.2  373.47   11512  386.05 11569.6  383.62
 11963.3   401.6 12115.2  403.57 12222.6  397.11 12523.8  412.72 12695.5  409.52
#Mann= 3 ,-1 , 0
   352.3     .05       0  4968.8     .04       0  5038.8     .05       0
Bank Sta=4958.8,5048.8
XS Rating Curve= 0 ,0
Exp/Cntr=0.3,0.1

Type RM Length L Ch R = 1 ,186222  ,4074,4074,4074
BEGIN DESCRIPTION:
Cedar Creek 58.9
END DESCRIPTION:
XS GIS Cut Line= 5
      2693696.72       6857215.5      2689263.05      6857043.09
      2688804.59      6857039.98      2685731.06      6857019.17
      2682106.43      6859472.44
#Sta/Elev= 30
   255.6  375.46   726.7  364.34    1137  371.53  1627.4  351.52    2428  336.29
  4158.6  337.35  4375.2  334.75  4618.2   335.2  4959.7  336.08  4978.6  324.03
  5021.5  324.03  5039.7  335.26  5059.7  336.11  6894.6  332.66  6993.6  331.63
  7289.7     333  7309.7   326.1  7379.7  326.31  7587.4  333.81  8338.7  332.85
  8359.7  327.34  8401.7  334.27  9574.3  336.56  9857.2  340.85 10951.2  355.43
 11319.7   382.4 11497.5  385.64 12018.2   398.1 12545.6  395.93 12601.5  393.78
#Mann= 14 ,-1 , 0
   255.6     .05       0  4158.6     .12       0  4375.2      .1       0
  4618.2     .12       0  4959.7     .04       0  5059.7      .1       0
  6894.6     .12       0  6993.6      .1       0  7587.4     .05       0
  9574.3     .12       0  9857.2     .05       0 11497.5     .12       0
 12018.2     .05       0 12545.6     .12       0
Bank Sta=4959.7,5059.7
XS Rating Curve= 0 ,0
Exp/Cntr=0.3,0.1

Type RM Length L Ch R = 1 ,182148  ,4154,4154,4154
BEGIN DESCRIPTION:
Cedar Creek 57.0
END DESCRIPTION:
XS GIS Cut Line= 4
      2693938.42       6854942.5      2687923.65      6855355.03
      2685569.98      6856030.67      2682475.98      6857561.01
#Sta/Elev= 30
 -1028.9  377.37  -775.9  379.13    43.1  366.28   346.7  367.15   482.9  356.06
   797.8  343.29  1065.9  339.49    1740  337.22  1770.1  333.96  4410.8  332.51
  4732.5  333.09  4957.5  333.75  4967.6     333  4978.6  324.09  5021.5  324.09
    5060  333.71  5425.7  331.96    5641  332.72  6305.8  332.65    6490  327.74
  6568.5   332.6  6601.6  326.09  6620.6  332.63  6691.2  331.47  7542.4  332.45
    7587  335.98  7609.4  332.77  9237.6  347.92  9893.8  393.35 10900.5  412.37
#Mann= 8 ,-1 , 0
 -1028.9     .05       0  4410.8     .12       0  4732.5      .1       0
  4957.5     .04       0    5060      .1       0  5425.7     .12       0
    5641      .1       0  6691.2     .05       0
Bank Sta=4957.5,5060
XS Rating Curve= 0 ,0
Exp/Cntr=0.3,0.1

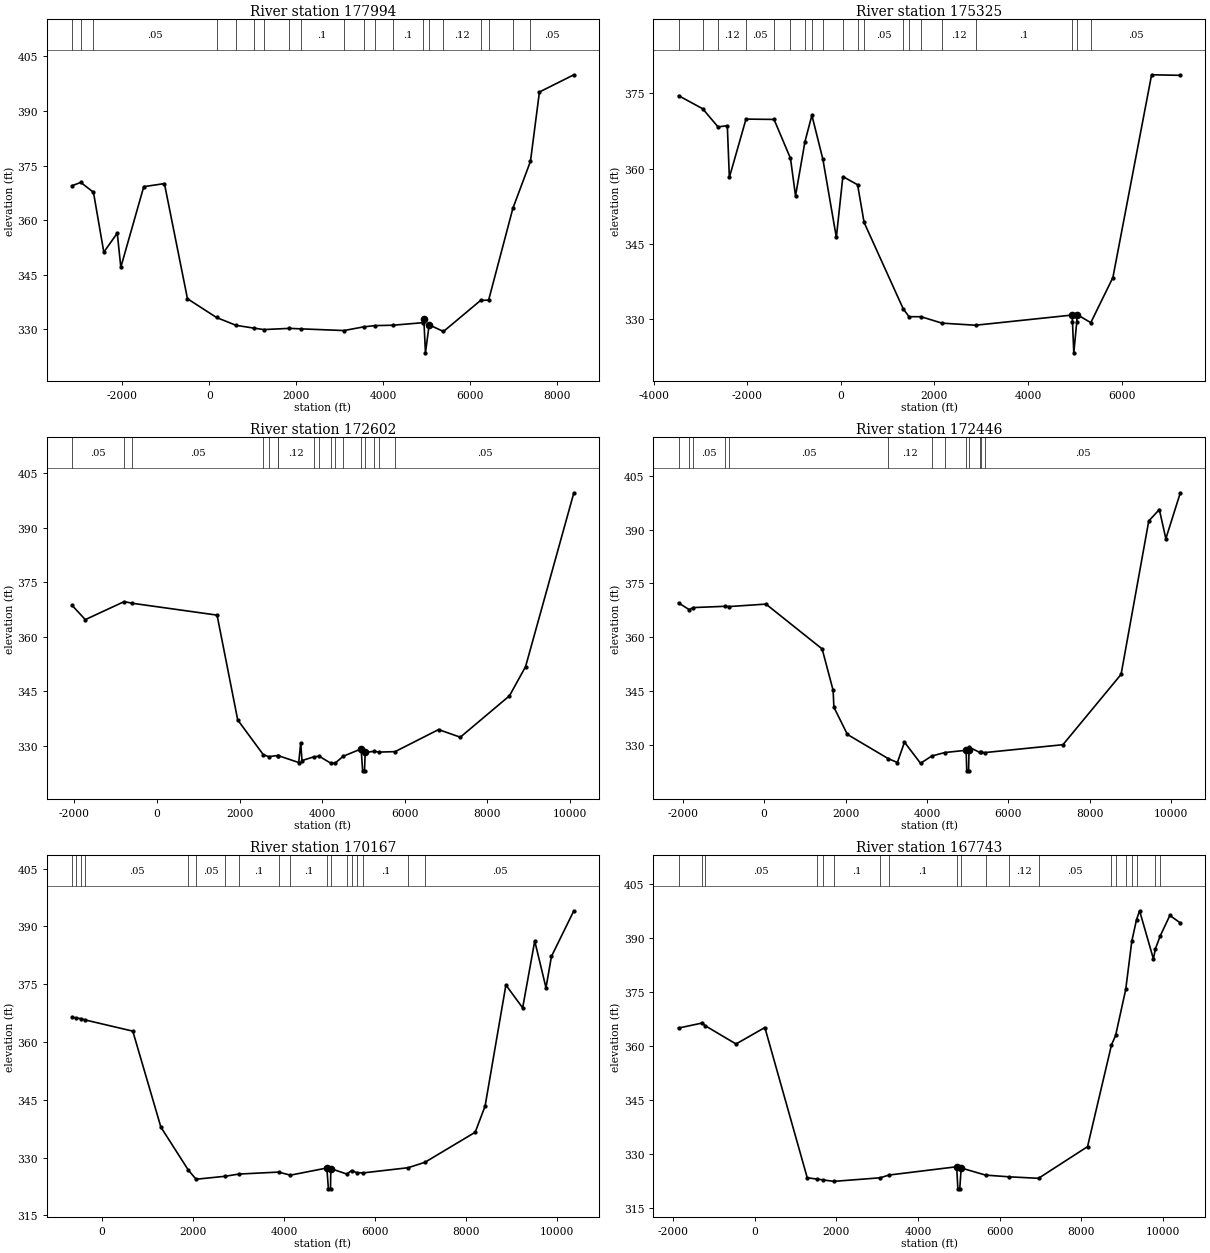
Type RM Length L Ch R = 1 ,177994  ,2669,2669,2669
BEGIN DESCRIPTION:
Cedar Creek 55.0
END DESCRIPTION:
XS GIS Cut Line= 3
      2693981.78      6851926.02      2686017.84      6853704.95
      2683125.38      6855483.66
#Sta/Elev= 30
 -3160.2  369.48 -2960.3  370.39 -2667.5  367.68 -2429.1  351.23 -2119.4  356.46
 -2037.4  347.09 -1509.3  369.22 -1033.3  370.06  -502.7  338.44     166   333.3
   613.7  331.15  1024.7  330.38  1253.9  329.98    1847  330.31  2100.6  330.18
  3102.8  329.71  3557.3  330.73  3820.8  331.07  4225.4  331.17  4930.2  331.88
  4940.4  332.95  4977.8  323.59    5063  331.28  5392.5  329.45  6249.6     338
  6432.8338.0655    6992   363.3  7396.3  376.18  7602.5  395.21  8395.6  399.94
#Mann= 20 ,-1 , 0
 -3160.2     .05       0 -2960.3     .12       0 -2667.5     .05       0
     166     .12       0   613.7      .1       0  1024.7      .1       0
  1253.9     .12       0    1847     .12       0  2100.6      .1       0
  3102.8     .12       0  3557.3      .1       0  3820.8     .12       0
  4225.4      .1       0  4930.2     .04       0    5063      .1       0
  5392.5     .12       0  6249.6     .12       0  6432.8     .05       0
    6992     .12       0  7396.3     .05       0
Bank Sta=4940.4,5063
XS Rating Curve= 0 ,0
Exp/Cntr=0.3,0.1

Type RM Length L Ch R = 1 ,175325  ,2723,2723,2723
BEGIN DESCRIPTION:
Cedar Creek 53.0
END DESCRIPTION:
XS GIS Cut Line= 3
      2693268.59       6848882.1      2685217.86      6851504.94
      2683305.08      6852696.19
#Sta/Elev= 30
 -3467.2  374.54 -2952.1  371.94 -2624.2  368.32   -2425  368.55 -2381.2  358.25
 -2025.9  369.87 -1426.7   369.8 -1075.3  362.04  -967.7  354.56  -766.7  365.36
    -618  370.63  -382.8  361.84   -95.5   346.3    43.6  358.42   358.4  356.78
   496.9  349.29  1333.1  332.06  1457.7  330.49  1713.3  330.49    2160  329.21
  2877.9  328.79  4941.5  330.82  4949.4  329.43  4977.7  323.29  5041.6  329.52
  5049.3   330.9  5340.5  329.31  5812.3  338.28  6639.7   378.7  7253.4  378.59
#Mann= 20 ,-1 , 0
 -3467.2     .05       0 -2952.1      .1       0 -2624.2     .12       0
 -2025.9     .05       0 -1426.7      .1       0 -1075.3     .12       0
  -766.7      .1       0    -618     .05       0  -382.8      .1       0
    43.6     .05       0   358.4      .1       0   496.9     .05       0
  1333.1      .1       0  1457.7     .12       0  1713.3      .1       0
    2160     .12       0  2877.9      .1       0  4949.4     .04       0
  5041.6      .1       0  5340.5     .05       0
Bank Sta=4941.5,5049.3
XS Rating Curve= 0 ,0
Exp/Cntr=0.3,0.1

Type RM Length L Ch R = 1 ,172602  ,156,156,156
BEGIN DESCRIPTION:
Cedar Creek 49.5
END DESCRIPTION:
XS GIS Cut Line= 6
      2692116.45      6848509.36      2687648.11      6848468.85
      2687375.64      6848531.76      2683867.29      6849882.31
      2683018.33      6850017.72      2680236.62      6850042.46
#Sta/Elev= 30
 -2057.9  368.62 -1737.4   364.7  -795.9  369.66  -598.8   369.2  1452.7  365.94
  1952.7  337.08    2571  327.53  2702.9326.9691  2917.1327.2865  2930.2 327.266
  3429.5  325.36  3478.6  330.79  3508.6  325.89  3787.7   326.9  3924.2   327.1
  4202.3  325.19  4309.4  325.17    4509   327.1  4940.9   329.1  4977.3  323.07
  5022.7  323.07  5038.6  328.12  5250.1  328.44  5380.4  328.23  5763.6  328.36
  6815.4  334.43  7341.6  332.33  8531.7  343.72  8921.7  351.75 10091.1  399.62
#Mann= 17 ,-1 , 0
 -2057.9     .05       0  -795.9     .12       0  -598.8     .05       0
    2571      .1       0  2702.9     .12       0  2917.1     .05       0
  2930.2     .12       0  3787.7      .1       0  3924.2     .12       0
  4202.3    .075       0  4309.4     .05       0    4509     .12       0
  4940.9     .04       0  5038.6     .12       0  5250.1      .1       0
  5380.4     .12       0  5763.6     .05       0
Bank Sta=4940.9,5038.6
XS Rating Curve= 0 ,0
Exp/Cntr=0.3,0.1

Type RM Length L Ch R = 1 ,172446  ,2279,2279,2279
BEGIN DESCRIPTION:
Cedar Creek 49.2
END DESCRIPTION:
XS GIS Cut Line= 6
      2692083.88      6848390.73       2688264.3      6848313.81
      2687417.48      6848346.56      2683862.08      6849705.22
      2682908.96      6849866.68      2680020.34      6849860.17
#Sta/Elev= 30
 -2104.5  369.56 -1842.3  367.68 -1743.4  368.26  -951.7  368.62  -852.8  368.55
    43.8  369.23  1424.1  356.74  1694.2   345.2  1712.5  340.52  2044.4  332.92
  3043.4  326.21  3273.1   325.1  3447.1  330.77  3841.8  324.88  4117.6  326.91
  4439.2  327.88  4961.9  328.51  4977.3  322.78  5022.7  322.78  5032.9  328.68
  5040.8  329.34    5297  327.91  5335.7   327.9  5422.8  327.87  7340.5  330.06
  8769.4  349.65  9449.4  392.38  9709.4  395.58  9869.4  387.46 10225.1  400.24
#Mann= 13 ,-1 , 0
 -2104.5     .05       0 -1842.3     .12       0 -1743.4     .05       0
  -951.7     .12       0  -852.8     .05       0  3043.4     .12       0
  4117.6    .075       0  4439.2     .12       0  4961.9     .04       0
  5040.8     .12       0    5297      .1       0  5335.7     .12       0
  5422.8     .05       0
Bank Sta=4961.9,5032.9
XS Rating Curve= 0 ,0
Exp/Cntr=0.3,0.1

Type RM Length L Ch R = 1 ,170167  ,2424,2424,2424
BEGIN DESCRIPTION:
Cedar Creek 49.0
END DESCRIPTION:
XS GIS Cut Line= 4
      2690082.11      6845879.28      2685301.75      6847333.26
      2684046.79      6848084.14      2679795.64      6849746.66
#Sta/Elev= 30
  -654.1  366.45  -568.9  366.28  -464.6  366.07  -360.4  365.72   679.9  362.83
  1297.5  337.91  1903.5   326.7  2071.3  324.39  2714.4  325.17  3007.4  325.73
  3881.1  326.25  4141.9  325.45  4943.5  327.31  4976.7   321.9  5023.3   321.9
  5030.2  327.15  5378.5  325.75  5488.3  326.65  5597.2  326.11  5734.5  326.03
  6728.2  327.38  7098.3  328.79  8202.2  336.59  8419.4  343.38  8876.7   374.8
  9244.6  368.88  9510.2  386.23  9757.2  374.09  9877.1  382.22 10369.6  394.07
#Mann= 18 ,-1 , 0
  -654.1     .05       0  -568.9      .1       0  -464.6     .12       0
  -360.4     .05       0  1903.5     .12       0  2071.3     .05       0
  2714.4     .12       0  3007.4      .1       0  3881.1     .12       0
  4141.9      .1       0  4943.5     .04       0  5030.2      .1       0
  5378.5     .12       0  5488.3      .1       0  5597.2     .12       0
  5734.5      .1       0  6728.2     .12       0  7098.3     .05       0
Bank Sta=4943.5,5030.2
XS Rating Curve= 0 ,0
Exp/Cntr=0.3,0.1

Type RM Length L Ch R = 1 ,167743  ,2838,2838,2838
BEGIN DESCRIPTION:
Cedar Creek 47.0
END DESCRIPTION:
XS GIS Cut Line= 3
      2690568.74      6844149.24        2683926.        6845861.
        2679220.        6848554.
#Sta/Elev= 30
   -1860  364.98 -1275.2  366.39 -1214.1  365.67  -452.7  360.57   252.8  365.13
  1290.1  323.51  1531.1  323.14  1687.5   322.9    1940  322.51  3075.5   323.5
  3291.2  324.26  4948.1  326.56  4976.7  320.44  5023.3  320.44  5057.4  326.22
  5656.9  324.24  6229.4  323.77  6951.4  323.36  8150.8  332.13  8737.1  360.32
  8837.7  362.92  9085.8  375.71  9234.4  389.07    9350  395.02  9424.5  397.47
  9762.7  384.15  9812.5  386.95  9928.2  390.47 10165.6  396.18 10421.8   394.1
#Mann= 20 ,-1 , 0
   -1860     .05       0 -1275.2      .1       0 -1214.1     .05       0
  1531.1     .12       0  1687.5     .05       0    1940      .1       0
  3075.5     .12       0  3291.2      .1       0  4948.1     .04       0
  5057.4      .1       0  5656.9     .12       0  6229.4     .12       0
  6951.4     .05       0  8737.1     .12       0  8837.7      .1       0
  9085.8     .05       0  9234.4     .12       0    9350     .05       0
  9812.5      .1       0  9928.2     .12       0
Bank Sta=4948.1,5057.4
XS Rating Curve= 0 ,0
Exp/Cntr=0.3,0.1

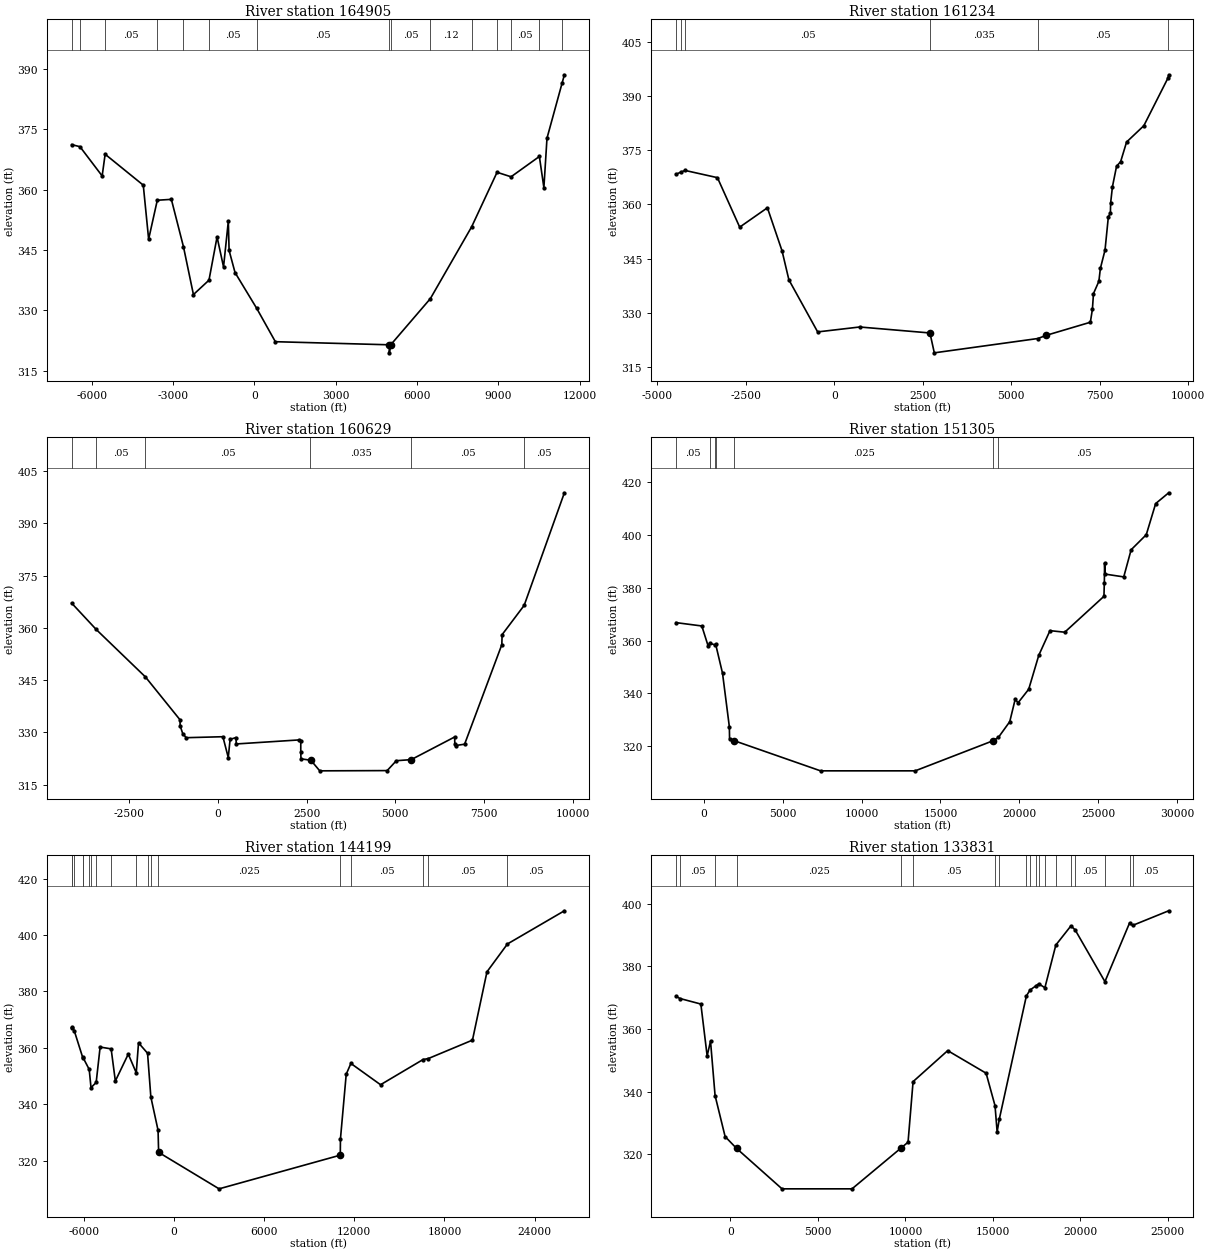
Type RM Length L Ch R = 1 ,164905  ,3671,3671,3671
BEGIN DESCRIPTION:
Cedar Creek 45.0
END DESCRIPTION:
XS GIS Cut Line= 3
      2693780.54      6840763.82        2682476.        6843961.
      2676635.07        6846664.
#Sta/Elev= 30
 -6747.6  371.23 -6440.4  370.72 -5620.5  363.44 -5510.7  368.84 -4103.3  361.15
 -3905.4  347.72   -3586   357.4 -3067.2  357.62 -2620.1  345.83 -2252.5  333.94
 -1678.7  337.52 -1380.5  348.27 -1141.5  340.82  -964.8  352.19  -936.4  344.92
    -717  339.41      82  330.52   770.7  322.22  4972.2  321.45  4976.7  319.45
  5027.8  321.45  6490.5  332.93    8015   350.8  8952.1  364.35  9468.5  363.23
 10513.4368.2832 10679.9  360.54 10794.5  372.83 11354.4  386.59 11436.4   388.6
#Mann= 15 ,-1 , 0
 -6747.6     .12       0 -6440.4     .05       0 -5510.7     .05       0
   -3586     .05       0 -2620.1      .1       0 -1678.7     .05       0
      82     .05       0  4972.2     .04       0  5027.8     .05       0
  6490.5     .12       0    8015      .1       0  8952.1      .1       0
  9468.5     .05       0 10513.4      .1       0 11354.4     .12       0
Bank Sta=4972.2,5027.8
XS Rating Curve= 0 ,0
Exp/Cntr=0.3,0.1

Type RM Length L Ch R = 1 ,161234  ,605,605,605
BEGIN DESCRIPTION:
Cedar Creek 42.0
END DESCRIPTION:
XS GIS Cut Line= 3
      2688854.37      6836662.24      2680869.31      6841754.68
      2677092.19      6844105.83
#Sta/Elev= 30
 -4470.8  368.31   -4330  368.94 -4210.8  369.38 -3298.5  367.39 -2669.9  353.72
 -1887.1  359.07 -1473.8  347.18   -1280  339.16  -467.6  324.78   720.6  326.14
  2704.1  324.49  2827.8     319  5755.5  322.96    5981  323.81  7235.6  327.45
  7293.5  331.03  7324.2  335.38  7476.4  338.76  7518.9  342.33  7649.9  347.38
  7744.3   356.6  7802.2  357.57  7808.1  360.37    7860  364.92  7975.7  370.53
  8091.3  371.82  8258.9  377.23  8746.4  381.74  9434.5  395.04    9449  395.81
#Mann= 6 ,-1 , 0
 -4470.8      .1       0   -4330      .1       0 -4210.8     .05       0
  2704.1    .035       0  5755.5     .05       0  9434.5     .05       0
Bank Sta=2704.1,5981
XS Rating Curve= 0 ,0
Exp/Cntr=0.3,0.1

Type RM Length L Ch R = 1 ,160629  ,9324,9324,9324
BEGIN DESCRIPTION:
Cedar Creek 38
END DESCRIPTION:
XS GIS Cut Line= 3
      2688528.79      6836336.76      2680846.54      6841219.54
      2676810.55      6843801.71
#Sta/Elev= 30
 -4127.5  367.11 -3435.2  359.54 -2046.3   345.9 -1072.3   333.6 -1066.4  331.82
  -993.6   329.6 -896.78  328.45   137.9  328.73   289.4  322.75   341.1  327.97
   507.9  328.49   513.9  326.65 2273.12   327.8  2333.5  327.46 2333.52   324.3
  2339.7  322.37  2600.5     322  2615.8     322 2868.68  318.93 4769.76     319
  5028.2  321.84 5448.19  322.15  6671.6  328.65  6677.5  326.71  6698.7   326.2
  6953.2  326.58    8003  355.18  8010.3  358.04  8632.5  366.45  9766.5  398.79
#Mann= 6 ,-1 , 0
 -4127.5     .05       0 -3435.2     .05       0 -2046.3     .05       0
  2600.5    .035       0 5448.19     .05       0  8632.5     .05       0
Bank Sta=2615.8,5448.19
XS Rating Curve= 0 ,0
Exp/Cntr=0.3,0.1

Type RM Length L Ch R = 1 ,151305  ,7106,7106,7106
BEGIN DESCRIPTION:
Cedar Creek 37.0
END DESCRIPTION:
XS GIS Cut Line= 3
      2688684.66      6835779.62       2682276.5      6833621.21
      2658701.03      6827086.01
#Sta/Elev= 30
 -1761.9  366.82    -122  365.55   282.1   357.9   365.1     359   695.4  358.44
   756.3  358.59  1190.1  347.65  1623.9  327.32  1636.3  322.79 1924.39  322.12
    7400   310.7   13400   310.7 18348.5  322.13   18671  323.35 19391.4  329.32
 19736.3  337.81 19918.1  336.46 20592.3  341.59 21232.2  354.47 21940.6  363.78
 22875.5  363.19 25360.4  376.77 25385.2   381.9 25401.9  389.39   25433  385.19
 26615.1  384.13   27083   394.4 28042.4   400.1 28637.7  411.89 29464.5  415.98
#Mann= 7 ,-1 , 0
 -1761.9     .05       0   365.1     .12       0   695.4     .05       0
   756.3     .12       0 1924.39    .025       0 18348.5      .1       0
   18671     .05       0
Bank Sta=1924.39,18348.5
XS Rating Curve= 0 ,0
Exp/Cntr=0.3,0.1

Type RM Length L Ch R = 1 ,144199  ,10368,10368,10368
BEGIN DESCRIPTION:
Cedar Creek 32.0
END DESCRIPTION:
XS GIS Cut Line= 4
      2691451.85      6833985.18      2688802.27      6830201.31
      2682582.08       6826608.8      2662380.96      6820946.03
#Sta/Elev= 30
 -6802.4  367.13 -6772.9  367.33 -6627.6  366.08 -6069.8  356.67 -6019.7  356.31
 -5632.1  352.35 -5512.3  345.88 -5168.7  347.73 -4905.9  360.28 -4173.5  359.64
 -3893.7  348.24 -3033.2  357.78   -2502  351.15 -2351.4  361.77 -1750.4  358.09
 -1532.1  342.59 -1051.2  330.75   -1014  322.94    3008     310 11071.4  321.95
 11081.5  327.67 11466.1  350.65   11777  354.47 13749.8  346.92 16579.7  355.86
 16925.9   356.2 19864.8  362.74 20829.4  386.96 22191.6  396.84 25979.8  408.61
#Mann= 18 ,-1 , 0
 -6802.4    .075       0 -6772.9     .05       0 -6627.6     .12       0
 -6069.8     .05       0 -6019.7      .1       0 -5632.1     .05       0
 -5512.3     .12       0 -5168.7      .1       0 -4173.5     .05       0
   -2502     .05       0 -1750.4      .1       0 -1532.1      .1       0
 -1051.2    .025       0 11081.5     .12       0   11777     .05       0
 16579.7     .12       0 16925.9     .05       0 22191.6     .05       0
Bank Sta=-1014,11071.4
XS Rating Curve= 0 ,0
Exp/Cntr=0.3,0.1

Type RM Length L Ch R = 1 ,133831  ,8726,8726,8726
BEGIN DESCRIPTION:
Cedar Creek 29.0
END DESCRIPTION:
XS GIS Cut Line= 3
      2694489.08      6818661.06      2686428.14      6817776.19
      2666501.01        6815586.
#Sta/Elev= 30
 -3111.1  370.46 -2880.8  369.75 -1687.3  367.98 -1327.9   351.4 -1135.7  356.13
  -875.1  338.72  -301.2  325.61  352.47  321.83    2950   308.9    6950   308.9
 9724.28  321.83 10151.3  323.81 10438.5  343.18   12417  353.09 14611.9  345.87
 15121.3  335.48 15241.7  327.12 15367.4  331.22 16911.7  370.56 17122.8  372.47
 17456.5   373.8 17619.3  374.44 17970.4   373.2 18596.5  386.85 19458.2  392.97
 19698.5   391.7 21401.3  375.14 22812.9  393.95 22981.9  393.12 25045.4   397.8
#Mann= 19 ,-1 , 0
 -3111.1     .12       0 -2880.8     .05       0  -875.1    .075       0
  352.47    .025       0 9724.28     .05       0 10438.5     .05       0
 15121.3     .12       0 15367.4     .05       0 16911.7     .12       0
 17122.8      .1       0 17456.5      .1       0 17619.3     .12       0
 17970.4     .12       0 18596.5     .05       0 19458.2     .12       0
 19698.5     .05       0 21401.3     .05       0 22812.9    .075       0
 22981.9     .05       0
#XS Ineff= 2 , 0
                        12430.36          352.99
Permanent Ineff=
       F       F
Bank Sta=352.47,9724.28
XS Rating Curve= 0 ,0
Exp/Cntr=0.3,0.1