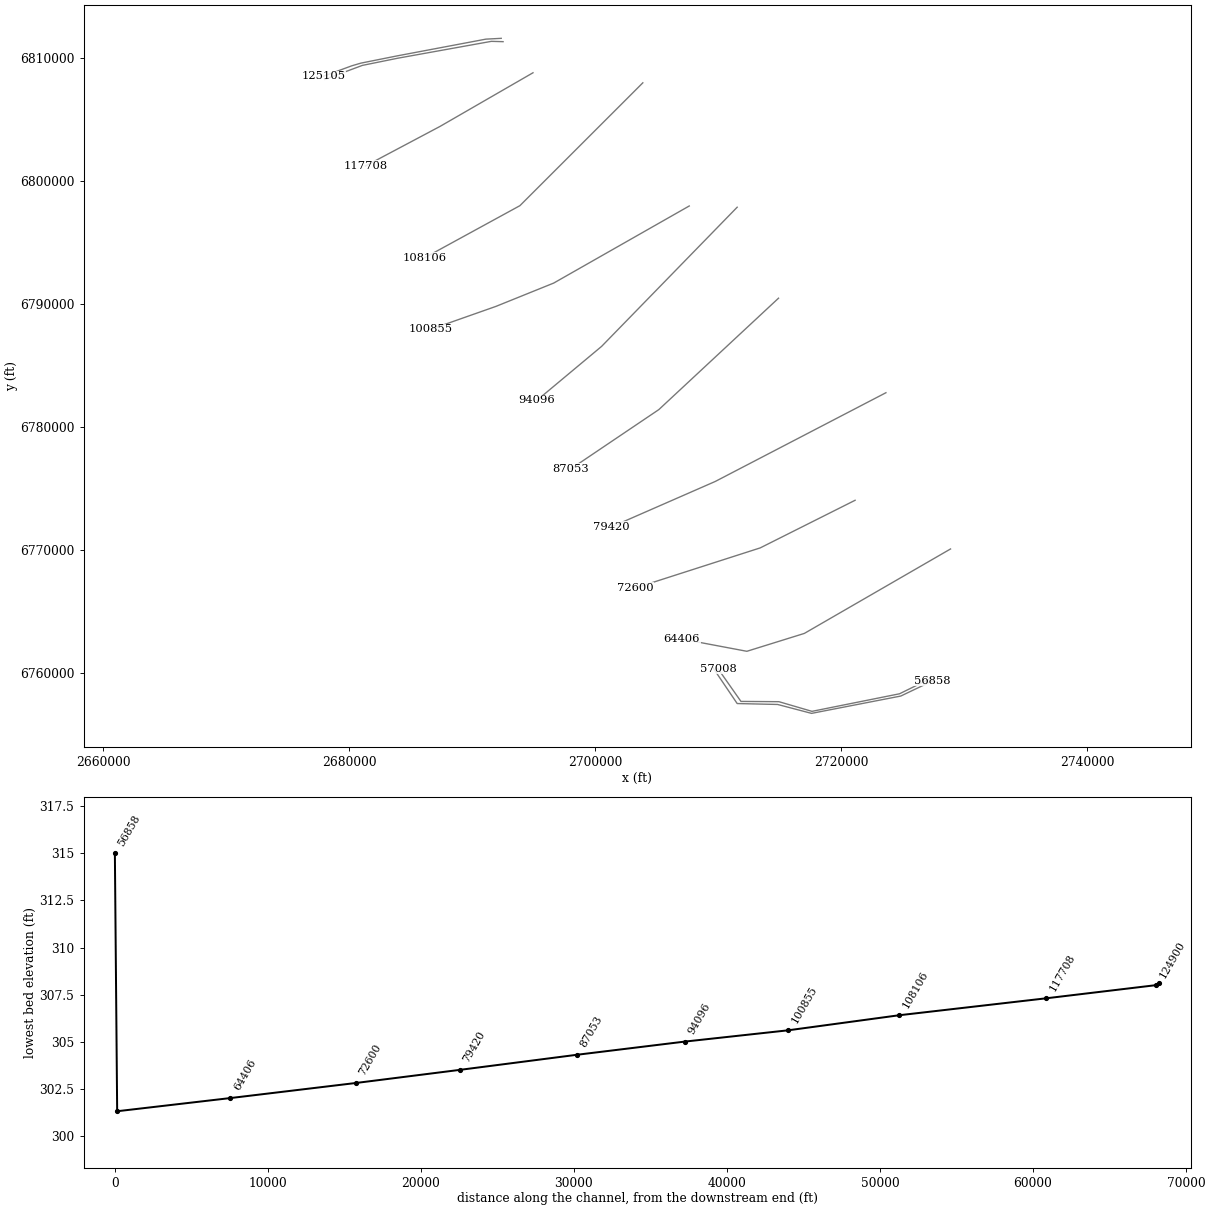
HEC-RAS study Cedar Creek.prj: Cedar Creek Base Level Engineering

--- Cedar Creek.g01 (geometry) --- (continued)

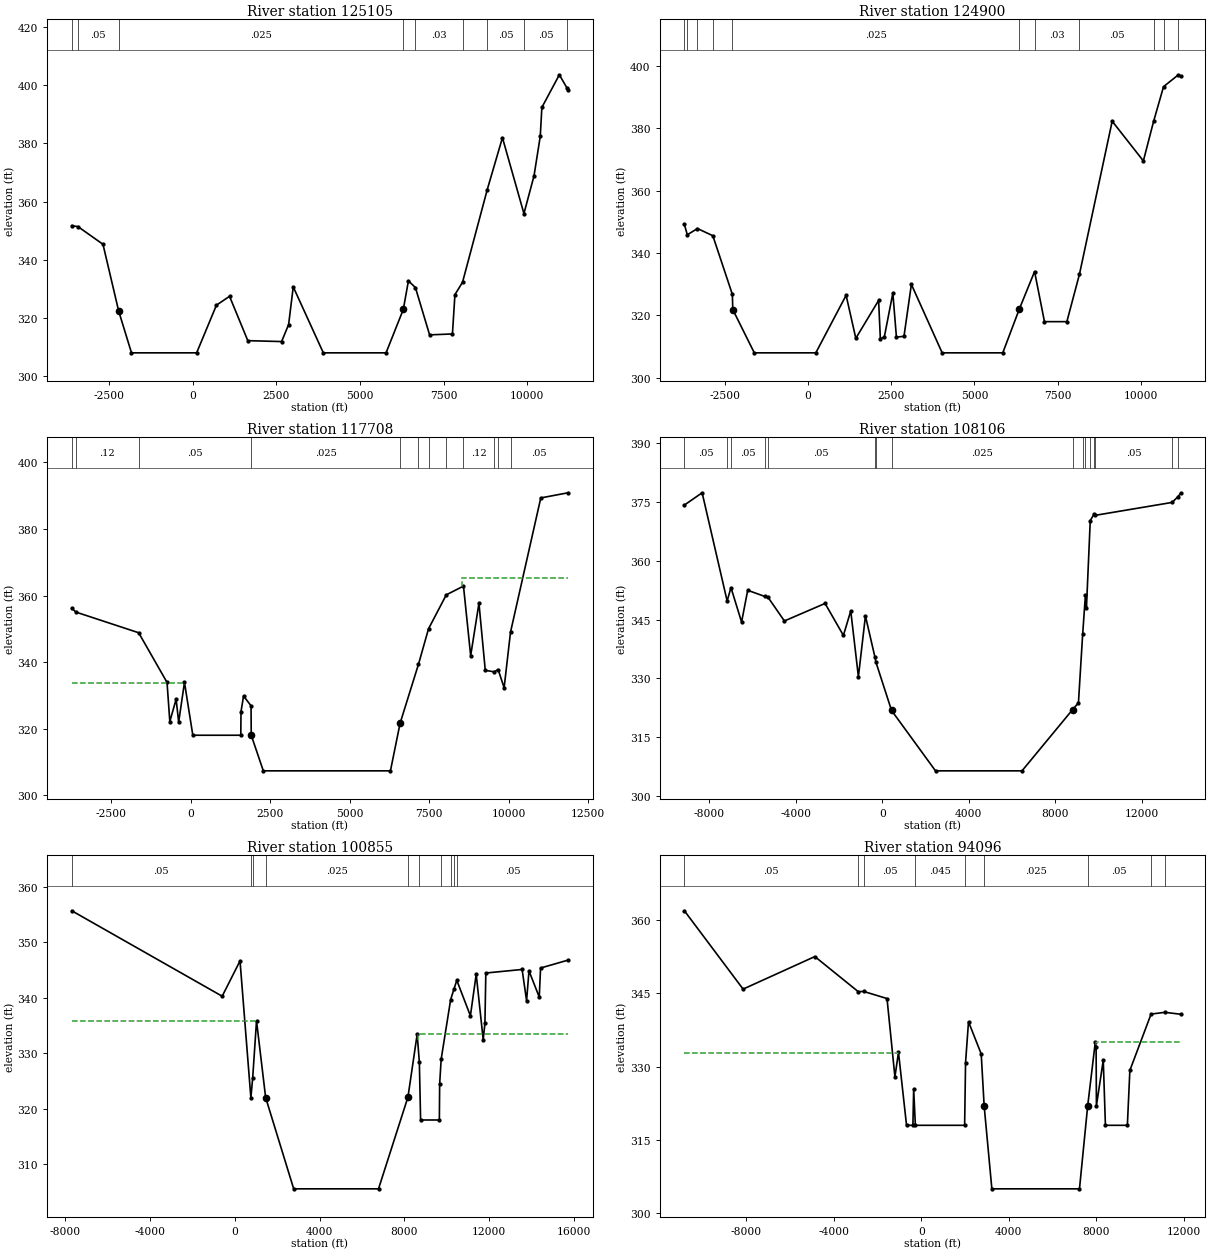
Type RM Length L Ch R = 1 ,125105  ,205,205,205
BEGIN DESCRIPTION:
Cedar Creek 27.0
END DESCRIPTION:
XS GIS Cut Line= 6
      2692356.42      6811631.35      2691108.63      6811566.25
      2683871.22      6810199.06      2680941.53      6809613.12
      2680203.69      6809396.11      2677903.35      6808549.76
#Sta/Elev= 30
 -3609.3  351.74 -3422.3   351.4 -2677.6  345.35-2208.07   322.4-1826.04   308.1
  120.52   308.1   711.7  324.46    1103   327.5 1648.66  312.28 2658.33  311.97
 2867.54   317.8  3006.1  330.73 3904.49   308.1 5778.28   308.1  6293.4  322.99
  6446.3  332.79  6655.4  330.51 7079.02  314.27 7761.23  314.58  7835.8  328.08
  8062.4  332.31  8802.1  364.15  9255.2  381.93  9896.9  355.89 10198.4  368.83
 10384.7  382.41 10432.8  392.31 10954.9  403.52 11188.9  398.87 11213.5  398.41
#Mann= 9 ,-1 , 0
 -3609.3    .075       0 -3422.3     .05       0-2208.07    .025       0
  6293.4     .05       0  6655.4     .03       0  8062.4     .05       0
  8802.1     .05       0  9896.9     .05       0 11188.9    .075       0
Bank Sta=-2208.07,6293.4
XS Rating Curve= 0 ,0
Exp/Cntr=0.3,0.1

Type RM Length L Ch R = 1 ,124900  ,7192,7192,7192
BEGIN DESCRIPTION:
Cedar Creek 26.0
END DESCRIPTION:
XS GIS Cut Line= 5
      2692508.37      6811360.09      2691554.72      6811385.94
        2683926.        6810011.      2681060.89      6809428.66
        2678001.        6808286.
#Sta/Elev= 30
 -3706.3  349.16 -3619.1  345.86 -3313.2  347.85 -2852.8  345.56 -2265.9  326.73
-2253.55  321.87-1607.73     308  238.77     308  1148.3  326.45 1439.45  312.66
  2123.7   324.8 2176.24  312.53 2294.49  313.04  2551.2  327.15 2658.33  313.04
 2885.73   313.3  3107.5  329.95 4031.84     308 5851.05     308  6346.3     322
  6805.5  334.06  7102.5     318  7774.9     318  8152.4  333.17  9135.5  382.27
 10071.5  369.54 10377.9  382.19 10677.1  393.35 11123.5  397.16 11189.3  396.82
#Mann= 11 ,-1 , 0
 -3706.3      .1       0 -3619.1    .075       0 -3313.2     .05       0
 -2852.8    .075       0 -2265.9    .025       0  6346.3     .05       0
  6805.5     .03       0  8152.4     .05       0 10377.9     .05       0
 10677.1     .05       0 11123.5     .05       0
Bank Sta=-2253.55,6346.3
XS Rating Curve= 0 ,0
Exp/Cntr=0.3,0.1

Type RM Length L Ch R = 1 ,117708  ,9602,9602,9602
BEGIN DESCRIPTION:
Cedar Creek 24.0
END DESCRIPTION:
XS GIS Cut Line= 3
      2694941.43      6808828.91        2687376.        6804461.
      2681300.97      6801235.98
#Sta/Elev= 30
 -3741.5  356.13 -3606.1     355 -1637.6  348.81  -744.6  333.88  -656.8  322.11
  -458.7  328.82  -378.3  321.95  -195.9  333.89    66.9     318  1576.4     318
  1583.2  325.12  1663.7   329.8  1899.1  326.84  1904.9     318    2285   307.3
    6285   307.3 6587.83  321.57  7167.3  339.33  7483.6     350  8042.2   360.2
  8583.3  362.83  8809.7  341.92  9070.1  357.68  9269.3   337.5    9549  337.07
  9673.4  337.75  9862.3  332.28 10063.5     349 11015.5  389.33 11872.3  390.88
#Mann= 12 ,-1 , 0
 -3741.5     .05       0 -3606.1     .12       0 -1637.6     .05       0
  1899.1    .025       0 6587.83     .12       0  7167.3     .05       0
  7483.6     .12       0  8042.2     .05       0  8583.3     .12       0
    9549     .05       0  9673.4     .12       0 10063.5     .05       0
#XS Ineff= 2 , 0
         -206.94  333.71 8543.49          365.12
Permanent Ineff=
       F       F
Bank Sta=1904.9,6587.83
XS Rating Curve= 0 ,0
Exp/Cntr=0.3,0.1

Type RM Length L Ch R = 1 ,108106  ,7251,7251,7251
BEGIN DESCRIPTION:
Cedar Creek 20.0
END DESCRIPTION:
XS GIS Cut Line= 3
      2703876.01      6808011.01        2693876.        6798011.
      2686150.96      6793785.98
#Sta/Elev= 30
 -9147.7   374.2 -8327.4  377.33 -7170.9  349.73 -6993.4  353.13 -6503.1  344.36
 -6220.3  352.46 -5440.9  350.91   -5298  350.81 -4523.2  344.63 -2642.3   349.1
 -1793.8  340.94 -1454.4  347.19 -1100.8  330.42  -775.5  345.91  -333.3  335.34
    -288  334.08  432.06   321.8    2465   306.4    6465   306.4  8803.3  322.01
  9074.9  323.75  9269.7   341.2  9398.4  351.31  9444.6  347.91    9621  370.21
  9793.3  371.88  9843.7  371.57 13406.6  374.87 13680.3  376.34 13799.4  377.21
#Mann= 16 ,-1 , 0
 -9147.7     .05       0 -7170.9     .12       0 -6993.4     .05       0
 -5440.9    .075       0   -5298     .05       0  -333.3    .075       0
    -288     .05       0  432.06    .025       0  8803.3     .12       0
  9269.7     .05       0  9398.4     .12       0    9621     .05       0
  9793.3     .12       0  9843.7     .05       0 13406.6     .12       0
 13680.3     .05       0
Bank Sta=432.06,8803.3
XS Rating Curve= 0 ,0
Exp/Cntr=0.3,0.1

Type RM Length L Ch R = 1 ,100855  ,6759,6759,6759
BEGIN DESCRIPTION:
Cedar Creek 19.0
END DESCRIPTION:
XS GIS Cut Line= 4
      2707650.98      6797985.99        2696626.        6791711.
      2691922.44       6789811.3      2686600.97      6787935.99
#Sta/Elev= 30
 -7684.5  355.68  -592.6  340.29   249.1  346.65   760.8     322   847.1  325.62
  1027.2  335.86 1456.79  322.05    2780   305.6    6780   305.6 8167.99  322.12
  8603.3  333.44  8706.1   328.4  8765.1     318  9649.4     318  9663.2  324.48
  9735.5  328.97   10182  339.69 10339.8   341.6 10472.1  343.15 11113.6  336.76
 11386.8  344.24 11716.7  332.47 11798.3  335.42 11840.7  344.47 13551.5  345.11
 13762.8  339.49   13876  344.86 14360.5  340.13 14422.4  345.37 15716.1  346.79
#Mann= 10 ,-1 , 0
 -7684.5     .05       0   760.8     .12       0   847.1     .05       0
 1456.79    .025       0 8167.99     .12       0  8706.1     .05       0
  9735.5     .12       0   10182     .05       0 10339.8     .12       0
 10472.1     .05       0
#XS Ineff= 2 , 0
         1034.68  335.86 8624.22           333.5
Permanent Ineff=
       F       F
Bank Sta=1456.79,8167.99
XS Rating Curve= 0 ,0
Exp/Cntr=0.3,0.1

Type RM Length L Ch R = 1 ,94096   ,7043,7043,7043
BEGIN DESCRIPTION:
Cedar Creek 18.0
END DESCRIPTION:
XS GIS Cut Line= 3
      2711551.03      6797886.03        2700526.        6786561.
      2695270.41      6782173.31
#Sta/Elev= 30
-10810.6   361.9 -8130.4  345.87 -4856.2  352.53 -2877.4  345.36 -2624.2  345.39
 -1560.8  343.94 -1200.2  327.91 -1037.4  332.93  -669.8     318  -379.7     318
  -344.4  325.41  -266.7     318  1982.1     318  2024.5  330.84    2159  339.19
  2738.8  332.61 2873.79  321.93    3225     305    7225     305 7598.07  321.93
  7948.4  335.08  7983.6  334.04  7997.9     322  8310.3  331.31  8409.2     318
  9410.8     318  9524.6  329.23 10492.9  340.76 11122.3  341.12 11841.1  340.73
#Mann= 9 ,-1 , 0
-10810.6     .05       0 -2877.4     .12       0 -2624.2     .05       0
  -266.7    .045       0  1982.1     .05       0 2873.79    .025       0
 7598.07     .05       0 10492.9     .12       0 11122.3     .05       0
#XS Ineff= 2 , 0
        -1048.89  332.79 7973.28          335.09
Permanent Ineff=
       F       F
Bank Sta=2873.79,7598.07
XS Rating Curve= 0 ,0
Exp/Cntr=0.3,0.1

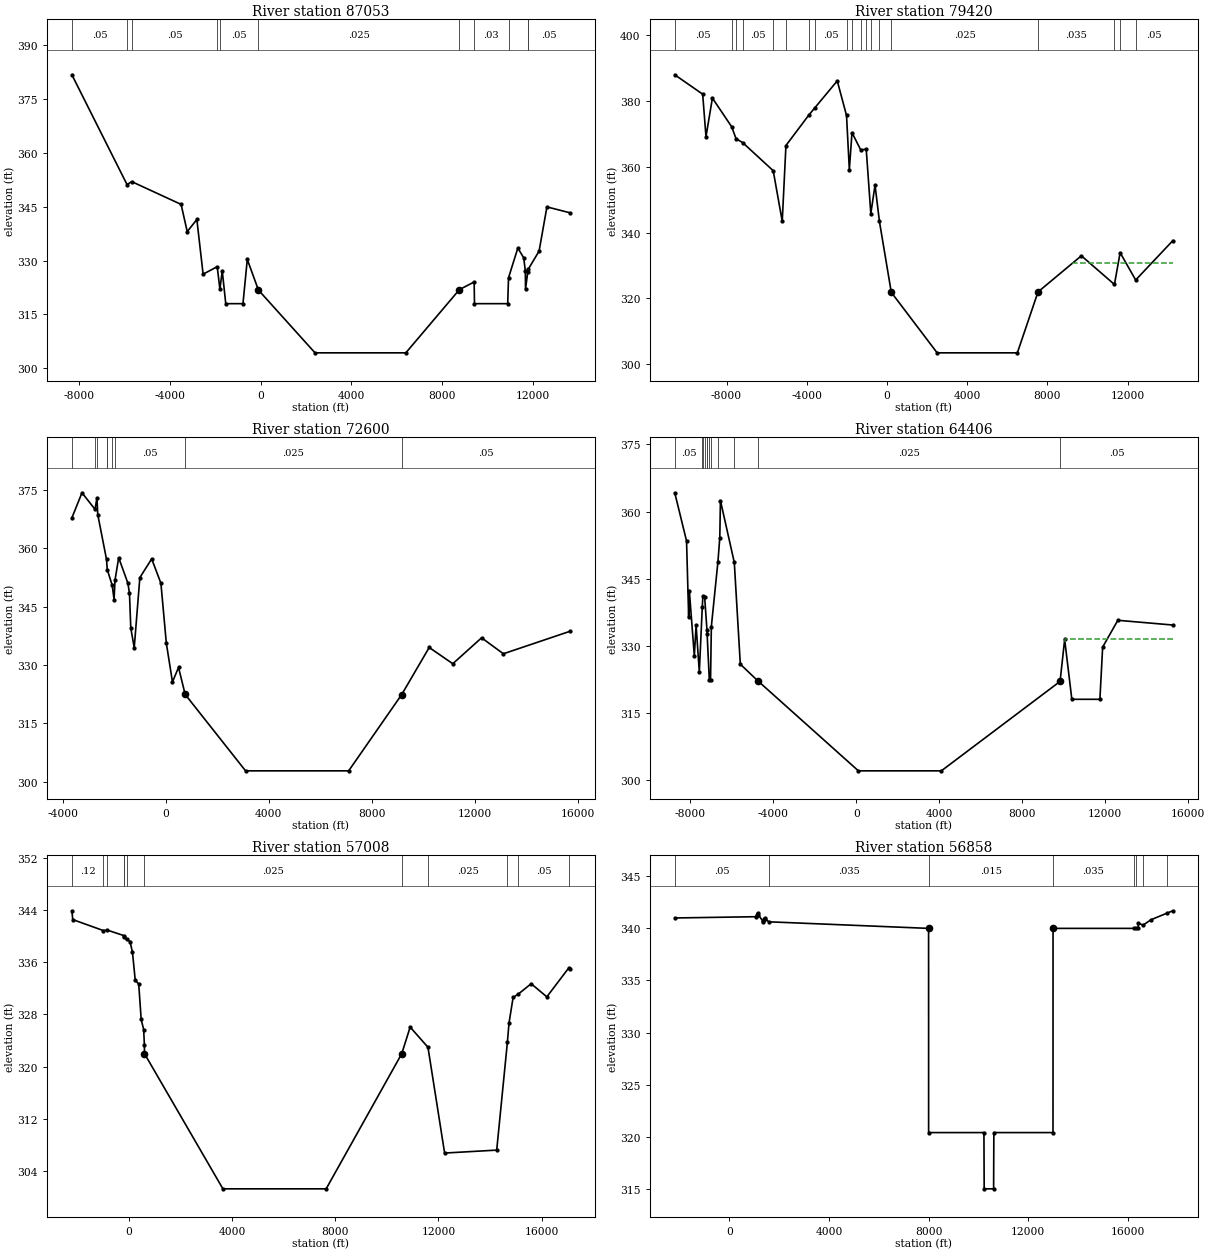
Type RM Length L Ch R = 1 ,87053   ,7633,7633,7633
BEGIN DESCRIPTION:
Cedar Creek 17.0
END DESCRIPTION:
XS GIS Cut Line= 3
      2714914.49      6790481.12        2705176.        6781411.
      2698022.98      6776586.57
#Sta/Elev= 30
   -8308  381.77 -5880.2  351.19 -5672.2     352 -3497.8  345.66 -3228.6  338.07
   -2804  341.45 -2528.5  326.22 -1907.2   328.3 -1788.5     322 -1686.2  327.16
 -1530.8     318  -773.5     318  -582.5  330.33   -93.8  321.81    2400   304.3
    6400   304.3 8760.66  321.93  9408.6  324.04  9423.6     318 10886.3     318
 10922.5  325.21 11332.6  333.51 11591.1  330.76   11663   327.1 11670.3     322
 11768.9   326.8   11786  327.54 12268.6  332.65 12613.4  344.96   13628  343.32
#Mann= 11 ,-1 , 0
   -8308     .05       0 -5880.2    .075       0 -5672.2     .05       0
 -1907.2     .12       0 -1788.5     .05       0   -93.8    .025       0
 8760.66     .05       0  9408.6     .03       0 10922.5     .05       0
 11768.9     .12       0   11786     .05       0
#XS Ineff= 2 , 0
         -577.03   330.211333.14          333.43
Permanent Ineff=
       F       F
Bank Sta=-93.8,8760.66
XS Rating Curve= 0 ,0
Exp/Cntr=0.3,0.1

Type RM Length L Ch R = 1 ,79420   ,6820,6820,6820
BEGIN DESCRIPTION:
Cedar Creek 16.0
END DESCRIPTION:
XS GIS Cut Line= 3
      2723651.04      6782786.02      2709766.23      6775562.26
      2701351.25      6771877.27
#Sta/Elev= 30
-10584.9  387.91 -9192.6  382.02 -9027.1  369.11   -8708  380.83 -7748.6  372.15
 -7527.4   368.5 -7197.7  367.32 -5674.7  358.79 -5224.8  343.43 -5040.2  366.44
 -3892.2  375.73   -3591  377.94 -2480.7  386.07 -2019.1  375.56 -1878.7  359.15
   -1746  370.35   -1313  365.12 -1036.6  365.31  -807.1  345.79    -597  354.41
  -378.2  343.39  213.19  321.87    2500   303.5    6500   303.5 7529.85  321.99
  9692.2  332.96 11341.2  324.26   11625  333.91 12399.8  325.61 14253.1  337.56
#Mann= 19 ,-1 , 0
-10584.9     .05       0 -7748.6      .1       0 -7527.4      .1       0
 -7197.7     .05       0 -5674.7      .1       0 -5040.2     .05       0
 -3892.2     .05       0   -3591     .05       0 -2019.1     .05       0
   -1746     .12       0   -1313     .05       0 -1036.6     .12       0
  -807.1      .1       0  -378.2     .12       0  213.19    .025       0
 7529.85    .035       0 11341.2     .12       0   11625     .05       0
 12399.8     .05       0
#XS Ineff= 2 , 0
                         9235.36          330.74
Permanent Ineff=
       F       F
Bank Sta=213.19,7529.85
XS Rating Curve= 0 ,0
Exp/Cntr=0.3,0.1

Type RM Length L Ch R = 1 ,72600   ,8194,8194,8194
BEGIN DESCRIPTION:
Cedar Creek 15.0
END DESCRIPTION:
XS GIS Cut Line= 3
      2721142.78      6774031.44      2713423.65      6770155.03
        2703251.        6766886.
#Sta/Elev= 30
 -3637.8  367.87 -3245.5  374.32 -2740.3  370.06   -2665  373.04 -2634.3  368.73
 -2293.8  357.17 -2265.1  354.55 -2074.9  350.57 -2000.5  346.85 -1965.5  351.83
 -1821.9  357.62 -1464.6  351.05 -1403.4  348.47 -1352.9  339.54 -1218.9  334.47
 -1001.2   352.5  -541.7  357.32  -183.7  351.04      26  335.65   263.9  325.67
   500.6  329.39   756.3  322.46    3100   302.8    7100   302.8 9155.77   322.4
 10224.8  334.53 11139.3  330.35 12256.9  337.02   13102  332.91   15685  338.69
#Mann= 9 ,-1 , 0
 -3637.8     .05       0 -2740.3     .12       0   -2665     .05       0
 -2293.8     .12       0 -2265.1     .05       0 -2074.9     .12       0
 -1965.5     .05       0   756.3    .025       0 9155.77     .05       0
Bank Sta=756.3,9155.77
XS Rating Curve= 0 ,0
Exp/Cntr=0.3,0.1

Type RM Length L Ch R = 1 ,64406   ,7398,7398,7398
BEGIN DESCRIPTION:
Cedar Creek 14.0
END DESCRIPTION:
XS GIS Cut Line= 4
      2728906.24      6770069.01      2717015.63      6763194.89
      2712338.13      6761739.13      2707051.02        6762736.
#Sta/Elev= 30
 -8753.8  364.19 -8185.1  353.41 -8083.1  336.41 -8051.6  342.32 -7810.4  327.74
 -7724.3  334.55 -7569.3  324.09 -7425.6  338.72 -7397.4  341.08 -7312.9  340.91
 -7200.1  333.44 -7193.3  332.66 -7087.4  322.36 -7028.1  322.32 -6989.1  334.28
 -6671.8  348.78   -6582  354.18 -6551.5  362.45 -5883.2   348.6 -5592.7  325.85
-4764.07   322.2     100     302    4100     302  9823.6     322 10044.6  331.38
 10390.6     318   11744     318 11876.3  329.67   12609  335.67 15259.9  334.61
#Mann= 12 ,-1 , 0
 -8753.8     .05       0 -7425.6     .12       0 -7397.4     .05       0
 -7312.9     .12       0 -7200.1     .05       0 -7193.3     .12       0
 -7087.4     .05       0 -6989.1      .1       0 -6671.8     .05       0
 -5883.2     .12       0-4764.07    .025       0  9823.6     .05       0
#XS Ineff= 2 , 0
                        10056.85          331.45
Permanent Ineff=
       F       F
Bank Sta=-4764.07,9823.6
XS Rating Curve= 0 ,0
Exp/Cntr=0.3,0.1

Type RM Length L Ch R = 1 ,57008   ,150,150,150
BEGIN DESCRIPTION:
Cedar Creek 13.5
END DESCRIPTION:
XS GIS Cut Line= 6
      2727340.21      6759551.33      2724756.89      6758280.51
      2717634.09      6756851.17      2714943.98      6757637.63
      2711857.18      6757659.33      2709995.13      6760315.11
#Sta/Elev= 30
 -2201.5  343.88 -2167.9  342.53  -982.1  340.85  -830.9  340.92  -194.6  340.09
  -184.5   339.9   -84.8  339.49    51.1  339.17   146.5  337.51   253.3  333.23
   388.2  332.67   483.6  327.24   579.1   325.7  607.34  323.38   611.6     322
    3650   301.3    7650   301.310579.71     322 10904.5  326.07 11594.7  322.98
12239.91  306.78 14258.1  307.23 14671.7  323.74 14735.2   326.7 14894.2  330.62
 15080.9  331.08 15593.6  332.71 16199.9   330.7 17055.8  335.16 17096.2  334.92
#Mann= 12 ,-1 , 0
 -2201.5     .12       0  -982.1     .05       0  -830.9     .12       0
  -194.6      .1       0  -184.5     .12       0   -84.8     .05       0
   611.6    .025       010579.71     .05       0 11594.7    .025       0
 14671.7     .12       0 15080.9     .05       0 17055.8      .1       0
Bank Sta=611.6,10579.71
XS Rating Curve= 0 ,0
Exp/Cntr=0.3,0.1

Type RM Length L Ch R = 1 ,56858   ,422,422,422
BEGIN DESCRIPTION:
Cedar Creek 13.0
END DESCRIPTION:
XS GIS Cut Line= 6
      2709558.71      6760433.16        2711551.        6757486.
      2714840.81      6757411.06        2717601.        6756686.
      2724858.74      6758096.84      2727458.31      6759336.07
#Sta/Elev= 27
 -2198.2     3411046.199  341.12  1099.6  341.281127.899  341.49  1155.8  341.32
  1333.1  340.721347.199  340.61  1392.1  340.91  1415.8  340.971427.899  340.88
1593.899  340.63    8000     340    8001   320.4   10223   320.4   10233     315
   10612     315   10622   320.4   12998   320.4   13000     340 16233.9     340
 16342.3     340 16418.4     340 16424.8  340.51 16614.2  340.31 16934.4  340.83
 17564.9  341.45 17812.1  341.69
#Mann= 8 ,-1 , 0
 -2198.2     .05       01593.899    .035       0    8001    .015       0
   13000    .035       0 16233.9     .12       0 16342.3     .05       0
 16614.2     .12       0 17564.9     .05       0
Bank Sta=8000,13000
XS Rating Curve= 0 ,0
Exp/Cntr=0.3,0.1