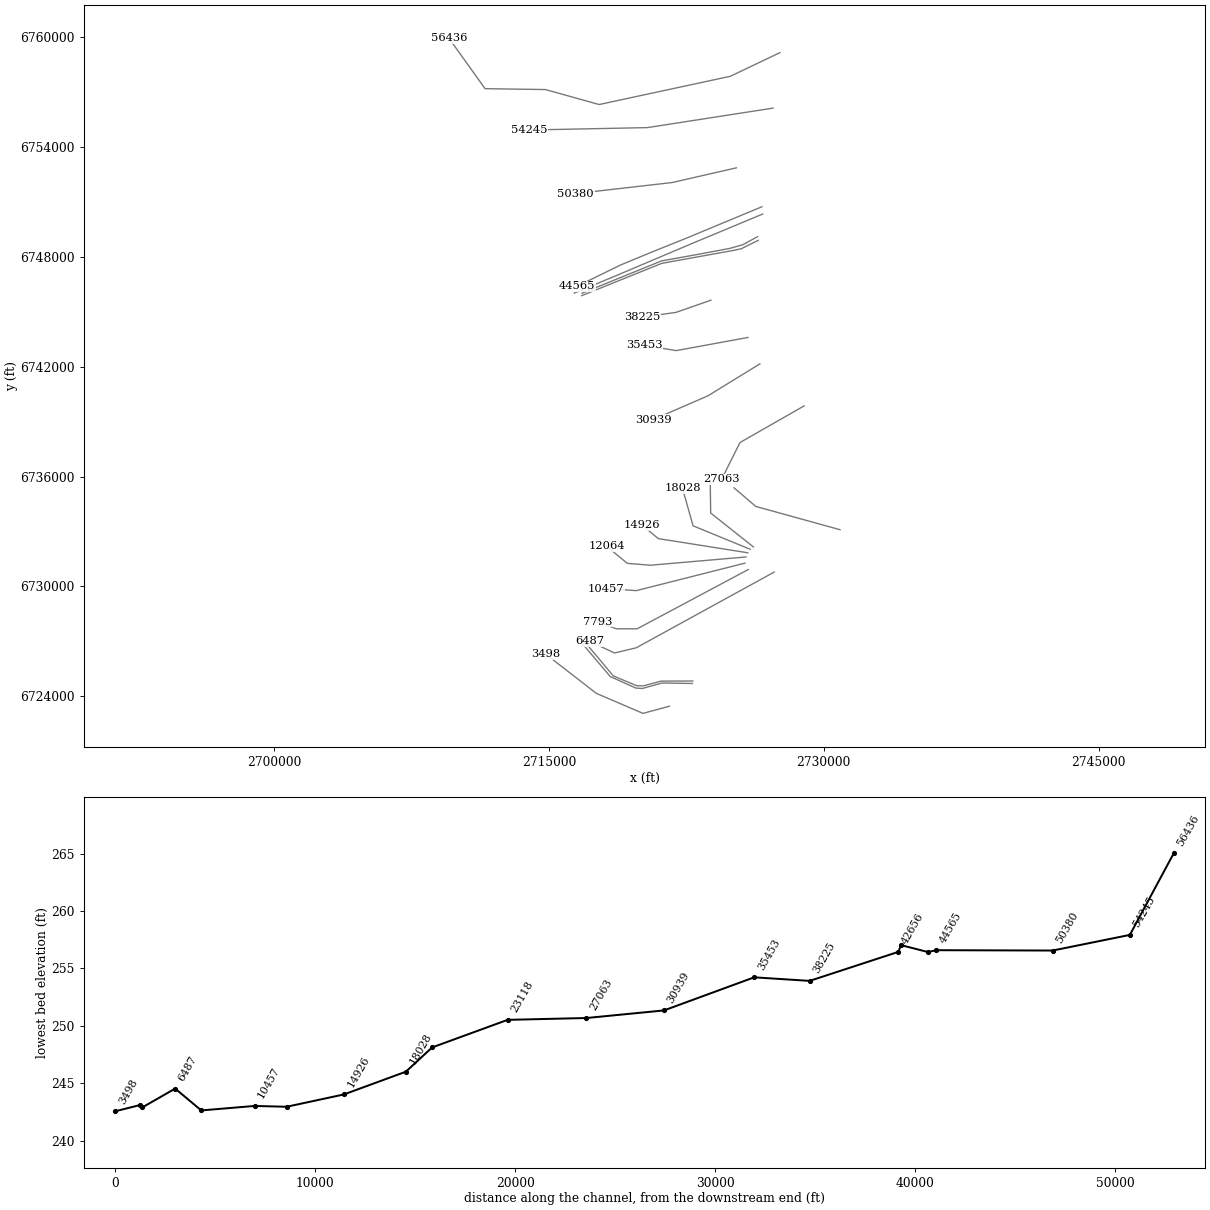
HEC-RAS study Cedar Creek.prj: Cedar Creek Base Level Engineering

--- Cedar Creek.g01 (geometry) --- (continued)

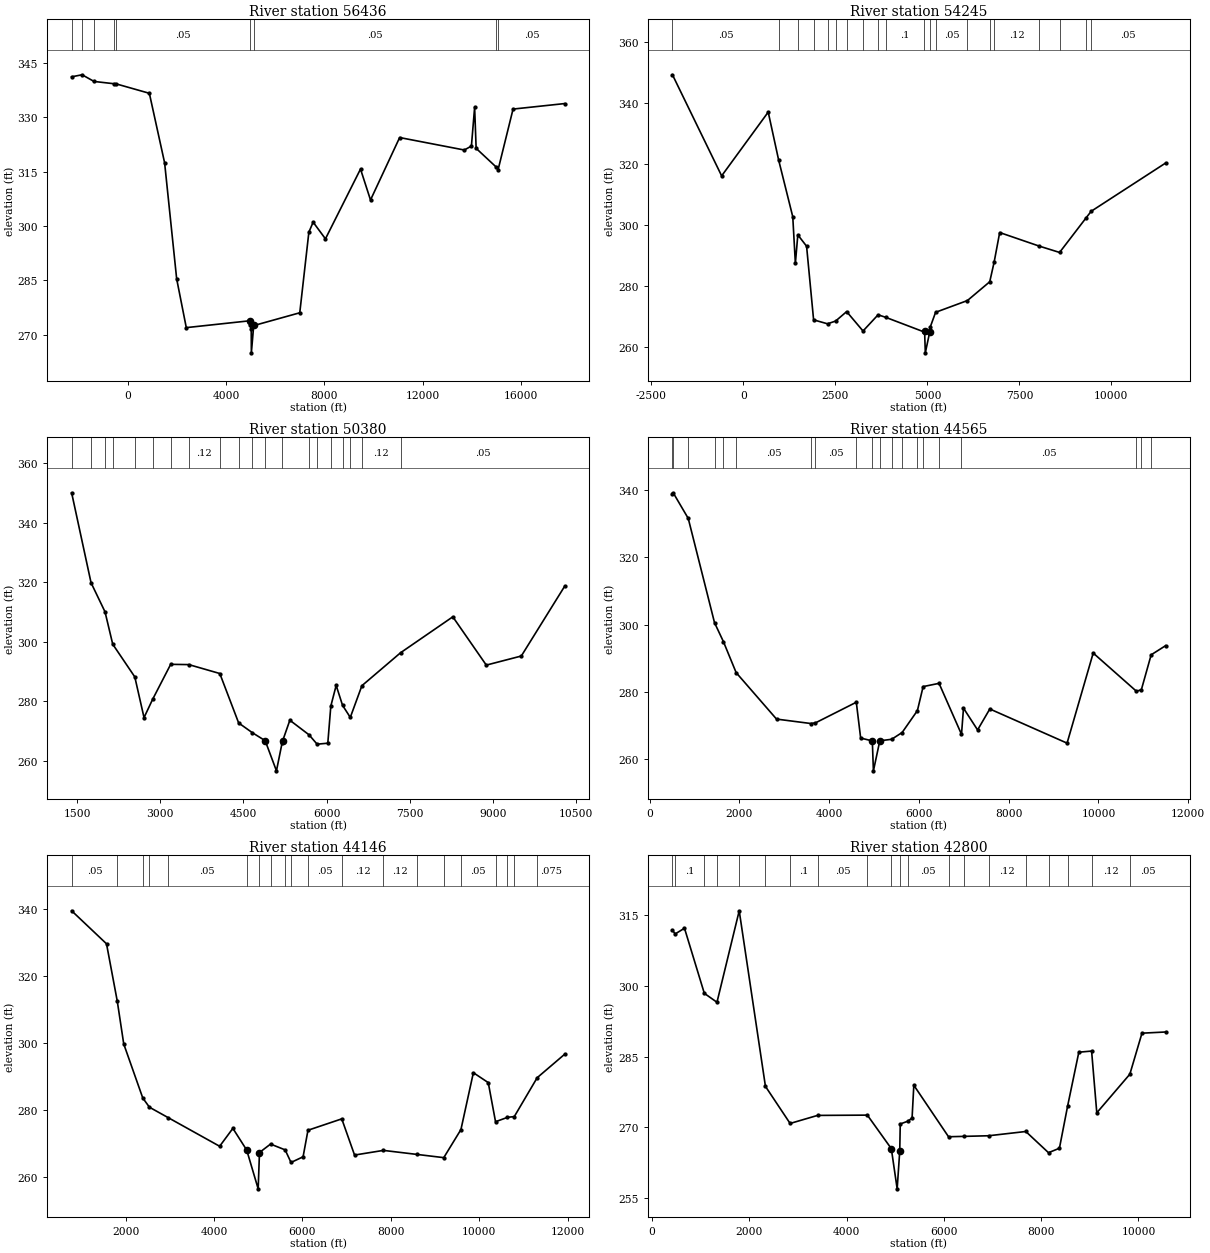
Type RM Length L Ch R = 1 ,56436   ,2191,2191,2191
BEGIN DESCRIPTION:
Cedar Creek 12.5
END DESCRIPTION:
XS GIS Cut Line= 6
       2727604.1       6759155.5      2724900.97      6757864.42
      2717737.68      6756321.02      2714808.31       6757138.8
      2711512.56      6757187.11      2709545.06      6759936.55
#Sta/Elev= 30
 -2282.5  341.22 -1856.6  341.78 -1370.6  339.94  -548.7   339.3  -477.9  339.28
   879.9  336.67  1501.3  317.47  1991.5  285.44  2383.2  271.97  4976.1  273.87
  4981.3  272.58    5026  271.49  5031.1  265.01  5130.3  272.81  5135.4  272.55
    7001  276.07  7371.1  298.32  7545.1  301.09  8045.7  296.48  9472.8  315.75
  9879.8  307.21 11065.3  324.45   13696  321.01   13986   322.1 14116.5  332.78
   14178  321.47 14975.7  316.42 15072.8   315.6 15680.7  332.31 17780.8  333.83
#Mann= 9 ,-1 , 0
 -2282.5     .05       0 -1856.6     .12       0 -1370.6     .05       0
  -548.7      .1       0  -477.9     .05       0  4981.3    .035       0
  5135.4     .05       0 14975.7     .12       0 15072.8     .05       0
Bank Sta=4976.1,5130.3
XS Rating Curve= 0 ,0
Exp/Cntr=0.3,0.1

Type RM Length L Ch R = 1 ,54245   ,3865,3865,3865
BEGIN DESCRIPTION:
Cedar Creek 12.0
END DESCRIPTION:
XS GIS Cut Line= 3
      2727226.91      6756124.58        2720376.        6755061.
      2713910.21       6754929.4
#Sta/Elev= 30
 -1928.6  349.38  -591.9  316.13   673.9  337.11   957.1  321.34    1341  302.69
  1411.9  287.33  1478.2  296.72  1716.5  292.99  1907.3  268.77  2285.9  267.47
  2505.9  268.38  2805.2  271.48  3250.8   265.1  3659.7  270.43  3863.1  269.62
  4913.3  264.78  4923.4   265.2  4943.7  257.92  5064.4  264.85  5074.4   266.3
  5222.8  271.25  6088.2  275.12  6694.5   281.3  6814.9  287.82  6964.8  297.49
  8033.9  293.05  8592.7  290.94  9319.8  302.42  9451.6  304.48 11471.5  320.33
#Mann= 20 ,-1 , 0
 -1928.6     .05       0   957.1     .12       0  1478.2      .1       0
  1907.3     .05       0  2285.9     .12       0  2505.9     .05       0
  2805.2     .12       0  3250.8     .05       0  3659.7     .12       0
  3863.1      .1       0  4913.3    .035       0  5074.4      .1       0
  5222.8     .05       0  6088.2      .1       0  6694.5     .05       0
  6814.9     .12       0  8033.9      .1       0  8592.7     .12       0
  9319.8      .1       0  9451.6     .05       0
Bank Sta=4923.4,5064.4
XS Rating Curve= 0 ,0
Exp/Cntr=0.3,0.1

Type RM Length L Ch R = 1 ,50380   ,5815,5815,5815
BEGIN DESCRIPTION:
Cedar Creek 11.0
END DESCRIPTION:
XS GIS Cut Line= 3
      2725228.84      6752863.42        2721726.        6752061.
      2716461.49      6751457.17
#Sta/Elev= 30
  1401.5  350.13  1751.8  319.85  2003.8  310.06  2142.8  299.17  2540.8  288.17
  2707.3  274.48  2862.4  280.62    3188   292.4  3514.7  292.31  4073.9  289.31
    4414  272.67  4662.9  269.37  4892.5  266.71  5095.7  256.56  5196.4  265.86
  5206.5   266.6  5337.3  273.59  5682.8  268.69  5829.2  265.53  6021.8  265.86
  6076.2  278.34  6172.7  285.31    6288   278.6  6427.4  274.54  6636.9  285.21
  7334.4   296.3  8276.4  308.39  8880.4  292.14    9512   295.2 10294.1  318.68
#Mann= 20 ,-1 , 0
  1401.5     .05       0  1751.8     .12       0  2003.8      .1       0
  2142.8     .12       0  2540.8      .1       0  2862.4     .12       0
    3188     .05       0  3514.7     .12       0  4073.9      .1       0
    4414     .12       0  4662.9     .12       0  4892.5    .035       0
  5196.4     .12       0  5682.8     .12       0  5829.2     .12       0
  6076.2     .12       0    6288      .1       0  6427.4     .12       0
  6636.9     .12       0  7334.4     .05       0
Bank Sta=4892.5,5206.5
XS Rating Curve= 0 ,0
Exp/Cntr=0.3,0.1

Type RM Length L Ch R = 1 ,44565   ,419,419,419
BEGIN DESCRIPTION:
Cedar Creek 10.5
END DESCRIPTION:
XS GIS Cut Line= 5
      2726620.16      6750736.66      2722475.26      6749012.24
      2720661.84      6748283.54      2718901.43      6747554.38
      2716536.97      6746396.39
#Sta/Elev= 30
   510.7  338.67   526.8  339.12   862.2  331.51  1447.5300.5598  1645.7294.9355
  1929.2285.7392  2828.5  271.95    3590  270.64  3696.1  270.83  4605.6  276.95
  4702.6  266.32    4945  265.53  4962.7  265.36  4986.6  256.59    5129  265.51
  5392.1 265.951  5626.5267.9687  5966.3  274.46    6094 281.593  6448.4  282.56
  6948.6  267.42  6993.1  275.19    7307  268.73  7579.1  274.95  9300.1  264.81
    9882  291.55 10846.5  280.19 10955.4  280.69 11173.2  291.03 11492.6  293.72
#Mann= 20 ,-1 , 0
   510.7     .05       0   526.8     .12       0   862.2     .05       0
  1447.5     .12       0  1645.7     .05       0  1929.2     .05       0
    3590     .12       0  3696.1     .05       0  4605.6     .07       0
    4945    .035       0    5129     .05       0  5392.1     .12       0
  5626.5     .12       0  5966.3      .1       0    6094     .05       0
  6448.4      .1       0  6948.6     .05       0 10846.5     .05       0
 10955.4     .12       0 11173.2     .05       0
Bank Sta=4962.7,5129
XS Rating Curve= 0 ,0
Exp/Cntr=0.3,0.1

Type RM Length L Ch R = 1 ,44146   ,1346,1346,1346
BEGIN DESCRIPTION:
Cedar Creek 10.0
END DESCRIPTION:
XS GIS Cut Line= 4
      2726667.07      6750340.85      2722771.51      6748716.13
      2718557.68      6746929.38      2716380.84      6746023.23
#Sta/Elev= 30
   779.2  339.39  1568.5  329.54  1812.2   312.4  1958.4  299.64  2388.6  283.54
  2539.7  280.78  2959.9   277.7  4128.3  269.13  4427.5  274.47  4740.5     268
    5000  256.43  5029.5  267.27  5280.4269.7874  5610.4  268.05    5743 264.298
  6016.1  265.99  6126.8  273.91  6891.3 277.306  7180.7  266.51  7833.9   267.9
  8599.3  266.69    9199265.7354  9587.6  274.11  9868.9  291.08   10206  288.12
 10370.6  276.45   10641  277.76   10795  277.99 11313.2  289.59 11934.9  296.59
#Mann= 20 ,-1 , 0
   779.2     .05       0  1812.2     .12       0  2388.6     .05       0
  2539.7     .12       0  2959.9     .05       0  4740.5    .035       0
  5029.5    .075       0  5280.4     .12       0  5610.4     .05       0
    5743      .1       0  6126.8     .05       0  6891.3     .12       0
  7833.9     .12       0  8599.3     .05       0    9199     .12       0
  9587.6     .05       0 10370.6     .12       0   10641     .12       0
   10795     .05       0 11313.2    .075       0
Bank Sta=4740.5,5029.5
XS Rating Curve= 0 ,0
Exp/Cntr=0.3,0.1

Type RM Length L Ch R = 1 ,42800   ,144,144,144
BEGIN DESCRIPTION:
Cedar Creek 9.6
END DESCRIPTION:
XS GIS Cut Line= 6
      2726385.62      6749106.25      2725580.53      6748663.56
      2724860.05      6748461.73      2723149.98      6748140.55
      2721138.26      6747779.41      2716801.06      6746014.44
#Sta/Elev= 30
   422.8  311.71   477.6   310.9     670  312.11  1077.8  298.35  1337.7296.4636
  1794.7   315.8  2333.7  278.69  2840.8  270.85    3405  272.55  4428.5  272.61
  4920.9  265.53  5040.9  257.03  5093.6  264.94  5104.7  270.74  5263.3271.3377
  5347.6  272.01  5383.4  278.92  6096.7  268.04  6421.2  268.12  6921.4  268.25
    7685  269.15  8151.5  264.67    8376  265.61  8545.5  274.59  8774.7  285.91
  9037.3  286.15  9143.9   273.1  9823.4  281.26 10072.5  289.93 10556.2  290.18
#Mann= 20 ,-1 , 0
   422.8     .12       0   477.6      .1       0  1077.8     .12       0
  1337.7      .1       0  1794.7      .1       0  2333.7     .12       0
  2840.8      .1       0    3405     .05       0  4428.5     .12       0
  4920.9    .035       0  5104.7      .1       0  5263.3     .05       0
  6096.7     .12       0  6421.2     .05       0  6921.4     .12       0
    7685     .05       0  8151.5     .12       0  8545.5     .05       0
  9037.3     .12       0  9823.4     .05       0
Bank Sta=4920.9,5093.6
XS Rating Curve= 0 ,0
Exp/Cntr=0.3,0.1

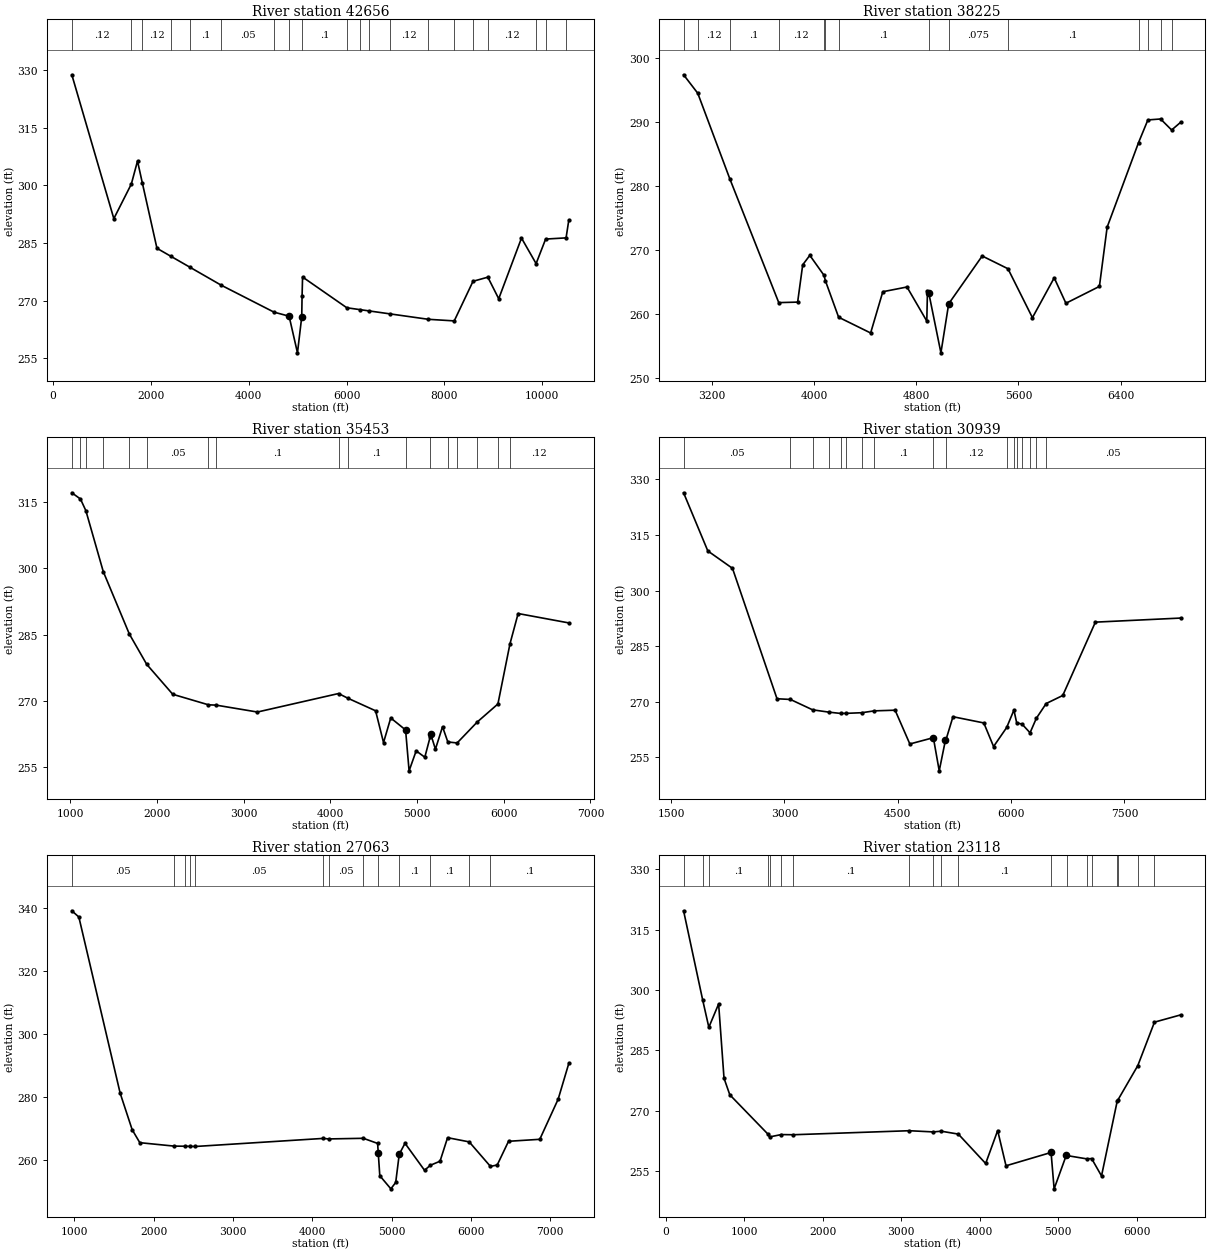
Type RM Length L Ch R = 1 ,42656   ,4431,4431,4431
BEGIN DESCRIPTION:
Cedar Creek 9.3
END DESCRIPTION:
XS GIS Cut Line= 6
       2726424.1      6748905.34      2725486.57      6748440.91
      2724909.31      6748323.72       2721975.7      6747795.94
      2721149.11      6747643.77      2716787.16      6745882.49
#Sta/Elev= 30
     384  328.76  1242.7  291.35  1600.6  300.34  1726.8  306.33  1826.4  300.57
  2124.4  283.63  2415.7   281.5  2793.8  278.74  3435.4  274.05  4517.9  267.02
  4822.6265.9819  4826.1  265.97  4997.1  256.44 5084.24   265.8  5091.2  271.18
  5101.4  276.16  6006.2  268.16  6284.7  267.66  6452.7  267.36  6883.9  266.58
  7674.6  265.16  8202.2264.7472  8586.3  275.05  8889.1  276.12  9111.5  270.51
  9577.2  286.29  9875.8  279.65 10070.6  286.03 10488.7  286.34 10544.6  290.99
#Mann= 20 ,-1 , 0
     384     .12       0  1600.6     .05       0  1826.4     .12       0
  2415.7      .1       0  2793.8      .1       0  3435.4     .05       0
  4517.9     .12       0  4822.6    .035       0  5091.2      .1       0
  6006.2     .05       0  6284.7     .12       0  6452.7     .05       0
  6883.9     .12       0  7674.6     .05       0  8202.2     .12       0
  8586.3     .12       0  8889.1     .12       0  9875.8     .12       0
 10070.6     .05       0 10488.7     .05       0
Bank Sta=4826.1,5084.24
XS Rating Curve= 0 ,0
Exp/Cntr=0.3,0.1

Type RM Length L Ch R = 1 ,38225   ,2772,2772,2772
BEGIN DESCRIPTION:
Cedar Creek 9.0
END DESCRIPTION:
XS GIS Cut Line= 3
      2723839.94      6745634.68      2721928.36      6744966.98
        2720076.        6744711.
#Sta/Elev= 30
  2975.8  297.33  3086.9  294.45  3337.5  281.12  3721.7  261.76  3869.7  261.84
  3909.4  267.66  3965.1  269.14  4076.4  266.02  4086.9  265.19  4190.8  259.48
  4441.7  257.02  4537.1  263.46  4726.6   264.2  4881.8  258.88  4887.1  263.61
  4897.2  263.28  4992.5  253.92  5053.5  261.58    5316  269.04  5517.9  267.05
  5709.7  259.41  5880.3  265.63  5972.1  261.66  6234.6  264.29  6295.2  273.54
  6541.1  286.73  6614.4  290.28    6714  290.43  6800.5  288.71  6870.6   289.9
#Mann= 14 ,-1 , 0
  2975.8      .1       0  3086.9     .12       0  3337.5      .1       0
  3721.7     .12       0  4076.4     .05       0  4086.9     .12       0
  4190.8      .1       0  4897.2    .035       0  5053.5    .075       0
  5517.9      .1       0  6541.1     .12       0  6614.4     .05       0
    6714      .1       0  6800.5     .05       0
Bank Sta=4897.2,5053.5
XS Rating Curve= 0 ,0
Exp/Cntr=0.3,0.1

Type RM Length L Ch R = 1 ,35453   ,4514,4514,4514
BEGIN DESCRIPTION:
Cedar Creek 8.0
END DESCRIPTION:
XS GIS Cut Line= 3
      2725860.37       6743599.1      2721946.49       6742880.8
      2720219.44      6743164.82
#Sta/Elev= 30
  1020.7  317.07  1120.3  315.66  1182.7  313.02  1383.1  299.26  1683.5285.1552
  1883.9   278.3  2184.2  271.53    2596  269.15  2684.3  269.08  3160.2  267.52
  4095.3   271.7  4201.1  270.66  4522.6   267.8  4614.1  260.62  4697.3  266.18
  4868.3  263.47  4908.9  254.23  4990.3  258.74  5090.1  257.31  5151.3  261.86
  5156.4  262.62  5212.5  259.13  5294.3   264.2  5355.4  260.76  5462.7  260.53
  5693.7  265.25  5932.8  269.34  6071.9  282.94  6165.9  289.78  6750.2  287.66
#Mann= 17 ,-1 , 0
  1020.7     .05       0  1120.3      .1       0  1182.7     .05       0
  1383.1     .12       0  1683.5      .1       0  1883.9     .05       0
    2596     .12       0  2684.3      .1       0  4095.3     .12       0
  4201.1      .1       0  4868.3    .035       0  5151.3     .05       0
  5355.4     .12       0  5462.7     .05       0  5693.7      .1       0
  5932.8     .05       0  6071.9     .12       0
Bank Sta=4868.3,5156.4
XS Rating Curve= 0 ,0
Exp/Cntr=0.3,0.1

Type RM Length L Ch R = 1 ,30939   ,3876,3876,3876
BEGIN DESCRIPTION:
Cedar Creek 7.0
END DESCRIPTION:
XS GIS Cut Line= 3
      2726511.36      6742155.94        2723676.        6740411.
      2720695.44      6739117.77
#Sta/Elev= 30
  1665.4  326.41  1986.2  310.71  2312.8  306.01  2902.1  270.81  3079.5  270.62
  3373.1  267.82  3594.6  267.18  3742.7  266.85    3819  266.87  4024.8  267.04
  4189.6  267.54  4465.2  267.72  4660.4   258.6  4971.6   260.3  5049.2  251.35
  5131.9  259.68  5137.3  259.65  5231.2  265.96  5639.3  264.28  5768.6  257.91
  5942.2  263.05  6037.9  267.75  6074.8  264.28  6144.7  263.98  6251.4  261.62
  6335.2  265.55  6464.9  269.52  6684.3  271.69  7116.2  291.49  8243.7  292.59
#Mann= 17 ,-1 , 0
  1665.4     .05       0  3079.5     .12       0  3373.1     .05       0
  3594.6     .12       0  3742.7     .05       0    3819     .12       0
  4024.8     .05       0  4189.6      .1       0  4971.6    .035       0
  5137.3     .12       0  5942.2     .12       0  6037.9      .1       0
  6074.8     .12       0  6144.7     .05       0  6251.4     .12       0
  6335.2      .1       0  6464.9     .05       0
Bank Sta=4971.6,5131.9
XS Rating Curve= 0 ,0
Exp/Cntr=0.3,0.1

Type RM Length L Ch R = 1 ,27063   ,3945,3945,3945
BEGIN DESCRIPTION:
Cedar Creek 6.0
END DESCRIPTION:
XS GIS Cut Line= 3
      2728926.01      6739861.01        2725426.        6737861.
        2724426.      6735861.01
#Sta/Elev= 30
   968.5  339.05  1057.1  337.07  1578.2  281.07  1729.4  269.48  1825.8  265.36
  2257.3  264.27  2396.3  264.23  2463.3  264.19  2525.8  264.15  4136.1  266.71
  4209.1  266.55  4644.8  266.75  4824.7  265.12 4833.07  261.97  4852.1  254.86
  4991.7  250.69  5052.7  252.72  5097.5  261.71  5170.1  265.16  5416.1  256.59
  5490.1  258.18  5611.8  259.47  5706.8  266.95  5979.7  265.61  6247.3  257.82
  6332.9  258.27  6475.4   265.8  6869.6  266.43  7101.5  279.19  7235.7  290.56
#Mann= 13 ,-1 , 0
   968.5     .05       0  2257.3     .12       0  2396.3     .05       0
  2463.3     .12       0  2525.8     .05       0  4136.1     .12       0
  4209.1     .05       0  4644.8      .1       0  4824.7    .035       0
  5097.5      .1       0  5490.1      .1       0  5979.7     .12       0
  6247.3      .1       0
Bank Sta=4833.07,5097.5
XS Rating Curve= 0 ,0
Exp/Cntr=0.3,0.1

Type RM Length L Ch R = 1 ,23118   ,3779,3779,3779
BEGIN DESCRIPTION:
Cedar Creek 5.0
END DESCRIPTION:
XS GIS Cut Line= 3
      2730886.53      6733098.32        2726286.      6734370.71
        2725101.        6735386.
#Sta/Elev= 30
   225.8  319.66   469.7  297.44   547.7  290.69   672.5   296.5   741.1  278.03
   814.9  273.91  1300.5  264.14    1321  263.43  1470.3  264.02    1624  263.98
  3102.1  264.98  3409.2  264.68  3508.8  264.86  3727.3  264.14  4075.6  256.83
  4228.6  265.02    4335  256.26  4903.4  259.54  4908.6  259.69  4948.1  250.53
  5105.2  258.99  5112.9   258.8    5364  257.98  5426.1  258.05  5552.1  253.74
    5753  272.42  5759.4  272.57  6014.6  281.17  6226.8  291.97  6559.5  293.77
#Mann= 19 ,-1 , 0
   225.8      .1       0   469.7     .12       0   547.7      .1       0
  1300.5     .12       0    1321      .1       0  1470.3     .12       0
    1624      .1       0  3102.1     .12       0  3409.2     .05       0
  3508.8     .12       0  3727.3      .1       0  4903.4    .035       0
  5112.9      .1       0    5364      .1       0  5426.1     .12       0
    5753      .1       0  5759.4     .05       0  6014.6      .1       0
  6226.8     .05       0
Bank Sta=4908.6,5105.2
XS Rating Curve= 0 ,0
Exp/Cntr=0.3,0.1

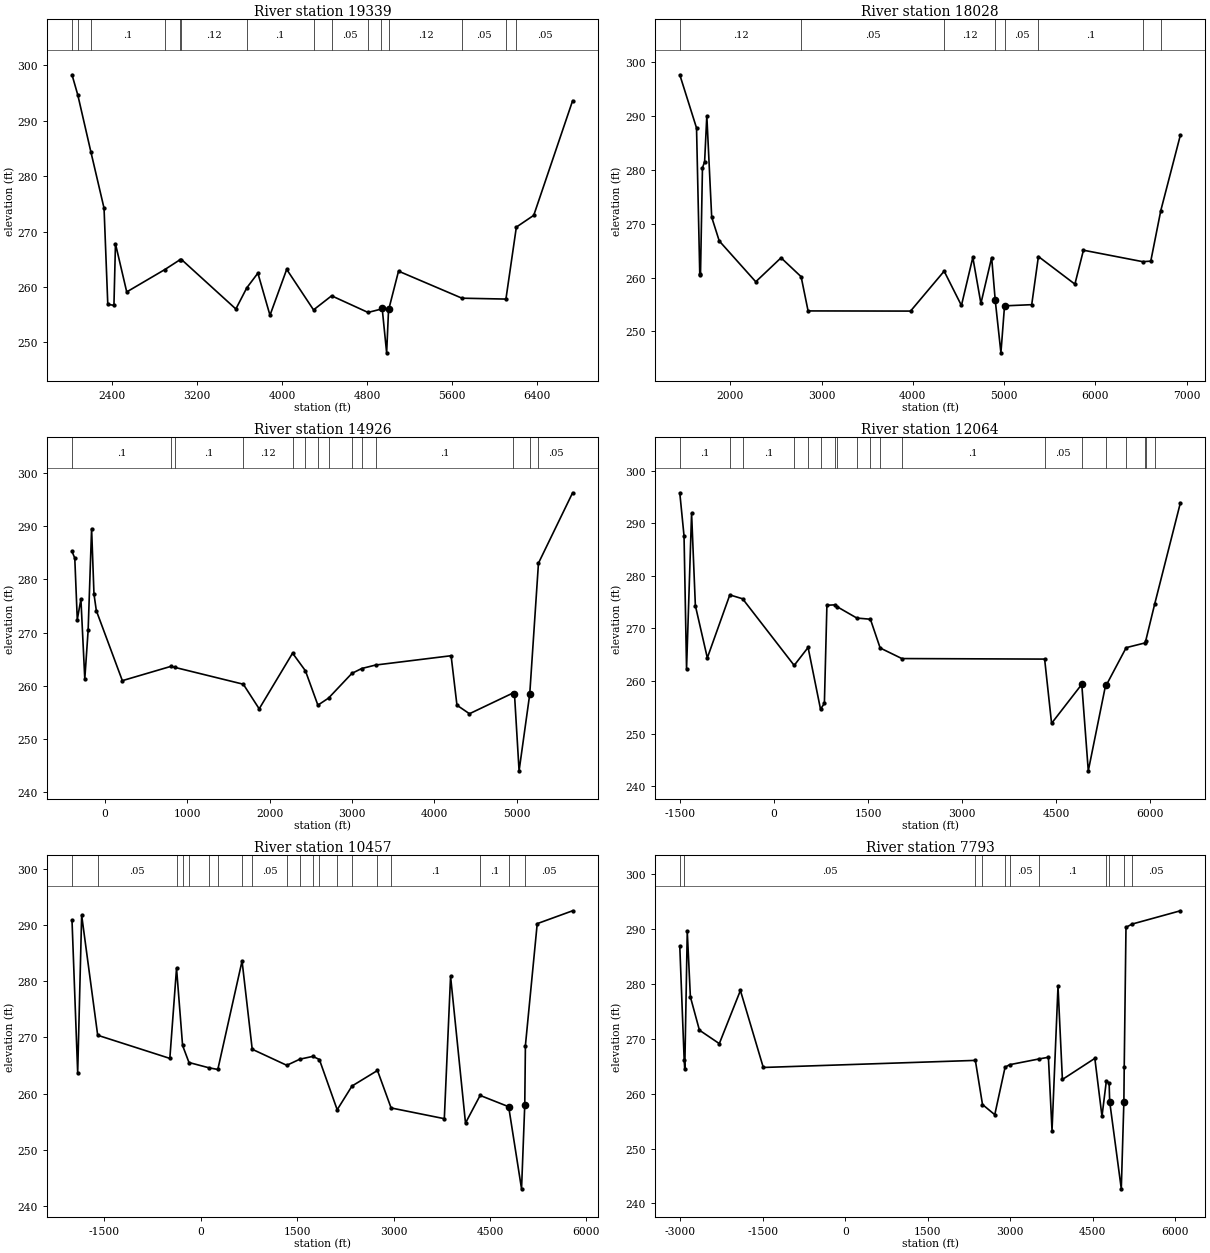
Type RM Length L Ch R = 1 ,19339   ,1311,1311,1311
BEGIN DESCRIPTION:
Cedar Creek 4.0
END DESCRIPTION:
XS GIS Cut Line= 3
      2726156.48      6732158.78        2723826.        6734011.
        2723801.      6735736.03
#Sta/Elev= 30
  2028.7   298.3  2083.1  294.65  2205.2  284.45  2329.6  274.23  2364.8  256.88
  2422.5   256.7  2436.9  267.81  2542.6  259.12    2899  263.14  3040.2  264.89
  3056.8  264.97  3567.8  256.04  3670.4  259.86  3774.5  262.51  3888.2  254.91
  4045.2  263.19  4297.3  255.88  4467.1  258.42    4809  255.42  4934.3  256.03
  4941.7  256.23    4984  248.13  5002.4  256.11  5005.6  256.11  5095.6  262.87
  5691.4  257.99  6104.4  257.83  6202.4  270.82  6365.7  272.94  6730.8  293.62
#Mann= 15 ,-1 , 0
  2028.7      .1       0  2083.1     .12       0  2205.2      .1       0
    2899     .12       0  3040.2      .1       0  3056.8     .12       0
  3670.4      .1       0  4297.3     .12       0  4467.1     .05       0
    4809     .12       0  4934.3    .035       0  5005.6     .12       0
  5691.4     .05       0  6104.4     .12       0  6202.4     .05       0
Bank Sta=4941.7,5002.4
XS Rating Curve= 0 ,0
Exp/Cntr=0.3,0.1

Type RM Length L Ch R = 1 ,18028   ,3102,3102,3102
BEGIN DESCRIPTION:
Cedar Creek 3.7
END DESCRIPTION:
XS GIS Cut Line= 3
      2725975.86      6732033.82      2722864.79      6733311.58
       2722288.4      6735353.23
#Sta/Elev= 30
  1446.2  297.63  1629.8  287.75  1665.1   260.7  1673.1   260.5  1694.7  280.35
  1718.4  281.51  1742.4  290.03  1795.8  271.21  1878.5  266.79  2278.5  259.21
  2555.8  263.66  2775.7  260.15  2851.9   253.8  3974.6  253.77  4342.6  261.18
    4532  254.81  4656.8  263.73  4745.4  255.19  4863.1  263.71  4902.4  255.76
  4964.7  246.02  5004.2  254.74  5302.1  254.96  5375.3   263.9  5775.2  258.77
  5868.7  265.07  6518.6  262.94  6606.5  263.04  6716.2  272.42  6930.9  286.44
#Mann= 8 ,-1 , 0
  1446.2     .12       0  2775.7     .05       0  4342.6     .12       0
  4902.4    .035       0  5004.2     .05       0  5375.3      .1       0
  6518.6     .12       0  6716.2     .05       0
Bank Sta=4902.4,5004.2
XS Rating Curve= 0 ,0
Exp/Cntr=0.3,0.1

Type RM Length L Ch R = 1 ,14926   ,2862,2862,2862
BEGIN DESCRIPTION:
Cedar Creek 3.2
END DESCRIPTION:
XS GIS Cut Line= 3
      2725849.19      6731839.36      2720970.69      6732611.93
      2720093.95      6733332.42
#Sta/Elev= 30
    -398  285.23  -364.4  283.97    -334  272.43    -290  276.28  -242.9  261.29
  -202.4  270.41  -160.3  289.51  -131.5  277.24    -103  274.12   212.7  260.97
   801.9  263.65   853.1  263.45  1680.4   260.3  1873.1  255.68  2278.3  266.13
  2434.1  262.82  2585.4  256.37  2714.3  257.69  2998.3  262.34  3117.1  263.25
  3284.9   263.9  4201.8  265.65  4272.7  256.36  4424.5  254.76  4956.2  258.68
  4970.5  258.52  5026.5  244.04  5155.6   258.4  5261.8  283.03  5676.1  296.24
#Mann= 14 ,-1 , 0
    -398      .1       0   801.9     .12       0   853.1      .1       0
  1680.4     .12       0  2278.3      .1       0  2434.1     .12       0
  2585.4     .05       0  2714.3     .12       0  2998.3      .1       0
  3117.1     .12       0  3284.9      .1       0  4956.2    .035       0
  5155.6      .1       0  5261.8     .05       0
Bank Sta=4970.5,5155.6
XS Rating Curve= 0 ,0
Exp/Cntr=0.3,0.1

Type RM Length L Ch R = 1 ,12064   ,1607,1607,1607
BEGIN DESCRIPTION:
Cedar Creek 3.0
END DESCRIPTION:
XS GIS Cut Line= 4
      2725753.64      6731610.19      2720531.45       6731158.8
        2719276.        6731261.      2718132.13      6732203.96
#Sta/Elev= 30
 -1501.4  295.77 -1433.5  287.56 -1393.4  262.34 -1313.1  291.89 -1252.8  274.34
 -1062.1  264.42  -703.5  276.38  -499.4  275.64     323  262.99   544.9   266.4
   743.2  254.67   804.8  255.79     845  274.41   971.1  274.49  1009.8  274.12
  1322.5  271.98  1538.6  271.76  1694.1   266.3  2040.5  264.29  4317.3  264.19
    4428  251.99  4909.6   259.4  5013.5  242.97  5291.1  259.33  5297.9  259.18
  5617.7  266.36  5925.2  267.28  5927.9  267.58  6071.8  274.61  6482.3  293.86
#Mann= 19 ,-1 , 0
 -1501.4      .1       0  -703.5     .12       0  -499.4      .1       0
     323     .12       0   544.9     .05       0   743.2      .1       0
   971.1     .05       0  1009.8      .1       0  1322.5     .12       0
  1538.6      .1       0  1694.1     .12       0  2040.5      .1       0
  4317.3     .05       0  4909.6    .035       0  5297.9     .05       0
  5617.7     .12       0  5925.2      .1       0  5927.9     .12       0
  6071.8     .05       0
Bank Sta=4909.6,5291.1
XS Rating Curve= 0 ,0
Exp/Cntr=0.3,0.1

Type RM Length L Ch R = 1 ,10457   ,2664,2664,2664
BEGIN DESCRIPTION:
Cedar Creek 2.5
END DESCRIPTION:
XS GIS Cut Line= 3
       2725691.6      6731271.43       2719766.7      6729771.48
       2718093.1      6729882.59
#Sta/Elev= 30
 -2004.8  290.84 -1916.5  263.69 -1854.6  291.75 -1605.2  270.38  -482.6  266.26
  -378.4  282.32  -284.3  268.56  -184.9  265.53   125.3  264.59   263.9  264.29
     641   283.6     799  267.89  1336.9  265.03  1539.8  266.12  1742.7  266.62
  1844.2  266.06  2121.2  257.12  2351.4  261.34    2748  264.11  2960.1  257.44
    3788  255.53  3885.4  280.88  4117.7  254.75  4345.2  259.67  4789.2  257.66
  4989.7  243.04  5039.8  258.02  5049.8  268.55  5233.6  290.25  5784.3  292.54
#Mann= 20 ,-1 , 0
 -2004.8      .1       0 -1605.2     .05       0  -378.4      .1       0
  -284.3     .05       0  -184.9     .12       0   125.3     .05       0
   263.9     .12       0     641     .05       0     799     .05       0
  1336.9     .12       0  1539.8      .1       0  1742.7     .12       0
  1844.2      .1       0  2121.2     .05       0  2351.4     .12       0
    2748     .05       0  2960.1      .1       0  4345.2      .1       0
  4789.2    .035       0  5049.8     .05       0
Bank Sta=4789.2,5039.8
XS Rating Curve= 0 ,0
Exp/Cntr=0.3,0.1

Type RM Length L Ch R = 1 ,7793    ,1306,1306,1306
BEGIN DESCRIPTION:
Cedar Creek 2.0
END DESCRIPTION:
XS GIS Cut Line= 4
      2725876.06      6730924.22      2719815.31      6727688.15
       2718675.7      6727686.12      2717649.36      6728070.36
#Sta/Elev= 30
 -3009.5  286.91 -2929.8  266.21 -2918.7  264.45 -2873.4  289.59 -2816.6  277.66
 -2652.3  271.58 -2290.5  269.13 -1906.7  278.82 -1490.4  264.78  2366.9  266.07
    2497  258.02  2720.1  256.17    2908  264.83  2988.6  265.28  3533.5  266.35
  3695.9  266.64  3761.7  253.28  3870.4  279.57  3950.4  262.59  4540.4  266.44
  4670.4  255.87  4749.3  262.27  4800.4  261.94  4810.4  258.56  5021.7  242.65
 5068.67  258.52  5075.1  264.93  5107.1  290.33  5216.1  290.92  6096.6  293.35
#Mann= 11 ,-1 , 0
 -3009.5     .12       0 -2929.8     .05       0  2366.9     .12       0
    2497     .05       0    2908     .12       0  2988.6     .05       0
  3533.5      .1       0  4749.3     .12       0  4800.4    .035       0
  5075.1     .05       0  5216.1     .05       0
Bank Sta=4810.4,5068.67
XS Rating Curve= 0 ,0
Exp/Cntr=0.3,0.1

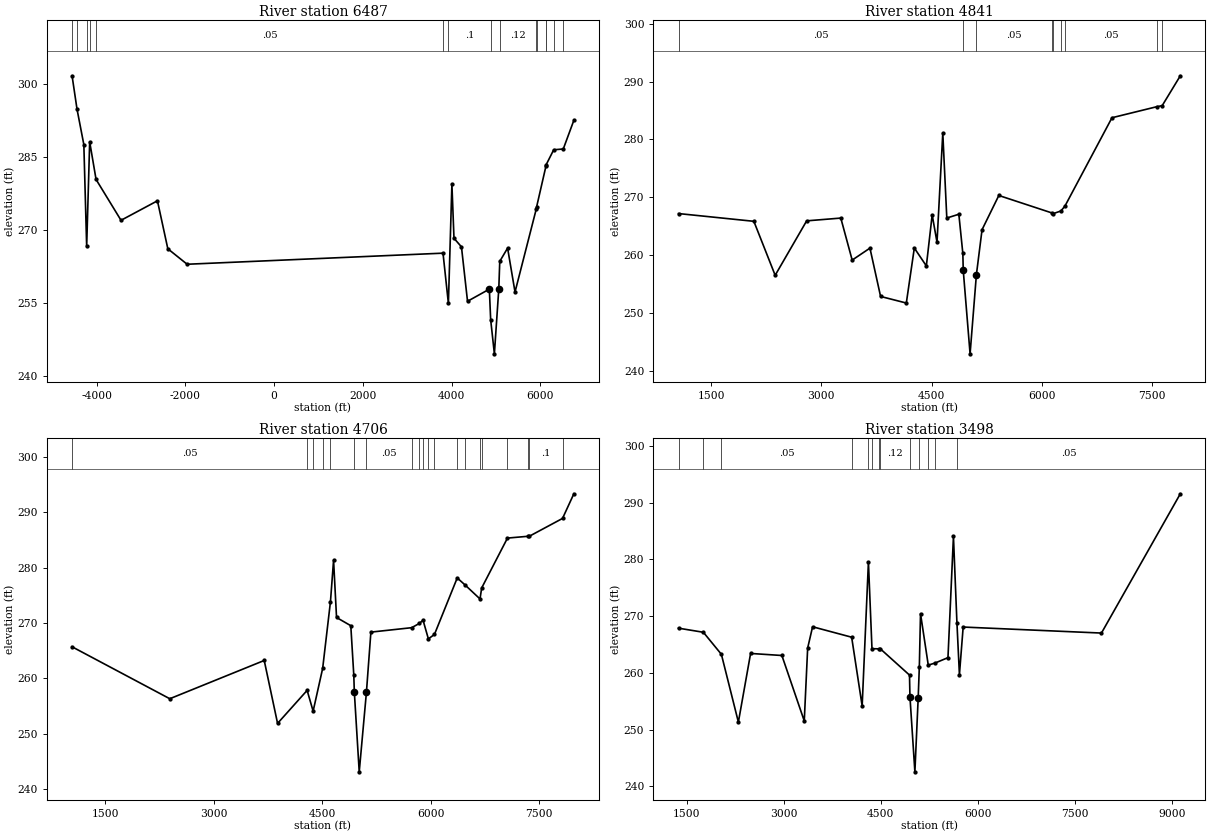
Type RM Length L Ch R = 1 ,6487    ,1646,1646,1646
BEGIN DESCRIPTION:
Cedar Creek 1.5
END DESCRIPTION:
XS GIS Cut Line= 4
      2727292.31      6730784.29       2719763.8      6726649.63
      2718574.86       6726366.1      2717224.21      6727001.49
#Sta/Elev= 30
 -4551.2  301.75 -4439.8  294.89   -4286  287.59 -4222.2  266.64 -4154.5  288.17
 -4010.5  280.42 -3448.4  272.02 -2627.9  276.03 -2393.9  266.16   -1959  262.98
  3805.3  265.26  3926.4  254.92  4005.5  279.45  4052.4  268.32  4220.8  266.56
  4357.5  255.36 4848.84  257.86  4878.7  251.58  4962.5  244.55 5062.05  257.95
  5083.7  263.58  5260.3   266.3  5427.4  257.27  5904.6  274.29  5911.9   274.7
  6125.8  283.23    6131  283.49    6299  286.53  6514.5  286.69  6752.9  292.59
#Mann= 15 ,-1 , 0
 -4551.2     .05       0 -4439.8     .12       0 -4222.2     .05       0
 -4154.5     .12       0 -4010.5     .05       0  3805.3     .12       0
  3926.4      .1       0  4878.7    .035       0  5083.7     .12       0
  5904.6     .05       0  5911.9      .1       0  6125.8     .05       0
    6131     .12       0    6299      .1       0  6514.5     .05       0
Bank Sta=4848.84,5062.05
XS Rating Curve= 0 ,0
Exp/Cntr=0.3,0.1

Type RM Length L Ch R = 1 ,4841    ,135,135,135
BEGIN DESCRIPTION:
Cedar Creek 1.0
END DESCRIPTION:
XS GIS Cut Line= 6
      2722850.96      6724835.17      2721119.19      6724829.96
      2720141.06      6724567.55      2719779.95      6724580.14
      2718511.01      6725113.48      2717005.66      6726911.28
#Sta/Elev= 30
  1056.6  267.18  2081.6  265.84  2371.6   256.5  2800.3  265.92  3264.8   266.4
  3419.6  259.13  3661.4   261.2  3806.2  252.84  4156.4   251.7  4265.3  261.22
    4429  258.12  4508.2  266.95    4574  262.22  4652.7  281.12  4707.3  266.41
  4871.1  267.06  4925.6  260.28    4931  257.37  5024.1  242.91  5109.9  256.59
    5187  264.39  5415.3  270.31  6134.9   267.3  6155.8  267.17  6260.1  267.63
  6314.4  268.46  6955.1  283.76  7568.6  285.68  7638.2  285.85  7885.2  291.02
#Mann= 9 ,-1 , 0
  1056.6     .05       0  4925.6    .035       0  5109.9     .05       0
  6134.9     .12       0  6155.8     .05       0  6260.1     .12       0
  6314.4     .05       0  7568.6      .1       0  7638.2     .05       0
Bank Sta=4931,5109.9
XS Rating Curve= 0 ,0
Exp/Cntr=0.3,0.1

Type RM Length L Ch R = 1 ,4706    ,1208,1208,1208
BEGIN DESCRIPTION:
Cedar Creek 0.8
END DESCRIPTION:
XS GIS Cut Line= 6
      2722827.49      6724699.76      2721171.27       6724725.8
      2720090.28      6724426.06      2719734.38       6724452.1
      2718344.19      6725077.97      2716875.46      6726812.31
#Sta/Elev= 30
  1040.8  265.69  2392.5  256.31  3698.9  263.22  3883.5  251.86  4292.3  257.82
  4375.3  254.07  4507.2  261.79  4615.2  273.85  4658.1  281.31  4699.2  270.98
  4896.4   269.5  4937.7  260.61  4945.1  257.57    5013  243.11  5112.7   257.5
  5174.3  268.34  5738.4  269.14  5843.6   269.9  5895.9  270.49  5969.5  267.12
  6053.5  267.92  6368.6  278.12  6472.8276.9066  6683.6  274.33  6707.1  276.32
  7063.5  285.32  7342.8  285.64  7367.2  285.66  7825.3  288.87    7982  293.32
#Mann= 20 ,-1 , 0
  1040.8     .05       0  4292.3     .12       0  4375.3     .05       0
  4507.2     .12       0  4615.2     .05       0  4937.7    .035       0
  5112.7     .05       0  5738.4     .12       0  5843.6     .05       0
  5895.9      .1       0  5969.5     .05       0  6053.5      .1       0
  6368.6      .1       0  6472.8     .05       0  6683.6     .12       0
  6707.1     .05       0  7063.5      .1       0  7342.8     .05       0
  7367.2      .1       0  7825.3     .05       0
Bank Sta=4945.1,5112.7
XS Rating Curve= 0 ,0
Exp/Cntr=0.3,0.1

Type RM Length L Ch R = 1 ,3498    ,0,0,0
BEGIN DESCRIPTION:
Cedar Creek 0.5
END DESCRIPTION:
XS GIS Cut Line= 4
      2721573.19        6723458.      2720130.04      6723067.38
      2717582.31      6724161.63      2714824.03       6726300.9
#Sta/Elev= 30
    1372  267.88  1755.8  267.16  2034.4  263.28  2297.3  251.34  2486.2  263.43
  2969.9  263.07    3316  251.54  3368.5  264.38  3444.6  268.13  4048.8  266.29
  4211.1  254.18    4308  279.53  4362.9  264.27  4471.7  264.24  4494.5  264.22
  4943.1  259.62  4950.2  255.77  5026.4  242.58 5077.72  255.67  5095.3  261.13
  5113.4  270.44  5233.3  261.37  5342.1  261.76  5537.9  262.69  5622.6  284.03
  5676.3  268.87  5714.9   259.7  5772.8  268.08  7910.9  267.02  9130.5  291.55
#Mann= 13 ,-1 , 0
    1372     .05       0  1755.8     .12       0  2034.4     .05       0
  4048.8     .12       0    4308     .05       0  4362.9     .12       0
  4471.7     .05       0  4494.5     .12       0  4943.1    .035       0
  5095.3     .05       0  5233.3     .05       0  5342.1      .1       0
  5676.3     .05       0
Bank Sta=4950.2,5077.72
XS Rating Curve= 0 ,0
Exp/Cntr=0.3,0.1

Chan Stop Cuts=-1
Use User Specified Reach Order=0
Composite Channel Slope=5