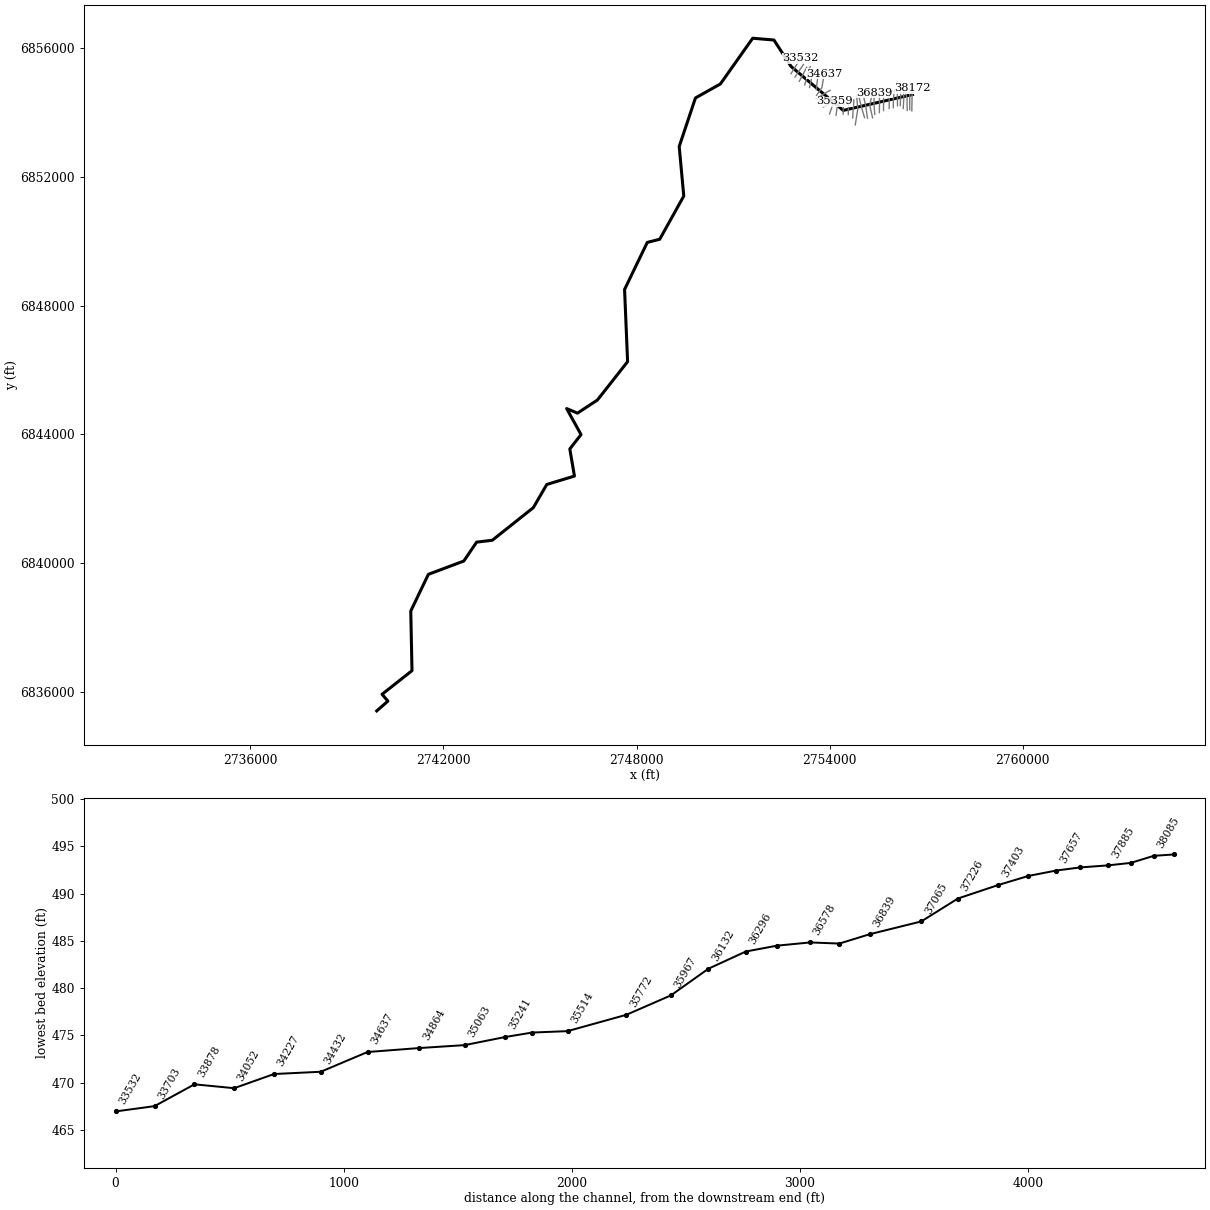
--- Chamblee Creek.prj (project) ---

Proj Title=Chamblee Creek Base Level Engineering
Current Plan=p01
Default Exp/Contr=0.3,0.1
English Units
Geom File=g01
Flow File=f01
Plan File=p01
BEGIN DESCRIPTION:
Chamblee Creek
END DESCRIPTION:

--- Chamblee Creek.p01 (plan) ---

Plan Title=Multiple Run
Short Identifier=Multiple
Geom File=g01
Flow File=f01
Subcritical Flow
K Sum by GR= 0
Std Step Tol= 0.01
Critical Tol= 0.01
Num of Std Step Trials= 20
Max Error Tol= 0.3
Flow Tol Ratio= 0.001
Split Flow NTrial= 30
Split Flow Tol= 0.02
Split Flow Ratio= 0.02
Log Output Level= 0
Friction Slope Method= 1
Unsteady Friction Slope Method= 2
Unsteady Bridges Friction Slope Method= 1
Parabolic Critical Depth
Global Vel Dist=  1 , 1 , 1
Global Log Level= 0
CheckData=True
Encroach Param= -1, 0, 0, 0
BEGIN DESCRIPTION:
Multiple Run
END DESCRIPTION:

--- Chamblee Creek.f01 (steady flow) ---

Flow Title=Multiple
Number of Profiles=7
Profile Names=10-year,25-year,50-year,1pct_min,100-year,1pct_plu,500-year
River Rch & RM= Chamblee Creek,Reach-1,38172
     605     821     998     604    1204    2403    1757
River Rch & RM= Chamblee Creek,Reach-1,34227
     710     970    1185     719    1435    2864    2112
River Rch & RM= Chamblee Creek,Reach-1,32042
    1019    1414    1744    1068    2130    4250    3187
River Rch & RM= Chamblee Creek,Reach-1,28412
    1267    1771    2197    1350    2694    5376    4067
River Rch & RM= Chamblee Creek,Reach-1,24339
    1390    1949    2421    1490    2973    5933    4500
River Rch & RM= Chamblee Creek,Reach-1,21625
    1453    2033    2522    1549    3092    6169    4662
River Rch & RM= Chamblee Creek,Reach-1,19002
    1523    2131    2644    1624    3239    6463    4880
River Rch & RM= Chamblee Creek,Reach-1,14963
    1593    2223    2753    1687    3365    6715    5046
River Rch & RM= Chamblee Creek,Reach-1,9938
    1692    2365    2932    1798    3587    7157    5388
River Rch & RM= Chamblee Creek,Reach-1,5822
    1801    2522    3130    1921    3834    7649    5769
River Rch & RM= Chamblee Creek,Reach-1,3139
    2480    3505    4374    2692    5371   10717    8105
Boundary for River Rch & Prof#=Chamblee Creek,Reach-1,1
Up Type=0
Dn Type=3
Dn Slope=0.005
Boundary for River Rch & Prof#=Chamblee Creek,Reach-1,2
Up Type=0
Dn Type=3
Dn Slope=0.005
Boundary for River Rch & Prof#=Chamblee Creek,Reach-1,3
Up Type=0
Dn Type=3
Dn Slope=0.005
Boundary for River Rch & Prof#=Chamblee Creek,Reach-1,4
Up Type=0
Dn Type=3
Dn Slope=0.005
Boundary for River Rch & Prof#=Chamblee Creek,Reach-1,5
Up Type=0
Dn Type=3
Dn Slope=0.005
Boundary for River Rch & Prof#=Chamblee Creek,Reach-1,6
Up Type=0
Dn Type=3
Dn Slope=0.005
Boundary for River Rch & Prof#=Chamblee Creek,Reach-1,7
Up Type=0
Dn Type=3
Dn Slope=0.005

--- Chamblee Creek.g01 (geometry) ---

Geom Title=Existing Conditions

River Reach=Chamblee Creek,Reach-1
Reach XY= 30
      2756576.00      6854561.00      2754422.65      6854068.98
      2752802.33      6855434.29      2752270.42      6856255.42
      2751610.82      6856311.44      2750606.40      6854890.83
      2749831.26      6854455.53      2749326.48      6852947.27
      2749468.27      6851407.35      2748720.96      6850065.94
      2748333.80      6849967.21      2747628.39      6848505.47
      2747722.47      6846262.45      2746785.68      6845071.76
      2746164.14      6844662.49      2745828.13      6844805.57
      2746275.48      6843997.14      2745926.97      6843551.13
      2746070.55      6842707.99      2745212.31      6842447.57
      2744792.80      6841727.42      2743518.01      6840714.23
      2743031.41      6840655.83      2742632.48      6840068.69
      2741531.58      6839655.42      2740984.04      6838514.32
      2741022.47      6836662.47      2740091.93      6835927.91
      2740274.47      6835716.78      2739926.00      6835411.00

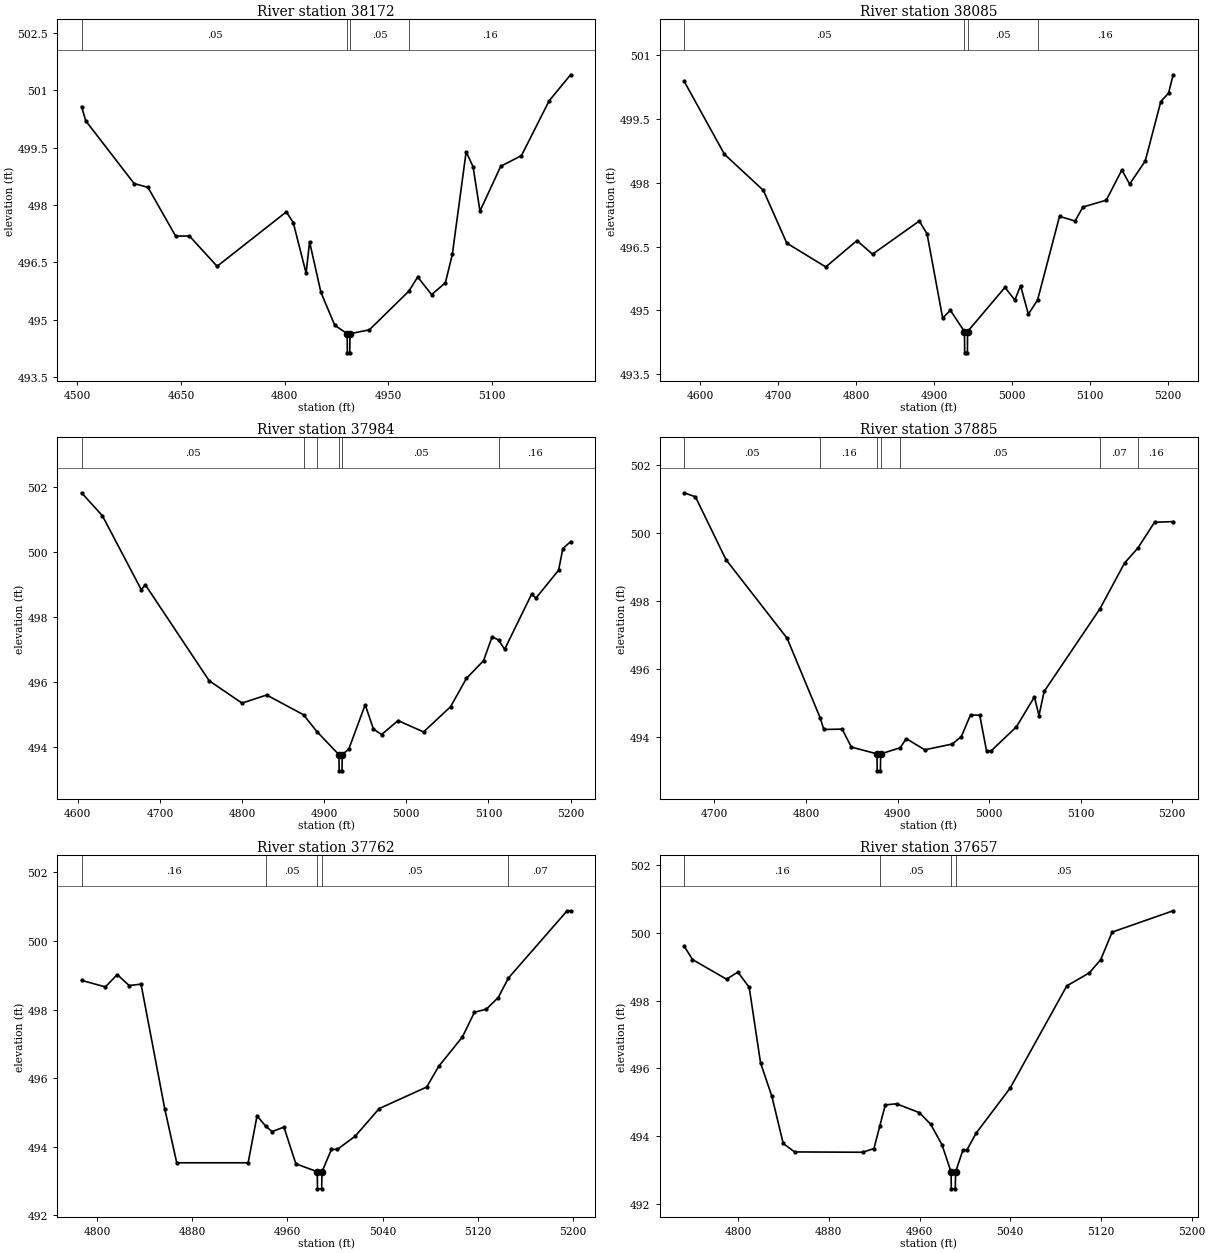
Type RM Length L Ch R = 1,38172,87,87,87
BEGIN DESCRIPTION:
Chamblee Creek38171.525
END DESCRIPTION:
XS GIS Cut Line= 3
      2756554.75      6854055.00      2756564.15      6854548.61
      2756561.50      6854761.99
#Sta/Elev= 30
  4506.3  500.57  4512.3  500.20  4582.3  498.56  4602.3  498.46  4642.3  497.19
  4662.3  497.19  4702.3  496.40  4802.4  497.82  4812.4  497.54  4831.0  496.22
  4836.0  497.04  4852.4  495.72  4872.4  494.86  4890.4  494.64  4890.6  494.14
  4894.1  494.14  4894.4  494.64  4922.4  494.74  4979.5  495.75  4992.4  496.12
  5012.4  495.66  5032.4  495.97  5042.4  496.71  5062.4  499.39  5072.4  499.00
  5082.4  497.84  5112.4  499.01  5142.4  499.29  5182.4  500.72  5213.4  501.40
#Mann=4,-1,0
  4506.3    0.05       0  4890.4    0.07       0  4894.4    0.05       0
  4979.5    0.16       0
Bank Sta=4890.4,4894.4
Exp/Cntr=0.3,0.1

Type RM Length L Ch R = 1,38085,101,101,101
BEGIN DESCRIPTION:
Chamblee Creek38085.37
END DESCRIPTION:
XS GIS Cut Line= 3
      2756489.67      6854089.19      2756491.17      6854511.31
      2756493.49      6854716.77
#Sta/Elev= 30
  4579.0  500.39  4630.8  498.67  4680.8  497.82  4710.8  496.58  4760.8  496.02
  4800.8  496.64  4820.8  496.32  4880.8  497.10  4890.8  496.80  4910.8  494.82
  4920.8  495.00  4938.8  494.50  4939.1  494.00  4942.6  494.00  4942.8  494.50
  4990.8  495.54  5003.5  495.24  5010.8  495.58  5020.8  494.91  5032.6  495.24
  5060.8  497.21  5080.8  497.10  5090.8  497.43  5120.8  497.59  5140.8  498.30
  5150.8  497.97  5170.8  498.51  5190.8  499.91  5200.8  500.11  5206.6  500.54
#Mann=4,-1,0
  4579.0    0.05       0  4938.8    0.05       0  4942.8    0.05       0
  5032.6    0.16       0
Bank Sta=4938.8,4942.8
Exp/Cntr=0.3,0.1

Type RM Length L Ch R = 1,37984,99,99,99
BEGIN DESCRIPTION:
Chamblee Creek37983.97
END DESCRIPTION:
XS GIS Cut Line= 3
      2756412.23      6854065.63      2756405.76      6854460.74
      2756347.50      6854652.42
#Sta/Elev= 30
  4604.5  501.83  4629.9  501.12  4677.2  498.84  4682.2  498.99  4759.9  496.03
  4799.9  495.34  4829.9  495.59  4874.8  494.98  4891.1  494.46  4917.9  493.75
  4918.2  493.25  4921.7  493.25  4921.9  493.75  4929.9  493.92  4949.9  495.29
  4959.9  494.54  4969.9  494.37  4989.9  494.80  5021.0  494.45  5053.9  495.23
  5073.1  496.10  5094.0  496.65  5104.5  497.39  5112.5  497.28  5119.7  497.00
  5152.5  498.70  5157.8  498.58  5185.4  499.44  5190.6  500.11  5200.0  500.32
#Mann=6,-1,0
  4604.5    0.05       0  4874.8    0.16       0  4891.1    0.05       0
  4917.9    0.05       0  4921.9    0.05       0  5112.5    0.16       0
Bank Sta=4917.9,4921.9
Exp/Cntr=0.3,0.1

Type RM Length L Ch R = 1,37885,123,123,123
BEGIN DESCRIPTION:
Chamblee Creek37884.89
END DESCRIPTION:
XS GIS Cut Line= 3
      2756288.63      6854128.62      2756306.63      6854460.93
      2756285.77      6854661.14
#Sta/Elev= 30
  4666.9  501.19  4679.3  501.07  4712.6  499.22  4779.4  496.90  4815.4  494.56
  4819.5  494.21  4839.5  494.22  4849.6  493.69  4877.6  493.49  4877.8  492.99
  4881.3  492.99  4881.6  493.49  4902.9  493.67  4909.6  493.94  4929.7  493.61
  4959.7  493.78  4969.7  494.00  4979.7  494.64  4989.8  494.63  4997.2  493.58
  5002.3  493.58  5029.9  494.29  5049.5  495.17  5054.5  494.62  5060.1  495.33
  5121.1  497.77  5148.0  499.12  5162.5  499.56  5180.7  500.32  5201.0  500.34
#Mann=7,-1,0
  4666.9    0.05       0  4815.4    0.16       0  4877.6    0.05       0
  4881.6    0.16       0  4902.9    0.05       0  5121.1    0.07       0
  5162.5    0.16       0
Bank Sta=4877.6,4881.6
Exp/Cntr=0.3,0.1

Type RM Length L Ch R = 1,37762,105,105,105
BEGIN DESCRIPTION:
Chamblee Creek37762.01
END DESCRIPTION:
XS GIS Cut Line= 3
      2756196.45      6854221.02      2756202.97      6854435.90
      2756209.96      6854631.80
#Sta/Elev= 30
  4787.0  498.85  4807.0  498.66  4817.0  499.02  4827.0  498.70  4837.0  498.74
  4857.0  495.09  4867.0  493.53  4927.0  493.53  4934.5  494.90  4941.7  494.60
  4947.1  494.44  4957.1  494.57  4967.1  493.50  4985.1  493.27  4985.3  492.77
  4988.8  492.77  4989.1  493.27  4997.0  493.92  5002.0  493.92  5017.1  494.31
  5037.1  495.11  5077.1  495.74  5087.1  496.34  5107.1  497.20  5117.2  497.92
  5127.2  498.01  5137.2  498.35  5145.8  498.92  5195.1  500.88  5198.0  500.88
#Mann=5,-1,0
  4787.0    0.16       0  4941.7    0.05       0  4985.1    0.05       0
  4989.1    0.05       0  5145.8    0.07       0
Bank Sta=4985.1,4989.1
Exp/Cntr=0.3,0.1

Type RM Length L Ch R = 1,37657,122,122,122
BEGIN DESCRIPTION:
Chamblee Creek37657.13
END DESCRIPTION:
XS GIS Cut Line= 3
      2756109.99      6854213.65      2756106.86      6854463.00
      2756102.44      6854644.78
#Sta/Elev= 30
  4752.4  499.61  4759.8  499.21  4789.8  498.63  4799.8  498.84  4809.8  498.39
  4819.8  496.16  4829.8  495.17  4839.8  493.78  4849.8  493.53  4909.8  493.52
  4919.8  493.63  4925.0  494.30  4929.8  494.92  4939.8  494.95  4959.8  494.69
  4969.8  494.35  4979.8  493.74  4987.8  492.94  4988.0  492.44  4991.5  492.44
  4991.8  492.94  4998.3  493.59  5001.8  493.59  5009.8  494.08  5039.8  495.41
  5089.8  498.43  5109.8  498.82  5119.8  499.21  5129.8  500.02  5183.6  500.65
#Mann=4,-1,0
  4752.4    0.16       0  4925.0    0.05       0  4987.8    0.05       0
  4991.8    0.05       0
Bank Sta=4987.8,4991.8
Exp/Cntr=0.3,0.1

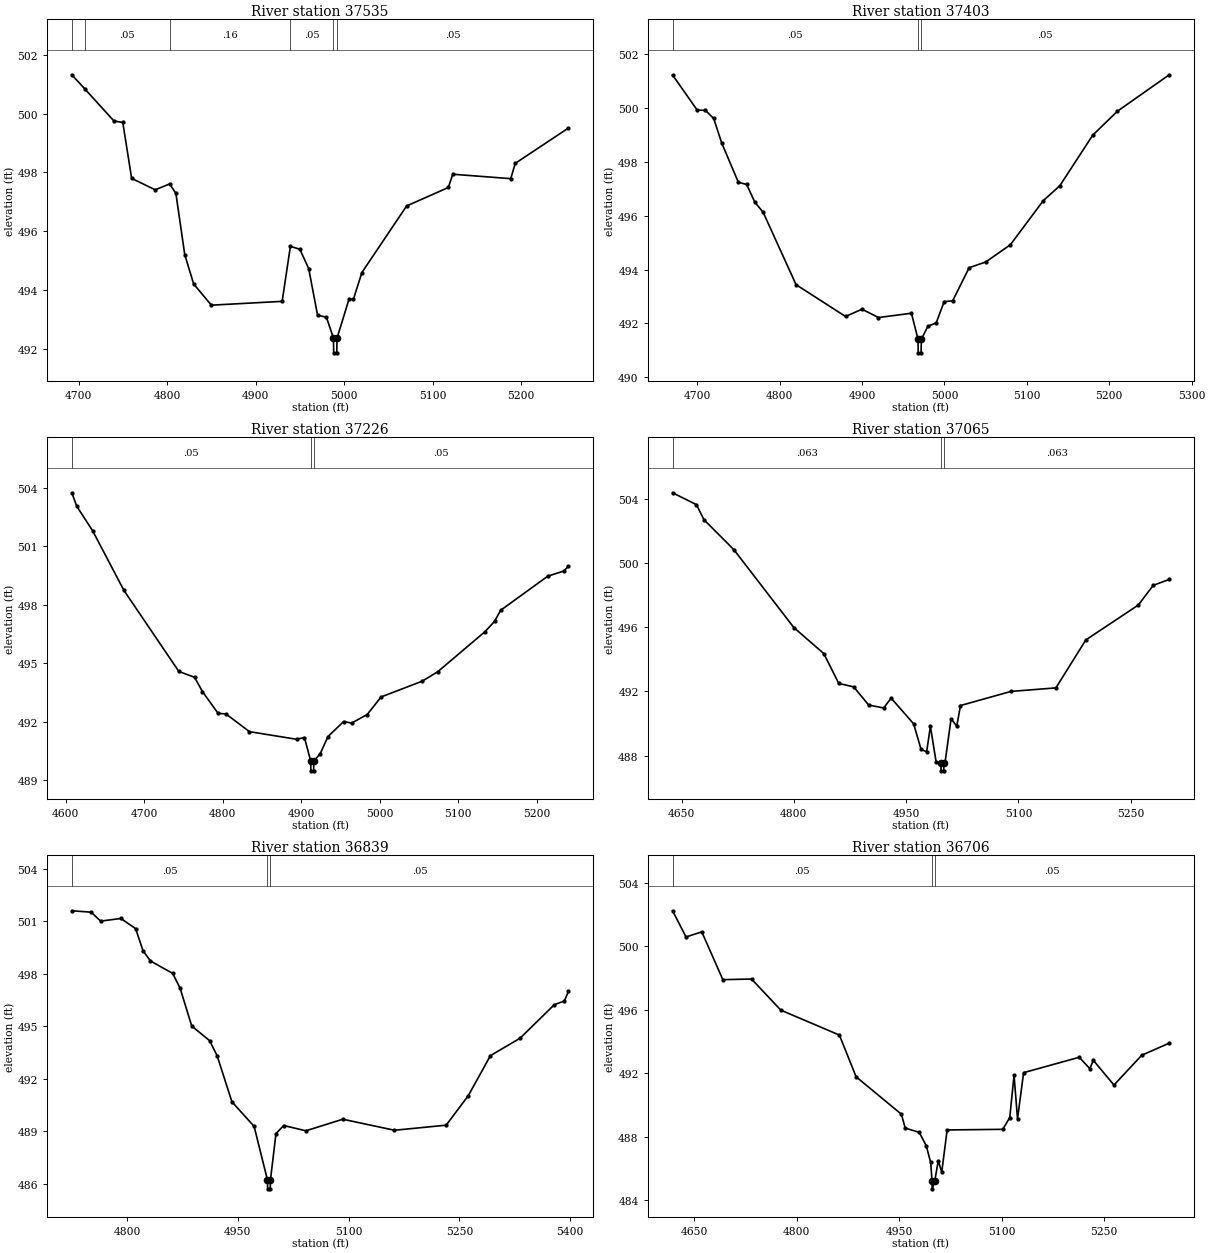
Type RM Length L Ch R = 1,37535,132,132,132
BEGIN DESCRIPTION:
Chamblee Creek37535.02
END DESCRIPTION:
XS GIS Cut Line= 3
      2755979.29      6854153.37      2755984.88      6854466.96
      2756020.04      6854712.01
#Sta/Elev= 30
  4692.3  501.32  4707.0  500.84  4739.9  499.75  4749.9  499.70  4759.9  497.80
  4786.6  497.41  4802.8  497.61  4809.9  497.29  4819.9  495.21  4830.0  494.21
  4850.0  493.49  4930.0  493.62  4939.3  495.49  4950.0  495.39  4960.0  494.73
  4970.0  493.15  4980.0  493.08  4988.0  492.37  4988.2  491.87  4991.7  491.87
  4992.0  492.37  5005.5  493.69  5010.5  493.69  5020.1  494.60  5070.6  496.86
  5117.8  497.49  5122.8  497.94  5188.3  497.79  5193.4  498.31  5253.5  499.51
#Mann=6,-1,0
  4692.3   0.045       0  4707.0    0.05       0  4802.8    0.16       0
  4939.3    0.05       0  4988.0    0.05       0  4992.0    0.05       0
Bank Sta=4988,4992
Exp/Cntr=0.3,0.1

Type RM Length L Ch R = 1,37403,177,177,177
BEGIN DESCRIPTION:
Chamblee Creek37402.99
END DESCRIPTION:
XS GIS Cut Line= 3
      2755852.06      6854131.21      2755852.75      6854465.48
      2755847.70      6854733.76
#Sta/Elev= 30
  4670.2  501.22  4700.0  499.92  4710.0  499.91  4720.0  499.61  4730.0  498.68
  4750.0  497.24  4760.0  497.16  4770.0  496.50  4780.0  496.13  4820.0  493.44
  4880.0  492.26  4900.0  492.53  4920.0  492.22  4960.0  492.38  4968.0  491.41
  4968.2  490.91  4971.7  490.91  4972.0  491.41  4980.0  491.90  4990.0  492.02
  4999.7  492.81  5010.0  492.84  5030.0  494.07  5050.0  494.28  5080.0  494.92
  5120.0  496.56  5140.0  497.11  5180.0  498.99  5210.0  499.88  5272.8  501.23
#Mann=3,-1,0
  4670.2    0.05       0  4968.0    0.05       0  4972.0    0.05       0
Bank Sta=4968,4972
Exp/Cntr=0.3,0.1

Type RM Length L Ch R = 1,37226,161,161,161
BEGIN DESCRIPTION:
Chamblee Creek37226.35
END DESCRIPTION:
XS GIS Cut Line= 3
      2755675.99      6854064.64      2755676.64      6854461.20
      2755684.04      6854697.32
#Sta/Elev= 30
  4607.6  503.75  4614.0  503.05  4634.0  501.81  4674.0  498.74  4744.0  494.58
  4764.0  494.28  4774.0  493.55  4794.0  492.43  4804.0  492.40  4834.0  491.49
  4894.0  491.10  4904.0  491.19  4912.0  489.98  4912.2  489.48  4915.7  489.48
  4916.0  489.98  4924.0  490.35  4934.0  491.24  4954.0  492.01  4964.0  491.93
  4984.0  492.37  5001.6  493.27  5054.0  494.08  5074.0  494.57  5134.0  496.62
  5146.2  497.15  5154.0  497.72  5214.1  499.47  5234.1  499.73  5240.4  499.97
#Mann=3,-1,0
  4607.6    0.05       0  4912.0    0.05       0  4916.0    0.05       0
Bank Sta=4912,4916
Exp/Cntr=0.3,0.1

Type RM Length L Ch R = 1,37065,226,226,226
BEGIN DESCRIPTION:
Chamblee Creek37064.57
END DESCRIPTION:
XS GIS Cut Line= 3
      2755546.89      6853999.15      2755551.27      6854362.91
      2755546.93      6854662.39
#Sta/Elev= 30
  4638.1  504.38  4669.9  503.64  4680.0  502.70  4720.0  500.83  4800.0  495.98
  4840.0  494.36  4860.0  492.50  4880.0  492.28  4900.0  491.15  4920.0  490.97
  4930.0  491.58  4960.0  489.98  4970.0  488.38  4977.4  488.24  4982.4  489.82
  4990.0  487.62  4996.4  487.55  4996.7  487.05  5000.2  487.05  5000.4  487.55
  5001.9  487.55  5010.0  490.29  5017.6  489.84  5022.6  491.12  5090.0  492.00
  5150.0  492.22  5190.0  495.21  5260.0  497.38  5280.0  498.61  5301.4  498.98
#Mann=3,-1,0
  4638.1   0.063       0  4996.4   0.063       0  5000.4   0.063       0
Bank Sta=4996.4,5000.4
Exp/Cntr=0.3,0.1

Type RM Length L Ch R = 1,36839,133,133,133
BEGIN DESCRIPTION:
Chamblee Creek36839.38
END DESCRIPTION:
XS GIS Cut Line= 3
      2755403.91      6853944.86      2755381.68      6854224.91
      2755380.97      6854616.58
#Sta/Elev= 30
  4725.2  501.60  4751.4  501.52  4764.2  501.01  4791.6  501.16  4811.6  500.58
  4821.6  499.32  4831.7  498.73  4861.8  498.02  4871.8  497.18  4887.6  495.01
  4911.9  494.17  4922.0  493.31  4942.0  490.68  4972.1  489.27  4990.2  486.20
  4990.4  485.70  4993.9  485.70  4994.2  486.20  5001.7  488.86  5012.2  489.32
  5042.2  489.02  5092.2  489.68  5162.2  489.05  5232.2  489.34  5262.2  491.03
  5292.2  493.32  5332.2  494.31  5378.7  496.23  5392.2  496.44  5397.8  496.99
#Mann=3,-1,0
  4725.2    0.05       0  4990.2    0.05       0  4994.2    0.05       0
Bank Sta=4990.2,4994.2
Exp/Cntr=0.3,0.1

Type RM Length L Ch R = 1,36706,128,128,128
BEGIN DESCRIPTION:
Chamblee Creek36706.13
END DESCRIPTION:
XS GIS Cut Line= 3
      2755335.97      6853839.36      2755249.78      6854213.92
      2755312.10      6854550.55
#Sta/Elev= 30
  4618.7  502.23  4638.3  500.58  4661.4  500.90  4692.2  497.89  4734.2  497.93
  4777.0  495.97  4862.7  494.40  4887.2  491.77  4953.5  489.41  4959.0  488.54
  4979.5  488.27  4989.8  487.43  4996.3  486.37  4998.3  485.21  4998.6  484.71
  5002.3  485.21  5007.4  486.48  5012.5  485.76  5020.4  488.42  5101.8  488.46
  5112.0  489.20  5118.3  491.86  5123.4  489.12  5132.3  492.03  5213.7  493.00
  5229.2  492.28  5234.3  492.81  5264.5  491.25  5305.2  493.13  5345.4  493.89
#Mann=3,-1,0
  4618.7    0.05       0  4998.3    0.05       0  5002.3    0.05       0
Bank Sta=4998.3,5002.3
Exp/Cntr=0.3,0.1

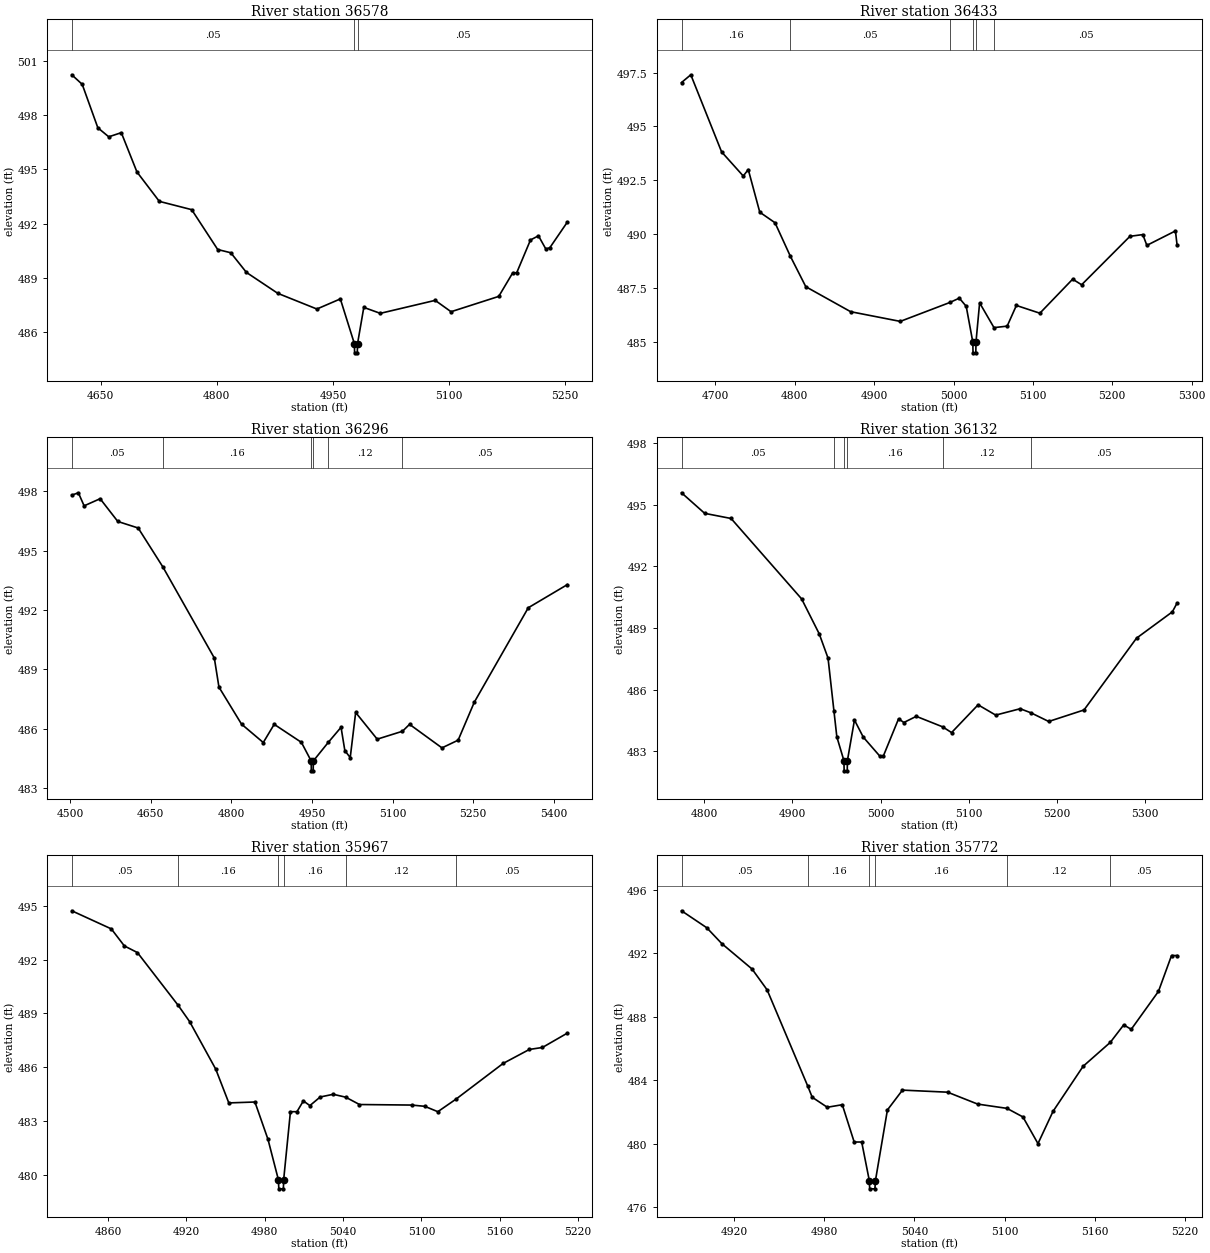
Type RM Length L Ch R = 1,36578,145,145,145
BEGIN DESCRIPTION:
Chamblee Creek36578.03
END DESCRIPTION:
XS GIS Cut Line= 3
      2755177.66      6853827.67      2755122.04      6854213.41
      2755065.75      6854457.37
#Sta/Elev= 30
  4612.6  500.25  4626.1  499.72  4646.3  497.31  4660.4  496.81  4676.6  497.04
  4696.8  494.86  4725.7  493.23  4767.5  492.77  4801.1  490.56  4818.0  490.38
  4838.2  489.29  4878.7  488.13  4929.2  487.26  4959.5  487.82  4977.7  485.33
  4977.9  484.83  4981.4  484.83  4981.7  485.33  4989.8  487.35  5011.1  487.02
  5082.0  487.74  5102.5  487.11  5164.1  487.96  5182.2  489.27  5187.3  489.27
  5205.1  491.09  5215.4  491.32  5224.9  490.59  5230.1  490.66  5252.7  492.08
#Mann=3,-1,0
  4612.6    0.05       0  4977.7    0.05       0  4981.7    0.05       0
Bank Sta=4977.7,4981.7
Exp/Cntr=0.3,0.1

Type RM Length L Ch R = 1,36433,137,137,137
BEGIN DESCRIPTION:
Chamblee Creek36433
END DESCRIPTION:
XS GIS Cut Line= 3
      2755084.68      6853846.26      2754988.50      6854179.00
      2754920.62      6854448.63
#Sta/Elev= 30
  4657.3  497.04  4669.0  497.40  4707.8  493.82  4735.1  492.70  4741.4  493.00
  4755.9  491.02  4775.1  490.53  4794.5  488.97  4813.9  487.56  4870.4  486.40
  4932.9  485.95  4995.5  486.83  5007.3  487.03  5016.0  486.65  5024.3  484.99
  5024.6  484.49  5028.1  484.49  5028.3  484.99  5032.9  486.81  5051.0  485.66
  5067.6  485.73  5079.2  486.69  5108.8  486.33  5150.1  487.91  5161.4  487.65
  5222.3  489.90  5238.5  489.98  5243.6  489.48  5279.6  490.15  5281.7  489.49
#Mann=6,-1,0
  4657.3    0.16       0  4794.5    0.05       0  4995.5    0.12       0
  5024.3    0.07       0  5028.3    0.12       0  5051.0    0.05       0
Bank Sta=5024.3,5028.3
Exp/Cntr=0.3,0.1

Type RM Length L Ch R = 1,36296,164,164,164
BEGIN DESCRIPTION:
Chamblee Creek36295.63
END DESCRIPTION:
XS GIS Cut Line= 3
      2754798.14      6853618.87      2754875.54      6854113.91
      2754838.35      6854533.41
#Sta/Elev= 30
  4503.1  497.80  4515.4  497.92  4526.1  497.26  4555.9  497.62  4588.8  496.47
  4626.7  496.14  4672.7  494.17  4768.4  489.57  4777.0  488.10  4819.0  486.23
  4859.5  485.30  4879.8  486.22  4930.4  485.31  4948.6  484.37  4948.9  483.87
  4952.4  483.87  4952.6  484.37  4980.5  485.31  5004.2  486.07  5011.3  484.89
  5021.3  484.54  5031.4  486.82  5071.5  485.47  5118.5  485.87  5131.7  486.22
  5192.0  485.03  5222.1  485.42  5252.2  487.34  5352.6  492.11  5425.3  493.28
#Mann=6,-1,0
  4503.1    0.05       0  4672.7    0.16       0  4948.6    0.07       0
  4952.6    0.16       0  4980.5    0.12       0  5118.5    0.05       0
Bank Sta=4948.6,4952.6
Exp/Cntr=0.3,0.1

Type RM Length L Ch R = 1,36132,165,165,165
BEGIN DESCRIPTION:
Chamblee Creek36131.9
END DESCRIPTION:
XS GIS Cut Line= 3
      2754719.31      6853834.74      2754729.17      6854063.60
      2754754.11      6854396.40
#Sta/Elev= 30
  4774.0  495.57  4800.3  494.57  4830.3  494.32  4910.4  490.41  4930.4  488.71
  4940.4  487.53  4947.1  484.96  4950.4  483.70  4958.4  482.55  4958.7  482.05
  4962.2  482.05  4962.4  482.55  4970.4  484.52  4980.4  483.69  4999.3  482.76
  5003.1  482.76  5020.5  484.58  5026.5  484.40  5040.6  484.70  5070.5  484.19
  5080.7  483.91  5110.8  485.26  5130.8  484.76  5158.6  485.07  5170.9  484.87
  5191.0  484.45  5231.1  485.01  5290.7  488.50  5331.4  489.78  5336.8  490.21
#Mann=6,-1,0
  4774.0    0.05       0  4947.1    0.16       0  4958.4    0.07       0
  4962.4    0.16       0  5070.5    0.12       0  5170.9    0.05       0
Bank Sta=4958.4,4962.4
Exp/Cntr=0.3,0.1

Type RM Length L Ch R = 1,35967,195,195,195
BEGIN DESCRIPTION:
Chamblee Creek35966.88
END DESCRIPTION:
XS GIS Cut Line= 3
      2754580.34      6853940.68      2754580.62      6854110.42
      2754588.75      6854320.12
#Sta/Elev= 30
  4832.2  494.72  4862.5  493.71  4872.5  492.76  4882.5  492.39  4913.8  489.44
  4922.5  488.54  4942.5  485.89  4952.5  484.01  4972.5  484.06  4982.5  481.98
  4990.5  479.72  4990.8  479.22  4994.3  479.22  4994.5  479.72  4999.7  483.52
  5004.7  483.52  5009.6  484.12  5014.6  483.86  5022.5  484.34  5032.5  484.49
  5042.0  484.33  5052.6  483.92  5092.6  483.89  5102.6  483.82  5112.6  483.52
  5126.7  484.23  5162.6  486.21  5182.7  486.99  5192.7  487.10  5211.8  487.90
#Mann=6,-1,0
  4832.2    0.05       0  4913.8    0.16       0  4990.5    0.07       0
  4994.5    0.16       0  5042.0    0.12       0  5126.7    0.05       0
Bank Sta=4990.5,4994.5
Exp/Cntr=0.3,0.1

Type RM Length L Ch R = 1,35772,258,258,258
BEGIN DESCRIPTION:
Chamblee Creek35771.85
END DESCRIPTION:
XS GIS Cut Line= 3
      2754421.41      6853954.15      2754422.96      6854071.96
      2754432.51      6854283.43
#Sta/Elev= 30
  4885.2  494.69  4902.0  493.62  4912.0  492.62  4932.1  491.02  4942.1  489.71
  4969.1  483.65  4972.1  482.94  4982.1  482.31  4992.1  482.47  5000.0  480.12
  5005.0  480.12  5010.1  477.67  5010.3  477.17  5013.8  477.17  5014.1  477.67
  5022.1  482.14  5032.1  483.39  5062.1  483.26  5082.1  482.51  5101.6  482.24
  5112.2  481.70  5122.2  480.02  5132.2  482.05  5152.2  484.89  5170.3  486.40
  5179.2  487.50  5184.2  487.22  5202.3  489.61  5211.0  491.87  5214.7  491.87
#Mann=6,-1,0
  4885.2    0.05       0  4969.1    0.16       0  5010.1    0.07       0
  5014.1    0.16       0  5101.6    0.12       0  5170.3    0.05       0
Bank Sta=5010.1,5014.1
Exp/Cntr=0.3,0.1

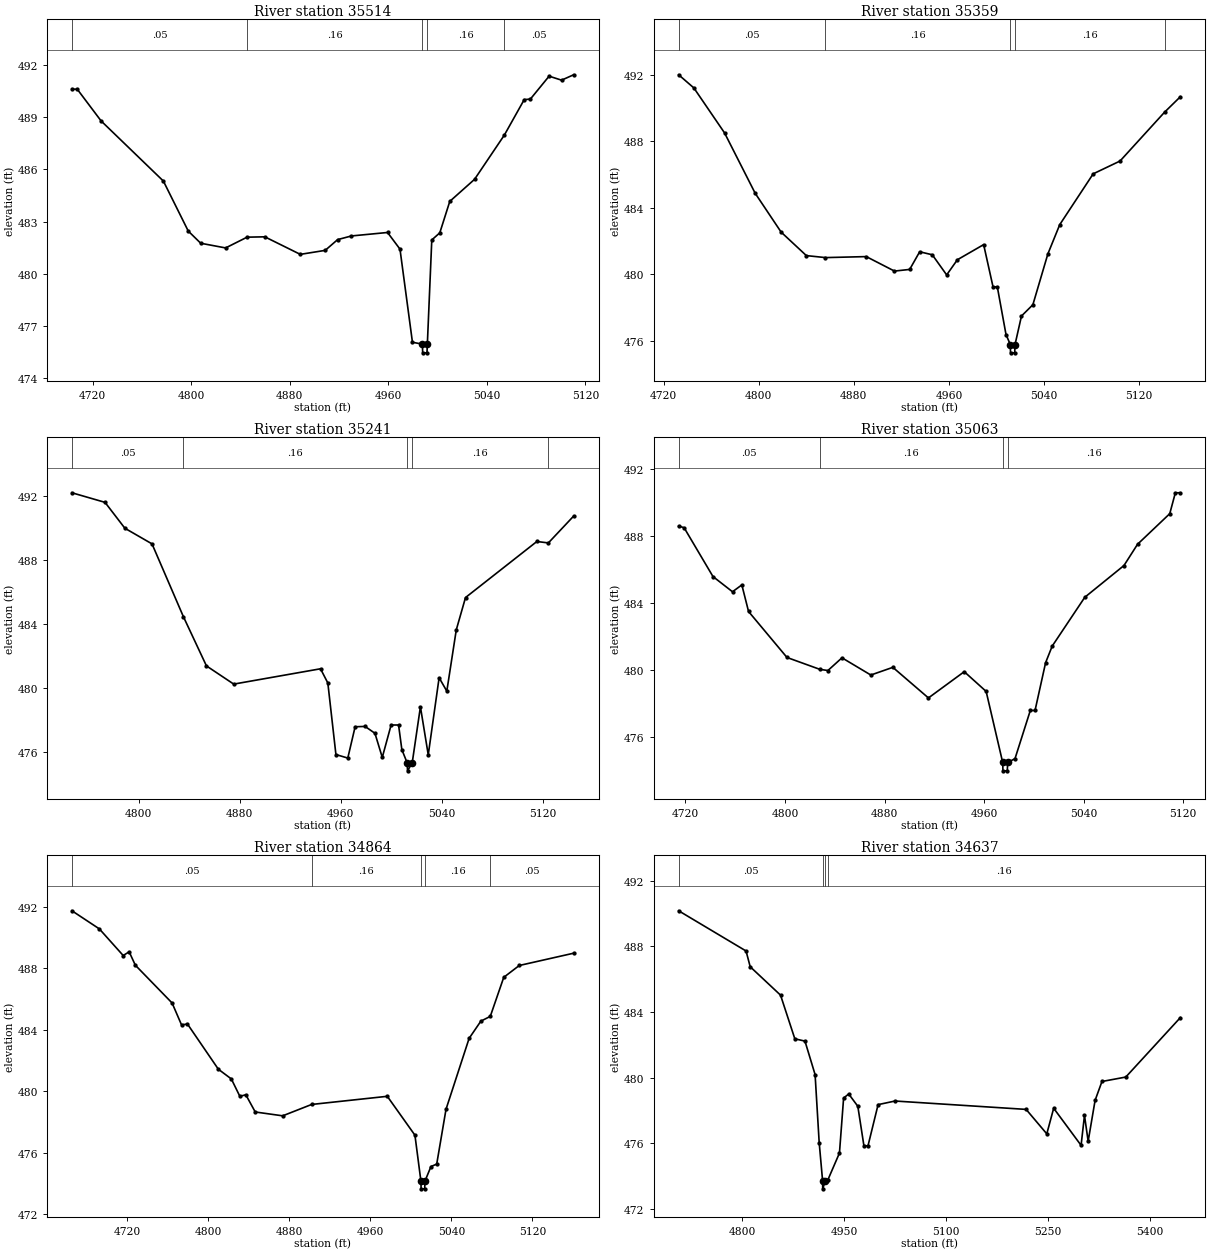
Type RM Length L Ch R = 1,35514,155,155,155
BEGIN DESCRIPTION:
Chamblee Creek35514.21
END DESCRIPTION:
XS GIS Cut Line= 3
      2754199.08      6853917.58      2754241.85      6854213.04
      2754255.39      6854320.75
#Sta/Elev= 30
  4703.3  490.62  4707.6  490.62  4727.0  488.79  4777.5  485.33  4797.7  482.45
  4807.8  481.75  4828.0  481.48  4845.4  482.10  4859.8  482.12  4888.6  481.11
  4908.8  481.34  4918.9  481.96  4930.1  482.17  4959.4  482.37  4969.5  481.41
  4979.6  476.05  4987.7  475.94  4987.9  475.44  4991.4  475.44  4991.7  475.94
  4995.3  481.94  5001.8  482.35  5009.9  484.16  5030.0  485.43  5054.2  487.98
  5070.3  490.02  5075.3  490.05  5090.5  491.37  5100.6  491.14  5110.4  491.45
#Mann=5,-1,0
  4703.3    0.05       0  4845.4    0.16       0  4987.7    0.07       0
  4991.7    0.16       0  5054.2    0.05       0
Bank Sta=4987.7,4991.7
Exp/Cntr=0.3,0.1

Type RM Length L Ch R = 1,35359,118,118,118
BEGIN DESCRIPTION:
Chamblee Creek35358.5
END DESCRIPTION:
XS GIS Cut Line= 3
      2753998.36      6853959.52      2754086.19      6854212.73
      2754153.34      6854351.20
#Sta/Elev= 30
  4732.7  491.99  4745.5  491.20  4771.3  488.50  4797.1  484.87  4818.9  482.54
  4840.1  481.13  4856.2  481.01  4890.5  481.07  4914.2  480.20  4927.0  480.30
  4935.4  481.36  4946.0  481.18  4958.1  479.97  4967.1  480.88  4989.2  481.79
  4997.1  479.25  5000.7  479.25  5008.0  476.39  5011.6  475.79  5011.8  475.29
  5015.3  475.29  5015.6  475.79  5021.0  477.50  5030.6  478.18  5043.2  481.23
  5053.2  482.99  5081.3  486.04  5103.9  486.81  5141.3  489.74  5154.6  490.67
#Mann=5,-1,0
  4732.7    0.05       0  4856.2    0.16       0  5011.6    0.07       0
  5015.6    0.16       0  5141.3    0.05       0
Bank Sta=5011.6,5015.6
Exp/Cntr=0.3,0.1

Type RM Length L Ch R = 1,35241,178,178,178
BEGIN DESCRIPTION:
Chamblee Creek35241.43
END DESCRIPTION:
XS GIS Cut Line= 3
      2753805.16      6854174.74      2754026.73      6854303.07
      2754141.60      6854385.10
#Sta/Elev= 30
  4747.1  492.23  4773.3  491.63  4789.0  490.01  4810.5  489.03  4835.3  484.48
  4853.6  481.39  4875.2  480.25  4943.9  481.21  4949.7  480.32  4956.1  475.84
  4965.5  475.62  4971.3  477.58  4979.2  477.60  4987.0  477.17  4992.8  475.66
  4999.8  477.69  5005.7  477.69  5008.3  476.15  5012.5  475.32  5012.8  474.82
  5016.5  475.32  5023.0  478.83  5029.2  475.82  5037.8  480.65  5043.9  479.81
  5051.4  483.65  5058.7  485.67  5115.2  489.18  5124.3  489.09  5144.3  490.77
#Mann=5,-1,0
  4747.1    0.05       0  4835.3    0.16       0  5012.5    0.07       0
  5016.5    0.16       0  5124.3    0.05       0
Bank Sta=5012.5,5016.5
Exp/Cntr=0.3,0.1

Type RM Length L Ch R = 1,35063,199,199,199
BEGIN DESCRIPTION:
Chamblee Creek35063.08
END DESCRIPTION:
XS GIS Cut Line= 3
      2753676.49      6854334.42      2753937.96      6854451.59
      2754048.62      6854488.89
#Sta/Elev= 30
  4714.5  488.60  4718.9  488.50  4742.1  485.58  4757.8  484.67  4765.3  485.08
  4770.7  483.49  4801.6  480.74  4828.0  480.03  4834.5  479.96  4845.8  480.72
  4869.0  479.69  4886.7  480.15  4915.3  478.32  4944.1  479.89  4961.7  478.71
  4975.0  474.46  4975.2  473.96  4978.7  473.96  4979.0  474.46  4984.9  474.69
  4997.2  477.57  5001.0  477.57  5009.5  480.43  5014.8  481.42  5041.0  484.34
  5072.5  486.24  5083.4  487.51  5109.3  489.34  5113.8  490.59  5117.8  490.59
#Mann=4,-1,0
  4714.5    0.05       0  4828.0    0.16       0  4975.0    0.07       0
  4979.0    0.16       0
Bank Sta=4975,4979
Exp/Cntr=0.3,0.1

Type RM Length L Ch R = 1,34864,227,227,227
BEGIN DESCRIPTION:
Chamblee Creek34864.4
END DESCRIPTION:
XS GIS Cut Line= 3
      2753593.17      6854435.75      2753877.18      6854616.22
      2754016.43      6854692.77
#Sta/Elev= 30
  4665.3  491.74  4692.4  490.56  4715.9  488.83  4721.8  489.07  4727.9  488.20
  4764.2  485.74  4773.5  484.32  4779.4  484.37  4809.9  481.43  4822.7  480.80
  4831.1  479.67  4837.0  479.77  4846.3  478.65  4873.4  478.40  4902.0  479.14
  4976.7  479.67  5004.0  477.14  5009.9  474.15  5010.1  473.65  5013.6  473.65
  5013.9  474.15  5019.8  475.10  5025.5  475.26  5034.7  478.83  5057.5  483.44
  5069.1  484.56  5078.4  484.87  5091.7  487.41  5107.0  488.18  5160.7  488.98
#Mann=5,-1,0
  4665.3    0.05       0  4902.0    0.16       0  5009.9    0.07       0
  5013.9    0.16       0  5078.4    0.05       0
Bank Sta=5009.9,5013.9
Exp/Cntr=0.3,0.1

Type RM Length L Ch R = 1,34637,205,205,205
BEGIN DESCRIPTION:
Chamblee Creek34637.26
END DESCRIPTION:
XS GIS Cut Line= 3
      2753594.30      6854535.08      2753761.15      6854777.39
      2753834.30      6855214.61
#Sta/Elev= 30
  4707.0  490.17  4806.1  487.72  4812.2  486.76  4856.8  485.03  4877.8  482.37
  4892.7  482.23  4907.6  480.19  4913.6  476.05  4918.6  473.73  4918.8  473.23
  4922.6  473.73  4926.0  473.74  4943.4  475.41  4949.5  478.76  4957.0  479.01
  4970.4  478.26  4979.3  475.87  4985.3  475.84  5000.2  478.36  5025.1  478.58
  5217.8  478.07  5248.2  476.58  5258.3  478.14  5298.6  475.88  5303.6  477.70
  5309.0  476.13  5319.2  478.62  5329.3  479.77  5364.3  480.04  5444.5  483.66
#Mann=4,-1,0
  4707.0    0.05       0  4918.6    0.07       0  4922.6    0.05       0
  4926.0    0.16       0
Bank Sta=4918.6,4922.6
Exp/Cntr=0.3,0.1

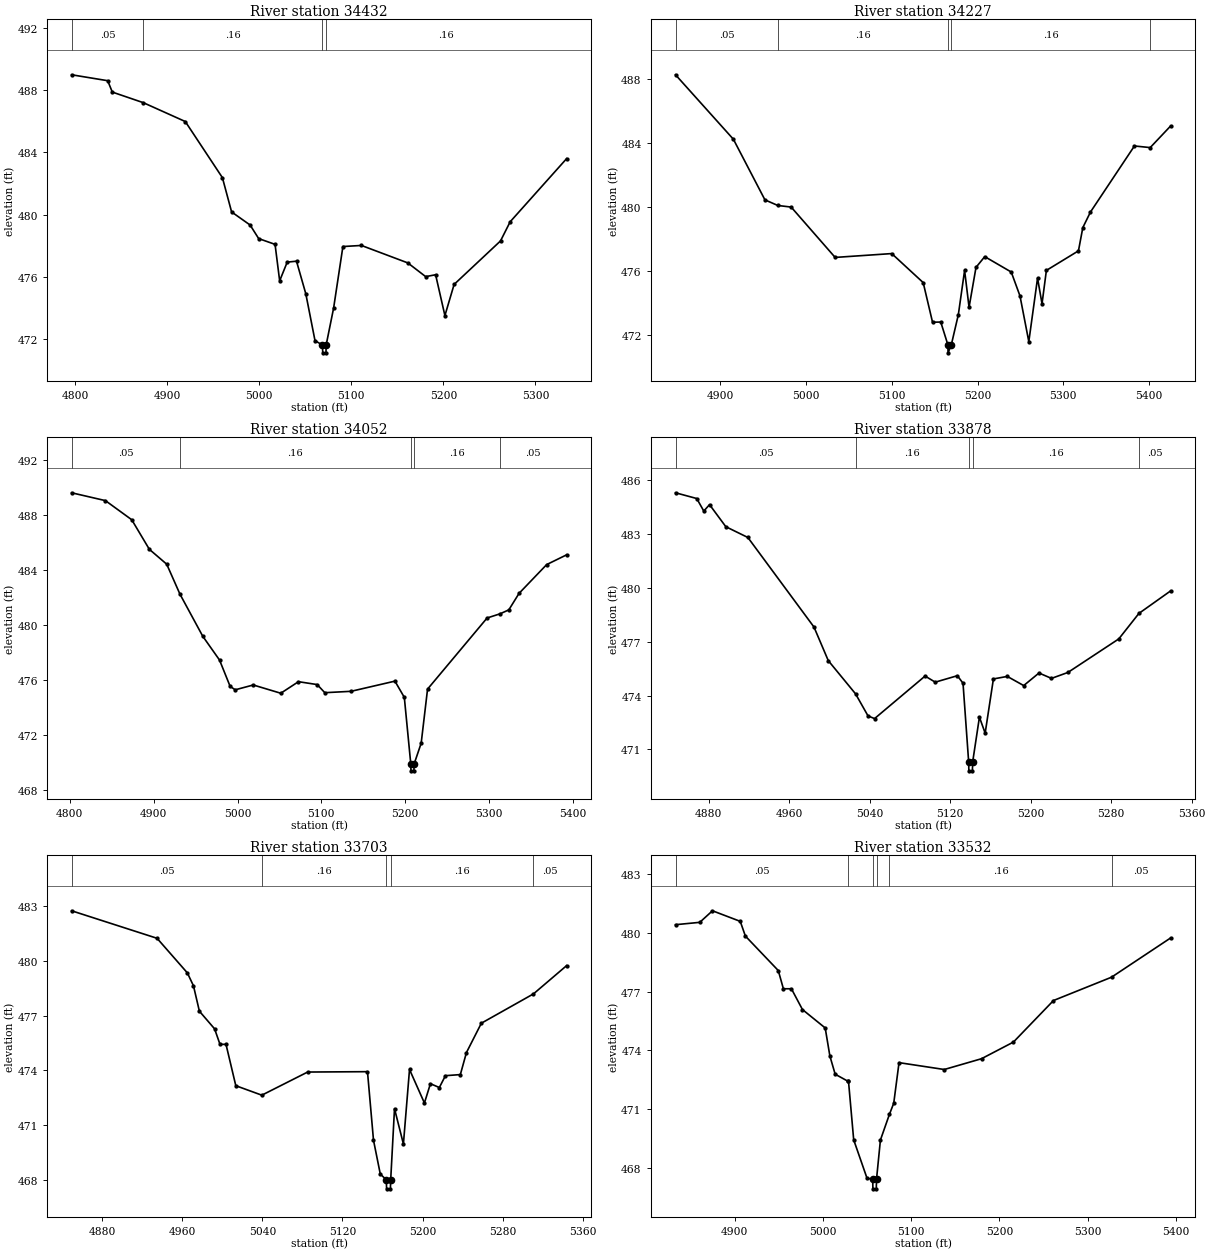
Type RM Length L Ch R = 1,34432,205,205,205
BEGIN DESCRIPTION:
Chamblee Creek34431.69
END DESCRIPTION:
XS GIS Cut Line= 3
      2753586.61      6854708.21      2753609.15      6854914.42
      2753648.93      6855242.27
#Sta/Elev= 30
  4796.2  488.98  4835.4  488.60  4840.4  487.87  4874.1  487.19  4919.7  485.98
  4960.0  482.38  4970.0  480.18  4990.1  479.34  4999.4  478.47  5017.2  478.10
  5022.2  475.76  5030.4  476.96  5040.5  477.02  5050.6  474.93  5060.6  471.92
  5068.7  471.64  5069.0  471.14  5072.5  471.14  5072.7  471.64  5080.8  474.01
  5090.9  477.96  5111.0  478.03  5161.4  476.91  5180.8  476.03  5191.6  476.15
  5201.7  473.53  5211.7  475.53  5262.1  478.32  5272.6  479.55  5333.9  483.60
#Mann=4,-1,0
  4796.2    0.05       0  4874.1    0.16       0  5068.7    0.07       0
  5072.7    0.16       0
Bank Sta=5068.7,5072.7
Exp/Cntr=0.3,0.1

Type RM Length L Ch R = 1,34227,175,175,175
BEGIN DESCRIPTION:
Chamblee Creek34226.54
END DESCRIPTION:
XS GIS Cut Line= 3
      2753377.47      6854778.90      2753408.71      6854929.04
      2753505.09      6855341.98
#Sta/Elev= 30
  4847.6  488.24  4915.1  484.22  4951.9  480.44  4966.9  480.09  4982.5  479.99
  5033.8  476.85  5099.8  477.09  5136.5  475.28  5147.4  472.81  5157.0  472.82
  5165.3  471.40  5165.5  470.90  5169.3  471.40  5177.5  473.28  5184.8  476.04
  5190.0  473.74  5198.1  476.23  5208.3  476.90  5239.2  475.94  5249.4  474.45
  5259.7  471.60  5269.9  475.56  5275.1  473.96  5280.2  476.04  5317.6  477.26
  5322.7  478.71  5331.6  479.68  5382.9  483.80  5401.3  483.70  5425.0  485.04
#Mann=5,-1,0
  4847.6    0.05       0  4966.9    0.16       0  5165.3    0.07       0
  5169.3    0.16       0  5401.3    0.05       0
Bank Sta=5165.3,5169.3
Exp/Cntr=0.3,0.1

Type RM Length L Ch R = 1,34052,174,174,174
BEGIN DESCRIPTION:
Chamblee Creek34051.61
END DESCRIPTION:
XS GIS Cut Line= 3
      2753225.96      6854862.47      2753284.60      6855051.59
      2753398.49      6855426.89
#Sta/Elev= 30
  4802.2  489.61  4842.5  489.04  4873.9  487.65  4894.9  485.50  4915.6  484.42
  4931.4  482.24  4958.6  479.18  4978.6  477.45  4991.2  475.54  4997.3  475.29
  5018.8  475.64  5051.6  475.04  5072.7  475.88  5095.0  475.67  5104.1  475.08
  5135.4  475.18  5187.7  475.92  5198.9  474.74  5206.6  469.90  5206.8  469.40
  5210.3  469.40  5210.6  469.90  5219.0  471.41  5226.6  475.34  5297.6  480.51
  5312.9  480.81  5323.5  481.10  5335.7  482.30  5368.6  484.39  5392.4  485.10
#Mann=5,-1,0
  4802.2    0.05       0  4931.4    0.16       0  5206.6    0.07       0
  5210.6    0.16       0  5312.9    0.05       0
Bank Sta=5206.6,5210.6
Exp/Cntr=0.3,0.1

Type RM Length L Ch R = 1,33878,175,175,175
BEGIN DESCRIPTION:
Chamblee Creek33877.7
END DESCRIPTION:
XS GIS Cut Line= 3
      2753057.04      6854972.44      2753129.08      6855106.27
      2753288.67      6855406.39
#Sta/Elev= 30
  4847.1  485.30  4868.2  484.98  4875.2  484.28  4880.9  484.64  4897.1  483.41
  4919.0  482.81  4984.7  477.82  4998.9  475.95  5026.0  474.10  5038.4  472.87
  5044.9  472.72  5095.1  475.09  5105.2  474.75  5127.2  475.11  5132.8  474.69
  5138.4  470.31  5138.6  469.81  5142.1  469.81  5142.4  470.31  5149.1  472.80
  5154.8  471.91  5163.0  474.93  5176.8  475.07  5193.1  474.56  5208.3  475.26
  5220.7  474.96  5237.0  475.29  5287.6  477.16  5307.6  478.58  5339.0  479.83
#Mann=5,-1,0
  4847.1    0.05       0  5026.0    0.16       0  5138.4    0.05       0
  5142.4    0.16       0  5307.6    0.05       0
Bank Sta=5138.4,5142.4
Exp/Cntr=0.3,0.1

Type RM Length L Ch R = 1,33703,171,171,171
BEGIN DESCRIPTION:
Chamblee Creek33703.37
END DESCRIPTION:
XS GIS Cut Line= 3
      2752925.39      6855103.49      2753006.75      6855231.03
      2753199.95      6855514.96
#Sta/Elev= 30
  4849.3  482.76  4934.7  481.25  4965.0  479.35  4971.1  478.64  4977.0  477.25
  4992.2  476.28  4997.6  475.43  5003.6  475.43  5013.4  473.16  5039.4  472.64
  5085.2  473.91  5145.0  473.93  5151.0  470.17  5157.8  468.31  5163.8  468.00
  5164.1  467.50  5167.9  467.50  5168.2  468.00  5172.0  471.90  5180.9  469.96
  5187.0  474.05  5201.9  472.21  5207.9  473.27  5216.8  473.06  5222.9  473.71
  5237.8  473.77  5243.9  474.98  5258.8  476.59  5310.9  478.20  5344.0  479.75
#Mann=5,-1,0
  4849.3    0.05       0  5039.4    0.16       0  5163.8    0.05       0
  5168.2    0.16       0  5310.9    0.05       0
Bank Sta=5163.8,5168.2
Exp/Cntr=0.3,0.1

Type RM Length L Ch R = 1,33532,231,231,231
BEGIN DESCRIPTION:
Chamblee Creek33531.7
END DESCRIPTION:
XS GIS Cut Line= 3
      2752801.48      6855207.22      2752885.18      6855352.15
      2753100.23      6855682.10
#Sta/Elev= 30
  4832.9  480.42  4860.4  480.54  4874.8  481.13  4906.3  480.59  4912.1  479.84
  4949.4  478.08  4955.2  477.15  4964.3  477.15  4976.8  476.09  5002.6  475.15
  5007.9  473.72  5013.9  472.79  5028.0  472.44  5029.0  472.44  5034.9  469.44
  5050.1  467.47  5056.4  467.44  5056.7  466.94  5060.5  466.94  5060.8  467.44
  5065.2  469.43  5075.4  470.74  5080.3  471.31  5086.3  473.38  5137.6  473.03
  5179.8  473.58  5216.0  474.43  5261.4  476.55  5327.2  477.74  5394.1  479.74
#Mann=6,-1,0
  4832.9    0.05       0  5028.0   0.063       0  5056.4    0.05       0
  5060.8   0.063       0  5075.4    0.16       0  5327.2    0.05       0
Bank Sta=5056.4,5060.8
Exp/Cntr=0.3,0.1