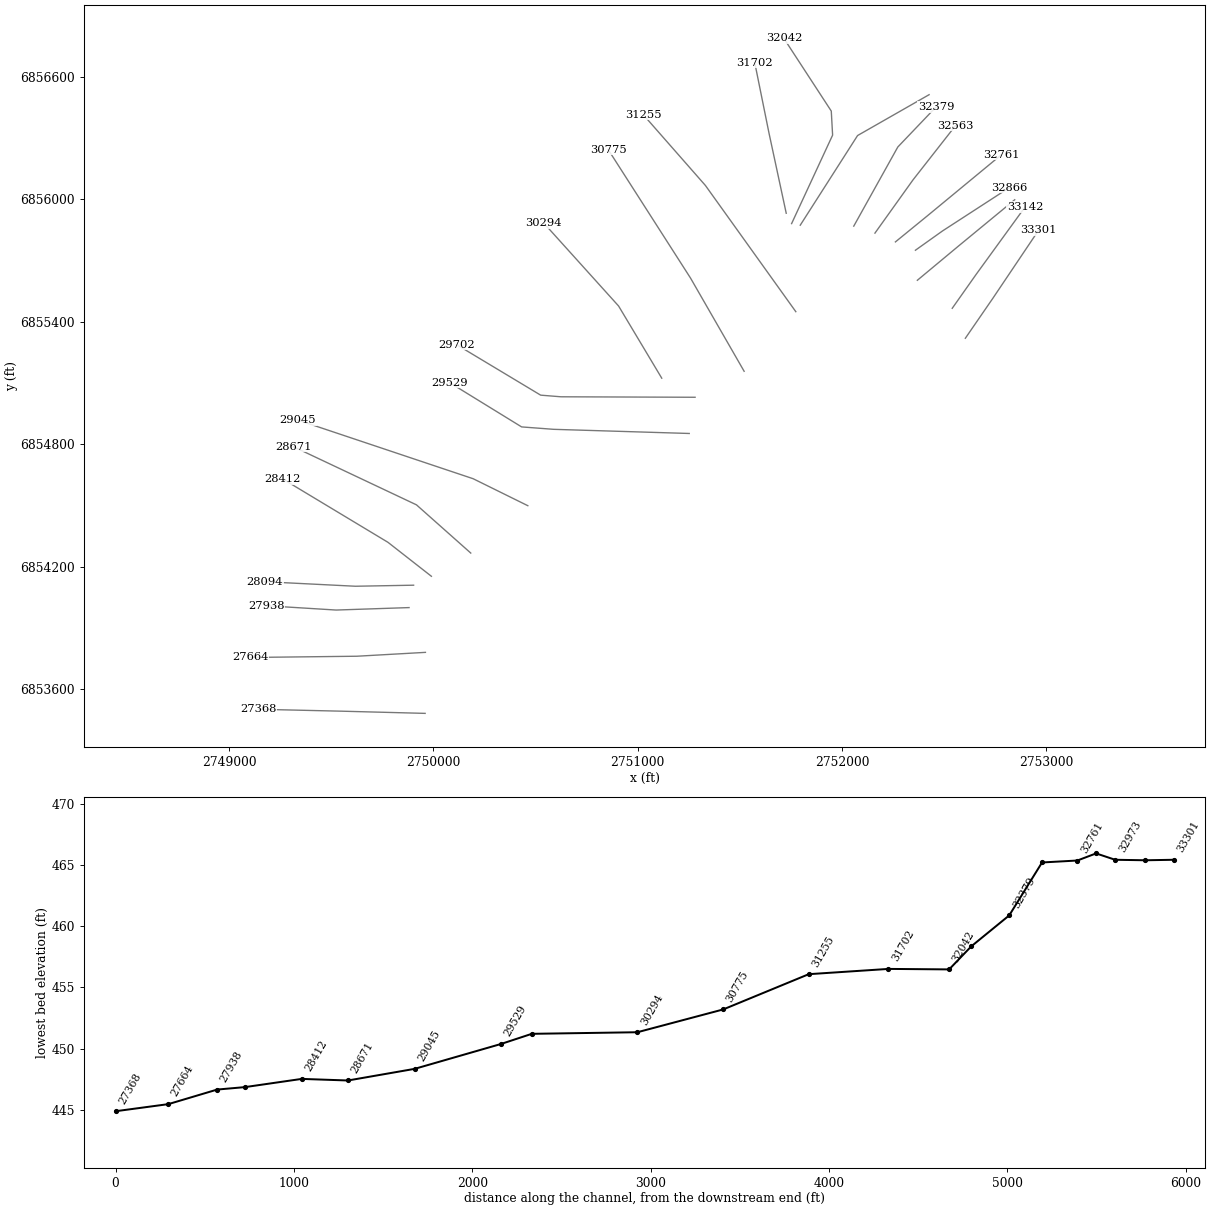
HEC-RAS study Chamblee Creek.prj: Chamblee Creek Base Level Engineering

--- Chamblee Creek.g01 (geometry) --- (continued)

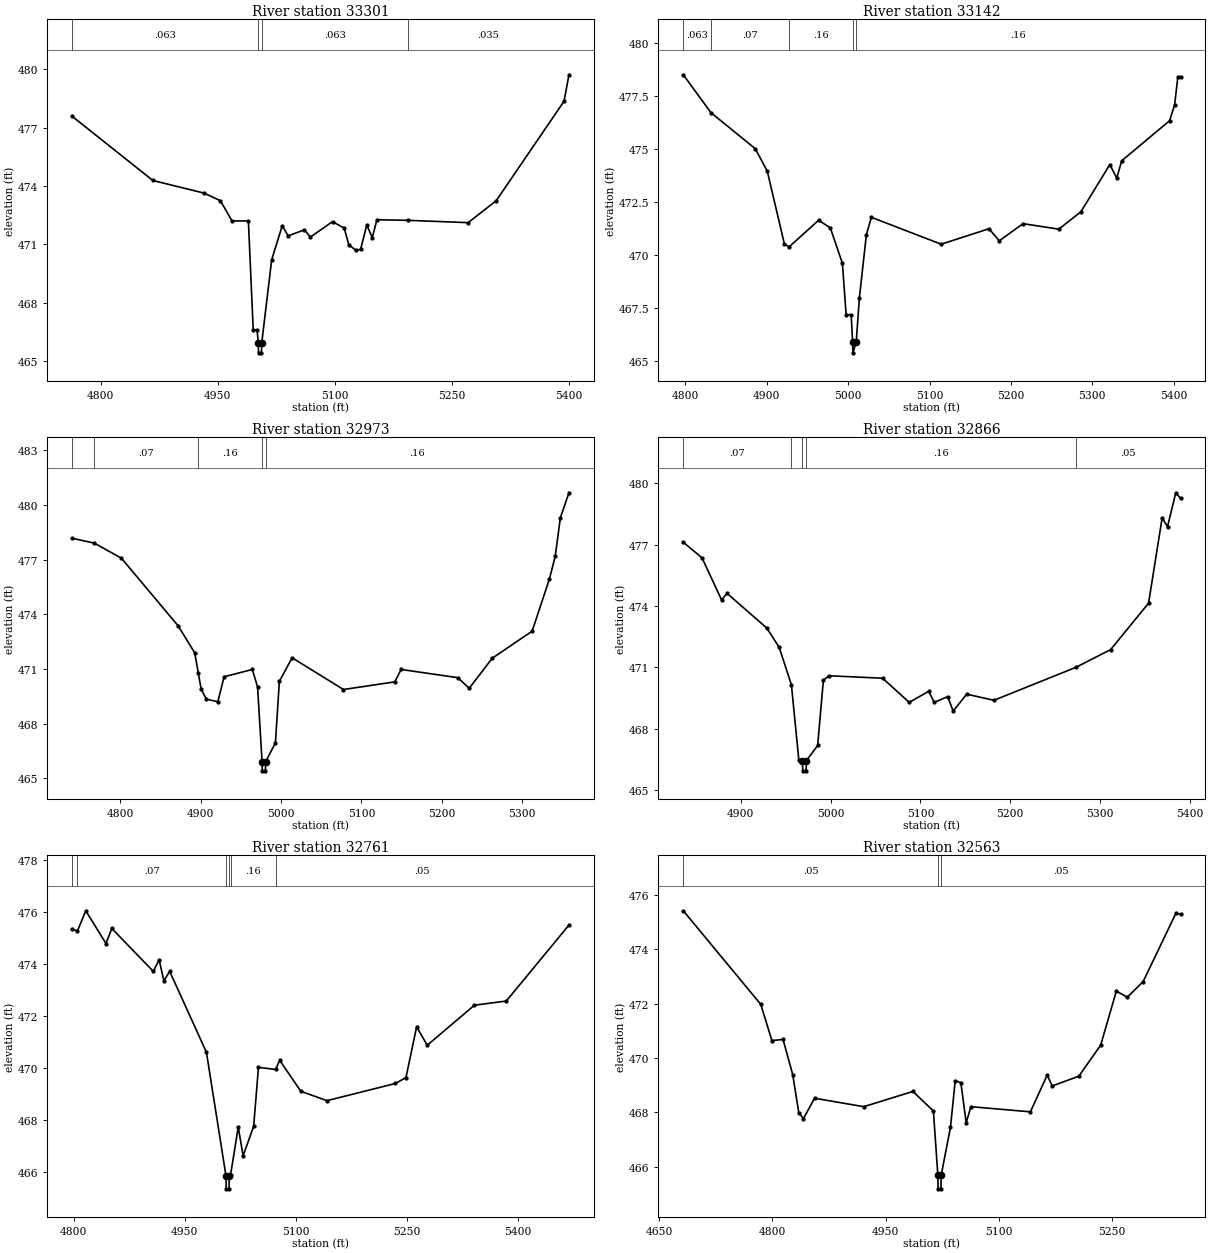
Type RM Length L Ch R = 1,33301,159,159,159
BEGIN DESCRIPTION:
Chamblee Creek33300.79
END DESCRIPTION:
XS GIS Cut Line= 3
      2752603.32      6855318.27      2752738.08      6855514.19
      2752961.15      6855846.23
#Sta/Elev= 30
  4762.7  477.60  4866.8  474.28  4932.5  473.63  4953.4  473.24  4968.3  472.20
  4989.3  472.20  4995.5  466.59  5000.5  466.59  5002.0  465.91  5002.3  465.41
  5006.1  465.41  5006.4  465.91  5019.2  470.20  5032.8  471.96  5040.2  471.43
  5061.2  471.74  5068.9  471.37  5097.2  472.16  5112.2  471.83  5118.2  470.96
  5127.2  470.69  5133.2  470.73  5141.2  471.99  5148.2  471.34  5154.2  472.26
  5193.7  472.23  5271.2  472.11  5307.2  473.24  5394.2  478.36  5400.5  479.72
#Mann=4,-1,0
  4762.7   0.063       0  5002.0   0.063       0  5006.4   0.063       0
  5193.7   0.035       0
Bank Sta=5002,5006.4
Exp/Cntr=0.3,0.1

Type RM Length L Ch R = 1,33142,169,169,169
BEGIN DESCRIPTION:
Chamblee Creek33142.49
END DESCRIPTION:
XS GIS Cut Line= 3
      2752539.21      6855465.02      2752656.32      6855631.27
      2752895.75      6855961.31
#Sta/Elev= 30
  4797.4  478.50  4831.4  476.71  4885.8  475.01  4900.6  473.95  4921.5  470.53
  4927.3  470.37  4963.7  471.63  4978.1  471.27  4992.9  469.60  4997.5  467.17
  5003.7  467.17  5005.5  465.87  5005.8  465.37  5009.9  465.87  5013.8  467.97
  5022.4  470.95  5028.5  471.77  5114.3  470.50  5173.1  471.23  5185.7  470.66
  5214.9  471.47  5258.9  471.21  5286.0  472.03  5321.6  474.26  5330.1  473.62
  5336.2  474.44  5395.0  476.33  5401.2  477.08  5405.2  478.41  5408.5  478.41
#Mann=5,-1,0
  4797.4   0.063       0  4831.4    0.07       0  4927.3    0.16       0
  5005.5    0.07       0  5009.9    0.16       0
Bank Sta=5005.5,5009.9
Exp/Cntr=0.3,0.1

Type RM Length L Ch R = 1,32973,107,107,107
BEGIN DESCRIPTION:
Chamblee Creek32973.36
END DESCRIPTION:
XS GIS Cut Line= 3
      2752368.48      6855602.19      2752568.56      6855768.77
      2752844.79      6855996.43
#Sta/Elev= 30
  4739.7  478.17  4767.8  477.90  4801.5  477.07  4871.9  473.37  4892.7  471.88
  4897.0  470.80  4900.5  469.92  4907.0  469.34  4921.4  469.20  4929.2  470.57
  4964.3  470.97  4970.8  470.01  4976.4  465.91  4976.7  465.41  4980.5  465.41
  4980.8  465.91  4993.0  466.94  4997.9  470.32  5013.8  471.61  5077.6  469.87
  5141.5  470.29  5149.3  470.97  5219.7  470.52  5234.0  469.94  5262.7  471.59
  5312.2  473.07  5333.7  475.93  5340.9  477.17  5347.3  479.29  5358.0  480.66
#Mann=5,-1,0
  4739.7    0.05       0  4767.8    0.07       0  4897.0    0.16       0
  4976.4    0.07       0  4980.8    0.16       0
Bank Sta=4976.4,4980.8
Exp/Cntr=0.3,0.1

Type RM Length L Ch R = 1,32866,105,105,105
BEGIN DESCRIPTION:
Chamblee Creek32866.19
END DESCRIPTION:
XS GIS Cut Line= 3
      2752359.07      6855749.33      2752491.12      6855843.42
      2752819.32      6856056.42
#Sta/Elev= 30
  4836.1  477.11  4856.9  476.35  4878.7  474.29  4884.8  474.61  4929.1  472.91
  4942.8  471.97  4956.4  470.14  4964.7  466.44  4968.7  466.43  4969.0  465.93
  4972.8  465.93  4973.1  466.43  4985.6  467.17  4992.0  470.36  4998.2  470.58
  5057.9  470.46  5087.5  469.28  5109.3  469.82  5115.3  469.28  5130.4  469.56
  5136.4  468.85  5151.5  469.68  5181.8  469.38  5272.9  470.99  5311.7  471.86
  5353.9  474.13  5369.0  478.30  5375.0  477.87  5384.2  479.53  5389.5  479.26
#Mann=5,-1,0
  4836.1    0.07       0  4956.4    0.16       0  4968.7    0.07       0
  4973.1    0.16       0  5272.9    0.05       0
Bank Sta=4968.7,4973.1
Exp/Cntr=0.3,0.1

Type RM Length L Ch R = 1,32761,198,198,198
BEGIN DESCRIPTION:
Chamblee Creek32761.36
END DESCRIPTION:
XS GIS Cut Line= 3
      2752261.11      6855790.06      2752419.05      6855918.98
      2752779.75      6856217.07
#Sta/Elev= 30
  4797.2  475.33  4805.0  475.27  4816.2  476.04  4843.5  474.78  4851.4  475.36
  4907.4  473.71  4915.3  474.16  4921.7  473.35  4929.6  473.71  4979.2  470.60
  5005.6  465.85  5005.9  465.35  5009.7  465.35  5010.0  465.85  5011.8  465.88
  5022.2  467.73  5028.7  466.62  5043.0  467.75  5049.5  470.02  5072.6  469.94
  5078.2  470.29  5106.8  469.10  5142.0  468.74  5234.5  469.40  5248.8  469.63
  5263.2  471.58  5277.5  470.87  5341.3  472.41  5384.3  472.57  5469.0  475.49
#Mann=6,-1,0
  4797.2    0.05       0  4805.0    0.07       0  5005.6    0.07       0
  5010.0    0.07       0  5011.8    0.16       0  5072.6    0.05       0
Bank Sta=5005.6,5010
Exp/Cntr=0.3,0.1

Type RM Length L Ch R = 1,32563,184,184,184
BEGIN DESCRIPTION:
Chamblee Creek32561.97
END DESCRIPTION:
XS GIS Cut Line= 3
      2752160.97      6855833.12      2752347.27      6856093.89
      2752555.68      6856360.01
#Sta/Elev= 30
  4682.2  475.41  4784.8  471.97  4799.5  470.64  4814.3  470.68  4827.1  469.39
  4835.1  467.99  4841.3  467.77  4856.0  468.52  4921.2  468.21  4986.3  468.77
  5013.4  468.05  5019.3  465.69  5019.6  465.19  5023.4  465.19  5023.7  465.69
  5036.0  467.45  5042.3  469.17  5049.8  469.09  5056.8  467.62  5063.1  468.21
  5141.8  468.02  5164.1  469.37  5170.7  468.97  5206.0  469.33  5234.9  470.47
  5255.7  472.46  5270.2  472.23  5291.2  472.81  5334.4  475.31  5340.7  475.28
#Mann=3,-1,0
  4682.2    0.05       0  5019.3    0.05       0  5023.7    0.05       0
Bank Sta=5019.3,5023.7
Exp/Cntr=0.3,0.1

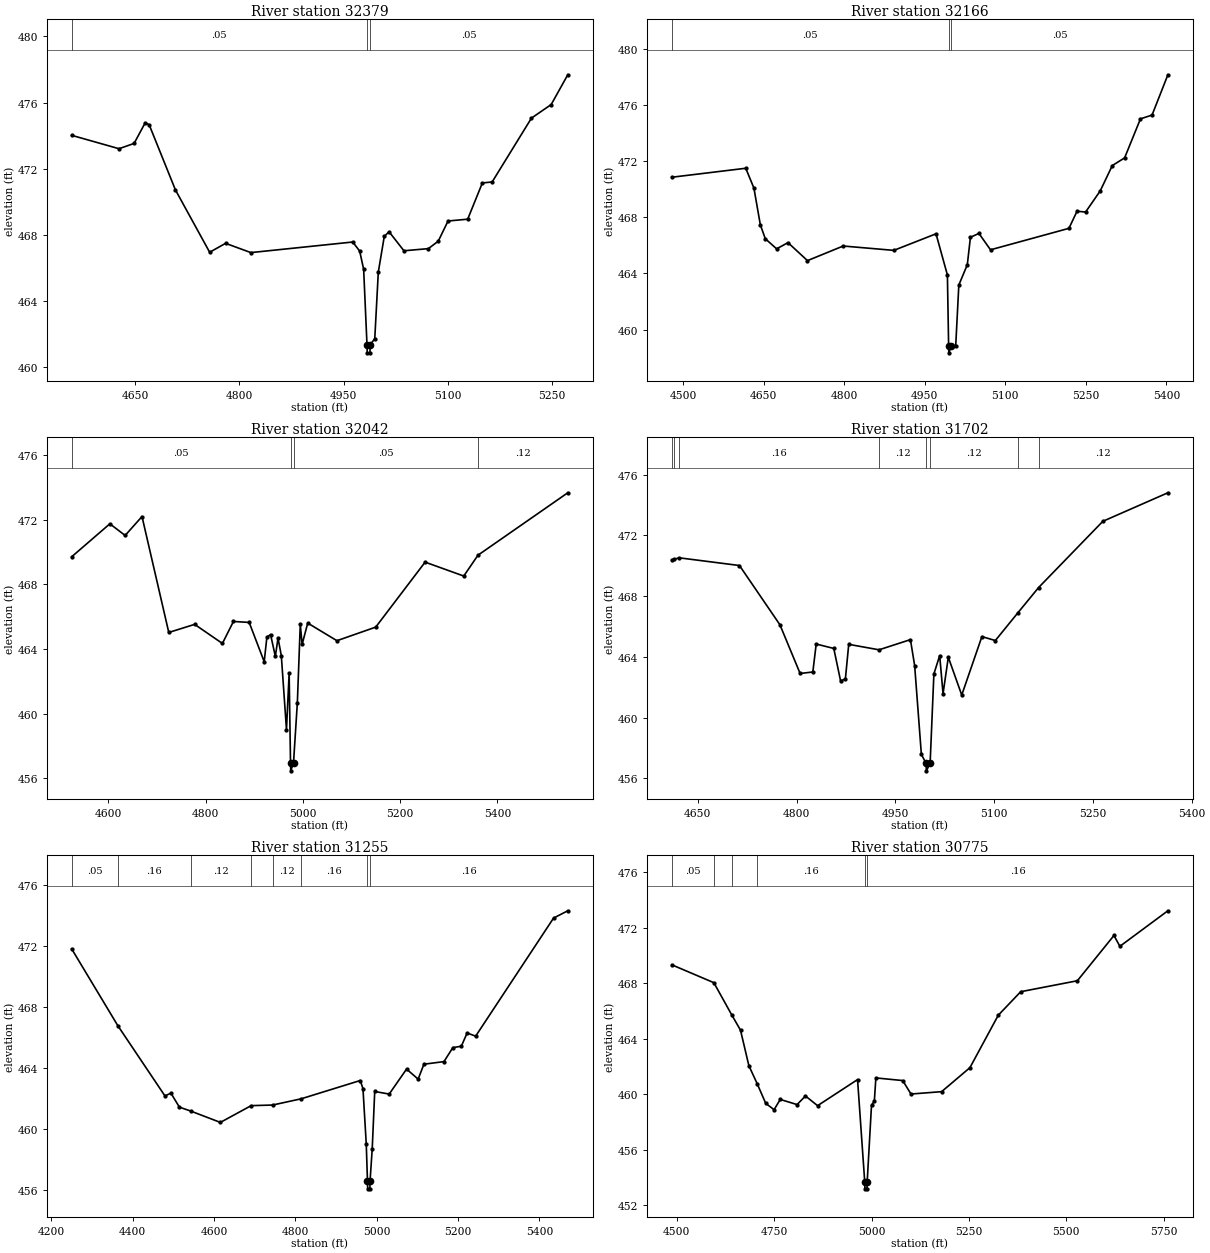
Type RM Length L Ch R = 1,32379,213,213,213
BEGIN DESCRIPTION:
Chamblee Creek32378.95
END DESCRIPTION:
XS GIS Cut Line= 3
      2752057.33      6855867.38      2752272.90      6856254.88
      2752459.92      6856450.83
#Sta/Elev= 30
  4558.4  474.02  4626.6  473.21  4648.3  473.53  4664.3  474.78  4670.0  474.66
  4707.8  470.72  4757.1  466.95  4780.0  467.49  4816.4  466.93  4963.1  467.57
  4973.1  467.02  4978.8  465.92  4983.6  461.37  4984.0  460.87  4987.9  460.87
  4988.2  461.37  4994.8  461.72  4999.9  465.75  5008.5  467.91  5015.4  468.19
  5036.8  467.04  5072.0  467.17  5086.2  467.62  5100.3  468.84  5128.6  468.95
  5149.7  471.14  5163.8  471.20  5220.4  475.06  5248.8  475.88  5272.7  477.68
#Mann=3,-1,0
  4558.4    0.05       0  4983.6    0.05       0  4988.2    0.05       0
Bank Sta=4983.6,4988.2
Exp/Cntr=0.3,0.1

Type RM Length L Ch R = 1,32166,124,124,124
BEGIN DESCRIPTION:
Chamblee Creek32165.527
END DESCRIPTION:
XS GIS Cut Line= 3
      2751795.50      6855871.96      2752076.00      6856311.00
      2752425.99      6856511.00
#Sta/Elev= 30
  4478.8  470.85  4616.6  471.49  4631.8  470.08  4643.8  467.46  4653.0  466.47
  4674.1  465.75  4695.3  466.19  4731.6  464.91  4798.1  465.95  4892.4  465.64
  4971.0  466.82  4992.2  463.89  4994.5  458.84  4994.9  458.34  4999.1  458.84
  5007.7  458.84  5013.5  463.17  5029.3  464.62  5035.1  466.57  5050.9  466.85
  5072.5  465.68  5218.6  467.21  5233.7  468.43  5249.6  468.37  5276.9  469.88
  5299.3  471.68  5322.3  472.23  5351.8  475.01  5373.4  475.28  5402.9  478.15
#Mann=3,-1,0
  4478.8    0.05       0  4994.5    0.05       0  4999.1    0.05       0
Bank Sta=4994.5,4999.1
Exp/Cntr=0.3,0.1

Type RM Length L Ch R = 1,32042,340,340,340
BEGIN DESCRIPTION:
Chamblee Creek32042.44
END DESCRIPTION:
XS GIS Cut Line= 4
      2751753.14      6855879.66      2751953.81      6856312.91
      2751947.29      6856430.73      2751715.25      6856786.96
#Sta/Elev= 30
  4524.3  469.70  4602.9  471.74  4634.3  471.02  4669.0  472.19  4724.1  465.02
  4777.3  465.52  4834.4  464.34  4857.1  465.70  4889.5  465.64  4920.4  463.21
  4925.9  464.73  4933.5  464.89  4943.3  463.54  4948.8  464.67  4955.6  463.59
  4966.2  459.01  4971.7  462.50  4974.5  456.96  4975.0  456.46  4980.7  456.96
  4988.6  460.68  4994.6  465.52  4998.4  464.28  5009.9  465.60  5070.0  464.51
  5149.8  465.35  5251.4  469.37  5330.9  468.51  5360.2  469.80  5544.9  473.66
#Mann=4,-1,0
  4524.3    0.05       0  4974.5    0.05       0  4980.7    0.05       0
  5360.2    0.12       0
Bank Sta=4974.5,4980.7
Exp/Cntr=0.3,0.1

Type RM Length L Ch R = 1,31702,447,447,447
BEGIN DESCRIPTION:
Chamblee Creek31701.5
END DESCRIPTION:
XS GIS Cut Line= 3
      2751726.83      6855930.46      2751642.45      6856323.26
      2751572.78      6856667.83
#Sta/Elev= 30
  4610.5  470.40  4614.4  470.42  4621.3  470.53  4713.3  470.02  4774.7  466.12
  4805.4  462.91  4824.7  463.01  4829.8  464.85  4856.5  464.56  4866.8  462.43
  4874.1  462.54  4879.2  464.83  4925.2  464.47  4972.9  465.14  4979.3  463.43
  4989.5  457.58  4996.6  457.00  4997.1  456.50  5002.8  457.00  5008.5  462.88
  5017.3  464.09  5022.4  461.58  5030.4  463.98  5050.8  461.49  5081.4  465.34
  5101.8  465.08  5136.1  466.91  5167.5  468.57  5265.0  472.93  5363.8  474.81
#Mann=8,-1,0
  4610.5    0.05       0  4614.4    0.12       0  4621.3    0.16       0
  4925.2    0.12       0  4996.6    0.07       0  5002.8    0.12       0
  5136.1    0.16       0  5167.5    0.12       0
Bank Sta=4996.6,5002.8
Exp/Cntr=0.3,0.1

Type RM Length L Ch R = 1,31255,480,480,480
BEGIN DESCRIPTION:
Chamblee Creek31255.24
END DESCRIPTION:
XS GIS Cut Line= 3
      2751773.72      6855448.42      2751331.48      6856066.36
      2751027.98      6856412.31
#Sta/Elev= 30
  4249.8  471.82  4363.3  466.78  4479.2  462.17  4493.9  462.35  4514.8  461.43
  4542.1  461.18  4615.5  460.43  4691.2  461.53  4744.0  461.57  4814.3  461.98
  4959.5  463.18  4966.2  462.65  4974.3  459.01  4977.3  456.57  4977.8  456.07
  4983.1  456.07  4983.6  456.57  4989.0  458.71  4995.1  462.46  5030.7  462.29
  5073.4  463.93  5101.9  463.27  5116.1  464.25  5165.4  464.42  5187.3  465.34
  5208.1  465.43  5222.4  466.30  5243.3  466.09  5434.9  473.84  5469.9  474.32
#Mann=8,-1,0
  4249.8    0.05       0  4363.3    0.16       0  4542.1    0.12       0
  4691.2    0.16       0  4744.0    0.12       0  4814.3    0.16       0
  4977.3    0.07       0  4983.6    0.16       0
Bank Sta=4977.3,4983.6
Exp/Cntr=0.3,0.1

Type RM Length L Ch R = 1,30775,481,481,481
BEGIN DESCRIPTION:
Chamblee Creek30775.06
END DESCRIPTION:
XS GIS Cut Line= 3
      2751520.87      6855156.55      2751258.75      6855612.60
      2750855.90      6856241.88
#Sta/Elev= 30
  4487.4  469.33  4595.4  468.04  4640.9  465.74  4663.8  464.62  4685.3  462.06
  4706.8  460.75  4728.5  459.35  4750.0  458.89  4765.8  459.63  4809.0  459.26
  4830.5  459.88  4861.6  459.18  4964.2  461.06  4982.6  453.69  4983.1  453.19
  4988.4  453.19  4988.9  453.69  5000.0  459.21  5007.3  459.52  5011.2  461.18
  5080.1  460.99  5101.3  460.02  5179.9  460.19  5252.6  461.92  5325.4  465.70
  5382.9  467.39  5528.3  468.18  5622.2  471.44  5637.4  470.66  5760.6  473.22
#Mann=6,-1,0
  4487.4    0.05       0  4595.4    0.16       0  4640.9    0.12       0
  4706.8    0.16       0  4982.6    0.07       0  4988.9    0.16       0
Bank Sta=4982.6,4988.9
Exp/Cntr=0.3,0.1

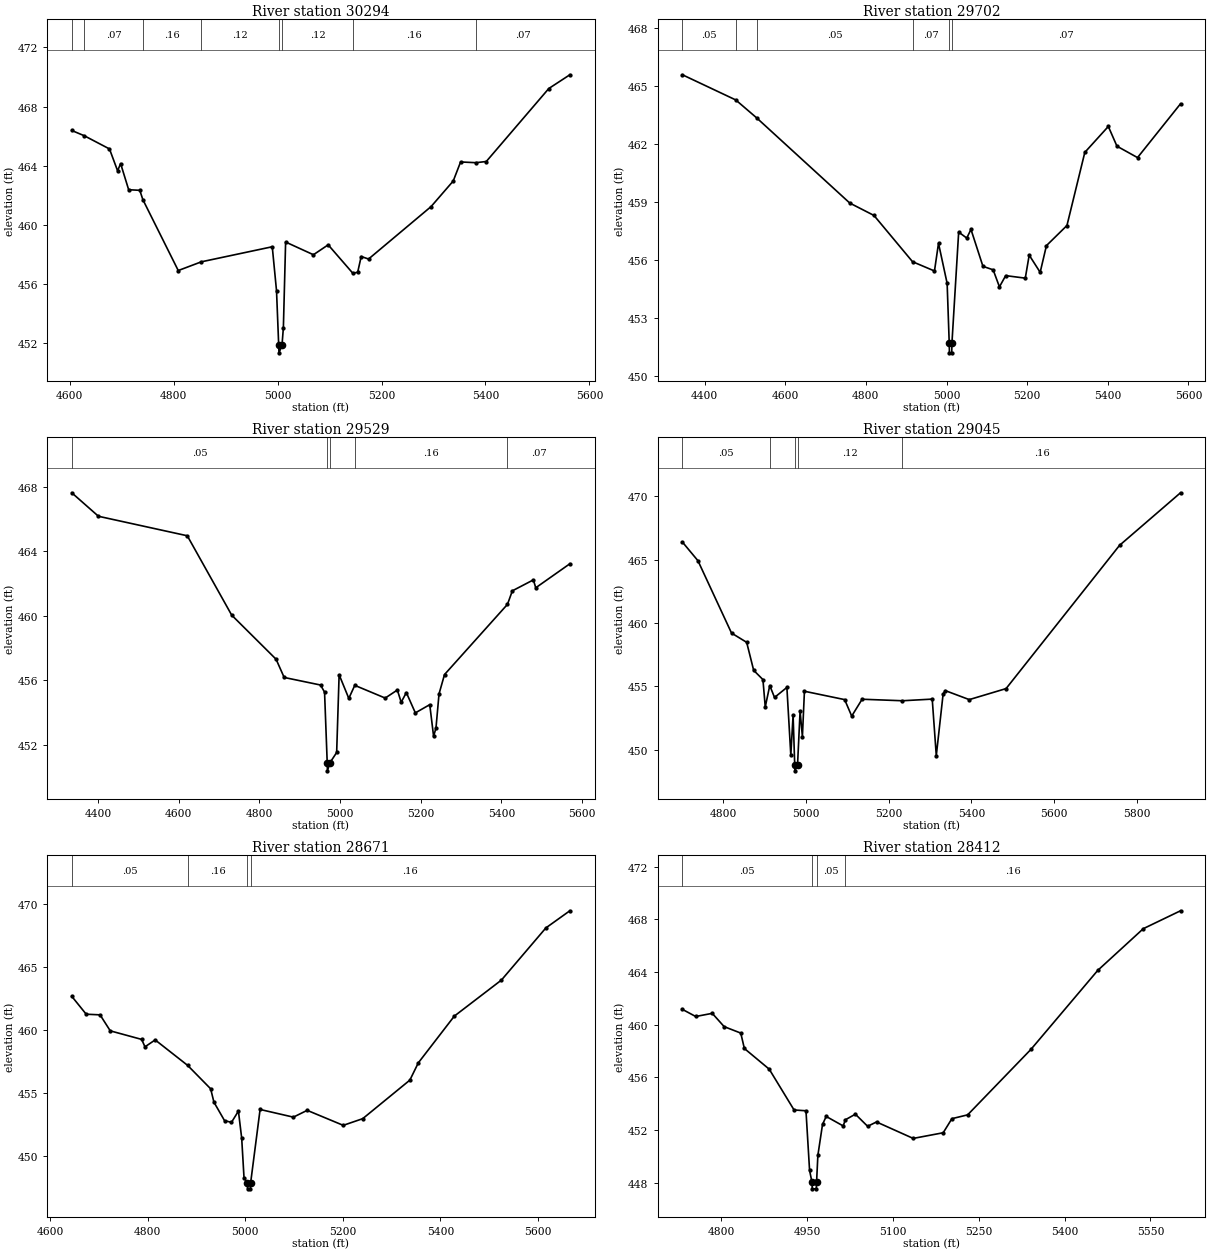
Type RM Length L Ch R = 1,30294,592,592,592
BEGIN DESCRIPTION:
Chamblee Creek30293.85
END DESCRIPTION:
XS GIS Cut Line= 3
      2751117.70      6855122.81      2750906.54      6855476.16
      2750540.47      6855882.29
#Sta/Elev= 30
  4604.0  466.38  4628.3  466.02  4676.6  465.13  4692.2  463.65  4698.0  464.14
  4713.5  462.37  4734.9  462.33  4740.8  461.70  4808.9  456.90  4853.3  457.49
  4989.8  458.51  4998.0  455.53  5002.2  451.83  5002.7  451.33  5008.5  451.83
  5011.2  453.04  5015.5  458.83  5069.0  457.97  5097.4  458.64  5145.0  456.71
  5154.2  456.79  5160.9  457.85  5175.1  457.68  5295.4  461.23  5338.0  462.96
  5352.2  464.25  5381.5  464.20  5401.6  464.28  5521.9  469.22  5562.4  470.15
#Mann=8,-1,0
  4604.0    0.05       0  4628.3    0.07       0  4740.8    0.16       0
  4853.3    0.12       0  5002.2    0.07       0  5008.5    0.12       0
  5145.0    0.16       0  5381.5    0.07       0
Bank Sta=5002.2,5008.5
Exp/Cntr=0.3,0.1

Type RM Length L Ch R = 1,29702,173,173,173
BEGIN DESCRIPTION:
Chamblee Creek29701.98
END DESCRIPTION:
XS GIS Cut Line= 4
      2751280.95      6855029.30      2750624.53      6855031.63
      2750525.22      6855039.63      2750114.66      6855286.45
#Sta/Elev= 30
  4345.1  465.57  4477.3  464.27  4528.8  463.35  4760.1  458.94  4820.1  458.30
  4915.7  455.91  4970.1  455.43  4980.1  456.86  5001.5  454.79  5006.7  451.70
  5007.2  451.20  5012.9  451.20  5013.4  451.70  5030.1  457.44  5050.2  457.13
  5060.6  457.58  5090.3  455.67  5115.6  455.49  5131.2  454.61  5146.7  455.19
  5195.3  455.06  5205.0  456.25  5232.2  455.36  5247.7  456.74  5298.6  457.78
  5342.9  461.56  5401.2  462.90  5422.6  461.88  5473.6  461.29  5580.2  464.07
#Mann=6,-1,0
  4345.1    0.05       0  4477.3    0.07       0  4528.8    0.05       0
  4915.7    0.07       0  5006.7    0.07       0  5013.4    0.07       0
Bank Sta=5006.7,5013.4
Exp/Cntr=0.3,0.1

Type RM Length L Ch R = 1,29529,484,484,484
BEGIN DESCRIPTION:
Chamblee Creek29529.17
END DESCRIPTION:
XS GIS Cut Line= 4
      2751252.20      6854851.97      2750588.73      6854872.31
      2750432.05      6854884.11      2750079.93      6855100.88
#Sta/Elev= 30
  4335.4  467.64  4401.6  466.18  4621.7  464.97  4731.8  460.04  4841.8  457.30
  4861.8  456.17  4951.9  455.70  4961.9  455.26  4968.5  450.87  4969.0  450.37
  4975.2  450.87  4991.9  451.51  4998.0  456.34  5022.0  454.87  5036.8  455.68
  5112.2  454.89  5142.3  455.39  5151.8  454.63  5164.6  455.23  5186.9  453.97
  5222.6  454.48  5232.1  452.52  5238.0  453.02  5245.6  455.15  5259.2  456.35
  5415.2  460.71  5427.3  461.55  5479.4  462.23  5485.3  461.74  5569.8  463.23
#Mann=5,-1,0
  4335.4    0.05       0  4968.5    0.05       0  4975.2    0.05       0
  5036.8    0.16       0  5415.2    0.07       0
Bank Sta=4968.5,4975.2
Exp/Cntr=0.3,0.1

Type RM Length L Ch R = 1,29045,374,374,374
BEGIN DESCRIPTION:
Chamblee Creek29045.43
END DESCRIPTION:
XS GIS Cut Line= 3
      2750462.41      6854498.31      2750194.90      6854630.40
      2749336.21      6854917.96
#Sta/Elev= 30
  4701.5  466.39  4739.0  464.92  4820.2  459.21  4856.8  458.48  4873.7  456.27
  4896.1  455.54  4901.7  453.38  4912.6  455.07  4924.1  454.13  4954.0  454.92
  4963.5  449.58  4969.0  452.74  4972.9  448.84  4973.4  448.34  4979.8  448.84
  4985.9  453.05  4991.5  451.04  4996.4  454.62  5093.6  453.96  5110.7  452.66
  5135.8  453.99  5233.3  453.87  5305.3  454.00  5315.1  449.54  5331.6  454.40
  5336.9  454.67  5394.8  453.96  5483.8  454.83  5758.0  466.13  5905.4  470.28
#Mann=5,-1,0
  4701.5    0.05       0  4912.6    0.12       0  4972.9    0.07       0
  4979.8    0.12       0  5233.3    0.16       0
Bank Sta=4972.9,4979.8
Exp/Cntr=0.3,0.1

Type RM Length L Ch R = 1,28671,259,259,259
BEGIN DESCRIPTION:
Chamblee Creek28670.55
END DESCRIPTION:
XS GIS Cut Line= 3
      2750183.15      6854266.41      2749917.51      6854502.48
      2749316.09      6854786.75
#Sta/Elev= 30
  4644.6  462.67  4674.2  461.25  4702.6  461.20  4723.5  459.93  4787.9  459.25
  4794.6  458.66  4815.5  459.21  4882.0  457.19  4929.2  455.33  4935.9  454.27
  4957.7  452.80  4971.9  452.67  4986.1  453.56  4992.8  451.41  4997.6  448.25
  5004.3  447.89  5004.8  447.39  5010.7  447.39  5011.2  447.89  5030.5  453.69
  5098.7  453.08  5127.0  453.62  5200.9  452.43  5240.8  452.96  5337.4  456.02
  5354.7  457.39  5428.5  461.10  5525.0  463.96  5616.1  468.10  5665.2  469.46
#Mann=4,-1,0
  4644.6    0.05       0  4882.0    0.16       0  5004.3    0.07       0
  5011.2    0.16       0
Bank Sta=5004.3,5011.2
Exp/Cntr=0.3,0.1

Type RM Length L Ch R = 1,28412,318,318,318
BEGIN DESCRIPTION:
Chamblee Creek28411.51
END DESCRIPTION:
XS GIS Cut Line= 3
      2749990.54      6854152.70      2749778.02      6854319.01
      2749263.96      6854628.71
#Sta/Elev= 30
  4732.5  461.15  4755.7  460.61  4784.6  460.85  4805.4  459.84  4834.4  459.35
  4840.7  458.18  4884.1  456.61  4927.5  453.51  4948.3  453.45  4954.6  448.92
  4958.8  448.02  4959.3  447.52  4966.3  447.52  4966.8  448.02  4969.1  450.07
  4977.2  452.41  4983.6  453.02  5013.2  452.30  5017.3  452.77  5034.6  453.19
  5056.0  452.27  5071.5  452.60  5135.6  451.35  5188.0  451.78  5203.2  452.85
  5230.7  453.14  5341.4  458.12  5457.9  464.11  5537.5  467.28  5602.5  468.64
#Mann=4,-1,0
  4732.5    0.05       0  4958.8    0.05       0  4966.8    0.05       0
  5017.3    0.16       0
Bank Sta=4958.8,4966.8
Exp/Cntr=0.3,0.1

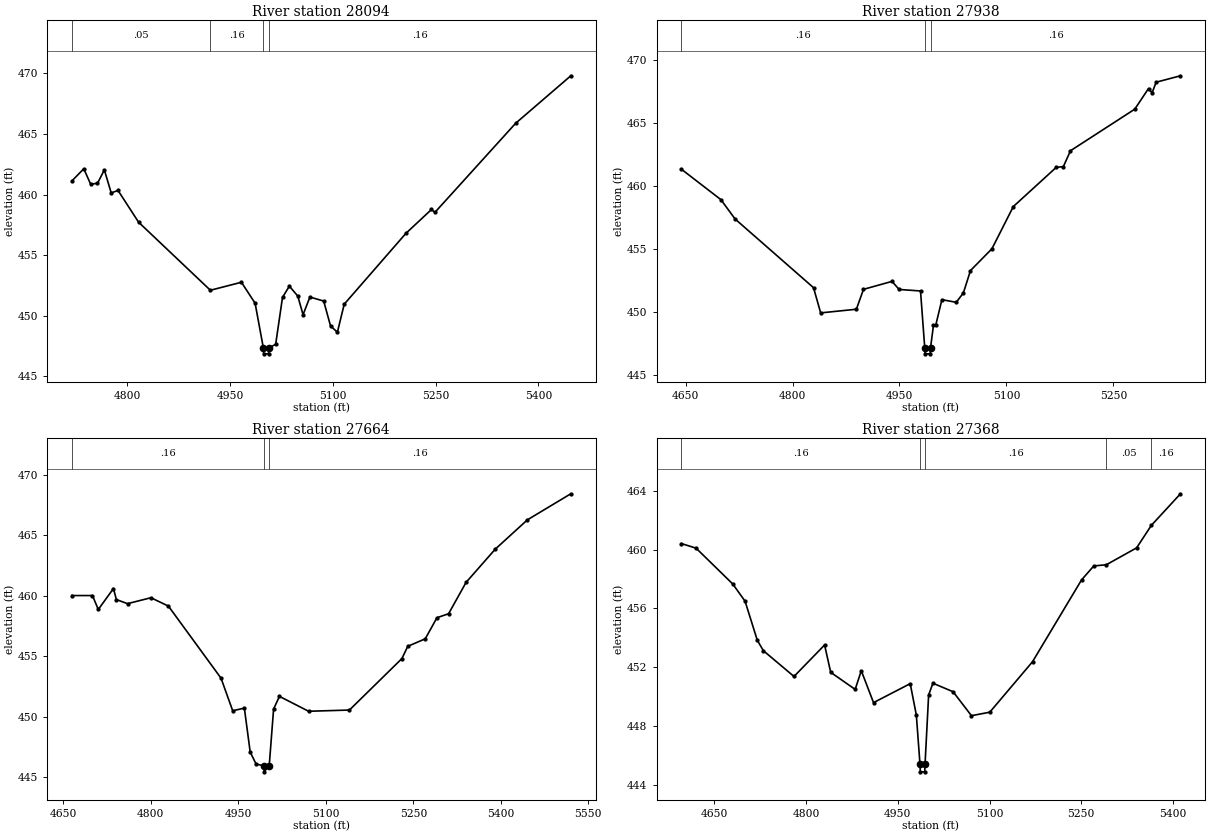
Type RM Length L Ch R = 1,28094,156,156,156
BEGIN DESCRIPTION:
Chamblee Creek28093.7
END DESCRIPTION:
XS GIS Cut Line= 3
      2749903.52      6854109.02      2749618.73      6854103.89
      2749175.62      6854126.04
#Sta/Elev= 30
  4718.8  461.12  4736.3  462.13  4746.3  460.86  4756.3  460.93  4766.3  462.04
  4776.3  460.14  4786.3  460.34  4816.3  457.72  4921.1  452.10  4966.4  452.76
  4986.4  451.03  4998.4  447.35  4998.9  446.85  5006.0  446.85  5006.5  447.35
  5016.4  447.63  5026.4  451.51  5036.4  452.44  5048.7  451.62  5056.4  450.08
  5066.4  451.54  5086.5  451.21  5096.5  449.16  5106.5  448.63  5116.5  450.95
  5206.6  456.80  5243.9  458.77  5248.9  458.53  5366.8  465.89  5447.3  469.81
#Mann=4,-1,0
  4718.8    0.05       0  4921.1    0.16       0  4998.4    0.07       0
  5006.5    0.16       0
Bank Sta=4998.4,5006.5
Exp/Cntr=0.3,0.1

Type RM Length L Ch R = 1,27938,274,274,274
BEGIN DESCRIPTION:
Chamblee Creek27938
END DESCRIPTION:
XS GIS Cut Line= 3
      2749881.22      6853999.38      2749524.62      6853987.32
      2749181.98      6854008.50
#Sta/Elev= 30
  4644.1  461.30  4699.4  458.89  4719.4  457.35  4829.4  451.90  4839.4  449.90
  4889.5  450.19  4899.5  451.77  4939.5  452.40  4949.5  451.76  4979.5  451.64
  4985.4  447.15  4985.9  446.65  4993.1  446.65  4993.6  447.15  4997.7  448.93
  5000.9  448.93  5009.5  450.95  5029.6  450.74  5039.6  451.48  5049.6  453.26
  5079.7  454.99  5109.7  458.34  5169.9  461.45  5179.9  461.51  5189.9  462.77
  5280.1  466.07  5299.4  467.71  5304.4  467.37  5310.1  468.21  5344.2  468.72
#Mann=3,-1,0
  4644.1    0.16       0  4985.4    0.07       0  4993.6    0.16       0
Bank Sta=4985.4,4993.6
Exp/Cntr=0.3,0.1

Type RM Length L Ch R = 1,27664,296,296,296
BEGIN DESCRIPTION:
Chamblee Creek27664.24
END DESCRIPTION:
XS GIS Cut Line= 3
      2749961.36      6853780.08      2749625.90      6853761.16
      2749106.53      6853755.14
#Sta/Elev= 30
  4664.5  460.01  4699.9  460.01  4709.9  458.86  4735.9  460.59  4740.9  459.68
  4760.0  459.34  4800.1  459.83  4830.1  459.14  4920.3  453.19  4940.3  450.50
  4960.3  450.72  4970.3  447.09  4980.4  446.10  4993.8  445.96  4994.3  445.46
  5002.0  445.96  5002.9  445.96  5010.4  450.64  5020.4  451.69  5070.4  450.46
  5140.4  450.56  5230.4  454.81  5240.4  455.82  5270.4  456.44  5290.4  458.18
  5310.4  458.51  5340.4  461.10  5390.4  463.84  5445.5  466.26  5519.9  468.41
#Mann=3,-1,0
  4664.5    0.16       0  4993.8    0.07       0  5002.0    0.16       0
Bank Sta=4993.8,5002
Exp/Cntr=0.3,0.1

Type RM Length L Ch R = 1,27368,389,389,389
BEGIN DESCRIPTION:
Chamblee Creek27368.03
END DESCRIPTION:
XS GIS Cut Line= 3
      2749959.91      6853481.33      2749546.96      6853492.16
      2749144.37      6853501.50
#Sta/Elev= 30
  4596.3  460.41  4620.2  460.10  4680.2  457.66  4700.3  456.49  4720.3  453.83
  4730.3  453.12  4780.3  451.37  4830.3  453.51  4840.3  451.65  4880.3  450.49
  4890.3  451.76  4910.3  449.59  4970.3  450.88  4980.3  448.74  4986.3  445.38
  4986.8  444.88  4994.0  444.88  4994.5  445.38  5000.4  450.11  5007.4  450.91
  5040.4  450.33  5070.4  448.70  5100.4  448.94  5170.2  452.37  5250.4  457.94
  5270.4  458.89  5290.9  458.97  5340.4  460.12  5364.5  461.65  5412.1  463.80
#Mann=5,-1,0
  4596.3    0.16       0  4986.3    0.07       0  4994.5    0.16       0
  5290.9    0.05       0  5364.5    0.16       0
Bank Sta=4986.3,4994.5
Exp/Cntr=0.3,0.1