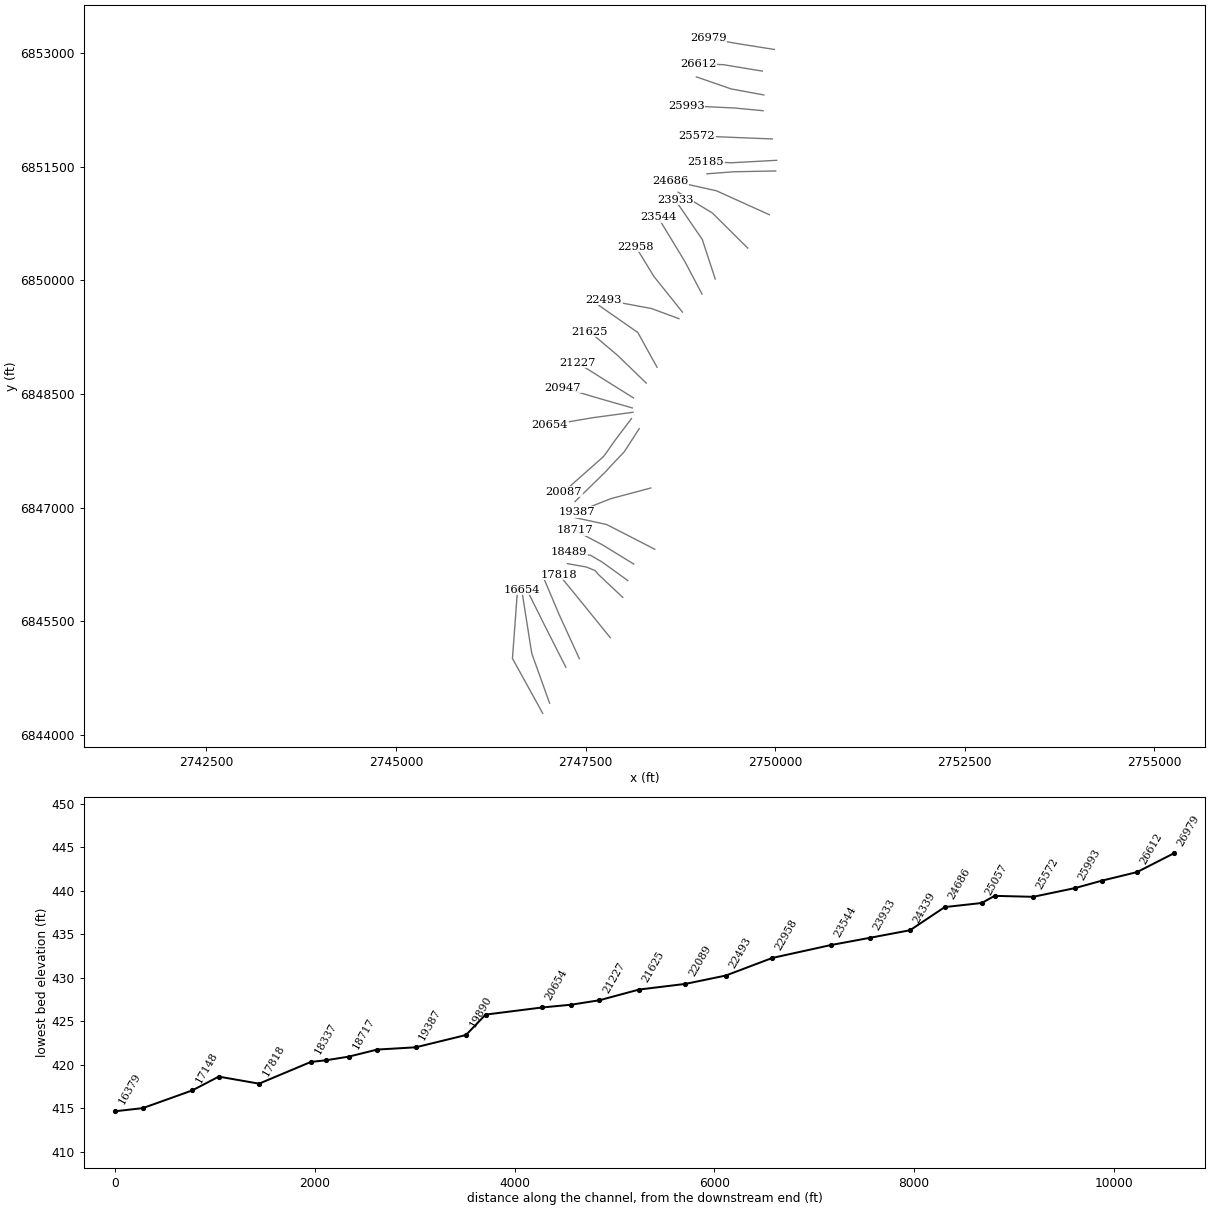
HEC-RAS study Chamblee Creek.prj: Chamblee Creek Base Level Engineering

--- Chamblee Creek.g01 (geometry) --- (continued)

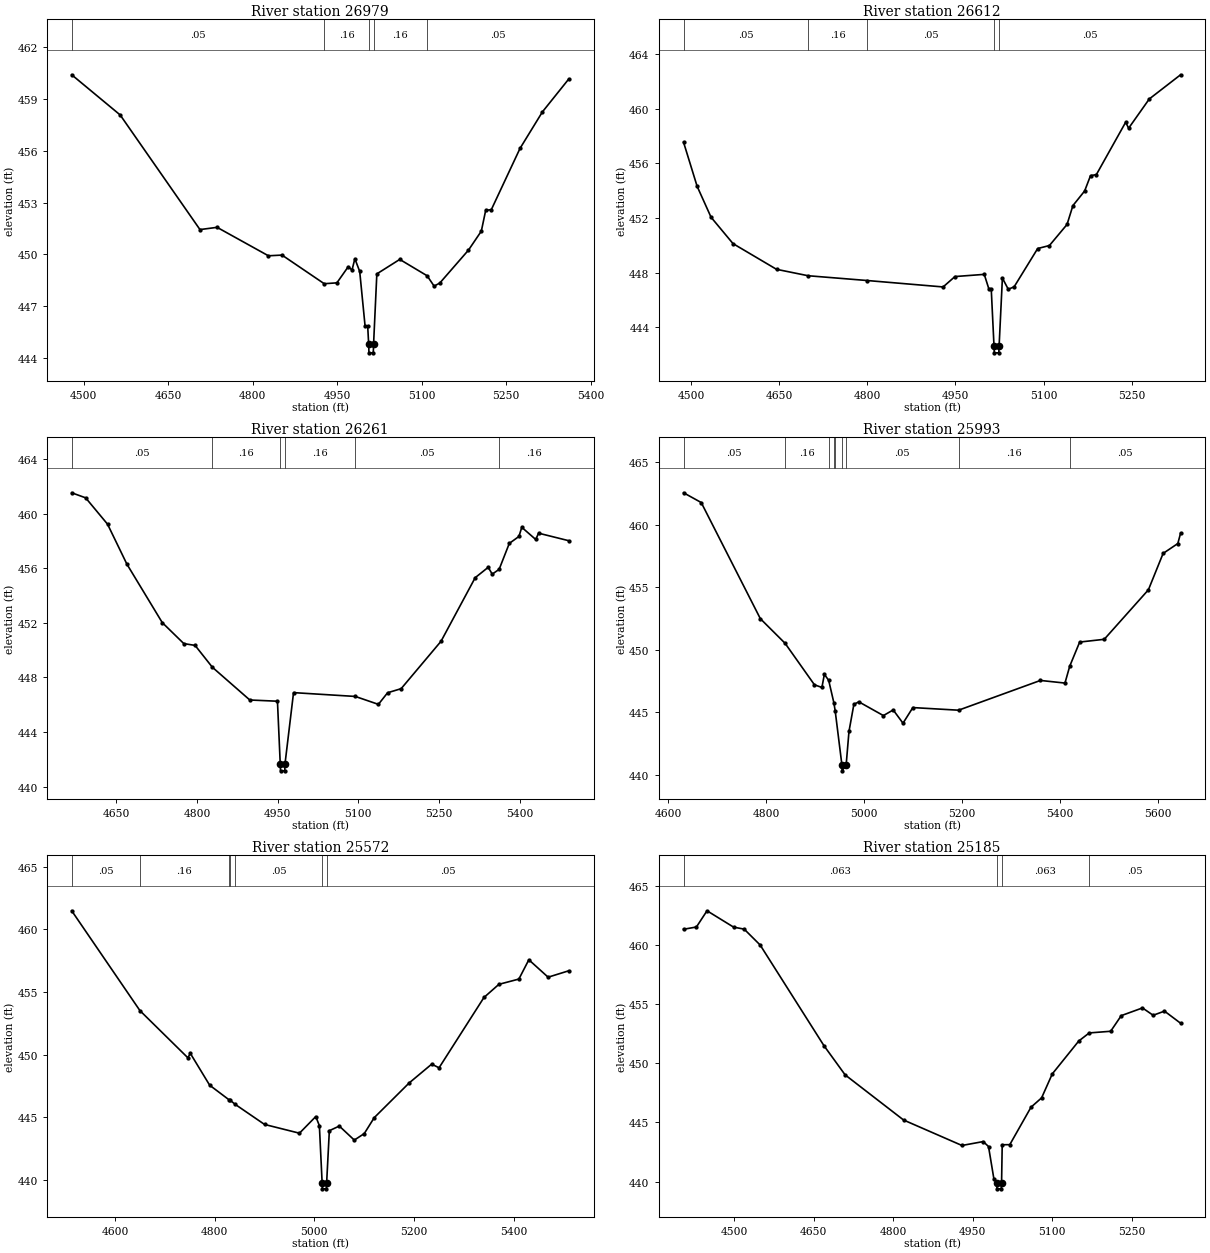
Type RM Length L Ch R = 1,26979,367,367,367
BEGIN DESCRIPTION:
Chamblee Creek26979.15
END DESCRIPTION:
XS GIS Cut Line= 3
      2749990.89      6853047.40      2749471.98      6853130.14
      2749120.98      6853194.40
#Sta/Elev= 30
  4478.7  460.41  4564.7  458.08  4706.4  451.43  4736.8  451.56  4827.9  449.91
  4852.1  449.95  4927.0  448.29  4949.5  448.34  4969.7  449.28  4976.3  449.08
  4981.4  449.74  4990.0  449.00  4999.6  445.81  5004.2  445.81  5005.9  444.78
  5006.4  444.28  5014.1  444.28  5014.6  444.78  5020.4  448.86  5061.1  449.70
  5109.7  448.75  5122.1  448.15  5132.2  448.33  5183.1  450.24  5205.9  451.34
  5213.6  452.54  5223.7  452.59  5274.6  456.14  5314.4  458.26  5361.0  460.16
#Mann=5,-1,0
  4478.7    0.05       0  4927.0    0.16       0  5005.9    0.07       0
  5014.6    0.16       0  5109.7    0.05       0
Bank Sta=5005.9,5014.6
Exp/Cntr=0.3,0.1

Type RM Length L Ch R = 1,26612,351,351,351
BEGIN DESCRIPTION:
Chamblee Creek26612.1
END DESCRIPTION:
XS GIS Cut Line= 3
      2749832.17      6852761.97      2749319.04      6852846.59
      2748992.76      6852859.51
#Sta/Elev= 30
  4486.8  457.53  4509.9  454.31  4533.6  452.05  4571.0  450.12  4645.1  448.24
  4698.9  447.77  4799.6  447.42  4928.9  446.95  4949.1  447.71  4999.0  447.87
  5006.9  446.80  5010.9  446.80  5015.6  442.63  5016.1  442.13  5023.8  442.13
  5024.3  442.63  5029.9  447.60  5039.9  446.78  5049.9  446.96  5090.0  449.76
  5110.0  449.98  5140.0  451.52  5150.0  452.90  5170.0  453.97  5180.0  455.09
  5190.0  455.17  5239.9  459.00  5244.9  458.56  5280.1  460.70  5333.4  462.47
#Mann=5,-1,0
  4486.8    0.05       0  4698.9    0.16       0  4799.6    0.05       0
  5015.6    0.05       0  5024.3    0.05       0
Bank Sta=5015.6,5024.3
Exp/Cntr=0.3,0.1

Type RM Length L Ch R = 1,26261,268,268,268
BEGIN DESCRIPTION:
Chamblee Creek26260.86
END DESCRIPTION:
XS GIS Cut Line= 3
      2749851.44      6852447.26      2749420.73      6852526.93
      2748961.69      6852685.57
#Sta/Elev= 30
  4567.2  461.52  4593.1  461.15  4633.8  459.22  4669.8  456.29  4735.5  452.01
  4775.6  450.47  4796.5  450.34  4828.6  448.74  4898.2  446.34  4949.6  446.25
  4954.8  441.65  4955.3  441.15  4963.1  441.15  4963.6  441.65  4979.5  446.88
  5094.3  446.60  5137.2  446.02  5154.3  446.87  5179.5  447.17  5253.6  450.64
  5317.1  455.30  5341.3  456.06  5348.8  455.56  5361.6  455.91  5380.5  457.81
  5398.4  458.32  5403.7  458.99  5429.6  458.10  5434.9  458.56  5490.9  458.01
#Mann=6,-1,0
  4567.2    0.05       0  4828.6    0.16       0  4954.8    0.07       0
  4963.6    0.16       0  5094.3    0.05       0  5361.6    0.16       0
Bank Sta=4954.8,4963.6
Exp/Cntr=0.3,0.1

Type RM Length L Ch R = 1,25993,421,421,421
BEGIN DESCRIPTION:
Chamblee Creek25992.87
END DESCRIPTION:
XS GIS Cut Line= 3
      2749841.84      6852239.20      2749464.98      6852275.15
      2748830.45      6852304.84
#Sta/Elev= 30
  4631.7  462.54  4667.7  461.76  4788.3  452.47  4838.8  450.50  4898.7  447.18
  4913.9  446.97  4918.9  448.02  4927.7  447.54  4938.2  445.76  4940.9  445.12
  4954.6  440.80  4955.1  440.30  4963.4  440.80  4969.1  443.45  4979.1  445.62
  4989.2  445.82  5039.3  444.72  5059.3  445.17  5079.3  444.11  5099.4  445.36
  5192.6  445.15  5359.6  447.53  5409.7  447.32  5419.4  448.67  5439.7  450.60
  5489.8  450.82  5579.9  454.78  5609.9  457.69  5639.9  458.48  5645.5  459.30
#Mann=9,-1,0
  4631.7    0.05       0  4838.8    0.16       0  4927.7    0.05       0
  4938.2    0.16       0  4940.9    0.05       0  4954.6    0.05       0
  4963.4    0.05       0  5192.6    0.16       0  5419.4    0.05       0
Bank Sta=4954.6,4963.4
Exp/Cntr=0.3,0.1

Type RM Length L Ch R = 1,25572,387,387,387
BEGIN DESCRIPTION:
Chamblee Creek25572.49
END DESCRIPTION:
XS GIS Cut Line= 3
      2749962.70      6851866.67      2749475.39      6851886.09
      2748966.04      6851907.58
#Sta/Elev= 30
  4513.2  461.48  4650.2  453.51  4746.3  449.75  4751.3  450.10  4790.1  447.56
  4828.5  446.41  4831.5  446.35  4841.4  446.03  4900.2  444.43  4970.3  443.73
  5003.1  445.06  5010.3  444.33  5015.8  439.79  5016.3  439.29  5024.4  439.29
  5024.9  439.79  5030.3  443.93  5050.3  444.30  5080.4  443.18  5100.4  443.70
  5120.4  444.97  5190.5  447.74  5235.7  449.24  5250.5  448.95  5340.6  454.56
  5370.6  455.61  5410.7  456.03  5430.7  457.57  5469.4  456.18  5510.7  456.69
#Mann=7,-1,0
  4513.2    0.05       0  4650.2    0.16       0  4828.5    0.05       0
  4831.5    0.16       0  4841.4    0.05       0  5015.8    0.05       0
  5024.9    0.05       0
Bank Sta=5015.8,5024.9
Exp/Cntr=0.3,0.1

Type RM Length L Ch R = 1,25185,128,128,128
BEGIN DESCRIPTION:
Chamblee Creek25185.19
END DESCRIPTION:
XS GIS Cut Line= 3
      2750020.17      6851584.90      2749419.55      6851552.24
      2749084.31      6851567.54
#Sta/Elev= 30
  4404.9  461.31  4429.1  461.50  4449.1  462.87  4499.2  461.49  4519.2  461.32
  4549.3  459.98  4669.5  451.49  4709.5  449.02  4819.7  445.21  4929.8  443.06
  4969.9  443.39  4979.9  442.97  4989.9  440.27  4995.4  439.90  4995.9  439.40
  5004.0  439.40  5004.5  439.90  5005.7  443.12  5020.0  443.13  5060.0  446.29
  5080.0  447.08  5100.1  449.10  5150.1  451.88  5169.8  452.56  5210.2  452.70
  5230.2  454.02  5270.2  454.67  5290.3  454.05  5311.7  454.40  5342.0  453.38
#Mann=4,-1,0
  4404.9   0.063       0  4995.4   0.063       0  5004.5   0.063       0
  5169.8    0.05       0
Bank Sta=4995.4,5004.5
Exp/Cntr=0.3,0.1

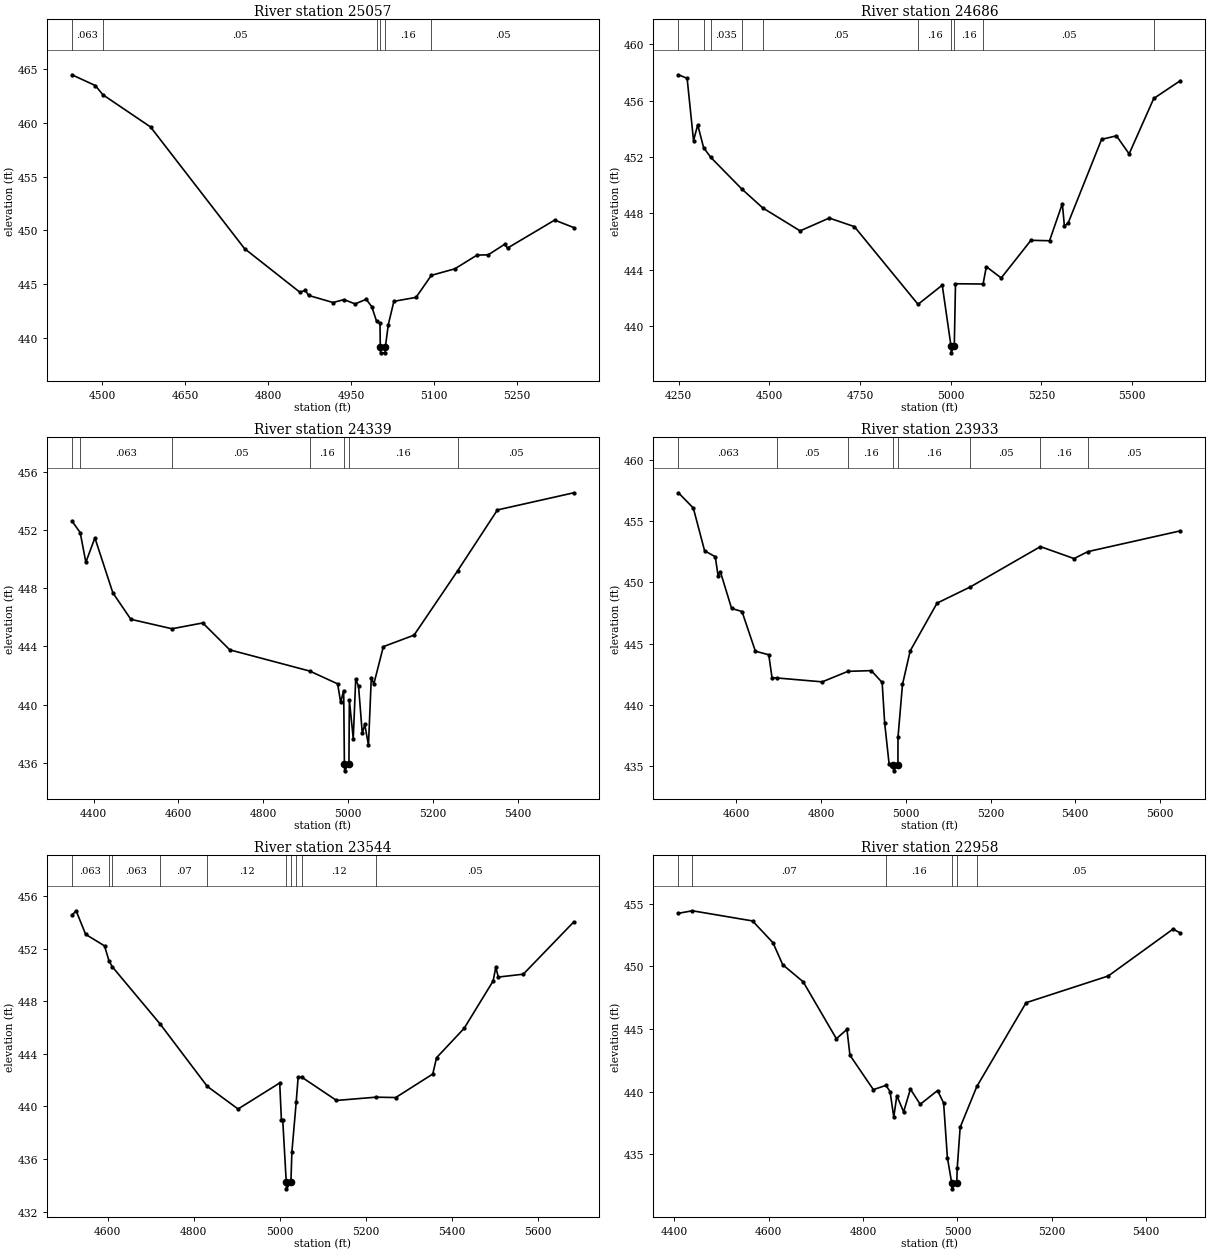
Type RM Length L Ch R = 1,25057,371,371,371
BEGIN DESCRIPTION:
Chamblee Creek25057.09
END DESCRIPTION:
XS GIS Cut Line= 3
      2750008.10      6851444.34      2749451.05      6851433.50
      2749101.42      6851406.89
#Sta/Elev= 30
  4445.4  464.49  4487.5  463.49  4501.6  462.62  4587.5  459.63  4757.6  448.29
  4857.6  444.23  4867.6  444.40  4873.4  443.93  4917.6  443.27  4937.6  443.54
  4957.6  443.14  4977.6  443.57  4987.6  442.89  4996.3  441.53  5002.6  441.33
  5003.1  439.08  5003.6  438.58  5011.7  438.58  5012.2  439.08  5017.6  441.21
  5027.7  443.38  5067.8  443.75  5095.4  445.80  5138.0  446.41  5178.1  447.69
  5198.2  447.71  5228.2  448.70  5233.2  448.34  5318.5  450.95  5353.2  450.25
#Mann=6,-1,0
  4445.4   0.063       0  4501.6    0.05       0  4996.3    0.16       0
  5003.1    0.07       0  5012.2    0.16       0  5095.4    0.05       0
Bank Sta=5003.1,5012.2
Exp/Cntr=0.3,0.1

Type RM Length L Ch R = 1,24686,347,347,347
BEGIN DESCRIPTION:
Chamblee Creek24685.62
END DESCRIPTION:
XS GIS Cut Line= 3
      2749924.51      6850866.81      2749226.61      6851182.51
      2748624.21      6851316.93
#Sta/Elev= 30
  4249.7  457.83  4273.7  457.58  4291.4  453.16  4302.9  454.28  4319.1  452.66
  4339.0  451.97  4423.6  449.75  4482.0  448.39  4585.1  446.76  4665.4  447.67
  4734.7  447.06  4910.1  441.55  4976.8  442.91  5000.8  438.61  5001.3  438.11
  5010.0  438.61  5013.3  443.01  5089.3  442.99  5098.3  444.22  5139.3  443.42
  5221.2  446.09  5272.5  446.06  5307.8  448.69  5313.4  447.10  5323.7  447.31
  5415.9  453.25  5456.9  453.50  5491.8  452.22  5559.7  456.15  5632.9  457.41
#Mann=10,-1,0
  4249.7    0.05       0  4319.1   0.063       0  4339.0   0.035       0
  4423.6   0.063       0  4482.0    0.05       0  4910.1    0.16       0
  5000.8    0.07       0  5010.0    0.16       0  5089.3    0.05       0
  5559.7    0.16       0
Bank Sta=5000.8,5010
Exp/Cntr=0.3,0.1

Type RM Length L Ch R = 1,24339,406,406,406
BEGIN DESCRIPTION:
Chamblee Creek24338.52
END DESCRIPTION:
XS GIS Cut Line= 3
      2749638.44      6850426.96      2749171.97      6850890.25
      2748721.83      6851163.44
#Sta/Elev= 30
  4348.8  452.63  4368.3  451.83  4381.6  449.79  4402.9  451.47  4445.3  447.69
  4487.7  445.87  4584.8  445.22  4657.4  445.62  4721.1  443.77  4909.8  442.31
  4975.6  441.43  4982.7  440.16  4989.8  440.97  4991.5  435.95  4992.0  435.45
  5002.2  435.95  5003.2  440.33  5012.4  437.66  5018.2  441.76  5024.9  441.26
  5033.7  438.02  5039.5  438.64  5048.3  437.22  5055.0  441.86  5060.9  441.42
  5083.4  443.99  5155.8  444.78  5258.5  449.20  5352.5  453.39  5532.8  454.57
#Mann=7,-1,0
  4348.8    0.05       0  4368.3   0.063       0  4584.8    0.05       0
  4909.8    0.16       0  4991.5    0.07       0  5002.2    0.16       0
  5258.5    0.05       0
Bank Sta=4991.5,5002.2
Exp/Cntr=0.3,0.1

Type RM Length L Ch R = 1,23933,389,389,389
BEGIN DESCRIPTION:
Chamblee Creek23932.78
END DESCRIPTION:
XS GIS Cut Line= 3
      2749210.60      6850018.36      2749039.40      6850540.70
      2748680.56      6851064.85
#Sta/Elev= 30
  4463.2  457.35  4498.4  456.10  4525.0  452.60  4550.2  452.11  4556.8  450.56
  4562.1  450.90  4588.7  447.88  4613.3  447.62  4644.9  444.37  4676.5  444.08
  4684.2  442.19  4695.3  442.18  4802.7  441.86  4863.4  442.72  4918.5  442.78
  4944.2  441.81  4950.1  438.50  4960.6  435.13  4970.7  435.07  4971.2  434.57
  4981.4  435.07  4981.6  437.32  4992.2  441.65  5010.4  444.40  5073.8  448.31
  5152.5  449.64  5317.8  452.94  5397.2  451.96  5429.9  452.53  5648.1  454.23
#Mann=8,-1,0
  4463.2   0.063       0  4695.3    0.05       0  4863.4    0.16       0
  4970.7    0.07       0  4981.4    0.16       0  5152.5    0.05       0
  5317.8    0.16       0  5429.9    0.05       0
Bank Sta=4970.7,4981.4
Exp/Cntr=0.3,0.1

Type RM Length L Ch R = 1,23544,586,586,586
BEGIN DESCRIPTION:
Chamblee Creek23544.15
END DESCRIPTION:
XS GIS Cut Line= 3
      2749036.57      6849819.35      2748808.04      6850252.84
      2748457.05      6850831.47
#Sta/Elev= 30
  4517.3  454.55  4527.0  454.88  4549.1  453.09  4593.1  452.21  4603.4  451.07
  4611.4  450.61  4722.6  446.26  4831.9  441.53  4903.5  439.81  5000.3  441.79
  5004.2  439.00  5007.3  439.00  5015.5  434.24  5016.0  433.74  5026.3  434.24
  5028.6  436.54  5038.6  440.32  5043.2  442.26  5052.0  442.22  5132.3  440.46
  5224.3  440.71  5270.0  440.68  5356.1  442.47  5364.9  443.71  5429.0  445.94
  5496.4  449.54  5502.6  450.58  5508.5  449.84  5566.6  450.06  5684.1  454.04
#Mann=10,-1,0
  4517.3   0.063       0  4603.4    0.07       0  4611.4   0.063       0
  4722.6    0.07       0  4831.9    0.12       0  5015.5    0.07       0
  5026.3    0.12       0  5038.6    0.16       0  5052.0    0.12       0
  5224.3    0.05       0
Bank Sta=5015.5,5026.3
Exp/Cntr=0.3,0.1

Type RM Length L Ch R = 1,22958,465,465,465
BEGIN DESCRIPTION:
Chamblee Creek22958.26
END DESCRIPTION:
XS GIS Cut Line= 3
      2748777.95      6849581.88      2748403.14      6850050.86
      2748161.06      6850446.05
#Sta/Elev= 30
  4408.6  454.23  4438.2  454.43  4565.7  453.62  4608.9  451.89  4629.7  450.13
  4673.0  448.77  4743.4  444.23  4765.8  444.97  4772.2  442.91  4821.8  440.17
  4848.5  440.51  4857.1  440.02  4865.1  437.98  4871.5  439.69  4885.9  438.40
  4900.3  440.21  4921.1  439.00  4957.9  440.10  4970.7  439.10  4978.7  434.75
  4987.7  432.76  4988.2  432.26  4998.6  432.76  4999.5  433.89  5005.8  437.17
  5041.1  440.42  5145.5  447.10  5319.6  449.23  5457.0  452.97  5472.4  452.66
#Mann=6,-1,0
  4408.6   0.063       0  4438.2    0.07       0  4848.5    0.16       0
  4987.7    0.07       0  4998.6    0.16       0  5041.1    0.05       0
Bank Sta=4987.7,4998.6
Exp/Cntr=0.3,0.1

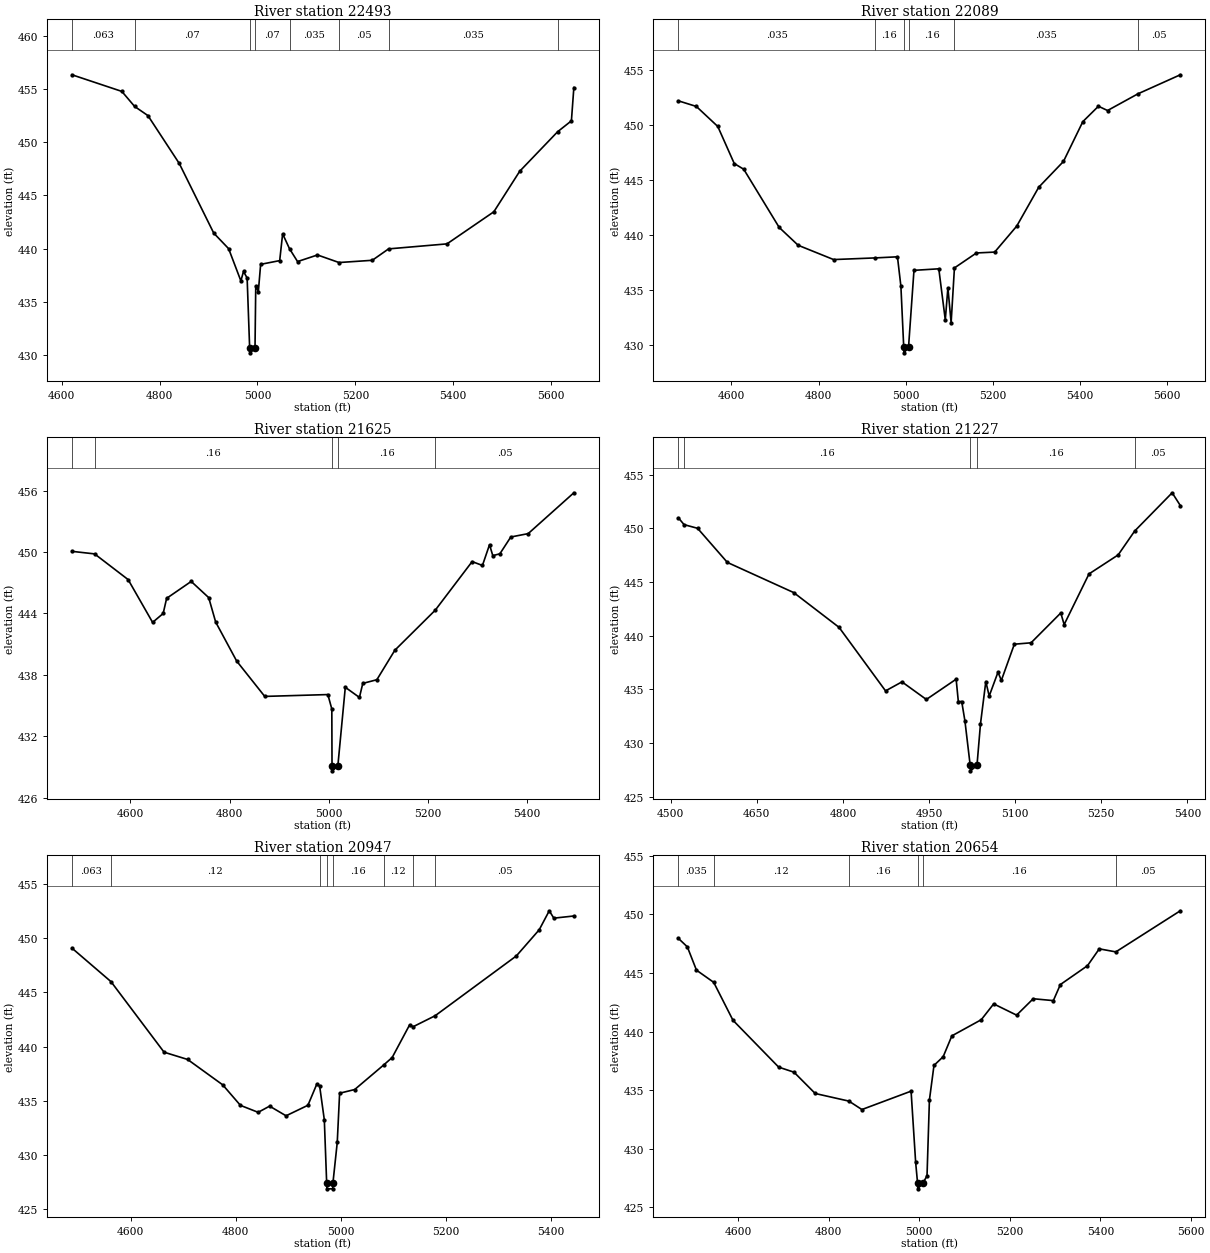
Type RM Length L Ch R = 1,22493,404,404,404
BEGIN DESCRIPTION:
Chamblee Creek22492.72
END DESCRIPTION:
XS GIS Cut Line= 3
      2748731.52      6849495.08      2748369.23      6849629.22
      2747741.23      6849746.03
#Sta/Elev= 30
  4621.1  456.32  4723.0  454.76  4749.1  453.35  4776.3  452.49  4840.3  448.00
  4910.7  441.47  4941.1  440.01  4966.1  436.99  4971.5  437.87  4978.9  437.26
  4984.0  430.74  4984.5  430.24  4995.0  430.74  4996.5  436.53  5001.8  435.99
  5006.5  438.54  5045.4  438.89  5051.4  441.40  5065.5  440.00  5081.9  438.80
  5122.6  439.42  5166.6  438.71  5234.5  438.92  5267.8  439.99  5387.1  440.46
  5482.8  443.47  5535.6  447.27  5613.1  450.98  5641.2  452.00  5646.2  455.12
#Mann=8,-1,0
  4621.1   0.063       0  4749.1    0.07       0  4984.0    0.07       0
  4995.0    0.07       0  5065.5   0.035       0  5166.6    0.05       0
  5267.8   0.035       0  5613.1    0.05       0
Bank Sta=4984,4995
Exp/Cntr=0.3,0.1

Type RM Length L Ch R = 1,22089,464,464,464
BEGIN DESCRIPTION:
Chamblee Creek22089.05
END DESCRIPTION:
XS GIS Cut Line= 3
      2748443.02      6848853.80      2748189.65      6849312.67
      2747674.29      6849671.76
#Sta/Elev= 30
  4478.2  452.19  4519.4  451.68  4568.6  449.86  4606.4  446.49  4628.2  445.97
  4709.6  440.68  4753.1  439.06  4834.5  437.76  4929.6  437.91  4981.1  438.01
  4989.0  435.33  4995.5  429.78  4996.0  429.28  5006.5  429.78  5019.0  436.78
  5076.0  436.92  5090.9  432.28  5096.9  435.19  5104.3  432.02  5111.9  437.00
  5162.4  438.36  5204.3  438.44  5254.9  440.80  5305.5  444.34  5362.2  446.68
  5406.7  450.30  5442.5  451.70  5463.4  451.31  5533.3  452.83  5630.5  454.56
#Mann=6,-1,0
  4478.2   0.035       0  4929.6    0.16       0  4995.5    0.07       0
  5006.5    0.16       0  5111.9   0.035       0  5533.3    0.05       0
Bank Sta=4995.5,5006.5
Exp/Cntr=0.3,0.1

Type RM Length L Ch R = 1,21625,398,398,398
BEGIN DESCRIPTION:
Chamblee Creek21624.75
END DESCRIPTION:
XS GIS Cut Line= 3
      2748300.41      6848645.16      2747923.74      6849010.13
      2747550.75      6849325.61
#Sta/Elev= 30
  4482.0  450.07  4527.7  449.82  4595.4  447.31  4644.8  443.13  4666.1  444.00
  4673.1  445.48  4722.7  447.13  4758.0  445.55  4772.1  443.16  4814.5  439.35
  4871.1  435.90  4998.5  436.08  5006.5  434.67  5006.9  429.13  5007.4  428.63
  5018.7  429.13  5033.7  436.79  5062.2  435.80  5069.0  437.17  5097.4  437.53
  5133.7  440.41  5215.2  444.32  5289.7  449.07  5310.5  448.69  5324.8  450.72
  5331.4  449.65  5345.7  449.83  5367.7  451.47  5402.8  451.80  5495.0  455.79
#Mann=5,-1,0
  4482.0   0.063       0  4527.7    0.16       0  5006.9    0.07       0
  5018.7    0.16       0  5215.2    0.05       0
Bank Sta=5006.9,5018.7
Exp/Cntr=0.3,0.1

Type RM Length L Ch R = 1,21227,280,280,280
BEGIN DESCRIPTION:
Chamblee Creek21227.14
END DESCRIPTION:
XS GIS Cut Line= 3
      2748131.96      6848449.89      2747715.94      6848710.04
      2747391.56      6848915.24
#Sta/Elev= 30
  4513.3  450.97  4523.2  450.34  4546.7  450.00  4598.6  446.82  4714.2  444.01
  4793.2  440.77  4874.2  434.85  4902.8  435.69  4945.3  434.05  4997.2  435.94
  5001.0  433.86  5006.9  433.86  5012.5  432.05  5021.7  427.90  5022.2  427.40
  5033.5  427.90  5039.6  431.77  5048.9  435.72  5054.8  434.37  5070.1  436.59
  5076.0  435.83  5098.6  439.20  5127.7  439.33  5179.5  442.11  5185.4  441.03
  5228.7  445.75  5279.5  447.52  5308.2  449.74  5373.6  453.31  5387.8  452.12
#Mann=5,-1,0
  4513.3   0.063       0  4523.2    0.16       0  5021.7    0.07       0
  5033.5    0.16       0  5308.2    0.05       0
Bank Sta=5021.7,5033.5
Exp/Cntr=0.3,0.1

Type RM Length L Ch R = 1,20947,293,293,293
BEGIN DESCRIPTION:
Chamblee Creek20946.72
END DESCRIPTION:
XS GIS Cut Line= 3
      2748117.53      6848317.06      2747625.05      6848458.47
      2747201.19      6848585.96
#Sta/Elev= 30
  4488.3  449.07  4562.6  445.98  4663.6  439.48  4708.4  438.81  4775.2  436.47
  4808.9  434.58  4842.6  433.94  4864.4  434.51  4895.7  433.62  4937.3  434.59
  4954.2  436.54  4959.6  436.36  4968.5  433.25  4973.0  427.39  4973.5  426.89
  4984.3  426.89  4984.8  427.39  4993.1  431.17  4997.6  435.70  5026.3  436.04
  5081.4  438.30  5097.6  438.99  5130.6  441.98  5137.6  441.83  5179.4  442.84
  5333.9  448.35  5377.4  450.76  5396.5  452.51  5405.2  451.83  5443.3  452.03
#Mann=8,-1,0
  4488.3   0.063       0  4562.6    0.12       0  4959.6    0.16       0
  4973.0    0.07       0  4984.8    0.16       0  5081.4    0.12       0
  5137.6    0.16       0  5179.4    0.05       0
Bank Sta=4973,4984.8
Exp/Cntr=0.3,0.1

Type RM Length L Ch R = 1,20654,567,567,567
BEGIN DESCRIPTION:
Chamblee Creek20653.94
END DESCRIPTION:
XS GIS Cut Line= 3
      2748125.56      6848260.10      2747589.71      6848187.46
      2747029.49      6848091.09
#Sta/Elev= 30
  4467.5  447.95  4487.2  447.23  4507.4  445.24  4545.5  444.20  4588.1  440.96
  4689.1  436.96  4722.9  436.53  4769.8  434.71  4844.3  434.06  4873.0  433.34
  4981.7  434.91  4991.8  428.82  4996.0  427.07  4996.5  426.57  5007.8  427.07
  5016.9  427.67  5022.2  434.15  5032.3  437.11  5052.6  437.85  5071.8  439.63
  5136.8  441.01  5164.2  442.36  5214.9  441.40  5251.6  442.80  5296.1  442.64
  5311.6  444.01  5371.5  445.62  5397.6  447.06  5434.2  446.80  5576.7  450.31
#Mann=6,-1,0
  4467.5   0.035       0  4545.5    0.12       0  4844.3    0.16       0
  4996.0    0.07       0  5007.8    0.16       0  5434.2    0.05       0
Bank Sta=4996,5007.8
Exp/Cntr=0.3,0.1

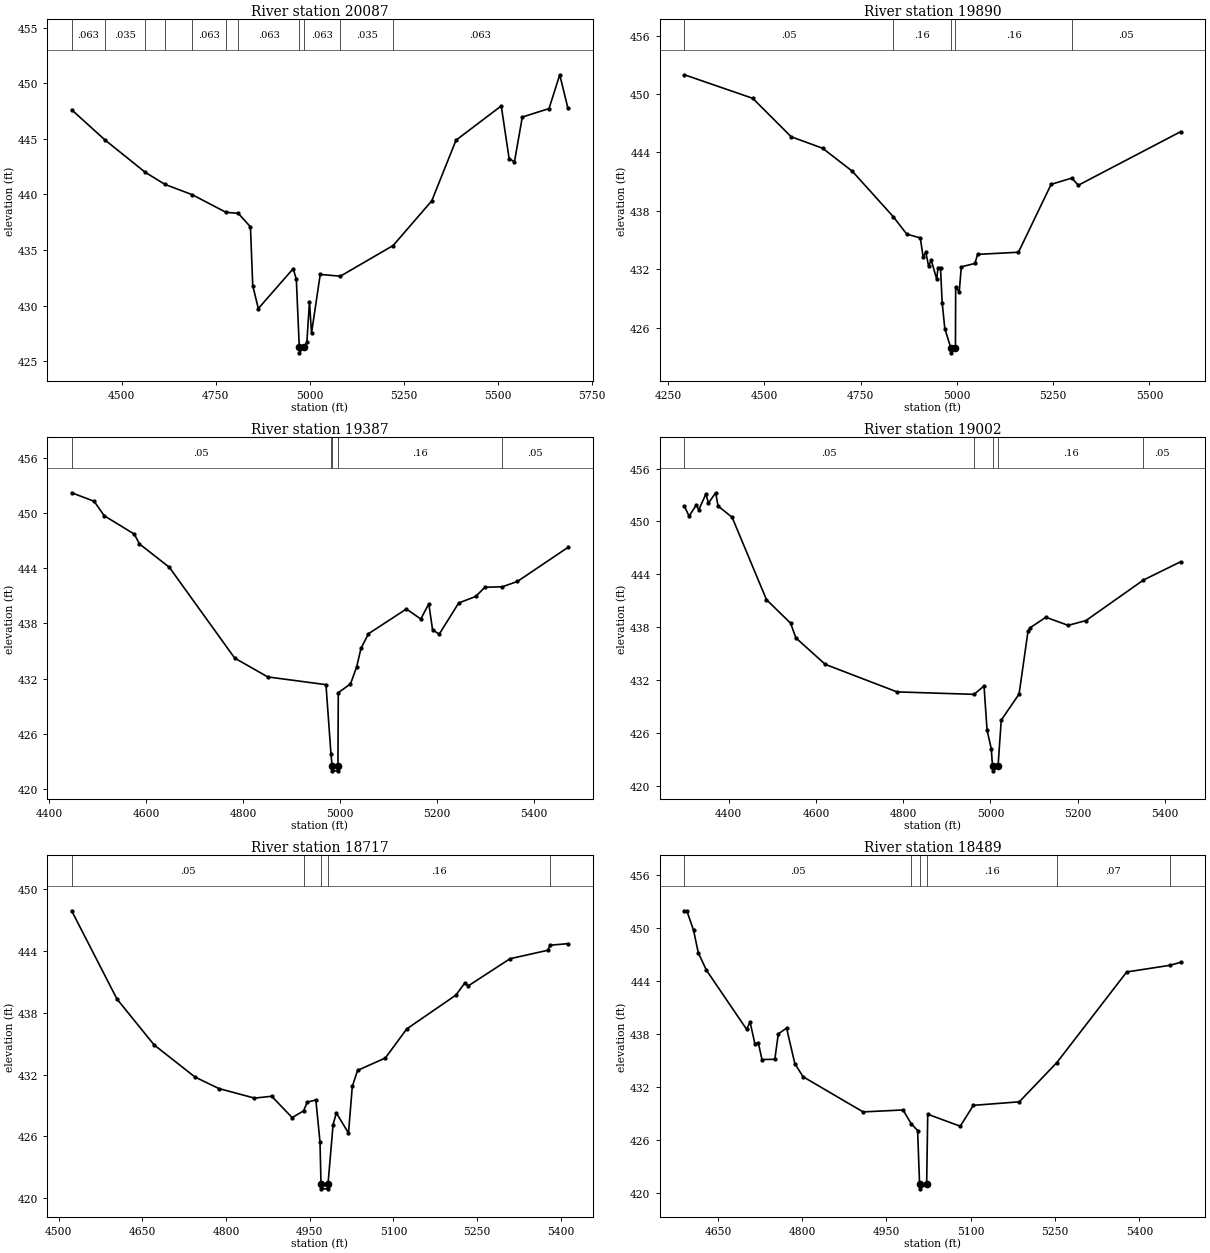
Type RM Length L Ch R = 1,20087,197,197,197
BEGIN DESCRIPTION:
Chamblee Creek20086.81
END DESCRIPTION:
XS GIS Cut Line= 5
      2748105.49      6848176.47      2747889.86      6847890.75
      2747749.28      6847689.94      2747723.48      6847663.35
      2747214.41      6847212.12
#Sta/Elev= 30
  4366.5  447.60  4455.9  444.87  4562.4  441.98  4615.2  440.89  4687.3  439.97
  4776.9  438.39  4809.9  438.29  4842.3  437.08  4848.4  431.80  4863.2  429.73
  4956.1  433.32  4964.4  432.36  4972.3  426.25  4972.8  425.75  4984.3  426.25
  4992.4  426.68  4999.4  430.36  5004.8  427.51  5028.0  432.80  5081.6  432.64
  5222.1  435.40  5324.9  439.42  5389.4  444.87  5509.8  447.95  5530.7  443.21
  5544.9  442.93  5565.8  446.95  5636.9  447.71  5665.4  450.75  5686.9  447.78
#Mann=11,-1,0
  4366.5   0.063       0  4455.9   0.035       0  4562.4   0.063       0
  4615.2   0.035       0  4687.3   0.063       0  4776.9   0.035       0
  4809.9   0.063       0  4972.3   0.063       0  4984.3   0.063       0
  5081.6   0.035       0  5222.1   0.063       0
Bank Sta=4972.3,4984.3
Exp/Cntr=0.3,0.1

Type RM Length L Ch R = 1,19890,503,503,503
BEGIN DESCRIPTION:
Chamblee Creek19889.99
END DESCRIPTION:
XS GIS Cut Line= 5
      2748207.82      6848043.84      2748010.31      6847737.78
      2747806.19      6847522.46      2747771.89      6847482.67
      2747360.89      6847080.67
#Sta/Elev= 30
  4292.5  451.98  4469.8  449.56  4569.6  445.61  4651.2  444.43  4728.3  442.07
  4834.4  437.41  4869.8  435.60  4905.0  435.21  4912.3  433.23  4919.2  433.75
  4926.5  432.32  4933.4  432.92  4947.5  430.98  4951.0  432.17  4957.4  432.17
  4961.7  428.57  4968.6  425.89  4984.2  423.90  4984.7  423.40  4996.2  423.90
  4996.8  430.21  5006.0  429.64  5011.4  432.24  5046.7  432.59  5053.8  433.52
  5159.8  433.74  5244.7  440.72  5298.1  441.36  5315.4  440.63  5580.9  446.13
#Mann=5,-1,0
  4292.5    0.05       0  4834.4    0.16       0  4984.2    0.07       0
  4996.2    0.16       0  5298.1    0.05       0
Bank Sta=4984.2,4996.2
Exp/Cntr=0.3,0.1

Type RM Length L Ch R = 1,19387,385,385,385
BEGIN DESCRIPTION:
Chamblee Creek19387.25
END DESCRIPTION:
XS GIS Cut Line= 3
      2748360.77      6847260.93      2747828.06      6847118.22
      2747389.49      6846943.73
#Sta/Elev= 30
  4446.1  452.19  4492.4  451.27  4513.2  449.70  4575.3  447.70  4585.9  446.64
  4647.7  444.09  4782.3  434.24  4850.6  432.19  4970.7  431.35  4981.0  423.85
  4983.4  422.49  4983.9  421.99  4994.9  421.99  4995.4  422.49  4996.1  430.48
  5021.3  431.43  5034.1  433.29  5042.9  435.29  5058.4  436.88  5136.6  439.57
  5166.3  438.48  5182.8  440.13  5190.6  437.32  5204.3  436.83  5244.5  440.22
  5279.6  440.93  5298.5  441.93  5334.4  441.98  5365.7  442.56  5469.6  446.25
#Mann=5,-1,0
  4446.1    0.05       0  4981.0    0.16       0  4983.4    0.07       0
  4995.4    0.16       0  5334.4    0.05       0
Bank Sta=4983.4,4995.4
Exp/Cntr=0.3,0.1

Type RM Length L Ch R = 1,19002,285,285,285
BEGIN DESCRIPTION:
Chamblee Creek19002.43
END DESCRIPTION:
XS GIS Cut Line= 3
      2748413.21      6846452.59      2747777.46      6846779.30
      2747364.05      6846868.94
#Sta/Elev= 30
  4298.3  451.72  4308.9  450.60  4325.5  451.87  4331.1  451.31  4347.6  453.13
  4353.3  452.07  4369.8  453.25  4375.4  451.75  4407.6  450.47  4486.4  441.13
  4541.7  438.47  4553.8  436.80  4621.2  433.80  4785.7  430.68  4962.3  430.40
  4985.3  431.35  4992.2  426.37  5001.9  424.23  5004.8  422.23  5005.3  421.73
  5017.4  422.23  5024.8  427.48  5065.7  430.44  5086.2  437.58  5091.6  437.97
  5127.1  439.14  5178.3  438.22  5219.2  438.77  5350.9  443.36  5436.1  445.43
#Mann=5,-1,0
  4298.3    0.05       0  4962.3    0.16       0  5004.8    0.07       0
  5017.4    0.16       0  5350.9    0.05       0
Bank Sta=5004.8,5017.4
Exp/Cntr=0.3,0.1

Type RM Length L Ch R = 1,18717,228,228,228
BEGIN DESCRIPTION:
Chamblee Creek18717.2
END DESCRIPTION:
XS GIS Cut Line= 3
      2748135.20      6846257.54      2747725.19      6846509.62
      2747364.39      6846700.11
#Sta/Elev= 30
  4523.2  447.89  4604.4  439.33  4671.0  434.88  4744.4  431.76  4787.0  430.65
  4850.9  429.72  4881.7  429.90  4918.4  427.83  4938.8  428.48  4945.5  429.33
  4960.9  429.54  4968.3  425.47  4970.1  421.42  4970.6  420.92  4982.2  420.92
  4982.7  421.42  4991.8  427.16  4997.6  428.28  5019.4  426.33  5026.2  430.85
  5035.7  432.41  5085.4  433.61  5123.8  436.43  5211.9  439.71  5228.2  440.91
  5233.9  440.60  5308.9  443.24  5376.7  444.06  5380.7  444.55  5412.5  444.70
#Mann=5,-1,0
  4523.2    0.05       0  4938.8    0.16       0  4970.1    0.07       0
  4982.7    0.16       0  5380.7    0.07       0
Bank Sta=4970.1,4982.7
Exp/Cntr=0.3,0.1

Type RM Length L Ch R = 1,18489,152,152,152
BEGIN DESCRIPTION:
Chamblee Creek18488.64
END DESCRIPTION:
XS GIS Cut Line= 4
      2748057.80      6846039.22      2747721.48      6846282.23
      2747568.77      6846371.64      2747281.26      6846416.69
#Sta/Elev= 30
  4590.5  451.91  4594.7  451.91  4606.6  449.73  4615.2  447.15  4629.7  445.19
  4701.1  438.52  4707.2  439.35  4715.8  436.90  4721.9  437.01  4728.4  435.11
  4751.3  435.13  4757.5  438.00  4772.2  438.66  4786.9  434.65  4801.6  433.16
  4908.4  429.19  4979.5  429.41  4994.1  427.84  5005.4  427.09  5008.9  421.00
  5009.4  420.50  5021.5  421.00  5023.4  428.93  5081.3  427.57  5104.5  429.93
  5186.3  430.33  5253.3  434.77  5377.5  445.00  5454.4  445.75  5473.4  446.09
#Mann=6,-1,0
  4590.5    0.05       0  4994.1    0.16       0  5008.9    0.07       0
  5021.5    0.16       0  5253.3    0.07       0  5454.4    0.05       0
Bank Sta=5008.9,5021.5
Exp/Cntr=0.3,0.1

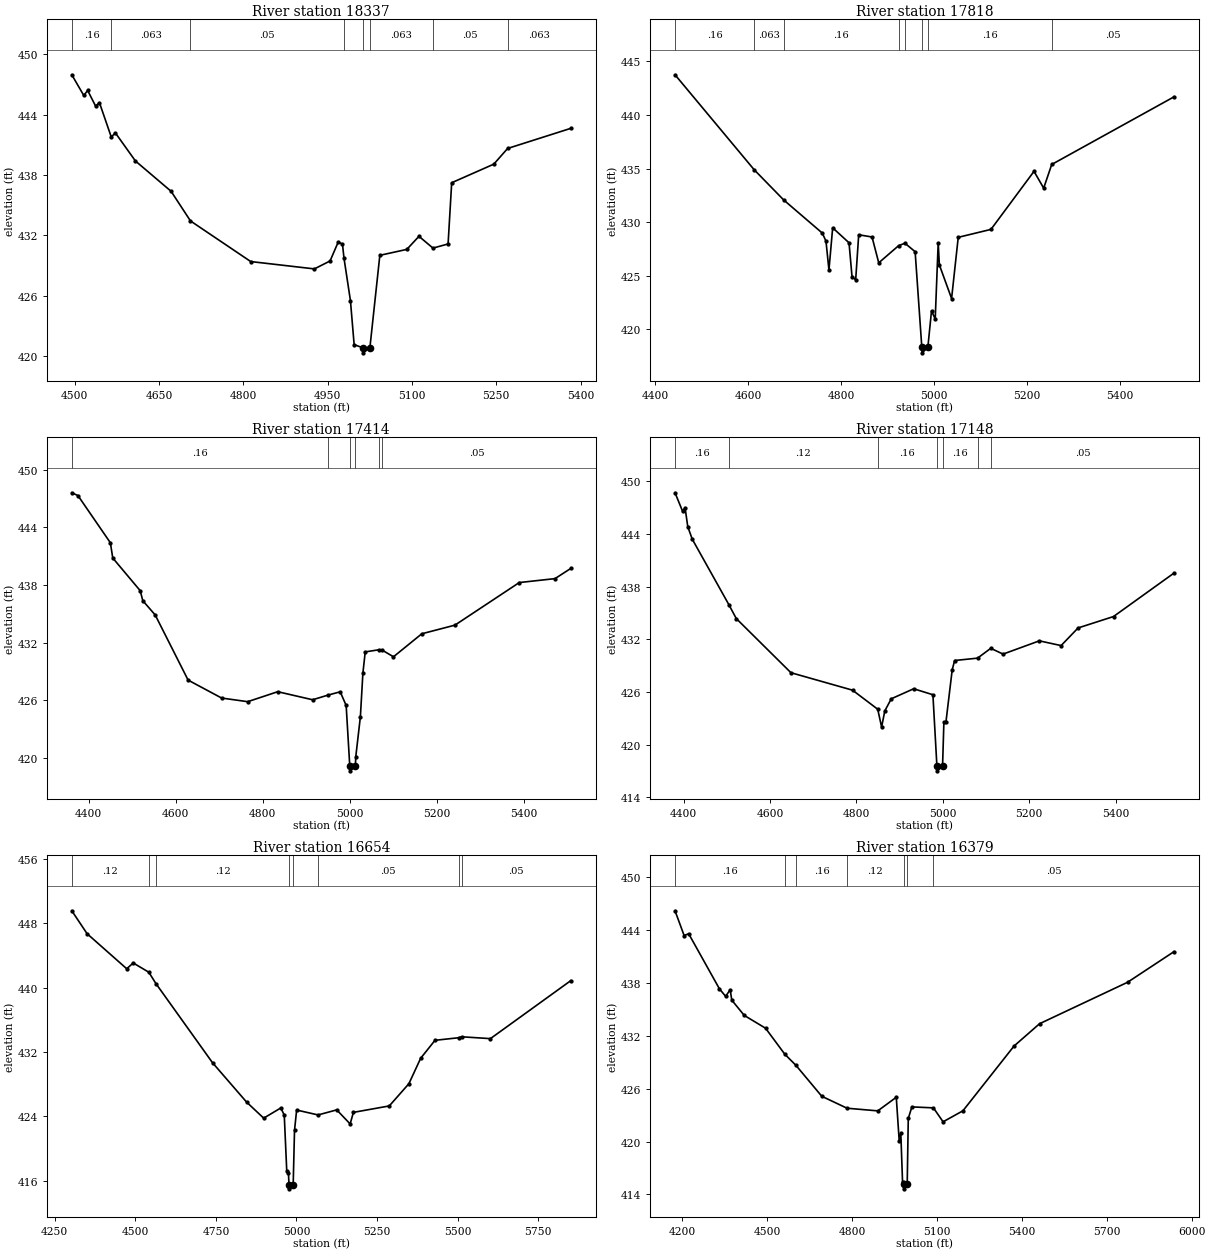
Type RM Length L Ch R = 1,18337,519,519,519
BEGIN DESCRIPTION:
Chamblee Creek18337.41
END DESCRIPTION:
XS GIS Cut Line= 5
      2747991.59      6845816.78      2747666.56      6846122.88
      2747624.99      6846171.67      2747510.02      6846218.70
      2747261.14      6846262.50
#Sta/Elev= 30
  4495.0  447.97  4516.3  445.91  4523.2  446.41  4537.3  444.86  4544.2  445.19
  4565.2  441.78  4572.5  442.19  4608.1  439.40  4671.6  436.38  4706.1  433.43
  4813.3  429.39  4926.5  428.66  4954.4  429.45  4968.7  431.31  4976.4  431.14
  4979.2  429.71  4990.6  425.51  4997.2  421.13  5012.6  420.81  5013.1  420.31
  5025.2  420.81  5042.9  430.01  5090.9  430.60  5112.5  431.90  5137.4  430.73
  5164.3  431.14  5170.7  437.23  5245.6  439.08  5270.2  440.64  5382.5  442.64
#Mann=8,-1,0
  4495.0    0.16       0  4565.2   0.063       0  4706.1    0.05       0
  4979.2   0.063       0  5012.6   0.063       0  5025.2   0.063       0
  5137.4    0.05       0  5270.2   0.063       0
Bank Sta=5012.6,5025.2
Exp/Cntr=0.3,0.1

Type RM Length L Ch R = 1,17818,404,404,404
BEGIN DESCRIPTION:
Chamblee Creek17818.03
END DESCRIPTION:
XS GIS Cut Line= 3
      2747826.70      6845285.40      2747467.91      6845728.78
      2747150.09      6846118.57
#Sta/Elev= 30
  4443.1  443.76  4613.3  434.90  4676.8  432.08  4759.8  428.99  4767.8  428.24
  4774.2  425.54  4782.2  429.48  4817.4  428.08  4823.8  424.93  4831.7  424.62
  4838.2  428.83  4866.9  428.62  4881.3  426.21  4924.0  427.81  4937.6  428.04
  4959.6  427.25  4974.0  418.31  4974.5  417.81  4986.9  418.31  4994.8  421.72
  5002.8  420.97  5009.2  428.08  5011.7  426.02  5038.0  422.88  5052.3  428.59
  5122.7  429.33  5215.3  434.75  5236.1  433.18  5253.4  435.39  5516.4  441.70
#Mann=8,-1,0
  4443.1    0.16       0  4613.3   0.063       0  4676.8    0.16       0
  4924.0    0.12       0  4937.6    0.16       0  4974.0    0.07       0
  4986.9    0.16       0  5253.4    0.05       0
Bank Sta=4974,4986.9
Exp/Cntr=0.3,0.1

Type RM Length L Ch R = 1,17414,266,266,266
BEGIN DESCRIPTION:
Chamblee Creek17413.79
END DESCRIPTION:
XS GIS Cut Line= 3
      2747419.12      6845008.07      2747149.41      6845596.43
      2746955.65      6846056.34
#Sta/Elev= 30
  4361.4  447.61  4375.5  447.32  4450.0  442.40  4455.5  440.81  4518.6  437.40
  4524.5  436.36  4553.0  434.87  4628.6  428.08  4705.6  426.21  4765.5  425.83
  4834.5  426.87  4914.7  426.03  4949.5  426.51  4978.0  426.86  4991.7  425.44
  5000.0  419.12  5000.5  418.62  5012.9  419.12  5013.8  420.09  5024.4  424.27
  5030.1  428.78  5035.5  431.02  5066.5  431.24  5074.7  431.20  5100.4  430.51
  5165.5  432.91  5241.6  433.81  5389.4  438.25  5471.5  438.66  5507.7  439.72
#Mann=6,-1,0
  4361.4    0.16       0  4949.5    0.12       0  5000.0    0.07       0
  5012.9    0.12       0  5066.5    0.16       0  5074.7    0.05       0
Bank Sta=5000,5012.9
Exp/Cntr=0.3,0.1

Type RM Length L Ch R = 1,17148,494,494,494
BEGIN DESCRIPTION:
Chamblee Creek17147.84
END DESCRIPTION:
XS GIS Cut Line= 3
      2747241.19      6844894.64      2746958.99      6845451.58
      2746722.95      6845926.28
#Sta/Elev= 30
  4380.3  448.71  4397.9  446.59  4403.5  447.02  4409.8  444.84  4420.2  443.42
  4504.9  435.96  4522.0  434.38  4648.5  428.21  4791.0  426.22  4849.3  424.05
  4858.3  422.02  4865.7  423.86  4880.7  425.24  4932.5  426.38  4977.0  425.70
  4986.3  417.53  4986.8  417.03  4999.3  417.53  5002.4  422.57  5007.1  422.57
  5021.7  428.56  5027.3  429.60  5080.3  429.87  5110.9  430.99  5139.3  430.33
  5223.3  431.84  5273.6  431.30  5312.9  433.31  5394.9  434.61  5534.8  439.56
#Mann=7,-1,0
  4380.3    0.16       0  4504.9    0.12       0  4849.3    0.16       0
  4986.3    0.07       0  4999.3    0.16       0  5080.3    0.07       0
  5110.9    0.05       0
Bank Sta=4986.3,4999.3
Exp/Cntr=0.3,0.1

Type RM Length L Ch R = 1,16654,275,275,275
BEGIN DESCRIPTION:
Chamblee Creek16653.76
END DESCRIPTION:
XS GIS Cut Line= 3
      2747026.65      6844420.54      2746790.48      6845079.87
      2746658.90      6845917.14
#Sta/Elev= 30
  4303.0  449.58  4350.4  446.73  4473.4  442.37  4493.5  443.09  4541.9  441.94
  4563.9  440.53  4739.6  430.68  4845.2  425.79  4898.3  423.79  4951.4  425.06
  4962.1  424.17  4969.8  417.25  4975.1  416.93  4976.8  415.50  4977.3  415.00
  4989.8  415.50  4993.9  422.26  5000.5  424.80  5067.0  424.19  5124.9  424.82
  5166.5  423.07  5176.6  424.51  5287.9  425.31  5348.7  428.07  5385.3  431.24
  5429.7  433.47  5502.7  433.79  5512.4  433.91  5601.7  433.68  5850.9  440.89
#Mann=8,-1,0
  4303.0    0.12       0  4541.9    0.16       0  4563.9    0.12       0
  4976.8    0.07       0  4989.8    0.12       0  5067.0    0.05       0
  5502.7    0.07       0  5512.4    0.05       0
Bank Sta=4976.8,4989.8
Exp/Cntr=0.3,0.1

Type RM Length L Ch R = 1,16379,670,670,670
BEGIN DESCRIPTION:
Chamblee Creek16379.46
END DESCRIPTION:
XS GIS Cut Line= 3
      2746935.87      6844286.72      2746536.53      6845011.43
      2746605.19      6845944.76
#Sta/Elev= 30
  4174.3  446.13  4206.4  443.33  4222.5  443.53  4331.4  437.28  4353.2  436.44
  4369.2  437.19  4374.9  436.01  4419.0  434.28  4494.2  432.83  4562.4  429.88
  4601.8  428.62  4693.0  425.12  4782.3  423.77  4890.8  423.47  4956.2  425.01
  4966.5  420.09  4972.2  420.94  4978.4  415.39  4981.8  415.14  4982.3  414.64
  4994.8  415.14  4998.6  422.61  5011.3  423.92  5087.5  423.81  5121.6  422.23
  5191.8  423.48  5372.3  430.81  5462.6  433.34  5773.4  438.03  5937.6  441.50
#Mann=7,-1,0
  4174.3    0.16       0  4562.4    0.12       0  4601.8    0.16       0
  4782.3    0.12       0  4981.8    0.07       0  4994.8    0.12       0
  5087.5    0.05       0
Bank Sta=4981.8,4994.8
Exp/Cntr=0.3,0.1