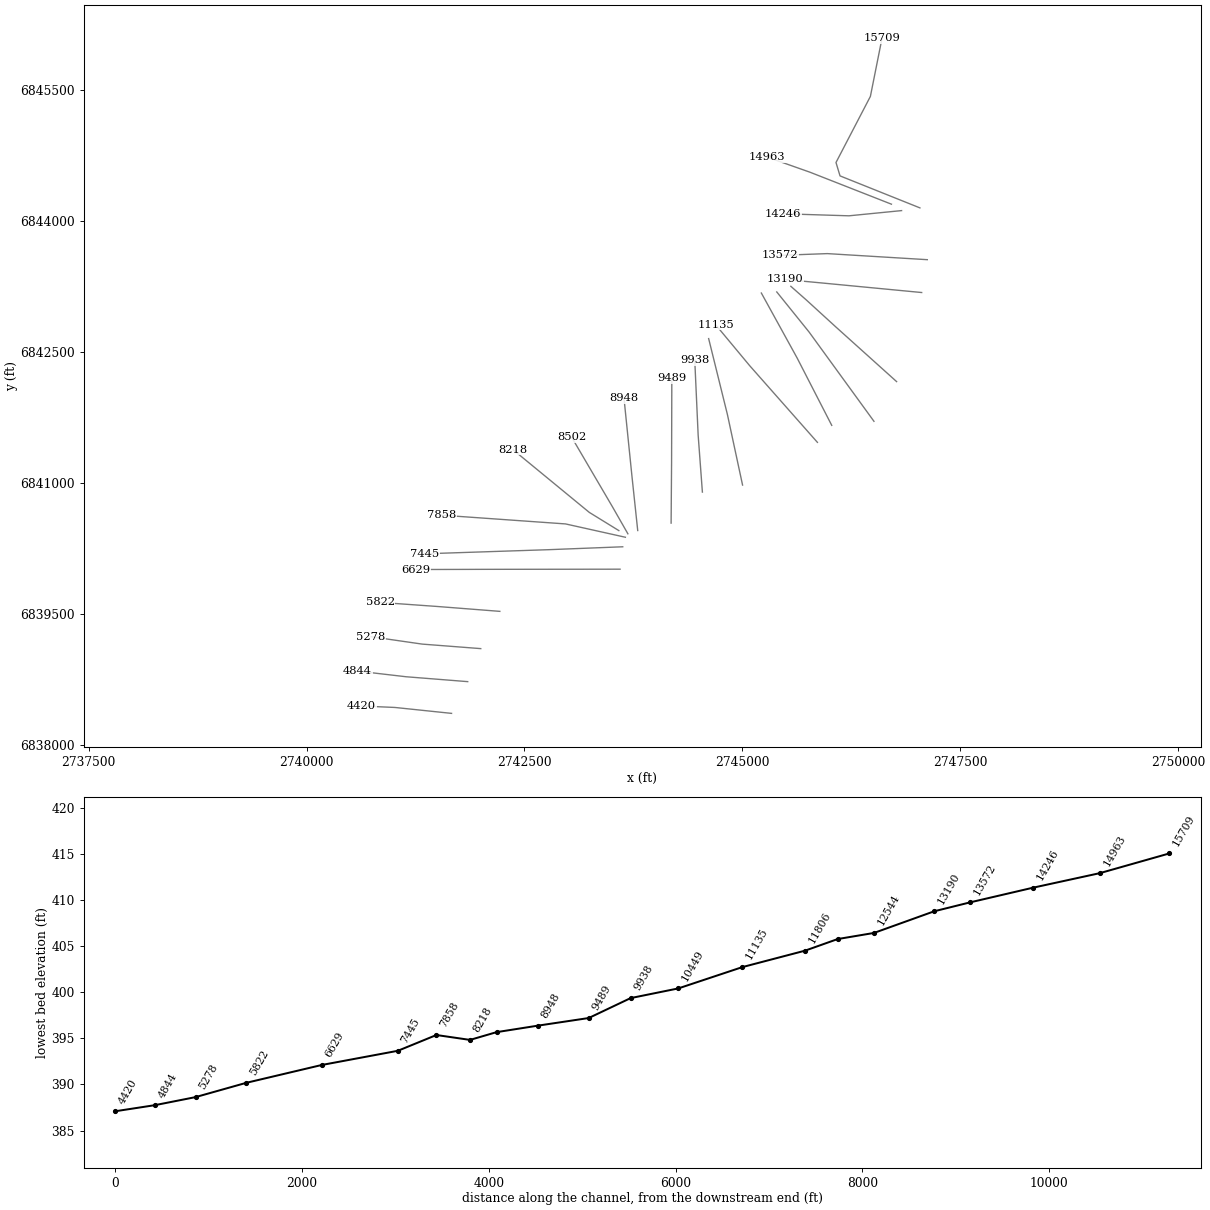
HEC-RAS study Chamblee Creek.prj: Chamblee Creek Base Level Engineering

--- Chamblee Creek.g01 (geometry) --- (continued)

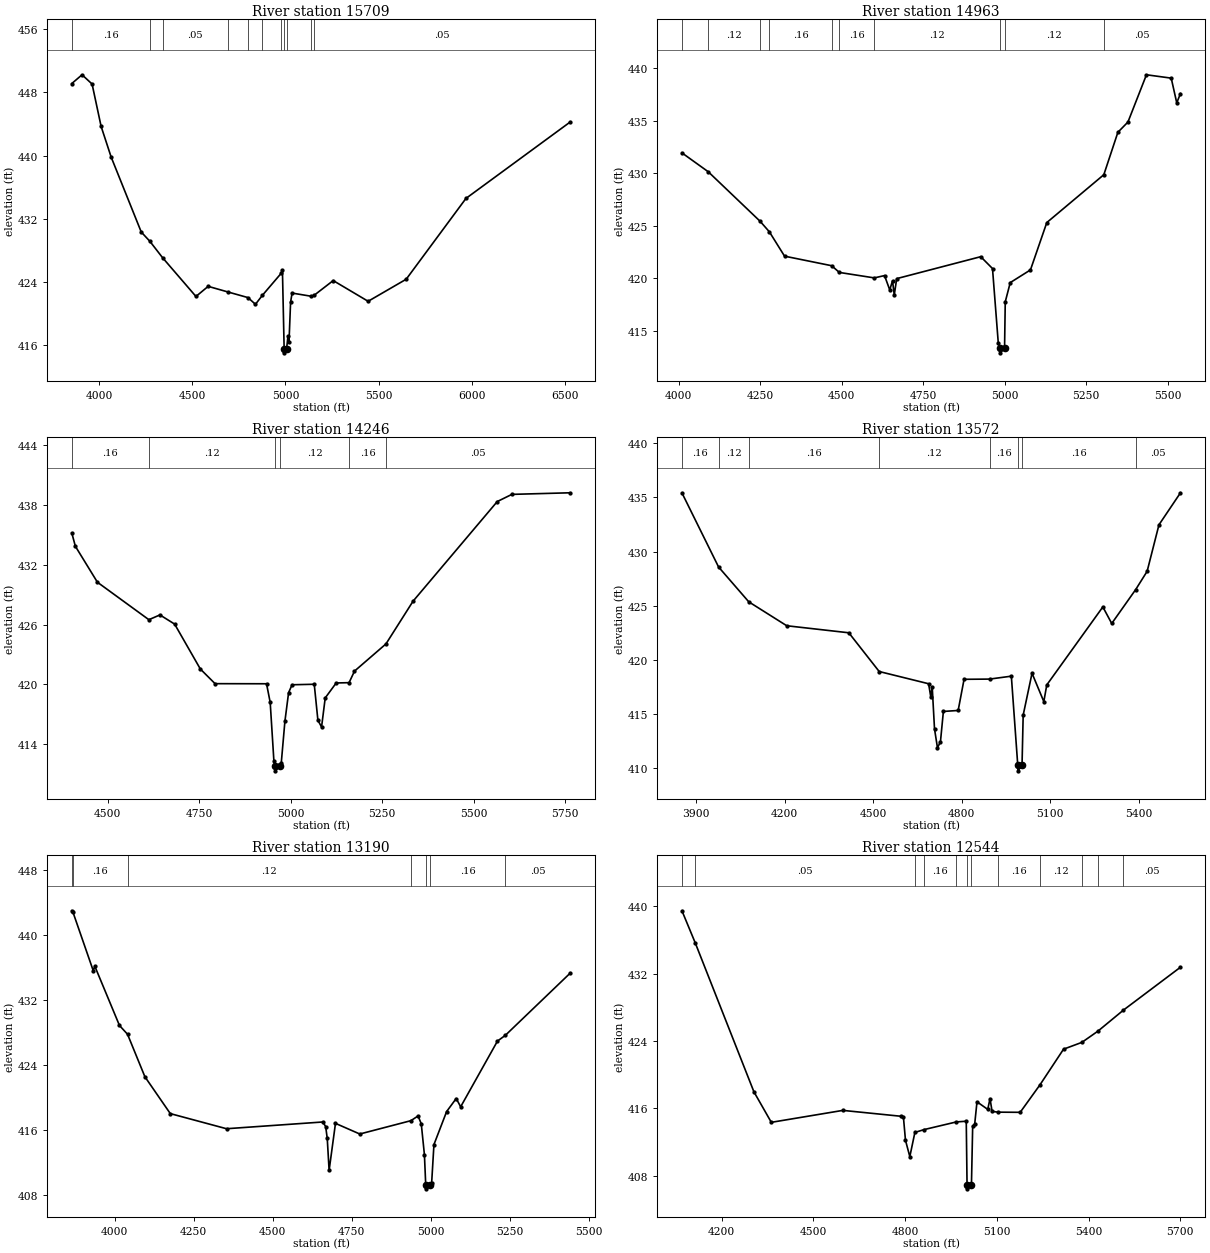
Type RM Length L Ch R = 1,15709,746,746,746
BEGIN DESCRIPTION:
Chamblee Creek15708.954
END DESCRIPTION:
XS GIS Cut Line= 5
      2747036.11      6844147.16      2746119.57      6844513.06
      2746073.35      6844666.25      2746467.92      6845421.95
      2746601.01      6846086.04
#Sta/Elev= 30
  3853.1  449.10  3908.2  450.21  3962.1  449.04  4010.6  443.68  4064.5  439.80
  4226.1  430.32  4272.6  429.14  4340.3  427.08  4519.8  422.17  4585.4  423.45
  4691.3  422.74  4798.9  422.03  4839.2  421.18  4877.0  422.33  4978.5  425.13
  4984.1  425.48  4993.3  415.54  4993.8  415.04  5006.4  415.54  5013.8  417.14
  5019.4  416.43  5027.9  421.45  5035.9  422.60  5137.9  422.20  5153.8  422.31
  5256.7  424.18  5444.2  421.56  5648.6  424.35  5969.4  434.57  6529.8  444.25
#Mann=11,-1,0
  3853.1    0.16       0  4272.6    0.12       0  4340.3    0.05       0
  4691.3    0.16       0  4798.9    0.12       0  4877.0    0.16       0
  4978.5    0.05       0  4993.3    0.05       0  5006.4    0.05       0
  5137.9    0.12       0  5153.8    0.05       0
Bank Sta=4993.3,5006.4
Exp/Cntr=0.3,0.1

Type RM Length L Ch R = 1,14963,717,717,717
BEGIN DESCRIPTION:
Chamblee Creek14963
END DESCRIPTION:
XS GIS Cut Line= 3
      2746709.36      6844189.53      2745775.20      6844555.02
      2745279.21      6844729.50
#Sta/Elev= 30
  4010.3  431.95  4091.0  430.15  4249.8  425.44  4278.4  424.43  4325.0  422.11
  4469.4  421.20  4493.0  420.56  4600.2  420.04  4631.6  420.26  4647.5  418.90
  4656.1  419.76  4661.4  418.41  4668.9  419.97  4926.6  422.06  4962.7  420.93
  4980.3  413.88  4985.4  413.40  4985.9  412.90  4999.7  413.40  5001.8  417.76
  5017.1  419.59  5079.1  420.80  5129.2  425.31  5304.1  429.87  5347.2  433.91
  5378.1  434.89  5434.8  439.39  5510.8  439.07  5527.7  436.72  5539.2  437.60
#Mann=10,-1,0
  4010.3    0.16       0  4091.0    0.12       0  4249.8    0.05       0
  4278.4    0.16       0  4469.4    0.05       0  4493.0    0.16       0
  4600.2    0.12       0  4985.4    0.07       0  4999.7    0.12       0
  5304.1    0.05       0
Bank Sta=4985.4,4999.7
Exp/Cntr=0.3,0.1

Type RM Length L Ch R = 1,14246,674,674,674
BEGIN DESCRIPTION:
Chamblee Creek14245.9
END DESCRIPTION:
XS GIS Cut Line= 3
      2746825.72      6844116.11      2746221.97      6844056.59
      2745466.41      6844080.02
#Sta/Elev= 30
  4401.7  435.20  4411.5  433.86  4471.8  430.25  4612.4  426.49  4642.6  426.97
  4682.8  426.05  4753.1  421.54  4793.3  420.07  4934.0  420.06  4944.0  418.19
  4954.1  412.31  4957.0  411.82  4957.5  411.32  4971.3  411.82  4974.2  412.08
  4984.2  416.29  4994.3  419.17  5003.8  419.96  5064.4  420.01  5074.4  416.39
  5084.4  415.72  5094.4  418.64  5124.4  420.14  5159.6  420.17  5174.4  421.33
  5260.4  424.06  5334.5  428.35  5564.6  438.35  5604.6  439.07  5764.3  439.23
#Mann=6,-1,0
  4401.7    0.16       0  4612.4    0.12       0  4957.0    0.07       0
  4971.3    0.12       0  5159.6    0.16       0  5260.4    0.05       0
Bank Sta=4957,4971.3
Exp/Cntr=0.3,0.1

Type RM Length L Ch R = 1,13572,382,382,382
BEGIN DESCRIPTION:
Chamblee Creek13571.53
END DESCRIPTION:
XS GIS Cut Line= 3
      2747120.66      6843554.93      2745973.16      6843624.36
      2745433.02      6843604.48
#Sta/Elev= 30
  3852.2  435.42  3976.4  428.57  4078.8  425.35  4207.5  423.14  4417.9  422.49
  4520.9  418.91  4688.4  417.78  4695.6  416.59  4700.6  417.51  4708.4  413.61
  4718.4  411.87  4728.5  412.40  4738.5  415.22  4788.6  415.31  4808.6  418.19
  4895.1  418.21  4968.9  418.48  4990.7  410.23  4991.2  409.73  5005.1  410.23
  5009.0  414.88  5039.0  418.75  5079.0  416.13  5089.0  417.67  5279.1  424.88
  5309.2  423.35  5390.3  426.48  5429.2  428.17  5469.3  432.47  5542.3  435.43
#Mann=8,-1,0
  3852.2    0.16       0  3976.4    0.12       0  4078.8    0.16       0
  4520.9    0.12       0  4895.1    0.16       0  4990.7    0.07       0
  5005.1    0.16       0  5390.3    0.05       0
Bank Sta=4990.7,5005.1
Exp/Cntr=0.3,0.1

Type RM Length L Ch R = 1,13190,646,646,646
BEGIN DESCRIPTION:
Chamblee Creek13190.1
END DESCRIPTION:
XS GIS Cut Line= 3
      2747056.16      6843179.32      2745925.43      6843287.25
      2745486.65      6843328.68
#Sta/Elev= 30
  3864.7  443.00  3868.4  442.83  3932.6  435.62  3937.6  436.17  4015.5  428.88
  4041.0  427.80  4095.9  422.57  4176.3  418.03  4354.0  416.17  4658.5  417.00
  4667.6  416.44  4672.6  414.97  4678.5  411.04  4698.6  416.83  4775.5  415.52
  4937.0  417.16  4959.8  417.74  4969.9  416.78  4979.9  412.97  4984.0  409.27
  4984.5  408.77  4998.4  409.27  5002.8  409.53  5010.0  414.22  5050.2  418.29
  5080.4  419.89  5094.5  418.87  5210.9  426.96  5235.9  427.67  5441.3  435.34
#Mann=7,-1,0
  3864.7    0.12       0  3868.4    0.16       0  4041.0    0.12       0
  4937.0    0.16       0  4984.0    0.07       0  4998.4    0.16       0
  5235.9    0.05       0
Bank Sta=4984,4998.4
Exp/Cntr=0.3,0.1

Type RM Length L Ch R = 1,12544,388,388,388
BEGIN DESCRIPTION:
Chamblee Creek12544.27
END DESCRIPTION:
XS GIS Cut Line= 4
      2746768.47      6842160.77      2746068.88      6842788.18
      2745735.47      6843091.91      2745555.40      6843250.37
#Sta/Elev= 30
  4070.2  439.49  4113.5  435.69  4305.6  417.96  4362.5  414.33  4596.5  415.75
  4787.1  415.05  4794.6  414.95  4801.3  412.20  4815.5  410.25  4832.1  413.13
  4862.6  413.47  4968.0  414.38  5000.1  414.46  5002.7  406.92  5003.2  406.42
  5017.1  406.92  5021.1  413.85  5027.8  414.15  5035.2  416.77  5070.4  415.87
  5077.8  417.15  5084.6  415.63  5104.6  415.54  5176.5  415.52  5241.4  418.80
  5318.3  423.03  5378.3  423.84  5430.6  425.17  5514.3  427.68  5700.8  432.78
#Mann=12,-1,0
  4070.2    0.16       0  4113.5    0.05       0  4832.1    0.12       0
  4862.6    0.16       0  4968.0    0.12       0  5002.7    0.07       0
  5017.1    0.12       0  5104.6    0.16       0  5241.4    0.12       0
  5378.3    0.05       0  5430.6    0.12       0  5514.3    0.05       0
Bank Sta=5002.7,5017.1
Exp/Cntr=0.3,0.1

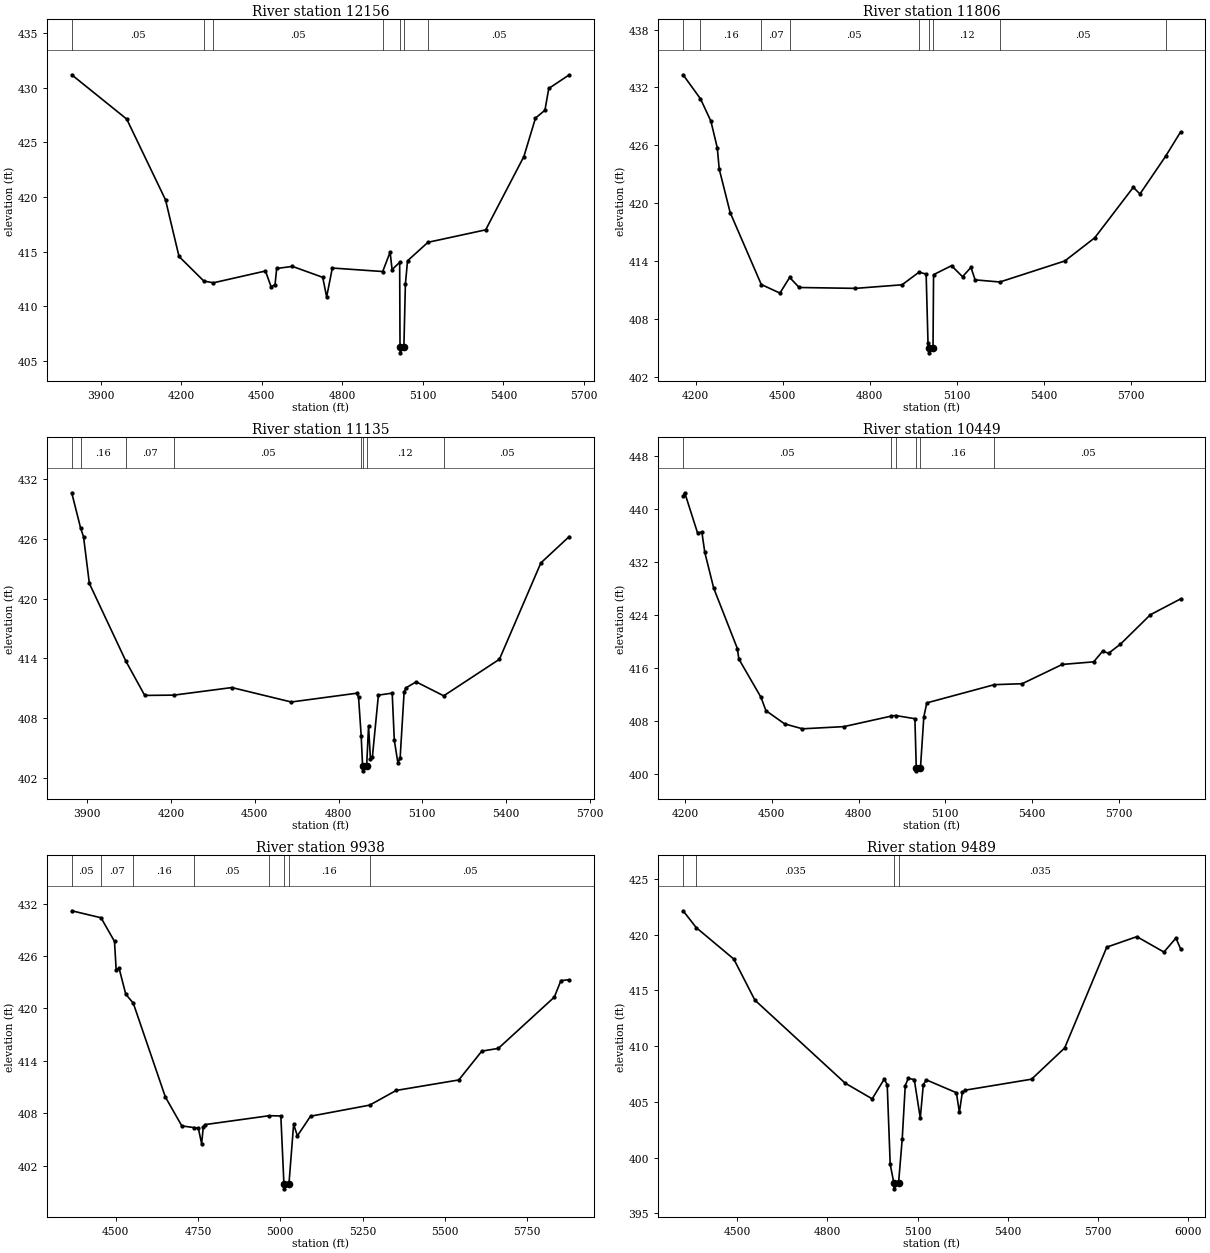
Type RM Length L Ch R = 1,12156,350,350,350
BEGIN DESCRIPTION:
Chamblee Creek12156.39
END DESCRIPTION:
XS GIS Cut Line= 3
      2746508.87      6841706.55      2745764.55      6842727.75
      2745394.00      6843186.01
#Sta/Elev= 30
  3791.8  431.17  3996.7  427.12  4141.2  419.74  4191.4  414.57  4283.9  412.32
  4319.6  412.16  4513.5  413.24  4534.4  411.80  4549.1  411.98  4555.3  413.47
  4614.0  413.66  4726.8  412.66  4741.4  410.87  4762.5  413.51  4950.2  413.19
  4977.8  414.96  4985.2  413.37  5013.4  414.03  5014.7  406.26  5015.2  405.76
  5029.1  406.26  5034.7  412.03  5042.7  414.17  5118.7  415.86  5333.8  417.00
  5476.1  423.70  5519.3  427.21  5554.5  427.93  5568.8  429.92  5644.8  431.16
#Mann=7,-1,0
  3791.8    0.05       0  4283.9    0.16       0  4319.6    0.05       0
  4950.2    0.16       0  5014.7    0.07       0  5029.1    0.16       0
  5118.7    0.05       0
Bank Sta=5014.7,5029.1
Exp/Cntr=0.3,0.1

Type RM Length L Ch R = 1,11806,671,671,671
BEGIN DESCRIPTION:
Chamblee Creek11806.34
END DESCRIPTION:
XS GIS Cut Line= 3
      2746024.58      6841660.30      2745627.85      6842430.06
      2745217.07      6843173.55
#Sta/Elev= 30
  4156.2  433.31  4216.1  430.82  4252.0  428.51  4274.1  425.74  4280.7  423.55
  4318.5  419.03  4425.8  411.58  4490.1  410.69  4523.6  412.31  4556.6  411.27
  4750.5  411.18  4911.3  411.55  4969.8  412.86  4994.3  412.66  5000.7  405.56
  5003.6  405.00  5004.1  404.50  5018.0  405.00  5019.9  412.60  5081.9  413.53
  5119.7  412.39  5148.9  413.35  5163.2  412.06  5248.6  411.84  5472.6  414.02
  5575.7  416.42  5708.7  421.65  5731.6  420.96  5820.0  424.86  5871.6  427.38
#Mann=9,-1,0
  4156.2    0.05       0  4216.1    0.16       0  4425.8    0.07       0
  4523.6    0.05       0  4969.8    0.12       0  5003.6    0.07       0
  5018.0    0.12       0  5248.6    0.05       0  5820.0    0.07       0
Bank Sta=5003.6,5018
Exp/Cntr=0.3,0.1

Type RM Length L Ch R = 1,11135,686,686,686
BEGIN DESCRIPTION:
Chamblee Creek11135.33
END DESCRIPTION:
XS GIS Cut Line= 3
      2745860.30      6841465.85      2745082.72      6842343.39
      2744693.26      6842810.31
#Sta/Elev= 30
  3845.0  430.63  3876.7  427.10  3887.2  426.22  3908.1  421.53  4039.2  413.71
  4106.3  410.29  4211.0  410.32  4418.3  411.08  4630.8  409.63  4865.0  410.51
  4871.6  410.12  4881.0  406.26  4886.1  403.22  4886.6  402.72  4900.7  403.22
  4907.4  407.23  4914.3  403.86  4921.0  404.06  4942.7  410.32  4992.1  410.52
  4999.6  405.80  5012.5  403.51  5020.5  404.02  5034.8  410.65  5041.3  411.05
  5077.8  411.65  5176.5  410.25  5375.9  413.92  5524.2  423.59  5625.5  426.23
#Mann=8,-1,0
  3845.0    0.05       0  3876.7    0.16       0  4039.2    0.07       0
  4211.0    0.05       0  4881.0    0.12       0  4886.1    0.07       0
  4900.7    0.12       0  5176.5    0.05       0
Bank Sta=4886.1,4900.7
Exp/Cntr=0.3,0.1

Type RM Length L Ch R = 1,10449,511,511,511
BEGIN DESCRIPTION:
Chamblee Creek10448.56
END DESCRIPTION:
XS GIS Cut Line= 3
      2745001.59      6840977.66      2744828.04      6841783.12
      2744612.58      6842652.47
#Sta/Elev= 30
  4193.5  441.99  4199.2  442.48  4243.4  436.41  4258.3  436.54  4268.5  433.46
  4299.2  428.06  4381.1  418.91  4386.2  417.33  4462.9  411.52  4479.7  409.52
  4544.7  407.51  4606.1  406.77  4749.3  407.10  4913.8  408.70  4927.8  408.78
  4994.8  408.30  4999.5  400.91  5000.0  400.41  5014.1  400.91  5025.6  408.55
  5035.9  410.69  5269.7  413.45  5365.5  413.59  5504.3  416.51  5612.8  416.90
  5643.7  418.51  5664.3  418.20  5705.5  419.58  5808.6  424.02  5913.1  426.42
#Mann=6,-1,0
  4193.5    0.05       0  4913.8    0.12       0  4927.8    0.16       0
  4999.5    0.07       0  5014.1    0.16       0  5269.7    0.05       0
Bank Sta=4999.5,5014.1
Exp/Cntr=0.3,0.1

Type RM Length L Ch R = 1,9938,449,449,449
BEGIN DESCRIPTION:
Chamblee Creek9937.91
END DESCRIPTION:
XS GIS Cut Line= 3
      2744540.75      6840897.39      2744492.07      6841549.94
      2744453.21      6842406.10
#Sta/Elev= 30
  4366.4  431.18  4455.4  430.38  4496.4  427.67  4501.4  424.43  4510.4  424.59
  4530.5  421.64  4553.4  420.61  4650.8  409.88  4700.9  406.56  4738.1  406.37
  4751.1  406.29  4761.1  404.52  4766.2  406.49  4771.2  406.71  4966.8  407.73
  5001.8  407.70  5011.2  399.86  5011.7  399.36  5026.3  399.86  5040.6  406.76
  5051.9  405.42  5091.9  407.67  5271.8  408.94  5352.2  410.62  5542.4  411.82
  5612.4  415.12  5662.5  415.43  5832.7  421.30  5852.7  423.19  5877.8  423.29
#Mann=8,-1,0
  4366.4    0.05       0  4455.4    0.07       0  4553.4    0.16       0
  4738.1    0.05       0  4966.8    0.16       0  5011.2    0.07       0
  5026.3    0.16       0  5271.8    0.05       0
Bank Sta=5011.2,5026.3
Exp/Cntr=0.3,0.1

Type RM Length L Ch R = 1,9489,541,541,541
BEGIN DESCRIPTION:
Chamblee Creek9488.77
END DESCRIPTION:
XS GIS Cut Line= 3
      2744181.97      6840542.40      2744187.32      6841239.58
      2744190.13      6842196.28
#Sta/Elev= 30
  4320.4  422.13  4364.1  420.62  4489.0  417.80  4559.0  414.12  4859.0  406.68
  4949.0  405.27  4989.0  407.03  4999.0  406.55  5009.0  399.39  5021.3  397.70
  5021.8  397.20  5036.7  397.70  5049.0  401.70  5059.0  406.46  5069.0  407.10
  5089.0  407.00  5109.0  403.54  5119.0  406.53  5129.0  406.97  5229.0  405.82
  5239.0  404.07  5249.0  405.88  5259.0  406.05  5479.0  407.03  5589.0  409.83
  5729.0  418.87  5829.0  419.81  5919.0  418.43  5959.0  419.68  5974.3  418.73
#Mann=4,-1,0
  4320.4   0.063       0  4364.1   0.035       0  5021.3   0.035       0
  5036.7   0.035       0
Bank Sta=5021.3,5036.7
Exp/Cntr=0.3,0.1

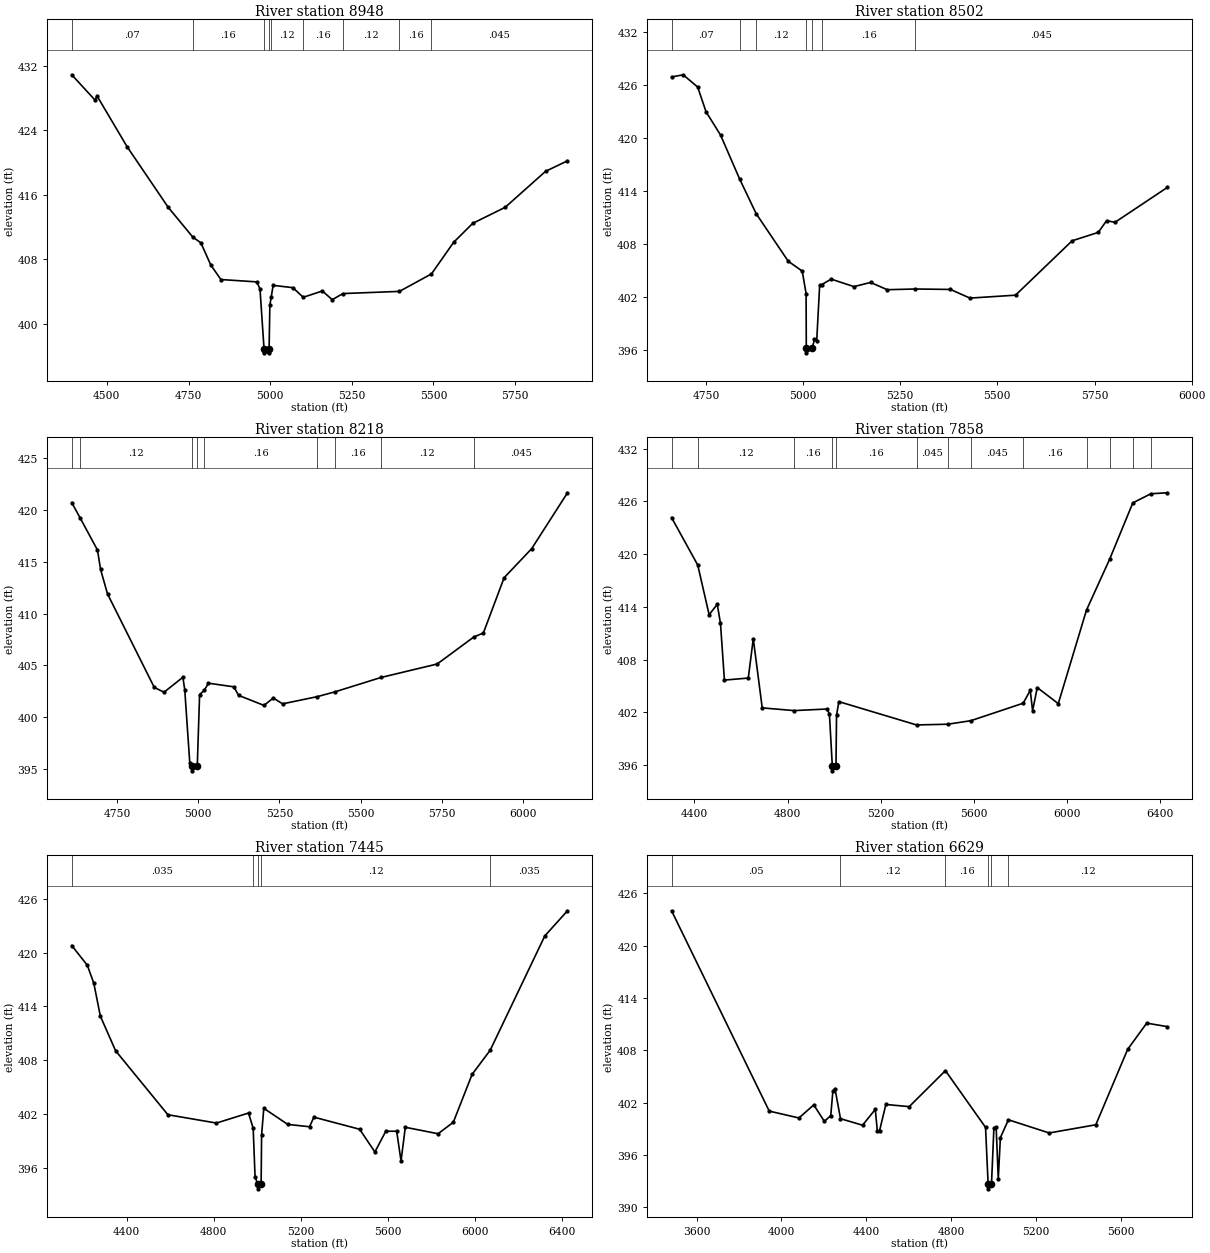
Type RM Length L Ch R = 1,8948,446,446,446
BEGIN DESCRIPTION:
Chamblee Creek8948.34
END DESCRIPTION:
XS GIS Cut Line= 3
      2743798.97      6840457.81      2743732.68      6841079.70
      2743641.78      6841967.74
#Sta/Elev= 30
  4392.5  430.86  4464.4  427.69  4469.4  428.27  4561.8  421.95  4687.4  414.45
  4763.0  410.74  4787.9  410.02  4818.1  407.28  4849.2  405.47  4958.9  405.18
  4968.9  404.32  4981.3  396.88  4981.8  396.38  4996.3  396.38  4996.8  396.88
  4999.1  402.27  5003.2  403.28  5009.2  404.75  5069.5  404.46  5101.4  403.27
  5160.0  404.05  5190.1  402.97  5222.9  403.73  5395.9  404.00  5494.1  406.17
  5562.0  410.09  5620.5  412.44  5719.9  414.43  5843.5  418.89  5910.6  420.19
#Mann=9,-1,0
  4392.5    0.07       0  4763.0    0.16       0  4981.3    0.07       0
  4996.8    0.16       0  5003.2    0.12       0  5101.4    0.16       0
  5222.9    0.12       0  5395.9    0.16       0  5494.1   0.045       0
Bank Sta=4981.3,4996.8
Exp/Cntr=0.3,0.1

Type RM Length L Ch R = 1,8502,284,284,284
BEGIN DESCRIPTION:
Chamblee Creek8502.12
END DESCRIPTION:
XS GIS Cut Line= 3
      2743686.00      6840420.51      2743509.71      6840728.00
      2743042.67      6841522.10
#Sta/Elev= 30
  4661.6  426.91  4691.4  427.16  4728.8  425.77  4750.3  422.97  4787.7  420.33
  4836.5  415.38  4879.3  411.43  4961.9  406.04  4997.8  404.93  5007.8  402.38
  5008.3  396.17  5008.8  395.67  5023.8  396.17  5029.3  397.23  5035.1  397.03
  5042.7  403.32  5047.9  403.39  5072.2  404.02  5130.8  403.17  5173.7  403.64
  5216.7  402.82  5289.0  402.90  5379.2  402.85  5429.5  401.87  5546.7  402.20
  5692.4  408.36  5759.6  409.31  5781.1  410.64  5802.6  410.45  5937.3  414.40
#Mann=7,-1,0
  4661.6    0.07       0  4836.5    0.16       0  4879.3    0.12       0
  5008.3    0.07       0  5023.8    0.12       0  5047.9    0.16       0
  5289.0   0.045       0
Bank Sta=5008.3,5023.8
Exp/Cntr=0.3,0.1

Type RM Length L Ch R = 1,8218,360,360,360
BEGIN DESCRIPTION:
Chamblee Creek8218.36
END DESCRIPTION:
XS GIS Cut Line= 3
      2743582.33      6840456.96      2743243.09      6840665.35
      2742370.67      6841380.18
#Sta/Elev= 30
  4610.6  420.69  4636.3  419.22  4689.7  416.12  4699.3  414.25  4720.6  411.89
  4864.5  402.88  4894.6  402.41  4952.6  403.85  4958.4  402.65  4973.9  395.58
  4981.5  395.33  4982.0  394.83  4997.0  395.33  5004.1  402.19  5018.5  402.59
  5031.4  403.28  5109.6  402.93  5124.0  402.11  5202.2  401.14  5230.9  401.85
  5259.6  401.29  5365.8  401.98  5420.1  402.44  5562.3  403.83  5735.5  405.13
  5848.4  407.74  5877.6  408.12  5941.5  413.45  6026.3  416.25  6136.6  421.64
#Mann=9,-1,0
  4610.6    0.07       0  4636.3    0.12       0  4981.5    0.07       0
  4997.0    0.12       0  5018.5    0.16       0  5365.8    0.12       0
  5420.1    0.16       0  5562.3    0.12       0  5848.4   0.045       0
Bank Sta=4981.5,4997
Exp/Cntr=0.3,0.1

Type RM Length L Ch R = 1,7858,413,413,413
BEGIN DESCRIPTION:
Chamblee Creek7857.95
END DESCRIPTION:
XS GIS Cut Line= 3
      2743657.57      6840380.85      2742970.79      6840533.28
      2741549.00      6840633.37
#Sta/Elev= 30
  4301.6  424.16  4414.0  418.76  4462.9  413.11  4497.8  414.30  4511.6  412.13
  4528.6  405.68  4631.0  405.91  4652.5  410.38  4690.9  402.52  4827.9  402.21
  4967.7  402.39  4979.3  401.88  4992.0  395.86  4992.5  395.36  5007.6  395.86
  5010.0  401.67  5019.9  403.23  5353.6  400.58  5487.1  400.66  5586.5  401.06
  5811.6  403.05  5841.9  404.51  5852.0  402.19  5872.0  404.83  5962.2  403.00
  6083.5  413.65  6182.9  419.43  6282.3  425.83  6359.9  426.87  6430.4  426.98
#Mann=13,-1,0
  4301.6    0.07       0  4414.0    0.12       0  4827.9    0.16       0
  4992.0    0.07       0  5007.6    0.16       0  5353.6   0.045       0
  5487.1    0.16       0  5586.5   0.045       0  5811.6    0.16       0
  6083.5    0.12       0  6182.9   0.045       0  6282.3   0.035       0
  6359.9   0.045       0
Bank Sta=4992,5007.6
Exp/Cntr=0.3,0.1

Type RM Length L Ch R = 1,7445,816,816,816
BEGIN DESCRIPTION:
Chamblee Creek7444.53
END DESCRIPTION:
XS GIS Cut Line= 3
      2743627.11      6840271.89      2742772.16      6840238.46
      2741351.94      6840191.58
#Sta/Elev= 30
  4148.5  420.80  4219.7  418.61  4249.7  416.60  4279.7  412.93  4349.8  409.06
  4589.9  401.92  4813.1  400.99  4960.2  402.11  4981.6  400.41  4990.3  394.99
  5002.5  394.15  5003.0  393.65  5018.1  394.15  5020.3  399.64  5030.3  402.64
  5140.3  400.84  5240.4  400.58  5260.4  401.65  5470.5  400.30  5540.6  397.76
  5590.6  400.08  5640.6  400.08  5660.6  396.76  5680.3  400.52  5830.7  399.80
  5900.8  401.08  5986.9  406.42  6070.1  409.12  6321.0  421.88  6425.1  424.68
#Mann=5,-1,0
  4148.5   0.035       0  4981.6    0.12       0  5002.5    0.07       0
  5018.1    0.12       0  6070.1   0.035       0
Bank Sta=5002.5,5018.1
Exp/Cntr=0.3,0.1

Type RM Length L Ch R = 1,6629,807,807,807
BEGIN DESCRIPTION:
Chamblee Creek6629.29
END DESCRIPTION:
XS GIS Cut Line= 3
      2743596.54      6840015.71      2742072.35      6840013.94
      2741259.04      6840011.81
#Sta/Elev= 30
  3482.3  424.01  3942.8  401.03  4082.8  400.24  4152.8  401.74  4202.8  399.85
  4232.8  400.51  4242.8  403.28  4252.8  403.61  4278.8  400.16  4382.8  399.41
  4442.8  401.22  4452.8  398.69  4462.8  398.76  4492.8  401.79  4602.8  401.54
  4773.7  405.67  4962.8  399.16  4975.0  392.61  4975.5  392.11  4990.7  392.61
  5002.2  399.10  5012.8  399.21  5022.8  393.27  5032.8  397.99  5070.7  400.03
  5262.8  398.52  5482.8  399.46  5632.8  408.11  5722.8  411.12  5819.8  410.72
#Mann=6,-1,0
  3482.3    0.05       0  4278.8    0.12       0  4773.7    0.16       0
  4975.0    0.07       0  4990.7    0.16       0  5070.7    0.12       0
Bank Sta=4975,4990.7
Exp/Cntr=0.3,0.1

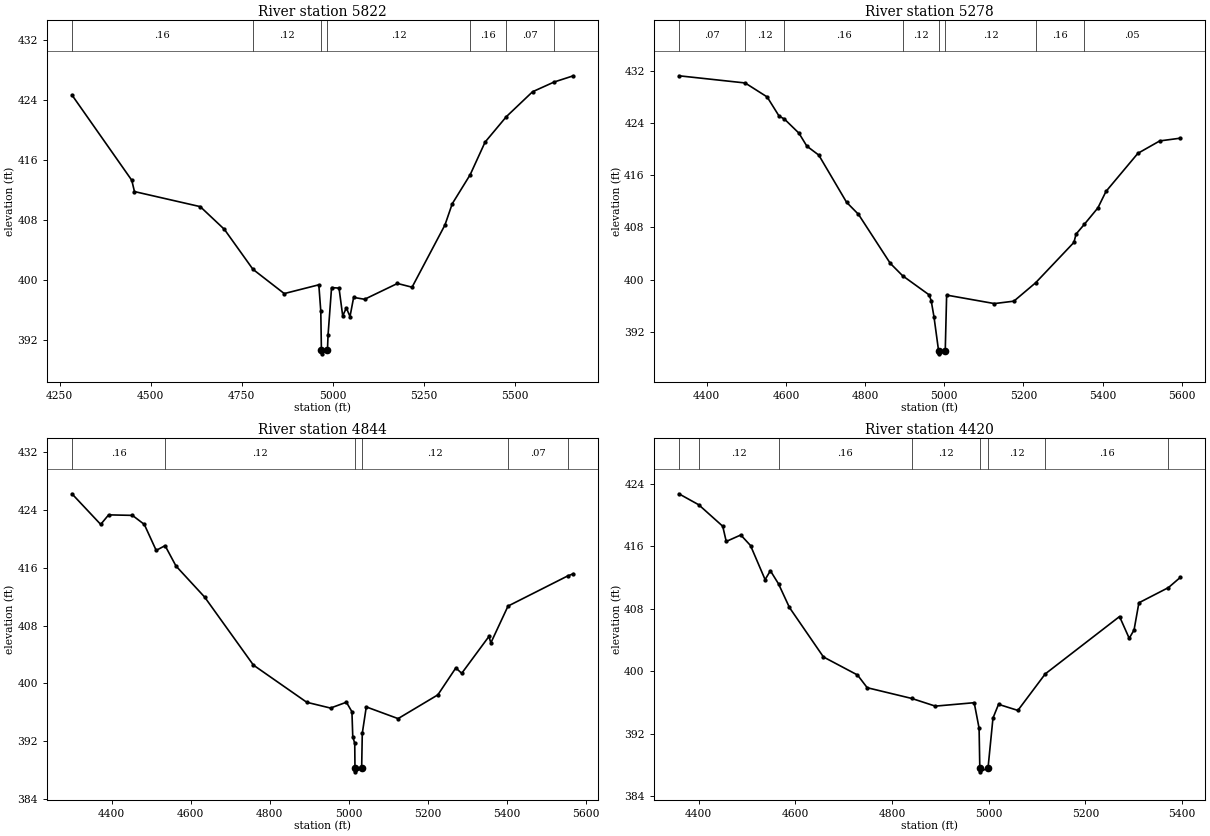
Type RM Length L Ch R = 1,5822,544,544,544
BEGIN DESCRIPTION:
Chamblee Creek5822.49
END DESCRIPTION:
XS GIS Cut Line= 3
      2742217.23      6839533.43      2741501.93      6839589.10
      2740844.14      6839635.76
#Sta/Elev= 30
  4284.0  424.72  4448.3  413.34  4455.7  411.83  4636.3  409.82  4702.6  406.79
  4781.0  401.46  4867.0  398.22  4961.9  399.39  4967.3  395.88  4969.0  390.68
  4969.5  390.18  4985.6  390.68  4987.3  392.73  4996.9  399.02  5017.4  398.95
  5027.5  395.24  5037.5  396.31  5047.5  395.15  5057.5  397.71  5087.6  397.46
  5177.8  399.57  5217.9  399.07  5308.2  407.37  5328.2  410.20  5377.5  414.08
  5418.4  418.43  5476.9  421.83  5548.8  425.15  5608.1  426.45  5660.9  427.28
#Mann=7,-1,0
  4284.0    0.16       0  4781.0    0.12       0  4969.0    0.07       0
  4985.6    0.12       0  5377.5    0.16       0  5476.9    0.07       0
  5608.1    0.05       0
Bank Sta=4969,4985.6
Exp/Cntr=0.3,0.1

Type RM Length L Ch R = 1,5278,434,434,434
BEGIN DESCRIPTION:
Chamblee Creek5278.4
END DESCRIPTION:
XS GIS Cut Line= 3
      2741998.27      6839107.38      2741327.08      6839158.91
      2740739.90      6839243.45
#Sta/Elev= 30
  4329.7  431.23  4497.0  430.13  4552.6  427.99  4582.7  425.06  4596.4  424.59
  4632.9  422.44  4652.9  420.45  4683.0  419.08  4753.2  411.85  4783.3  410.00
  4863.5  402.50  4894.8  400.59  4961.8  397.66  4966.9  396.77  4973.9  394.32
  4985.5  389.13  4986.0  388.63  5002.4  389.13  5005.9  397.63  5126.5  396.33
  5175.7  396.70  5230.7  399.52  5327.3  405.70  5332.8  406.98  5353.3  408.45
  5387.9  410.99  5408.3  413.51  5488.9  419.35  5544.1  421.25  5596.1  421.67
#Mann=8,-1,0
  4329.7    0.07       0  4497.0    0.12       0  4596.4    0.16       0
  4894.8    0.12       0  4985.5    0.07       0  5002.4    0.12       0
  5230.7    0.16       0  5353.3    0.05       0
Bank Sta=4985.5,5002.4
Exp/Cntr=0.3,0.1

Type RM Length L Ch R = 1,4844,424,424,424
BEGIN DESCRIPTION:
Chamblee Creek4843.52
END DESCRIPTION:
XS GIS Cut Line= 3
      2741848.60      6838729.74      2741142.04      6838785.63
      2740585.15      6838850.29
#Sta/Elev= 30
  4299.6  426.26  4372.4  422.02  4392.5  423.34  4452.7  423.27  4482.8  422.02
  4512.9  418.42  4535.4  419.08  4563.0  416.26  4635.5  411.96  4759.0  402.54
  4894.1  397.39  4954.2  396.59  4994.4  397.40  5008.4  396.08  5010.5  392.62
  5015.5  391.71  5016.1  388.26  5016.6  387.76  5033.0  388.26  5034.6  393.09
  5044.7  396.75  5125.2  395.13  5225.9  398.42  5271.4  402.15  5286.3  401.40
  5355.1  406.50  5360.1  405.62  5403.5  410.71  5554.7  414.89  5569.0  415.19
#Mann=6,-1,0
  4299.6    0.16       0  4535.4    0.12       0  5016.1    0.07       0
  5033.0    0.12       0  5403.5    0.07       0  5554.7    0.05       0
Bank Sta=5016.1,5033
Exp/Cntr=0.3,0.1

Type RM Length L Ch R = 1,4420,372,372,372
BEGIN DESCRIPTION:
Chamblee Creek4419.78
END DESCRIPTION:
XS GIS Cut Line= 3
      2741663.34      6838366.84      2741013.78      6838434.48
      2740630.42      6838451.29
#Sta/Elev= 30
  4359.4  422.73  4400.5  421.32  4450.1  418.57  4457.3  416.62  4487.4  417.45
  4507.5  416.10  4537.7  411.73  4548.6  412.87  4565.4  411.19  4588.0  408.16
  4658.3  401.82  4728.7  399.51  4748.8  397.88  4841.1  396.50  4889.6  395.52
  4970.0  395.96  4980.1  392.69  4981.6  387.60  4982.1  387.10  4998.6  387.60
  5008.8  393.99  5020.3  395.75  5060.3  394.97  5116.9  399.65  5270.5  407.00
  5290.5  404.21  5300.5  405.28  5310.5  408.76  5371.6  410.71  5396.2  412.02
#Mann=8,-1,0
  4359.4    0.16       0  4400.5    0.12       0  4565.4    0.16       0
  4841.1    0.12       0  4981.6    0.07       0  4998.6    0.12       0
  5116.9    0.16       0  5371.6    0.05       0
Bank Sta=4981.6,4998.6
Exp/Cntr=0.3,0.1