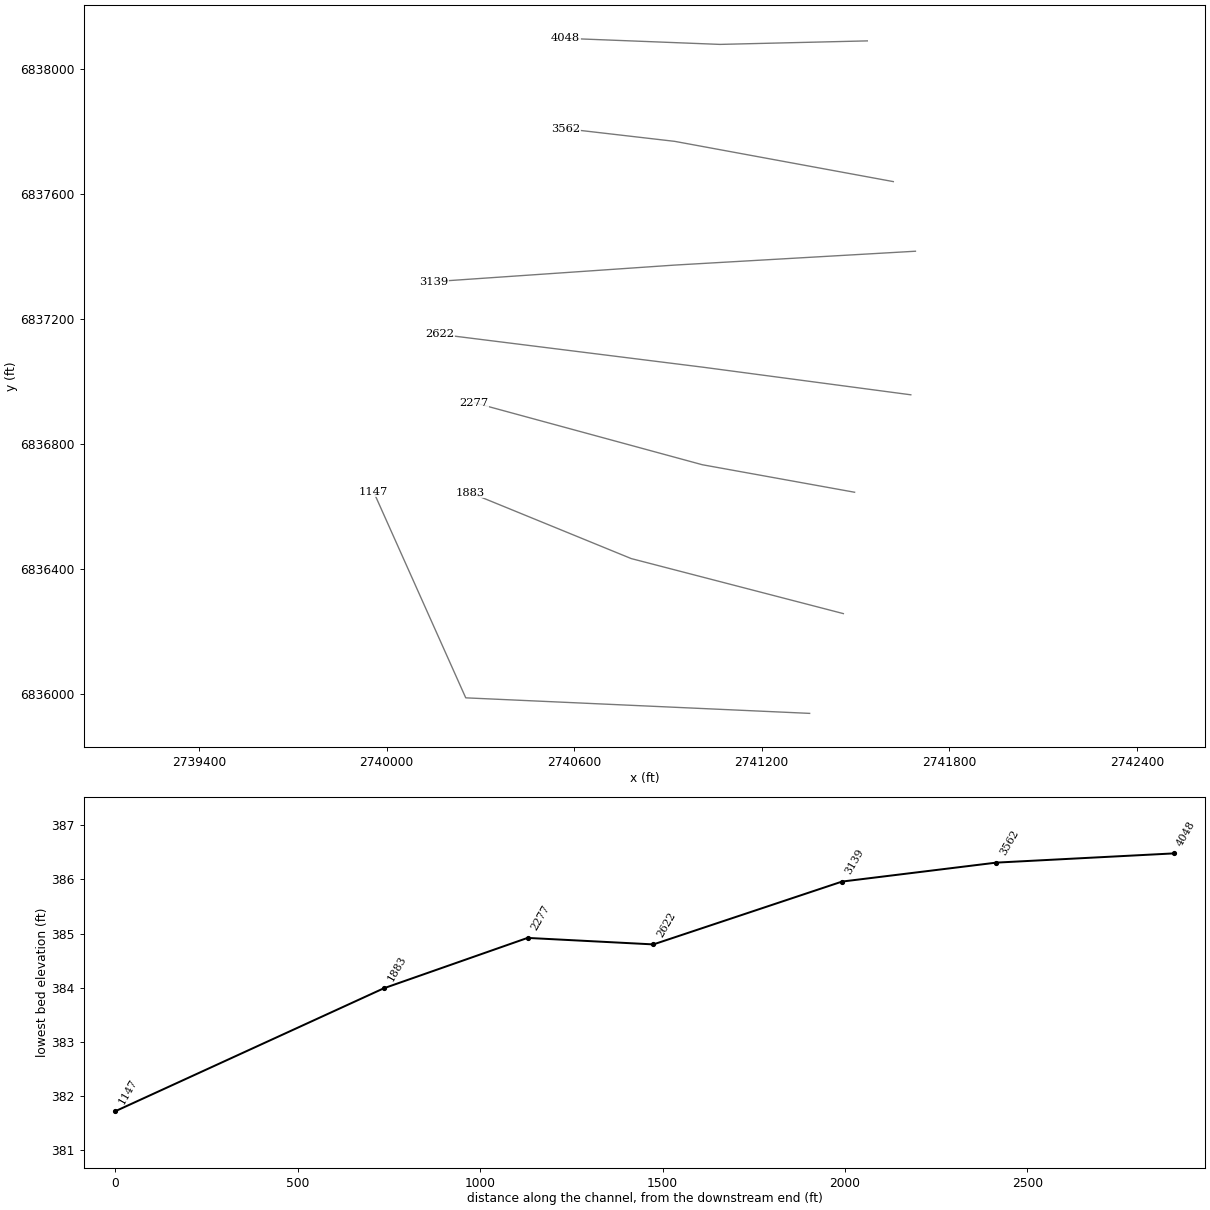
HEC-RAS study Chamblee Creek.prj: Chamblee Creek Base Level Engineering

--- Chamblee Creek.g01 (geometry) --- (continued)

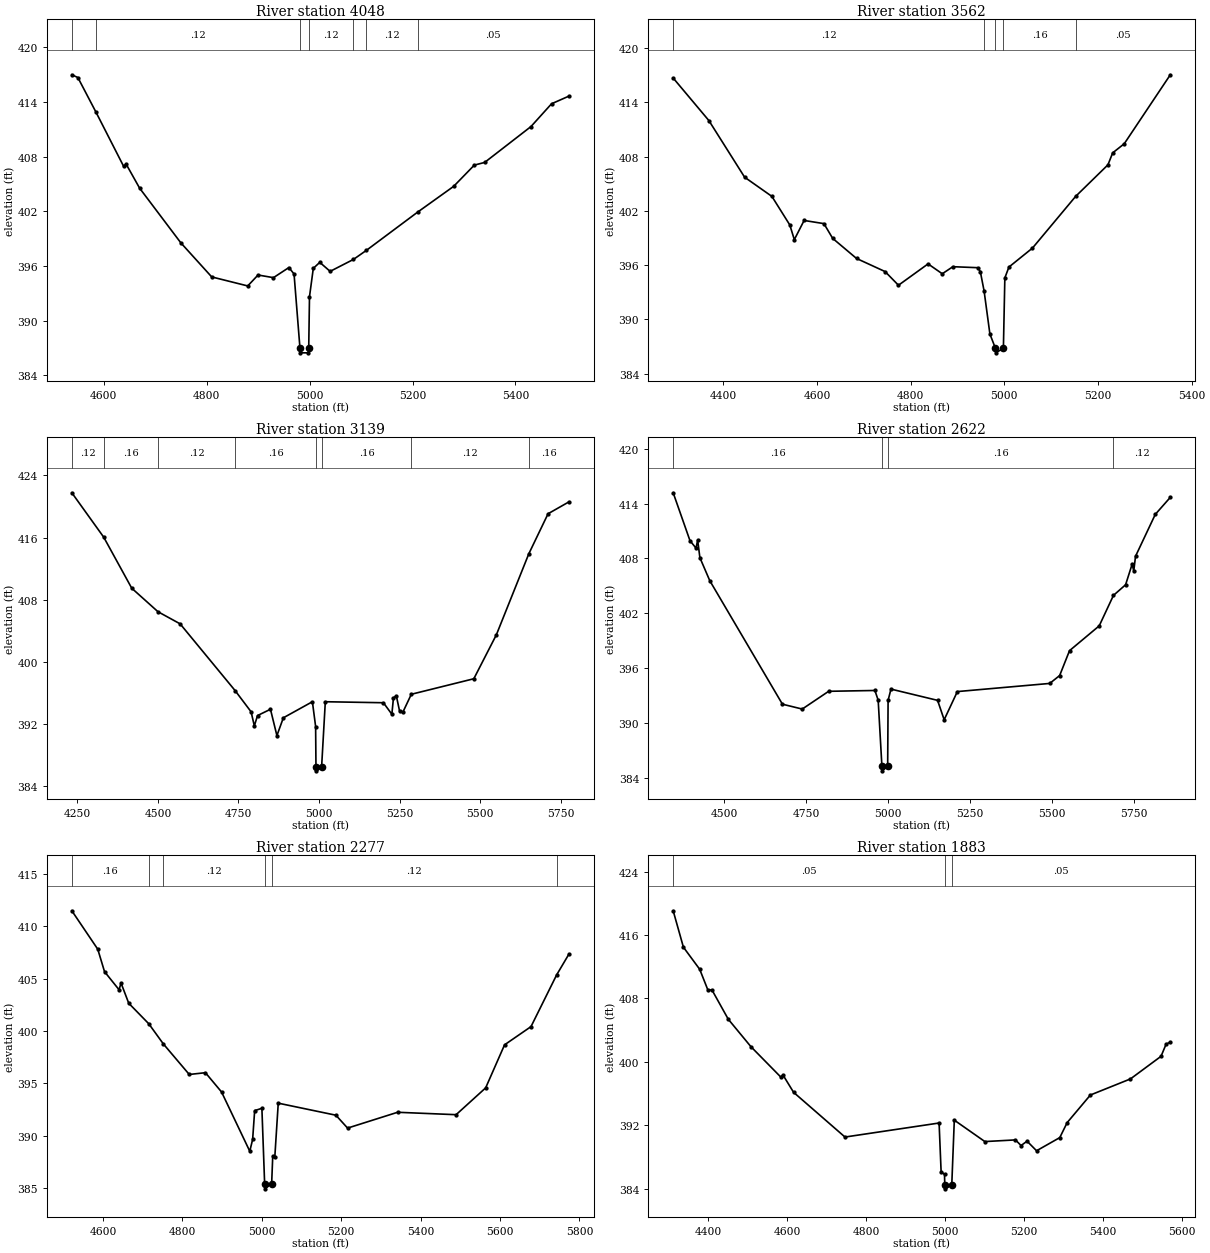
Type RM Length L Ch R = 1,4048,486,486,486
BEGIN DESCRIPTION:
Chamblee Creek4047.93
END DESCRIPTION:
XS GIS Cut Line= 3
      2741537.71      6838088.49      2741066.37      6838077.25
      2740572.22      6838096.65
#Sta/Elev= 30
  4537.9  416.99  4549.6  416.69  4584.8  412.89  4638.5  406.95  4643.5  407.18
  4669.6  404.55  4749.7  398.55  4809.7  394.81  4879.7  393.82  4899.7  395.02
  4929.7  394.73  4959.7  395.84  4969.7  395.13  4981.2  386.98  4981.7  386.48
  4997.7  386.48  4998.2  386.98  4999.7  392.64  5007.1  395.75  5019.7  396.41
  5039.8  395.42  5085.1  396.73  5110.4  397.73  5209.6  401.91  5279.9  404.75
  5320.0  407.08  5340.0  407.37  5430.1  411.31  5470.1  413.81  5503.9  414.65
#Mann=7,-1,0
  4537.9    0.16       0  4584.8    0.12       0  4981.2    0.07       0
  4998.2    0.12       0  5085.1    0.16       0  5110.4    0.12       0
  5209.6    0.05       0
Bank Sta=4981.2,4998.2
Exp/Cntr=0.3,0.1

Type RM Length L Ch R = 1,3562,423,423,423
BEGIN DESCRIPTION:
Mapping XS dbdd7849
END DESCRIPTION:
XS GIS Cut Line= 3
      2741620.91      6837638.36      2740921.47      6837767.14
      2740573.78      6837807.35
#Sta/Elev= 30
  4293.1  416.68  4369.3  411.98  4445.6  405.72  4503.8  403.60  4542.1  400.44
  4551.7  398.82  4572.6  400.94  4614.9  400.59  4633.6  398.96  4684.5  396.74
  4745.5  395.29  4774.0  393.78  4837.2  396.14  4867.5  395.05  4890.2  395.83
  4943.3  395.72  4948.8  395.28  4956.8  393.15  4969.2  388.39  4981.0  386.81
  4981.5  386.31  4998.0  386.81  5001.1  394.59  5009.8  395.79  5060.1  397.89
  5152.2  403.60  5221.2  407.09  5231.3  408.41  5256.0  409.42  5354.3  417.04
#Mann=5,-1,0
  4293.1    0.12       0  4956.8    0.16       0  4981.0    0.07       0
  4998.0    0.16       0  5152.2    0.05       0
Bank Sta=4981,4998
Exp/Cntr=0.3,0.1

Type RM Length L Ch R = 1,3139,517,517,517
BEGIN DESCRIPTION:
Chamblee Creek3138.83
END DESCRIPTION:
XS GIS Cut Line= 3
      2741691.66      6837415.66      2740921.35      6837371.32
      2740151.25      6837318.34
#Sta/Elev= 30
  4232.6  421.77  4331.6  416.05  4418.6  409.48  4500.1  406.45  4568.8  404.89
  4739.6  396.29  4789.2  393.56  4799.2  391.75  4809.2  393.08  4849.3  393.89
  4869.3  390.50  4889.3  392.79  4979.5  394.86  4989.5  391.67  4990.6  386.46
  4991.1  385.96  5008.1  386.46  5019.6  394.86  5200.0  394.73  5226.2  393.25
  5231.2  395.36  5240.1  395.62  5250.1  393.67  5260.1  393.49  5286.6  395.82
  5480.7  397.82  5550.8  403.49  5651.5  413.92  5711.2  419.07  5776.1  420.60
#Mann=8,-1,0
  4232.6    0.12       0  4331.6    0.16       0  4500.1    0.12       0
  4739.6    0.16       0  4990.6    0.07       0  5008.1    0.16       0
  5286.6    0.12       0  5651.5    0.16       0
Bank Sta=4990.6,5008.1
Exp/Cntr=0.3,0.1

Type RM Length L Ch R = 1,2622,345,345,345
BEGIN DESCRIPTION:
Chamblee Creek2622.42
END DESCRIPTION:
XS GIS Cut Line= 3
      2741676.89      6836956.38      2741013.62      6837044.48
      2740170.47      6837149.87
#Sta/Elev= 30
  4343.3  415.18  4394.6  409.95  4413.1  409.13  4418.1  410.01  4424.9  408.09
  4455.2  405.57  4677.1  392.08  4737.6  391.55  4818.3  393.49  4959.6  393.58
  4969.6  392.52  4981.0  385.30  4981.5  384.80  4998.6  385.30  4999.9  392.50
  5008.7  393.73  5151.1  392.50  5171.2  390.38  5211.5  393.46  5493.7  394.35
  5524.0  395.21  5554.2  397.93  5644.9  400.64  5688.4  403.97  5725.5  405.13
  5745.4  407.37  5750.5  406.65  5755.8  408.24  5816.2  412.82  5862.1  414.68
#Mann=4,-1,0
  4343.3    0.16       0  4981.0    0.07       0  4998.6    0.16       0
  5688.4    0.12       0
Bank Sta=4981,4998.6
Exp/Cntr=0.3,0.1

Type RM Length L Ch R = 1,2277,394,394,394
BEGIN DESCRIPTION:
Chamblee Creek2276.61
END DESCRIPTION:
XS GIS Cut Line= 3
      2741497.01      6836644.69      2741010.03      6836732.67
      2740279.51      6836931.30
#Sta/Elev= 30
  4521.8  411.47  4587.1  407.80  4604.1  405.66  4640.7  403.93  4645.7  404.57
  4665.1  402.64  4715.6  400.68  4752.2  398.76  4817.5  395.84  4858.2  396.01
  4898.8  394.17  4969.9  388.51  4977.1  389.64  4982.2  392.39  5000.4  392.61
  5007.3  385.42  5007.8  384.92  5025.0  385.42  5027.7  388.01  5032.9  387.93
  5041.6  393.10  5186.8  391.95  5216.2  390.72  5342.1  392.23  5489.5  392.00
  5563.9  394.56  5611.5  398.67  5678.1  400.41  5742.7  405.35  5773.7  407.34
#Mann=6,-1,0
  4521.8    0.16       0  4715.6    0.05       0  4752.2    0.12       0
  5007.3    0.07       0  5025.0    0.12       0  5742.7    0.05       0
Bank Sta=5007.3,5025
Exp/Cntr=0.3,0.1

Type RM Length L Ch R = 1,1883,736,736,736
BEGIN DESCRIPTION:
Chamblee Creek1882.54
END DESCRIPTION:
XS GIS Cut Line= 3
      2741461.09      6836256.46      2740782.48      6836432.52
      2740266.14      6836643.62
#Sta/Elev= 30
  4311.4  419.05  4337.3  414.46  4378.6  411.67  4399.3  409.06  4409.6  409.07
  4451.0  405.37  4508.2  401.92  4584.2  398.07  4589.4  398.35  4616.3  396.16
  4746.5  390.52  4984.8  392.29  4989.9  386.16  4998.5  385.80  4999.2  384.49
  4999.7  383.99  5016.9  384.49  5023.3  392.65  5100.7  389.95  5178.2  390.16
  5192.3  389.45  5207.6  390.00  5231.6  388.79  5290.4  390.45  5309.1  392.34
  5367.9  395.82  5469.4  397.85  5546.8  400.70  5559.7  402.24  5570.3  402.48
#Mann=3,-1,0
  4311.4    0.05       0  4999.2    0.05       0  5016.9    0.05       0
Bank Sta=4999.2,5016.9
Exp/Cntr=0.3,0.1

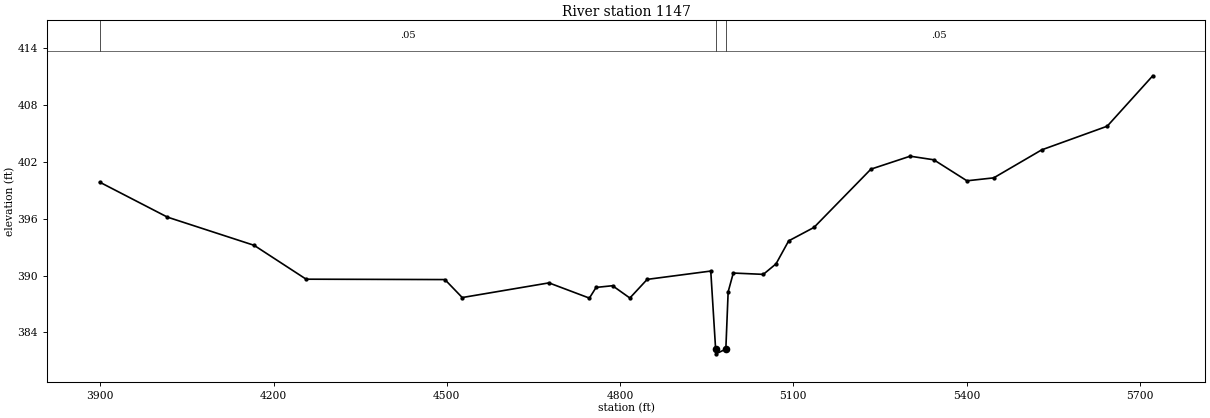
Type RM Length L Ch R = 1,1147,0,0,0
BEGIN DESCRIPTION:
Chamblee Creek1384.037
END DESCRIPTION:
XS GIS Cut Line= 3
      2741353.26      6835937.34      2740253.18      6835987.05
      2739958.17      6836646.58
#Sta/Elev= 30
  3898.8  399.87  4016.2  396.17  4166.3  393.19  4256.4  389.61  4496.7  389.57
  4526.7  387.67  4676.9  389.22  4746.9  387.61  4758.5  388.74  4787.0  388.92
  4817.0  387.62  4847.0  389.59  4957.1  390.47  4965.5  382.22  4966.0  381.72
  4983.2  382.22  4987.2  388.27  4996.1  390.26  5048.1  390.12  5070.1  391.23
  5092.0  393.66  5135.8  395.08  5234.4  401.24  5302.4  402.61  5343.3  402.23
  5400.7  400.01  5447.1  400.32  5530.2  403.28  5643.6  405.78  5722.5  411.11
#Mann=3,-1,0
  3898.8    0.05       0  4965.5    0.05       0  4983.2    0.05       0
Bank Sta=4965.5,4983.2
Exp/Cntr=0.3,0.1

Chan Stop Cuts=-1