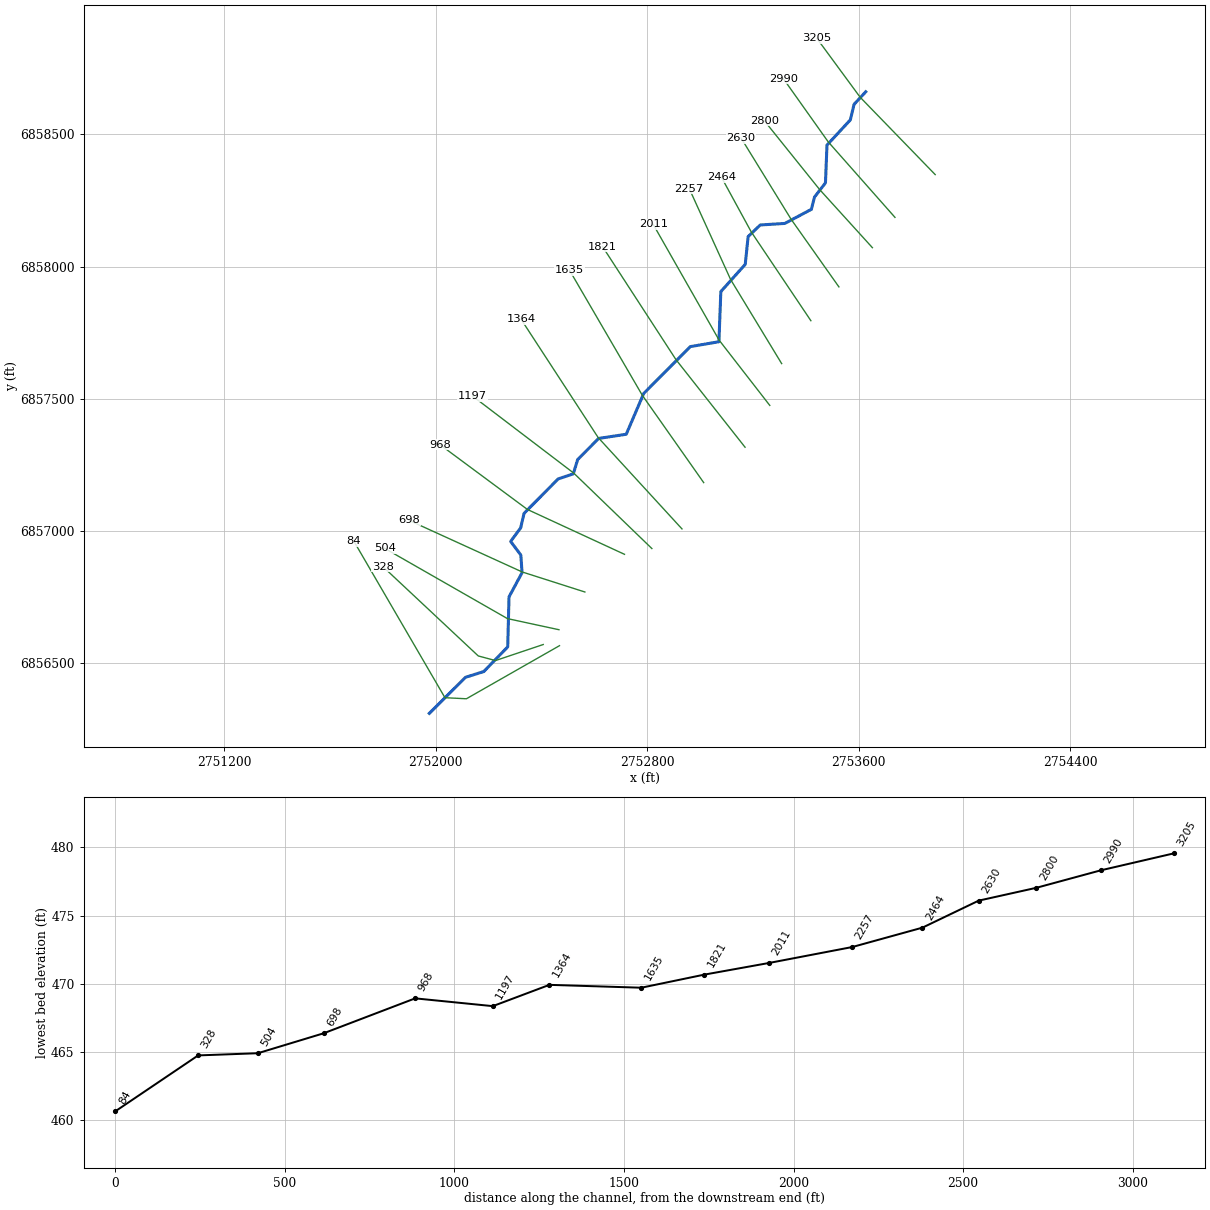
--- Chamblee Creek Trib A.prj (project) ---

Proj Title=Chamblee Creek Trib A Base Level Engineering
Current Plan=p01
Default Exp/Contr=0.3,0.1
English Units
Geom File=g01
Flow File=f01
Plan File=p01
BEGIN DESCRIPTION:
Chamblee Creek Trib A
END DESCRIPTION:

--- Chamblee Creek Trib A.p01 (plan) ---

Plan Title=Multiple Run
Short Identifier=Multiple
Geom File=g01
Flow File=f01
Subcritical Flow
K Sum by GR= 0
Std Step Tol= 0.01
Critical Tol= 0.01
Num of Std Step Trials= 20
Max Error Tol= 0.3
Flow Tol Ratio= 0.001
Split Flow NTrial= 30
Split Flow Tol= 0.02
Split Flow Ratio= 0.02
Log Output Level= 0
Friction Slope Method= 1
Unsteady Friction Slope Method= 2
Unsteady Bridges Friction Slope Method= 1
Parabolic Critical Depth
Global Vel Dist=  1 , 1 , 1
Global Log Level= 0
CheckData=True
Encroach Param= -1, 0, 0, 0
BEGIN DESCRIPTION:
Multiple Run
END DESCRIPTION:

--- Chamblee Creek Trib A.f01 (steady flow) ---

Flow Title=Multiple
Number of Profiles=7
Profile Names=10-year,25-year,50-year,1pct_min,100-year,1pct_plu,500-year
River Rch & RM= Chamblee Creek T,Reach-1,3205
     438     579     692     411     820    1637    1155
Boundary for River Rch & Prof#=Chamblee Creek T,Reach-1,1
Up Type=0
Dn Type=3
Dn Slope=0.005
Boundary for River Rch & Prof#=Chamblee Creek T,Reach-1,2
Up Type=0
Dn Type=3
Dn Slope=0.005
Boundary for River Rch & Prof#=Chamblee Creek T,Reach-1,3
Up Type=0
Dn Type=3
Dn Slope=0.005
Boundary for River Rch & Prof#=Chamblee Creek T,Reach-1,4
Up Type=0
Dn Type=3
Dn Slope=0.005
Boundary for River Rch & Prof#=Chamblee Creek T,Reach-1,5
Up Type=0
Dn Type=3
Dn Slope=0.005
Boundary for River Rch & Prof#=Chamblee Creek T,Reach-1,6
Up Type=0
Dn Type=3
Dn Slope=0.005
Boundary for River Rch & Prof#=Chamblee Creek T,Reach-1,7
Up Type=0
Dn Type=3
Dn Slope=0.005

--- Chamblee Creek Trib A.g01 (geometry) ---

Geom Title=Existing Conditions

River Reach=Chamblee Creek T,Reach-1
Reach XY= 30
      2753626.00      6858661.00      2753581.70      6858613.35
      2753567.93      6858554.92      2753479.55      6858459.53
      2753473.76      6858316.91      2753432.28      6858262.84
      2753420.42      6858216.58      2753320.05      6858163.33
      2753227.25      6858157.49      2753181.41      6858113.71
      2753170.46      6858008.58      2753078.18      6857905.55
      2753070.97      6857716.08      2752962.73      6857697.58
      2752786.77      6857520.68      2752720.56      6857366.25
      2752616.23      6857350.47      2752536.88      6857270.44
      2752520.38      6857216.62      2752463.02      6857197.28
      2752334.12      6857067.05      2752321.55      6857012.65
      2752283.53      6856961.01      2752322.06      6856909.50
      2752326.63      6856842.77      2752277.38      6856751.34
      2752272.47      6856562.45      2752182.07      6856469.15
      2752112.79      6856447.37      2751976.00      6856311.00

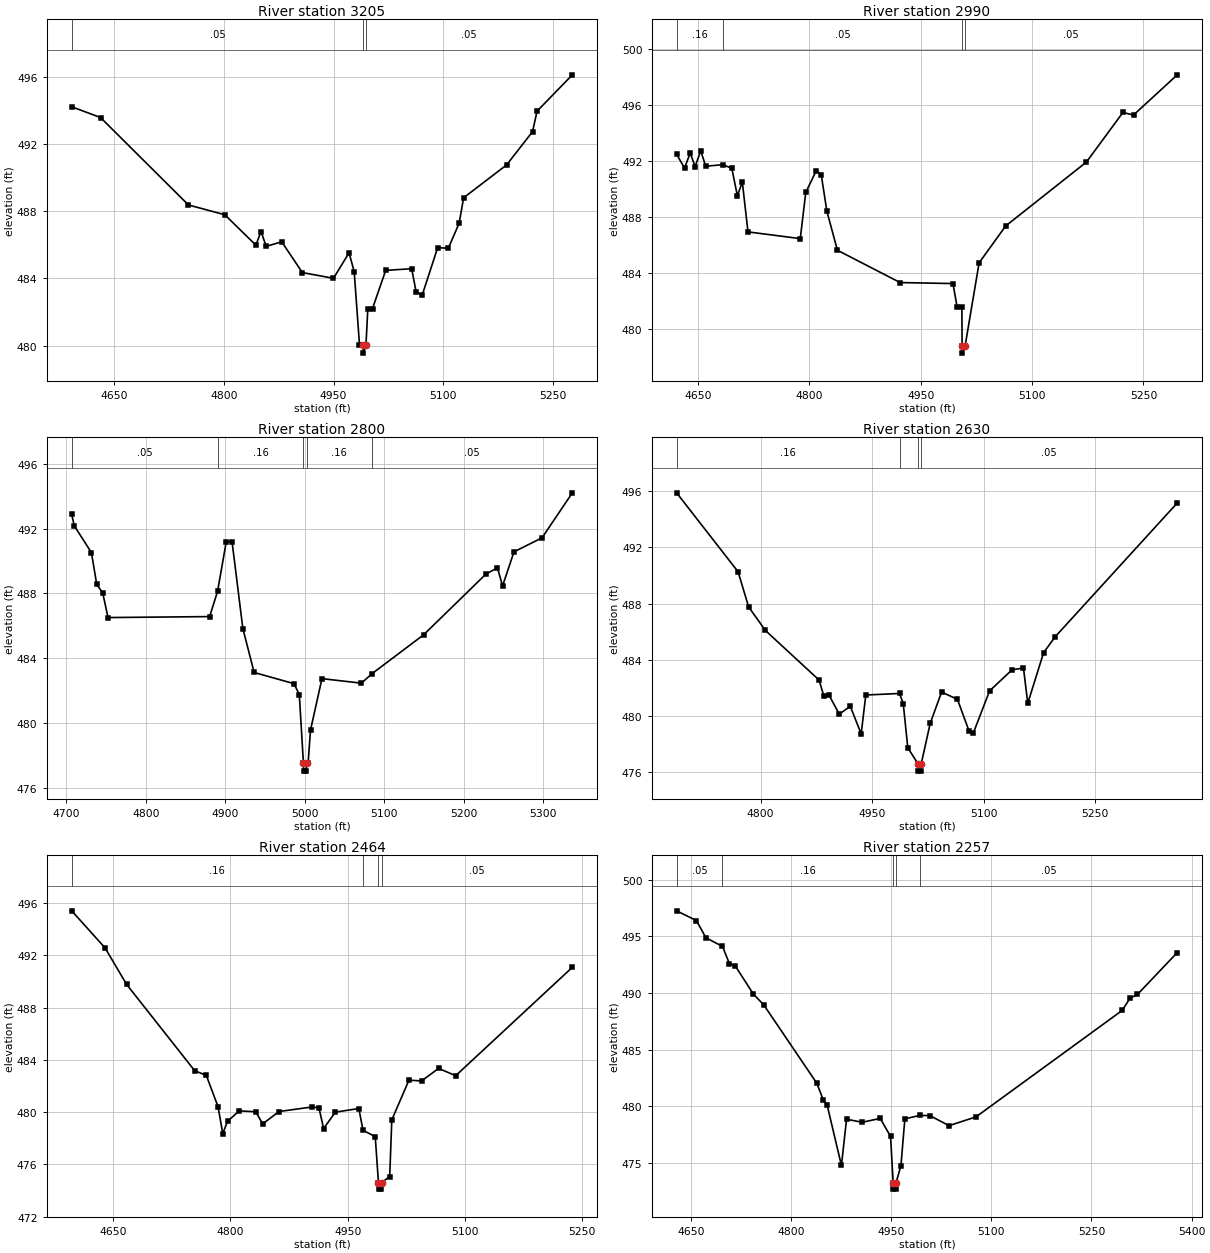
Type RM Length L Ch R = 1,3205,215,215,215
BEGIN DESCRIPTION:
Chamblee Creek Trib A3205.339
END DESCRIPTION:
XS GIS Cut Line= 3
      2753888.66      6858347.97      2753604.78      6858640.61
      2753441.20      6858863.15
#Sta/Elev= 30
  4592.3  494.20  4631.7  493.56  4751.8  488.36  4801.4  487.78  4843.9  485.97
  4850.9  486.78  4858.0  485.90  4879.2  486.17  4907.4  484.34  4949.9  484.00
  4971.2  485.52  4978.2  484.39  4985.4  480.06  4990.3  480.05  4990.6  479.55
  4994.3  480.05  4996.8  482.20  5003.2  482.20  5021.2  484.47  5056.7  484.57
  5062.9  483.16  5071.3  483.03  5092.2  485.82  5106.8  485.79  5121.5  487.27
  5127.7  488.79  5186.3  490.74  5221.8  492.72  5228.0  493.94  5276.2  496.10
#Mann=3,-1,0
  4592.3    0.05       0  4990.3    0.05       0  4994.3    0.05       0
Bank Sta=4990.3,4994.3
Exp/Cntr=0.3,0.1

Type RM Length L Ch R = 1,2990,190,190,190
BEGIN DESCRIPTION:
Chamblee Creek Trib A2990.49
END DESCRIPTION:
XS GIS Cut Line= 3
      2753736.58      6858186.24      2753483.72      6858472.34
      2753314.59      6858710.71
#Sta/Elev= 30
  4621.4  492.51  4632.1  491.53  4639.7  492.60  4646.3  491.64  4653.9  492.76
  4660.6  491.66  4683.3  491.77  4695.7  491.52  4703.2  489.56  4709.9  490.52
  4717.5  486.97  4787.9  486.49  4795.3  489.79  4809.5  491.35  4816.1  491.07
  4823.7  488.45  4837.9  485.66  4922.4  483.35  4993.5  483.28  4999.0  481.63
  5005.5  481.63  5005.8  478.81  5006.1  478.31  5009.8  478.81  5028.7  484.76
  5064.4  487.39  5173.2  491.96  5222.3  495.50  5236.6  495.32  5295.5  498.19
#Mann=4,-1,0
  4621.4    0.16       0  4683.3    0.05       0  5005.8    0.05       0
  5009.8    0.05       0
Bank Sta=5005.8,5009.8
Exp/Cntr=0.3,0.1

Type RM Length L Ch R = 1,2800,170,170,170
BEGIN DESCRIPTION:
Chamblee Creek Trib A2800.47
END DESCRIPTION:
XS GIS Cut Line= 3
      2753651.26      6858071.61      2753451.39      6858291.88
      2753243.20      6858550.97
#Sta/Elev= 30
  4706.6  492.88  4709.8  492.18  4731.4  490.52  4738.1  488.56  4745.6  488.03
  4752.3  486.51  4880.1  486.57  4890.1  488.13  4901.0  491.19  4908.3  491.20
  4921.9  485.83  4936.1  483.12  4986.2  482.43  4992.9  481.76  4998.1  477.53
  4998.3  477.03  5001.8  477.03  5002.1  477.53  5004.0  477.53  5007.0  479.56
  5021.4  482.74  5071.0  482.46  5084.5  483.05  5149.4  485.45  5227.8  489.20
  5242.2  489.58  5248.6  488.46  5263.0  490.57  5298.2  491.43  5336.4  494.21
#Mann=5,-1,0
  4706.6    0.05       0  4890.1    0.16       0  4998.1    0.07       0
  5002.1    0.16       0  5084.5    0.05       0
Bank Sta=4998.1,5002.1
Exp/Cntr=0.3,0.1

Type RM Length L Ch R = 1,2630,166,166,166
BEGIN DESCRIPTION:
Chamblee Creek Trib A2629.98
END DESCRIPTION:
XS GIS Cut Line= 3
      2753524.55      6857923.48      2753344.00      6858178.88
      2753154.85      6858486.04
#Sta/Elev= 30
  4687.1  495.87  4769.8  490.26  4784.0  487.76  4806.5  486.09  4878.8  482.56
  4885.0  481.45  4892.3  481.48  4905.9  480.14  4920.7  480.70  4935.4  478.74
  4941.6  481.50  4987.0  481.61  4992.0  480.88  4998.1  477.75  5012.1  476.59
  5012.4  476.09  5015.9  476.09  5016.1  476.59  5028.2  479.48  5043.6  481.71
  5064.9  481.19  5080.3  478.97  5086.2  478.79  5108.1  481.79  5138.3  483.29
  5153.7  483.42  5159.5  480.91  5180.8  484.51  5196.2  485.63  5360.6  495.15
#Mann=4,-1,0
  4687.1    0.16       0  4987.0    0.05       0  5012.1    0.05       0
  5016.1    0.05       0
Bank Sta=5012.1,5016.1
Exp/Cntr=0.3,0.1

Type RM Length L Ch R = 1,2464,207,207,207
BEGIN DESCRIPTION:
Chamblee Creek Trib A2464.37
END DESCRIPTION:
XS GIS Cut Line= 3
      2753418.67      6857795.52      2753193.23      6858131.21
      2753080.28      6858338.35
#Sta/Elev= 30
  4597.0  495.41  4639.7  492.57  4667.2  489.78  4754.2  483.18  4769.2  482.81
  4784.2  480.41  4790.2  478.36  4796.3  479.30  4811.2  480.10  4832.5  480.03
  4841.2  479.10  4862.2  480.05  4904.7  480.40  4913.2  480.33  4919.2  478.75
  4934.2  480.00  4964.2  480.28  4969.6  478.61  4985.2  478.13  4989.3  474.61
  4989.5  474.11  4993.0  474.11  4993.3  474.61  5003.7  475.07  5006.4  479.41
  5028.3  482.45  5044.4  482.39  5066.2  483.35  5088.1  482.79  5237.3  491.09
#Mann=4,-1,0
  4597.0    0.16       0  4969.6    0.05       0  4989.3    0.05       0
  4993.3    0.05       0
Bank Sta=4989.3,4993.3
Exp/Cntr=0.3,0.1

Type RM Length L Ch R = 1,2257,246,246,246
BEGIN DESCRIPTION:
Chamblee Creek Trib A2256.92
END DESCRIPTION:
XS GIS Cut Line= 3
      2753308.10      6857633.46      2753115.37      6857950.95
      2752958.72      6858295.28
#Sta/Elev= 30
  4628.8  497.25  4658.5  496.39  4672.7  494.87  4697.5  494.11  4707.8  492.60
  4716.6  492.39  4743.8  489.90  4759.3  488.95  4838.8  482.03  4848.2  480.59
  4854.2  480.11  4875.6  474.78  4883.3  478.86  4906.6  478.59  4933.7  478.93
  4949.2  477.34  4953.1  473.19  4953.3  472.69  4956.8  472.69  4957.1  473.19
  4964.7  474.76  4970.6  478.89  4993.1  479.20  5008.3  479.17  5036.8  478.29
  5077.2  479.07  5296.0  488.46  5307.9  489.55  5318.9  489.87  5378.5  493.57
#Mann=5,-1,0
  4628.8    0.05       0  4697.5    0.16       0  4953.1    0.05       0
  4957.1    0.16       0  4993.1    0.05       0
Bank Sta=4953.1,4957.1
Exp/Cntr=0.3,0.1

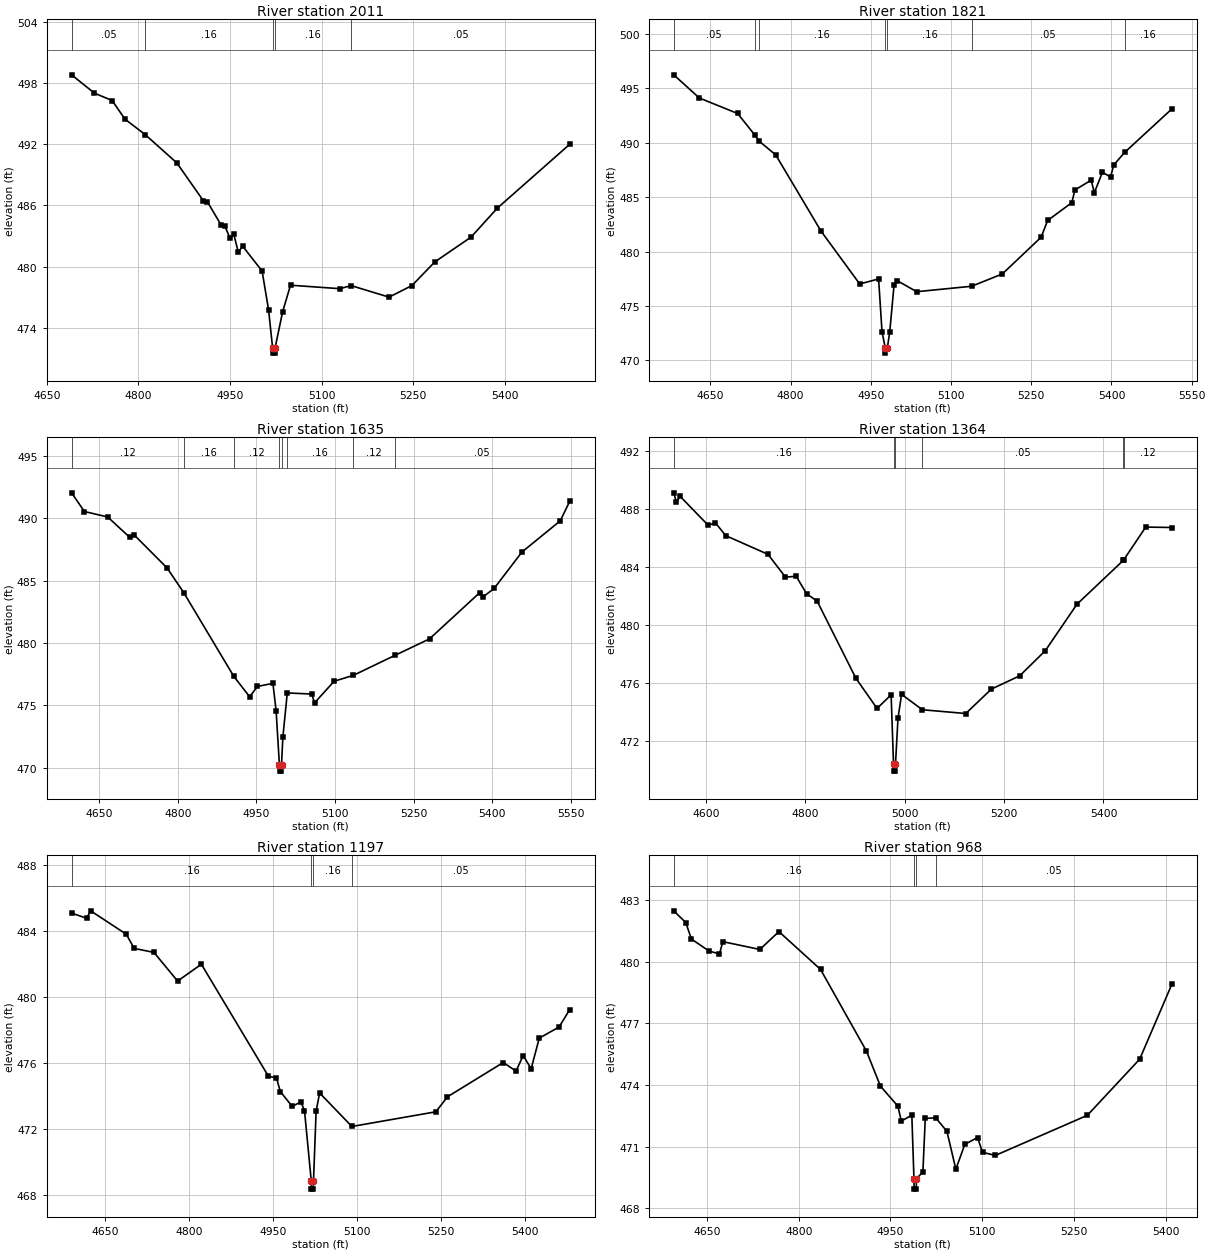
Type RM Length L Ch R = 1,2011,190,190,190
BEGIN DESCRIPTION:
Chamblee Creek Trib A2011.42
END DESCRIPTION:
XS GIS Cut Line= 3
      2753263.21      6857475.36      2753071.88      6857721.81
      2752822.68      6858159.55
#Sta/Elev= 30
  4690.5  498.81  4728.0  497.01  4757.0  496.29  4777.8  494.47  4811.2  492.94
  4862.9  490.17  4906.3  486.46  4912.9  486.36  4935.3  484.09  4941.6  483.96
  4949.8  482.81  4956.1  483.18  4963.5  481.41  4970.6  482.01  5002.5  479.57
  5013.1  475.75  5019.7  472.02  5019.9  471.52  5023.4  471.52  5023.7  472.02
  5036.1  475.58  5049.0  478.18  5129.7  477.84  5148.3  478.14  5210.4  477.01
  5247.9  478.15  5285.4  480.47  5344.5  482.89  5387.7  485.74  5506.2  492.00
#Mann=5,-1,0
  4690.5    0.05       0  4811.2    0.16       0  5019.7    0.07       0
  5023.7    0.16       0  5148.3    0.05       0
Bank Sta=5019.7,5023.7
Exp/Cntr=0.3,0.1

Type RM Length L Ch R = 1,1821,186,186,186
BEGIN DESCRIPTION:
Chamblee Creek Trib A1820.76
END DESCRIPTION:
XS GIS Cut Line= 3
      2753169.79      6857317.20      2752908.46      6857648.58
      2752630.88      6858075.79
#Sta/Elev= 30
  4581.5  496.22  4629.5  494.09  4701.0  492.67  4732.7  490.72  4740.8  490.15
  4772.2  488.87  4857.1  481.86  4929.3  477.02  4964.6  477.48  4971.0  472.63
  4977.0  471.17  4977.3  470.67  4981.0  471.17  4985.4  472.60  4993.5  476.92
  4999.8  477.31  5035.9  476.31  5138.6  476.81  5196.0  477.94  5268.5  481.31
  5280.7  482.85  5325.8  484.48  5331.8  485.65  5362.1  486.55  5368.0  485.40
  5383.2  487.28  5398.3  486.83  5404.3  487.94  5424.5  489.09  5513.0  493.09
#Mann=7,-1,0
  4581.5    0.05       0  4732.7    0.12       0  4740.8    0.16       0
  4977.0    0.07       0  4981.0    0.16       0  5138.6    0.05       0
  5424.5    0.16       0
Bank Sta=4977,4981
Exp/Cntr=0.3,0.1

Type RM Length L Ch R = 1,1635,271,271,271
BEGIN DESCRIPTION:
Chamblee Creek Trib A1635.47
END DESCRIPTION:
XS GIS Cut Line= 3
      2753013.35      6857183.51      2752781.42      6857513.46
      2752506.05      6857986.66
#Sta/Elev= 30
  4597.2  492.06  4621.7  490.56  4666.1  490.12  4707.9  488.50  4716.4  488.69
  4779.4  486.03  4811.5  484.03  4906.7  477.33  4937.1  475.68  4951.9  476.51
  4981.5  476.76  4987.6  474.55  4993.9  470.21  4994.2  469.71  4997.7  469.71
  4997.9  470.21  5000.5  472.44  5008.9  475.99  5055.4  475.90  5061.1  475.20
  5098.4  476.93  5134.9  477.40  5214.1  479.00  5280.4  480.33  5376.4  484.05
  5382.2  483.69  5403.7  484.38  5456.7  487.30  5529.9  489.81  5548.0  491.38
#Mann=8,-1,0
  4597.2    0.12       0  4811.5    0.16       0  4906.7    0.12       0
  4993.9    0.07       0  4997.9    0.12       0  5008.9    0.16       0
  5134.9    0.12       0  5214.1    0.05       0
Bank Sta=4993.9,4997.9
Exp/Cntr=0.3,0.1

Type RM Length L Ch R = 1,1364,167,167,167
BEGIN DESCRIPTION:
Chamblee Creek Trib A1364.43
END DESCRIPTION:
XS GIS Cut Line= 3
      2752931.32      6857008.36      2752614.59      6857353.56
      2752322.92      6857801.13
#Sta/Elev= 30
  4535.0  489.10  4540.4  488.46  4547.8  488.86  4604.5  486.86  4618.7  487.04
  4639.7  486.15  4724.8  484.86  4759.9  483.29  4781.5  483.35  4802.5  482.14
  4823.6  481.64  4901.7  476.32  4944.3  474.24  4972.6  475.18  4977.4  470.42
  4977.7  469.92  4981.2  469.92  4981.4  470.42  4986.4  473.56  4993.6  475.21
  5035.5  474.15  5122.9  473.89  5174.2  475.57  5231.5  476.49  5282.9  478.22
  5346.6  481.42  5439.8  484.44  5440.6  484.47  5485.1  486.74  5537.7  486.71
#Mann=6,-1,0
  4535.0    0.16       0  4977.4    0.07       0  4981.4    0.16       0
  5035.5    0.05       0  5439.8    0.16       0  5440.6    0.12       0
Bank Sta=4977.4,4981.4
Exp/Cntr=0.3,0.1

Type RM Length L Ch R = 1,1197,229,229,229
BEGIN DESCRIPTION:
Chamblee Creek Trib A1196.695
END DESCRIPTION:
XS GIS Cut Line= 3
      2752817.45      6856934.20      2752522.29      6857219.21
      2752139.71      6857510.57
#Sta/Elev= 30
  4589.7  485.10  4616.8  484.79  4623.8  485.24  4687.6  483.82  4701.7  482.96
  4737.0  482.72  4779.4  480.98  4821.9  482.00  4942.0  475.20  4956.1  475.11
  4963.3  474.27  4984.4  473.38  5000.0  473.65  5006.4  473.12  5018.5  468.86
  5018.7  468.36  5022.2  468.36  5022.5  468.86  5027.2  473.10  5033.5  474.19
  5091.2  472.16  5241.4  473.05  5262.2  473.96  5362.0  476.04  5384.8  475.52
  5397.6  476.46  5411.9  475.66  5426.4  477.52  5461.8  478.19  5480.9  479.25
#Mann=4,-1,0
  4589.7    0.16       0  5018.5    0.07       0  5022.5    0.16       0
  5091.2    0.05       0
Bank Sta=5018.5,5022.5
Exp/Cntr=0.3,0.1

Type RM Length L Ch R = 1,968,270,270,270
BEGIN DESCRIPTION:
Chamblee Creek Trib A968.01
END DESCRIPTION:
XS GIS Cut Line= 3
      2752713.91      6856912.36      2752347.11      6857081.86
      2752017.19      6857326.34
#Sta/Elev= 30
  4595.5  482.47  4615.2  481.90  4624.4  481.10  4652.8  480.52  4670.3  480.37
  4675.8  480.97  4736.4  480.59  4767.5  481.46  4835.6  479.62  4910.6  475.65
  4933.6  473.94  4962.0  472.97  4967.8  472.24  4984.9  472.53  4988.4  469.43
  4988.7  468.93  4992.2  468.93  4992.4  469.43  5003.0  469.77  5006.9  472.37
  5024.0  472.40  5042.3  471.74  5056.9  469.90  5071.6  471.11  5092.4  471.44
  5100.5  470.72  5121.6  470.57  5271.9  472.52  5357.5  475.25  5410.2  478.90
#Mann=4,-1,0
  4595.5    0.16       0  4988.4    0.07       0  4992.4    0.16       0
  5024.0    0.05       0
Bank Sta=4988.4,4992.4
Exp/Cntr=0.3,0.1

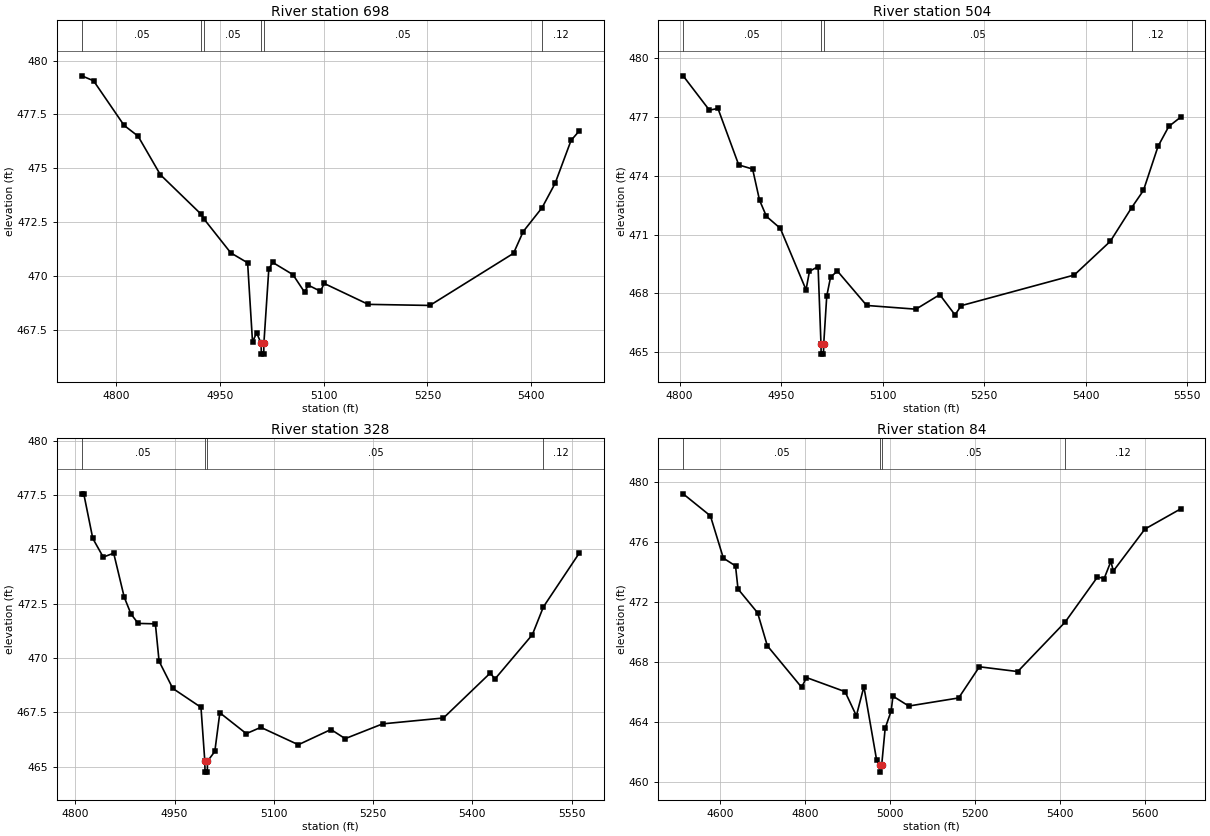
Type RM Length L Ch R = 1,698,194,194,194
BEGIN DESCRIPTION:
Chamblee Creek Trib A697.79
END DESCRIPTION:
XS GIS Cut Line= 3
      2752564.21      6856769.89      2752327.39      6856845.57
      2751899.69      6857040.64
#Sta/Elev= 30
  4750.6  479.29  4767.6  479.06  4811.7  476.99  4831.9  476.49  4864.1  474.70
  4923.2  472.86  4927.0  472.65  4965.9  471.07  4990.2  470.61  4997.3  466.93
  5003.2  467.36  5009.7  466.87  5010.0  466.37  5013.5  466.37  5013.7  466.87
  5020.8  470.31  5026.3  470.63  5055.7  470.06  5072.4  469.25  5077.9  469.57
  5095.4  469.29  5100.9  469.65  5164.5  468.68  5253.5  468.63  5374.4  471.05
  5388.4  472.06  5415.7  473.17  5434.5  474.30  5457.5  476.29  5469.3  476.73
#Mann=6,-1,0
  4750.6    0.05       0  4923.2    0.16       0  4927.0    0.05       0
  5009.7    0.05       0  5013.7    0.05       0  5415.7    0.12       0
Bank Sta=5009.7,5013.7
Exp/Cntr=0.3,0.1

Type RM Length L Ch R = 1,504,176,176,176
BEGIN DESCRIPTION:
Chamblee Creek Trib A504.03
END DESCRIPTION:
XS GIS Cut Line= 3
      2752466.27      6856627.26      2752271.45      6856669.30
      2751806.85      6856935.17
#Sta/Elev= 30
  4805.3  479.09  4844.1  477.34  4856.7  477.43  4887.4  474.55  4907.9  474.34
  4918.1  472.76  4928.3  471.93  4948.8  471.32  4986.8  468.19  4991.9  469.13
  5004.6  469.37  5008.9  465.41  5009.1  464.91  5012.6  464.91  5012.9  465.41
  5017.4  467.87  5023.1  468.84  5033.2  469.14  5076.4  467.39  5149.1  467.20
  5184.3  467.94  5206.8  466.91  5216.0  467.38  5382.9  468.94  5436.2  470.66
  5467.6  472.37  5485.1  473.25  5506.7  475.50  5522.5  476.51  5539.9  476.98
#Mann=4,-1,0
  4805.3    0.05       0  5008.9    0.05       0  5012.9    0.05       0
  5467.6    0.12       0
Bank Sta=5008.9,5012.9
Exp/Cntr=0.3,0.1

Type RM Length L Ch R = 1,328,244,244,244
BEGIN DESCRIPTION:
Chamblee Creek Trib A328.27
END DESCRIPTION:
XS GIS Cut Line= 4
      2752406.72      6856571.31      2752226.14      6856510.67
      2752161.11      6856528.15      2751800.76      6856865.72
#Sta/Elev= 30
  4809.9  477.55  4812.9  477.55  4826.5  475.50  4842.3  474.64  4858.1  474.82
  4874.0  472.80  4884.3  472.02  4895.1  471.59  4921.1  471.57  4926.7  469.85
  4947.4  468.60  4990.0  467.73  4995.8  465.25  4996.1  464.75  4999.6  464.75
  4999.8  465.25  5010.9  465.70  5018.5  467.48  5058.5  466.52  5080.4  466.81
  5137.1  466.01  5186.4  466.71  5207.9  466.29  5264.5  466.97  5356.4  467.24
  5427.2  469.31  5434.1  469.03  5490.7  471.07  5507.4  472.35  5561.5  474.82
#Mann=4,-1,0
  4809.9    0.05       0  4995.8    0.05       0  4999.8    0.05       0
  5507.4    0.12       0
Bank Sta=4995.8,4999.8
Exp/Cntr=0.3,0.1

Type RM Length L Ch R = 1,84,0,0,0
BEGIN DESCRIPTION:
Chamblee Creek Trib A83.722
END DESCRIPTION:
XS GIS Cut Line= 4
      2752468.24      6856566.99      2752116.27      6856366.24
      2752035.17      6856370.23      2751690.85      6856961.83
#Sta/Elev= 30
  4513.6  479.23  4577.8  477.76  4608.3  474.94  4636.9  474.42  4642.8  472.88
  4688.9  471.29  4711.8  469.09  4792.5  466.32  4804.0  466.97  4894.7  466.03
  4921.4  464.42  4939.1  466.36  4969.1  461.46  4977.1  461.16  4977.4  460.66
  4981.1  461.16  4989.2  463.59  5003.3  464.74  5007.5  465.73  5044.7  465.07
  5162.2  465.61  5211.0  467.69  5301.2  467.37  5412.5  470.66  5489.0  473.68
  5504.7  473.58  5520.5  474.72  5526.3  474.08  5600.7  476.88  5684.5  478.22
#Mann=4,-1,0
  4513.6    0.05       0  4977.1    0.05       0  4981.1    0.05       0
  5412.5    0.12       0
Bank Sta=4977.1,4981.1
Exp/Cntr=0.3,0.1

Chan Stop Cuts=-1