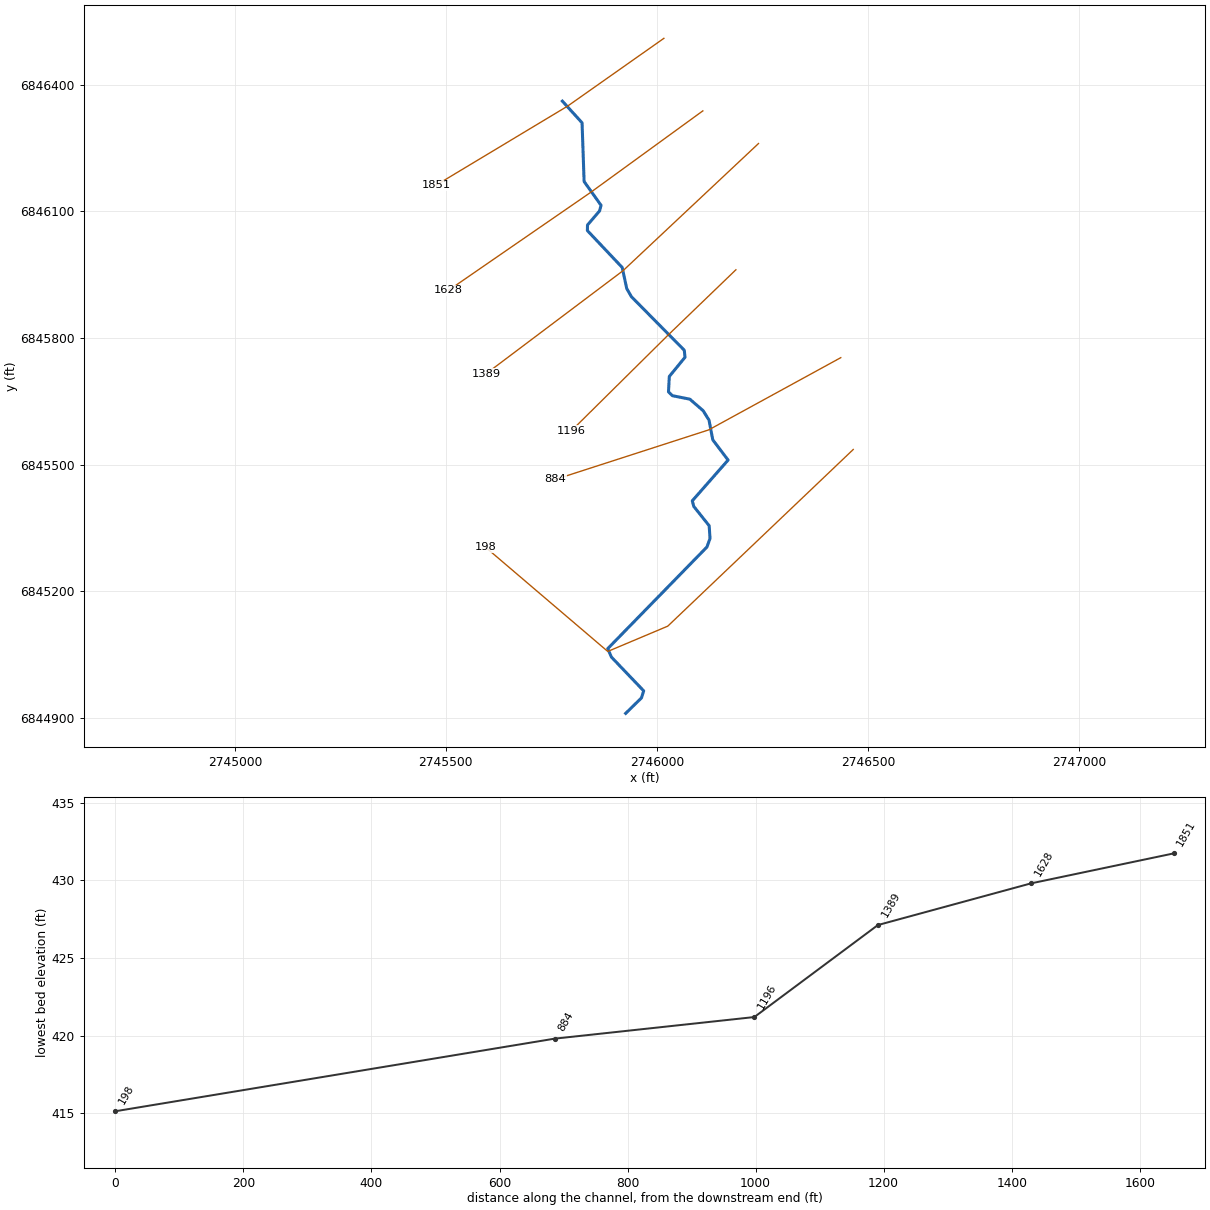
--- Chamblee Creek Trib B.prj (project) ---

Proj Title=Chamblee Creek Trib B Base Level Engineering
Current Plan=p01
Default Exp/Contr=0.3,0.1
English Units
Geom File=g01
Flow File=f01
Plan File=p01
BEGIN DESCRIPTION:
Chamblee Creek Trib B
END DESCRIPTION:

--- Chamblee Creek Trib B.p01 (plan) ---

Plan Title=Multiple Run
Short Identifier=Multiple
Geom File=g01
Flow File=f01
Subcritical Flow
K Sum by GR= 0
Std Step Tol= 0.01
Critical Tol= 0.01
Num of Std Step Trials= 20
Max Error Tol= 0.3
Flow Tol Ratio= 0.001
Split Flow NTrial= 30
Split Flow Tol= 0.02
Split Flow Ratio= 0.02
Log Output Level= 0
Friction Slope Method= 1
Unsteady Friction Slope Method= 2
Unsteady Bridges Friction Slope Method= 1
Parabolic Critical Depth
Global Vel Dist=  1 , 1 , 1
Global Log Level= 0
CheckData=True
Encroach Param= -1, 0, 0, 0
BEGIN DESCRIPTION:
Multiple Run
END DESCRIPTION:

--- Chamblee Creek Trib B.f01 (steady flow) ---

Flow Title=Multiple
Number of Profiles=7
Profile Names=10-year,25-year,50-year,1pct_min,100-year,1pct_plu,500-year
River Rch & RM= Chamblee Creek T,Reach-1,1851
     351     456     538     317     632    1261     871
Boundary for River Rch & Prof#=Chamblee Creek T,Reach-1,1
Up Type=0
Dn Type=3
Dn Slope=0.005
Boundary for River Rch & Prof#=Chamblee Creek T,Reach-1,2
Up Type=0
Dn Type=3
Dn Slope=0.005
Boundary for River Rch & Prof#=Chamblee Creek T,Reach-1,3
Up Type=0
Dn Type=3
Dn Slope=0.005
Boundary for River Rch & Prof#=Chamblee Creek T,Reach-1,4
Up Type=0
Dn Type=3
Dn Slope=0.005
Boundary for River Rch & Prof#=Chamblee Creek T,Reach-1,5
Up Type=0
Dn Type=3
Dn Slope=0.005
Boundary for River Rch & Prof#=Chamblee Creek T,Reach-1,6
Up Type=0
Dn Type=3
Dn Slope=0.005
Boundary for River Rch & Prof#=Chamblee Creek T,Reach-1,7
Up Type=0
Dn Type=3
Dn Slope=0.005

--- Chamblee Creek Trib B.g01 (geometry) ---

Geom Title=Existing Conditions

River Reach=Chamblee Creek T,Reach-1
Reach XY= 30
      2745776.00      6846361.00      2745822.70      6846309.63
      2745827.55      6846170.59      2745867.71      6846114.21
      2745864.15      6846100.94      2745835.60      6846067.66
      2745835.31      6846054.34      2745917.80      6845967.05
      2745928.53      6845917.05      2745939.63      6845897.79
      2746064.88      6845771.04      2746066.65      6845754.41
      2746029.44      6845708.99      2746027.46      6845672.36
      2746036.73      6845663.36      2746078.08      6845655.11
      2746109.43      6845628.01      2746123.48      6845605.53
      2746132.44      6845558.73      2746168.69      6845510.91
      2746083.85      6845414.41      2746087.40      6845401.13
      2746123.89      6845355.36      2746125.85      6845325.06
      2746118.50      6845304.95      2745883.60      6845064.33
      2745892.24      6845044.33      2745968.71      6844964.33
      2745963.48      6844947.67      2745926.00      6844911.00

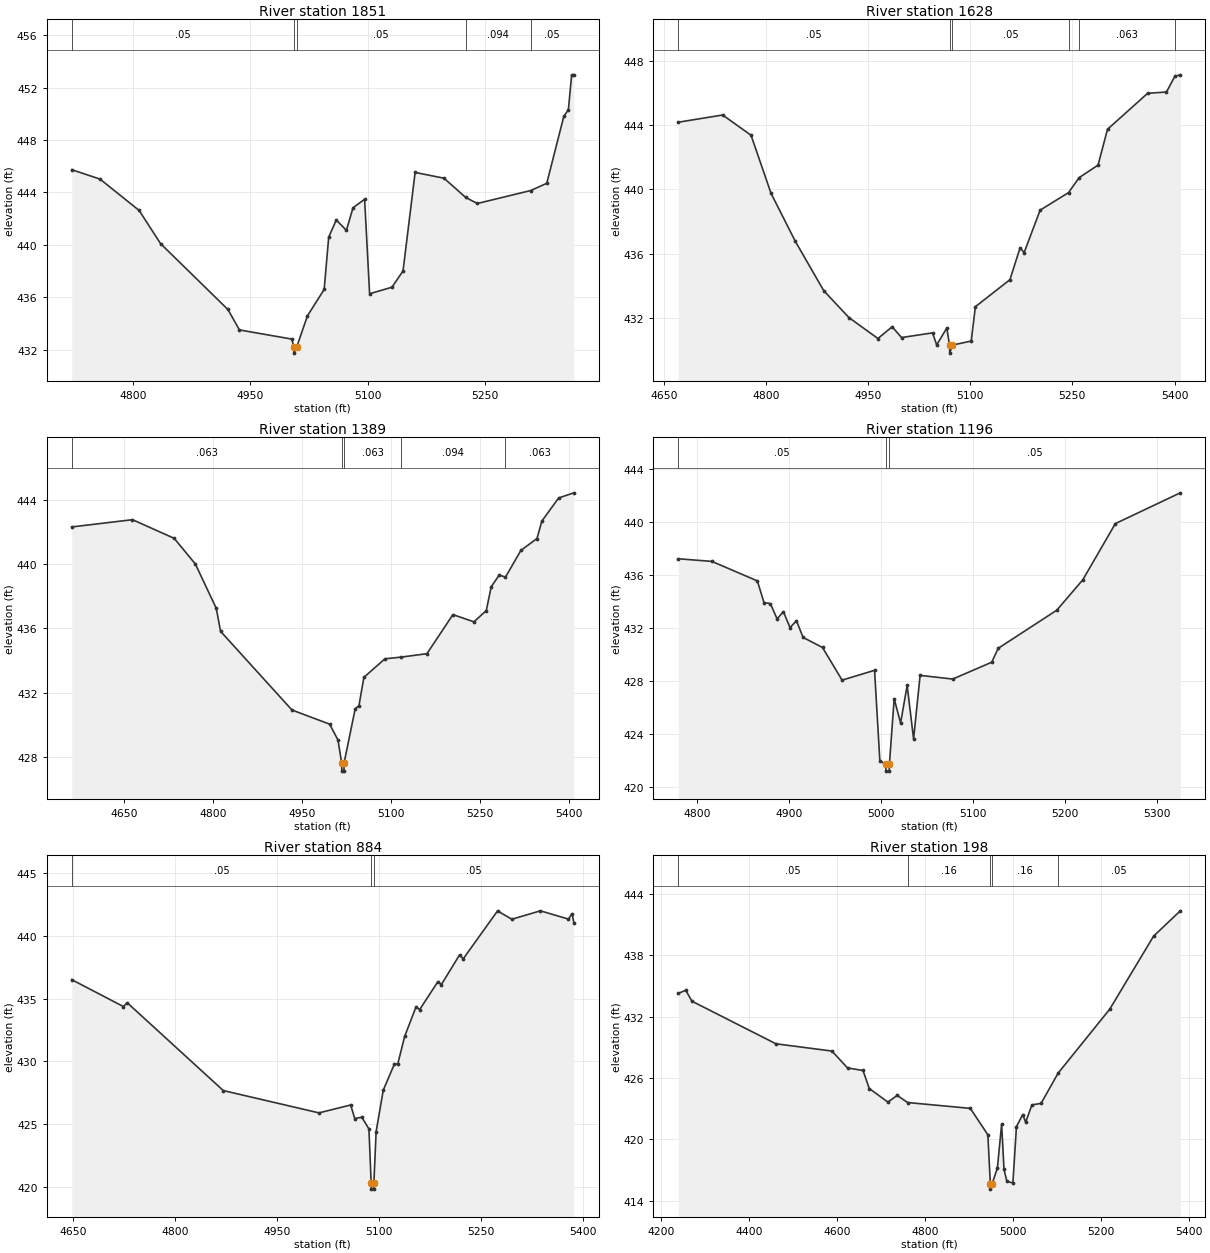
Type RM Length L Ch R = 1,1851,223,223,223
BEGIN DESCRIPTION:
Chamblee Creek Trib B1850.663
END DESCRIPTION:
XS GIS Cut Line= 3
      2746016.55      6846509.68      2745788.46      6846349.18
      2745476.28      6846161.62
#Sta/Elev= 30
  4721.1  445.73  4757.3  445.01  4807.4  442.62  4834.8  440.09  4921.1  435.06
  4935.9  433.50  5003.1  432.80  5005.4  432.23  5005.7  431.73  5009.4  432.23
  5023.0  434.58  5044.4  436.59  5050.2  440.58  5059.9  441.89  5072.9  441.10
  5081.3  442.82  5096.2  443.47  5102.6  436.26  5131.2  436.76  5145.4  438.00
  5160.9  445.52  5197.9  445.08  5225.7  443.61  5240.6  443.15  5309.0  444.14
  5329.5  444.69  5351.4  449.81  5357.2  450.30  5361.4  452.97  5364.2  452.97
#Mann=5,-1,0
  4721.1    0.05       0  5005.4    0.05       0  5009.4    0.05       0
  5225.7   0.094       0  5309.0    0.05       0
Bank Sta=5005.4,5009.4
Exp/Cntr=0.3,0.1

Type RM Length L Ch R = 1,1628,239,239,239
BEGIN DESCRIPTION:
Chamblee Creek Trib B1627.99
END DESCRIPTION:
XS GIS Cut Line= 3
      2746108.85      6846337.88      2745842.46      6846144.44
      2745506.50      6845912.98
#Sta/Elev= 30
  4671.3  444.17  4736.5  444.62  4778.2  443.36  4807.6  439.74  4843.2  436.76
  4884.9  433.69  4922.0  432.01  4964.5  430.71  4985.4  431.44  4999.2  430.77
  5044.7  431.06  5050.8  430.31  5065.6  431.36  5069.7  430.30  5070.0  429.80
  5073.7  430.30  5101.5  430.55  5107.6  432.69  5158.3  434.37  5173.2  436.35
  5179.2  436.06  5202.7  438.70  5244.4  439.79  5259.9  440.72  5287.7  441.50
  5301.6  443.73  5360.5  445.97  5388.2  446.05  5400.5  447.03  5408.5  447.12
#Mann=6,-1,0
  4671.3    0.05       0  5069.7    0.05       0  5073.7    0.05       0
  5244.4   0.094       0  5259.9   0.063       0  5400.5    0.05       0
Bank Sta=5069.7,5073.7
Exp/Cntr=0.3,0.1

Type RM Length L Ch R = 1,1389,193,193,193
BEGIN DESCRIPTION:
Chamblee Creek Trib B1388.75
END DESCRIPTION:
XS GIS Cut Line= 3
      2746240.71      6846260.53      2745919.61      6845959.25
      2745595.55      6845715.51
#Sta/Elev= 30
  4562.0  442.30  4664.3  442.75  4734.6  441.59  4770.3  439.99  4805.4  437.24
  4812.7  435.81  4932.9  430.92  4996.4  430.04  5010.4  429.06  5016.7  427.62
  5017.0  427.12  5020.5  427.12  5020.7  427.62  5039.5  431.00  5045.8  431.19
  5054.1  432.95  5089.5  434.10  5117.3  434.21  5160.3  434.42  5204.1  436.85
  5239.5  436.40  5260.3  437.10  5268.6  438.58  5282.1  439.31  5292.6  439.18
  5318.6  440.84  5345.7  441.58  5354.0  442.67  5382.2  444.10  5407.8  444.42
#Mann=5,-1,0
  4562.0   0.063       0  5016.7   0.063       0  5020.7   0.063       0
  5117.3   0.094       0  5292.6   0.063       0
Bank Sta=5016.7,5020.7
Exp/Cntr=0.3,0.1

Type RM Length L Ch R = 1,1196,312,312,312
BEGIN DESCRIPTION:
Mapping XS 357420ca
END DESCRIPTION:
XS GIS Cut Line= 3
      2746187.19      6845961.58      2746027.75      6845808.10
      2745797.10      6845579.99
#Sta/Elev= 30
  4779.9  437.21  4816.5  437.01  4865.9  435.54  4873.1  433.91  4880.1  433.83
  4887.3  432.68  4894.2  433.22  4901.4  432.02  4908.4  432.54  4915.6  431.28
  4936.7  430.52  4958.0  428.06  4993.3  428.80  4999.0  422.00  5005.4  421.70
  5005.7  421.20  5009.2  421.20  5009.4  421.70  5014.6  426.65  5021.6  424.83
  5028.7  427.66  5035.7  423.63  5042.8  428.42  5078.2  428.14  5120.6  429.41
  5127.7  430.46  5191.3  433.33  5219.6  435.62  5255.0  439.86  5325.6  442.18
#Mann=3,-1,0
  4779.9    0.05       0  5005.4    0.05       0  5009.4    0.05       0
Bank Sta=5005.4,5009.4
Exp/Cntr=0.3,0.1

Type RM Length L Ch R = 1,884,686,686,686
BEGIN DESCRIPTION:
Chamblee Creek Trib B883.81
END DESCRIPTION:
XS GIS Cut Line= 3
      2746435.69      6845753.42      2746122.55      6845582.26
      2745759.17      6845464.96
#Sta/Elev= 30
  4647.5  436.51  4723.4  434.37  4729.1  434.67  4870.4  427.67  5011.2  425.89
  5057.9  426.52  5063.8  425.44  5074.3  425.54  5084.7  424.61  5088.0  420.31
  5088.2  419.81  5091.7  419.81  5092.0  420.31  5095.3  424.39  5105.8  427.70
  5122.0  429.76  5127.2  429.80  5137.3  431.99  5154.0  434.34  5159.3  434.12
  5186.1  436.35  5191.3  436.12  5218.1  438.49  5223.4  438.17  5273.9  441.99
  5295.0  441.33  5337.0  442.00  5378.3  441.34  5383.6  441.77  5386.2  441.06
#Mann=3,-1,0
  4647.5    0.05       0  5088.0    0.05       0  5092.0    0.05       0
Bank Sta=5088,5092
Exp/Cntr=0.3,0.1

Type RM Length L Ch R = 1,198,0,0,0
BEGIN DESCRIPTION:
Chamblee Creek Trib B197.764
END DESCRIPTION:
XS GIS Cut Line= 4
      2746465.18      6845535.94      2746025.73      6845117.55
      2745883.60      6845057.67      2745593.83      6845304.58
#Sta/Elev= 30
  4239.0  434.26  4256.0  434.57  4270.2  433.50  4461.1  429.34  4588.5  428.63
  4624.0  426.98  4659.2  426.73  4673.4  424.97  4715.9  423.64  4736.9  424.30
  4760.6  423.60  4903.2  423.03  4943.1  420.45  4948.7  415.64  4948.9  415.14
  4952.7  415.64  4964.8  417.22  4974.4  421.49  4979.8  417.06  4986.5  415.89
  5000.0  415.75  5008.1  421.25  5022.4  422.42  5029.0  421.68  5043.3  423.37
  5064.1  423.52  5103.0  426.48  5220.2  432.72  5320.0  439.86  5380.7  442.33
#Mann=5,-1,0
  4239.0    0.05       0  4760.6    0.16       0  4948.7    0.07       0
  4952.7    0.16       0  5103.0    0.05       0
Bank Sta=4948.7,4952.7
Exp/Cntr=0.3,0.1

Chan Stop Cuts=-1