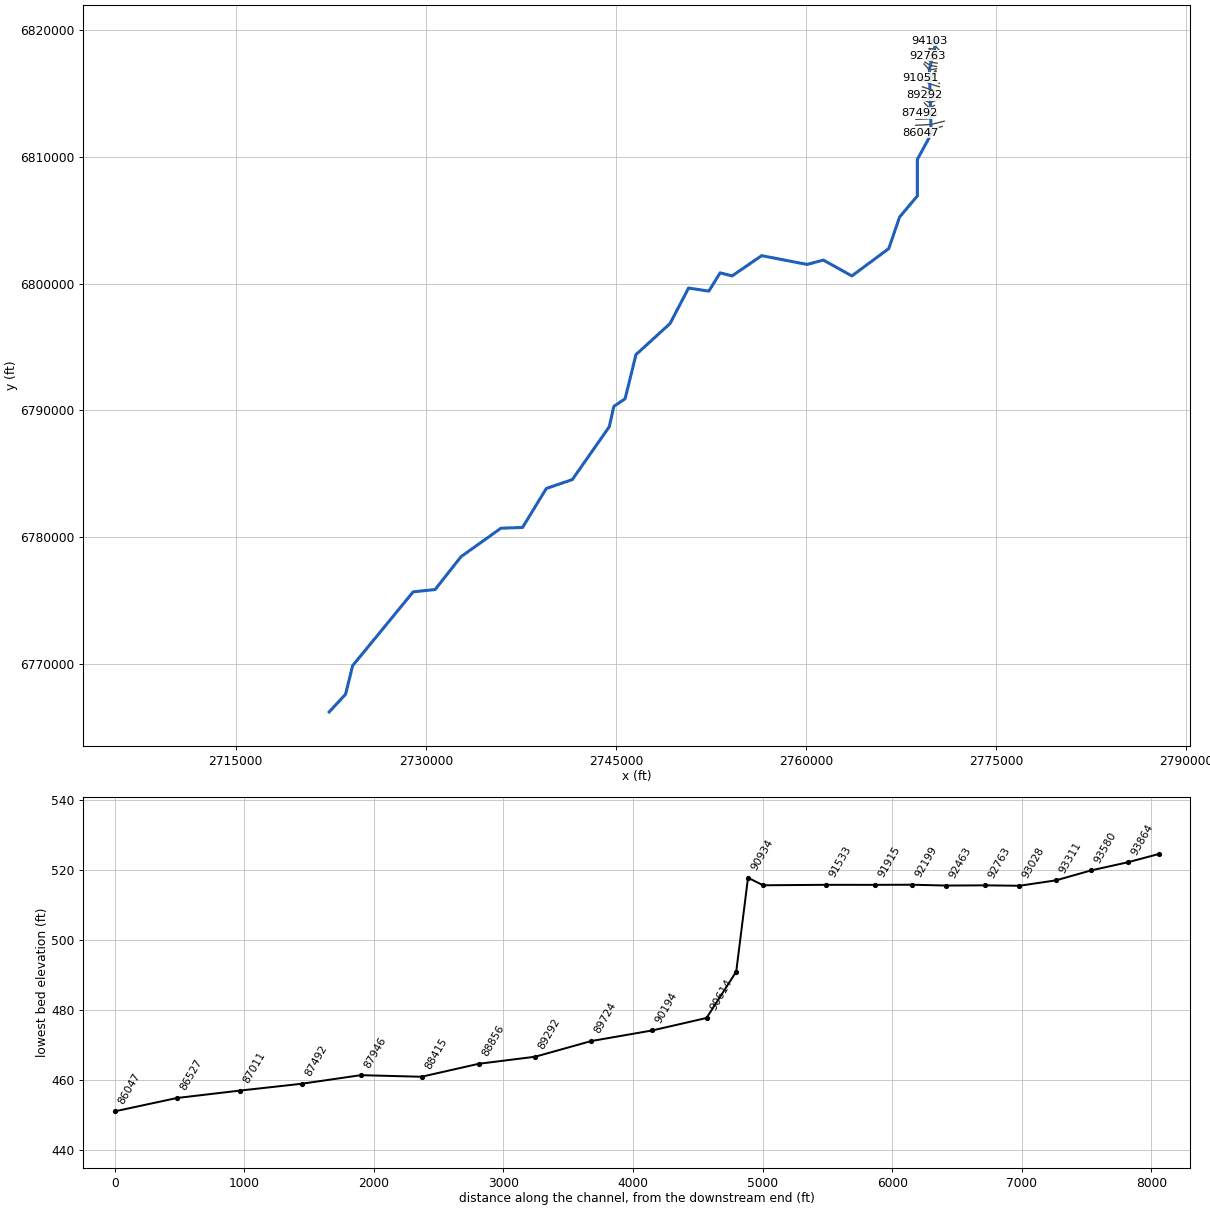
--- Clear Creek.prj (project) ---

Proj Title=Clear Creek Base Level Engineering
Current Plan=p01
Default Exp/Contr=0.3,0.1
English Units
Geom File=g01
Flow File=f01
Plan File=p01
Y Axis Title=Elevation
X Axis Title(PF)=Main Channel Distance
X Axis Title(XS)=Station
BEGIN DESCRIPTION:
Clear Creek
END DESCRIPTION:
DSS Export Rating Curves= 0
DSS Export Rating Curve Sorted= 0
DSS Export Volume Flow Curves= 0
DXF OffsetX= 0
DXF OffsetY= 0
DXF ScaleX= 1
DXF ScaleY= 10

--- Clear Creek.p01 (plan) ---

Plan Title=Multiple Run
Program Version=4.10
Short Identifier=Multiple
Geom File=g01
Flow File=f01
Subcritical Flow
K Sum by GR= 0
Std Step Tol= 0.01
Critical Tol= 0.01
Num of Std Step Trials= 20
Max Error Tol= 0.3
Flow Tol Ratio= 0.001
Split Flow NTrial= 30
Split Flow Tol= 0.02
Split Flow Ratio= 0.02
Log Output Level= 0
Friction Slope Method= 1
Unsteady Friction Slope Method= 2
Unsteady Bridges Friction Slope Method= 1
Parabolic Critical Depth
Global Vel Dist= 1 , 1 , 1
Global Log Level= 0
CheckData=True
Encroach Param=-1 ,0,0, 0
BEGIN DESCRIPTION:
Multiple Run
END DESCRIPTION:
Computation Interval=1HOUR
Output Interval=1HOUR
Run HTab= 0
Run UNet= 0
Run PostProcess= 0
Run WQNet= 0
UNET Theta= 1
UNET Theta Warmup= 1
UNET ZTol= 0.02
UNET ZSATol= 0.05
UNET MxIter= 20
UNET MaxInSteps= 0
UNET DtIC= 0
UNET DtMin= 0
UNET MaxCRTS= 20
UNET WFStab= 2
UNET SFStab= 1
UNET WFX= 1
UNET SFX= 1
UNET DSS MLevel= 4
UNET DZMax Abort= 100
UNET Convert EG Bridges= 0
UNET Use Existing IB Tables=-1
UNET Froude Reduction=False
UNET Froude Limit= 1
UNET Froude Power= 10
UNET Time Slicing=0,0, 5
UNET Junction Losses=0
Instantaneous Interval=1HOUR
Write IC File= 0
Write IC File at Sim End=0
Echo Input=False
Echo Parameters=False
Echo Output=False
Write Detailed= 0
WQ AD Non Conservative
WQ ULTIMATE=-1
WQ Max Comp Step=1HOUR
WQ Output Interval=15MIN
WQ Output Selected Increments= 0
WQ Output face flow=0
WQ Output face velocity=0
WQ Output face area=0
WQ Output face dispersion=0
WQ Output cell volume=0
WQ Output cell surface area=0
WQ Output cell continuity=0
WQ Output cumulative cell continuity=0
WQ Output face conc=0
WQ Output face dconc_dx=0
WQ Output face courant=0
WQ Output face peclet=0
WQ Output face adv mass=0
WQ Output face disp mass=0
WQ Output cell mass=0
WQ Output cell source sink temp=0
WQ Output cell source sink nsm=0
WQ Output MaxMinRange=-1
WQ Daily Max Min Mean=-1
WQ Daily Range=0
WQ Daily Time=0
WQ Create Restart=0
WQ Fixed Restart=0
WQ System Summary=0
WQ Use Fixed Temperature=0
Sorting and Armoring Iterations= 10
XS Update Threshold= 0.02
Hydraulics Update Threshold= 0.02
Energy Slope Method= 1
Volume Change Method= 0
XS Weighting Method= 0
Number of US Weighted Cross Sections= 1
Number of DS Weighted Cross Sections= 1
Upstream XS Weight=0.25
Main XS Weight=0.5
Downstream XS Weight=0.25
Number of DS XS's Weighted with US Boundary= 1
Upstream Boundary Weight= 1
Weight of XSs Associated with US Boundary= 0
Number of US XS's Weighted with DS Boundary= 1
Downstream Boundary Weight= 0.5
Weight of XSs Associated with DS Boundary= 0.5
Sediment Output Level= 4
Mass or Volume Output= 0
Output Increment Type= 1
Profile and TS Output Increment= 10
XS Output Flag= 0
XS Output Increment= 10
Disregard all LS=0
Disregard all Conn=0
Disregard all Breaches=0
Disregard all Pumps=0

--- Clear Creek.f01 (steady flow) ---

Flow Title=Multiple
Number of Profiles=7
Profile Names=10-year,25-year,50-year,1pct_min,100-year,1pct_plu,500-year
River Rch & RM= Clear Creek,Reach-1,94103
     420     561     676     406     810    1617    1165
River Rch & RM= Clear Creek,Reach-1,91533
     691     950    1166     712    1420    2834    2112
River Rch & RM= Clear Creek,Reach-1,90614
    1052    1481    1849    1146    2287    4563    3509
River Rch & RM= Clear Creek,Reach-1,85576
    1420    2030    2556    1598    3188    6361    4974
River Rch & RM= Clear Creek,Reach-1,83305
    1561    2232    2812    1757    3506    6996    5469
River Rch & RM= Clear Creek,Reach-1,79058
    2270    3278    4157    2610    5208   10391    8199
River Rch & RM= Clear Creek,Reach-1,72268
    2853    4154    5296    3340    6665   13298   10593
River Rch & RM= Clear Creek,Reach-1,70028
    3286    4788    6107    3852    7685   15334   12209
River Rch & RM= Clear Creek,Reach-1,63779
    3417    4974    6340    3995    7971   15904   12640
River Rch & RM= Clear Creek,Reach-1,60118
    3981    5811    7421    4682    9341   18638   14849
River Rch & RM= Clear Creek,Reach-1,56308
    4087    5969    7624    4811    9599   19152   15264
River Rch & RM= Clear Creek,Reach-1,51994
    4291    6271    8015    5060   10096   20144   16067
River Rch & RM= Clear Creek,Reach-1,50421
    4491    6573    8410    5314   10602   21154   16904
River Rch & RM= Clear Creek,Reach-1,47712
    4887    7167    9181    5807   11586   23118   18510
River Rch & RM= Clear Creek,Reach-1,44891
    5110    7479    9568    6043   12057   24056   19198
River Rch & RM= Clear Creek,Reach-1,37310
    4970    7280    9317    5886   11744   23432   18716
River Rch & RM= Clear Creek,Reach-1,36760
    4740    6872    8732    5475   10923   21795   17147
River Rch & RM= Clear Creek,Reach-1,32446
    4945    7173    9116    5716   11404   22754   17900
River Rch & RM= Clear Creek,Reach-1,30287
    4944    7160    9090    5692   11357   22661   17784
River Rch & RM= Clear Creek,Reach-1,26337
    5123    7409    9397    5877   11726   23397   18310
River Rch & RM= Clear Creek,Reach-1,21281
    5049    7282    9219    5754   11481   22907   17854
River Rch & RM= Clear Creek,Reach-1,17330
    5721    8260   10463    6531   13031   26000   20257
River Rch & RM= Clear Creek,Reach-1,11415
    5876    8470   10717    6679   13327   26591   20653
River Rch & RM= Clear Creek,Reach-1,6206
    5873    8456   10692    6659   13287   26511   20560
River Rch & RM= Clear Creek,Reach-1,3943
    5951    8555   10803    6719   13405   26747   20682
Boundary for River Rch & Prof#=Clear Creek,Reach-1,1
Up Type=0
Dn Type=3
Dn Slope=0.001
Boundary for River Rch & Prof#=Clear Creek,Reach-1,2
Up Type=0
Dn Type=3
Dn Slope=0.001
Boundary for River Rch & Prof#=Clear Creek,Reach-1,3
Up Type=0
Dn Type=3
Dn Slope=0.001
Boundary for River Rch & Prof#=Clear Creek,Reach-1,4
Up Type=0
Dn Type=3
Dn Slope=0.001
Boundary for River Rch & Prof#=Clear Creek,Reach-1,5
Up Type=0
Dn Type=3
Dn Slope=0.001
Boundary for River Rch & Prof#=Clear Creek,Reach-1,6
Up Type=0
Dn Type=3
Dn Slope=0.001
Boundary for River Rch & Prof#=Clear Creek,Reach-1,7
Up Type=0
Dn Type=3
Dn Slope=0.001

--- Clear Creek.g01 (geometry) ---

Geom Title=Existing Conditions

River Reach=Clear Creek,Reach-1
Reach XY= 30
      2770326.00      6819361.00      2769726.02      6816890.99
      2769868.77      6811807.55      2768776.95      6809800.51
      2768774.37      6806917.04      2767381.46      6805263.47
      2766521.20      6802766.56      2763615.32      6800611.75
      2761365.41      6801860.11      2760075.70      6801518.25
      2756496.03      6802210.94      2754168.09      6800613.92
      2753219.54      6800853.26      2752326.00      6799411.00
      2750731.28      6799656.10      2749265.48      6796851.21
      2746579.09      6794402.69      2745722.93      6790919.30
      2744833.52      6790317.04      2744470.92      6788708.69
      2741562.38      6784547.78      2739505.84      6783841.40
      2737632.17      6780768.86      2735927.46      6780707.46
      2732776.00      6778461.00      2730732.19      6775868.82
      2729002.47      6775688.14      2724226.00      6769861.00
      2723670.54      6767608.55      2722376.00      6766211.00

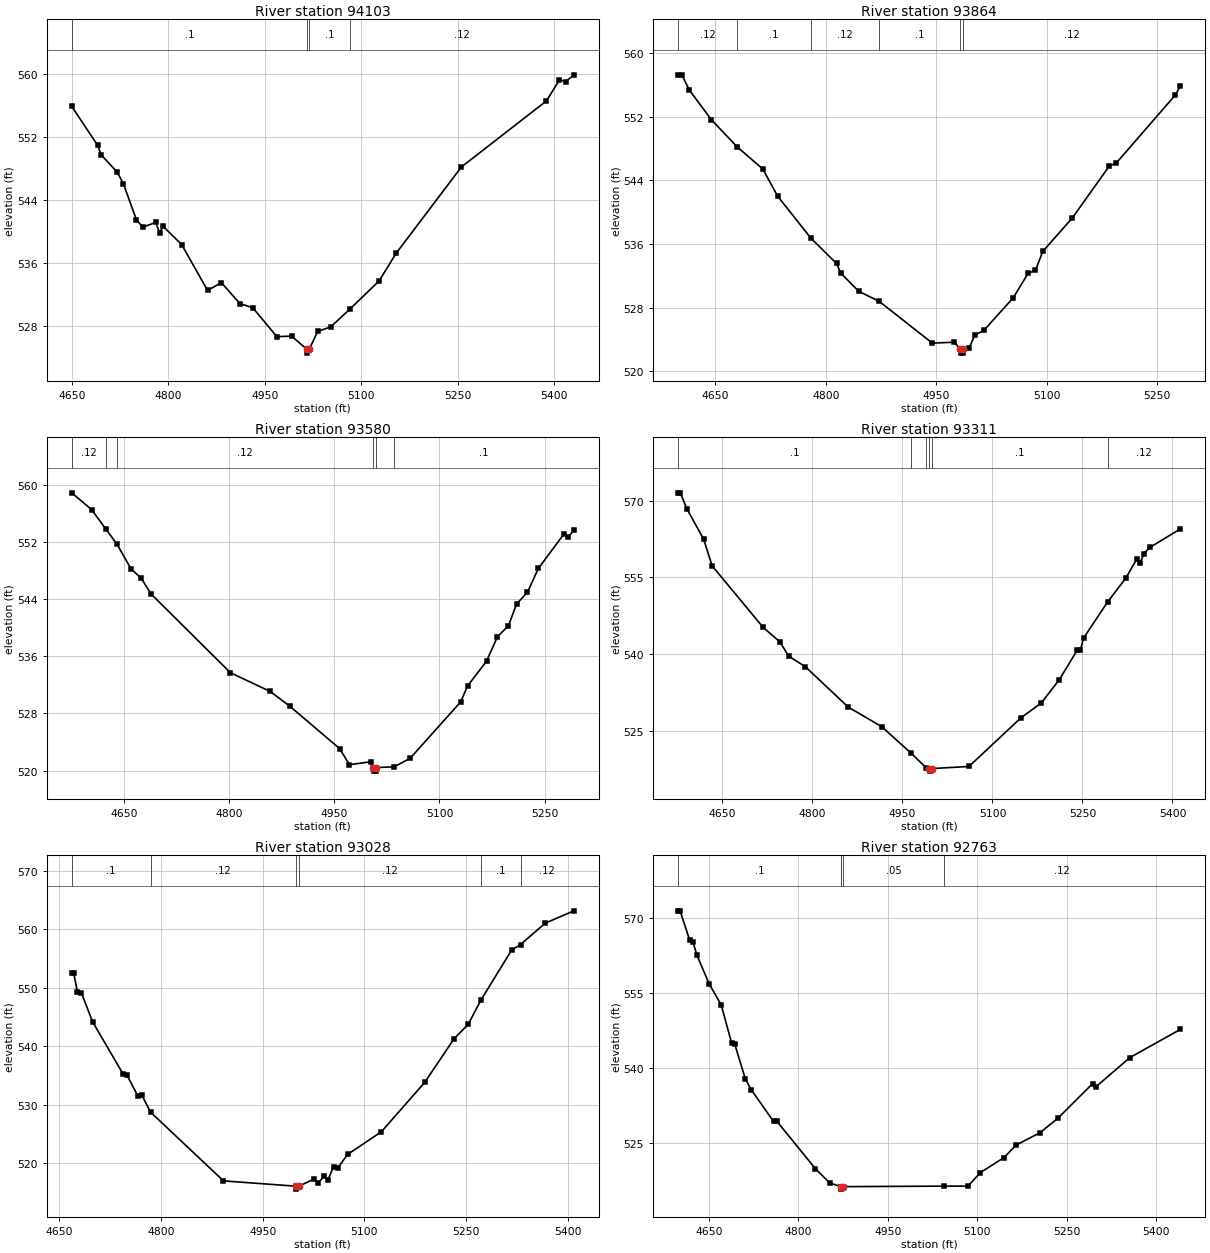
Type RM Length L Ch R = 1,94103,239,239,239
BEGIN DESCRIPTION:
Clear Creek 163.0
END DESCRIPTION:
XS GIS Cut Line= 3
      2770526.03      6819211.00      2770177.62      6819249.18
      2769753.97      6819170.45
#Sta/Elev= 30
  4649.5  555.84  4689.8  550.92  4695.1  549.73  4719.9  547.56  4730.0  546.03
  4750.1  541.50  4760.2  540.57  4780.3  541.17  4786.3  539.79  4791.3  540.70
  4820.5  538.37  4860.8  532.57  4882.5  533.54  4911.1  530.90  4931.2  530.37
  4968.6  526.72  4991.6  526.78  5015.2  525.13  5015.4  524.63  5019.2  525.13
  5032.2  527.37  5052.5  527.95  5082.7  530.23  5127.8  533.76  5154.2  537.25
  5255.9  548.18  5388.2  556.54  5408.5  559.19  5418.7  558.99  5430.9  559.84
#Mann=4,-1,0
  4649.5     0.1       0  5015.2    0.07       0  5019.2     0.1       0
  5082.7    0.12       0
Bank Sta=5015.2,5019.2
Exp/Cntr=0.3,0.1

Type RM Length L Ch R = 1,93864,284,284,284
BEGIN DESCRIPTION:
Clear Creek 162.0
END DESCRIPTION:
XS GIS Cut Line= 3
      2770580.86      6819022.03      2770176.00      6819011.00
      2769899.31      6819009.48
#Sta/Elev= 30
  4599.5  557.25  4604.4  557.25  4614.4  555.36  4644.4  551.62  4679.2  548.22
  4714.4  545.40  4734.4  542.01  4779.7  536.71  4814.4  533.54  4820.2  532.33
  4844.5  530.04  4872.2  528.79  4944.5  523.53  4974.5  523.64  4982.5  522.77
  4982.8  522.27  4986.3  522.27  4986.5  522.77  4994.5  522.91  5002.0  524.52
  5014.5  525.13  5054.5  529.24  5074.5  532.30  5084.5  532.67  5094.5  535.06
  5134.5  539.25  5184.5  545.75  5194.5  546.19  5274.5  554.72  5281.2  555.84
#Mann=6,-1,0
  4599.5    0.12       0  4679.2     0.1       0  4779.7    0.12       0
  4872.2     0.1       0  4982.5    0.07       0  4986.5    0.12       0
Bank Sta=4982.5,4986.5
Exp/Cntr=0.3,0.1

Type RM Length L Ch R = 1,93580,269,269,269
BEGIN DESCRIPTION:
Clear Creek 161.0
END DESCRIPTION:
XS GIS Cut Line= 3
      2770475.97      6818461.03      2770176.00      6818761.00
      2769925.97      6818911.02
#Sta/Elev= 30
  4575.8  558.86  4604.0  556.52  4624.5  553.78  4640.3  551.67  4660.6  548.18
  4674.7  546.94  4688.9  544.71  4802.0  533.70  4858.6  531.09  4886.9  529.00
  4957.6  523.10  4971.7  520.84  5002.9  521.26  5005.8  520.44  5006.0  519.94
  5009.5  519.94  5009.8  520.44  5035.5  520.54  5058.3  521.74  5130.2  529.62
  5140.0  531.84  5167.2  535.33  5182.7  538.74  5198.3  540.26  5209.9  543.30
  5225.5  544.96  5241.0  548.29  5278.0  553.17  5283.8  552.69  5291.6  553.64
#Mann=6,-1,0
  4575.8    0.12       0  4624.5     0.1       0  4640.3    0.12       0
  5005.8    0.07       0  5009.8    0.12       0  5035.5     0.1       0
Bank Sta=5005.8,5009.8
Exp/Cntr=0.3,0.1

Type RM Length L Ch R = 1,93311,283,283,283
BEGIN DESCRIPTION:
Clear Creek 160.0
END DESCRIPTION:
XS GIS Cut Line= 3
      2770425.99      6818211.01      2770126.00      6818511.00
      2769715.58      6818552.96
#Sta/Elev= 30
  4576.3  571.50  4579.8  571.50  4590.4  568.43  4618.7  562.43  4632.8  557.23
  4717.7  545.22  4746.0  542.35  4760.1  539.62  4788.4  537.50  4859.1  529.68
  4915.7  525.78  4964.6  520.61  4989.9  517.73  4995.0  517.62  4995.3  517.12
  4999.0  517.62  5060.9  518.03  5147.2  527.51  5181.5  530.45  5211.6  535.02
  5241.6  540.80  5246.6  540.79  5251.8  543.10  5292.3  550.24  5322.2  554.82
  5341.0  558.65  5346.0  557.71  5352.4  559.63  5362.4  560.84  5413.1  564.44
#Mann=6,-1,0
  4576.3     0.1       0  4964.6    0.12       0  4989.9     0.1       0
  4995.0    0.07       0  4999.0     0.1       0  5292.3    0.12       0
Bank Sta=4995,4999
Exp/Cntr=0.3,0.1

Type RM Length L Ch R = 1,93028,265,265,265
BEGIN DESCRIPTION:
Clear Creek 159.0
END DESCRIPTION:
XS GIS Cut Line= 3
      2770326.01      6818111.00      2770026.00      6818261.00
      2769710.57      6818514.36
#Sta/Elev= 30
  4668.7  552.57  4671.5  552.57  4677.1  549.27  4682.7  549.20  4699.5  544.17
  4744.2  535.30  4749.8  535.12  4766.5  531.42  4772.1  531.62  4784.8  528.74
  4892.3  516.98  4999.3  516.07  4999.6  515.57  5003.3  516.07  5025.7  517.29
  5032.1  516.61  5040.1  517.77  5046.5  517.19  5054.5  519.44  5060.9  519.22
  5075.3  521.51  5124.9  525.37  5188.9  533.83  5232.1  541.29  5252.9  543.74
  5271.9  547.94  5316.9  556.45  5330.1  557.41  5366.5  561.07  5408.7  563.18
#Mann=6,-1,0
  4668.7     0.1       0  4784.8    0.12       0  4999.3    0.07       0
  5003.3    0.12       0  5271.9     0.1       0  5330.1    0.12       0
Bank Sta=4999.3,5003.3
Exp/Cntr=0.3,0.1

Type RM Length L Ch R = 1,92763,300,300,300
BEGIN DESCRIPTION:
Clear Creek 158.0
END DESCRIPTION:
XS GIS Cut Line= 3
      2770377.20      6817952.79      2769976.00      6818011.00
      2769541.70      6817973.71
#Sta/Elev= 30
  4598.9  571.43  4602.0  571.43  4618.3  565.49  4623.3  565.27  4630.4  562.49
  4650.6  556.84  4670.8  552.61  4688.4  544.94  4693.5  544.78  4711.3  537.76
  4721.4  535.58  4758.6  529.24  4763.7  529.35  4828.8  519.77  4852.7  516.94
  4870.8  516.20  4870.9  516.19  4871.2  515.69  4874.9  516.19  5044.7  516.29
  5084.6  516.29  5104.7  518.97  5144.8  522.01  5164.9  524.50  5205.0  526.98
  5235.1  529.90  5293.4  536.84  5298.4  536.14  5355.6  542.03  5440.2  547.67
#Mann=5,-1,0
  4598.9     0.1       0  4870.8    0.05       0  4870.9    0.03       0
  4874.9    0.05       0  5044.7    0.12       0
Bank Sta=4870.9,4874.9
Exp/Cntr=0.3,0.1

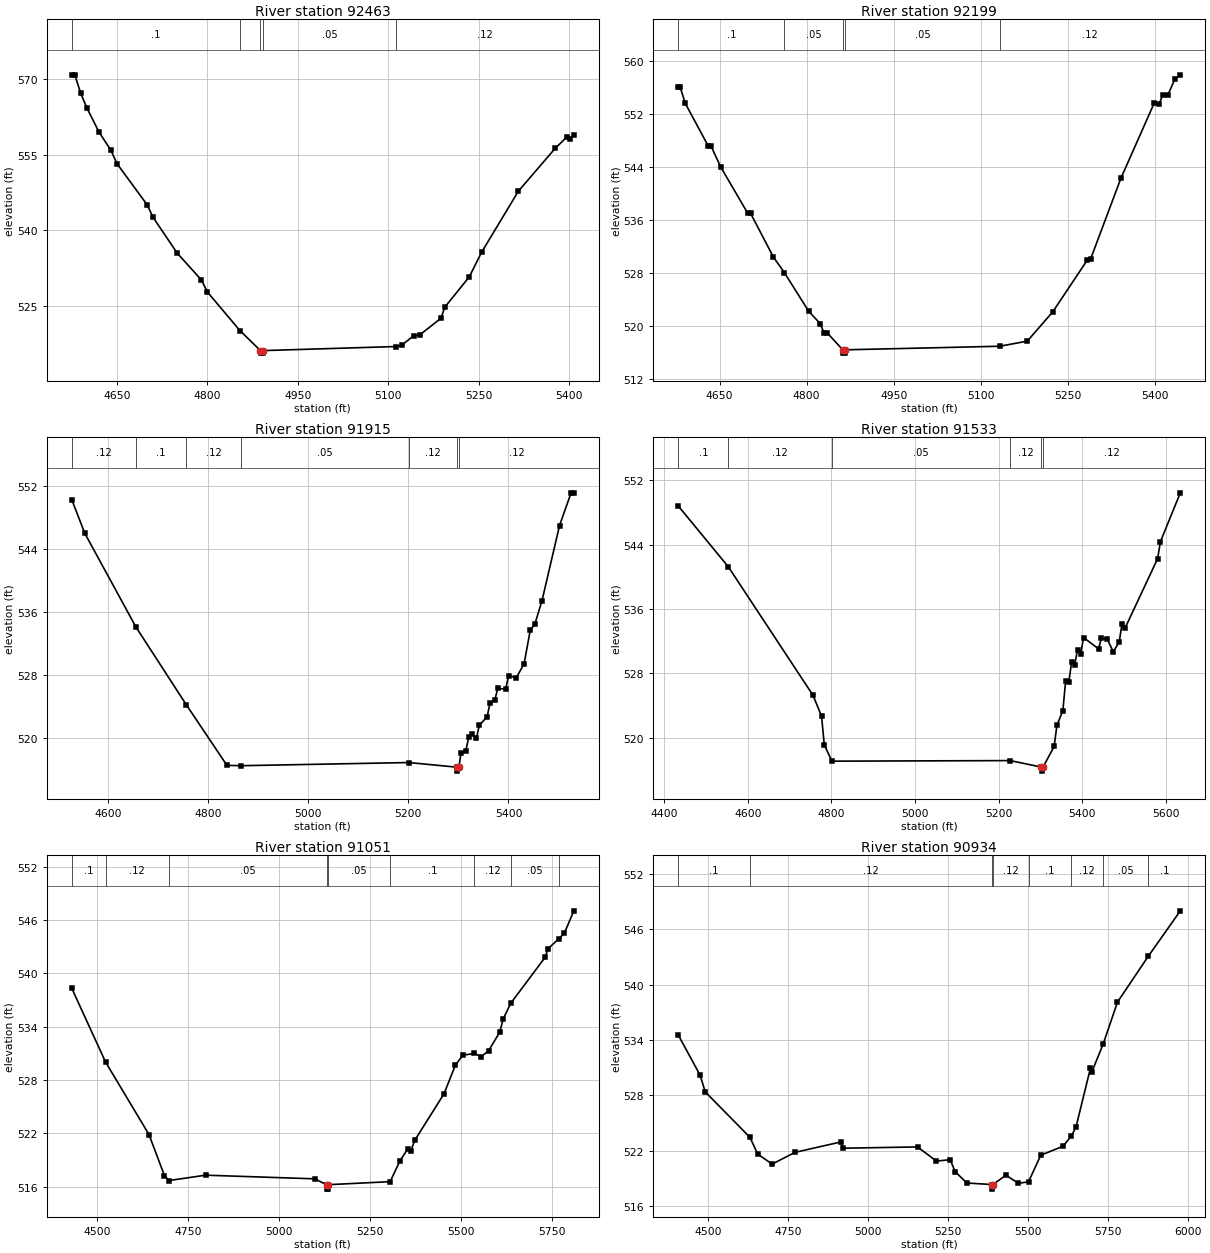
Type RM Length L Ch R = 1,92463,264,264,264
BEGIN DESCRIPTION:
Clear Creek 157.0
END DESCRIPTION:
XS GIS Cut Line= 3
      2770400.89      6817710.91      2769976.00      6817711.00
      2769575.63      6817787.51
#Sta/Elev= 30
  4575.2  570.89  4580.2  570.89  4590.1  567.20  4600.1  564.35  4620.1  559.58
  4640.1  555.91  4650.1  553.26  4700.1  545.10  4710.1  542.58  4750.1  535.47
  4790.1  530.17  4800.1  527.77  4853.9  520.12  4888.1  516.13  4888.3  515.63
  4891.8  515.63  4892.1  516.13  5112.8  516.94  5122.3  517.22  5142.6  519.11
  5152.8  519.30  5187.5  522.57  5193.5  524.72  5234.3  530.77  5254.6  535.63
  5315.7  547.78  5376.8  556.30  5395.9  558.51  5400.9  558.16  5407.7  558.95
#Mann=5,-1,0
  4575.2     0.1       0  4853.9    0.05       0  4888.1    0.03       0
  4892.1    0.05       0  5112.8    0.12       0
Bank Sta=4888.1,4892.1
Exp/Cntr=0.3,0.1

Type RM Length L Ch R = 1,92199,284,284,284
BEGIN DESCRIPTION:
Clear Creek 156.0
END DESCRIPTION:
XS GIS Cut Line= 3
      2770338.02      6817397.63      2769926.00      6817461.00
      2769537.09      6817682.64
#Sta/Elev= 30
  4578.9  556.03  4582.4  556.03  4591.1  553.61  4630.2  547.24  4635.3  547.18
  4651.8  544.05  4698.5  537.02  4703.6  536.98  4742.8  530.39  4761.6  528.05
  4803.5  522.20  4823.8  520.29  4830.1  518.84  4835.1  518.96  4862.2  516.37
  4862.5  515.87  4866.0  515.87  4866.2  516.37  5132.3  516.91  5179.9  517.68
  5224.1  522.15  5283.2  529.93  5288.9  530.09  5341.1  542.30  5398.6  553.70
  5407.1  553.56  5412.8  554.83  5421.6  554.83  5434.4  557.35  5443.4  557.94
#Mann=5,-1,0
  4578.9     0.1       0  4761.6    0.05       0  4862.2    0.03       0
  4866.2    0.05       0  5132.3    0.12       0
Bank Sta=4862.2,4866.2
Exp/Cntr=0.3,0.1

Type RM Length L Ch R = 1,91915,382,382,382
BEGIN DESCRIPTION:
Clear Creek 155.0
END DESCRIPTION:
XS GIS Cut Line= 3
      2770291.65      6817133.24      2769826.00      6817211.00
      2769371.47      6817484.56
#Sta/Elev= 30
  4527.9  550.31  4553.9  546.04  4655.8  534.16  4756.5  524.27  4837.8  516.56
  4866.7  516.52  5201.0  516.92  5297.1  516.33  5297.4  515.83  5301.1  516.33
  5304.9  518.10  5314.6  518.37  5320.5  520.11  5326.8  520.55  5336.0  520.03
  5341.8  521.66  5357.4  522.74  5363.2  524.52  5372.9  524.91  5378.7  526.38
  5394.3  526.20  5400.1  527.95  5415.6  527.69  5431.2  529.48  5443.5  533.75
  5452.5  534.48  5466.9  537.48  5501.9  547.02  5525.0  551.18  5530.5  551.18
#Mann=7,-1,0
  4527.9    0.12       0  4655.8     0.1       0  4756.5    0.12       0
  4866.7    0.05       0  5201.0    0.12       0  5297.1    0.03       0
  5301.1    0.12       0
Bank Sta=5297.1,5301.1
Exp/Cntr=0.3,0.1

Type RM Length L Ch R = 1,91533,482,482,482
BEGIN DESCRIPTION:
Clear Creek 154.0
END DESCRIPTION:
XS GIS Cut Line= 3
      2770284.39      6816952.96      2769726.00      6816861.00
      2769305.13      6817336.75
#Sta/Elev= 30
  4433.5  548.83  4553.3  541.26  4756.2  525.25  4776.4  522.66  4782.8  519.13
  4801.1  517.08  5227.9  517.15  5302.3  516.34  5302.6  515.84  5306.3  516.34
  5332.8  518.92  5339.4  521.53  5353.6  523.36  5360.3  527.07  5367.9  526.92
  5374.5  529.38  5382.1  529.08  5388.8  530.97  5396.3  530.39  5403.0  532.46
  5439.0  531.05  5445.7  532.37  5459.9  532.25  5474.1  530.71  5488.3  531.86
  5495.0  534.13  5502.5  533.64  5580.3  542.27  5587.0  544.38  5634.6  550.46
#Mann=6,-1,0
  4433.5     0.1       0  4553.3    0.12       0  4801.1    0.05       0
  5227.9    0.12       0  5302.3    0.03       0  5306.3    0.12       0
Bank Sta=5302.3,5306.3
Exp/Cntr=0.3,0.1

Type RM Length L Ch R = 1,91051,117,117,117
BEGIN DESCRIPTION:
Clear Creek 153.0
END DESCRIPTION:
XS GIS Cut Line= 3
      2770226.01      6816811.01      2769826.00      6816411.00
      2769026.05      6816261.01
#Sta/Elev= 30
  4429.6  538.32  4522.3  530.03  4641.8  521.85  4684.2  517.24  4696.9  516.68
  4797.3  517.28  5097.0  516.87  5129.8  516.21  5130.1  515.71  5133.6  515.71
  5133.8  516.21  5304.5  516.55  5331.1  518.87  5352.3  520.20  5361.6  520.04
  5371.8  521.19  5452.3  526.43  5483.7  529.67  5504.0  530.79  5535.8  530.98
  5554.9  530.63  5575.2  531.30  5605.8  533.40  5615.1  534.88  5636.1  536.65
  5730.4  541.81  5738.0  542.76  5768.0  543.90  5783.0  544.51  5809.2  547.04
#Mann=9,-1,0
  4429.6     0.1       0  4522.3    0.12       0  4696.9    0.05       0
  5129.8    0.03       0  5133.8    0.05       0  5304.5     0.1       0
  5535.8    0.12       0  5636.1    0.05       0  5768.0     0.1       0
Bank Sta=5129.8,5133.8
Exp/Cntr=0.3,0.1

Type RM Length L Ch R = 1,90934,91,91,91
BEGIN DESCRIPTION:
Mapping XS 5c123374
END DESCRIPTION:
XS GIS Cut Line= 6
      2770229.35      6816755.28      2770138.63      6816500.20
      2769878.59      6816313.66      2769649.51      6816183.31
      2769497.95      6816090.71      2768959.58      6816080.85
#Sta/Elev= 30
  4405.4  534.54  4473.6  530.20  4489.8  528.38  4629.4  523.47  4654.1  521.64
  4699.2  520.56  4770.4  521.83  4913.2  522.95  4921.4  522.28  5153.8  522.42
  5212.9  520.89  5256.1  521.03  5271.7  519.73  5308.5  518.51  5385.9  518.35
  5386.1  517.85  5389.9  518.35  5430.5  519.36  5469.3  518.48  5501.0  518.64
  5539.3  521.52  5609.3  522.50  5635.3  523.62  5649.3  524.54  5694.4  530.91
  5699.4  530.57  5734.2  533.53  5779.3  538.10  5876.2  543.09  5975.8  547.98
#Mann=8,-1,0
  4405.4     0.1       0  4629.4    0.12       0  5385.9    0.07       0
  5389.9    0.12       0  5501.0     0.1       0  5635.3    0.12       0
  5734.2    0.05       0  5876.2     0.1       0
Bank Sta=5385.9,5389.9
Exp/Cntr=0.3,0.1

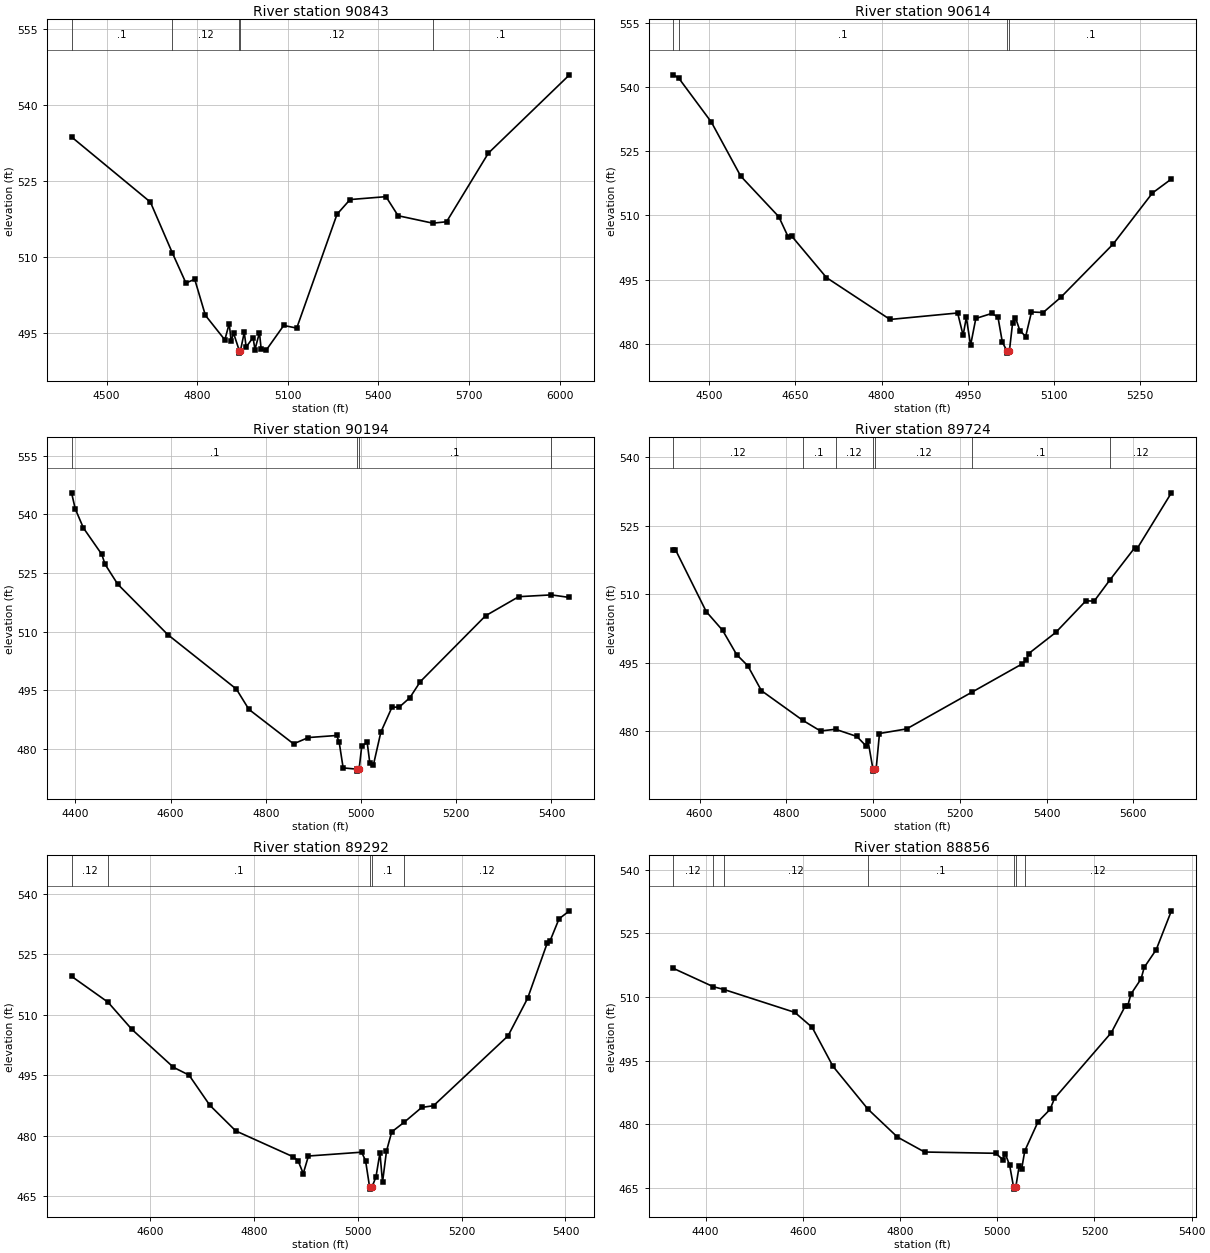
Type RM Length L Ch R = 1,90843,229,229,229
BEGIN DESCRIPTION:
Mapping XS c5150e0a
END DESCRIPTION:
XS GIS Cut Line= 5
      2770255.77      6816719.00      2770183.37      6816436.69
      2769926.53      6816239.84      2769569.94      6816033.60
      2768950.19      6815985.42
#Sta/Elev= 30
  4384.2  533.70  4645.2  520.85  4717.4  510.89  4762.9  504.88  4791.9  505.63
  4827.3  498.51  4891.7  493.67  4906.2  496.88  4912.5  493.46  4920.7  494.97
  4939.5  491.55  4939.8  491.05  4943.5  491.55  4956.0  495.15  4962.3  492.25
  4985.1  494.13  4991.4  491.76  5006.3  495.10  5012.1  491.77  5027.8  491.57
  5086.7  496.51  5129.7  495.99  5263.2  518.46  5306.3  521.35  5425.2  521.92
  5465.3  518.16  5580.3  516.69  5625.8  516.97  5764.2  530.51  6032.8  545.96
#Mann=5,-1,0
  4384.2     0.1       0  4717.4    0.12       0  4939.5    0.07       0
  4943.5    0.12       0  5580.3     0.1       0
Bank Sta=4939.5,4943.5
Exp/Cntr=0.3,0.1

Type RM Length L Ch R = 1,90614,420,420,420
BEGIN DESCRIPTION:
Clear Creek 152.0
END DESCRIPTION:
XS GIS Cut Line= 3
      2770524.54      6815802.01      2770026.00      6816061.00
      2769726.04      6816011.01
#Sta/Elev= 30
  4438.2  542.79  4447.5  542.00  4504.2  531.73  4555.1  519.15  4621.4  509.66
  4637.9  504.89  4643.6  505.17  4704.3  495.45  4814.8  485.68  4932.4  487.19
  4941.9  481.98  4947.5  486.15  4954.9  479.67  4964.0  485.91  4991.8  487.09
  5002.5  486.23  5010.1  480.41  5018.1  478.32  5018.5  477.82  5022.4  478.32
  5027.9  484.81  5032.9  486.10  5040.6  483.08  5050.7  481.70  5060.8  487.43
  5081.1  487.30  5111.5  490.81  5202.8  503.28  5271.2  515.21  5304.1  518.47
#Mann=4,-1,0
  4438.2    0.12       0  4447.5     0.1       0  5018.1    0.07       0
  5022.4     0.1       0
Bank Sta=5018.1,5022.4
Exp/Cntr=0.3,0.1

Type RM Length L Ch R = 1,90194,470,470,470
BEGIN DESCRIPTION:
Clear Creek 151.0
END DESCRIPTION:
XS GIS Cut Line= 3
      2770513.37      6815538.51      2769926.00      6815711.00
      2769529.78      6815887.67
#Sta/Elev= 30
  4391.8  545.53  4399.5  541.44  4416.7  536.53  4455.3  529.77  4462.0  527.26
  4488.7  522.14  4594.1  509.19  4738.0  495.27  4764.3  490.07  4858.1  481.24
  4889.3  482.85  4948.7  483.38  4953.9  481.73  4962.3  475.08  4991.4  474.75
  4991.8  474.25  4995.8  474.75  5001.4  480.67  5012.8  481.60  5018.3  476.39
  5025.9  475.84  5041.6  484.26  5064.8  490.59  5080.6  490.69  5102.5  493.06
  5124.4  497.17  5261.5  514.04  5331.2  518.93  5399.6  519.39  5437.8  518.73
#Mann=4,-1,0
  4391.8     0.1       0  4991.4    0.07       0  4995.8     0.1       0
  5399.6    0.12       0
Bank Sta=4991.4,4995.8
Exp/Cntr=0.3,0.1

Type RM Length L Ch R = 1,89724,432,432,432
BEGIN DESCRIPTION:
Clear Creek 150.0
END DESCRIPTION:
XS GIS Cut Line= 3
      2770269.51      6815172.27      2769826.00      6815311.00
      2769179.71      6815532.82
#Sta/Elev= 30
  4539.9  519.82  4544.3  519.82  4615.5  506.20  4653.2  502.10  4685.7  496.76
  4711.2  494.34  4742.7  488.87  4838.0  482.37  4878.9  480.03  4913.5  480.41
  4962.7  478.83  4983.1  476.84  4988.4  477.91  4999.7  471.73  5000.2  471.23
  5004.2  471.73  5007.2  471.73  5014.9  479.48  5077.5  480.49  5229.1  488.60
  5342.9  494.69  5353.5  495.51  5358.8  497.00  5421.3  501.64  5490.9  508.58
  5509.8  508.50  5545.6  513.08  5603.6  520.23  5608.9  520.02  5687.9  532.25
#Mann=7,-1,0
  4539.9    0.12       0  4838.0     0.1       0  4913.5    0.12       0
  4999.7    0.07       0  5004.2    0.12       0  5229.1     0.1       0
  5545.6    0.12       0
Bank Sta=4999.7,5004.2
Exp/Cntr=0.3,0.1

Type RM Length L Ch R = 1,89292,436,436,436
BEGIN DESCRIPTION:
Clear Creek 149.0
END DESCRIPTION:
XS GIS Cut Line= 3
      2770282.29      6814895.48      2769726.00      6814911.00
      2769326.02      6814861.00
#Sta/Elev= 30
  4448.1  519.52  4518.3  513.11  4564.4  506.36  4644.5  496.96  4674.5  495.03
  4714.5  487.56  4764.5  481.20  4874.6  474.81  4884.6  473.81  4894.6  470.62
  4904.6  474.97  5007.1  475.92  5014.7  473.81  5022.5  467.26  5023.0  466.76
  5027.1  467.26  5034.8  469.83  5042.4  475.75  5047.4  468.47  5055.0  476.17
  5065.1  480.95  5089.1  483.34  5123.0  487.02  5145.7  487.44  5289.3  504.76
  5327.1  514.10  5364.9  527.80  5369.9  528.19  5387.6  533.79  5407.7  535.76
#Mann=5,-1,0
  4448.1    0.12       0  4518.3     0.1       0  5022.5    0.07       0
  5027.1     0.1       0  5089.1    0.12       0
Bank Sta=5022.5,5027.1
Exp/Cntr=0.3,0.1

Type RM Length L Ch R = 1,88856,441,441,441
BEGIN DESCRIPTION:
Clear Creek 148.0
END DESCRIPTION:
XS GIS Cut Line= 3
      2770369.20      6814710.60      2769726.00      6814561.00
      2769375.98      6814661.01
#Sta/Elev= 30
  4333.9  516.72  4415.8  512.41  4438.2  511.74  4583.6  506.36  4619.3  502.83
  4661.9  493.69  4733.9  483.59  4794.8  476.99  4850.5  473.48  4996.9  473.18
  5011.2  471.71  5016.4  473.09  5025.5  470.39  5033.6  465.24  5034.1  464.74
  5038.2  465.24  5045.0  470.09  5050.2  469.46  5056.7  473.76  5084.0  480.62
  5108.7  483.52  5117.8  486.11  5234.8  501.61  5263.4  507.87  5268.6  507.96
  5275.1  510.67  5295.9  514.25  5302.4  516.96  5327.1  521.14  5358.3  530.28
#Mann=7,-1,0
  4333.9    0.12       0  4415.8     0.1       0  4438.2    0.12       0
  4733.9     0.1       0  5033.6    0.07       0  5038.2     0.1       0
  5056.7    0.12       0
Bank Sta=5033.6,5038.2
Exp/Cntr=0.3,0.1

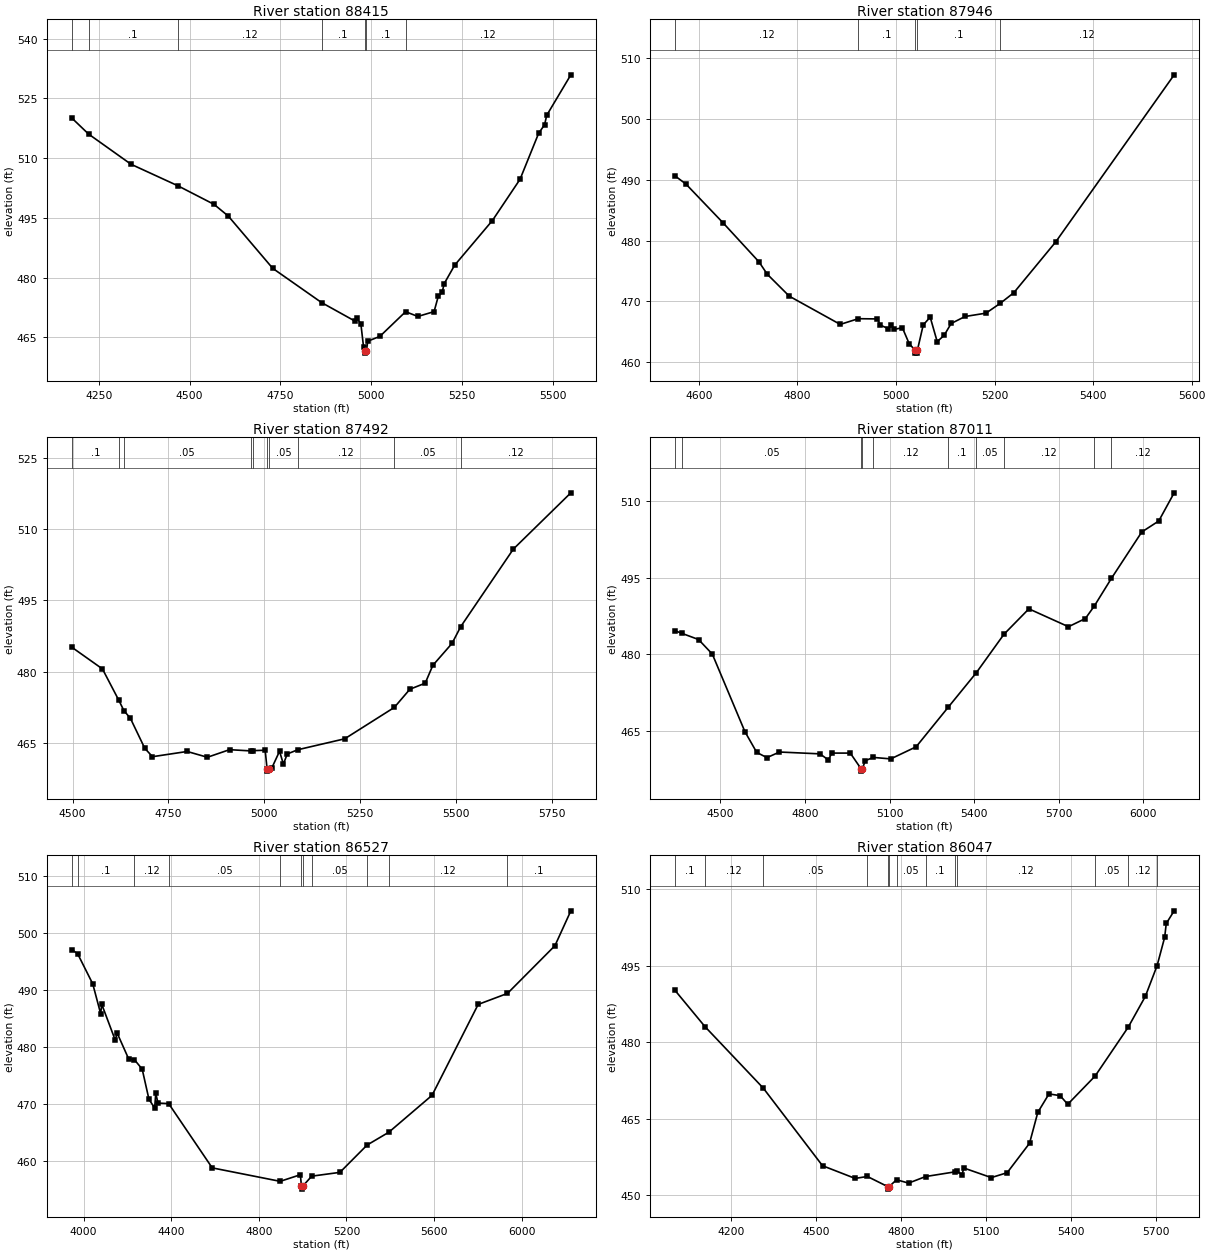
Type RM Length L Ch R = 1,88415,469,469,469
BEGIN DESCRIPTION:
Clear Creek 147.0
END DESCRIPTION:
XS GIS Cut Line= 3
      2770525.05      6814589.74      2769776.00      6814261.00
      2769281.85      6814516.48
#Sta/Elev= 30
  4175.5  520.12  4222.1  516.05  4338.9  508.47  4468.0  503.06  4567.6  498.39
  4606.8  495.45  4729.1  482.33  4863.5  473.74  4955.7  469.07  4961.2  469.75
  4971.7  468.43  4979.1  462.63  4982.3  461.54  4982.7  461.04  4986.9  461.54
  4990.8  464.05  5023.9  465.23  5094.9  471.44  5128.6  470.25  5173.3  471.46
  5184.9  475.33  5195.4  476.27  5201.1  478.48  5229.9  483.11  5333.9  494.34
  5410.0  504.70  5461.2  516.25  5477.6  518.40  5483.3  520.74  5549.8  530.92
#Mann=7,-1,0
  4175.5    0.12       0  4222.1     0.1       0  4468.0    0.12       0
  4863.5     0.1       0  4982.3    0.07       0  4986.9     0.1       0
  5094.9    0.12       0
Bank Sta=4982.3,4986.9
Exp/Cntr=0.3,0.1

Type RM Length L Ch R = 1,87946,454,454,454
BEGIN DESCRIPTION:
Clear Creek 146.0
END DESCRIPTION:
XS GIS Cut Line= 3
      2770126.01      6814061.01      2769726.00      6813861.00
      2769326.01      6814260.99
#Sta/Elev= 30
  4551.6  490.63  4574.0  489.27  4649.4  482.89  4722.1  476.49  4738.9  474.46
  4783.6  470.85  4887.0  466.21  4923.6  467.15  4962.5  467.11  4968.1  466.11
  4984.9  465.49  4990.4  466.12  4996.0  465.38  5013.0  465.67  5027.1  463.00
  5038.9  461.99  5039.4  461.49  5043.1  461.49  5043.6  461.99  5055.4  466.13
  5069.5  467.40  5083.7  463.38  5097.8  464.41  5112.0  466.36  5140.2  467.51
  5182.7  468.06  5211.4  469.66  5239.2  471.42  5324.1  479.76  5564.5  507.23
#Mann=5,-1,0
  4551.6    0.12       0  4923.6     0.1       0  5038.9    0.07       0
  5043.6     0.1       0  5211.4    0.12       0
Bank Sta=5038.9,5043.6
Exp/Cntr=0.3,0.1

Type RM Length L Ch R = 1,87492,481,481,481
BEGIN DESCRIPTION:
Clear Creek 145.0
END DESCRIPTION:
XS GIS Cut Line= 3
      2770275.99      6813511.00      2769776.00      6813461.00
      2768975.98      6813461.00
#Sta/Elev= 30
  4497.5  485.18  4577.9  480.58  4620.9  473.93  4633.8  471.81  4650.8  470.18
  4688.4  463.85  4708.5  462.09  4799.0  463.19  4851.7  461.97  4909.5  463.57
  4964.8  463.31  4971.5  463.37  5002.5  463.45  5007.4  459.55  5008.1  459.05
  5012.6  459.55  5020.0  459.75  5040.0  463.24  5050.0  460.52  5060.0  462.66
  5087.7  463.56  5210.0  465.86  5339.4  472.47  5380.0  476.30  5420.0  477.58
  5440.0  481.34  5490.0  485.96  5512.7  489.49  5650.0  505.83  5800.0  517.68
#Mann=10,-1,0
  4497.5     0.1       0  4620.9    0.12       0  4633.8    0.05       0
  4964.8    0.12       0  4971.5    0.05       0  5007.4    0.04       0
  5012.6    0.05       0  5087.7    0.12       0  5339.4    0.05       0
  5512.7    0.12       0
Bank Sta=5007.4,5012.6
Exp/Cntr=0.3,0.1

Type RM Length L Ch R = 1,87011,484,484,484
BEGIN DESCRIPTION:
Clear Creek 144.0
END DESCRIPTION:
XS GIS Cut Line= 3
      2770325.47      6813386.40      2769776.00      6813011.00
      2768671.34      6812964.54
#Sta/Elev= 30
  4338.7  484.65  4363.8  484.11  4422.4  482.91  4471.3  480.05  4587.0  464.82
  4628.9  460.75  4665.1  459.73  4709.6  460.83  4853.1  460.47  4883.0  459.28
  4895.2  460.62  4960.8  460.62  4998.5  457.58  4999.2  457.08  5003.7  457.58
  5014.2  459.14  5042.6  459.77  5104.3  459.48  5194.3  461.85  5308.2  469.62
  5407.2  476.34  5506.1  483.95  5594.4  488.93  5734.8  485.42  5794.9  487.03
  5826.7  489.50  5887.2  494.91  5995.0  504.02  6055.1  506.17  6109.8  511.70
#Mann=10,-1,0
  4338.7    0.12       0  4363.8    0.05       0  4998.5    0.04       0
  5003.7    0.05       0  5042.6    0.12       0  5308.2     0.1       0
  5407.2    0.05       0  5506.1    0.12       0  5826.7     0.1       0
  5887.2    0.12       0
Bank Sta=4998.5,5003.7
Exp/Cntr=0.3,0.1

Type RM Length L Ch R = 1,86527,480,480,480
BEGIN DESCRIPTION:
Clear Creek 143.0
END DESCRIPTION:
XS GIS Cut Line= 3
      2770898.26      6812818.66      2769876.00      6812561.00
      2768653.62      6812493.04
#Sta/Elev= 30
  3945.8  497.12  3972.9  496.41  4042.3  491.08  4078.2  485.85  4083.4  487.48
  4144.1  481.26  4154.4  482.36  4206.6  477.84  4232.0  477.76  4267.8  476.09
  4298.8  470.77  4324.7  469.25  4329.9  471.82  4340.0  470.11  4388.7  470.02
  4587.5  458.71  4897.7  456.34  4989.7  457.50  4994.9  455.47  4995.6  454.97
  5000.1  455.47  5041.5  457.25  5170.3  457.92  5294.5  462.73  5393.5  464.98
  5590.9  471.48  5801.3  487.47  5935.2  489.41  6151.8  497.81  6224.3  503.94
#Mann=11,-1,0
  3945.8    0.12       0  3972.9     0.1       0  4232.0    0.12       0
  4388.7    0.05       0  4897.7     0.1       0  4994.9    0.07       0
  5000.1     0.1       0  5041.5    0.05       0  5294.5     0.1       0
  5393.5    0.12       0  5935.2     0.1       0
Bank Sta=4994.9,5000.1
Exp/Cntr=0.3,0.1

Type RM Length L Ch R = 1,86047,471,471,471
BEGIN DESCRIPTION:
Clear Creek 142.0
END DESCRIPTION:
XS GIS Cut Line= 3
      2770733.41      6812409.33      2769776.00      6812111.00
      2769043.75      6811908.66
#Sta/Elev= 30
  4002.8  490.14  4108.8  483.02  4314.7  470.96  4523.8  455.75  4639.0  453.26
  4682.2  453.64  4753.8  451.66  4754.6  451.16  4759.2  451.66  4785.1  453.00
  4827.5  452.34  4888.0  453.63  4990.9  454.54  4998.5  454.73  5016.0  453.95
  5022.8  455.30  5119.7  453.42  5175.7  454.38  5254.7  460.15  5283.9  466.21
  5323.4  469.83  5362.9  469.48  5389.5  467.79  5486.4  473.34  5603.1  482.91
  5663.5  488.94  5705.1  494.98  5731.8  500.53  5737.4  503.24  5765.3  505.72
#Mann=13,-1,0
  4002.8     0.1       0  4108.8    0.12       0  4314.7    0.05       0
  4682.2     0.1       0  4753.8    0.07       0  4759.2     0.1       0
  4785.1    0.05       0  4888.0     0.1       0  4990.9    0.05       0
  4998.5    0.12       0  5486.4    0.05       0  5603.1    0.12       0
  5705.1     0.1       0
Bank Sta=4753.8,4759.2
Exp/Cntr=0.3,0.1