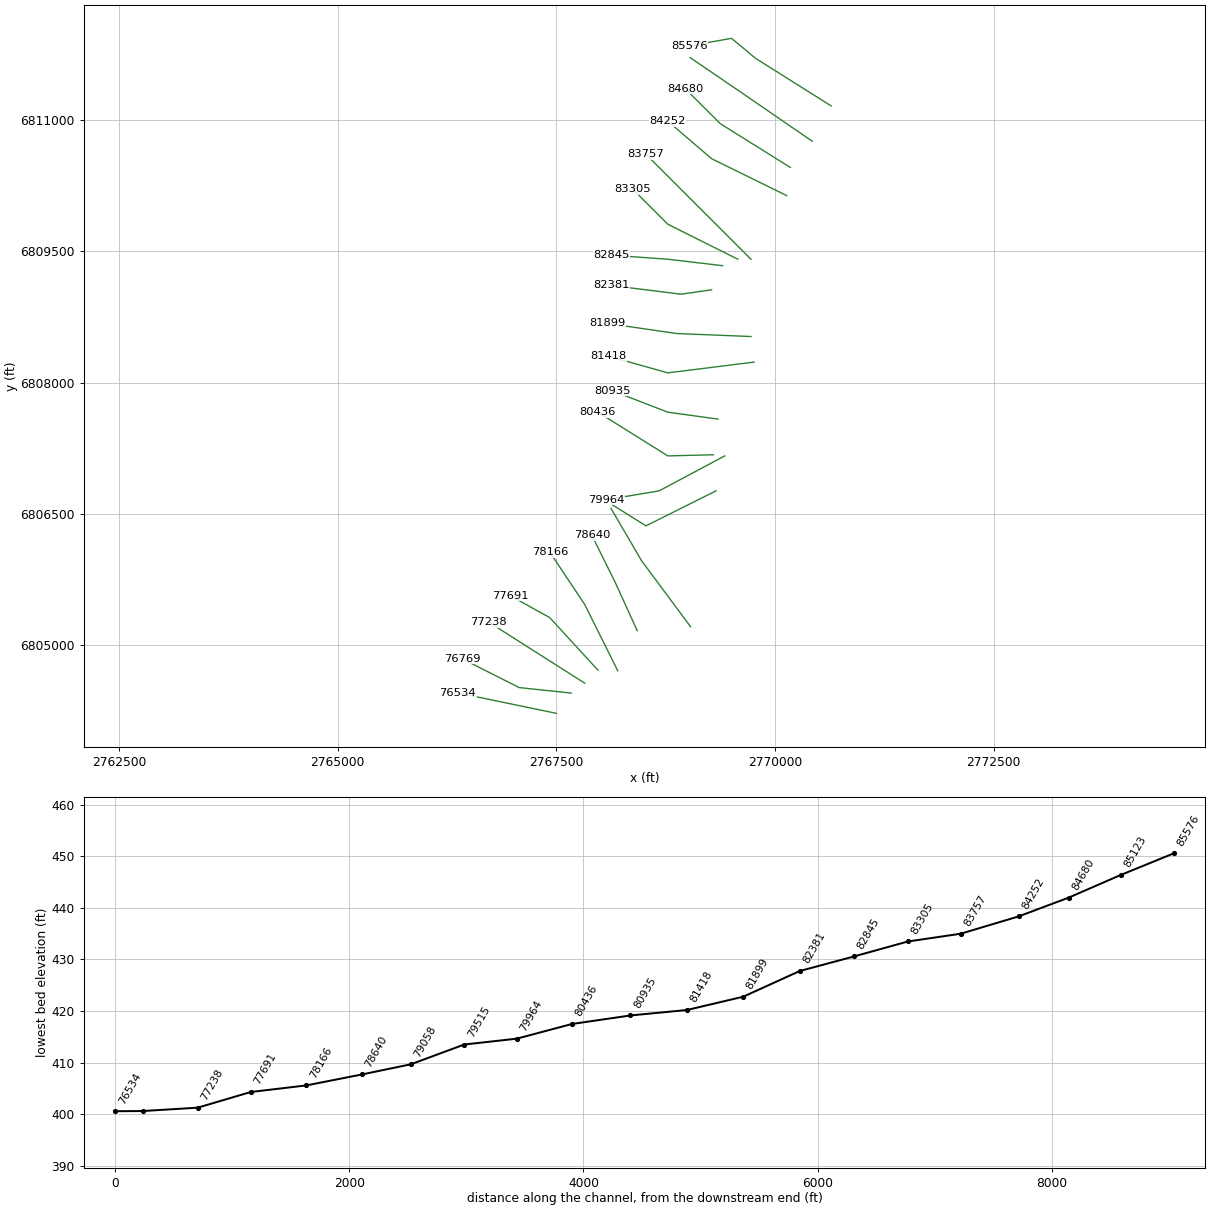
HEC-RAS study Clear Creek.prj: Clear Creek Base Level Engineering

--- Clear Creek.g01 (geometry) --- (continued)

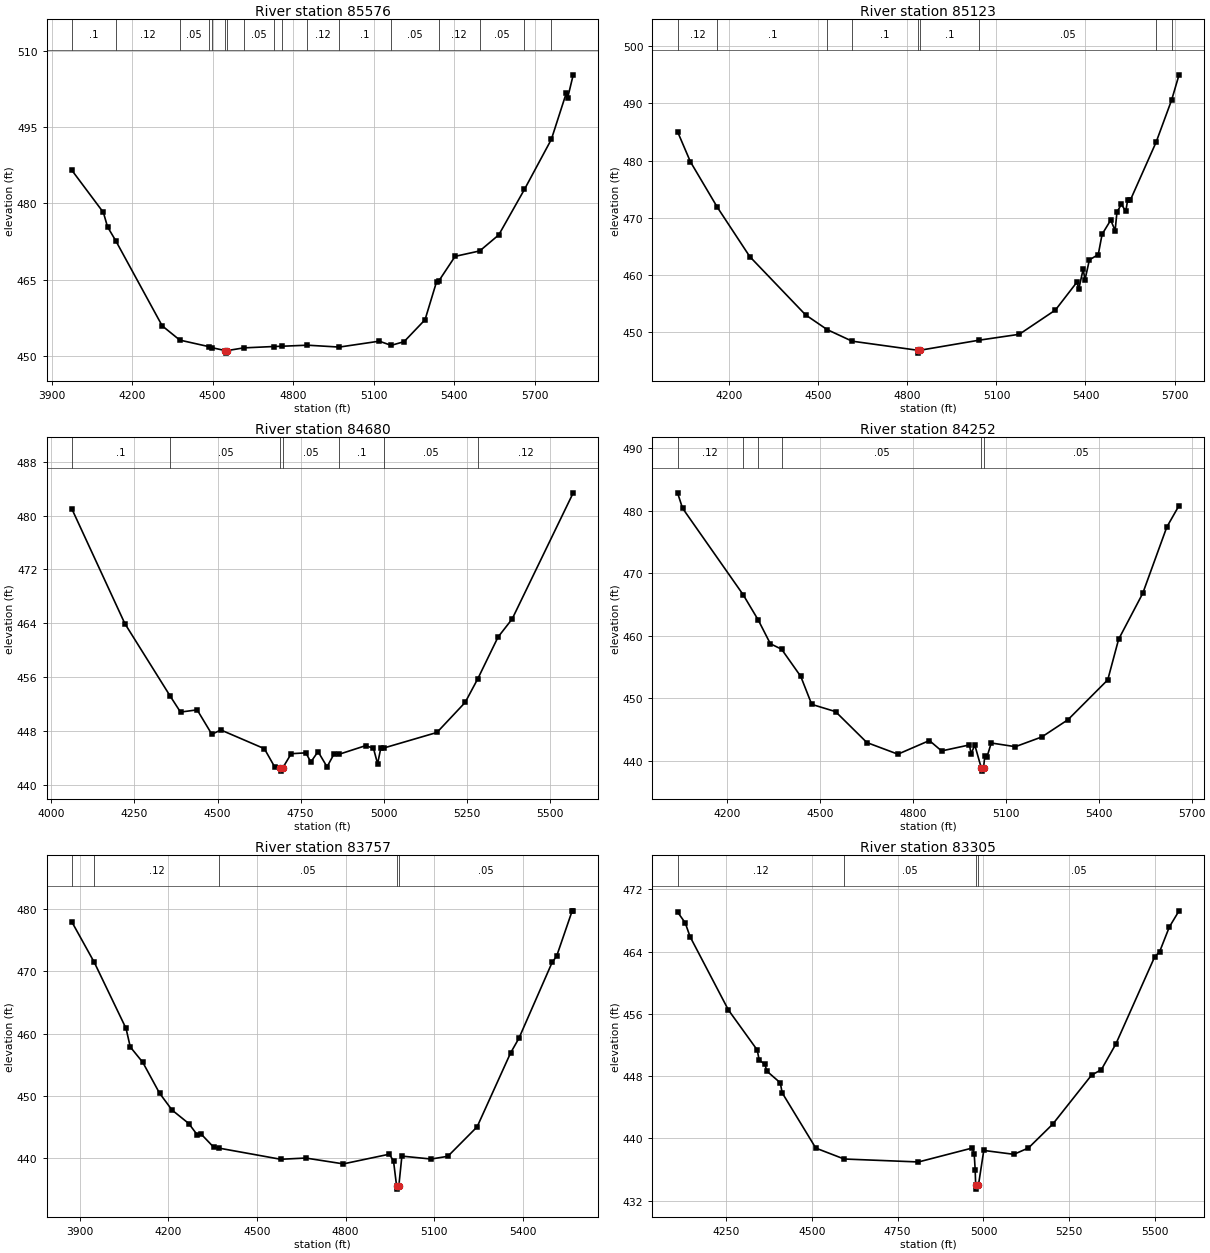
Type RM Length L Ch R = 1,85576,453,453,453
BEGIN DESCRIPTION:
Clear Creek 141.0
END DESCRIPTION:
XS GIS Cut Line= 4
      2770642.86      6811164.49      2769776.00      6811711.00
      2769503.79      6811937.84      2769023.02      6811851.85
#Sta/Elev= 30
  3975.2  486.56  4093.1  478.23  4108.4  475.41  4138.9  472.69  4312.0  455.94
  4377.7  453.13  4484.9  451.86  4496.5  451.65  4547.1  451.07  4548.2  450.57
  4554.3  451.07  4615.3  451.60  4726.7  451.87  4756.6  451.92  4852.8  452.13
  4971.6  451.76  5120.4  452.92  5164.6  452.10  5212.8  452.82  5290.9  457.14
  5333.8  464.62  5342.6  464.80  5402.8  469.60  5494.6  470.67  5565.4  473.82
  5661.2  482.78  5761.3  492.61  5816.7  501.69  5821.8  500.73  5842.7  505.30
#Mann=17,-1,0
  3975.2     0.1       0  4138.9    0.12       0  4377.7    0.05       0
  4484.9    0.12       0  4496.5     0.1       0  4547.1    0.07       0
  4554.3     0.1       0  4615.3    0.05       0  4726.7     0.1       0
  4756.6    0.05       0  4852.8    0.12       0  4971.6     0.1       0
  5164.6    0.05       0  5342.6    0.12       0  5494.6    0.05       0
  5661.2    0.12       0  5761.3     0.1       0
Bank Sta=4547.1,4554.3
Exp/Cntr=0.3,0.1

Type RM Length L Ch R = 1,85123,443,443,443
BEGIN DESCRIPTION:
Clear Creek 140.0
END DESCRIPTION:
XS GIS Cut Line= 3
      2770426.01      6810760.99      2769626.00      6811311.00
      2769031.86      6811716.57
#Sta/Elev= 30
  4025.1  485.08  4068.4  479.82  4159.6  471.83  4268.6  463.24  4456.7  453.06
  4529.4  450.49  4613.2  448.47  4834.5  446.88  4835.7  446.38  4841.8  446.88
  5041.3  448.64  5176.8  449.67  5298.6  453.91  5371.3  458.79  5377.3  457.55
  5392.2  461.05  5398.3  459.20  5413.2  462.68  5443.0  463.60  5456.0  467.15
  5485.0  469.62  5499.9  467.80  5506.0  471.00  5520.9  472.40  5535.8  471.15
  5541.9  473.08  5550.7  473.06  5638.1  483.25  5690.5  490.64  5715.3  495.01
#Mann=9,-1,0
  4025.1    0.12       0  4159.6     0.1       0  4529.4    0.05       0
  4613.2     0.1       0  4834.5    0.07       0  4841.8     0.1       0
  5041.3    0.05       0  5638.1    0.12       0  5690.5     0.1       0
Bank Sta=4834.5,4841.8
Exp/Cntr=0.3,0.1

Type RM Length L Ch R = 1,84680,428,428,428
BEGIN DESCRIPTION:
Clear Creek 139.0
END DESCRIPTION:
XS GIS Cut Line= 3
      2770176.01      6810460.99      2769376.00      6810961.00
      2768976.00      6811361.00
#Sta/Elev= 30
  4061.2  481.03  4221.0  463.94  4357.8  453.13  4388.5  450.78  4438.6  451.11
  4482.8  447.48  4509.9  448.12  4640.8  445.34  4671.5  442.66  4689.1  442.50
  4690.2  442.00  4696.4  442.50  4721.6  444.59  4765.8  444.72  4780.6  443.35
  4802.4  444.90  4829.5  442.64  4851.3  444.62  4866.6  444.52  4945.7  445.79
  4969.2  445.39  4981.6  443.09  4991.1  445.39  4999.7  445.43  5160.2  447.75
  5245.0  452.21  5283.4  455.76  5344.0  461.93  5386.5  464.62  5570.3  483.38
#Mann=7,-1,0
  4061.2     0.1       0  4357.8    0.05       0  4689.1    0.04       0
  4696.4    0.05       0  4866.6     0.1       0  4999.7    0.05       0
  5283.4    0.12       0
Bank Sta=4689.1,4696.4
Exp/Cntr=0.3,0.1

Type RM Length L Ch R = 1,84252,495,495,495
BEGIN DESCRIPTION:
Clear Creek 138.0
END DESCRIPTION:
XS GIS Cut Line= 3
      2770135.15      6810138.82      2769276.00      6810561.00
      2768772.25      6810992.71
#Sta/Elev= 30
  4038.6  482.87  4054.6  480.42  4250.5  466.58  4299.4  462.52  4338.5  458.73
  4374.8  457.85  4436.8  453.50  4472.2  449.03  4549.2  447.87  4650.5  442.92
  4750.7  441.06  4852.5  443.24  4891.9  441.58  4981.8  442.54  4987.4  441.13
  4999.2  442.53  5020.2  438.85  5021.3  438.35  5027.5  438.85  5031.5  440.79
  5038.1  440.54  5052.4  442.85  5130.3  442.26  5215.9  443.82  5300.5  446.58
  5428.9  452.95  5464.0  459.44  5541.9  466.78  5619.8  477.40  5659.3  480.83
#Mann=6,-1,0
  4038.6    0.12       0  4250.5     0.1       0  4299.4    0.12       0
  4374.8    0.05       0  5020.2    0.04       0  5027.5    0.05       0
Bank Sta=5020.2,5027.5
Exp/Cntr=0.3,0.1

Type RM Length L Ch R = 1,83757,452,452,452
BEGIN DESCRIPTION:
Clear Creek 137.0
END DESCRIPTION:
XS GIS Cut Line= 3
      2769725.99      6809411.01      2768926.00      6810211.00
      2768526.03      6810610.97
#Sta/Elev= 30
  3873.0  478.00  3949.3  471.46  4056.8  460.83  4071.0  457.86  4113.4  455.38
  4170.0  450.43  4212.4  447.71  4269.0  445.54  4297.3  443.75  4311.4  443.82
  4353.8  441.71  4370.6  441.59  4580.1  439.79  4664.9  439.99  4792.2  439.05
  4947.8  440.61  4961.9  439.51  4972.3  435.49  4973.5  434.99  4979.8  435.49
  4990.2  440.30  5089.2  439.83  5145.8  440.27  5244.8  445.01  5357.9  456.88
  5386.2  459.25  5499.3  471.53  5513.5  472.41  5566.5  479.75  5570.0  479.75
#Mann=5,-1,0
  3873.0     0.1       0  3949.3    0.12       0  4370.6    0.05       0
  4972.3    0.04       0  4979.8    0.05       0
Bank Sta=4972.3,4979.8
Exp/Cntr=0.3,0.1

Type RM Length L Ch R = 1,83305,460,460,460
BEGIN DESCRIPTION:
Clear Creek 136.0
END DESCRIPTION:
XS GIS Cut Line= 3
      2769575.98      6809411.01      2768776.00      6809811.00
      2768376.00      6810211.00
#Sta/Elev= 30
  4109.4  469.07  4131.7  467.69  4145.7  465.92  4257.5  456.49  4341.4  451.35
  4347.0  450.06  4363.7  449.52  4369.3  448.64  4408.5  447.14  4414.0  445.85
  4511.9  438.75  4594.3  437.35  4810.9  436.97  4967.5  438.76  4973.1  438.03
  4975.9  436.00  4977.4  433.98  4978.6  433.48  4985.4  433.98  5001.0  438.45
  5088.7  437.95  5131.1  438.77  5201.8  441.83  5314.9  448.13  5343.2  448.82
  5385.6  452.13  5498.8  463.34  5512.9  463.97  5541.2  467.15  5569.5  469.23
#Mann=4,-1,0
  4109.4    0.12       0  4594.3    0.05       0  4977.4    0.04       0
  4985.4    0.05       0
Bank Sta=4977.4,4985.4
Exp/Cntr=0.3,0.1

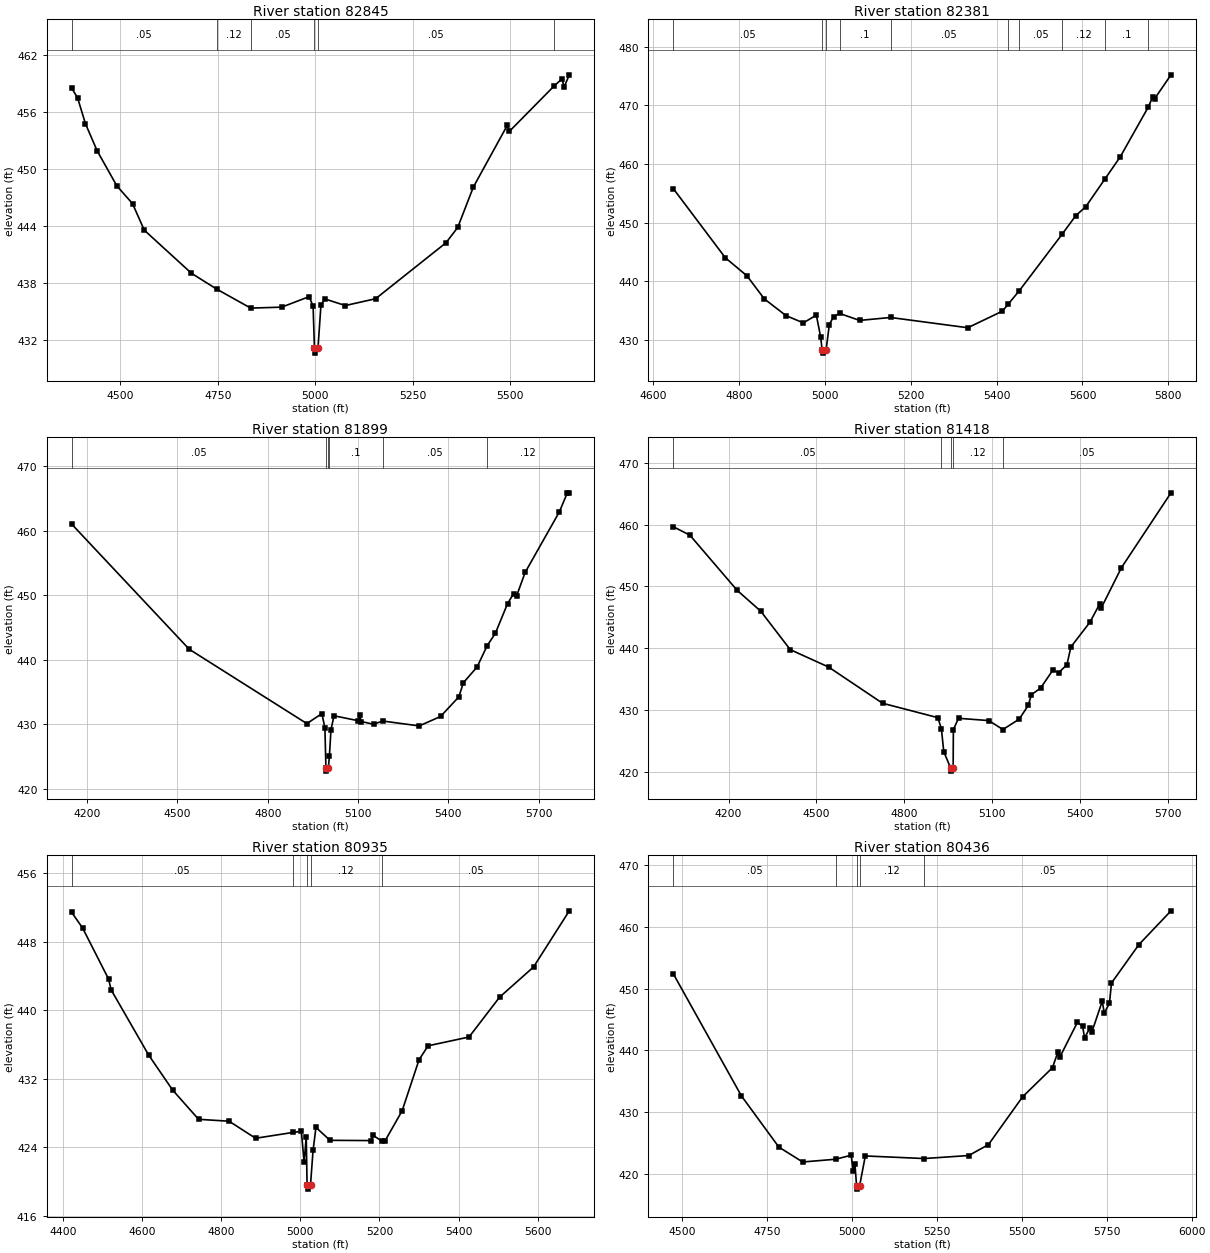
Type RM Length L Ch R = 1,82845,464,464,464
BEGIN DESCRIPTION:
Clear Creek 135.0
END DESCRIPTION:
XS GIS Cut Line= 3
      2769401.28      6809337.04      2768776.00      6809411.00
      2768130.48      6809457.18
#Sta/Elev= 30
  4374.5  458.56  4389.9  457.52  4410.0  454.80  4440.2  451.92  4490.6  448.23
  4530.9  446.35  4561.1  443.55  4681.9  439.01  4746.5  437.34  4834.1  435.33
  4913.5  435.43  4984.0  436.54  4994.1  435.52  4997.6  431.08  4998.8  430.58
  5005.6  431.08  5006.6  431.08  5014.2  435.62  5024.2  436.30  5076.8  435.60
  5154.5  436.32  5335.0  442.22  5365.1  443.84  5405.2  448.10  5492.5  454.63
  5497.5  453.97  5611.1  458.71  5632.8  459.53  5637.8  458.63  5651.3  459.94
#Mann=6,-1,0
  4374.5    0.05       0  4746.5    0.12       0  4834.1    0.05       0
  4997.6    0.04       0  5005.6    0.05       0  5611.1     0.1       0
Bank Sta=4997.6,5005.6
Exp/Cntr=0.3,0.1

Type RM Length L Ch R = 1,82381,482,482,482
BEGIN DESCRIPTION:
Clear Creek 134.0
END DESCRIPTION:
XS GIS Cut Line= 3
      2769276.04      6809061.01      2768926.00      6809011.00
      2768126.02      6809111.00
#Sta/Elev= 30
  4646.5  455.82  4767.8  444.02  4818.3  440.93  4858.7  437.00  4909.2  434.15
  4949.6  432.91  4979.9  434.23  4990.0  430.50  4993.5  428.25  4994.7  427.75
  5001.7  428.25  5002.6  428.25  5010.2  432.63  5020.2  433.98  5034.1  434.52
  5080.7  433.33  5152.8  433.83  5332.7  432.08  5413.3  434.90  5426.6  436.07
  5452.9  438.40  5552.9  448.06  5584.6  451.22  5607.3  452.68  5652.9  457.51
  5687.9  461.21  5753.0  469.67  5763.5  471.42  5768.5  471.18  5806.3  475.22
#Mann=10,-1,0
  4646.5    0.05       0  4993.5    0.04       0  5001.7    0.05       0
  5034.1     0.1       0  5152.8    0.05       0  5426.6     0.1       0
  5452.9    0.05       0  5552.9    0.12       0  5652.9     0.1       0
  5753.0    0.05       0
Bank Sta=4993.5,5001.7
Exp/Cntr=0.3,0.1

Type RM Length L Ch R = 1,81899,481,481,481
BEGIN DESCRIPTION:
Clear Creek 133.0
END DESCRIPTION:
XS GIS Cut Line= 3
      2769726.46      6808526.77      2768876.00      6808561.00
      2768083.05      6808676.73
#Sta/Elev= 30
  4148.8  461.08  4539.6  441.66  4929.9  430.14  4979.9  431.68  4989.9  429.48
  4993.3  423.27  4994.5  422.77  5001.5  423.27  5004.8  425.06  5010.1  429.20
  5020.2  431.35  5099.9  430.59  5104.9  431.40  5111.1  430.46  5151.5  430.03
  5181.3  430.54  5303.1  429.78  5373.9  431.24  5434.5  434.28  5449.8  436.48
  5495.1  438.91  5528.7  442.22  5555.8  444.13  5596.2  448.72  5616.4  450.29
  5626.5  449.95  5654.8  453.58  5768.0  462.93  5794.8  465.91  5801.3  465.83
#Mann=6,-1,0
  4148.8    0.05       0  4993.3    0.04       0  5001.5    0.05       0
  5004.8     0.1       0  5181.3    0.05       0  5528.7    0.12       0
Bank Sta=4993.3,5001.5
Exp/Cntr=0.3,0.1

Type RM Length L Ch R = 1,81418,483,483,483
BEGIN DESCRIPTION:
Clear Creek 132.0
END DESCRIPTION:
XS GIS Cut Line= 3
      2769762.43      6808234.38      2768776.00      6808111.00
      2768097.05      6808301.54
#Sta/Elev= 30
  4011.3  459.65  4068.2  458.28  4229.4  449.38  4310.0  446.01  4410.8  439.80
  4541.8  436.99  4725.8  431.15  4914.7  428.82  4926.7  427.03  4934.9  423.33
  4958.2  420.69  4959.5  420.19  4966.9  420.69  4967.6  426.90  4985.3  428.72
  5088.5  428.35  5136.8  426.91  5192.4  428.58  5223.5  430.82  5233.9  432.54
  5265.1  433.58  5306.6  436.45  5327.4  436.11  5355.2  437.35  5368.9  440.24
  5433.7  444.22  5467.8  447.23  5473.0  446.58  5541.2  453.02  5710.6  465.12
#Mann=5,-1,0
  4011.3    0.05       0  4926.7    0.12       0  4958.2    0.07       0
  4966.9    0.12       0  5136.8    0.05       0
Bank Sta=4958.2,4966.9
Exp/Cntr=0.3,0.1

Type RM Length L Ch R = 1,80935,499,499,499
BEGIN DESCRIPTION:
Clear Creek 131.0
END DESCRIPTION:
XS GIS Cut Line= 3
      2769349.05      6807582.26      2768776.00      6807661.00
      2768141.71      6807906.30
#Sta/Elev= 30
  4421.6  451.42  4449.5  449.58  4515.5  443.60  4521.5  442.38  4616.5  434.77
  4677.0  430.69  4742.8  427.27  4819.9  427.05  4886.9  425.06  4981.3  425.74
  5002.7  425.87  5009.6  422.24  5015.0  425.24  5017.1  419.63  5018.4  419.13
  5025.8  419.63  5032.2  423.64  5039.6  426.33  5075.1  424.82  5178.6  424.79
  5184.0  425.39  5206.1  424.74  5214.5  424.78  5257.4  428.26  5300.2  434.21
  5323.0  435.84  5426.7  436.87  5504.0  441.52  5589.7  445.03  5680.1  451.58
#Mann=5,-1,0
  4421.6    0.05       0  4981.3    0.12       0  5017.1    0.07       0
  5025.8    0.12       0  5206.1    0.05       0
Bank Sta=5017.1,5025.8
Exp/Cntr=0.3,0.1

Type RM Length L Ch R = 1,80436,472,472,472
BEGIN DESCRIPTION:
Clear Creek 130.0
END DESCRIPTION:
XS GIS Cut Line= 3
      2769296.55      6807173.99      2768776.00      6807161.00
      2767976.00      6807661.00
#Sta/Elev= 30
  4475.1  452.41  4675.7  432.59  4785.7  424.30  4855.8  421.88  4953.0  422.33
  4998.8  422.98  5003.5  420.37  5009.4  421.61  5014.4  417.98  5015.7  417.48
  5023.2  417.98  5040.0  422.86  5213.2  422.44  5344.3  422.93  5402.1  424.69
  5502.9  432.46  5590.7  437.18  5606.1  439.64  5612.0  438.86  5663.9  444.53
  5679.2  443.87  5685.1  442.01  5700.4  443.60  5706.3  442.93  5737.0  447.96
  5742.9  446.04  5758.2  447.62  5764.1  450.90  5844.9  457.14  5939.2  462.61
#Mann=5,-1,0
  4475.1    0.05       0  4953.0    0.12       0  5014.4    0.07       0
  5023.2    0.12       0  5213.2    0.05       0
Bank Sta=5014.4,5023.2
Exp/Cntr=0.3,0.1

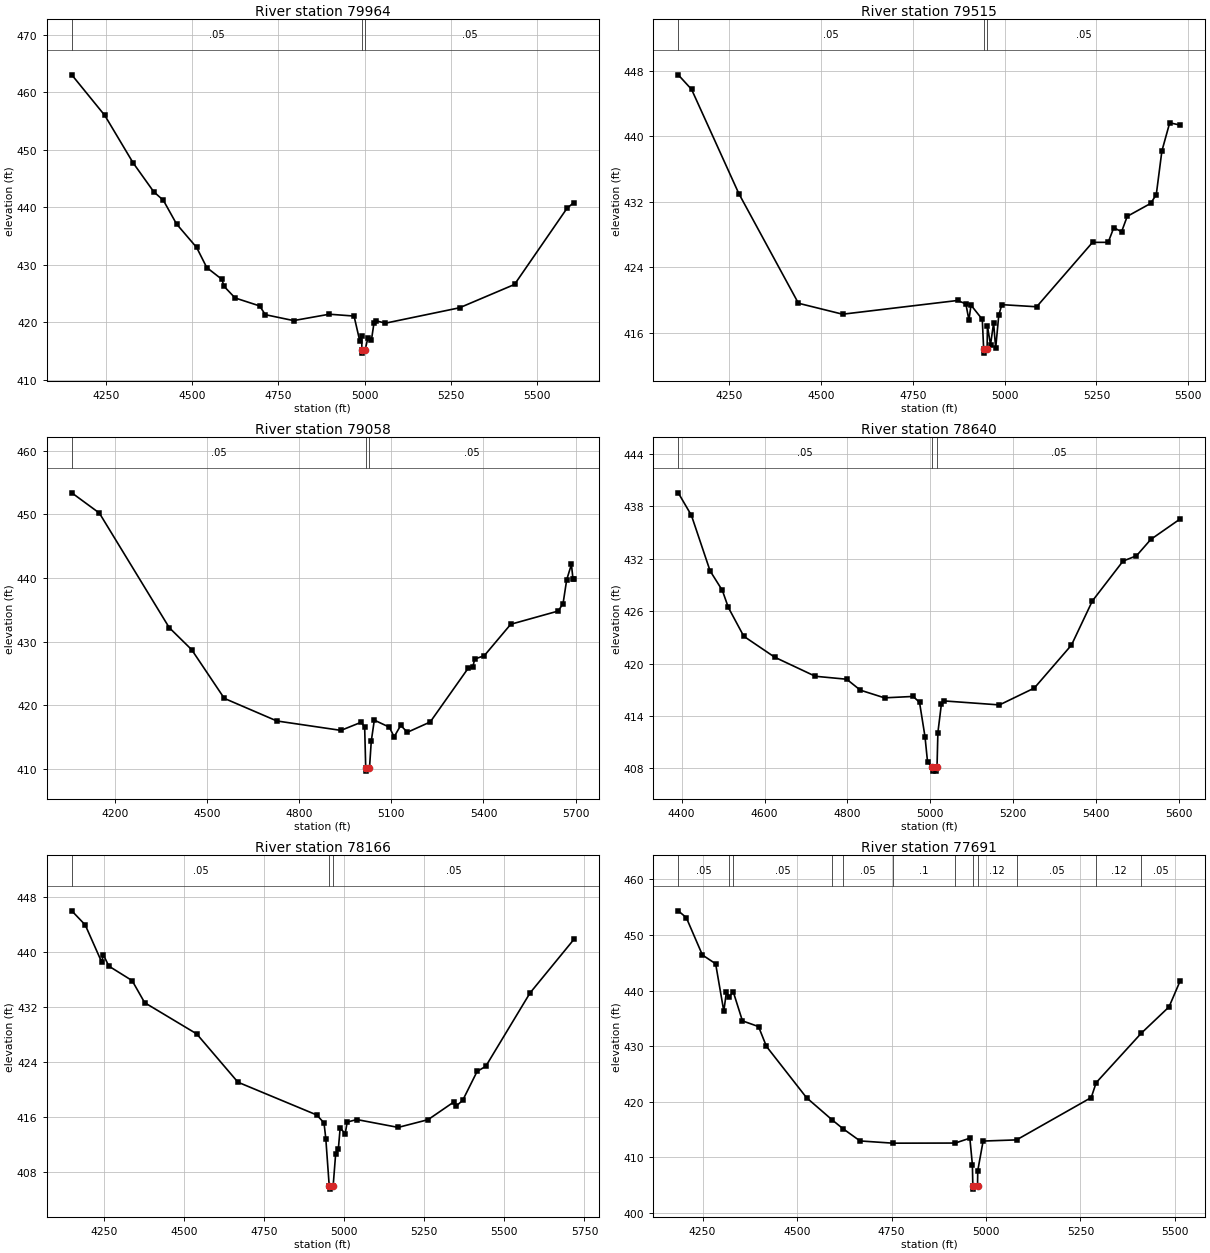
Type RM Length L Ch R = 1,79964,449,449,449
BEGIN DESCRIPTION:
Clear Creek 129.0
END DESCRIPTION:
XS GIS Cut Line= 3
      2769426.04      6807161.02      2768676.00      6806761.00
      2768076.03      6806661.00
#Sta/Elev= 30
  4149.6  463.05  4245.6  455.98  4327.8  447.73  4387.6  442.71  4415.6  441.22
  4453.9  437.10  4512.3  433.01  4541.7  429.52  4585.6  427.47  4591.6  426.27
  4623.9  424.23  4695.4  422.84  4711.7  421.32  4793.9  420.29  4897.6  421.40
  4969.5  421.08  4985.8  416.82  4991.5  417.61  4992.4  415.13  4993.7  414.63
  5001.3  415.13  5009.8  417.28  5019.9  416.87  5027.5  419.92  5032.6  420.27
  5060.5  419.84  5275.9  422.52  5435.6  426.58  5587.7  439.80  5607.9  440.83
#Mann=3,-1,0
  4149.6    0.05       0  4992.4    0.04       0  5001.3    0.05       0
Bank Sta=4992.4,5001.3
Exp/Cntr=0.3,0.1

Type RM Length L Ch R = 1,79515,457,457,457
BEGIN DESCRIPTION:
Clear Creek 128.0
END DESCRIPTION:
XS GIS Cut Line= 3
      2769325.99      6806760.99      2768526.00      6806361.00
      2768126.01      6806610.99
#Sta/Elev= 30
  4112.0  447.53  4148.3  445.75  4276.9  433.00  4439.0  419.59  4559.2  418.25
  4872.2  419.93  4894.6  419.51  4903.0  417.54  4908.6  419.36  4939.3  417.62
  4943.0  413.99  4944.4  413.49  4952.4  413.99  4953.3  416.80  4961.7  414.51
  4970.1  417.18  4975.7  414.09  4984.1  418.11  4992.4  419.42  5087.2  419.16
  5239.3  427.04  5281.8  427.04  5297.1  428.83  5318.3  428.34  5333.7  430.22
  5397.3  431.80  5412.7  432.88  5428.0  438.22  5449.2  441.66  5478.1  441.38
#Mann=3,-1,0
  4112.0    0.05       0  4943.0    0.04       0  4952.4    0.05       0
Bank Sta=4943,4952.4
Exp/Cntr=0.3,0.1

Type RM Length L Ch R = 1,79058,418,418,418
BEGIN DESCRIPTION:
Clear Creek 127.0
END DESCRIPTION:
XS GIS Cut Line= 3
      2769036.30      6805206.26      2768476.00      6805961.00
      2768126.00      6806561.00
#Sta/Elev= 30
  4059.7  453.37  4149.5  450.19  4377.0  432.19  4450.0  428.73  4556.3  421.08
  4727.4  417.53  4936.1  416.05  5002.6  417.34  5013.3  416.51  5016.7  410.15
  5018.4  409.65  5029.0  410.15  5034.8  414.37  5044.7  417.66  5093.5  416.56
  5109.2  415.04  5130.7  416.84  5152.2  415.75  5226.7  417.37  5349.9  425.79
  5365.6  426.05  5371.4  427.25  5402.8  427.79  5488.8  432.72  5643.4  434.80
  5659.2  435.98  5671.1  439.73  5686.4  442.12  5691.4  439.89  5694.3  439.89
#Mann=3,-1,0
  4059.7    0.05       0  5016.7    0.04       0  5029.0    0.05       0
Bank Sta=5016.7,5029
Exp/Cntr=0.3,0.1

Type RM Length L Ch R = 1,78640,474,474,474
BEGIN DESCRIPTION:
Clear Creek 126.0
END DESCRIPTION:
XS GIS Cut Line= 3
      2768425.98      6805161.04      2768176.00      6805711.00
      2767905.94      6806254.72
#Sta/Elev= 30
  4391.8  439.54  4423.6  436.96  4468.6  430.61  4498.3  428.36  4512.6  426.42
  4549.9  423.12  4624.6  420.72  4722.4  418.54  4798.2  418.20  4831.1  416.95
  4889.4  416.07  4958.6  416.23  4973.9  415.55  4987.1  411.62  4993.2  408.74
  5003.7  408.18  5005.5  407.68  5014.4  407.68  5016.1  408.18  5018.2  412.10
  5026.7  415.39  5032.3  415.72  5166.7  415.26  5250.8  417.19  5340.4  422.11
  5390.8  427.16  5464.9  431.73  5497.2  432.33  5531.9  434.21  5603.0  436.56
#Mann=3,-1,0
  4391.8    0.05       0  5003.7    0.04       0  5016.1    0.05       0
Bank Sta=5003.7,5016.1
Exp/Cntr=0.3,0.1

Type RM Length L Ch R = 1,78166,475,475,475
BEGIN DESCRIPTION:
Clear Creek 125.0
END DESCRIPTION:
XS GIS Cut Line= 3
      2768202.99      6804703.44      2767826.00      6805461.00
      2767425.99      6806061.01
#Sta/Elev= 30
  4149.5  446.00  4191.5  443.95  4242.7  438.57  4248.3  439.60  4265.1  437.97
  4337.9  435.86  4377.1  432.65  4539.4  428.12  4668.2  421.10  4914.5  416.33
  4936.9  415.18  4942.5  412.90  4953.1  406.06  4954.8  405.56  4965.5  406.06
  4973.3  410.71  4981.7  411.42  4987.3  414.42  5003.2  413.63  5009.2  415.30
  5039.2  415.67  5168.4  414.53  5261.6  415.65  5342.7  418.24  5348.7  417.59
  5369.8  418.46  5414.8  422.66  5441.9  423.41  5580.1  434.07  5716.8  441.84
#Mann=3,-1,0
  4149.5    0.05       0  4953.1    0.04       0  4965.5    0.05       0
Bank Sta=4953.1,4965.5
Exp/Cntr=0.3,0.1

Type RM Length L Ch R = 1,77691,453,453,453
BEGIN DESCRIPTION:
Clear Creek 124.0
END DESCRIPTION:
XS GIS Cut Line= 3
      2767976.03      6804710.96      2767426.00      6805311.00
      2766975.97      6805561.01
#Sta/Elev= 30
  4185.5  454.36  4206.8  453.14  4249.4  446.42  4284.5  444.83  4306.1  436.30
  4312.9  439.69  4320.5  438.91  4331.1  439.79  4355.4  434.56  4398.0  433.53
  4418.9  429.97  4525.0  420.74  4593.0  416.73  4621.2  415.17  4666.8  412.95
  4753.6  412.55  4918.7  412.57  4957.3  413.45  4964.0  408.67  4965.2  404.78
  4966.9  404.28  4977.6  404.78  4978.2  407.59  4992.4  412.93  5080.9  413.14
  5278.6  420.76  5291.6  423.44  5410.6  432.31  5484.5  437.08  5514.3  441.82
#Mann=12,-1,0
  4185.5    0.05       0  4320.5    0.12       0  4331.1    0.05       0
  4593.0     0.1       0  4621.2    0.05       0  4753.6     0.1       0
  4918.7    0.12       0  4965.2    0.07       0  4977.6    0.12       0
  5080.9    0.05       0  5291.6    0.12       0  5410.6    0.05       0
Bank Sta=4965.2,4977.6
Exp/Cntr=0.3,0.1

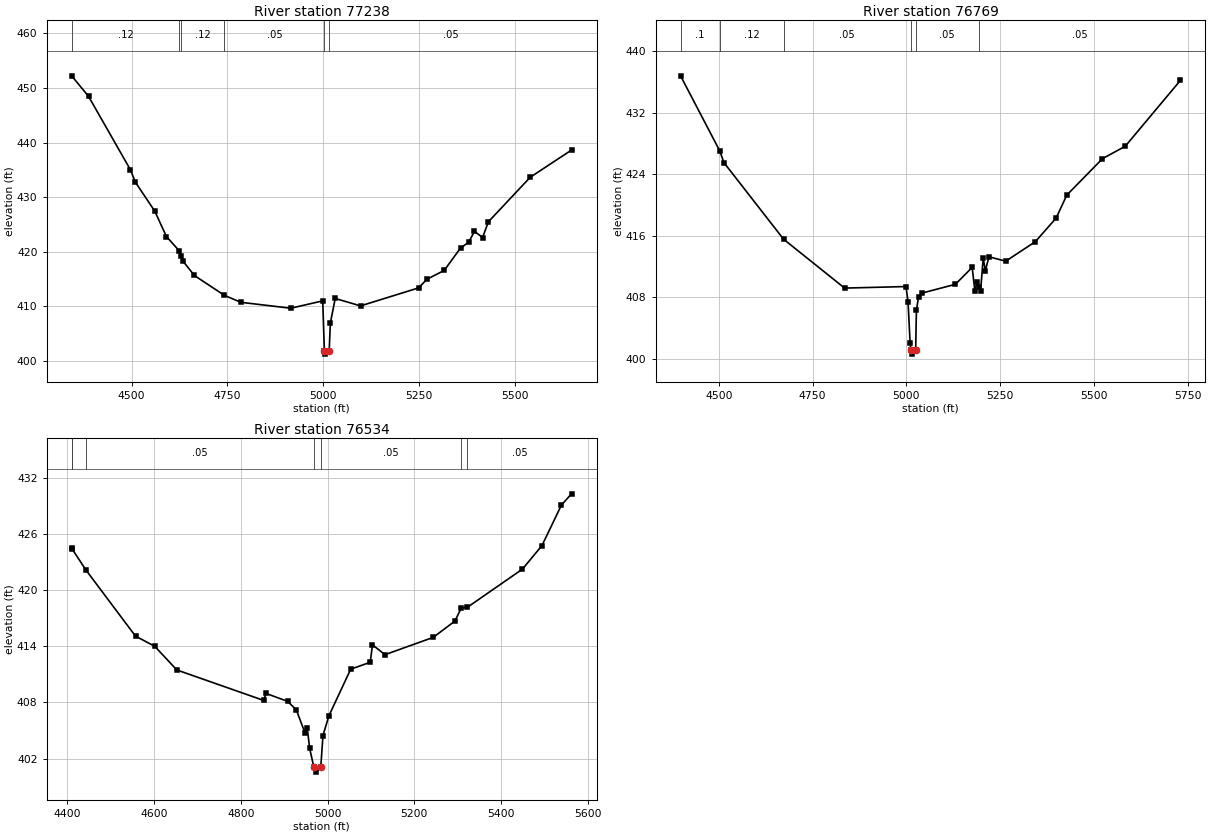
Type RM Length L Ch R = 1,77238,469,469,469
BEGIN DESCRIPTION:
Clear Creek 123.0
END DESCRIPTION:
XS GIS Cut Line= 3
      2767826.02      6804560.99      2767276.00      6804911.00
      2766725.97      6805261.02
#Sta/Elev= 30
  4343.8  452.24  4387.8  448.48  4497.1  435.02  4509.8  432.77  4560.6  427.44
  4591.0  422.79  4624.7  420.15  4630.3  419.27  4633.4  418.35  4663.9  415.65
  4742.3  412.01  4784.9  410.74  4915.3  409.65  4998.7  411.00  5003.0  401.74
  5004.8  401.24  5015.5  401.74  5018.6  406.93  5031.3  411.44  5097.3  410.08
  5248.9  413.38  5270.1  414.94  5315.8  416.59  5358.1  420.68  5379.3  421.73
  5394.5  423.74  5415.7  422.61  5430.9  425.50  5540.1  433.66  5647.7  438.64
#Mann=6,-1,0
  4343.8    0.12       0  4624.7    0.05       0  4630.3    0.12       0
  4742.3    0.05       0  5003.0    0.03       0  5015.5    0.05       0
Bank Sta=5003,5015.5
Exp/Cntr=0.3,0.1

Type RM Length L Ch R = 1,76769,235,235,235
BEGIN DESCRIPTION:
Clear Creek 122.0
END DESCRIPTION:
XS GIS Cut Line= 3
      2767671.01      6804447.83      2767076.00      6804511.00
      2766420.45      6804842.82
#Sta/Elev= 30
  4397.7  436.79  4502.4  427.01  4513.4  425.50  4672.4  415.54  4835.2  409.18
  4998.9  409.38  5004.4  407.39  5010.0  401.99  5012.2  401.09  5014.0  400.59
  5024.7  401.09  5026.7  406.28  5032.3  408.02  5040.9  408.52  5130.6  409.67
  5175.4  411.87  5182.6  408.84  5188.2  409.93  5193.4  409.32  5197.8  408.80
  5204.9  413.12  5210.5  411.44  5220.2  413.25  5265.0  412.68  5344.2  415.23
  5399.5  418.30  5427.7  421.27  5522.8  426.01  5583.7  427.63  5730.8  436.20
#Mann=6,-1,0
  4397.7     0.1       0  4502.4    0.12       0  4672.4    0.05       0
  5012.2    0.03       0  5024.7    0.05       0  5193.4    0.05       0
Bank Sta=5012.2,5024.7
Exp/Cntr=0.3,0.1

Type RM Length L Ch R = 1,76534,98,98,98
BEGIN DESCRIPTION:
Clear1
END DESCRIPTION:
XS GIS Cut Line= 2
      2767503.60      6804215.76      2766374.52      6804449.91
#Sta/Elev= 30
  4409.8  424.48  4410.4  424.43  4442.7  422.15  4557.1  415.08  4601.4  414.00
  4652.3  411.47  4852.9  408.21  4858.0  408.96  4908.2  408.11  4928.2  407.19
  4948.1  404.73  4953.2  405.28  4958.8  403.10  4968.6  401.05  4974.5  400.55
  4984.4  401.05  4989.5  404.46  5003.4  406.59  5053.5  411.55  5098.6  412.29
  5103.7  414.16  5132.5  413.10  5243.9  414.95  5294.1  416.70  5308.2  418.07
  5322.8  418.17  5449.6  422.24  5494.7  424.76  5539.7  429.10  5562.9  430.29
#Mann=7,-1,0
  4409.8    0.05       0  4410.4     0.1       0  4442.7    0.05       0
  4968.6    0.03       0  4984.4    0.05       0  5308.2    0.12       0
  5322.8    0.05       0
Bank Sta=4968.6,4984.4
Exp/Cntr=0.3,0.1