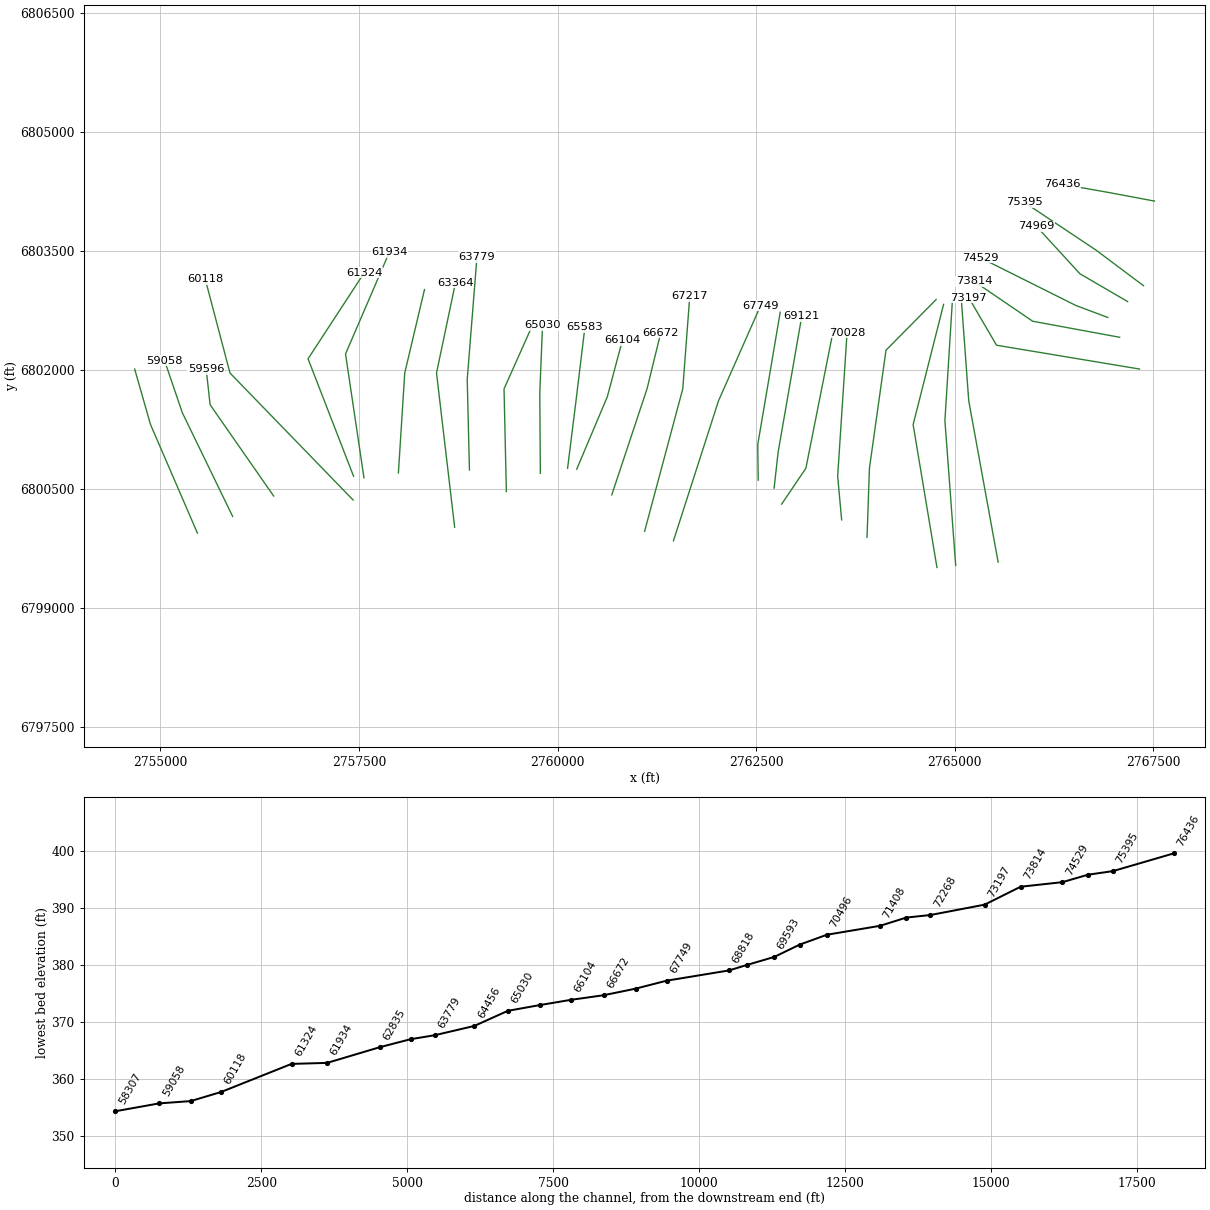
HEC-RAS study Clear Creek.prj: Clear Creek Base Level Engineering

--- Clear Creek.g01 (geometry) --- (continued)

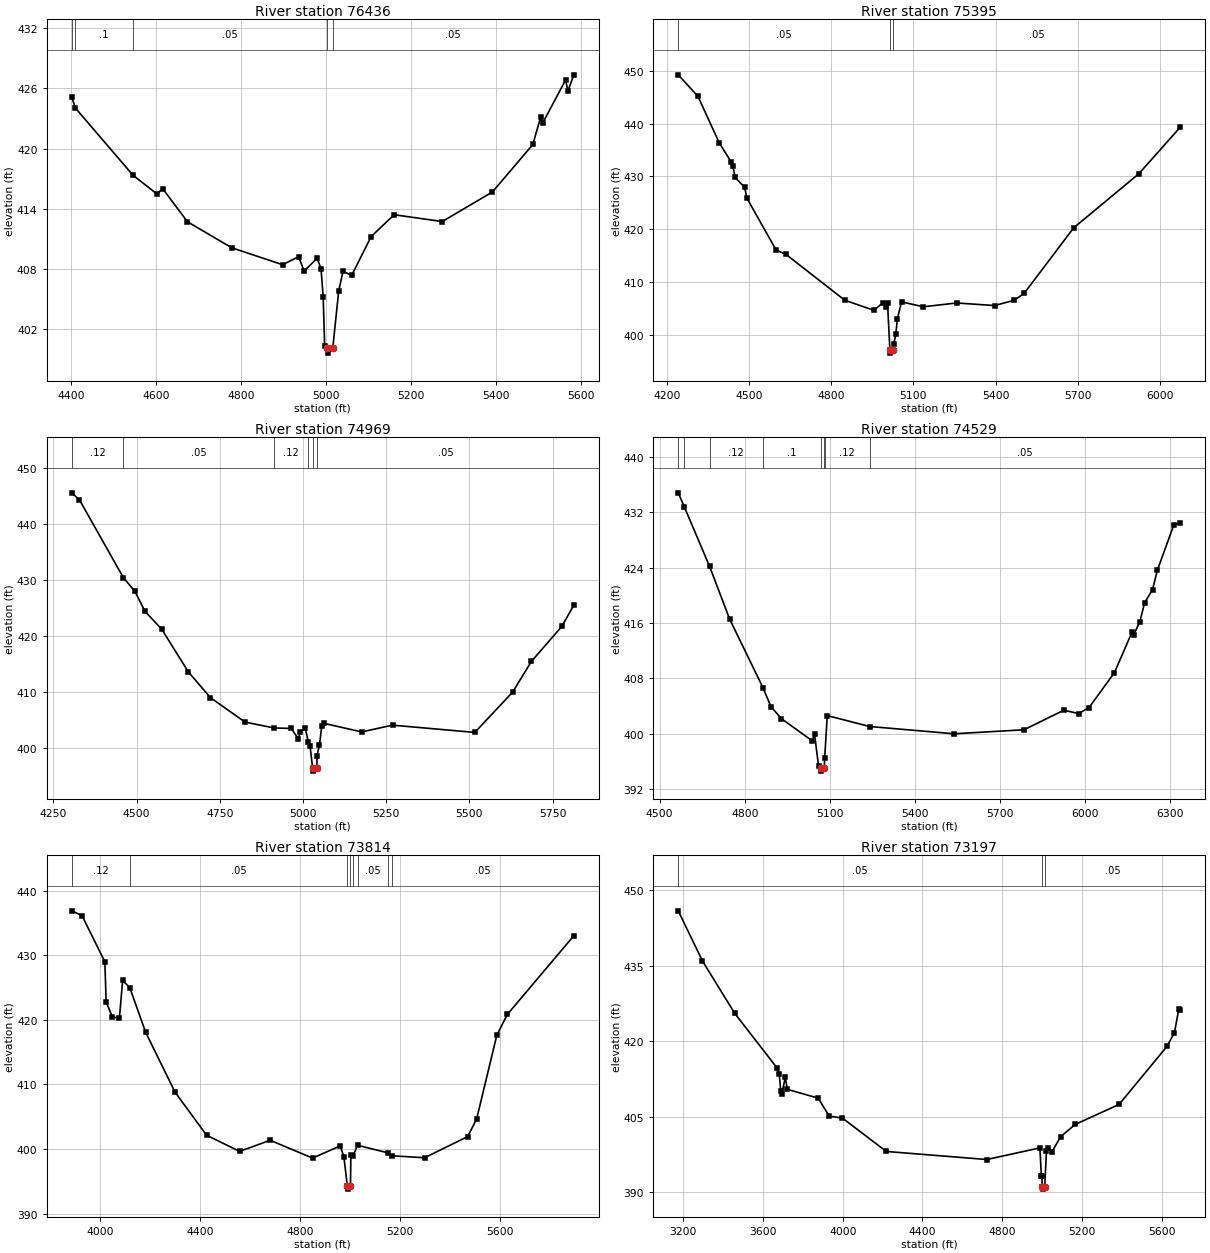
Type RM Length L Ch R = 1,76436,1041,1041,1041
BEGIN DESCRIPTION:
Clear Creek 121.0
END DESCRIPTION:
XS GIS Cut Line= 3
      2767513.65      6804127.04      2766926.20      6804237.28
      2766350.95      6804339.15
#Sta/Elev= 30
  4402.3  425.12  4411.0  424.04  4546.3  417.36  4603.4  415.47  4616.1  416.03
  4674.6  412.72  4778.8  410.13  4898.5  408.44  4936.4  409.24  4949.3  407.80
  4979.9  409.09  4989.0  408.05  4994.1  405.26  4997.6  400.35  5004.1  400.13
  5005.9  399.63  5016.7  400.13  5030.7  405.84  5040.8  407.79  5061.1  407.37
  5107.1  411.25  5161.2  413.42  5274.4  412.74  5392.6  415.69  5487.7  420.42
  5505.9  423.12  5510.9  422.56  5565.0  426.86  5570.1  425.74  5584.2  427.36
#Mann=5,-1,0
  4402.3    0.05       0  4411.0     0.1       0  4546.3    0.05       0
  5004.1    0.04       0  5016.7    0.05       0
Bank Sta=5004.1,5016.7
Exp/Cntr=0.3,0.1

Type RM Length L Ch R = 1,75395,426,426,426
BEGIN DESCRIPTION:
Clear Creek 120.0
END DESCRIPTION:
XS GIS Cut Line= 3
      2767376.02      6803060.98      2766776.00      6803511.00
      2765876.00      6804111.00
#Sta/Elev= 30
  4242.0  449.24  4313.9  445.16  4392.0  436.31  4434.7  432.79  4442.0  431.88
  4449.3  429.80  4484.7  427.91  4492.0  425.92  4599.3  416.03  4634.7  415.24
  4849.3  406.55  4955.6  404.63  4988.9  406.05  4999.5  405.25  5005.6  405.95
  5014.3  397.02  5016.0  396.52  5026.9  397.02  5028.1  398.21  5035.6  400.07
  5041.6  403.05  5056.6  406.23  5136.3  405.30  5257.9  406.02  5396.2  405.53
  5468.3  406.54  5504.3  407.86  5684.6  420.25  5922.0  430.48  6073.7  439.33
#Mann=3,-1,0
  4242.0    0.05       0  5014.3    0.04       0  5026.9    0.05       0
Bank Sta=5014.3,5026.9
Exp/Cntr=0.3,0.1

Type RM Length L Ch R = 1,74969,440,440,440
BEGIN DESCRIPTION:
Clear Creek 119.0
END DESCRIPTION:
XS GIS Cut Line= 3
      2767176.02      6802860.99      2766576.00      6803211.00
      2766025.99      6803811.01
#Sta/Elev= 30
  4305.3  445.65  4328.5  444.38  4460.4  430.48  4495.1  428.03  4525.3  424.45
  4575.3  421.29  4655.5  413.64  4722.1  409.02  4825.9  404.66  4913.7  403.60
  4964.8  403.53  4986.3  401.65  4992.1  402.94  5007.0  403.55  5016.1  401.08
  5021.2  400.41  5029.1  396.39  5030.9  395.89  5041.7  396.39  5042.2  398.67
  5049.6  400.52  5056.4  403.96  5063.8  404.42  5176.6  402.90  5269.1  404.11
  5516.4  402.81  5629.8  410.01  5686.6  415.52  5778.4  421.81  5813.9  425.58
#Mann=6,-1,0
  4305.3    0.12       0  4460.4    0.05       0  4913.7    0.12       0
  5016.1    0.05       0  5029.1    0.07       0  5041.7    0.05       0
Bank Sta=5029.1,5041.7
Exp/Cntr=0.3,0.1

Type RM Length L Ch R = 1,74529,715,715,715
BEGIN DESCRIPTION:
Clear Creek 118.0
END DESCRIPTION:
XS GIS Cut Line= 3
      2766925.99      6802661.00      2766526.00      6802811.00
      2765326.03      6803410.98
#Sta/Elev= 30
  4565.8  434.82  4587.4  432.77  4676.1  424.20  4746.5  416.60  4864.1  406.66
  4892.4  403.91  4928.9  402.18  5037.7  398.96  5046.1  399.91  5060.1  395.31
  5067.8  395.08  5069.5  394.58  5080.4  395.08  5081.6  396.44  5090.8  402.61
  5240.4  401.03  5538.0  399.98  5784.0  400.56  5923.8  403.38  5976.9  402.91
  6013.2  403.78  6102.6  408.83  6164.1  414.65  6169.7  414.23  6192.1  416.19
  6208.9  418.94  6236.8  420.82  6253.6  423.62  6312.3  430.24  6334.6  430.46
#Mann=8,-1,0
  4565.8    0.12       0  4587.4     0.1       0  4676.1    0.12       0
  4864.1     0.1       0  5067.8    0.07       0  5080.4     0.1       0
  5081.6    0.12       0  5240.4    0.05       0
Bank Sta=5067.8,5080.4
Exp/Cntr=0.3,0.1

Type RM Length L Ch R = 1,73814,617,617,617
BEGIN DESCRIPTION:
Clear Creek 117.0
END DESCRIPTION:
XS GIS Cut Line= 3
      2767076.01      6802411.00      2765981.99      6802612.96
      2765242.58      6803116.70
#Sta/Elev= 30
  3887.5  436.91  3928.2  436.18  4019.7  429.02  4025.0  422.79  4050.2  420.42
  4078.0  420.33  4090.9  426.12  4119.5  425.00  4182.4  418.13  4300.0  408.83
  4426.5  402.13  4558.7  399.63  4680.7  401.35  4850.0  398.59  4961.0  400.48
  4975.6  398.72  4989.1  394.28  4990.9  393.78  5001.7  394.28  5003.3  399.08
  5012.4  398.97  5030.0  400.57  5151.8  399.40  5168.7  398.95  5297.7  398.64
  5470.2  401.92  5506.1  404.65  5586.8  417.64  5628.7  420.85  5894.7  433.05
#Mann=8,-1,0
  3887.5    0.12       0  4119.5    0.05       0  4989.1    0.04       0
  5001.7    0.05       0  5012.4    0.12       0  5030.0    0.05       0
  5151.8    0.12       0  5168.7    0.05       0
Bank Sta=4989.1,5001.7
Exp/Cntr=0.3,0.1

Type RM Length L Ch R = 1,73197,929,929,929
BEGIN DESCRIPTION:
Clear Creek 116.0
END DESCRIPTION:
XS GIS Cut Line= 3
      2767325.97      6802011.01      2765526.00      6802311.00
      2765176.01      6802910.99
#Sta/Elev= 30
  3174.5  445.89  3296.1  435.93  3458.3  425.51  3671.2  414.66  3681.4  413.52
  3689.0  410.06  3694.0  409.42  3711.8  412.86  3721.9  410.44  3876.5  408.70
  3932.3  405.13  3998.2  404.74  4218.7  398.11  4723.0  396.51  4989.2  398.82
  4996.8  393.16  4999.3  393.16  5000.8  391.13  5002.6  390.63  5013.5  391.13
  5022.4  398.26  5028.7  398.87  5050.2  398.03  5093.2  401.05  5167.6  403.50
  5386.7  407.45  5627.3  418.98  5664.6  421.72  5686.1  426.34  5693.9  426.28
#Mann=3,-1,0
  3174.5    0.05       0  5000.8    0.04       0  5013.5    0.05       0
Bank Sta=5000.8,5013.5
Exp/Cntr=0.3,0.1

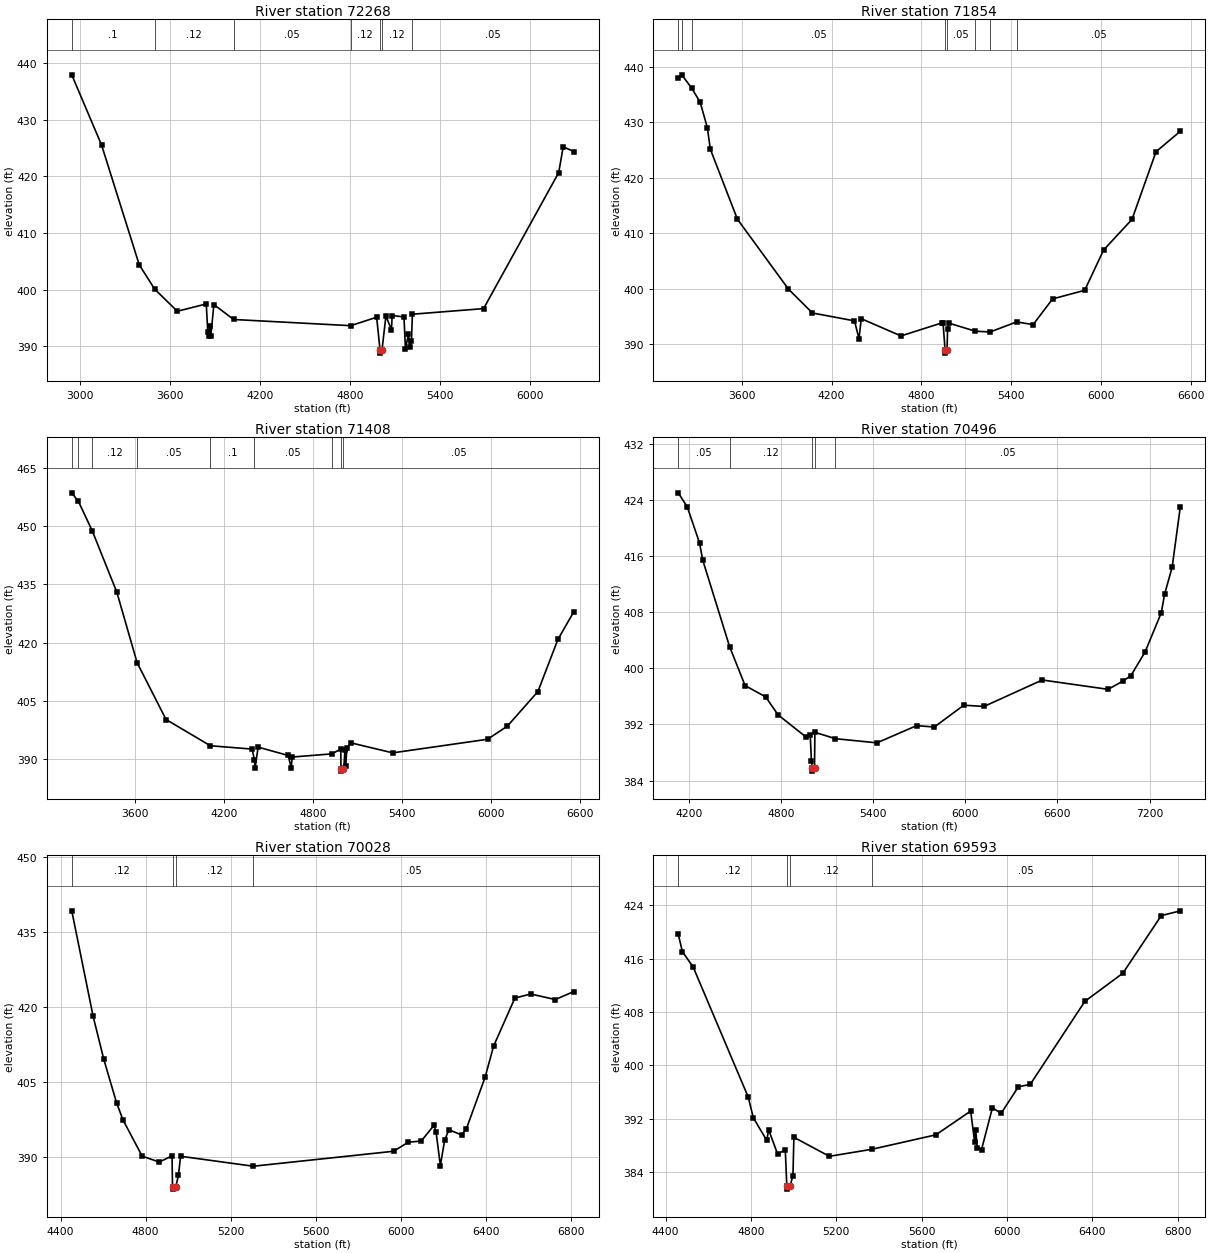
Type RM Length L Ch R = 1,72268,414,414,414
BEGIN DESCRIPTION:
Clear Creek 115.0
END DESCRIPTION:
XS GIS Cut Line= 3
      2765546.18      6799578.06      2765176.00      6801611.00
      2765082.37      6802891.81
#Sta/Elev= 30
  2944.0  437.88  3142.8  425.51  3394.2  404.39  3497.1  400.10  3648.3  396.19
  3841.5  397.48  3851.6  392.61  3861.4  391.87  3866.5  393.68  3872.0  391.83
  3892.3  397.37  4024.6  394.74  4805.2  393.65  4978.6  395.14  5001.5  389.31
  5003.2  388.81  5014.2  389.31  5040.5  395.39  5077.3  392.91  5082.3  395.44
  5160.8  395.20  5170.8  389.53  5190.9  392.19  5200.9  389.85  5210.9  391.02
  5217.2  395.67  5692.2  396.66  6193.5  420.64  6223.6  425.20  6294.6  424.34
#Mann=7,-1,0
  2944.0     0.1       0  3497.1    0.12       0  4024.6    0.05       0
  4805.2    0.12       0  5001.5    0.07       0  5014.2    0.12       0
  5217.2    0.05       0
Bank Sta=5001.5,5014.2
Exp/Cntr=0.3,0.1

Type RM Length L Ch R = 1,71854,446,446,446
BEGIN DESCRIPTION:
Clear Creek 114.0
END DESCRIPTION:
XS GIS Cut Line= 3
      2765011.74      6799537.23      2764876.00      6801361.00
      2764970.82      6802882.13
#Sta/Elev= 30
  3176.1  438.07  3200.1  438.56  3266.7  436.13  3323.0  433.59  3370.4  429.02
  3390.5  425.14  3571.0  412.53  3911.9  399.91  4072.3  395.60  4353.1  394.18
  4383.2  390.95  4398.4  394.57  4663.5  391.46  4938.6  393.83  4944.7  393.72
  4958.5  388.86  4960.2  388.36  4971.2  388.86  4974.8  392.63  4984.9  393.76
  5161.1  392.31  5259.4  392.18  5436.0  393.99  5546.0  393.50  5676.2  398.14
  5890.3  399.69  6016.9  406.97  6206.3  412.48  6366.8  424.69  6529.0  428.38
#Mann=8,-1,0
  3176.1    0.05       0  3200.1    0.12       0  3266.7    0.05       0
  4958.5    0.07       0  4971.2    0.05       0  5161.1    0.05       0
  5259.4    0.12       0  5436.0    0.05       0
Bank Sta=4958.5,4971.2
Exp/Cntr=0.3,0.1

Type RM Length L Ch R = 1,71408,912,912,912
BEGIN DESCRIPTION:
Clear Creek 113.0
END DESCRIPTION:
XS GIS Cut Line= 3
      2764775.99      6799511.04      2764476.00      6801311.00
      2764859.46      6802825.22
#Sta/Elev= 30
  3174.5  458.54  3219.5  456.33  3312.4  448.78  3478.6  432.96  3615.1  414.84
  3810.6  400.20  4109.6  393.45  4391.0  392.59  4406.3  389.91  4411.3  387.77
  4431.6  393.09  4634.3  390.96  4654.6  387.84  4662.2  390.55  4929.3  391.36
  4989.1  392.61  4990.4  387.42  4992.2  386.92  5003.2  387.42  5009.6  387.61
  5017.2  392.34  5022.4  388.22  5030.2  392.87  5058.2  394.19  5339.7  391.62
  5979.3  395.12  6113.4  398.52  6318.9  407.40  6453.8  420.81  6561.3  427.96
#Mann=9,-1,0
  3174.5    0.12       0  3219.5    0.05       0  3312.4    0.12       0
  3615.1    0.05       0  4109.6     0.1       0  4406.3    0.05       0
  4929.3    0.12       0  4990.4    0.05       0  5003.2    0.05       0
Bank Sta=4990.4,5003.2
Exp/Cntr=0.3,0.1

Type RM Length L Ch R = 1,70496,468,468,468
BEGIN DESCRIPTION:
Clear Creek 112.0
END DESCRIPTION:
XS GIS Cut Line= 4
      2763895.86      6799892.11      2763926.00      6800761.00
      2764134.50      6802248.05      2764765.54      6802886.52
#Sta/Elev= 30
  4130.9  424.99  4189.8  422.98  4269.9  417.83  4289.9  415.44  4465.6  403.06
  4566.3  397.53  4700.1  395.93  4780.2  393.38  4960.3  390.25  4990.3  390.43
  4997.8  386.86  5002.6  385.85  5004.6  385.35  5018.2  385.85  5020.5  390.88
  5154.1  389.97  5424.4  389.38  5683.2  391.83  5798.0  391.63  5989.9  394.74
  6121.4  394.56  6500.9  398.33  6929.3  397.00  7028.3  398.20  7077.8  398.95
  7169.7  402.30  7275.8  407.91  7297.0  410.53  7346.5  414.40  7399.6  423.00
#Mann=5,-1,0
  4130.9    0.05       0  4465.6    0.12       0  5002.6    0.07       0
  5018.2    0.12       0  5154.1    0.05       0
Bank Sta=5002.6,5018.2
Exp/Cntr=0.3,0.1

Type RM Length L Ch R = 1,70028,435,435,435
BEGIN DESCRIPTION:
Clear Creek 111.0
END DESCRIPTION:
XS GIS Cut Line= 3
      2763576.00      6800111.04      2763526.00      6800661.00
      2763644.29      6802467.91
#Sta/Elev= 30
  4452.7  439.25  4553.1  418.18  4603.3  409.58  4663.5  400.87  4693.6  397.46
  4784.0  390.20  4864.3  389.03  4924.6  390.25  4926.8  384.11  4928.8  383.61
  4942.4  384.11  4954.7  386.37  4964.8  390.18  5306.8  388.19  5967.0  391.18
  6037.1  393.00  6097.3  393.22  6157.7  396.37  6167.4  394.96  6187.5  388.33
  6207.5  393.36  6227.5  395.49  6287.7  394.43  6309.4  395.61  6397.9  405.97
  6438.0  412.21  6538.2  421.81  6612.8  422.62  6728.6  421.51  6815.7  423.12
#Mann=4,-1,0
  4452.7    0.12       0  4926.8    0.07       0  4942.4    0.12       0
  5306.8    0.05       0
Bank Sta=4926.8,4942.4
Exp/Cntr=0.3,0.1

Type RM Length L Ch R = 1,69593,472,472,472
BEGIN DESCRIPTION:
Clear Creek 110.0
END DESCRIPTION:
XS GIS Cut Line= 3
      2762820.69      6800309.15      2763126.00      6800761.00
      2763478.09      6802535.07
#Sta/Elev= 30
  4458.9  419.67  4478.3  417.06  4529.2  414.72  4787.0  395.25  4810.9  392.15
  4873.9  388.75  4882.8  390.35  4924.8  386.71  4960.8  387.35  4967.9  381.95
  4969.9  381.45  4983.6  381.95  4996.7  383.48  5001.2  389.22  5167.3  386.37
  5367.9  387.43  5666.9  389.59  5830.0  393.15  5848.6  388.53  5853.7  390.34
  5860.6  387.57  5881.0  387.39  5932.0  393.65  5972.8  392.81  6053.3  396.78
  6109.5  397.16  6365.4  409.60  6543.7  413.82  6723.6  422.45  6812.9  423.17
#Mann=4,-1,0
  4458.9    0.12       0  4967.9    0.07       0  4983.6    0.12       0
  5367.9    0.05       0
Bank Sta=4967.9,4983.6
Exp/Cntr=0.3,0.1

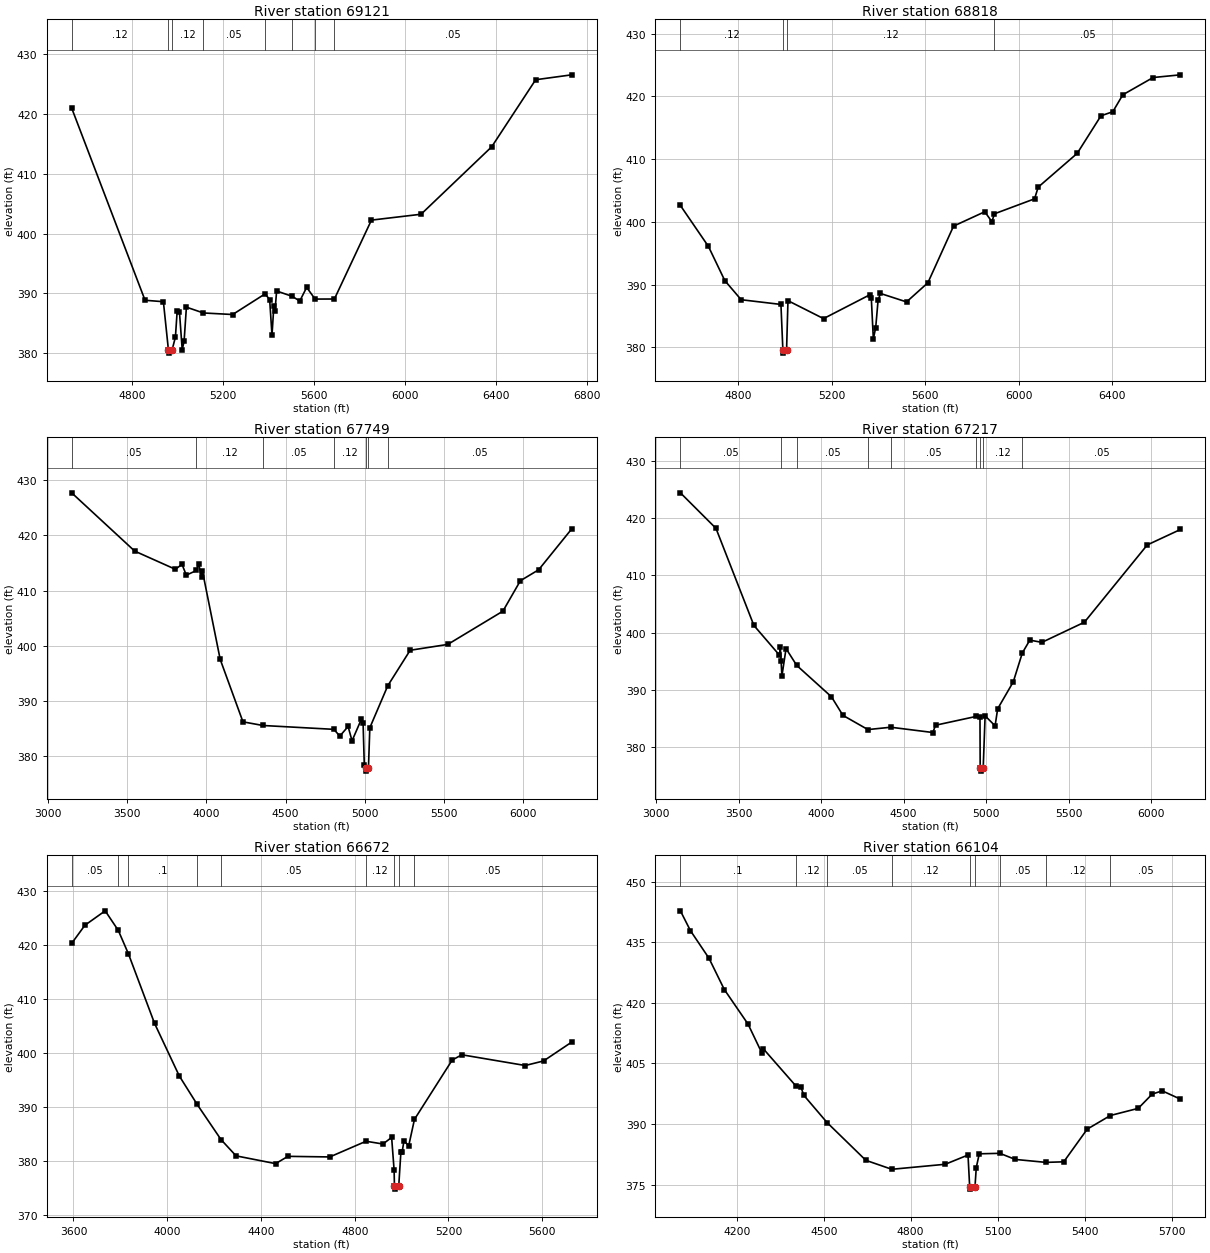
Type RM Length L Ch R = 1,69121,303,303,303
BEGIN DESCRIPTION:
Clear Creek 109.0
END DESCRIPTION:
XS GIS Cut Line= 3
      2762726.00      6800511.00      2762776.00      6800961.00
      2763074.38      6802676.78
#Sta/Elev= 30
  4536.6  420.97  4858.6  388.86  4939.1  388.62  4961.3  380.53  4963.3  380.03
  4977.1  380.53  4991.9  382.71  4999.5  387.01  5009.7  386.85  5021.7  380.61
  5030.0  382.04  5040.1  387.71  5114.6  386.74  5243.1  386.48  5385.5  389.93
  5405.5  388.97  5415.7  383.01  5423.9  387.93  5429.0  387.09  5436.0  390.41
  5504.9  389.51  5537.5  388.73  5567.9  391.01  5604.8  389.06  5689.6  389.07
  5852.1  402.25  6069.8  403.23  6379.9  414.50  6572.8  425.70  6730.9  426.52
#Mann=8,-1,0
  4536.6    0.12       0  4961.3    0.07       0  4977.1    0.12       0
  5114.6    0.05       0  5385.5    0.12       0  5504.9    0.05       0
  5604.8    0.12       0  5689.6    0.05       0
Bank Sta=4961.3,4977.1
Exp/Cntr=0.3,0.1

Type RM Length L Ch R = 1,68818,1069,1069,1069
BEGIN DESCRIPTION:
Clear Creek 108.0
END DESCRIPTION:
XS GIS Cut Line= 3
      2762526.00      6800610.98      2762519.94      6801058.44
      2762802.65      6802726.14
#Sta/Elev= 30
  4552.5  402.61  4672.5  396.08  4742.5  390.64  4812.5  387.59  4982.6  386.84
  4990.9  379.58  4992.9  379.08  5006.7  379.58  5012.7  387.44  5164.9  384.58
  5364.0  388.40  5369.1  387.93  5377.9  381.35  5388.0  383.14  5398.2  387.52
  5408.3  388.59  5519.9  387.24  5611.2  390.29  5721.0  399.32  5854.6  401.61
  5885.0  400.02  5895.8  401.28  6067.6  403.67  6083.1  405.53  6250.1  410.92
  6351.6  416.90  6402.3  417.55  6445.1  420.25  6574.7  423.00  6691.5  423.43
#Mann=4,-1,0
  4552.5    0.12       0  4990.9    0.07       0  5006.7    0.12       0
  5895.8    0.05       0
Bank Sta=4990.9,5006.7
Exp/Cntr=0.3,0.1

Type RM Length L Ch R = 1,67749,532,532,532
BEGIN DESCRIPTION:
Clear Creek 107.0
END DESCRIPTION:
XS GIS Cut Line= 3
      2761458.81      6799847.19      2762026.00      6801611.00
      2762554.99      6802807.73
#Sta/Elev= 30
  3148.1  427.71  3546.6  417.15  3803.3  413.86  3845.9  414.74  3872.8  412.79
  3937.1  413.64  3950.4  414.89  3969.0  412.44  3974.3  413.61  4087.0  397.54
  4231.0  386.21  4357.1  385.55  4805.8  384.85  4843.3  383.63  4895.8  385.37
  4920.6  382.77  4979.6  386.68  4990.4  386.04  4998.2  378.31  5006.1  377.78
  5008.1  377.28  5024.3  377.78  5033.1  385.14  5146.5  392.75  5288.0  399.18
  5525.7  400.24  5874.5  406.27  5984.9  411.78  6100.6  413.77  6309.3  421.17
#Mann=7,-1,0
  3148.1    0.05       0  3937.1    0.12       0  4357.1    0.05       0
  4805.8    0.12       0  5006.1    0.07       0  5024.3    0.12       0
  5146.5    0.05       0
Bank Sta=5006.1,5024.3
Exp/Cntr=0.3,0.1

Type RM Length L Ch R = 1,67217,545,545,545
BEGIN DESCRIPTION:
Clear Creek 106.0
END DESCRIPTION:
XS GIS Cut Line= 3
      2761095.50      6799966.47      2761576.00      6801761.00
      2761664.38      6802931.42
#Sta/Elev= 30
  3146.5  424.38  3362.2  418.19  3592.1  401.27  3747.1  396.09  3752.3  397.46
  3756.9  395.09  3762.0  392.46  3787.1  397.23  3851.9  394.30  4062.2  388.84
  4131.9  385.60  4283.4  383.12  4421.9  383.53  4676.9  382.61  4693.7  383.88
  4939.1  385.41  4962.8  385.23  4964.1  376.38  4966.1  375.88  4982.3  376.38
  4993.9  385.52  5054.4  383.77  5070.0  386.74  5164.7  391.44  5219.5  396.47
  5265.0  398.71  5338.2  398.32  5595.9  401.83  5977.0  415.30  6178.0  417.99
#Mann=9,-1,0
  3146.5    0.05       0  3756.9    0.12       0  3851.9    0.05       0
  4283.4    0.12       0  4421.9    0.05       0  4939.1    0.12       0
  4964.1    0.07       0  4982.3    0.12       0  5219.5    0.05       0
Bank Sta=4964.1,4982.3
Exp/Cntr=0.3,0.1

Type RM Length L Ch R = 1,66672,568,568,568
BEGIN DESCRIPTION:
Clear Creek 105.0
END DESCRIPTION:
XS GIS Cut Line= 3
      2760682.31      6800425.30      2761126.00      6801761.00
      2761298.71      6802466.29
#Sta/Elev= 30
  3592.2  420.31  3648.6  423.67  3735.2  426.35  3791.1  422.72  3834.7  418.34
  3945.9  405.47  4051.3  395.73  4127.7  390.44  4229.6  383.91  4293.7  380.90
  4462.3  379.46  4515.0  380.81  4693.6  380.70  4848.3  383.61  4920.5  383.10
  4957.5  384.32  4968.1  378.22  4969.5  375.23  4971.5  374.73  4987.7  375.23
  4997.0  381.60  5002.2  381.60  5010.0  383.65  5030.6  382.82  5054.9  387.67
  5215.9  398.67  5257.1  399.65  5527.5  397.66  5605.6  398.50  5725.8  402.00
#Mann=9,-1,0
  3592.2    0.05       0  3791.1    0.12       0  3834.7     0.1       0
  4127.7    0.12       0  4229.6    0.05       0  4848.3    0.12       0
  4969.5    0.07       0  4987.7    0.12       0  5054.9    0.05       0
Bank Sta=4969.5,4987.7
Exp/Cntr=0.3,0.1

Type RM Length L Ch R = 1,66104,521,521,521
BEGIN DESCRIPTION:
Clear Creek 104.0
END DESCRIPTION:
XS GIS Cut Line= 3
      2760240.88      6800749.16      2760626.00      6801661.00
      2760815.69      6802371.58
#Sta/Elev= 30
  4005.4  442.78  4040.0  437.88  4104.1  431.04  4156.9  423.31  4238.9  414.74
  4286.3  407.63  4291.7  408.63  4404.2  399.42  4421.1  399.26  4430.8  397.17
  4511.6  390.38  4645.3  381.04  4734.9  378.82  4919.2  380.06  4997.8  382.35
  5003.6  374.41  5005.6  373.91  5021.8  374.41  5026.3  379.24  5036.6  382.65
  5107.7  382.77  5160.8  381.26  5266.6  380.53  5328.2  380.67  5409.2  388.76
  5489.1  392.13  5585.2  393.90  5633.4  397.43  5668.0  398.23  5730.7  396.18
#Mann=9,-1,0
  4005.4     0.1       0  4404.2    0.12       0  4511.6    0.05       0
  4734.9    0.12       0  5003.6    0.07       0  5021.8    0.12       0
  5107.7    0.05       0  5266.6    0.12       0  5489.1    0.05       0
Bank Sta=5003.6,5021.8
Exp/Cntr=0.3,0.1

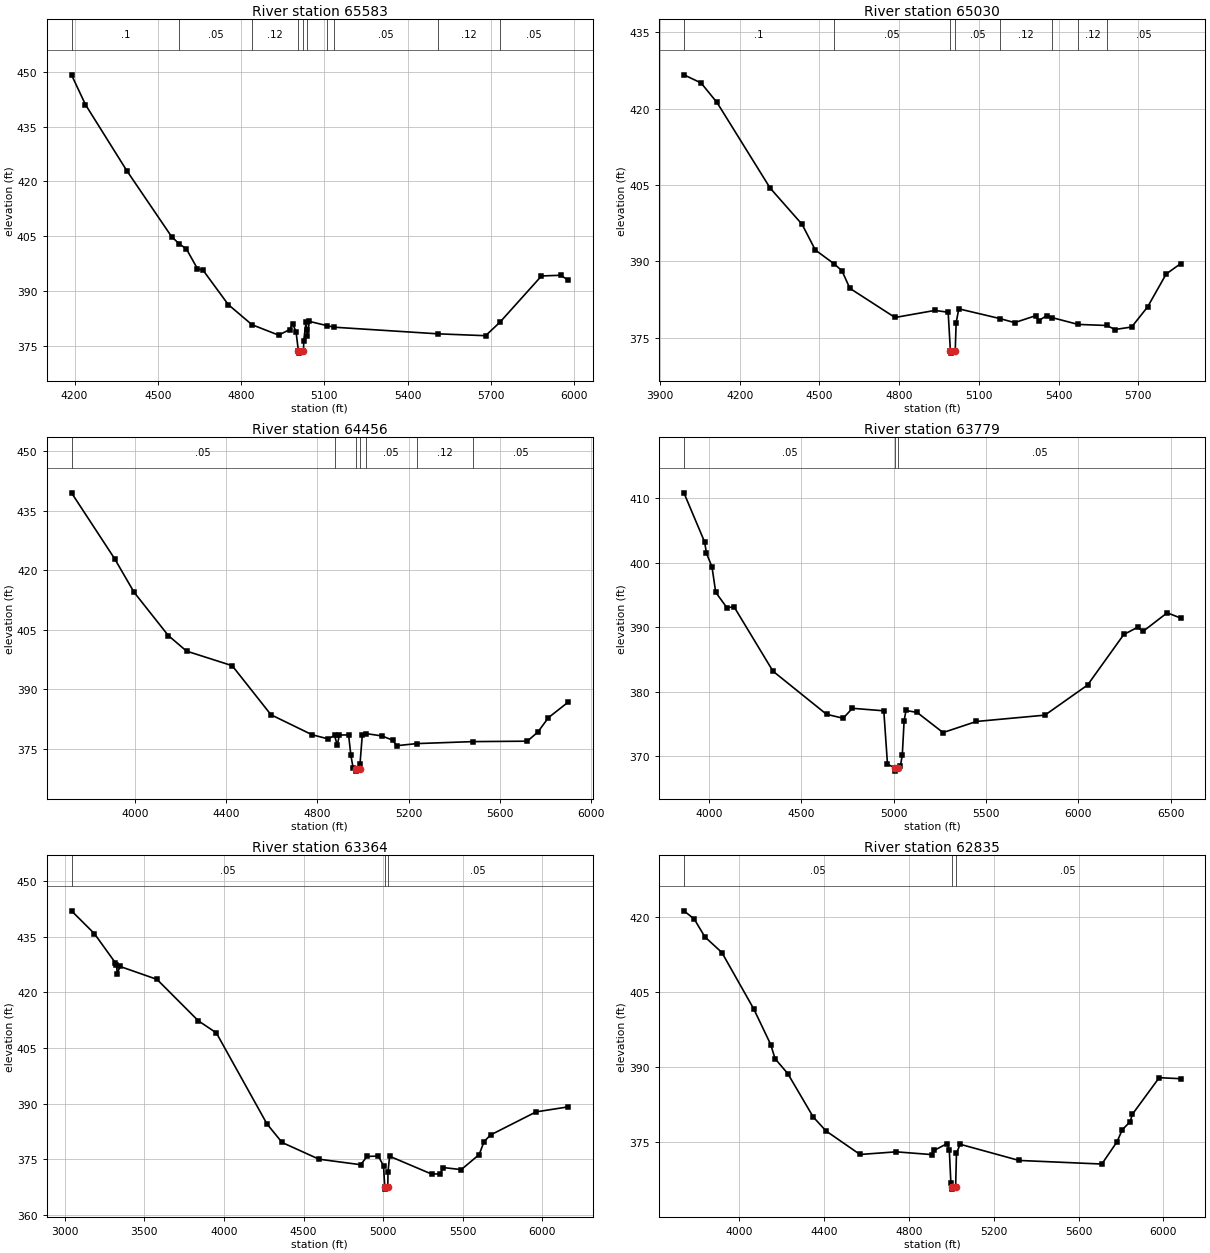
Type RM Length L Ch R = 1,65583,553,553,553
BEGIN DESCRIPTION:
Clear Creek 103.0
END DESCRIPTION:
XS GIS Cut Line= 3
      2760126.00      6800761.00      2760226.00      6801561.00
      2760343.90      6802536.37
#Sta/Elev= 30
  4189.1  449.18  4239.5  441.01  4388.1  422.96  4549.4  404.91  4577.7  402.85
  4602.3  401.60  4642.6  396.12  4662.8  395.71  4753.5  386.31  4839.0  380.79
  4934.9  377.94  4975.2  379.46  4985.3  381.09  4997.8  378.84  5006.3  373.51
  5008.3  373.01  5024.6  373.51  5025.5  376.44  5033.8  381.63  5036.9  379.27
  5038.8  377.82  5045.7  381.70  5109.7  380.52  5135.8  380.10  5509.0  378.29
  5680.3  377.78  5731.8  381.45  5881.7  394.13  5950.4  394.32  5977.8  393.01
#Mann=10,-1,0
  4189.1     0.1       0  4577.7    0.05       0  4839.0    0.12       0
  5006.3    0.07       0  5024.6    0.12       0  5036.9    0.05       0
  5109.7    0.12       0  5135.8    0.05       0  5509.0    0.12       0
  5731.8    0.05       0
Bank Sta=5006.3,5024.6
Exp/Cntr=0.3,0.1

Type RM Length L Ch R = 1,65030,574,574,574
BEGIN DESCRIPTION:
Clear Creek 102.0
END DESCRIPTION:
XS GIS Cut Line= 3
      2759783.24      6800696.46      2759776.00      6801711.00
      2759811.04      6802565.01
#Sta/Elev= 30
  3989.7  426.66  4054.2  425.07  4114.2  421.23  4314.3  404.41  4434.3  397.30
  4484.3  392.25  4553.7  389.58  4584.3  388.19  4614.3  384.72  4784.3  378.99
  4934.3  380.38  4984.3  380.02  4992.6  372.49  4994.6  371.99  5010.9  372.49
  5014.3  377.96  5024.3  380.69  5178.9  378.78  5234.5  377.98  5314.5  379.36
  5324.5  378.33  5354.6  379.36  5375.1  378.97  5473.2  377.63  5581.6  377.42
  5611.9  376.63  5674.8  377.12  5734.9  381.07  5804.9  387.54  5859.0  389.56
#Mann=8,-1,0
  3989.7     0.1       0  4553.7    0.05       0  4992.6    0.04       0
  5010.9    0.05       0  5178.9    0.12       0  5375.1    0.05       0
  5473.2    0.12       0  5581.6    0.05       0
Bank Sta=4992.6,5010.9
Exp/Cntr=0.3,0.1

Type RM Length L Ch R = 1,64456,677,677,677
BEGIN DESCRIPTION:
Clear Creek 101.0
END DESCRIPTION:
XS GIS Cut Line= 3
      2759355.27      6800466.98      2759326.00      6801761.00
      2759685.39      6802566.73
#Sta/Elev= 30
  3722.8  439.50  3911.8  422.89  3996.9  414.44  4146.9  403.53  4226.9  399.60
  4427.0  395.92  4597.0  383.55  4777.1  378.51  4847.1  377.47  4875.7  378.33
  4887.1  375.94  4897.1  378.44  4937.1  378.47  4947.1  373.34  4957.1  370.09
  4967.9  369.84  4969.9  369.34  4986.3  369.84  4987.1  371.17  4997.1  378.39
  5012.9  378.81  5083.4  378.21  5129.9  377.15  5147.6  375.75  5235.6  376.28
  5481.2  376.78  5720.1  376.89  5766.5  379.19  5813.0  382.83  5899.4  386.73
#Mann=7,-1,0
  3722.8    0.05       0  4875.7    0.12       0  4967.9    0.07       0
  4986.3    0.12       0  5012.9    0.05       0  5235.6    0.12       0
  5481.2    0.05       0
Bank Sta=4967.9,4986.3
Exp/Cntr=0.3,0.1

Type RM Length L Ch R = 1,63779,415,415,415
BEGIN DESCRIPTION:
Mapping XS e212a9bd
END DESCRIPTION:
XS GIS Cut Line= 3
      2758890.45      6800738.87      2758862.63      6801881.16
      2758985.34      6803423.25
#Sta/Elev= 30
  3863.6  410.81  3975.8  403.20  3985.8  401.46  4015.8  399.32  4035.8  395.41
  4095.8  393.04  4135.8  393.13  4345.9  383.19  4636.0  376.51  4726.0  375.90
  4776.0  377.44  4946.1  377.05  4966.1  368.77  5006.6  368.21  5008.6  367.71
  5025.6  368.21  5036.2  368.57  5046.2  370.18  5056.2  375.55  5066.3  377.10
  5126.4  376.80  5266.9  373.68  5447.5  375.40  5818.6  376.38  6049.4  381.04
  6245.7  388.87  6320.2  389.98  6350.3  389.36  6480.7  392.23  6553.2  391.42
#Mann=3,-1,0
  3863.6    0.05       0  5006.6    0.04       0  5025.6    0.05       0
Bank Sta=5006.6,5025.6
Exp/Cntr=0.3,0.1

Type RM Length L Ch R = 1,63364,529,529,529
BEGIN DESCRIPTION:
Clear Creek 100.0
END DESCRIPTION:
XS GIS Cut Line= 3
      2758704.27      6800018.23      2758476.00      6801961.00
      2758714.84      6803097.85
#Sta/Elev= 30
  3043.5  442.01  3187.2  435.86  3318.1  428.05  3325.9  427.35  3330.9  425.12
  3348.3  427.02  3579.9  423.54  3839.7  412.37  3952.5  409.13  4270.4  384.59
  4365.3  379.58  4596.9  375.08  4858.7  373.59  4898.9  375.82  4969.4  375.92
  5002.2  373.29  5010.0  367.51  5012.0  367.01  5029.0  367.51  5030.3  371.76
  5040.5  375.87  5306.2  371.03  5357.3  371.17  5377.7  372.82  5490.1  372.27
  5602.5  376.32  5633.2  379.81  5674.0  381.61  5960.1  387.83  6161.3  389.18
#Mann=3,-1,0
  3043.5    0.05       0  5010.0    0.04       0  5029.0    0.05       0
Bank Sta=5010,5029
Exp/Cntr=0.3,0.1

Type RM Length L Ch R = 1,62835,901,901,901
BEGIN DESCRIPTION:
Clear Creek 99.0
END DESCRIPTION:
XS GIS Cut Line= 3
      2757996.28      6800702.38      2758076.00      6801961.00
      2758324.64      6803012.25
#Sta/Elev= 30
  3739.3  421.19  3788.0  419.55  3838.1  415.99  3918.3  412.86  4068.6  401.59
  4148.7  394.47  4168.8  391.67  4228.9  388.68  4349.1  380.00  4409.3  377.22
  4569.6  372.52  4739.9  373.05  4910.3  372.49  4918.3  373.32  4980.4  374.70
  4990.4  373.41  4997.9  366.79  5001.2  366.10  5003.2  365.60  5020.2  366.10
  5024.2  372.76  5041.5  374.56  5319.0  371.33  5709.5  370.61  5781.4  375.08
  5805.7  377.47  5842.8  379.05  5853.3  380.54  5979.9  387.86  6080.7  387.66
#Mann=3,-1,0
  3739.3    0.05       0  5001.2    0.04       0  5020.2    0.05       0
Bank Sta=5001.2,5020.2
Exp/Cntr=0.3,0.1

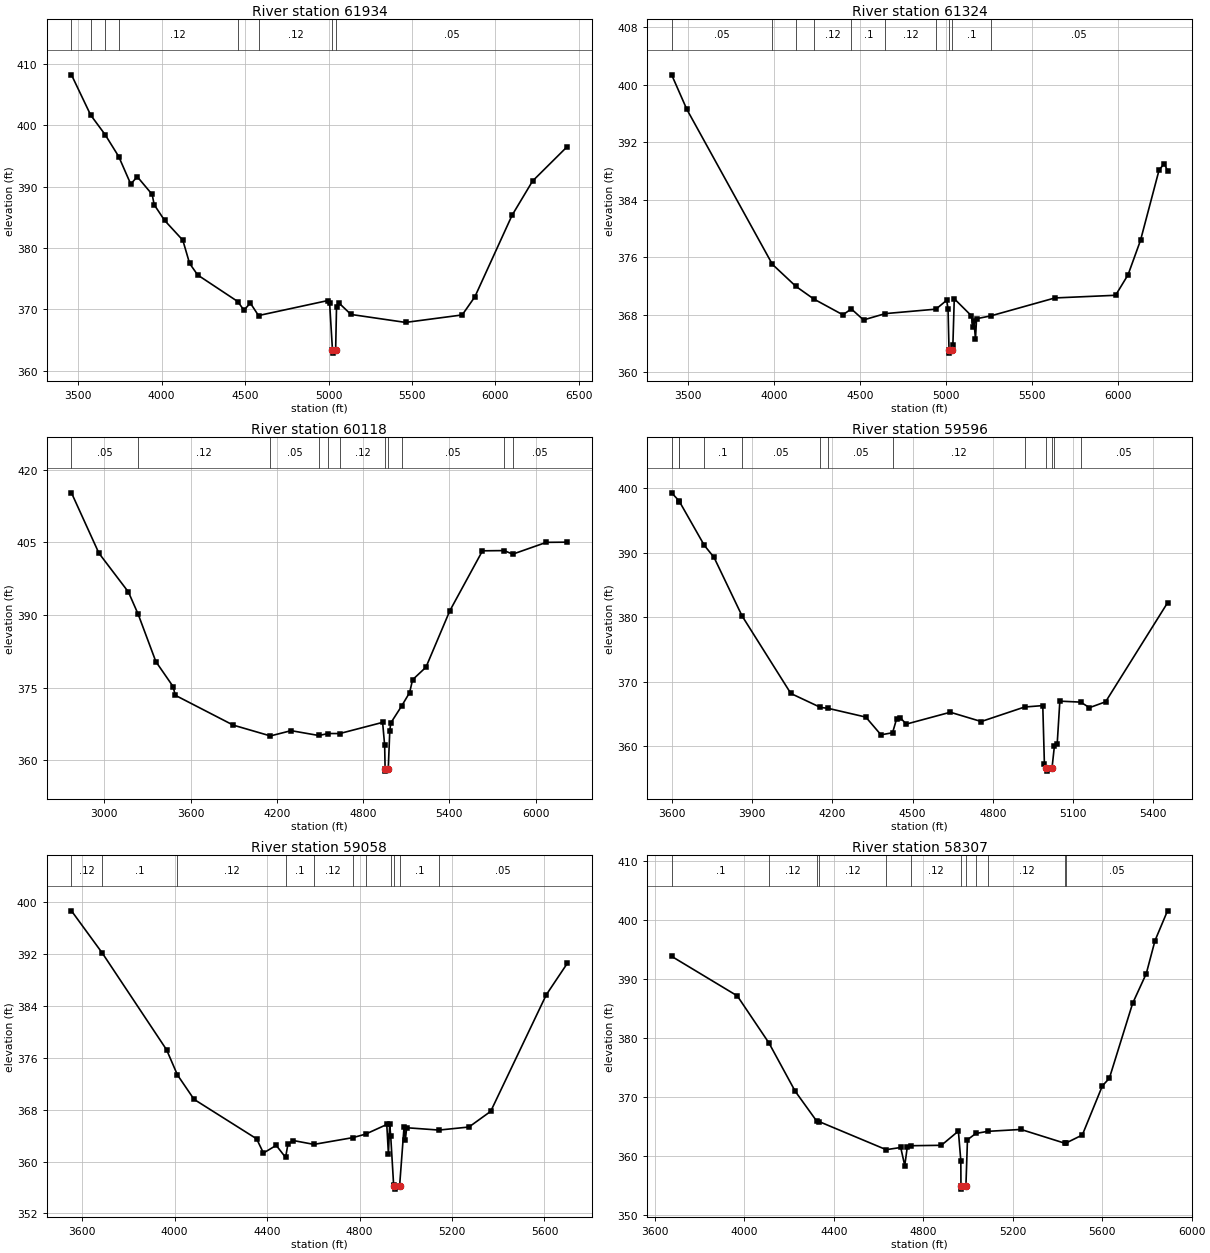
Type RM Length L Ch R = 1,61934,610,610,610
BEGIN DESCRIPTION:
Mapping XS 6018c6fc
END DESCRIPTION:
XS GIS Cut Line= 3
      2757562.69      6800641.03      2757330.60      6802201.00
      2757881.45      6803481.07
#Sta/Elev= 30
  3459.9  408.25  3574.9  401.69  3661.4  398.50  3743.0  394.92  3815.0  390.43
  3854.2  391.63  3943.6  388.73  3955.3  387.07  4018.0  384.50  4127.1  381.27
  4167.6  377.49  4216.0  375.60  4456.0  371.27  4493.4  369.85  4531.5  371.02
  4580.5  368.98  4996.6  371.43  5006.7  370.96  5023.6  363.35  5025.6  362.85
  5042.6  363.35  5047.9  370.30  5063.8  370.99  5134.4  369.16  5461.6  367.86
  5800.8  369.08  5876.8  372.04  6099.5  385.33  6222.7  390.93  6430.6  396.55
#Mann=8,-1,0
  3459.9    0.05       0  3574.9    0.12       0  3661.4    0.05       0
  3743.0    0.12       0  4456.0    0.05       0  4580.5    0.12       0
  5023.6    0.07       0  5042.6    0.05       0
Bank Sta=5023.6,5042.6
Exp/Cntr=0.3,0.1

Type RM Length L Ch R = 1,61324,1206,1206,1206
BEGIN DESCRIPTION:
Mapping XS 0c433fc2
END DESCRIPTION:
XS GIS Cut Line= 3
      2757431.68      6800660.36      2756858.82      6802140.18
      2757567.56      6803226.38
#Sta/Elev= 30
  3403.1  401.40  3491.5  396.59  3988.8  375.03  4125.2  371.97  4229.2  370.21
  4398.9  368.00  4448.0  368.82  4519.0  367.29  4645.5  368.17  4940.1  368.79
  5002.8  370.03  5010.5  368.84  5016.1  363.17  5018.1  362.67  5035.1  363.17
  5038.7  363.82  5046.7  370.24  5146.2  367.87  5155.4  366.30  5161.3  367.14
  5170.0  364.60  5176.4  367.46  5258.7  367.85  5632.1  370.35  5985.0  370.72
  6057.4  373.57  6129.9  378.37  6238.5  388.21  6268.5  389.02  6286.9  388.06
#Mann=10,-1,0
  3403.1    0.05       0  3988.8    0.12       0  4125.2     0.1       0
  4229.2    0.12       0  4448.0     0.1       0  4645.5    0.12       0
  4940.1     0.1       0  5016.1    0.07       0  5035.1     0.1       0
  5258.7    0.05       0
Bank Sta=5016.1,5035.1
Exp/Cntr=0.3,0.1

Type RM Length L Ch R = 1,60118,522,522,522
BEGIN DESCRIPTION:
Clear Creek 98.0
END DESCRIPTION:
XS GIS Cut Line= 3
      2757426.02      6800360.97      2755876.00      6801961.00
      2755565.02      6803141.53
#Sta/Elev= 30
  2772.0  415.23  2963.0  402.76  3168.1  394.74  3236.5  390.11  3358.9  380.37
  3479.3  375.19  3493.4  373.42  3896.5  367.25  4155.7  365.01  4299.6  366.10
  4491.6  365.10  4558.8  365.51  4637.3  365.50  4936.0  367.81  4950.2  363.06
  4953.3  358.24  4955.5  357.74  4975.3  358.24  4985.7  365.97  4992.6  367.68
  5068.3  371.19  5123.8  373.97  5144.5  376.62  5237.5  379.21  5403.0  390.84
  5630.5  403.25  5781.3  403.30  5840.9  402.56  6074.6  405.00  6220.5  405.04
#Mann=11,-1,0
  2772.0    0.05       0  3236.5    0.12       0  4155.7    0.05       0
  4491.6    0.12       0  4558.8     0.1       0  4637.3    0.12       0
  4953.3    0.07       0  4975.3    0.12       0  5068.3    0.05       0
  5781.3    0.12       0  5840.9    0.05       0
Bank Sta=4953.3,4975.3
Exp/Cntr=0.3,0.1

Type RM Length L Ch R = 1,59596,538,538,538
BEGIN DESCRIPTION:
Clear Creek 97.0
END DESCRIPTION:
XS GIS Cut Line= 3
      2756426.01      6800410.99      2755626.00      6801561.00
      2755576.00      6802011.02
#Sta/Elev= 30
  3599.3  399.29  3627.4  398.02  3628.3  397.94  3721.3  391.15  3757.7  389.28
  3862.4  380.21  4044.9  368.18  4155.7  366.02  4184.9  365.87  4325.1  364.52
  4381.8  361.77  4425.1  362.09  4439.9  364.19  4453.4  364.44  4476.4  363.43
  4641.0  365.27  4756.6  363.83  4918.6  366.08  4986.7  366.30  4992.8  357.23
  4999.3  356.64  5001.5  356.14  5021.3  356.64  5030.2  360.05  5040.5  360.30
  5050.5  366.99  5128.4  366.84  5161.2  365.98  5221.6  366.89  5453.0  382.23
#Mann=13,-1,0
  3599.3    0.12       0  3627.4    0.05       0  3628.3    0.12       0
  3721.3     0.1       0  3862.4    0.05       0  4155.7    0.12       0
  4184.9    0.05       0  4425.1    0.12       0  4918.6     0.1       0
  4999.3    0.07       0  5021.3     0.1       0  5030.2    0.12       0
  5128.4    0.05       0
Bank Sta=4999.3,5021.3
Exp/Cntr=0.3,0.1

Type RM Length L Ch R = 1,59058,751,751,751
BEGIN DESCRIPTION:
Clear Creek 96.0
END DESCRIPTION:
XS GIS Cut Line= 3
      2755909.59      6800153.89      2755276.00      6801461.00
      2755053.03      6802116.02
#Sta/Elev= 30
  3554.2  398.67  3688.4  392.11  3965.7  377.23  4012.5  373.36  4084.4  369.59
  4355.0  363.50  4384.5  361.31  4439.8  362.49  4480.3  360.63  4490.5  362.69
  4513.1  363.24  4602.7  362.64  4770.6  363.68  4826.0  364.22  4917.9  365.71
  4925.0  361.17  4930.5  365.77  4934.9  363.94  4947.6  356.34  4951.3  356.24
  4953.5  355.74  4973.4  356.24  4992.7  365.38  4998.3  363.38  5004.0  365.21
  5143.7  364.85  5273.3  365.32  5367.4  367.74  5607.8  385.72  5698.7  390.57
#Mann=11,-1,0
  3554.2    0.12       0  3688.4     0.1       0  4012.5    0.12       0
  4480.3     0.1       0  4602.7    0.12       0  4770.6     0.1       0
  4826.0    0.12       0  4934.9     0.1       0  4951.3    0.07       0
  4973.4     0.1       0  5143.7    0.05       0
Bank Sta=4951.3,4973.4
Exp/Cntr=0.3,0.1

Type RM Length L Ch R = 1,58307,322,322,322
BEGIN DESCRIPTION:
Clear Creek 95.0
END DESCRIPTION:
XS GIS Cut Line= 3
      2755466.07      6799943.92      2754876.00      6801311.00
      2754676.00      6802011.00
#Sta/Elev= 30
  3675.0  393.83  3968.4  387.13  4109.7  379.16  4227.3  370.96  4324.3  365.85
  4335.6  365.79  4634.2  361.05  4699.1  361.42  4717.2  358.36  4728.3  361.43
  4744.1  361.72  4880.8  361.79  4957.0  364.20  4967.9  359.16  4968.5  354.86
  4970.7  354.36  4990.6  354.86  4997.6  362.73  5034.9  363.80  5088.9  364.16
  5236.8  364.48  5434.7  362.12  5438.9  362.19  5511.1  363.54  5600.8  371.87
  5632.0  373.16  5736.0  385.86  5797.1  390.91  5836.1  396.50  5892.0  401.55
#Mann=12,-1,0
  3675.0     0.1       0  4109.7    0.12       0  4324.3     0.1       0
  4335.6    0.12       0  4634.2     0.1       0  4744.1    0.12       0
  4968.5    0.07       0  4990.6    0.12       0  5034.9     0.1       0
  5088.9    0.12       0  5434.7     0.1       0  5438.9    0.05       0
Bank Sta=4968.5,4990.6
Exp/Cntr=0.3,0.1