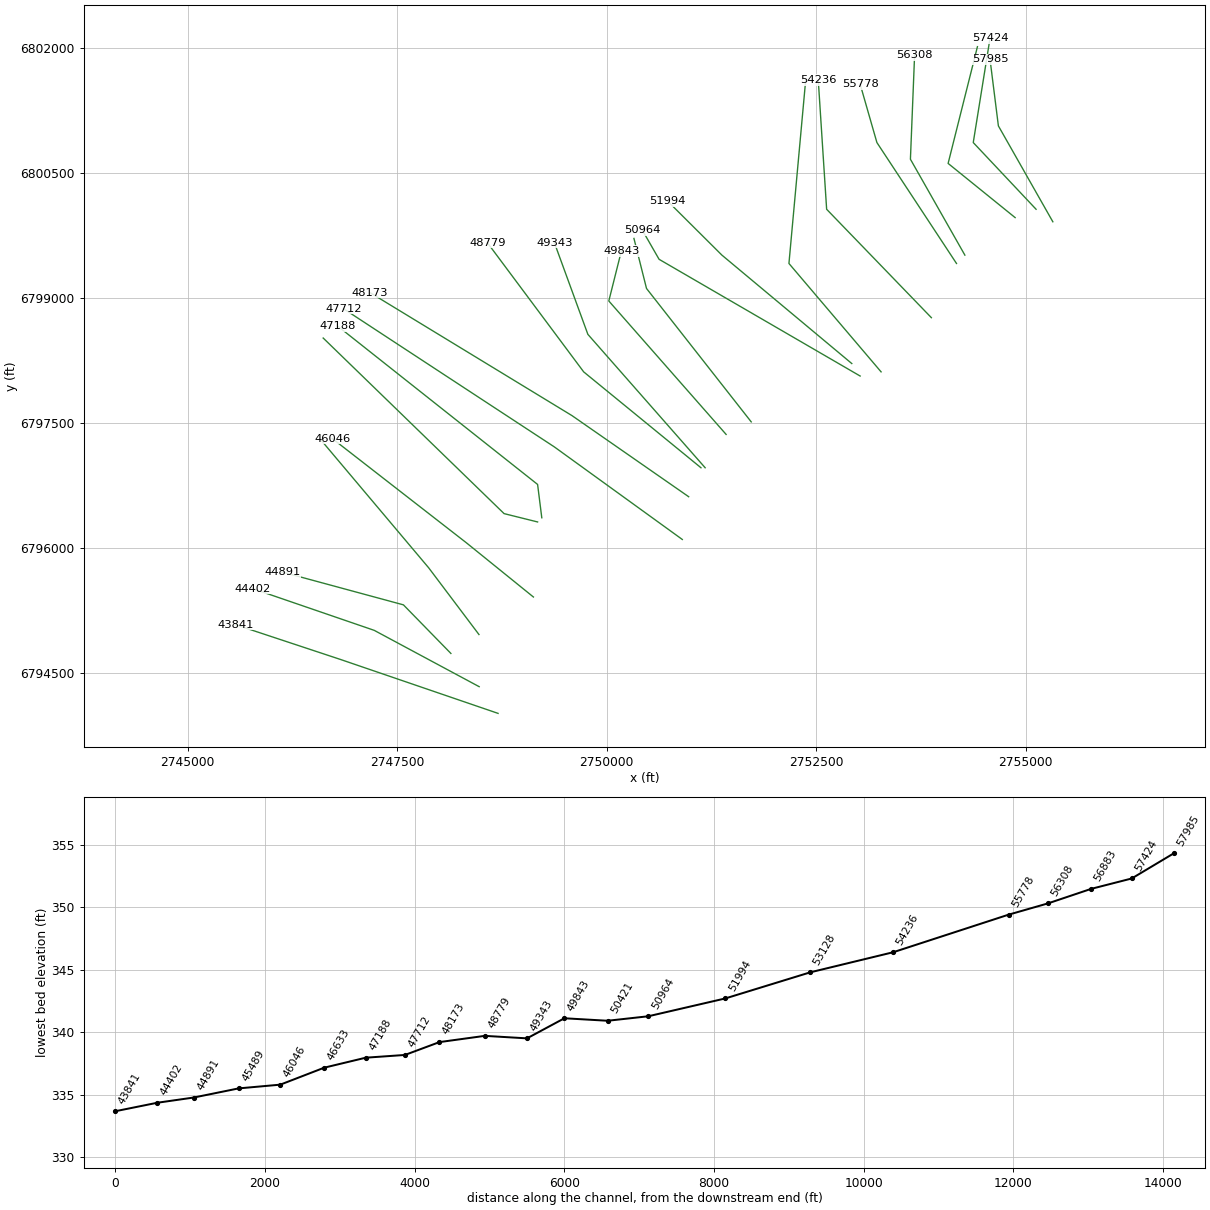
HEC-RAS study Clear Creek.prj: Clear Creek Base Level Engineering

--- Clear Creek.g01 (geometry) --- (continued)

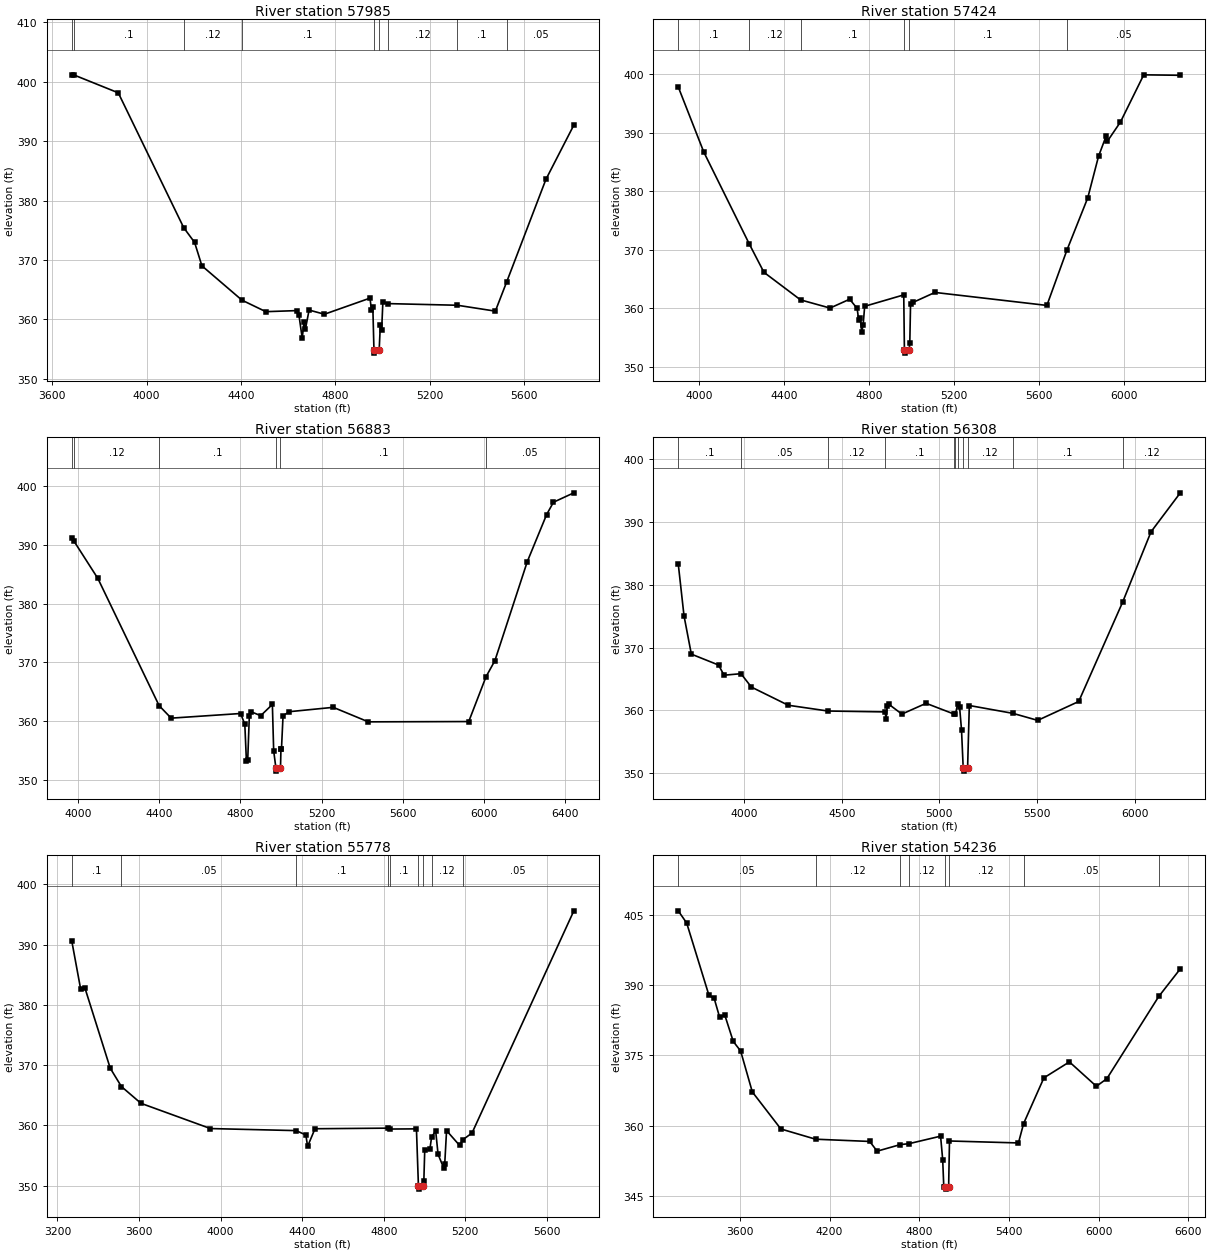
Type RM Length L Ch R = 1,57985,561,561,561
BEGIN DESCRIPTION:
Clear Creek 94.0
END DESCRIPTION:
XS GIS Cut Line= 3
      2755326.00      6799911.01      2754676.00      6801061.00
      2754576.00      6801861.00
#Sta/Elev= 30
  3682.9  401.18  3694.4  401.12  3879.9  398.15  4157.1  375.45  4203.3  372.96
  4234.3  369.02  4403.9  363.24  4505.1  361.30  4636.3  361.48  4645.1  360.81
  4659.3  356.83  4666.8  359.52  4672.5  358.31  4688.4  361.57  4753.4  360.87
  4946.4  363.58  4952.6  361.60  4958.4  362.13  4963.2  354.82  4965.4  354.32
  4985.3  354.82  4990.2  359.03  4995.9  358.29  5001.0  362.95  5021.6  362.66
  5316.8  362.38  5477.5  361.39  5526.0  366.36  5691.7  383.57  5810.1  392.72
#Mann=9,-1,0
  3682.9    0.12       0  3694.4     0.1       0  4157.1    0.12       0
  4403.9     0.1       0  4963.2    0.07       0  4985.3     0.1       0
  5021.6    0.12       0  5316.8     0.1       0  5526.0    0.05       0
Bank Sta=4963.2,4985.3
Exp/Cntr=0.3,0.1

Type RM Length L Ch R = 1,57424,541,541,541
BEGIN DESCRIPTION:
Clear Creek 93.0
END DESCRIPTION:
XS GIS Cut Line= 3
      2755125.97      6800061.04      2754376.00      6800861.00
      2754575.99      6802110.96
#Sta/Elev= 30
  3903.3  397.80  4023.6  386.66  4238.0  370.93  4306.5  366.12  4478.7  361.41
  4617.6  360.01  4709.9  361.52  4745.1  359.95  4752.4  357.95  4759.3  358.37
  4766.6  355.95  4773.4  357.16  4780.5  360.31  4964.4  362.26  4967.5  352.81
  4969.7  352.31  4989.6  352.81  4992.8  353.96  4996.4  360.66  5010.0  361.01
  5111.2  362.68  5637.9  360.46  5732.1  369.90  5830.3  378.85  5880.9  385.94
  5917.0  389.43  5922.0  388.48  5984.1  391.80  6093.6  399.86  6265.7  399.78
#Mann=6,-1,0
  3903.3     0.1       0  4238.0    0.12       0  4478.7     0.1       0
  4967.5    0.07       0  4989.6     0.1       0  5732.1    0.05       0
Bank Sta=4967.5,4989.6
Exp/Cntr=0.3,0.1

Type RM Length L Ch R = 1,56883,575,575,575
BEGIN DESCRIPTION:
Clear Creek 92.0
END DESCRIPTION:
XS GIS Cut Line= 3
      2754875.96      6799961.03      2754076.00      6800611.00
      2754426.00      6802010.98
#Sta/Elev= 30
  3969.0  391.09  3980.8  390.58  4097.6  384.28  4399.5  362.62  4458.8  360.50
  4800.8  361.29  4821.6  359.46  4829.5  353.19  4835.9  353.35  4843.9  360.92
  4850.3  361.62  4899.9  360.92  4957.4  362.83  4963.8  354.94  4974.9  351.98
  4977.1  351.48  4997.4  351.98  4999.7  355.31  5002.3  355.31  5010.0  360.92
  5041.0  361.60  5257.4  362.34  5430.1  359.87  5924.9  359.92  6010.1  367.55
  6053.7  370.28  6213.5  387.16  6308.8  395.17  6342.3  397.26  6442.8  398.86
#Mann=6,-1,0
  3969.0     0.1       0  3980.8    0.12       0  4399.5     0.1       0
  4974.9    0.07       0  4997.4     0.1       0  6010.1    0.05       0
Bank Sta=4974.9,4997.4
Exp/Cntr=0.3,0.1

Type RM Length L Ch R = 1,56308,530,530,530
BEGIN DESCRIPTION:
Clear Creek 91.0
END DESCRIPTION:
XS GIS Cut Line= 3
      2754275.99      6799511.03      2753626.00      6800661.00
      2753676.00      6801911.04
#Sta/Elev= 30
  3662.6  383.37  3692.2  375.07  3729.7  368.97  3869.3  367.23  3897.2  365.61
  3984.0  365.85  4037.2  363.72  4226.3  360.82  4429.6  359.90  4722.5  359.76
  4727.3  358.59  4733.1  360.72  4742.3  360.96  4808.2  359.41  4932.3  361.13
  5077.6  359.39  5082.5  359.36  5093.5  360.95  5103.7  360.59  5113.7  356.93
  5122.4  350.82  5124.7  350.32  5144.9  350.82  5153.7  360.78  5376.9  359.53
  5504.0  358.41  5714.1  361.42  5938.5  377.21  6084.4  388.46  6234.6  394.68
#Mann=11,-1,0
  3662.6     0.1       0  3984.0    0.05       0  4429.6    0.12       0
  4722.5     0.1       0  5077.6    0.12       0  5082.5     0.1       0
  5093.5    0.12       0  5122.4    0.07       0  5144.9    0.12       0
  5376.9     0.1       0  5938.5    0.12       0
Bank Sta=5122.4,5144.9
Exp/Cntr=0.3,0.1

Type RM Length L Ch R = 1,55778,1542,1542,1542
BEGIN DESCRIPTION:
Clear Creek 90.0
END DESCRIPTION:
XS GIS Cut Line= 3
      2754176.02      6799410.97      2753226.00      6800861.00
      2753026.01      6801560.97
#Sta/Elev= 30
  3270.3  390.59  3314.1  382.55  3335.1  382.76  3458.8  369.48  3513.7  366.43
  3609.5  363.65  3950.2  359.46  4369.8  359.12  4418.0  358.40  4426.5  356.50
  4462.7  359.43  4822.1  359.53  4828.1  359.38  4960.1  359.41  4969.9  349.91
  4972.2  349.41  4992.4  349.91  4996.3  350.68  5000.8  355.91  5025.9  356.02
  5034.6  358.09  5054.5  359.03  5066.2  355.18  5093.5  352.94  5098.7  353.54
  5107.8  359.12  5171.5  356.67  5187.2  357.60  5232.6  358.72  5731.8  395.59
#Mann=9,-1,0
  3270.3     0.1       0  3513.7    0.05       0  4369.8     0.1       0
  4822.1    0.12       0  4828.1     0.1       0  4969.9    0.07       0
  4992.4     0.1       0  5034.6    0.12       0  5187.2    0.05       0
Bank Sta=4969.9,4992.4
Exp/Cntr=0.3,0.1

Type RM Length L Ch R = 1,54236,1108,1108,1108
BEGIN DESCRIPTION:
Clear Creek 89.0
END DESCRIPTION:
XS GIS Cut Line= 3
      2753876.03      6798760.97      2752626.00      6800061.00
      2752526.00      6801610.97
#Sta/Elev= 30
  3188.6  405.94  3245.1  403.33  3393.8  387.88  3429.1  387.19  3464.6  383.25
  3499.8  383.64  3556.4  378.00  3605.8  375.95  3683.8  367.20  3874.7  359.27
  4106.9  357.08  4468.7  356.60  4518.4  354.52  4673.5  355.93  4730.8  356.12
  4942.6  357.73  4956.7  352.68  4963.9  346.95  4973.6  346.90  4975.9  346.40
  4996.4  346.90  5002.1  356.70  5463.1  356.28  5497.6  360.43  5633.4  370.21
  5803.8  373.62  5984.2  368.40  6054.3  370.03  6401.2  387.62  6545.3  393.53
#Mann=8,-1,0
  3188.6    0.05       0  4106.9    0.12       0  4673.5     0.1       0
  4730.8    0.12       0  4973.6    0.07       0  4996.4    0.12       0
  5497.6    0.05       0  6401.2    0.12       0
Bank Sta=4973.6,4996.4
Exp/Cntr=0.3,0.1

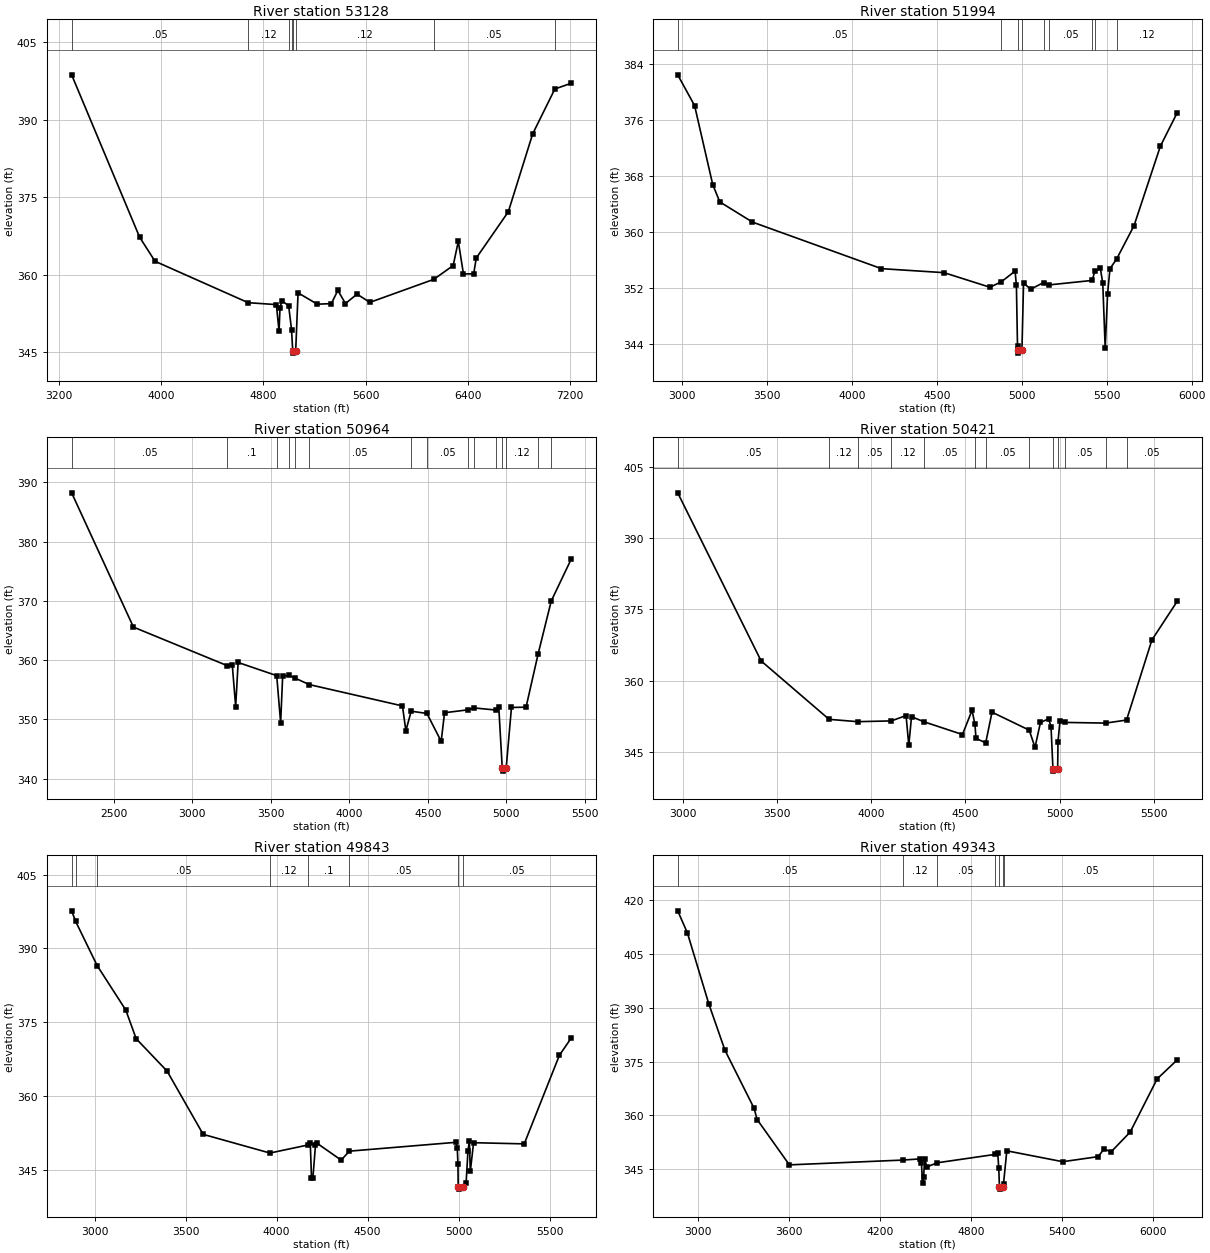
Type RM Length L Ch R = 1,53128,1134,1134,1134
BEGIN DESCRIPTION:
Clear Creek 88.0
END DESCRIPTION:
XS GIS Cut Line= 3
      2753276.03      6798110.96      2752176.00      6799411.00
      2752376.00      6801611.04
#Sta/Elev= 30
  3297.6  398.70  3830.0  367.25  3950.8  362.58  4680.4  354.56  4901.1  354.19
  4922.0  349.01  4929.7  353.60  4944.0  354.94  4997.1  353.98  5019.8  349.36
  5029.0  345.29  5031.3  344.79  5052.5  345.29  5070.9  356.47  5221.5  354.27
  5331.9  354.38  5382.2  356.94  5442.4  354.40  5532.8  356.22  5633.2  354.62
  6133.7  359.08  6285.9  361.76  6326.0  366.45  6366.2  360.13  6446.5  360.15
  6466.6  363.21  6717.6  372.17  6908.4  387.26  7082.2  395.96  7209.7  397.06
#Mann=8,-1,0
  3297.6    0.05       0  4680.4    0.12       0  4997.1     0.1       0
  5019.8    0.12       0  5029.0    0.07       0  5052.5    0.12       0
  6133.7    0.05       0  7082.2    0.12       0
Bank Sta=5029,5052.5
Exp/Cntr=0.3,0.1

Type RM Length L Ch R = 1,51994,1030,1030,1030
BEGIN DESCRIPTION:
Clear Creek 87.0
END DESCRIPTION:
XS GIS Cut Line= 3
      2752926.01      6798210.99      2751376.00      6799511.00
      2750726.03      6800160.97
#Sta/Elev= 30
  2972.9  382.40  3072.4  378.01  3179.1  366.75  3220.9  364.27  3413.3  361.39
  4173.0  354.75  4541.2  354.18  4811.8  352.10  4878.2  352.86  4960.1  354.40
  4967.9  352.37  4974.4  343.67  4977.0  343.20  4979.3  342.70  5000.6  343.20
  5010.0  352.68  5052.5  351.82  5127.6  352.77  5159.1  352.43  5414.3  353.07
  5429.6  354.35  5462.6  354.79  5476.7  352.65  5490.9  343.39  5505.0  351.19
  5519.2  354.76  5557.7  356.10  5660.6  360.87  5816.2  372.24  5915.1  376.99
#Mann=9,-1,0
  2972.9    0.05       0  4878.2     0.1       0  4977.0    0.07       0
  5000.6     0.1       0  5127.6    0.12       0  5159.1    0.05       0
  5414.3     0.1       0  5429.6    0.05       0  5557.7    0.12       0
Bank Sta=4977,5000.6
Exp/Cntr=0.3,0.1

Type RM Length L Ch R = 1,50964,543,543,543
BEGIN DESCRIPTION:
Clear Creek 86.0
END DESCRIPTION:
XS GIS Cut Line= 3
      2753025.97      6798061.02      2750626.00      6799461.00
      2750425.98      6799811.03
#Sta/Elev= 30
  2231.7  388.22  2625.3  365.57  3224.1  359.05  3255.0  359.13  3276.5  352.17
  3292.2  359.60  3537.9  357.38  3563.0  349.42  3575.8  357.27  3615.9  357.43
  3654.0  356.97  3745.4  355.87  4338.7  352.27  4360.6  348.09  4394.5  351.38
  4494.7  351.00  4585.5  346.29  4607.0  351.12  4758.9  351.62  4792.5  351.94
  4932.1  351.58  4952.3  352.12  4974.5  341.77  4977.0  341.27  4999.5  341.77
  5033.2  352.01  5126.1  352.06  5203.2  361.06  5286.5  369.97  5413.3  377.01
#Mann=15,-1,0
  2231.7    0.05       0  3224.1     0.1       0  3537.9    0.12       0
  3615.9    0.05       0  3654.0    0.12       0  3745.4    0.05       0
  4394.5     0.1       0  4494.7    0.05       0  4758.9    0.12       0
  4792.5     0.1       0  4932.1    0.12       0  4974.5    0.07       0
  4999.5    0.12       0  5203.2     0.1       0  5286.5    0.05       0
Bank Sta=4974.5,4999.5
Exp/Cntr=0.3,0.1

Type RM Length L Ch R = 1,50421,578,578,578
BEGIN DESCRIPTION:
Clear Creek 85.0
END DESCRIPTION:
XS GIS Cut Line= 3
      2751726.00      6797511.00      2750476.00      6799111.00
      2750325.99      6799711.03
#Sta/Elev= 30
  2974.2  399.60  3416.5  364.15  3777.0  351.83  3928.8  351.34  4107.0  351.50
  4185.2  352.63  4199.7  346.34  4214.1  352.39  4281.3  351.30  4484.3  348.63
  4535.1  353.74  4550.6  350.76  4556.0  347.81  4607.6  346.88  4641.0  353.34
  4838.4  349.55  4868.9  345.92  4897.9  351.17  4941.1  351.94  4954.0  350.28
  4964.1  341.41  4966.6  340.91  4989.1  341.41  4991.0  347.15  5001.4  351.48
  5027.7  351.18  5243.8  351.04  5354.5  351.68  5489.1  368.58  5623.1  376.72
#Mann=13,-1,0
  2974.2    0.05       0  3777.0    0.12       0  3928.8    0.05       0
  4107.0    0.12       0  4281.3    0.05       0  4550.6     0.1       0
  4607.6    0.05       0  4838.4     0.1       0  4964.1    0.07       0
  4989.1     0.1       0  5027.7    0.05       0  5243.8    0.12       0
  5354.5    0.05       0
Bank Sta=4964.1,4989.1
Exp/Cntr=0.3,0.1

Type RM Length L Ch R = 1,49843,500,500,500
BEGIN DESCRIPTION:
Clear Creek 84.0
END DESCRIPTION:
XS GIS Cut Line= 3
      2751426.01      6797360.98      2750026.00      6798961.00
      2750176.00      6799560.98
#Sta/Elev= 30
  2873.5  397.63  2895.4  395.49  3013.7  386.51  3171.1  377.47  3228.0  371.66
  3397.9  365.08  3596.3  352.23  3963.0  348.44  4170.2  350.06  4184.7  350.45
  4191.4  343.42  4199.0  343.36  4213.2  349.99  4219.8  350.48  4354.6  347.00
  4399.0  348.82  4985.8  350.62  4992.4  349.38  4996.2  346.16  4997.4  341.61
  4999.9  341.11  5022.4  341.61  5040.8  342.30  5051.1  348.92  5058.8  350.85
  5064.0  344.72  5082.0  350.54  5360.3  350.30  5553.6  368.30  5618.0  371.77
#Mann=8,-1,0
  2873.5    0.05       0  2895.4    0.12       0  3013.7    0.05       0
  3963.0    0.12       0  4170.2     0.1       0  4399.0    0.05       0
  4997.4    0.04       0  5022.4    0.05       0
Bank Sta=4997.4,5022.4
Exp/Cntr=0.3,0.1

Type RM Length L Ch R = 1,49343,564,564,564
BEGIN DESCRIPTION:
Clear Creek 83.0
END DESCRIPTION:
XS GIS Cut Line= 3
      2751175.98      6796961.02      2749776.00      6798561.00
      2749375.99      6799661.03
#Sta/Elev= 30
  2866.2  416.93  2930.2  410.78  3071.7  391.01  3178.0  378.14  3369.7  362.04
  3390.6  358.85  3603.2  346.25  4350.3  347.58  4467.8  347.92  4474.5  346.86
  4482.1  341.15  4488.7  342.74  4496.3  347.95  4510.5  345.68  4579.1  346.83
  4962.3  349.17  4978.4  349.54  4985.1  345.24  4989.7  340.00  4992.2  339.50
  5014.7  340.00  5016.5  341.01  5038.1  350.16  5407.2  347.13  5641.3  348.54
  5679.2  350.66  5726.4  349.87  5852.1  355.36  6030.3  370.17  6162.7  375.45
#Mann=7,-1,0
  2866.2    0.05       0  4350.3    0.12       0  4579.1    0.05       0
  4962.3     0.1       0  4989.7    0.07       0  5014.7     0.1       0
  5016.5    0.05       0
Bank Sta=4989.7,5014.7
Exp/Cntr=0.3,0.1

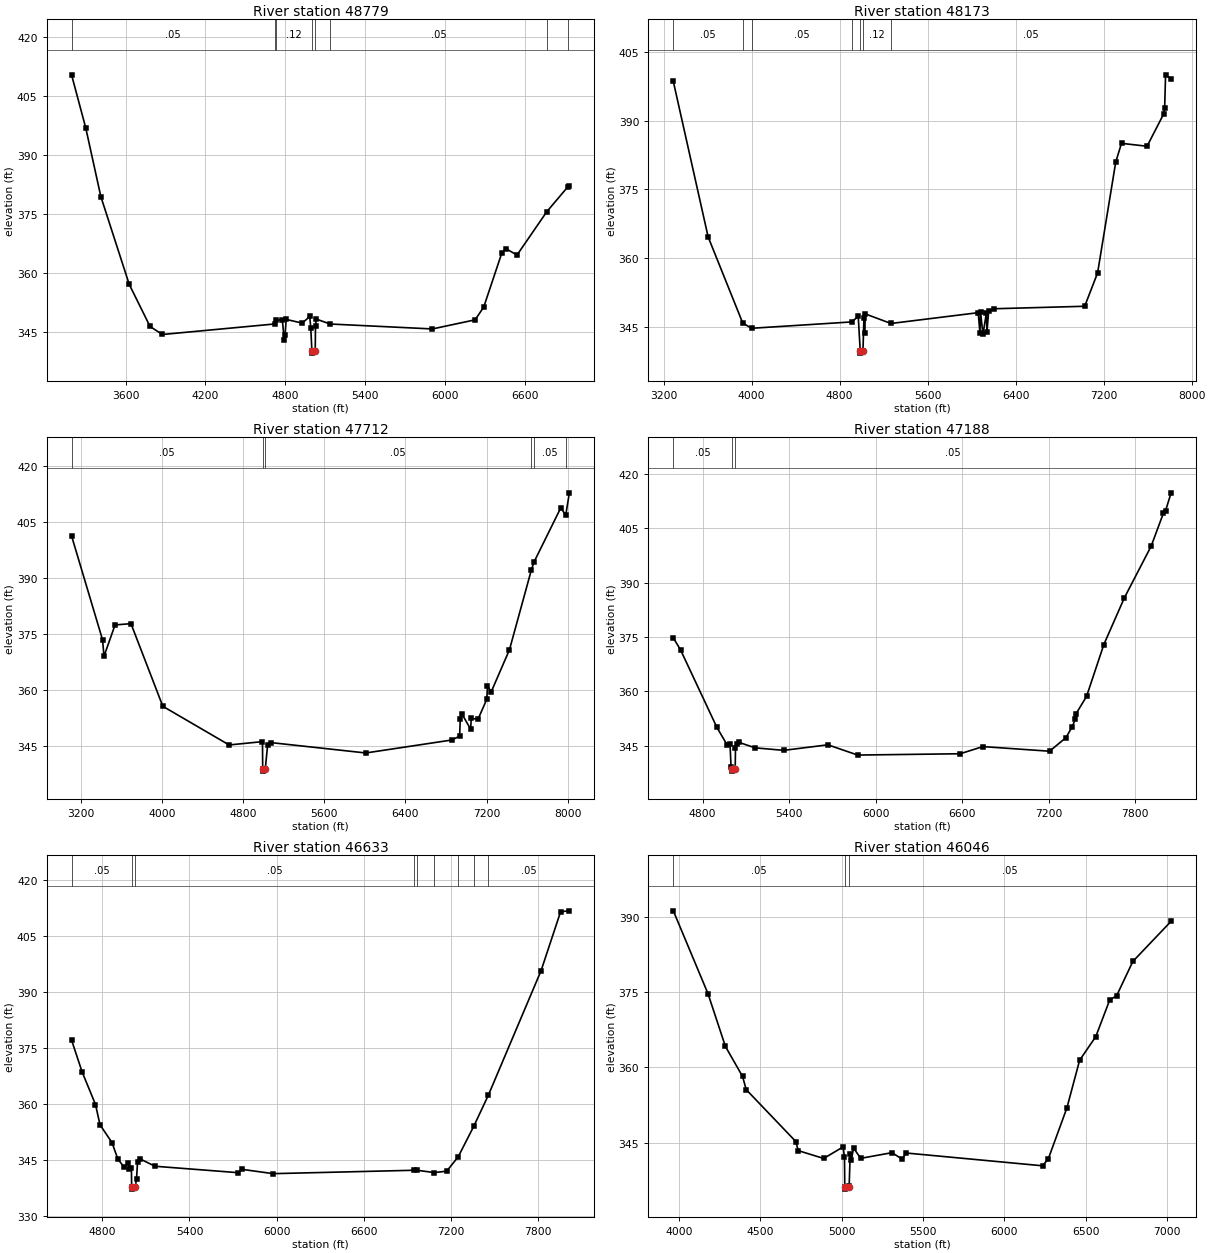
Type RM Length L Ch R = 1,48779,606,606,606
BEGIN DESCRIPTION:
Clear Creek 82.0
END DESCRIPTION:
XS GIS Cut Line= 3
      2751125.99      6796961.01      2749726.00      6798111.00
      2748575.99      6799661.02
#Sta/Elev= 30
  3193.2  410.34  3299.4  396.93  3413.2  379.45  3626.6  357.16  3783.0  346.47
  3875.6  344.43  4720.2  347.10  4731.9  348.05  4777.5  348.16  4791.8  343.12
  4798.3  344.21  4806.2  348.26  4927.3  347.32  4983.4  349.00  4991.3  346.15
  4999.8  340.20  5002.3  339.70  5024.8  340.20  5026.9  346.62  5033.1  348.34
  5136.9  347.09  5905.3  345.84  6226.6  348.15  6291.3  351.39  6426.9  365.07
  6456.1  366.25  6541.7  364.60  6765.0  375.58  6923.3  381.90  6935.0  382.23
#Mann=8,-1,0
  3193.2    0.05       0  4720.2     0.1       0  4731.9    0.12       0
  4999.8    0.07       0  5024.8    0.12       0  5136.9    0.05       0
  6765.0    0.12       0  6923.3    0.05       0
Bank Sta=4999.8,5024.8
Exp/Cntr=0.3,0.1

Type RM Length L Ch R = 1,48173,461,461,461
BEGIN DESCRIPTION:
Clear2
END DESCRIPTION:
XS GIS Cut Line= 3
      2750979.14      6796613.72      2749587.43      6797585.75
      2747175.96      6799061.02
#Sta/Elev= 30
  3288.7  398.57  3605.3  364.59  3919.8  345.77  3999.9  344.63  4910.6  346.02
  4969.5  347.24  4987.5  339.70  4990.0  339.20  5012.5  339.70  5021.2  346.86
  5027.0  343.64  5034.8  347.76  5266.9  345.68  6060.2  348.04  6075.6  343.64
  6081.5  348.10  6102.8  343.29  6133.7  347.89  6139.6  343.87  6155.0  348.41
  6207.1  348.90  7027.7  349.44  7145.0  356.73  7310.1  380.98  7362.3  385.05
  7594.5  384.41  7747.4  391.55  7754.5  392.69  7762.8  400.02  7813.2  399.18
#Mann=7,-1,0
  3288.7    0.05       0  3919.8    0.12       0  3999.9    0.05       0
  4910.6    0.12       0  4987.5    0.07       0  5012.5    0.12       0
  5266.9    0.05       0
Bank Sta=4987.5,5012.5
Exp/Cntr=0.3,0.1

Type RM Length L Ch R = 1,47712,524,524,524
BEGIN DESCRIPTION:
Clear Creek 80.0
END DESCRIPTION:
XS GIS Cut Line= 3
      2750903.24      6796101.00      2749376.00      6797211.00
      2746857.44      6798869.87
#Sta/Elev= 30
  3111.7  401.26  3417.3  373.36  3431.1  368.96  3540.1  377.38  3697.0  377.72
  4010.8  355.56  4663.9  345.19  4992.4  346.08  4994.7  338.67  4997.2  338.17
  5019.7  338.67  5043.4  345.22  5079.5  345.81  6010.1  343.04  6855.7  346.51
  6934.7  347.55  6940.7  352.09  6955.8  353.58  7043.1  349.41  7049.1  352.33
  7115.4  352.07  7202.8  357.48  7208.8  361.07  7244.9  359.38  7425.6  370.73
  7640.2  392.02  7667.2  394.24  7931.6  408.82  7979.9  406.78  8015.5  412.81
#Mann=6,-1,0
  3111.7    0.05       0  4994.7    0.05       0  5019.7    0.05       0
  7640.2   0.075       0  7667.2    0.05       0  7979.9   0.075       0
Bank Sta=4994.7,5019.7
Exp/Cntr=0.3,0.1

Type RM Length L Ch R = 1,47188,555,555,555
BEGIN DESCRIPTION:
Clear Creek 79.0
END DESCRIPTION:
XS GIS Cut Line= 3
      2749226.00      6796360.96      2749176.00      6796761.00
      2746789.94      6798659.59
#Sta/Elev= 30
  4596.9  374.77  4647.3  371.43  4899.3  350.02  4969.8  345.22  4990.0  345.53
  4997.5  339.00  5001.1  338.45  5003.6  337.95  5026.1  338.45  5028.1  344.29
  5036.1  345.57  5050.5  345.92  5164.2  344.38  5362.8  343.69  5668.8  345.22
  5875.4  342.39  6586.6  342.75  6743.5  344.73  7206.4  343.45  7320.2  347.21
  7363.4  350.22  7384.2  352.22  7390.6  353.84  7462.7  358.58  7582.8  372.93
  7725.4  385.85  7911.2  400.13  7996.1  409.25  8010.5  409.86  8049.3  414.84
#Mann=3,-1,0
  4596.9    0.05       0  5001.1    0.04       0  5026.1    0.05       0
Bank Sta=5001.1,5026.1
Exp/Cntr=0.3,0.1

Type RM Length L Ch R = 1,46633,587,587,587
BEGIN DESCRIPTION:
Clear Creek 78.0
END DESCRIPTION:
XS GIS Cut Line= 3
      2749175.95      6796311.01      2748776.00      6796411.00
      2746616.71      6798516.84
#Sta/Elev= 30
  4588.0  377.05  4660.1  368.57  4752.9  359.79  4783.8  354.38  4866.3  349.61
  4907.5  345.14  4948.7  343.11  4977.1  344.01  4982.2  342.61  5000.3  342.87
  5001.8  337.65  5004.3  337.15  5026.8  337.65  5035.6  339.99  5042.6  344.46
  5056.8  345.29  5162.9  343.27  5735.7  341.55  5764.0  342.43  5976.2  341.29
  6948.6  342.20  6967.7  342.20  7085.5  341.58  7171.2  341.95  7250.7  345.78
  7359.4  354.07  7459.5  362.37  7821.8  395.62  7956.2  411.39  8016.4  411.62
#Mann=9,-1,0
  4588.0    0.05       0  5001.8    0.04       0  5026.8    0.05       0
  6948.6    0.12       0  6967.7    0.05       0  7085.5    0.12       0
  7250.7    0.05       0  7359.4    0.12       0  7459.5    0.05       0
Bank Sta=5001.8,5026.8
Exp/Cntr=0.3,0.1

Type RM Length L Ch R = 1,46046,557,557,557
BEGIN DESCRIPTION:
Clear Creek 77.0
END DESCRIPTION:
XS GIS Cut Line= 3
      2749126.00      6795411.00      2748326.00      6796061.00
      2746725.98      6797311.02
#Sta/Elev= 30
  3964.1  391.14  4177.4  374.66  4284.5  364.17  4390.0  358.20  4412.3  355.58
  4717.6  345.25  4732.0  343.45  4888.6  341.89  5008.5  344.19  5016.6  342.10
  5018.5  336.29  5021.0  335.79  5043.5  336.29  5045.5  336.44  5051.9  342.83
  5058.3  341.54  5072.7  343.97  5116.1  341.91  5308.7  343.04  5372.9  341.73
  5393.7  342.98  6234.8  340.43  6270.1  341.82  6384.0  351.90  6462.7  361.42
  6562.2  366.13  6647.2  373.37  6690.6  374.28  6790.1  381.08  7025.3  389.06
#Mann=3,-1,0
  3964.1    0.05       0  5018.5    0.04       0  5043.5    0.05       0
Bank Sta=5018.5,5043.5
Exp/Cntr=0.3,0.1

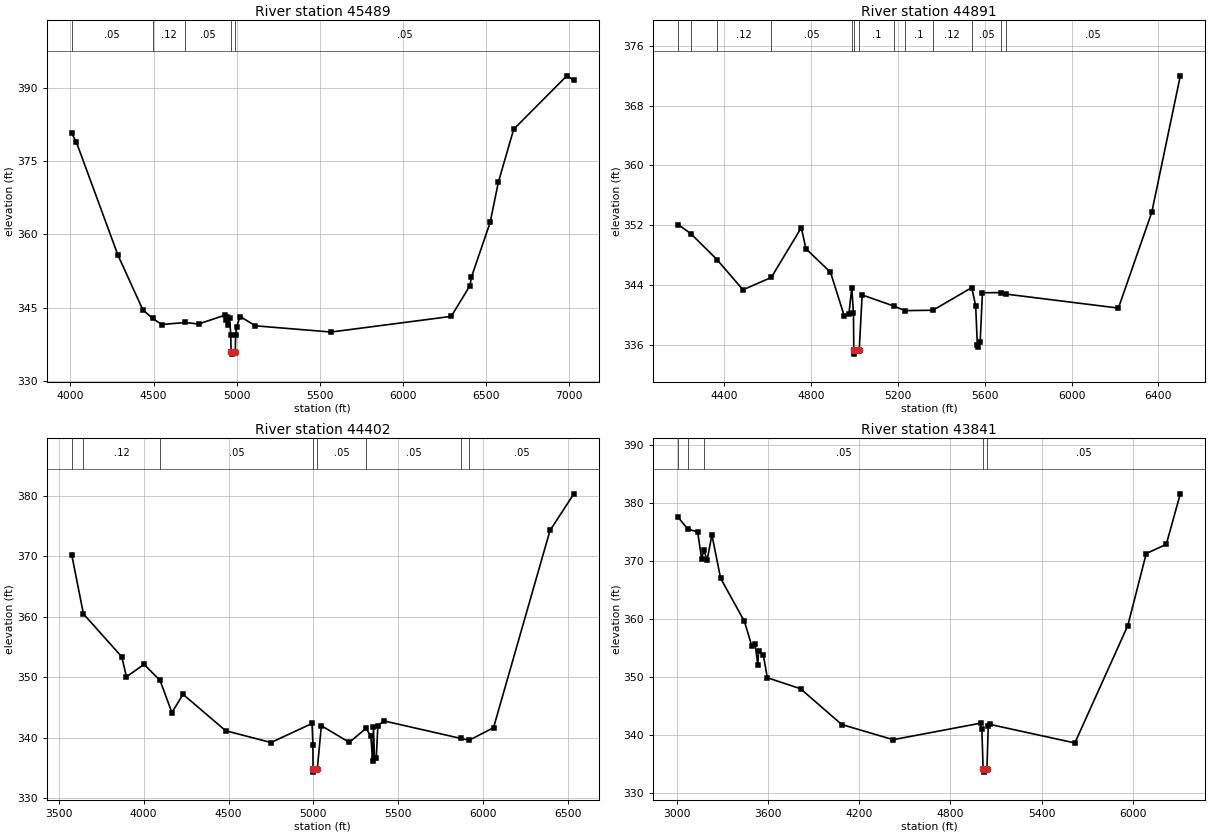
Type RM Length L Ch R = 1,45489,598,598,598
BEGIN DESCRIPTION:
Clear Creek 76.0
END DESCRIPTION:
XS GIS Cut Line= 3
      2748476.01      6794960.99      2747876.00      6795761.00
      2746576.01      6797310.99
#Sta/Elev= 30
  4007.8  380.65  4035.9  378.82  4285.9  355.73  4435.9  344.54  4494.6  342.79
  4550.5  341.55  4690.7  341.96  4771.4  341.65  4929.7  343.46  4935.9  342.54
  4944.3  343.10  4950.5  341.55  4957.8  342.80  4965.1  339.48  4967.2  335.99
  4969.7  335.49  4992.2  335.99  4994.3  339.37  5000.5  341.13  5021.5  343.18
  5113.9  341.28  5569.0  340.01  6292.5  343.21  6405.7  349.51  6413.5  351.18
  6526.7  362.42  6576.1  370.63  6668.5  381.49  6988.5  392.42  7030.8  391.53
#Mann=5,-1,0
  4007.8    0.05       0  4494.6    0.12       0  4690.7    0.05       0
  4967.2    0.05       0  4992.2    0.05       0
Bank Sta=4967.2,4992.2
Exp/Cntr=0.3,0.1

Type RM Length L Ch R = 1,44891,489,489,489
BEGIN DESCRIPTION:
Clear Creek 75.0
END DESCRIPTION:
XS GIS Cut Line= 3
      2748141.13      6794734.05      2747574.44      6795316.87
      2746126.01      6795711.00
#Sta/Elev= 30
  4187.1  352.10  4246.4  350.84  4365.6  347.41  4485.6  343.36  4616.0  345.02
  4754.4  351.68  4775.5  348.86  4888.7  345.72  4952.3  339.86  4973.6  340.13
  4987.0  343.64  4994.7  340.23  4996.2  335.26  4998.7  334.76  5021.2  335.26
  5034.7  342.68  5181.4  341.18  5231.7  340.58  5361.1  340.63  5540.0  343.66
  5558.0  341.21  5565.6  335.99  5570.8  335.66  5578.7  336.42  5589.1  342.97
  5674.9  342.99  5698.0  342.79  6215.8  340.92  6369.7  353.75  6501.1  371.99
#Mann=13,-1,0
  4187.1    0.12       0  4246.4    0.05       0  4365.6    0.12       0
  4616.0    0.05       0  4987.0     0.1       0  4996.2    0.07       0
  5021.2     0.1       0  5181.4    0.12       0  5231.7     0.1       0
  5361.1    0.12       0  5540.0    0.05       0  5674.9    0.12       0
  5698.0    0.05       0
Bank Sta=4996.2,5021.2
Exp/Cntr=0.3,0.1

Type RM Length L Ch R = 1,44402,561,561,561
BEGIN DESCRIPTION:
Clear Creek 74.0
END DESCRIPTION:
XS GIS Cut Line= 3
      2748478.70      6794335.52      2747226.00      6795011.00
      2745776.00      6795511.00
#Sta/Elev= 30
  3576.8  370.18  3645.7  360.45  3871.2  353.38  3898.8  350.08  4002.6  352.12
  4096.8  349.48  4166.4  344.17  4232.1  347.18  4483.4  341.17  4750.1  339.23
  4991.9  342.37  4997.2  338.81  4997.8  334.84  5000.3  334.34  5022.8  334.84
  5046.8  342.00  5211.6  339.25  5309.8  341.57  5338.5  340.27  5348.3  336.15
  5353.6  341.72  5359.7  336.67  5370.2  336.68  5379.5  342.02  5416.0  342.79
  5868.6  339.90  5917.6  339.61  6060.7  341.67  6393.4  374.23  6533.8  380.28
#Mann=8,-1,0
  3576.8    0.05       0  3645.7    0.12       0  4096.8    0.05       0
  4997.8    0.04       0  5022.8    0.05       0  5309.8    0.05       0
  5868.6    0.12       0  5917.6    0.05       0
Bank Sta=4997.8,5022.8
Exp/Cntr=0.3,0.1

Type RM Length L Ch R = 1,43841,566,566,566
BEGIN DESCRIPTION:
Clear Creek 73.0
END DESCRIPTION:
XS GIS Cut Line= 3
      2748704.17      6794015.35      2746826.00      6794661.00
      2745577.44      6795076.41
#Sta/Elev= 30
  3009.6  377.46  3073.0  375.45  3137.2  374.99  3163.2  370.40  3178.5  371.85
  3199.7  370.11  3231.0  374.48  3288.2  367.01  3444.4  359.61  3494.1  355.32
  3515.2  355.76  3532.8  352.04  3538.1  354.50  3569.3  353.80  3595.3  349.90
  3814.0  348.00  4084.6  341.85  4423.0  339.24  4998.3  342.08  5006.2  341.09
  5014.8  334.16  5017.3  333.66  5039.8  334.16  5048.4  341.60  5058.9  341.87
  5618.0  338.68  5966.1  358.86  6087.4  371.26  6219.3  372.84  6311.5  381.53
#Mann=5,-1,0
  3009.6    0.05       0  3073.0    0.12       0  3178.5    0.05       0
  5014.8    0.04       0  5039.8    0.05       0
Bank Sta=5014.8,5039.8
Exp/Cntr=0.3,0.1