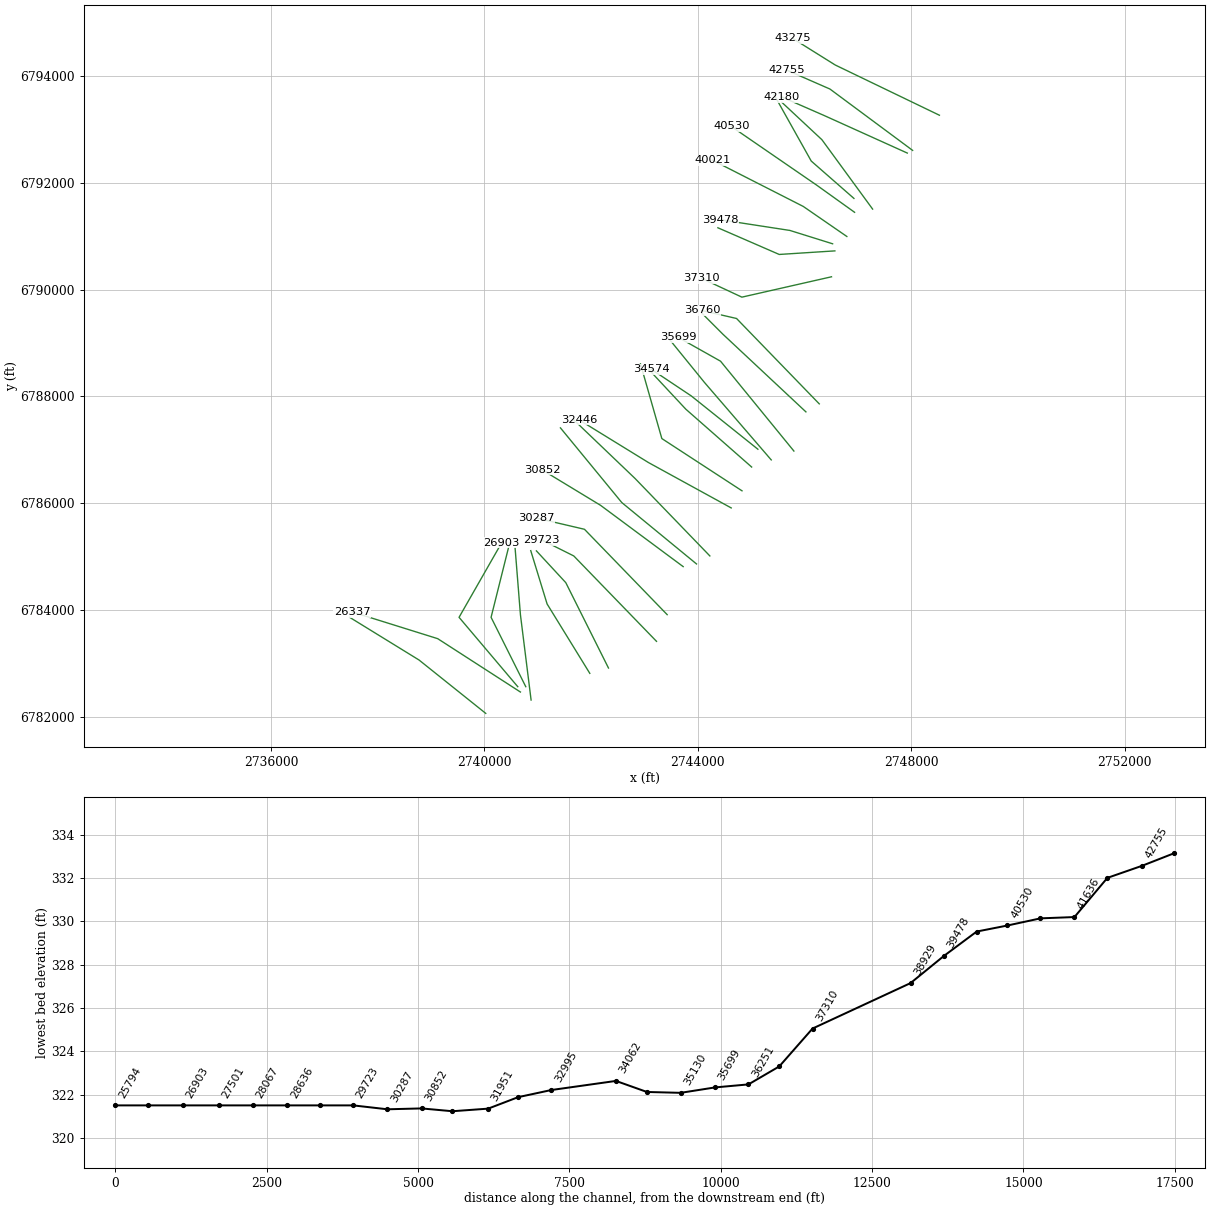
HEC-RAS study Clear Creek.prj: Clear Creek Base Level Engineering

--- Clear Creek.g01 (geometry) --- (continued)

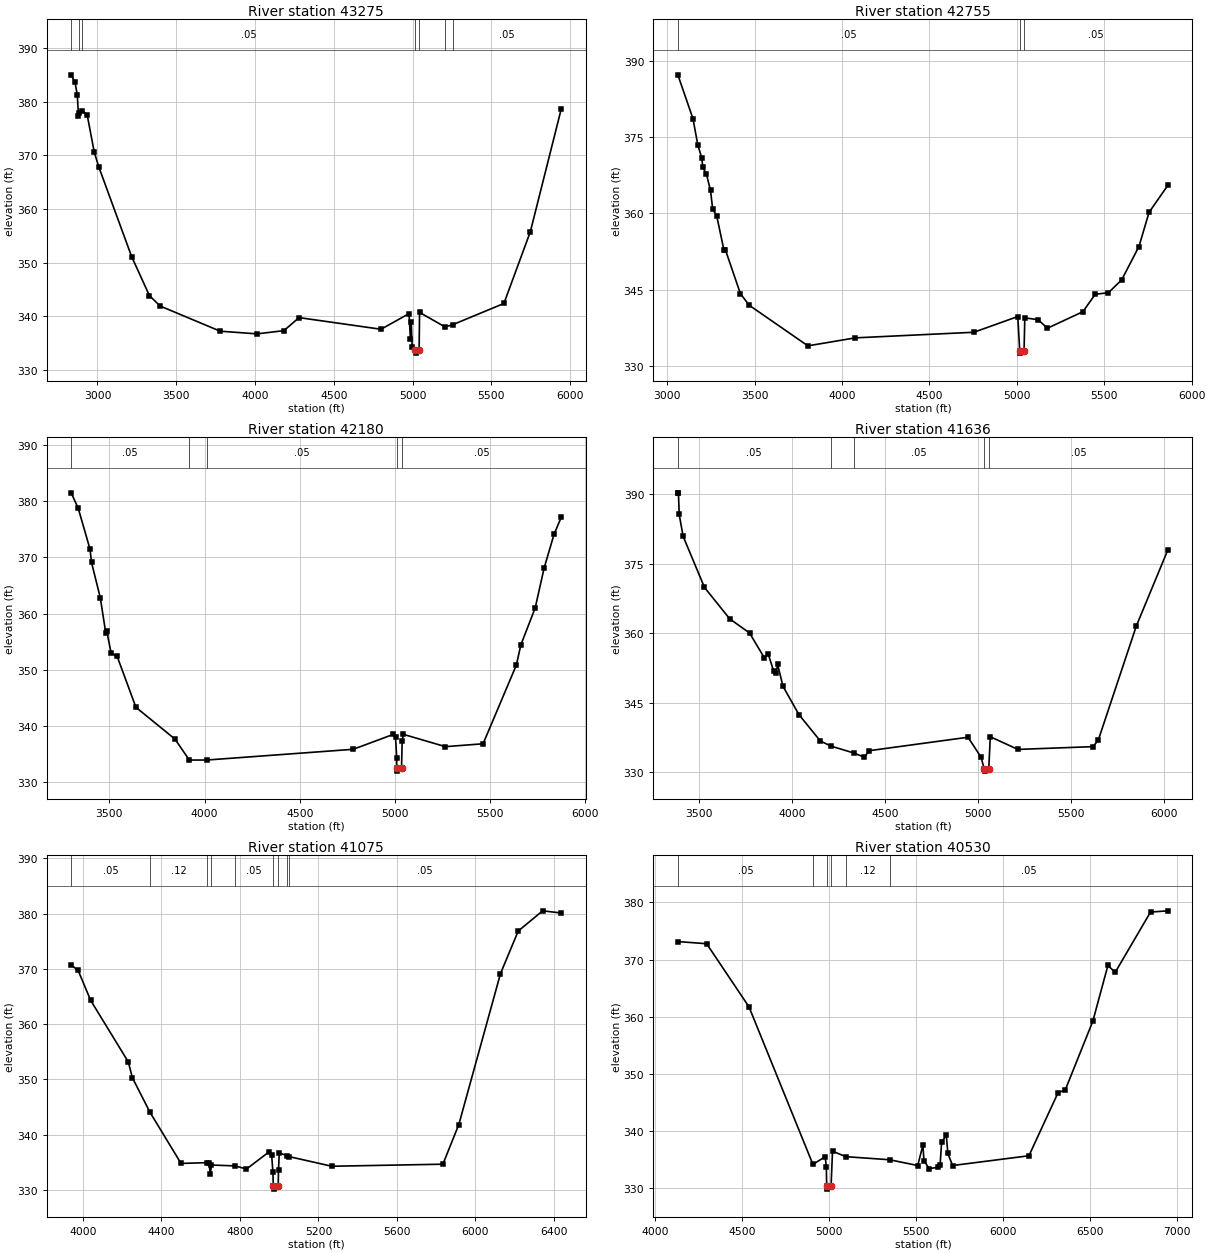
Type RM Length L Ch R = 1,43275,520,520,520
BEGIN DESCRIPTION:
Clear Creek 72.0
END DESCRIPTION:
XS GIS Cut Line= 3
      2748527.87      6793269.89      2746576.00      6794211.00
      2745776.01      6794711.00
#Sta/Elev= 30
  2833.2  385.01  2857.5  383.60  2872.2  381.25  2879.7  377.25  2885.1  377.96
  2904.4  378.30  2934.5  377.59  2979.6  370.62  3007.9  367.89  3217.0  351.13
  3330.0  343.85  3397.9  341.92  3778.9  337.23  4012.1  336.73  4183.4  337.33
  4279.4  339.76  4799.6  337.59  4977.9  340.51  4986.0  335.78  4991.6  338.85
  4997.3  334.35  5016.5  333.64  5019.0  333.14  5041.5  333.64  5044.3  340.73
  5206.3  338.02  5254.0  338.43  5579.7  342.40  5747.2  355.76  5943.5  378.65
#Mann=7,-1,0
  2833.2    0.05       0  2885.1    0.12       0  2904.4    0.05       0
  5016.5    0.04       0  5041.5    0.05       0  5206.3     0.1       0
  5254.0    0.05       0
Bank Sta=5016.5,5041.5
Exp/Cntr=0.3,0.1

Type RM Length L Ch R = 1,42755,575,575,575
BEGIN DESCRIPTION:
Clear Creek 71.0
END DESCRIPTION:
XS GIS Cut Line= 3
      2748026.04      6792610.97      2746476.00      6793761.00
      2745675.98      6794111.01
#Sta/Elev= 30
  3060.9  387.24  3147.6  378.60  3174.6  373.55  3197.6  370.91  3203.9  369.06
  3224.7  367.68  3247.7  364.54  3260.2  360.87  3283.2  359.54  3324.9  352.75
  3333.3  352.82  3418.8  344.25  3468.9  341.98  3804.8  334.00  4076.0  335.57
  4754.4  336.67  5005.4  339.76  5016.3  333.07  5018.8  332.57  5041.3  333.07
  5045.5  339.50  5122.0  339.14  5174.6  337.46  5378.1  340.71  5448.2  344.13
  5523.9  344.44  5599.5  346.96  5698.5  353.51  5756.2  360.22  5864.2  365.56
#Mann=3,-1,0
  3060.9    0.05       0  5016.3    0.04       0  5041.3    0.05       0
Bank Sta=5016.3,5041.3
Exp/Cntr=0.3,0.1

Type RM Length L Ch R = 1,42180,544,544,544
BEGIN DESCRIPTION:
Clear Creek 70.0
END DESCRIPTION:
XS GIS Cut Line= 3
      2747925.97      6792561.01      2746376.00      6793261.00
      2745576.01      6793610.99
#Sta/Elev= 30
  3299.2  381.47  3336.6  378.69  3397.9  371.49  3406.0  369.11  3452.2  362.81
  3480.8  356.58  3486.3  356.86  3509.4  352.92  3540.6  352.41  3639.3  343.35
  3844.1  337.71  3919.8  333.98  4010.6  333.98  4780.5  335.89  4991.1  338.54
  5002.6  338.03  5008.9  334.36  5009.2  332.51  5011.7  332.01  5034.2  332.51
  5037.7  337.39  5043.6  338.55  5264.6  336.36  5462.6  336.87  5637.3  350.86
  5660.7  354.42  5736.3  361.02  5783.1  368.09  5835.3  374.11  5873.1  377.12
#Mann=5,-1,0
  3299.2    0.05       0  3919.8    0.12       0  4010.6    0.05       0
  5009.2    0.04       0  5034.2    0.05       0
Bank Sta=5009.2,5034.2
Exp/Cntr=0.3,0.1

Type RM Length L Ch R = 1,41636,561,561,561
BEGIN DESCRIPTION:
Clear Creek 69.0
END DESCRIPTION:
XS GIS Cut Line= 3
      2747275.98      6791511.02      2746326.00      6792811.00
      2745576.01      6793510.99
#Sta/Elev= 30
  3385.4  390.33  3388.5  390.33  3392.7  385.66  3413.6  380.95  3528.6  369.89
  3664.5  363.10  3771.1  360.04  3850.6  354.69  3871.5  355.50  3900.8  351.80
  3915.5  351.45  3921.7  353.31  3951.0  348.52  4036.8  342.41  4151.8  336.71
  4207.7  335.63  4333.0  334.10  4388.1  333.21  4415.2  334.62  4946.0  337.52
  5016.7  333.19  5032.6  330.70  5035.1  330.20  5057.6  330.70  5066.1  337.63
  5214.6  334.89  5618.1  335.49  5646.5  336.86  5851.6  361.58  6021.4  378.04
#Mann=5,-1,0
  3385.4    0.05       0  4207.7    0.12       0  4333.0    0.05       0
  5032.6    0.05       0  5057.6    0.05       0
Bank Sta=5032.6,5057.6
Exp/Cntr=0.3,0.1

Type RM Length L Ch R = 1,41075,545,545,545
BEGIN DESCRIPTION:
Clear Creek 68.0
END DESCRIPTION:
XS GIS Cut Line= 3
      2746926.02      6791710.98      2746126.00      6792411.00
      2745426.00      6793661.00
#Sta/Elev= 30
  3941.1  370.70  3976.7  369.70  4040.3  364.29  4232.0  353.16  4252.9  350.29
  4342.2  344.06  4500.6  334.79  4632.0  334.93  4643.0  334.93  4649.7  332.84
  4655.4  334.50  4776.5  334.34  4833.8  333.77  4947.7  336.85  4961.9  336.37
  4968.6  333.16  4970.3  330.64  4972.8  330.14  4995.3  330.64  4997.0  333.64
  5000.8  336.71  5038.8  336.20  5051.6  336.02  5267.8  334.28  5834.1  334.65
  5915.1  341.82  6127.3  369.12  6217.6  376.83  6342.0  380.49  6436.8  380.10
#Mann=9,-1,0
  3941.1    0.05       0  4342.2    0.12       0  4632.0     0.1       0
  4655.4    0.12       0  4776.5    0.05       0  4970.3    0.04       0
  4995.3    0.05       0  5038.8    0.12       0  5051.6    0.05       0
Bank Sta=4970.3,4995.3
Exp/Cntr=0.3,0.1

Type RM Length L Ch R = 1,40530,509,509,509
BEGIN DESCRIPTION:
Clear Creek 67.0
END DESCRIPTION:
XS GIS Cut Line= 3
      2746937.82      6791451.13      2746226.00      6791961.00
      2744626.03      6793060.98
#Sta/Elev= 30
  4129.2  373.14  4294.8  372.76  4538.0  361.72  4905.6  334.14  4976.5  335.49
  4982.7  333.65  4984.9  330.31  4987.4  329.81  5009.9  330.31  5018.3  336.45
  5095.1  335.49  5346.8  334.95  5508.1  333.94  5537.9  337.50  5544.0  334.80
  5573.8  333.40  5623.7  333.62  5636.7  333.97  5645.5  338.07  5672.5  339.22
  5681.3  336.05  5708.6  333.94  6147.4  335.65  6314.6  346.67  6356.5  347.19
  6514.8  359.21  6601.4  368.96  6643.3  367.75  6846.3  378.30  6946.4  378.52
#Mann=6,-1,0
  4129.2    0.05       0  4905.6     0.1       0  4984.9    0.07       0
  5009.9     0.1       0  5095.1    0.12       0  5346.8    0.05       0
Bank Sta=4984.9,5009.9
Exp/Cntr=0.3,0.1

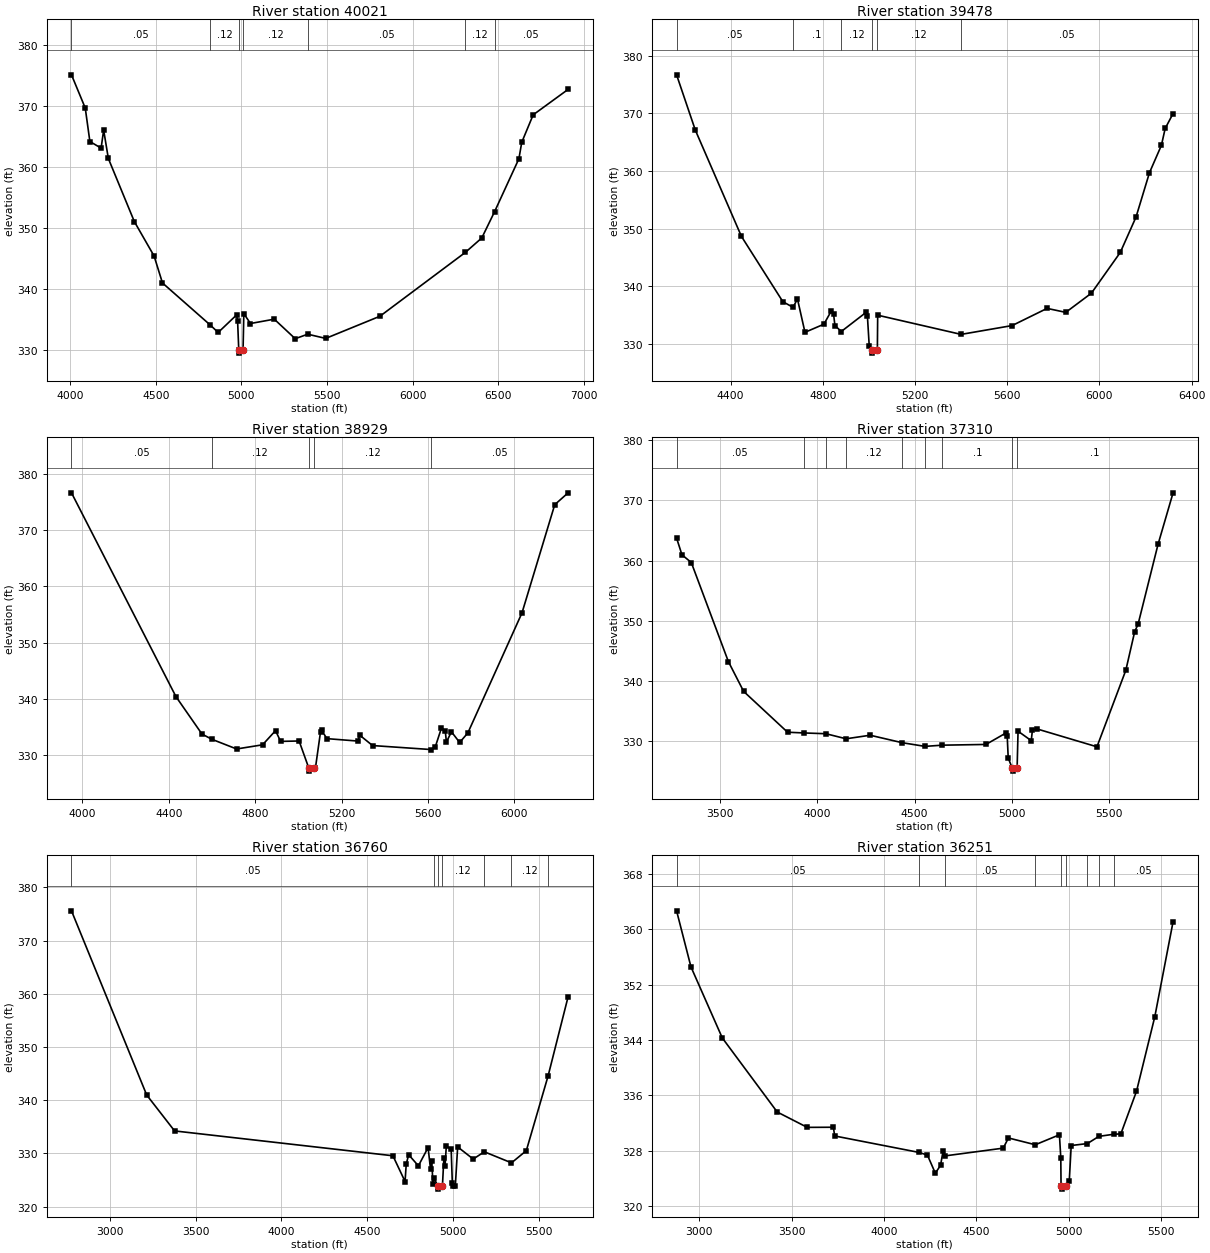
Type RM Length L Ch R = 1,40021,543,543,543
BEGIN DESCRIPTION:
Clear Creek 66.0
END DESCRIPTION:
XS GIS Cut Line= 3
      2746793.31      6790997.67      2745976.00      6791561.00
      2744276.26      6792426.39
#Sta/Elev= 30
  4007.6  375.10  4088.0  369.66  4115.0  364.18  4180.6  363.10  4195.5  366.05
  4222.9  361.40  4374.7  351.07  4490.1  345.43  4539.0  341.02  4819.4  334.10
  4864.3  332.91  4971.8  335.78  4977.9  334.77  4984.7  330.03  4987.2  329.53
  5009.7  330.03  5014.2  336.00  5053.0  334.38  5192.1  335.09  5314.3  331.89
  5387.4  332.63  5492.3  331.94  5809.3  335.57  6308.4  346.03  6404.2  348.39
  6479.2  352.71  6621.0  361.36  6637.6  364.05  6704.3  368.55  6907.6  372.70
#Mann=7,-1,0
  4007.6    0.05       0  4819.4    0.12       0  4984.7    0.07       0
  5009.7    0.12       0  5387.4    0.05       0  6308.4    0.12       0
  6479.2    0.05       0
Bank Sta=4984.7,5009.7
Exp/Cntr=0.3,0.1

Type RM Length L Ch R = 1,39478,549,549,549
BEGIN DESCRIPTION:
Clear Creek 65.0
END DESCRIPTION:
XS GIS Cut Line= 3
      2746526.05      6790860.99      2745726.00      6791111.00
      2744426.00      6791311.00
#Sta/Elev= 30
  4165.9  376.67  4247.1  367.09  4447.3  348.64  4626.9  337.32  4670.8  336.35
  4690.3  337.78  4722.8  332.01  4805.0  333.42  4836.5  335.68  4846.9  335.16
  4852.7  333.19  4880.3  332.15  4987.9  335.47  4993.6  334.83  5001.5  329.67
  5011.8  328.90  5014.3  328.40  5036.8  328.90  5038.2  334.98  5400.0  331.65
  5621.3  333.18  5773.0  336.16  5854.0  335.47  5965.3  338.80  6090.5  345.87
  6158.8  352.01  6217.0  359.69  6268.8  364.44  6285.2  367.37  6319.4  369.95
#Mann=6,-1,0
  4165.9    0.05       0  4670.8     0.1       0  4880.3    0.12       0
  5011.8    0.07       0  5036.8    0.12       0  5400.0    0.05       0
Bank Sta=5011.8,5036.8
Exp/Cntr=0.3,0.1

Type RM Length L Ch R = 1,38929,1619,1619,1619
BEGIN DESCRIPTION:
Clear Creek 64.0
END DESCRIPTION:
XS GIS Cut Line= 3
      2746568.90      6790727.91      2745526.00      6790661.00
      2744376.03      6791160.99
#Sta/Elev= 30
  3949.5  376.65  4433.4  340.39  4553.6  333.75  4599.2  332.82  4714.0  331.09
  4834.2  331.83  4894.3  334.35  4917.9  332.44  5003.5  332.51  5048.8  327.65
  5051.3  327.15  5073.8  327.65  5079.3  327.77  5102.8  334.17  5108.2  334.43
  5131.7  332.93  5277.8  332.49  5283.2  333.58  5343.5  331.70  5613.8  330.99
  5633.3  331.37  5662.2  334.77  5680.1  334.35  5685.6  332.34  5709.0  334.14
  5746.9  332.25  5784.8  333.94  6035.6  355.30  6187.2  374.54  6248.5  376.63
#Mann=5,-1,0
  3949.5    0.05       0  4599.2    0.12       0  5048.8    0.07       0
  5073.8    0.12       0  5613.8    0.05       0
Bank Sta=5048.8,5073.8
Exp/Cntr=0.3,0.1

Type RM Length L Ch R = 1,37310,550,550,550
BEGIN DESCRIPTION:
Clear Creek 63.0
END DESCRIPTION:
XS GIS Cut Line= 3
      2746505.37      6790242.67      2744826.00      6789861.00
      2744076.04      6790210.98
#Sta/Elev= 30
  3278.1  363.75  3305.6  360.98  3353.8  359.68  3544.1  343.24  3622.5  338.29
  3848.1  331.51  3931.8  331.39  4045.2  331.26  4148.6  330.42  4272.2  331.01
  4436.5  329.77  4553.8  329.16  4643.2  329.36  4867.0  329.48  4969.5  331.38
  4976.2  330.84  4981.3  327.22  5002.0  325.55  5004.5  325.05  5027.0  325.55
  5031.8  331.68  5099.6  330.11  5105.9  331.95  5128.8  332.06  5437.0  329.09
  5585.2  341.79  5630.9  348.22  5648.2  349.44  5750.7  362.70  5827.9  371.26
#Mann=9,-1,0
  3278.1    0.05       0  3931.8    0.12       0  4045.2    0.05       0
  4148.6    0.12       0  4436.5     0.1       0  4553.8    0.12       0
  4643.2     0.1       0  5002.0    0.07       0  5027.0     0.1       0
Bank Sta=5002,5027
Exp/Cntr=0.3,0.1

Type RM Length L Ch R = 1,36760,509,509,509
BEGIN DESCRIPTION:
Clear Creek 62.0
END DESCRIPTION:
XS GIS Cut Line= 3
      2746276.02      6787860.97      2744726.00      6789461.00
      2744075.99      6789611.00
#Sta/Elev= 30
  2776.7  375.61  3215.2  340.99  3377.8  334.24  4650.8  329.57  4721.6  324.73
  4728.5  328.03  4742.7  329.76  4799.3  327.68  4855.9  331.11  4870.0  327.07
  4877.2  328.67  4884.1  324.31  4891.2  325.34  4913.9  323.80  4916.4  323.30
  4939.3  323.80  4947.9  329.07  4954.9  327.68  4962.1  331.39  4990.4  330.79
  4997.3  324.43  5000.9  323.98  5014.7  323.92  5028.3  331.24  5119.0  328.95
  5183.6  330.32  5342.2  328.24  5428.6  330.53  5555.8  344.60  5671.5  359.36
#Mann=7,-1,0
  2776.7    0.05       0  4891.2    0.12       0  4913.9    0.07       0
  4939.3    0.12       0  5183.6     0.1       0  5342.2    0.12       0
  5555.8    0.05       0
Bank Sta=4913.9,4939.3
Exp/Cntr=0.3,0.1

Type RM Length L Ch R = 1,36251,552,552,552
BEGIN DESCRIPTION:
Clear Creek 61.0
END DESCRIPTION:
XS GIS Cut Line= 3
      2746026.02      6787710.98      2744476.00      6789161.00
      2744076.01      6789560.99
#Sta/Elev= 30
  2877.0  362.67  2954.9  354.57  3124.5  344.31  3421.9  333.61  3584.6  331.39
  3726.0  331.41  3733.1  330.15  4190.3  327.77  4235.3  327.38  4277.8  324.78
  4306.1  325.89  4320.3  328.02  4330.1  327.27  4645.6  328.39  4673.9  329.86
  4819.3  328.88  4949.9  330.32  4957.3  327.00  4958.7  322.97  4961.2  322.47
  4984.2  322.97  5003.1  323.61  5013.7  328.77  5101.3  329.05  5163.4  330.09
  5244.6  330.40  5282.4  330.45  5367.2  336.60  5466.2  347.36  5565.2  361.09
#Mann=9,-1,0
  2877.0    0.05       0  4190.3    0.12       0  4330.1    0.05       0
  4819.3    0.12       0  4958.7    0.07       0  4984.2    0.12       0
  5101.3    0.05       0  5163.4    0.12       0  5244.6    0.05       0
Bank Sta=4958.7,4984.2
Exp/Cntr=0.3,0.1

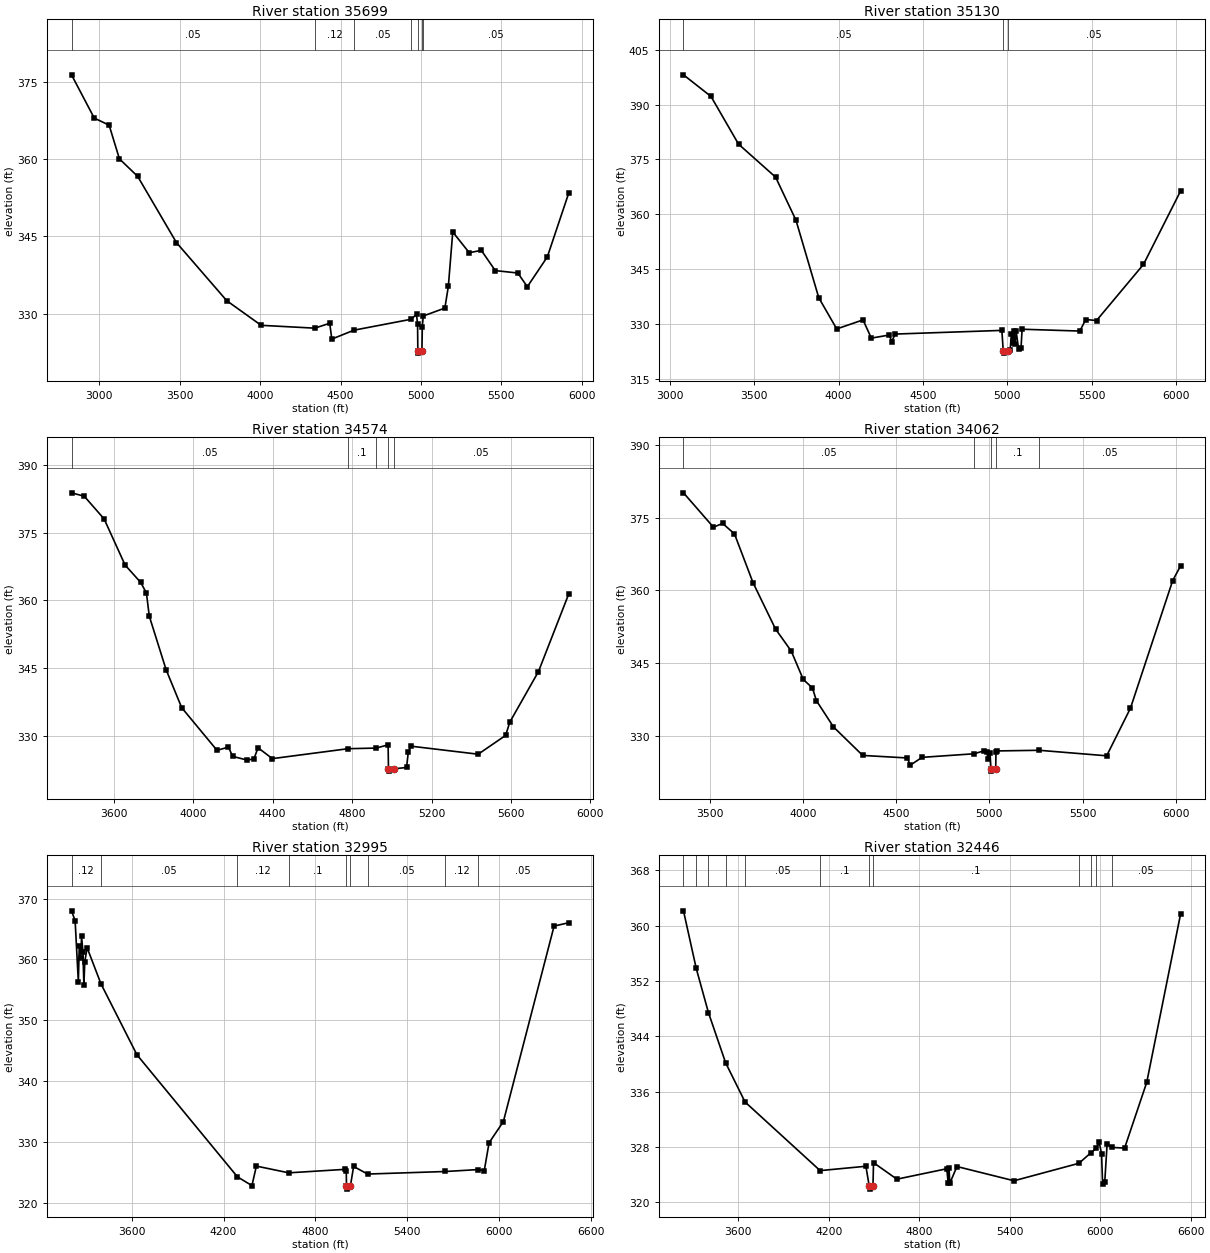
Type RM Length L Ch R = 1,35699,569,569,569
BEGIN DESCRIPTION:
Clear Creek 60.0
END DESCRIPTION:
XS GIS Cut Line= 3
      2745800.76      6786976.86      2744426.00      6788661.00
      2743625.98      6789111.01
#Sta/Elev= 30
  2826.5  376.38  2967.9  367.98  3060.5  366.60  3124.4  360.06  3237.9  356.66
  3479.1  343.80  3792.1  332.51  4006.1  327.73  4339.5  327.18  4432.5  328.13
  4445.5  325.06  4583.8  326.79  4937.6  328.90  4972.5  329.84  4979.0  327.91
  4980.6  322.83  4983.1  322.33  5006.1  322.83  5008.5  327.48  5014.4  329.54
  5148.7  331.08  5170.4  335.29  5197.8  345.86  5300.4  341.83  5375.6  342.29
  5462.3  338.36  5602.5  337.89  5661.8  335.23  5786.1  341.02  5918.4  353.34
#Mann=7,-1,0
  2826.5    0.05       0  4339.5    0.12       0  4583.8    0.05       0
  4937.6    0.12       0  4980.6    0.07       0  5006.1    0.12       0
  5014.4    0.05       0
Bank Sta=4980.6,5006.1
Exp/Cntr=0.3,0.1

Type RM Length L Ch R = 1,35130,556,556,556
BEGIN DESCRIPTION:
Clear Creek 59.0
END DESCRIPTION:
XS GIS Cut Line= 3
      2745376.03      6786810.97      2744126.00      6788261.00
      2743476.02      6789060.97
#Sta/Elev= 30
  3081.1  398.12  3244.1  392.21  3407.5  379.17  3627.0  370.16  3747.6  358.39
  3882.6  337.22  3989.0  328.69  4144.8  331.16  4194.1  326.18  4300.6  327.03
  4314.8  325.24  4335.7  327.29  4967.6  328.29  4975.7  322.58  4978.2  322.08
  5001.2  322.58  5017.1  322.97  5023.6  327.40  5031.5  324.83  5037.9  328.23
  5045.9  324.60  5052.3  327.99  5066.7  323.22  5081.0  323.48  5087.5  328.61
  5429.4  328.11  5464.6  331.26  5528.5  330.99  5806.6  346.32  6026.3  366.36
#Mann=3,-1,0
  3081.1    0.05       0  4975.7    0.04       0  5001.2    0.05       0
Bank Sta=4975.7,5001.2
Exp/Cntr=0.3,0.1

Type RM Length L Ch R = 1,34574,512,512,512
BEGIN DESCRIPTION:
Clear Creek 58.0
END DESCRIPTION:
XS GIS Cut Line= 3
      2745126.00      6787011.00      2743876.00      6788011.00
      2743125.97      6788511.02
#Sta/Elev= 30
  3387.7  383.81  3451.7  383.06  3551.8  378.02  3657.4  367.80  3735.9  363.95
  3764.7  361.61  3779.1  356.48  3863.9  344.59  3942.4  336.18  4120.1  326.73
  4177.7  327.45  4198.5  325.40  4270.5  324.58  4305.7  324.81  4326.6  327.30
  4398.6  324.89  4779.6  327.09  4921.0  327.23  4981.3  327.94  4983.2  322.62
  4985.8  322.12  5008.7  322.62  5074.1  322.93  5083.1  326.36  5096.6  327.65
  5434.7  325.87  5572.9  330.04  5593.9  332.98  5738.1  344.18  5889.9  361.31
#Mann=5,-1,0
  3387.7    0.05       0  4779.6     0.1       0  4921.0    0.05       0
  4983.2    0.04       0  5008.7    0.05       0
Bank Sta=4983.2,5008.7
Exp/Cntr=0.3,0.1

Type RM Length L Ch R = 1,34062,1067,1067,1067
BEGIN DESCRIPTION:
Clear Creek 57.0
END DESCRIPTION:
XS GIS Cut Line= 3
      2745008.99      6786677.45      2743776.00      6787761.00
      2743075.97      6788511.03
#Sta/Elev= 30
  3358.3  380.20  3519.1  373.09  3568.4  373.87  3632.0  371.70  3731.6  361.60
  3852.1  352.03  3936.6  347.46  4001.1  341.59  4050.4  339.83  4071.3  337.23
  4163.3  331.77  4319.9  325.88  4560.4  325.35  4574.2  323.84  4638.7  325.48
  4917.6  326.22  4971.7  326.84  4986.0  326.63  4992.6  325.13  5003.2  326.40
  5008.2  323.13  5010.8  322.63  5033.7  323.13  5035.2  326.63  5042.0  326.81
  5267.5  326.94  5629.2  325.80  5756.7  335.64  5983.4  362.04  6025.7  365.08
#Mann=5,-1,0
  3358.3    0.05       0  4917.6     0.1       0  5008.2    0.07       0
  5033.7     0.1       0  5267.5    0.05       0
Bank Sta=5008.2,5033.7
Exp/Cntr=0.3,0.1

Type RM Length L Ch R = 1,32995,549,549,549
BEGIN DESCRIPTION:
Clear Creek 56.0
END DESCRIPTION:
XS GIS Cut Line= 3
      2744828.30      6786231.56      2743326.00      6787211.00
      2742926.00      6788611.00
#Sta/Elev= 30
  3206.2  367.99  3229.8  366.36  3250.8  356.30  3256.8  362.18  3266.0  360.23
  3271.9  363.77  3280.6  361.29  3287.1  355.81  3293.0  359.63  3308.2  361.92
  3398.5  355.99  3634.1  344.30  4290.8  324.23  4385.5  322.79  4414.6  326.00
  4626.3  324.89  4992.0  325.46  5002.2  325.23  5003.7  322.71  5006.3  322.21
  5029.2  322.71  5050.3  325.94  5141.5  324.69  5650.9  325.11  5860.6  325.42
  5904.4  325.26  5935.6  329.83  6029.2  333.32  6360.7  365.48  6455.6  366.03
#Mann=9,-1,0
  3206.2    0.12       0  3398.5    0.05       0  4290.8    0.12       0
  4626.3     0.1       0  5003.7    0.07       0  5029.2     0.1       0
  5141.5    0.05       0  5650.9    0.12       0  5860.6    0.05       0
Bank Sta=5003.7,5029.2
Exp/Cntr=0.3,0.1

Type RM Length L Ch R = 1,32446,495,495,495
BEGIN DESCRIPTION:
Clear Creek 55.0
END DESCRIPTION:
XS GIS Cut Line= 3
      2744626.02      6785910.99      2743076.00      6786761.00
      2741776.02      6787560.99
#Sta/Elev= 30
  3236.6  362.16  3320.9  353.84  3401.8  347.44  3516.1  340.15  3644.7  334.49
  4142.1  324.56  4445.5  325.19  4467.0  322.38  4469.6  321.88  4492.5  322.38
  4495.9  325.71  4650.8  323.32  4981.6  324.83  4990.6  322.80  4996.3  324.98
  5001.5  322.72  5048.8  325.15  5427.1  323.09  5857.4  325.62  5937.4  327.16
  5971.7  327.77  5991.8  328.63  6007.2  327.01  6014.2  322.61  6028.5  322.96
  6043.9  328.36  6076.0  327.92  6159.9  327.82  6306.6  337.33  6530.8  361.68
#Mann=12,-1,0
  3236.6    0.05       0  3320.9    0.12       0  3401.8     0.1       0
  3516.1    0.12       0  3644.7    0.05       0  4142.1     0.1       0
  4467.0    0.07       0  4492.5     0.1       0  5857.4    0.12       0
  5937.4     0.1       0  5971.7    0.12       0  6076.0    0.05       0
Bank Sta=4467,4492.5
Exp/Cntr=0.3,0.1

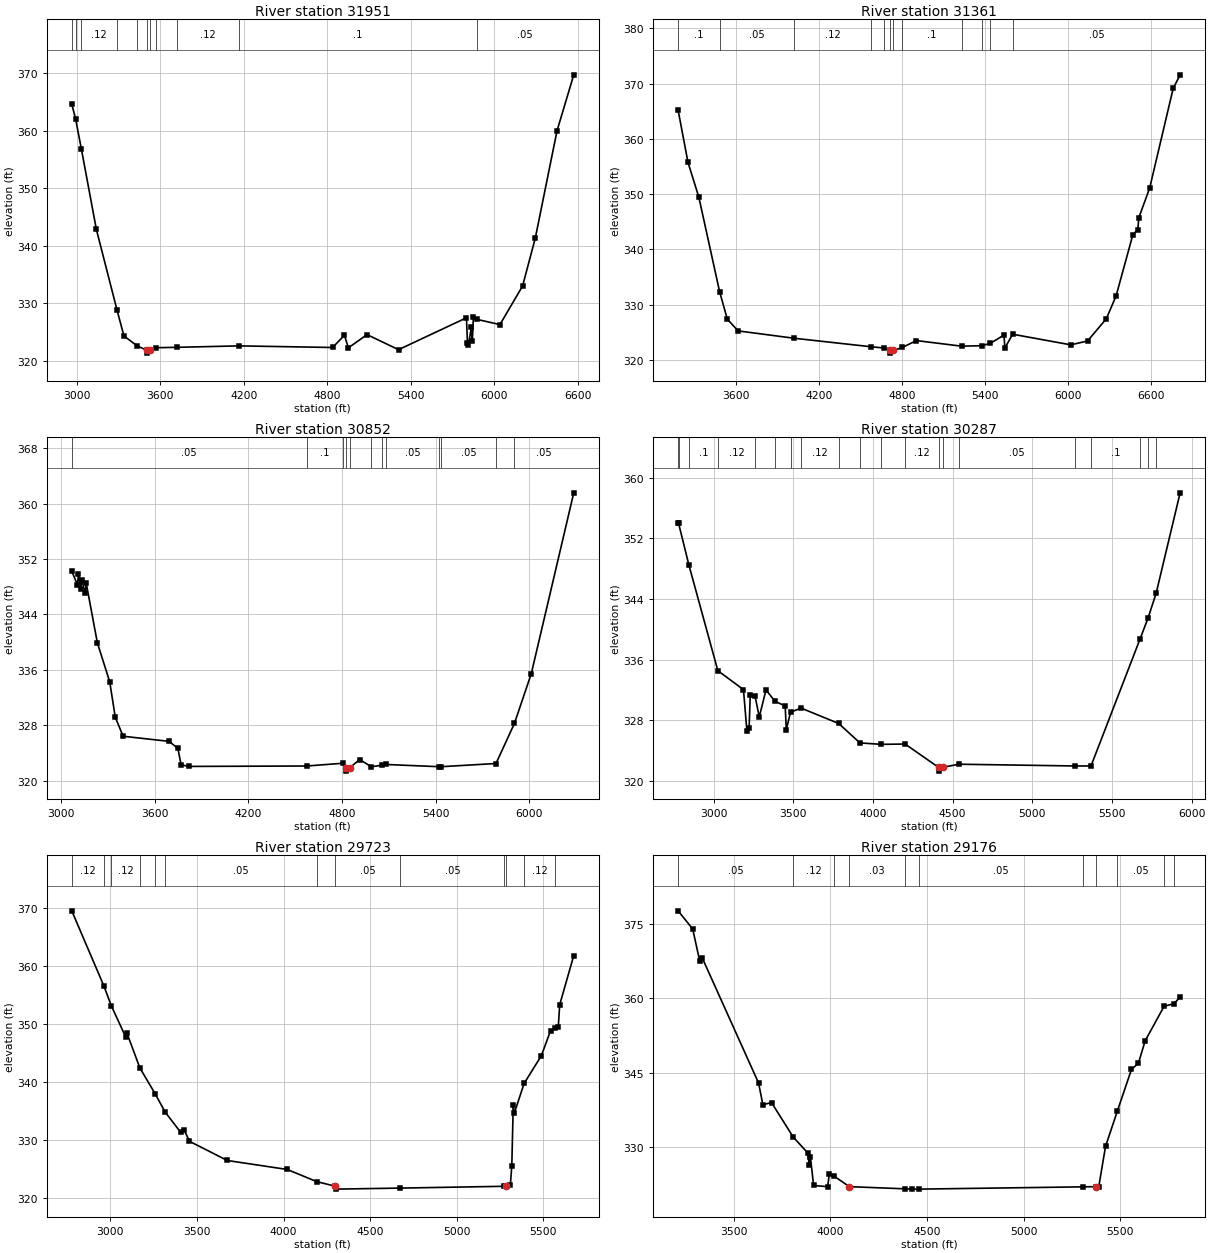
Type RM Length L Ch R = 1,31951,590,590,590
BEGIN DESCRIPTION:
Clear Creek 54.0
END DESCRIPTION:
XS GIS Cut Line= 3
      2744226.00      6785011.00      2742826.00      6786461.00
      2741676.04      6787560.97
#Sta/Elev= 30
  2963.8  364.64  2991.0  362.09  3033.5  356.75  3140.7  342.84  3289.0  328.83
  3338.7  324.34  3432.8  322.62  3502.7  321.85  3505.3  321.35  3528.2  321.85
  3565.8  322.29  3721.3  322.36  4165.3  322.61  4838.0  322.33  4922.9  324.46
  4951.2  322.27  5085.5  324.57  5311.6  321.95  5799.7  327.49  5807.0  323.09
  5813.9  322.77  5835.3  325.86  5842.2  323.38  5849.4  327.57  5874.5  327.22
  6040.3  326.31  6202.9  333.01  6294.8  341.39  6450.5  359.99  6570.7  369.72
#Mann=11,-1,0
  2963.8    0.05       0  2991.0     0.1       0  3033.5    0.12       0
  3289.0    0.05       0  3432.8    0.12       0  3502.7    0.07       0
  3528.2    0.12       0  3565.8     0.1       0  3721.3    0.12       0
  4165.3     0.1       0  5874.5    0.05       0
Bank Sta=3502.7,3528.2
Exp/Cntr=0.3,0.1

Type RM Length L Ch R = 1,31361,509,509,509
BEGIN DESCRIPTION:
Clear Creek 53.0
END DESCRIPTION:
XS GIS Cut Line= 3
      2743976.02      6784860.99      2742576.00      6786011.00
      2741425.97      6787411.03
#Sta/Elev= 30
  3184.7  365.18  3255.8  355.76  3334.0  349.47  3483.8  332.38  3539.9  327.36
  3618.1  325.25  4023.3  323.92  4574.8  322.39  4669.7  322.16  4713.2  321.73
  4715.7  321.23  4738.8  321.73  4802.9  322.25  4904.6  323.50  5230.3  322.49
  5377.2  322.57  5438.5  323.00  5536.8  324.50  5543.3  322.16  5599.1  324.65
  6019.0  322.73  6140.2  323.43  6275.8  327.46  6346.2  331.60  6467.4  342.69
  6502.6  343.58  6510.5  345.77  6588.3  351.09  6758.0  369.13  6808.3  371.60
#Mann=12,-1,0
  3184.7     0.1       0  3483.8    0.05       0  4023.3    0.12       0
  4574.8    0.05       0  4669.7    0.12       0  4713.2    0.07       0
  4738.8    0.12       0  4802.9     0.1       0  5230.3    0.12       0
  5377.2     0.1       0  5438.5    0.12       0  5599.1    0.05       0
Bank Sta=4713.2,4738.8
Exp/Cntr=0.3,0.1

Type RM Length L Ch R = 1,30852,565,565,565
BEGIN DESCRIPTION:
Clear Creek 52.0
END DESCRIPTION:
XS GIS Cut Line= 3
      2743725.97      6784811.02      2742176.00      6785961.00
      2741078.48      6786626.85
#Sta/Elev= 30
  3070.0  350.26  3106.5  348.26  3112.7  349.85  3127.4  347.65  3133.6  348.95
  3156.6  347.12  3162.8  348.48  3233.7  339.91  3313.0  334.26  3348.5  329.16
  3398.6  326.40  3692.6  325.66  3749.1  324.66  3770.0  322.27  3820.0  322.04
  4574.1  322.10  4807.7  322.50  4823.0  321.86  4825.6  321.36  4849.5  321.86
  4913.4  323.02  4987.6  322.00  5059.2  322.22  5082.1  322.32  5422.6  322.00
  5434.4  322.00  5786.0  322.46  5904.2  328.27  6011.9  335.45  6283.7  361.56
#Mann=12,-1,0
  3070.0    0.05       0  4574.1     0.1       0  4807.7    0.12       0
  4823.0    0.05       0  4849.5    0.12       0  4987.6    0.05       0
  5059.2    0.12       0  5082.1    0.05       0  5422.6    0.12       0
  5434.4    0.05       0  5786.0    0.12       0  5904.2    0.05       0
Bank Sta=4823,4849.5
Exp/Cntr=0.3,0.1

Type RM Length L Ch R = 1,30287,564,564,564
BEGIN DESCRIPTION:
Clear Creek 51.0
END DESCRIPTION:
XS GIS Cut Line= 3
      2743425.98      6783911.02      2741876.00      6785511.00
      2740977.05      6785721.03
#Sta/Elev= 30
  2777.0  354.02  2779.3  354.02  2845.0  348.45  3026.2  334.56  3187.1  332.06
  3208.5  326.65  3222.5  327.03  3229.6  331.30  3260.1  331.18  3286.2  328.46
  3328.6  332.03  3384.9  330.52  3448.8  329.91  3455.9  326.80  3482.3  329.08
  3548.5  329.63  3784.7  327.60  3918.0  325.04  4051.3  324.85  4201.8  324.89
  4411.3  321.82  4414.0  321.32  4438.1  321.82  4538.6  322.23  5266.2  322.00
  5368.4  322.00  5675.0  338.67  5726.5  341.50  5777.2  344.76  5927.8  358.00
#Mann=20,-1,0
  2777.0     0.1       0  2779.3    0.12       0  2845.0     0.1       0
  3026.2    0.12       0  3260.1     0.1       0  3384.9    0.12       0
  3482.3    0.05       0  3548.5    0.12       0  3784.7     0.1       0
  3918.0    0.12       0  4051.3    0.05       0  4201.8    0.12       0
  4411.3    0.03       0  4438.1    0.12       0  4538.6    0.05       0
  5266.2    0.12       0  5368.4     0.1       0  5675.0    0.12       0
  5726.5     0.1       0  5777.2    0.05       0
Bank Sta=4411.3,4438.1
Exp/Cntr=0.3,0.1

Type RM Length L Ch R = 1,29723,547,547,547
BEGIN DESCRIPTION:
Clear Creek 50.0
END DESCRIPTION:
XS GIS Cut Line= 3
      2743226.00      6783411.00      2741676.00      6785011.00
      2741075.99      6785311.00
#Sta/Elev= 30
  2776.9  369.52  2962.9  356.52  3004.8  353.17  3088.0  347.76  3095.2  348.44
  3170.0  342.42  3259.0  337.92  3315.9  334.81  3406.2  331.28  3427.6  331.64
  3455.9  329.76  3675.0  326.44  4021.5  324.89  4190.7  322.80  4298.0  322.00
  4300.7  321.50  4674.2  321.68  5275.4  321.99  5285.6  322.00  5309.2  322.19
  5317.6  325.48  5326.0  335.93  5331.6  334.57  5388.7  339.73  5488.1  344.51
  5541.2  348.82  5567.2  349.25  5586.0  349.48  5594.3  353.32  5675.4  361.80
#Mann=13,-1,0
  2776.9    0.12       0  2962.9     0.1       0  3004.8    0.12       0
  3170.0    0.05       0  3259.0    0.12       0  3315.9    0.05       0
  4190.7    0.12       0  4298.0    0.05       0  4674.2    0.05       0
  5275.4     0.1       0  5285.6    0.12       0  5388.7    0.12       0
  5567.2    0.05       0
Bank Sta=4298,5285.6
Exp/Cntr=0.3,0.1

Type RM Length L Ch R = 1,29176,540,540,540
BEGIN DESCRIPTION:
Clear Creek 49.0
END DESCRIPTION:
XS GIS Cut Line= 3
      2742325.99      6782911.01      2741526.00      6784511.00
      2740975.64      6785106.07
#Sta/Elev= 30
  3211.4  377.67  3286.9  374.00  3323.2  367.52  3337.2  368.08  3627.9  342.92
  3650.2  338.54  3694.9  338.97  3807.0  332.03  3882.2  328.82  3890.6  326.39
  3896.2  328.03  3913.0  322.24  3985.6  322.00  3994.0  324.50  4020.3  324.08
  4098.2  322.00  4385.8  321.56  4422.3  321.50  4456.3  321.50  5306.0  321.96
  5376.9  322.00  5389.5  322.00  5424.6  330.13  5486.2  337.30  5559.0  345.68
  5594.7  346.91  5629.9  351.44  5727.7  358.40  5779.9  358.94  5810.8  360.30
#Mann=11,-1,0
  3211.4    0.05       0  3807.0    0.12       0  4020.3    0.05       0
  4098.2    0.03       0  4385.8    0.12       0  4456.3    0.05       0
  5306.0     0.1       0  5376.9    0.12       0  5486.2    0.05       0
  5727.7    0.12       0  5779.9    0.05       0
Bank Sta=4098.2,5376.9
Exp/Cntr=0.3,0.1

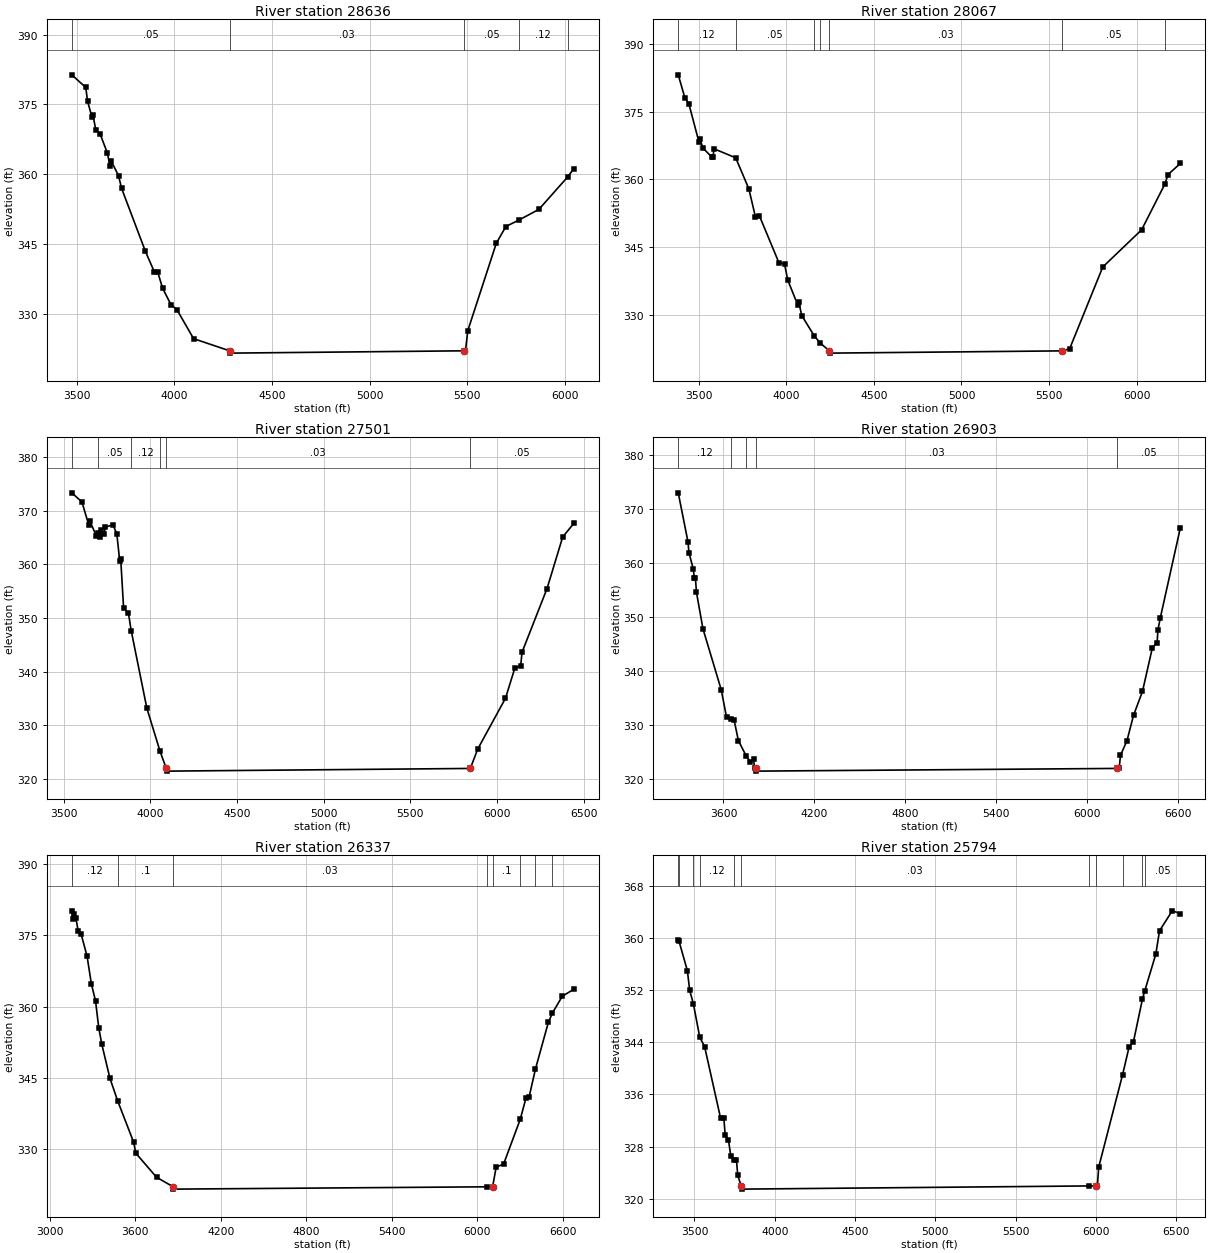
Type RM Length L Ch R = 1,28636,569,569,569
BEGIN DESCRIPTION:
Clear Creek 48.0
END DESCRIPTION:
XS GIS Cut Line= 3
      2741975.99      6782811.01      2741176.00      6784111.00
      2740869.45      6785110.63
#Sta/Elev= 30
  3473.9  381.35  3545.4  378.65  3555.0  375.67  3576.3  372.36  3582.1  372.73
  3597.5  369.43  3618.8  368.67  3655.5  364.61  3670.9  361.65  3676.8  362.74
  3713.5  359.65  3728.9  356.96  3850.7  343.44  3896.6  338.99  3914.2  338.94
  3939.5  335.42  3982.1  331.93  4012.9  330.82  4098.0  324.61  4282.4  322.00
  4285.0  321.50  5484.8  322.00  5490.8  322.00  5502.4  326.30  5648.8  345.14
  5697.7  348.73  5764.0  350.11  5866.7  352.41  6014.5  359.40  6045.9  361.20
#Mann=5,-1,0
  3473.9    0.05       0  4282.4    0.03       0  5484.8    0.05       0
  5764.0    0.12       0  6014.5    0.05       0
Bank Sta=4282.4,5484.8
Exp/Cntr=0.3,0.1

Type RM Length L Ch R = 1,28067,566,566,566
BEGIN DESCRIPTION:
Clear Creek 47.0
END DESCRIPTION:
XS GIS Cut Line= 3
      2740875.99      6782311.04      2740676.00      6783911.00
      2740576.00      6785161.00
#Sta/Elev= 30
  3383.1  383.18  3420.9  378.10  3443.5  376.79  3501.5  368.27  3506.5  369.02
  3524.1  366.96  3574.5  364.96  3582.1  365.01  3587.1  366.79  3711.2  364.79
  3786.2  357.91  3824.0  351.67  3846.6  351.93  3957.5  341.57  3990.2  341.23
  4007.9  337.75  4065.8  332.13  4070.9  332.84  4088.5  329.81  4159.3  325.35
  4192.2  323.79  4246.1  322.00  4248.8  321.50  5573.6  322.00  5617.5  322.45
  5806.8  340.59  6028.8  348.84  6161.8  359.01  6179.3  361.08  6249.5  363.53
#Mann=7,-1,0
  3383.1    0.12       0  3711.2    0.05       0  4159.3    0.12       0
  4192.2    0.05       0  4246.1    0.03       0  5573.6    0.05       0
  6161.8    0.12       0
Bank Sta=4246.1,5573.6
Exp/Cntr=0.3,0.1

Type RM Length L Ch R = 1,27501,598,598,598
BEGIN DESCRIPTION:
Clear Creek 46.0
END DESCRIPTION:
XS GIS Cut Line= 3
      2740775.98      6782561.04      2740126.00      6783861.00
      2740476.00      6785261.01
#Sta/Elev= 30
  3546.6  373.33  3605.3  371.63  3644.4  367.37  3650.0  368.16  3689.1  365.23
  3698.8  365.86  3711.5  365.07  3717.1  366.36  3733.8  365.72  3739.4  366.92
  3784.1  367.39  3806.5  365.68  3823.3  360.63  3828.9  361.06  3845.6  351.85
  3873.6  350.90  3889.5  347.65  3979.8  333.22  4056.2  325.16  4091.9  322.00
  4094.6  321.50  5845.8  322.00  5889.0  325.64  6048.8  335.07  6102.9  340.72
  6136.4  341.10  6144.2  343.64  6288.5  355.51  6378.7  365.10  6443.1  367.64
#Mann=6,-1,0
  3546.6    0.12       0  3698.8    0.05       0  3889.5    0.12       0
  4056.2    0.05       0  4091.9    0.03       0  5845.8    0.05       0
Bank Sta=4091.9,5845.8
Exp/Cntr=0.3,0.1

Type RM Length L Ch R = 1,26903,566,566,566
BEGIN DESCRIPTION:
Clear Creek 45.0
END DESCRIPTION:
XS GIS Cut Line= 3
      2740625.98      6782561.02      2739526.00      6783861.00
      2740326.02      6785261.04
#Sta/Elev= 30
  3301.2  372.95  3365.5  363.90  3372.0  361.88  3400.6  358.86  3407.2  357.25
  3414.9  357.13  3421.4  354.59  3464.3  347.83  3585.2  336.53  3620.3  331.44
  3650.9  331.21  3669.7  330.99  3698.3  327.16  3748.7  324.37  3776.3  323.25
  3798.4  323.80  3804.9  322.08  3812.0  322.00  3814.7  321.50  6199.1  322.00
  6213.4  322.15  6221.4  324.41  6264.6  327.15  6307.7  331.82  6366.8  336.24
  6432.3  344.33  6463.2  345.26  6469.0  347.64  6484.8  349.87  6616.6  366.46
#Mann=5,-1,0
  3301.2    0.12       0  3650.9     0.1       0  3748.7    0.05       0
  3812.0    0.03       0  6199.1    0.05       0
Bank Sta=3812,6199.1
Exp/Cntr=0.3,0.1

Type RM Length L Ch R = 1,26337,543,543,543
BEGIN DESCRIPTION:
Clear Creek 44.0
END DESCRIPTION:
XS GIS Cut Line= 3
      2740676.01      6782461.00      2739126.00      6783461.00
      2737526.00      6783961.00
#Sta/Elev= 30
  3155.4  380.20  3163.0  378.58  3168.9  379.53  3184.1  378.77  3199.3  376.05
  3220.4  375.36  3262.7  370.63  3293.0  364.76  3322.0  361.21  3344.5  355.56
  3365.6  352.11  3423.0  344.87  3478.3  340.03  3589.3  331.39  3604.5  329.08
  3749.7  324.01  3866.0  322.00  3868.7  321.50  6066.5  321.99  6106.6  322.00
  6131.5  326.12  6183.9  326.80  6300.4  336.23  6341.0  340.75  6362.5  340.93
  6406.8  346.80  6498.2  356.76  6526.4  358.66  6595.1  362.18  6676.3  363.66
#Mann=8,-1,0
  3155.4    0.12       0  3478.3     0.1       0  3866.0    0.03       0
  6066.5    0.12       0  6106.6     0.1       0  6300.4    0.05       0
  6406.8    0.12       0  6526.4    0.05       0
Bank Sta=3866,6106.6
Exp/Cntr=0.3,0.1

Type RM Length L Ch R = 1,25794,584,584,584
BEGIN DESCRIPTION:
Clear Creek 43.0
END DESCRIPTION:
XS GIS Cut Line= 3
      2740026.03      6782060.98      2738776.00      6783061.00
      2737475.96      6783861.02
#Sta/Elev= 30
  3398.8  359.64  3403.4  359.51  3455.7  354.96  3470.1  351.95  3493.7  349.83
  3532.6  344.78  3562.9  343.34  3662.2  332.41  3683.0  332.37  3691.0  329.83
  3711.8  328.99  3726.2  326.59  3748.0  326.03  3761.4  325.95  3769.4  323.63
  3790.5  322.00  3793.3  321.50  5955.3  321.99  5998.7  322.00  6009.4  322.00
  6017.9  324.88  6166.8  339.05  6207.2  343.29  6234.3  344.09  6290.1  350.59
  6304.3  351.85  6373.4  357.48  6396.5  361.07  6475.8  364.13  6526.1  363.72
#Mann=11,-1,0
  3398.8     0.1       0  3403.4    0.12       0  3493.7     0.1       0
  3532.6    0.12       0  3748.0    0.05       0  3790.5    0.03       0
  5955.3    0.12       0  5998.7    0.05       0  6166.8    0.05       0
  6290.1    0.12       0  6304.3    0.05       0
Bank Sta=3790.5,5998.7
Exp/Cntr=0.3,0.1