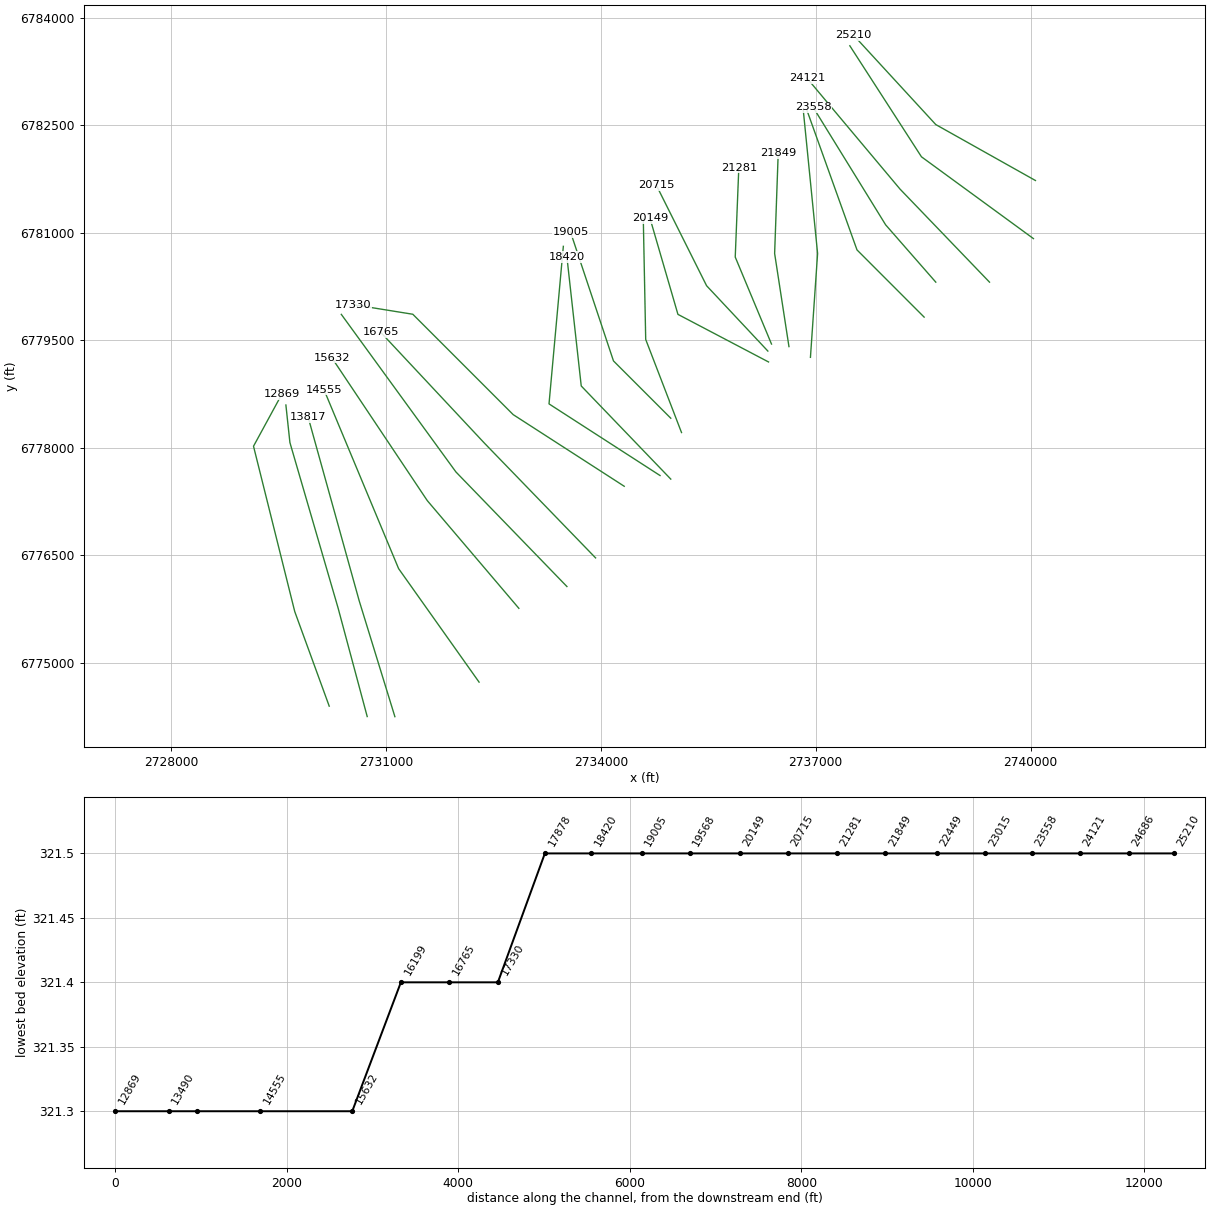
HEC-RAS study Clear Creek.prj: Clear Creek Base Level Engineering

--- Clear Creek.g01 (geometry) --- (continued)

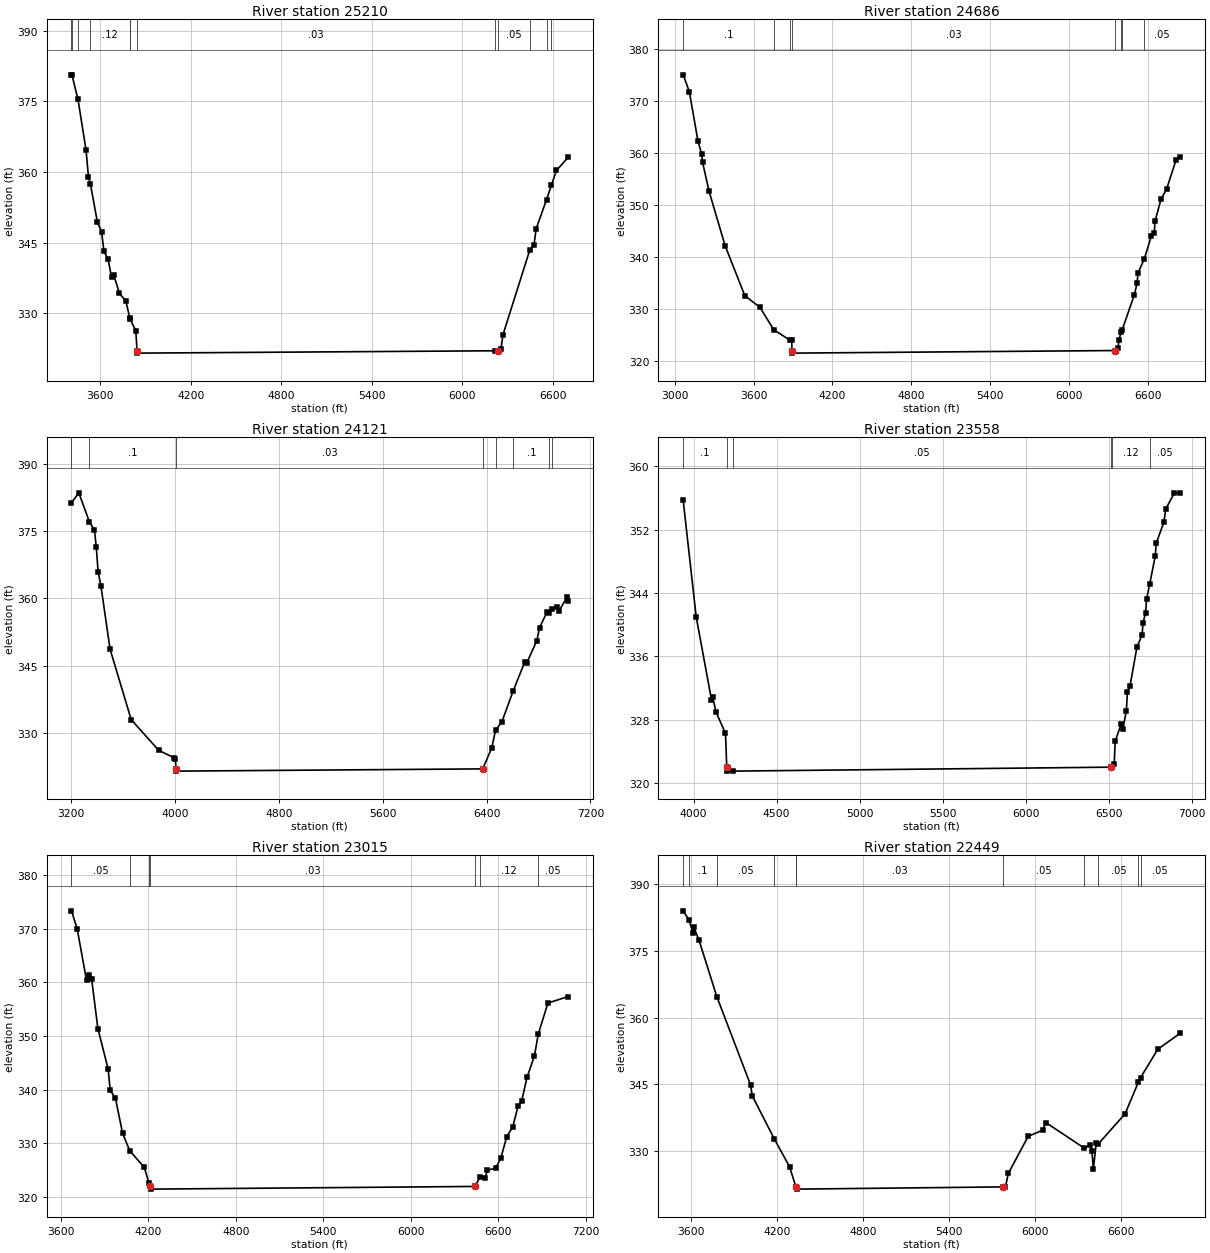
Type RM Length L Ch R = 1,25210,524,524,524
BEGIN DESCRIPTION:
Clear Creek 42.0
END DESCRIPTION:
XS GIS Cut Line= 3
      2740067.50      6781729.88      2738676.00      6782511.00
      2737525.99      6783761.01
#Sta/Elev= 30
  3408.4  380.67  3411.1  380.67  3451.6  375.43  3505.1  364.61  3521.1  358.91
  3533.7  357.53  3580.4  349.30  3607.8  347.35  3623.7  343.12  3651.2  341.46
  3673.9  337.62  3688.8  338.08  3726.4  334.22  3769.8  332.48  3795.0  328.94
  3796.6  328.75  3834.8  326.29  3843.2  322.00  3846.0  321.50  6216.2  322.00
  6237.2  322.00  6256.6  322.36  6270.8  325.46  6448.4  343.44  6476.1  344.45
  6490.3  347.93  6559.5  354.15  6591.3  357.16  6624.7  360.33  6702.7  363.13
#Mann=12,-1,0
  3408.4    0.05       0  3411.1    0.12       0  3451.6     0.1       0
  3533.7    0.12       0  3795.0     0.1       0  3796.6    0.05       0
  3843.2    0.03       0  6216.2    0.12       0  6237.2    0.05       0
  6448.4    0.05       0  6559.5    0.12       0  6591.3    0.05       0
Bank Sta=3843.2,6237.2
Exp/Cntr=0.3,0.1

Type RM Length L Ch R = 1,24686,565,565,565
BEGIN DESCRIPTION:
Clear Creek 41.0
END DESCRIPTION:
XS GIS Cut Line= 3
      2740039.64      6780918.75      2738476.00      6782061.00
      2737476.00      6783611.00
#Sta/Elev= 30
  3063.6  375.06  3110.6  371.81  3175.5  362.37  3204.3  359.83  3211.0  358.25
  3261.2  352.61  3382.5  342.19  3533.1  332.55  3648.1  330.31  3753.3  326.00
  3875.9  324.00  3890.6  323.95  3891.1  322.00  3893.9  321.50  6354.6  322.00
  6374.4  322.47  6380.5  324.02  6398.5  325.61  6404.1  325.86  6498.4  332.75
  6519.6  334.99  6525.5  336.93  6572.9  339.53  6628.5  344.11  6649.6  344.54
  6655.5  346.86  6701.1  351.12  6743.3  353.04  6815.9  358.69  6844.6  359.29
#Mann=8,-1,0
  3063.6     0.1       0  3753.3    0.12       0  3875.9    0.05       0
  3891.1    0.03       0  6354.6    0.05       0  6398.5     0.1       0
  6404.1    0.12       0  6572.9    0.05       0
Bank Sta=3891.1,6354.6
Exp/Cntr=0.3,0.1

Type RM Length L Ch R = 1,24121,563,563,563
BEGIN DESCRIPTION:
Clear Creek 40.0
END DESCRIPTION:
XS GIS Cut Line= 3
      2739426.02      6780310.98      2738176.00      6781611.00
      2736875.99      6783161.01
#Sta/Elev= 30
  3201.6  381.32  3258.1  383.52  3339.9  377.02  3378.5  375.24  3392.7  371.37
  3406.8  365.92  3427.9  362.85  3498.6  348.70  3661.2  332.99  3873.5  326.13
  3993.6  324.46  4000.8  324.17  4007.7  322.00  4010.5  321.50  6369.8  322.00
  6439.4  326.67  6468.5  330.59  6517.4  332.50  6605.3  339.43  6694.4  345.88
  6708.7  345.59  6786.8  350.58  6807.6  353.49  6864.8  356.91  6883.0  356.83
  6900.4  357.73  6942.9  358.16  6957.2  357.19  7020.9  360.32  7028.1  359.46
#Mann=8,-1,0
  3201.6    0.05       0  3339.9     0.1       0  4007.7    0.03       0
  6369.8     0.1       0  6468.5    0.12       0  6605.3     0.1       0
  6883.0    0.05       0  6900.4     0.1       0
Bank Sta=4007.7,6369.8
Exp/Cntr=0.3,0.1

Type RM Length L Ch R = 1,23558,543,543,543
BEGIN DESCRIPTION:
Clear Creek 39.0
END DESCRIPTION:
XS GIS Cut Line= 3
      2738676.02      6780310.98      2737976.00      6781111.00
      2736963.62      6782752.70
#Sta/Elev= 30
  3937.2  355.72  4015.5  341.01  4107.6  330.53  4114.2  330.90  4136.1  328.92
  4192.1  326.26  4199.7  322.00  4202.5  321.50  4235.1  321.50  6511.4  322.00
  6522.8  322.03  6533.7  322.40  6539.5  325.27  6576.2  327.49  6585.7  326.78
  6607.0  329.13  6612.9  331.50  6628.3  332.20  6670.8  337.20  6701.6  338.70
  6707.5  340.28  6722.9  341.50  6728.8  343.26  6748.2  345.21  6780.9  348.69
  6786.7  350.29  6832.9  352.96  6844.8  354.67  6896.8  356.67  6929.0  356.59
#Mann=6,-1,0
  3937.2     0.1       0  4199.7    0.03       0  4235.1    0.05       0
  6511.4     0.1       0  6522.8    0.12       0  6748.2    0.05       0
Bank Sta=4199.7,6511.4
Exp/Cntr=0.3,0.1

Type RM Length L Ch R = 1,23015,566,566,566
BEGIN DESCRIPTION:
Clear Creek 38.0
END DESCRIPTION:
XS GIS Cut Line= 3
      2738513.29      6779822.80      2737576.00      6780761.00
      2736874.52      6782717.68
#Sta/Elev= 30
  3673.9  373.33  3713.1  369.94  3776.8  360.39  3790.9  361.31  3812.1  360.59
  3854.6  351.41  3925.3  343.85  3939.4  339.88  3974.8  338.46  4024.3  331.88
  4073.6  328.63  4172.8  325.55  4204.1  322.72  4215.0  322.00  4217.8  321.50
  6440.6  322.00  6475.4  323.80  6508.6  323.52  6525.3  325.06  6581.5  325.38
  6617.6  327.33  6657.3  331.22  6699.2  333.14  6735.3  336.97  6760.7  338.00
  6796.8  342.33  6847.6  346.32  6873.8  350.36  6939.9  356.15  7078.7  357.37
#Mann=7,-1,0
  3673.9    0.05       0  4073.6    0.12       0  4204.1    0.05       0
  4215.0    0.03       0  6440.6    0.05       0  6475.4    0.12       0
  6873.8    0.05       0
Bank Sta=4215,6440.6
Exp/Cntr=0.3,0.1

Type RM Length L Ch R = 1,22449,600,600,600
BEGIN DESCRIPTION:
Clear Creek 37.0
END DESCRIPTION:
XS GIS Cut Line= 3
      2736926.00      6779261.04      2737026.00      6780711.00
      2736826.00      6782711.02
#Sta/Elev= 30
  3546.6  383.97  3586.2  381.96  3615.5  378.97  3620.5  380.28  3656.8  377.40
  3781.3  364.70  4017.7  344.79  4027.7  342.48  4181.6  332.79  4288.3  326.54
  4332.1  322.06  4335.3  322.00  4338.1  321.50  5775.2  322.00  5793.9  322.00
  5814.0  325.02  5952.2  333.34  6052.7  334.73  6075.3  336.45  6343.1  330.72
  6386.9  331.45  6396.9  330.09  6407.0  325.95  6427.1  331.92  6441.3  331.64
  6628.1  338.41  6720.6  345.49  6735.9  346.52  6856.7  352.91  7010.0  356.44
#Mann=11,-1,0
  3546.6    0.05       0  3586.2     0.1       0  3781.3    0.05       0
  4181.6    0.12       0  4332.1    0.05       0  4335.3    0.03       0
  5775.2    0.05       0  6343.1    0.12       0  6441.3    0.05       0
  6720.6    0.12       0  6735.9    0.05       0
Bank Sta=4335.3,5775.2
Exp/Cntr=0.3,0.1

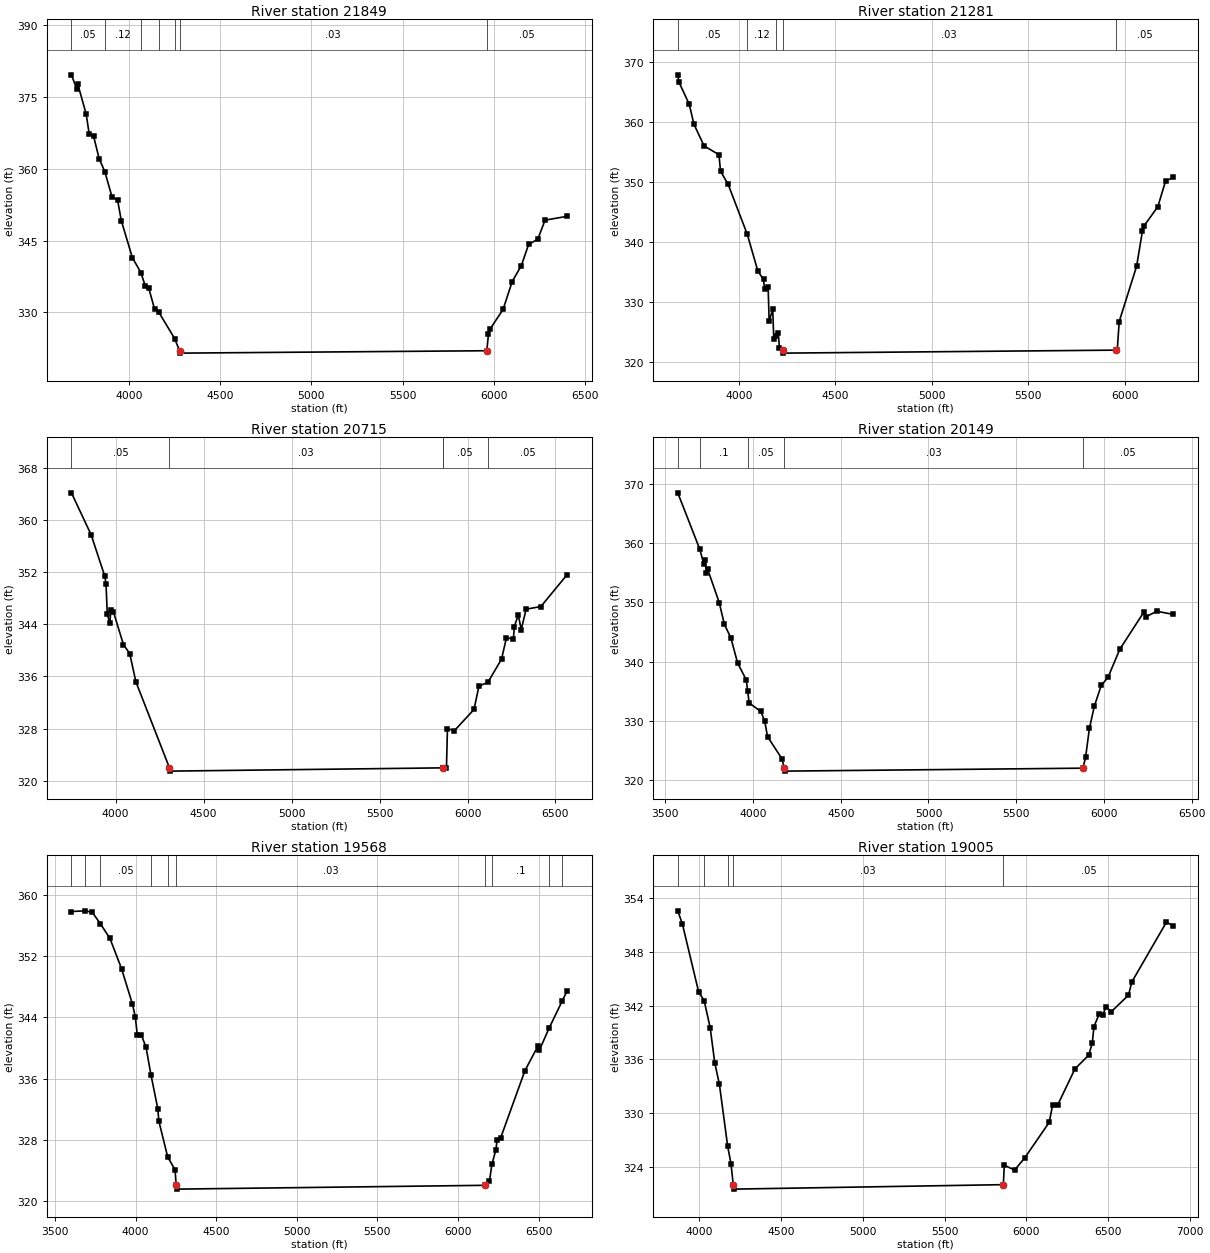
Type RM Length L Ch R = 1,21849,568,568,568
BEGIN DESCRIPTION:
Clear Creek 36.0
END DESCRIPTION:
XS GIS Cut Line= 3
      2736626.00      6779411.00      2736426.00      6780711.00
      2736476.00      6782111.01
#Sta/Elev= 30
  3684.7  379.57  3713.8  376.60  3718.8  377.72  3765.6  371.36  3782.1  367.20
  3806.1  366.77  3836.5  362.08  3867.7  359.36  3907.3  354.08  3937.6  353.44
  3957.9  349.16  4018.6  341.43  4065.2  338.31  4089.4  335.52  4108.4  335.07
  4140.0  330.74  4163.9  330.01  4250.6  324.53  4277.3  322.00  4280.2  321.50
  5961.4  322.00  5970.6  325.43  5978.1  326.45  6050.7  330.62  6100.7  336.44
  6150.7  339.76  6190.8  344.19  6240.8  345.26  6280.8  349.25  6400.9  350.04
#Mann=7,-1,0
  3684.7    0.05       0  3867.7    0.12       0  4065.2    0.05       0
  4163.9    0.12       0  4250.6    0.05       0  4277.3    0.03       0
  5961.4    0.05       0
Bank Sta=4277.3,5961.4
Exp/Cntr=0.3,0.1

Type RM Length L Ch R = 1,21281,566,566,566
BEGIN DESCRIPTION:
Clear Creek 35.0
END DESCRIPTION:
XS GIS Cut Line= 3
      2736382.13      6779446.75      2735876.00      6780661.00
      2735926.00      6781910.98
#Sta/Elev= 30
  3684.1  367.89  3690.6  366.65  3743.7  362.97  3767.5  359.68  3820.6  356.03
  3897.5  354.58  3905.4  351.84  3945.1  349.62  4044.4  341.28  4098.9  335.17
  4128.2  333.78  4133.6  332.17  4152.0  332.59  4157.4  326.82  4175.8  328.85
  4181.3  323.83  4193.4  324.32  4205.1  324.78  4210.5  322.36  4226.8  322.00
  4229.6  321.50  5953.7  322.00  5960.4  322.00  5970.4  326.77  6060.5  335.97
  6090.5  341.79  6100.5  342.77  6170.6  345.92  6210.6  350.19  6250.6  350.78
#Mann=5,-1,0
  3684.1    0.05       0  4044.4    0.12       0  4193.4    0.05       0
  4226.8    0.03       0  5953.7    0.05       0
Bank Sta=4226.8,5953.7
Exp/Cntr=0.3,0.1

Type RM Length L Ch R = 1,20715,566,566,566
BEGIN DESCRIPTION:
Clear Creek 34.0
END DESCRIPTION:
XS GIS Cut Line= 3
      2736331.44      6779348.61      2735476.00      6780261.00
      2734776.02      6781660.96
#Sta/Elev= 30
  3749.3  364.14  3861.1  357.72  3938.8  351.36  3945.7  350.21  3953.0  345.55
  3967.2  344.19  3974.0  346.20  3988.2  345.88  4044.8  340.89  4080.5  339.51
  4115.6  335.18  4306.3  322.00  4309.1  321.50  5858.1  322.00  5859.5  322.00
  5880.4  322.00  5886.0  328.01  5925.2  327.69  6037.0  330.95  6064.9  334.54
  6115.4  335.09  6193.5  338.66  6221.4  341.96  6260.6  341.71  6266.2  343.65
  6288.5  345.44  6305.3  343.19  6333.3  346.31  6417.1  346.72  6565.2  351.57
#Mann=5,-1,0
  3749.3    0.05       0  4306.3    0.03       0  5858.1    0.12       0
  5859.5    0.05       0  6115.4    0.05       0
Bank Sta=4306.3,5859.5
Exp/Cntr=0.3,0.1

Type RM Length L Ch R = 1,20149,581,581,581
BEGIN DESCRIPTION:
Clear Creek 33.0
END DESCRIPTION:
XS GIS Cut Line= 3
      2736340.95      6779196.41      2735076.00      6779861.00
      2734686.36      6781200.89
#Sta/Elev= 30
  3571.1  368.48  3696.6  358.95  3719.3  356.47  3725.0  357.20  3734.8  354.97
  3741.3  355.58  3807.5  349.95  3836.5  346.29  3873.6  344.01  3912.1  339.75
  3961.8  336.89  3969.0  335.06  3978.2  333.00  4044.4  331.57  4066.4  329.97
  4082.8  327.32  4164.1  323.62  4178.5  322.00  4181.4  321.50  5880.5  322.00
  5895.6  323.86  5917.4  328.75  5945.8  332.50  5984.5  335.96  6023.2  337.33
  6090.3  342.06  6228.9  348.41  6240.0  347.57  6301.8  348.48  6395.4  347.96
#Mann=5,-1,0
  3571.1    0.05       0  3696.6     0.1       0  3969.0    0.05       0
  4178.5    0.03       0  5880.5    0.05       0
Bank Sta=4178.5,5880.5
Exp/Cntr=0.3,0.1

Type RM Length L Ch R = 1,19568,563,563,563
BEGIN DESCRIPTION:
Clear Creek 32.0
END DESCRIPTION:
XS GIS Cut Line= 3
      2735126.00      6778211.00      2734626.00      6779511.00
      2734592.39      6781191.72
#Sta/Elev= 30
  3602.2  357.89  3687.6  357.98  3731.8  357.78  3781.9  356.28  3841.1  354.36
  3912.9  350.41  3980.4  345.76  3998.6  344.05  4010.4  341.75  4035.1  341.74
  4065.1  340.08  4095.1  336.52  4137.9  332.04  4144.3  330.43  4199.1  325.72
  4245.1  324.03  4251.9  322.00  4254.8  321.50  6168.2  322.00  6195.3  322.56
  6210.3  324.73  6235.3  326.67  6242.9  327.97  6265.3  328.25  6415.3  337.03
  6495.3  340.22  6505.3  339.74  6565.7  342.62  6647.8  346.22  6676.1  347.45
#Mann=10,-1,0
  3602.2    0.05       0  3687.6    0.12       0  3781.9    0.05       0
  4095.1    0.12       0  4199.1    0.05       0  4251.9    0.03       0
  6168.2    0.05       0  6210.3     0.1       0  6565.7    0.05       0
  6647.8     0.1       0
Bank Sta=4251.9,6168.2
Exp/Cntr=0.3,0.1

Type RM Length L Ch R = 1,19005,585,585,585
BEGIN DESCRIPTION:
Clear Creek 31.0
END DESCRIPTION:
XS GIS Cut Line= 3
      2734975.97      6778411.03      2734176.00      6779211.00
      2733576.00      6781011.00
#Sta/Elev= 30
  3868.7  352.59  3896.9  351.12  3995.9  343.56  4030.1  342.54  4066.7  339.54
  4094.9  335.60  4123.2  333.20  4173.5  326.31  4193.9  324.35  4207.7  322.00
  4210.5  321.50  5858.6  322.00  5864.4  324.17  5927.6  323.63  5990.9  325.03
  6138.5  328.95  6159.5  330.86  6191.2  330.92  6296.6  334.94  6380.9  336.48
  6402.0  337.82  6412.5  339.65  6444.1  341.05  6465.2  340.92  6486.3  341.88
  6517.9  341.31  6623.3  343.17  6644.4  344.66  6855.2  351.32  6897.4  350.94
#Mann=5,-1,0
  3868.7    0.05       0  4030.1    0.12       0  4173.5    0.05       0
  4207.7    0.03       0  5858.6    0.05       0
Bank Sta=4207.7,5858.6
Exp/Cntr=0.3,0.1

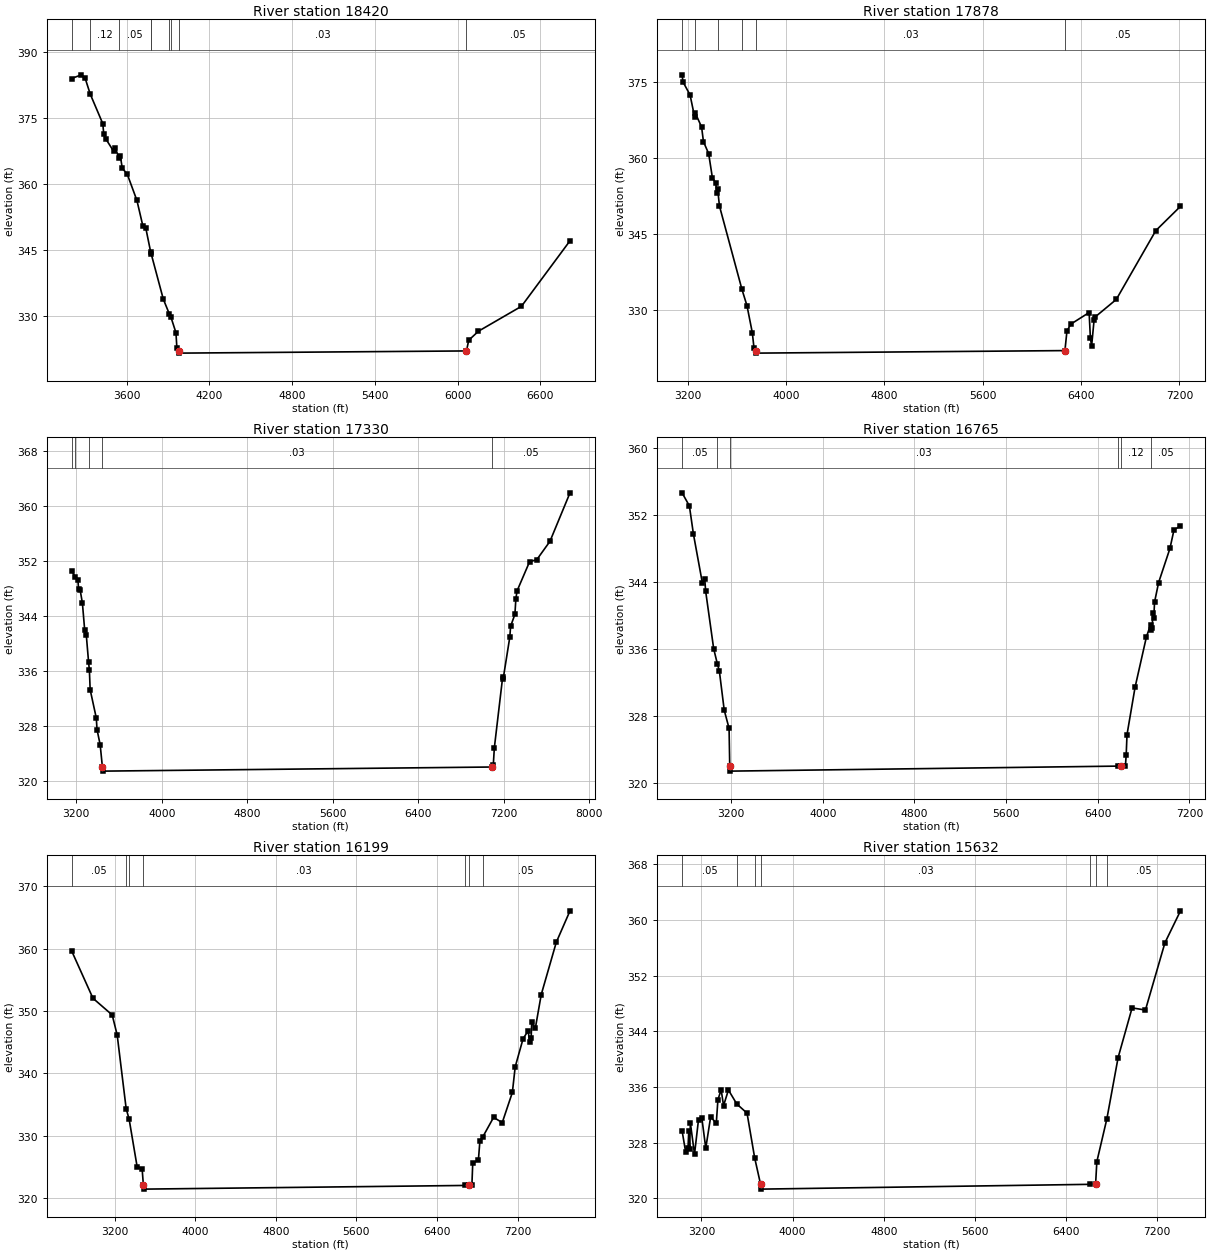
Type RM Length L Ch R = 1,18420,542,542,542
BEGIN DESCRIPTION:
Clear Creek 30.0
END DESCRIPTION:
XS GIS Cut Line= 3
      2734976.00      6777561.00      2733726.00      6778861.00
      2733526.00      6780660.96
#Sta/Elev= 30
  3201.3  384.02  3271.9  384.86  3300.2  384.03  3336.2  380.50  3427.6  373.74
  3434.8  371.31  3448.9  370.30  3505.5  367.49  3519.7  368.16  3544.7  365.82
  3554.9  366.35  3569.1  363.57  3604.3  362.30  3675.1  356.26  3717.5  350.55
  3738.9  350.05  3775.4  344.44  3777.9  344.18  3866.2  333.81  3910.7  330.38
  3921.8  329.69  3958.1  326.16  3965.0  322.65  3978.7  322.00  3981.6  321.50
  6065.0  322.00  6081.3  324.43  6151.8  326.49  6463.7  332.16  6815.8  347.08
#Mann=9,-1,0
  3201.3    0.05       0  3336.2    0.12       0  3544.7    0.05       0
  3775.4    0.12       0  3777.9    0.05       0  3910.7    0.12       0
  3921.8    0.05       0  3978.7    0.03       0  6065.0    0.05       0
Bank Sta=3978.7,6065
Exp/Cntr=0.3,0.1

Type RM Length L Ch R = 1,17878,548,548,548
BEGIN DESCRIPTION:
Clear Creek 29.0
END DESCRIPTION:
XS GIS Cut Line= 3
      2734826.01      6777610.99      2733276.00      6778611.00
      2733476.00      6780811.03
#Sta/Elev= 30
  3155.4  376.34  3163.0  374.93  3220.4  372.37  3257.5  368.02  3262.7  368.81
  3314.1  366.06  3329.3  363.17  3371.6  360.81  3401.9  356.06  3429.1  355.05
  3438.2  353.10  3444.6  353.85  3459.3  350.50  3642.1  334.08  3683.1  330.86
  3726.6  325.53  3740.5  322.47  3756.3  322.00  3759.1  321.50  6269.2  322.00
  6285.3  325.79  6315.4  327.19  6466.0  329.50  6476.1  324.56  6486.1  322.87
  6506.2  328.01  6516.2  328.65  6686.9  332.08  7008.2  345.64  7209.1  350.43
#Mann=6,-1,0
  3155.4    0.12       0  3257.5    0.05       0  3444.6    0.12       0
  3642.1    0.05       0  3756.3    0.03       0  6269.2    0.05       0
Bank Sta=3756.3,6269.2
Exp/Cntr=0.3,0.1

Type RM Length L Ch R = 1,17330,565,565,565
BEGIN DESCRIPTION:
Clear Creek 28.0
END DESCRIPTION:
XS GIS Cut Line= 4
      2734326.01      6777460.99      2732776.00      6778461.00
      2731374.29      6779862.64      2730547.05      6779996.07
#Sta/Elev= 30
  3155.4  350.61  3190.8  349.68  3214.5  349.29  3220.4  348.01  3235.6  347.79
  3256.7  345.89  3277.8  341.99  3293.0  341.24  3314.4  337.31  3322.0  336.10
  3329.3  333.27  3386.7  329.14  3393.4  327.46  3423.0  325.24  3443.8  322.00
  3446.8  321.40  7088.7  322.00  7102.1  322.26  7112.2  324.82  7190.0  335.11
  7195.0  334.88  7256.8  340.94  7264.2  342.50  7304.7  344.27  7313.5  346.52
  7324.9  347.68  7442.2  351.94  7509.0  352.22  7632.6  354.90  7820.2  361.97
#Mann=5,-1,0
  3155.4    0.12       0  3190.8    0.05       0  3314.4    0.12       0
  3443.8    0.03       0  7088.7    0.05       0
Bank Sta=3443.8,7088.7
Exp/Cntr=0.3,0.1

Type RM Length L Ch R = 1,16765,566,566,566
BEGIN DESCRIPTION:
Clear Creek 27.0
END DESCRIPTION:
XS GIS Cut Line= 3
      2733926.02      6776460.98      2732376.00      6778061.00
      2730926.00      6779611.00
#Sta/Elev= 30
  2772.3  354.63  2836.0  353.07  2871.3  349.71  2949.2  343.88  2970.3  344.36
  2977.5  342.94  3048.2  336.01  3081.0  334.16  3097.6  333.36  3140.1  328.68
  3182.5  326.50  3188.3  322.00  3191.3  321.40  6578.0  322.00  6604.4  322.00
  6641.6  322.00  6648.4  323.30  6655.7  325.76  6726.1  331.42  6825.3  337.44
  6860.9  338.85  6865.5  338.29  6875.1  338.51  6881.9  340.31  6889.2  339.66
  6896.1  341.58  6931.3  343.91  7030.4  347.99  7066.1  350.23  7122.5  350.65
#Mann=6,-1,0
  2772.3    0.05       0  3081.0    0.12       0  3188.3    0.03       0
  6578.0    0.12       0  6604.4    0.12       0  6865.5    0.05       0
Bank Sta=3188.3,6604.4
Exp/Cntr=0.3,0.1

Type RM Length L Ch R = 1,16199,567,567,567
BEGIN DESCRIPTION:
Clear Creek 26.0
END DESCRIPTION:
XS GIS Cut Line= 3
      2733526.02      6776060.98      2731976.00      6777661.00
      2730375.99      6779861.01
#Sta/Elev= 30
  2772.3  359.65  2984.4  352.03  3175.5  349.35  3224.9  346.14  3314.2  334.30
  3343.6  332.62  3423.0  324.99  3472.4  324.71  3485.2  322.00  3488.2  321.40
  6678.3  321.99  6716.9  322.00  6746.2  322.00  6754.7  325.54  6811.1  326.11
  6825.8  329.13  6852.0  329.71  6961.8  332.92  7047.6  332.07  7148.0  336.91
  7176.2  341.02  7254.7  345.55  7304.9  346.80  7319.6  344.99  7334.3  345.61
  7340.5  348.15  7376.0  347.21  7434.7  352.62  7584.3  361.02  7720.3  366.06
#Mann=7,-1,0
  2772.3    0.05       0  3314.2    0.12       0  3343.6    0.05       0
  3485.2    0.03       0  6678.3    0.12       0  6716.9    0.05       0
  6852.0    0.05       0
Bank Sta=3485.2,6716.9
Exp/Cntr=0.3,0.1

Type RM Length L Ch R = 1,15632,1077,1077,1077
BEGIN DESCRIPTION:
Clear Creek 25.0
END DESCRIPTION:
XS GIS Cut Line= 3
      2732854.93      6775756.69      2731576.00      6777261.00
      2730242.94      6779256.15
#Sta/Elev= 30
  3030.5  329.69  3061.6  326.66  3082.5  327.20  3089.1  329.63  3096.8  327.07
  3103.3  330.80  3139.6  326.32  3174.7  331.29  3203.3  331.58  3238.4  327.19
  3281.3  331.69  3330.7  330.76  3345.0  334.15  3373.5  335.58  3394.4  333.30
  3437.2  335.55  3510.4  333.54  3600.6  332.22  3667.6  325.79  3719.3  322.00
  3722.3  321.30  6613.3  321.99  6659.4  322.00  6670.3  325.24  6758.3  331.40
  6857.1  340.21  6979.7  347.35  7096.8  347.04  7268.0  356.71  7404.5  361.30
#Mann=7,-1,0
  3030.5    0.05       0  3510.4    0.12       0  3667.6    0.05       0
  3719.3    0.03       0  6613.3    0.12       0  6659.4    0.05       0
  6758.3    0.05       0
Bank Sta=3719.3,6659.4
Exp/Cntr=0.3,0.1

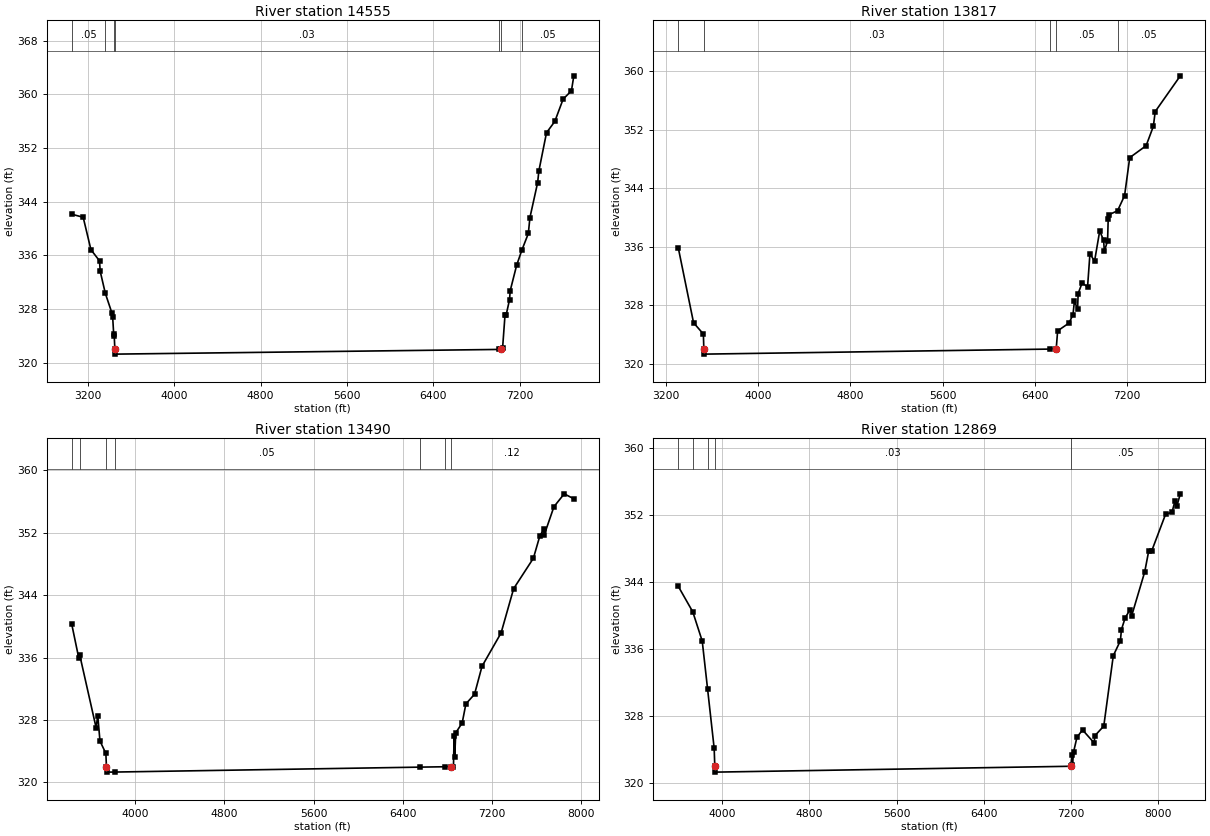
Type RM Length L Ch R = 1,14555,738,738,738
BEGIN DESCRIPTION:
Clear Creek 24.0
END DESCRIPTION:
XS GIS Cut Line= 3
      2732299.57      6774726.19      2731176.00      6776311.00
      2730133.67      6778810.05
#Sta/Elev= 30
  3050.8  342.13  3156.5  341.68  3228.3  336.85  3307.8  335.19  3314.1  333.64
  3361.6  330.35  3423.5  327.38  3429.6  326.82  3439.1  324.27  3444.4  323.95
  3449.8  322.00  3452.8  321.30  7012.0  322.00  7028.2  322.00  7041.3  322.23
  7063.5  327.09  7073.8  327.11  7105.8  329.43  7111.2  330.71  7171.3  334.53
  7218.9  336.75  7279.7  339.27  7294.2  341.62  7365.7  346.83  7377.2  348.58
  7448.0  354.27  7524.9  355.95  7601.8  359.27  7678.7  360.51  7701.2  362.74
#Mann=7,-1,0
  3050.8    0.05       0  3361.6    0.12       0  3439.1    0.05       0
  3449.8    0.03       0  7012.0    0.12       0  7028.2    0.05       0
  7218.9    0.05       0
Bank Sta=3449.8,7028.2
Exp/Cntr=0.3,0.1

Type RM Length L Ch R = 1,13817,327,327,327
BEGIN DESCRIPTION:
Clear Creek 23.0
END DESCRIPTION:
XS GIS Cut Line= 3
      2731124.02      6774244.01      2730625.86      6775861.33
      2729912.71      6778426.02
#Sta/Elev= 30
  3307.7  335.87  3440.6  325.59  3525.7  324.05  3529.7  322.00  3532.7  321.30
  6530.1  321.99  6585.6  322.00  6598.1  324.48  6697.3  325.56  6731.5  326.72
  6743.4  328.55  6770.9  327.46  6776.1  329.59  6810.4  331.04  6857.6  330.49
  6878.3  335.04  6918.2  334.01  6962.9  338.14  6997.1  336.87  7002.9  335.34
  7031.3  336.82  7036.5  339.75  7044.4  340.38  7117.6  340.91  7178.6  342.98
  7223.2  348.18  7365.4  349.81  7428.4  352.47  7444.2  354.48  7662.0  359.37
#Mann=5,-1,0
  3307.7    0.05       0  3529.7    0.03       0  6530.1    0.12       0
  6585.6    0.05       0  7117.6    0.05       0
Bank Sta=3529.7,6585.6
Exp/Cntr=0.3,0.1

Type RM Length L Ch R = 1,13490,621,621,621
BEGIN DESCRIPTION:
Clear Creek 22.0
END DESCRIPTION:
XS GIS Cut Line= 4
      2730737.57      6774245.72      2730331.18      6775760.56
      2729658.38      6778071.30      2729602.23      6778595.51
#Sta/Elev= 30
  3431.6  340.25  3494.8  335.90  3503.1  336.31  3649.6  327.02  3664.8  328.54
  3684.4  325.29  3737.3  323.70  3742.5  322.00  3745.5  321.30  3819.0  321.31
  6550.5  321.94  6778.1  321.99  6828.6  322.00  6854.4  322.00  6860.2  325.90
  6865.4  323.27  6875.2  326.35  6932.4  327.60  6965.9  330.05  7043.3  331.29
  7110.3  334.87  7281.4  339.15  7394.0  344.83  7571.1  348.73  7627.7  351.53
  7663.3  352.47  7668.3  351.72  7755.5  355.34  7847.7  356.99  7933.9  356.35
#Mann=7,-1,0
  3431.6    0.05       0  3503.1    0.12       0  3742.5    0.05       0
  3819.0    0.05       0  6550.5   0.075       0  6778.1    0.05       0
  6828.6    0.12       0
Bank Sta=3742.5,6828.6
Exp/Cntr=0.3,0.1

Type RM Length L Ch R = 1,12869,600,600,600
BEGIN DESCRIPTION:
Clear Creek 21.0
END DESCRIPTION:
XS GIS Cut Line= 4
      2730207.18      6774390.96      2729726.00      6775711.00
      2729150.20      6778019.99      2729545.54      6778746.25
#Sta/Elev= 30
  3595.0  343.50  3728.7  340.44  3815.3  336.96  3864.2  331.27  3925.0  324.15
  3930.8  322.00  3933.8  321.30  7200.5  322.00  7210.9  323.30  7216.0  322.16
  7226.2  323.70  7257.3  325.47  7308.6  326.34  7415.0  324.79  7422.0  325.65
  7503.6  326.80  7591.0  335.21  7656.6  337.01  7665.5  338.31  7700.2  339.73
  7745.2  340.71  7760.1  339.99  7879.8  345.22  7916.0  347.69  7945.3  347.77
  8070.6  352.08  8130.5  352.35  8158.0  353.70  8174.2  353.05  8206.6  354.54
#Mann=5,-1,0
  3595.0    0.05       0  3728.7    0.12       0  3864.2    0.05       0
  3930.8    0.03       0  7200.5    0.05       0
Bank Sta=3930.8,7200.5
Exp/Cntr=0.3,0.1