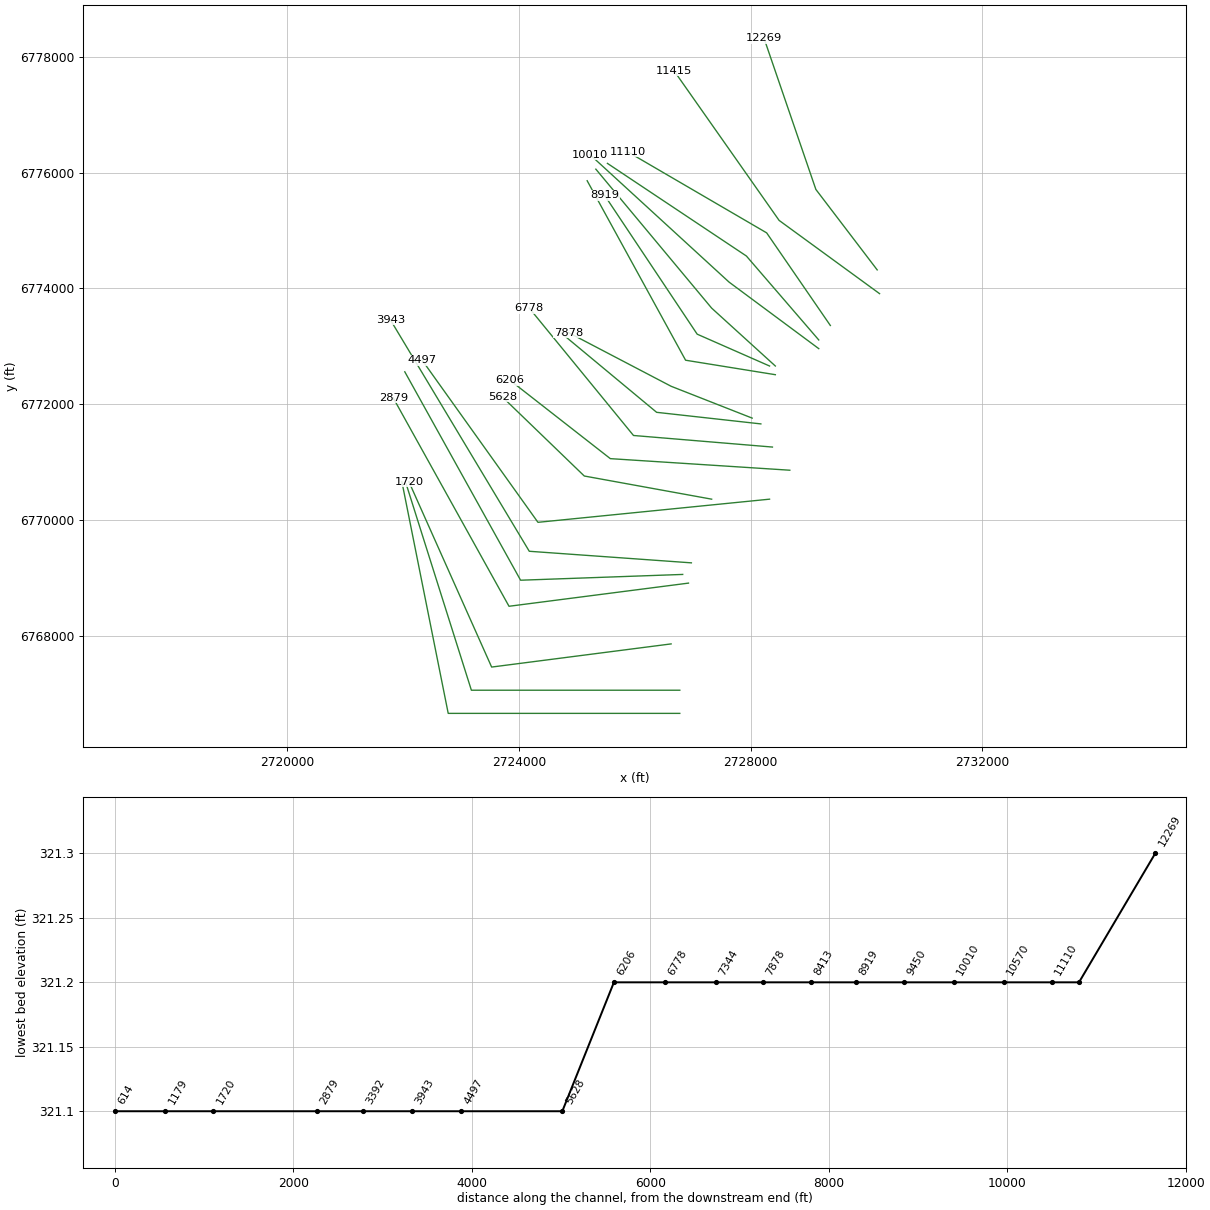
HEC-RAS study Clear Creek.prj: Clear Creek Base Level Engineering

--- Clear Creek.g01 (geometry) --- (continued)

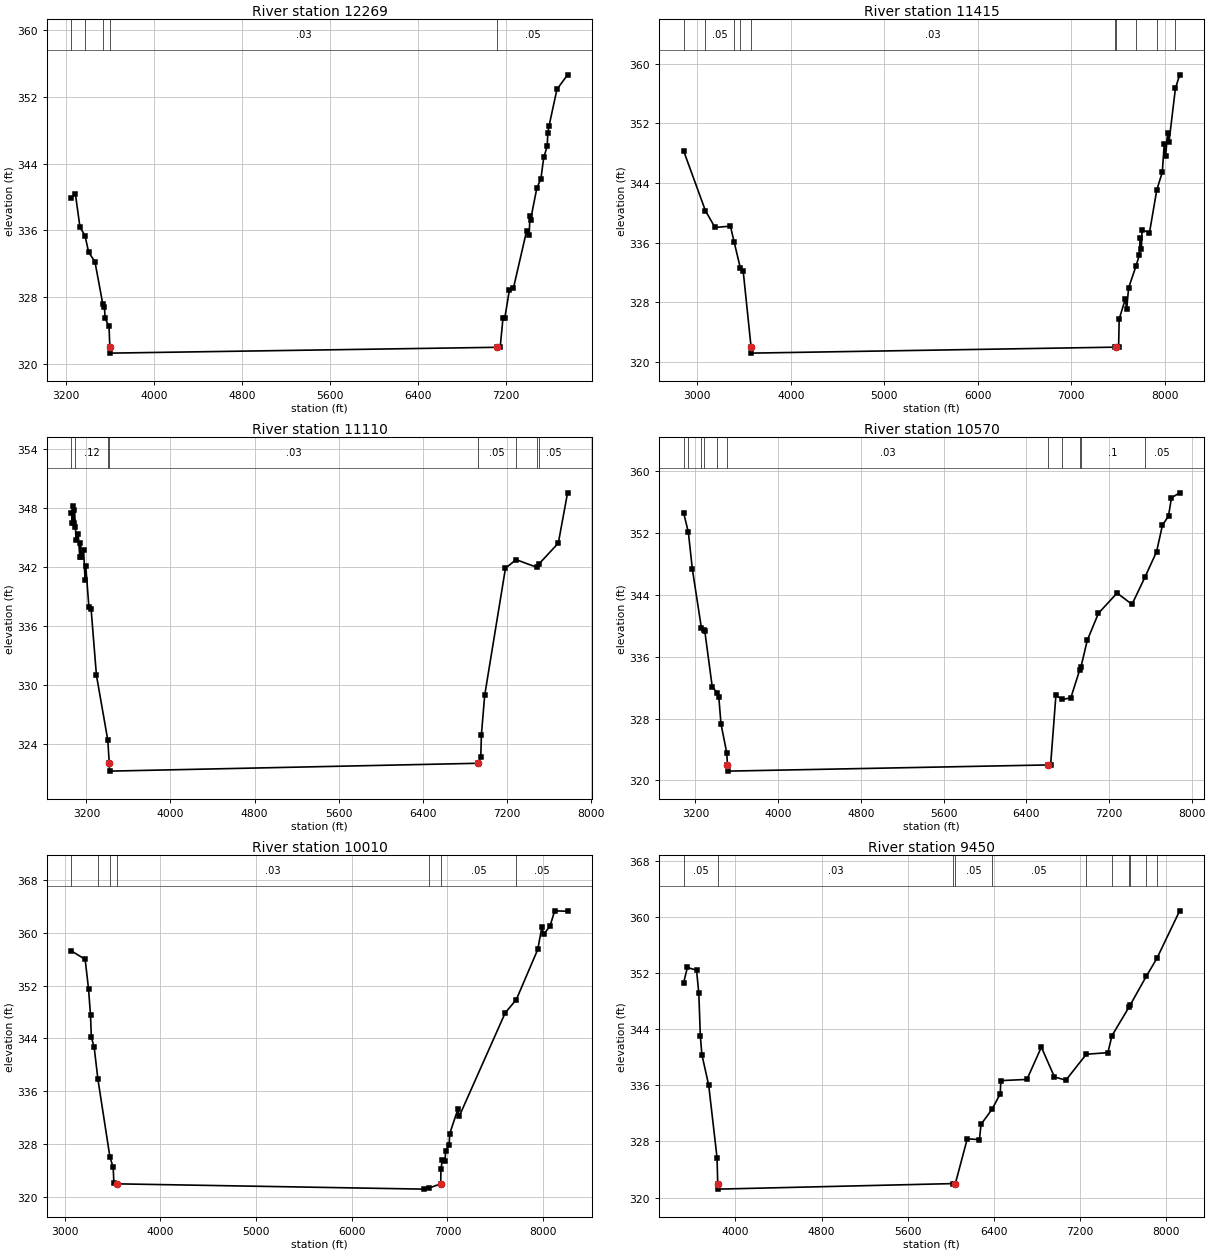
Type RM Length L Ch R = 1,12269,854,854,854
BEGIN DESCRIPTION:
Clear Creek 20.0
END DESCRIPTION:
XS GIS Cut Line= 3
      2730185.23      6774321.24      2729126.00      6775711.00
      2728230.99      6778320.90
#Sta/Elev= 30
  3252.5  339.93  3288.1  340.38  3329.7  336.39  3375.4  335.38  3408.7  333.38
  3465.9  332.25  3536.1  327.24  3552.1  326.77  3558.3  325.45  3593.7  324.52
  3601.0  322.00  3604.0  321.30  7122.2  322.00  7146.8  322.00  7172.8  325.54
  7188.2  325.46  7230.1  328.82  7266.6  329.05  7386.4  335.91  7410.2  335.51
  7417.7  337.74  7423.0  337.28  7480.2  341.10  7516.8  342.19  7542.8  344.77
  7574.0  346.08  7579.4  347.70  7590.0  348.48  7662.6  352.91  7759.0  354.65
#Mann=5,-1,0
  3252.5    0.05       0  3375.4    0.12       0  3536.1    0.05       0
  3601.0    0.03       0  7122.2    0.05       0
Bank Sta=3601,7122.2
Exp/Cntr=0.3,0.1

Type RM Length L Ch R = 1,11415,305,305,305
BEGIN DESCRIPTION:
Clear Creek 19.0
END DESCRIPTION:
XS GIS Cut Line= 3
      2730226.03      6773910.98      2728491.16      6775176.16
      2726676.01      6777760.99
#Sta/Elev= 30
  2852.8  348.32  3086.3  340.29  3188.5  338.04  3353.8  338.22  3394.1  336.06
  3460.8  332.55  3489.8  332.25  3574.7  322.00  3577.7  321.20  7462.8  322.00
  7481.3  322.00  7505.4  322.00  7511.5  325.77  7576.8  328.43  7591.6  327.12
  7612.6  329.96  7690.2  332.82  7728.5  334.41  7734.6  336.61  7749.4  335.11
  7755.5  337.71  7835.6  337.36  7913.9  343.08  7972.5  345.45  7993.4  349.20
  8008.2  347.58  8029.1  350.73  8043.9  349.45  8112.9  356.68  8158.5  358.50
#Mann=10,-1,0
  2852.8    0.12       0  3086.3    0.05       0  3394.1    0.12       0
  3460.8    0.05       0  3574.7    0.03       0  7462.8    0.12       0
  7481.3    0.05       0  7690.2    0.05       0  7913.9    0.12       0
  8112.9    0.05       0
Bank Sta=3574.7,7481.3
Exp/Cntr=0.3,0.1

Type RM Length L Ch R = 1,11110,540,540,540
BEGIN DESCRIPTION:
Clear Creek 18.0
END DESCRIPTION:
XS GIS Cut Line= 3
      2729376.03      6773360.96      2728276.00      6774961.00
      2725875.98      6776361.01
#Sta/Elev= 30
  3058.3  347.53  3065.8  346.47  3071.9  348.19  3080.7  346.49  3086.8  347.86
  3096.1  346.07  3101.6  344.74  3122.6  345.35  3137.5  342.98  3143.6  344.46
  3152.4  343.06  3173.4  343.72  3188.2  340.66  3194.3  342.11  3224.1  337.94
  3245.1  337.71  3295.8  330.98  3404.2  324.34  3417.7  322.00  3420.7  321.20
  6925.3  322.00  6952.8  322.63  6958.6  324.91  6990.0  328.93  7187.6  341.88
  7288.8  342.76  7490.3  341.96  7508.4  342.34  7690.4  344.44  7778.5  349.57
#Mann=8,-1,0
  3058.3    0.05       0  3096.1    0.12       0  3404.2    0.05       0
  3417.7    0.03       0  6925.3    0.05       0  7288.8     0.1       0
  7490.3    0.12       0  7508.4    0.05       0
Bank Sta=3417.7,6925.3
Exp/Cntr=0.3,0.1

Type RM Length L Ch R = 1,10570,560,560,560
BEGIN DESCRIPTION:
Clear Creek 17.0
END DESCRIPTION:
XS GIS Cut Line= 3
      2729175.98      6773111.02      2727926.00      6774561.00
      2725526.03      6776160.98
#Sta/Elev= 30
  3085.6  354.59  3131.6  352.08  3170.6  347.28  3258.3  339.66  3278.7  339.48
  3291.3  339.25  3362.6  332.10  3411.8  331.30  3426.2  330.83  3447.1  327.32
  3504.1  323.49  3509.5  322.00  3512.5  321.20  6607.9  322.00  6636.0  322.00
  6687.1  331.00  6747.4  330.46  6831.3  330.66  6918.6  334.33  6928.5  334.60
  6990.6  338.10  7098.7  341.60  7279.0  344.21  7423.2  342.75  7548.1  346.25
  7660.6  349.54  7717.7  352.98  7776.3  354.16  7804.8  356.52  7884.4  357.16
#Mann=11,-1,0
  3085.6    0.05       0  3131.6    0.12       0  3258.3    0.05       0
  3278.7    0.12       0  3411.8    0.05       0  3509.5    0.03       0
  6607.9    0.05       0  6747.4     0.1       0  6918.6    0.05       0
  6928.5     0.1       0  7548.1    0.05       0
Bank Sta=3509.5,6607.9
Exp/Cntr=0.3,0.1

Type RM Length L Ch R = 1,10010,560,560,560
BEGIN DESCRIPTION:
Clear Creek 16.0
END DESCRIPTION:
XS GIS Cut Line= 3
      2729175.98      6772961.02      2727626.00      6774111.00
      2725225.97      6776311.02
#Sta/Elev= 30
  3070.0  357.23  3212.9  355.97  3248.4  351.51  3269.2  347.48  3277.6  344.16
  3306.6  342.76  3346.3  337.83  3471.8  326.07  3505.8  324.50  3513.4  322.16
  3545.9  322.00  6750.1  321.20  6804.9  321.35  6929.6  322.00  6932.2  324.24
  6946.4  325.59  6974.7  325.43  6981.5  327.00  7017.3  327.87  7024.1  329.59
  7109.2  333.29  7123.3  332.22  7604.6  347.89  7719.8  349.87  7944.1  357.46
  7986.6  360.79  8008.2  359.80  8071.7  360.97  8121.0  363.31  8255.8  363.24
#Mann=7,-1,0
  3070.0    0.05       0  3346.3    0.12       0  3471.8    0.05       0
  3545.9    0.03       0  6804.9     0.1       0  6929.6    0.05       0
  7719.8    0.05       0
Bank Sta=3545.9,6929.6
Exp/Cntr=0.3,0.1

Type RM Length L Ch R = 1,9450,531,531,531
BEGIN DESCRIPTION:
Clear Creek 15.0
END DESCRIPTION:
XS GIS Cut Line= 3
      2728425.98      6772661.02      2727326.00      6773661.00
      2725325.99      6776061.02
#Sta/Elev= 30
  3518.1  350.62  3553.5  352.82  3638.7  352.43  3659.6  349.13  3673.8  343.08
  3688.0  340.39  3751.5  336.03  3829.2  325.65  3835.4  322.00  3838.4  321.20
  6023.1  321.99  6044.0  322.00  6154.7  328.38  6268.0  328.26  6282.3  330.44
  6385.5  332.60  6460.6  334.79  6467.1  336.68  6709.3  336.85  6843.3  341.46
  6964.4  337.21  7071.1  336.74  7261.2  340.44  7461.7  340.67  7499.4  343.09
  7658.5  347.18  7667.1  347.41  7817.7  351.54  7917.1  354.12  8128.8  360.90
#Mann=11,-1,0
  3518.1    0.05       0  3835.4    0.03       0  6023.1    0.12       0
  6044.0    0.05       0  6385.5    0.05       0  7261.2     0.1       0
  7499.4    0.05       0  7658.5    0.12       0  7667.1    0.05       0
  7817.7    0.12       0  7917.1    0.05       0
Bank Sta=3835.4,6044
Exp/Cntr=0.3,0.1

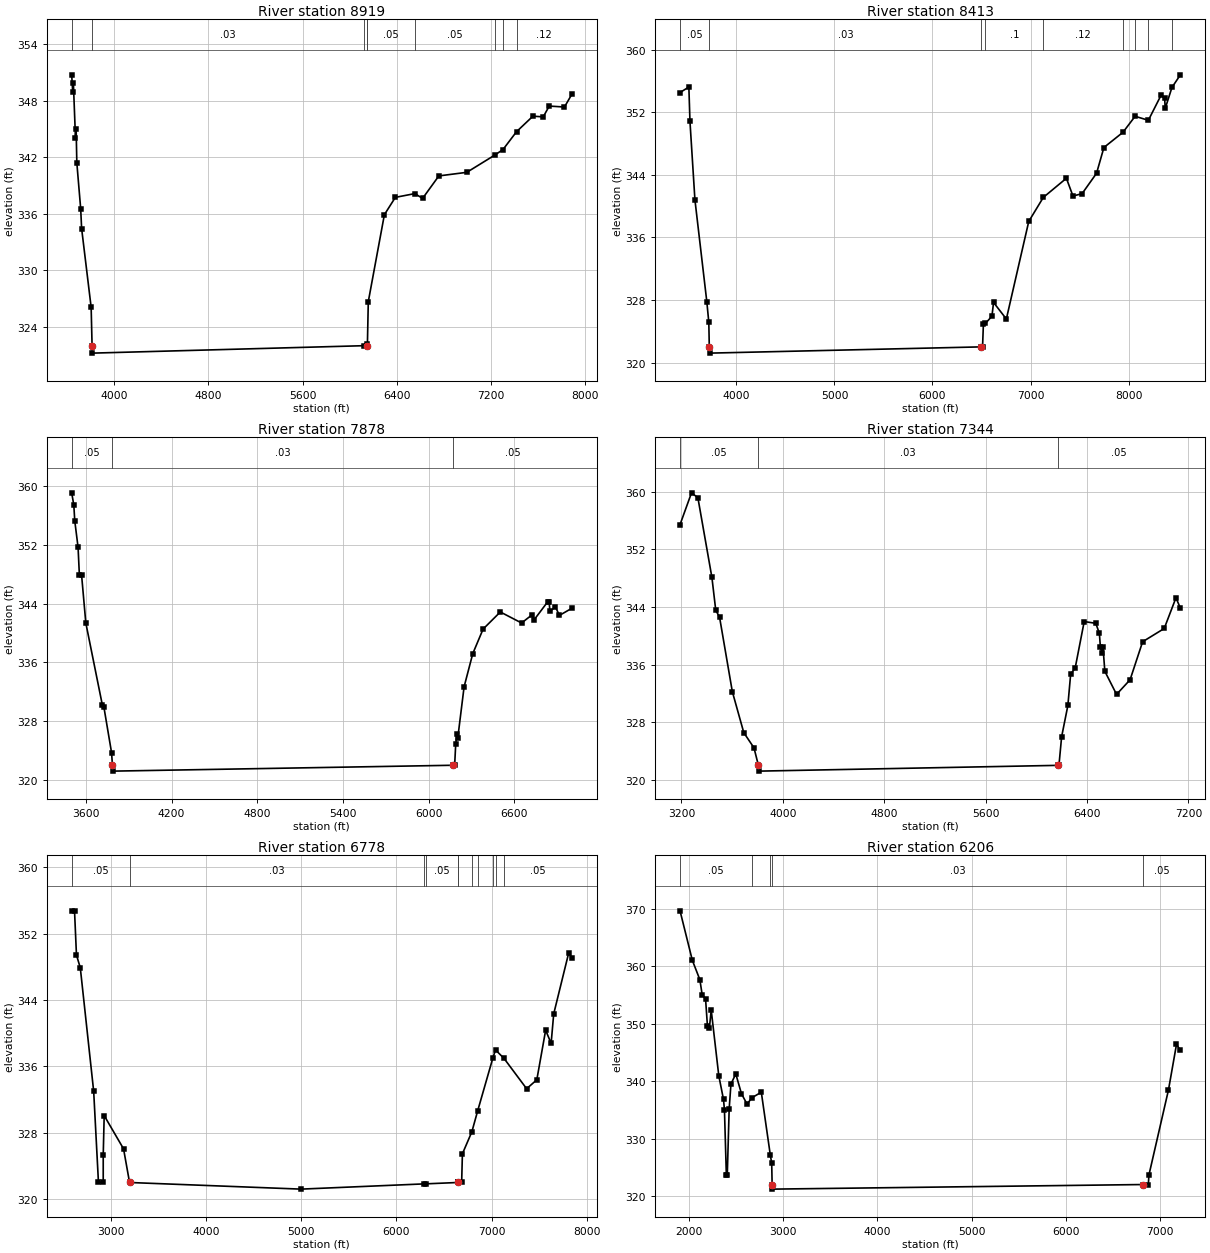
Type RM Length L Ch R = 1,8919,506,506,506
BEGIN DESCRIPTION:
Clear Creek 14.0
END DESCRIPTION:
XS GIS Cut Line= 3
      2728325.96      6772661.02      2727076.00      6773211.00
      2725475.97      6775611.04
#Sta/Elev= 30
  3638.9  350.77  3647.8  348.94  3653.3  349.89  3671.1  344.08  3676.6  345.06
  3682.6  341.42  3715.3  336.55  3723.3  334.44  3804.2  326.07  3812.1  322.00
  3815.1  321.20  6122.4  321.99  6143.6  322.00  6148.7  322.00  6150.8  322.14
  6158.3  326.67  6295.0  335.91  6388.1  337.75  6553.7  338.15  6619.5  337.64
  6757.7  340.03  6995.1  340.41  7232.5  342.24  7302.4  342.83  7417.6  344.73
  7556.9  346.38  7644.1  346.30  7695.2  347.45  7824.4  347.35  7889.0  348.74
#Mann=9,-1,0
  3638.9    0.05       0  3812.1    0.03       0  6122.4    0.12       0
  6143.6     0.1       0  6148.7    0.05       0  6553.7    0.05       0
  7232.5    0.12       0  7302.4    0.05       0  7417.6    0.12       0
Bank Sta=3812.1,6148.7
Exp/Cntr=0.3,0.1

Type RM Length L Ch R = 1,8413,535,535,535
BEGIN DESCRIPTION:
Clear Creek 13.0
END DESCRIPTION:
XS GIS Cut Line= 3
      2728425.99      6772511.00      2726876.00      6772761.00
      2725175.98      6775861.04
#Sta/Elev= 30
  3423.9  354.51  3514.0  355.21  3525.2  350.82  3575.8  340.80  3697.4  327.75
  3717.6  325.12  3722.4  322.00  3725.4  321.20  6499.9  322.00  6510.8  322.00
  6519.5  324.95  6539.1  324.99  6606.7  325.92  6622.8  327.68  6753.6  325.56
  6982.1  338.03  7130.5  341.10  7366.2  343.55  7433.2  341.28  7526.2  341.58
  7674.1  344.19  7748.9  347.48  7943.9  349.43  8067.3  351.47  8202.6  350.96
  8330.9  354.13  8368.8  353.79  8374.5  352.47  8443.3  355.16  8529.5  356.77
#Mann=9,-1,0
  3423.9    0.05       0  3722.4    0.03       0  6499.9    0.05       0
  6539.1     0.1       0  7130.5    0.12       0  7943.9    0.05       0
  8067.3    0.12       0  8202.6    0.05       0  8443.3    0.12       0
Bank Sta=3722.4,6499.9
Exp/Cntr=0.3,0.1

Type RM Length L Ch R = 1,7878,534,534,534
BEGIN DESCRIPTION:
Clear Creek 12.0
END DESCRIPTION:
XS GIS Cut Line= 3
      2728026.05      6771760.98      2726626.00      6772311.00
      2724854.09      6773237.88
#Sta/Elev= 30
  3500.3  359.11  3515.2  357.45  3521.8  355.30  3545.0  351.69  3554.1  347.93
  3569.5  347.94  3599.2  341.39  3715.2  330.19  3726.0  329.91  3779.7  323.70
  3785.7  322.00  3788.7  321.20  6173.9  322.00  6182.1  322.00  6189.5  324.88
  6198.5  326.23  6204.2  325.76  6248.3  332.69  6308.9  337.20  6381.3  340.55
  6501.9  342.88  6650.8  341.38  6722.6  342.47  6739.0  341.82  6833.0  344.25
  6843.8  344.18  6849.4  342.97  6887.9  343.58  6915.6  342.41  7004.2  343.40
#Mann=3,-1,0
  3500.3    0.05       0  3785.7    0.03       0  6173.9    0.05       0
Bank Sta=3785.7,6173.9
Exp/Cntr=0.3,0.1

Type RM Length L Ch R = 1,7344,566,566,566
BEGIN DESCRIPTION:
Clear Creek 11.0
END DESCRIPTION:
XS GIS Cut Line= 3
      2728176.04      6771661.00      2726376.00      6771861.00
      2724732.11      6773226.87
#Sta/Elev= 30
  3188.9  355.42  3279.5  359.83  3329.8  359.15  3440.5  348.08  3470.7  343.54
  3500.9  342.56  3601.5  332.24  3692.0  326.54  3772.5  324.43  3807.3  322.00
  3810.3  321.20  6168.0  322.00  6179.0  322.00  6199.9  325.95  6249.3  330.31
  6271.5  334.69  6306.6  335.48  6378.2  341.96  6469.4  341.72  6498.0  340.33
  6505.9  338.42  6520.2  337.54  6526.7  338.38  6541.0  335.06  6633.5  331.85
  6740.2  333.88  6839.2  339.16  7009.7  341.00  7102.2  345.26  7137.3  343.82
#Mann=3,-1,0
  3188.9    0.05       0  3807.3    0.03       0  6168.0    0.05       0
Bank Sta=3807.3,6168
Exp/Cntr=0.3,0.1

Type RM Length L Ch R = 1,6778,572,572,572
BEGIN DESCRIPTION:
Clear Creek 10.0
END DESCRIPTION:
XS GIS Cut Line= 3
      2728375.97      6771261.00      2725976.00      6771461.00
      2724176.01      6773660.98
#Sta/Elev= 30
  2591.7  354.77  2621.8  354.69  2641.8  349.44  2682.0  347.90  2822.5  333.00
  2872.6  322.02  2922.7  322.00  2922.8  325.35  2932.8  330.07  3136.0  326.06
  3199.1  322.00  4998.0  321.20  6285.3  321.83  6314.9  321.84  6643.1  322.00
  6645.2  322.00  6684.0  322.00  6691.9  325.46  6791.2  328.12  6851.8  330.63
  7012.8  337.07  7039.4  337.99  7128.6  336.97  7365.9  333.31  7472.8  334.39
  7565.4  340.37  7622.9  338.78  7650.1  342.34  7806.6  349.66  7842.5  349.12
#Mann=11,-1,0
  2591.7    0.05       0  3199.1    0.03       0  6285.3    0.12       0
  6314.9    0.05       0  6643.1    0.05       0  6645.2    0.12       0
  6791.2    0.05       0  6851.8    0.12       0  7012.8    0.05       0
  7039.4    0.12       0  7128.6    0.05       0
Bank Sta=3199.1,6643.1
Exp/Cntr=0.3,0.1

Type RM Length L Ch R = 1,6206,578,578,578
BEGIN DESCRIPTION:
Clear Creek 9.0
END DESCRIPTION:
XS GIS Cut Line= 3
      2728676.02      6770861.00      2725576.00      6771061.00
      2723842.75      6772415.01
#Sta/Elev= 30
  1909.0  369.66  2039.3  361.05  2119.5  357.66  2143.3  355.09  2179.6  354.34
  2199.6  349.62  2219.7  349.18  2239.7  352.37  2319.9  340.95  2370.0  336.81
  2380.0  334.99  2400.0  323.74  2410.1  323.74  2430.1  335.17  2448.9  339.49
  2500.2  341.27  2560.4  337.81  2620.5  335.98  2668.2  337.08  2770.8  338.08
  2866.9  327.07  2881.0  325.76  2885.6  322.00  2888.6  321.20  6818.6  322.00
  6874.9  322.00  6881.3  323.67  7088.4  338.47  7173.4  346.39  7214.9  345.37
#Mann=5,-1,0
  1909.0    0.05       0  2668.2    0.12       0  2866.9    0.05       0
  2885.6    0.03       0  6818.6    0.05       0
Bank Sta=2885.6,6818.6
Exp/Cntr=0.3,0.1

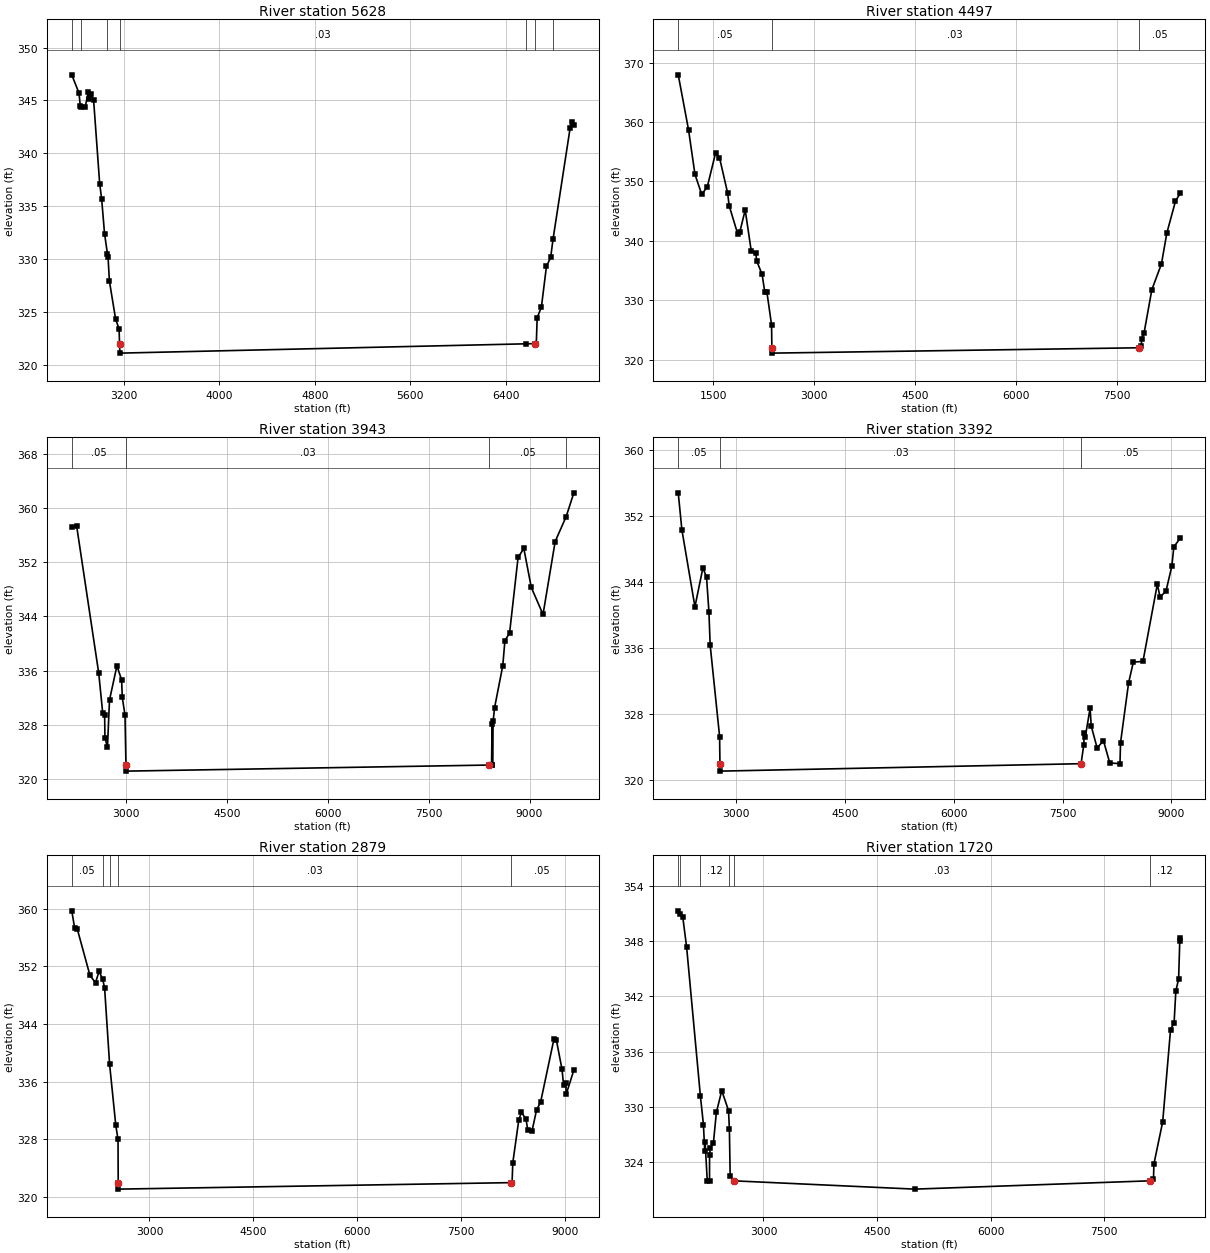
Type RM Length L Ch R = 1,5628,1131,1131,1131
BEGIN DESCRIPTION:
Clear Creek 8.0
END DESCRIPTION:
XS GIS Cut Line= 3
      2727326.03      6770361.00      2725126.00      6770761.00
      2723709.30      6772128.75
#Sta/Elev= 30
  2763.9  347.42  2824.9  345.68  2835.1  344.46  2844.1  344.40  2875.7  344.34
  2902.4  345.80  2907.5  345.18  2926.5  345.57  2946.9  345.02  2997.7  337.12
  3014.2  335.68  3038.4  332.40  3062.4  330.52  3067.6  330.22  3079.0  327.92
  3131.1  324.32  3160.3  323.38  3163.9  322.00  3166.9  321.10  6564.7  321.98
  6640.7  322.00  6654.8  322.00  6662.0  324.46  6697.2  325.44  6739.7  329.30
  6775.2  330.16  6794.5  331.85  6937.7  342.37  6951.9  343.00  6969.2  342.68
#Mann=7,-1,0
  2763.9    0.05       0  2844.1    0.12       0  3062.4    0.05       0
  3163.9    0.03       0  6564.7   0.075       0  6640.7    0.05       0
  6794.5    0.05       0
Bank Sta=3163.9,6640.7
Exp/Cntr=0.3,0.1

Type RM Length L Ch R = 1,4497,554,554,554
BEGIN DESCRIPTION:
Clear Creek 7.0
END DESCRIPTION:
XS GIS Cut Line= 3
      2728326.05      6770361.00      2724326.00      6769961.00
      2722326.02      6772760.98
#Sta/Elev= 30
   980.0  367.95  1133.3  358.68  1228.8  351.18  1329.3  347.82  1412.2  349.12
  1535.3  354.81  1593.1  354.02  1713.7  348.07  1736.3  345.94  1864.4  341.14
  1894.6  341.47  1975.0  345.21  2065.4  338.26  2133.3  337.88  2145.8  336.62
  2226.2  334.36  2266.4  331.35  2296.6  331.46  2366.9  325.84  2371.5  322.00
  2374.5  321.10  7819.9  322.00  7860.9  322.29  7867.0  323.53  7902.7  324.54
  8018.2  331.79  8160.7  336.13  8240.6  341.31  8368.4  346.66  8440.9  348.04
#Mann=3,-1,0
   980.0    0.05       0  2371.5    0.03       0  7819.9    0.05       0
Bank Sta=2371.5,7819.9
Exp/Cntr=0.3,0.1

Type RM Length L Ch R = 1,3943,551,551,551
BEGIN DESCRIPTION:
Clear Creek 6.0
END DESCRIPTION:
XS GIS Cut Line= 3
      2726976.04      6769261.00      2724176.00      6769461.00
      2721776.02      6773460.97
#Sta/Elev= 30
  2187.5  357.24  2260.2  357.39  2588.6  335.62  2648.7  329.65  2676.3  329.46
  2681.3  326.05  2718.9  324.63  2749.0  331.63  2859.3  336.69  2929.4  334.60
  2939.5  332.01  2979.6  329.39  2994.1  322.00  2997.1  321.10  8394.4  322.00
  8434.9  322.00  8442.7  328.13  8448.5  322.00  8458.3  328.49  8479.6  330.49
  8602.1  336.74  8633.2  340.41  8703.2  341.57  8829.5  352.74  8915.0  354.07
  9025.8  348.31  9200.7  344.30  9381.5  355.10  9545.4  358.80  9659.4  362.31
#Mann=4,-1,0
  2187.5    0.05       0  2994.1    0.03       0  8394.4    0.05       0
  9545.4     0.1       0
Bank Sta=2994.1,8394.4
Exp/Cntr=0.3,0.1

Type RM Length L Ch R = 1,3392,513,513,513
BEGIN DESCRIPTION:
Clear Creek 5.0
END DESCRIPTION:
XS GIS Cut Line= 3
      2726825.95      6769061.00      2724026.00      6768961.00
      2722026.00      6772561.01
#Sta/Elev= 30
  2203.0  354.79  2253.0  350.33  2433.1  341.00  2543.2  345.71  2593.2  344.57
  2625.7  340.41  2643.2  336.35  2773.3  325.28  2777.8  322.00  2780.8  321.10
  7755.1  322.00  7792.6  324.29  7798.3  325.67  7814.3  325.29  7879.5  328.71
  7895.5  326.55  7976.7  323.90  8063.7  324.79  8150.6  322.09  8291.3  322.00
  8299.3  324.56  8410.3  331.79  8475.5  334.30  8608.2  334.38  8806.1  343.72
  8843.9  342.19  8925.1  342.87  9006.3  345.93  9033.8  348.25  9123.0  349.31
#Mann=3,-1,0
  2203.0    0.05       0  2777.8    0.03       0  7755.1    0.05       0
Bank Sta=2777.8,7755.1
Exp/Cntr=0.3,0.1

Type RM Length L Ch R = 1,2879,1159,1159,1159
BEGIN DESCRIPTION:
Clear Creek 4.0
END DESCRIPTION:
XS GIS Cut Line= 3
      2726925.97      6768911.00      2723826.00      6768511.00
      2721826.01      6772110.98
#Sta/Elev= 30
  1879.3  359.68  1921.5  357.24  1959.9  357.12  2141.4  350.74  2222.1  349.70
  2272.5  351.29  2325.9  350.19  2353.2  348.97  2425.3  338.39  2514.5  329.94
  2546.6  327.98  2549.4  322.00  2552.4  321.10  8211.0  322.00  8232.1  322.00
  8242.4  324.76  8329.3  330.72  8367.1  331.74  8432.3  330.83  8459.7  329.24
  8519.2  329.15  8585.6  332.08  8643.9  333.18  8837.2  341.95  8871.6  341.74
  8952.8  337.69  8974.5  335.55  9006.5  335.79  9012.3  334.24  9123.2  337.60
#Mann=5,-1,0
  1879.3    0.05       0  2325.9    0.12       0  2425.3    0.05       0
  2549.4    0.03       0  8211.0    0.05       0
Bank Sta=2549.4,8211
Exp/Cntr=0.3,0.1

Type RM Length L Ch R = 1,1720,541,541,541
BEGIN DESCRIPTION:
Clear Creek 3.0
END DESCRIPTION:
XS GIS Cut Line= 3
      2726626.04      6767861.01      2723526.00      6767461.00
      2722097.53      6770661.33
#Sta/Elev= 30
  1874.3  351.28  1894.7  350.93  1934.8  350.57  1985.3  347.32  2167.4  331.16
  2207.1  328.10  2224.1  325.23  2229.1  326.22  2257.5  322.00  2287.6  322.03
  2287.7  324.77  2297.8  325.58  2338.2  326.06  2377.9  329.42  2449.1  331.78
  2538.5  329.62  2549.9  327.58  2560.0  322.55  2607.4  322.00  4998.0  321.10
  8100.1  322.00  8150.6  322.17  8156.0  323.83  8272.1  328.40  8376.0  338.41
  8422.4  339.11  8445.6  342.58  8482.4  343.90  8497.5  348.00  8504.7  348.31
#Mann=6,-1,0
  1874.3    0.05       0  1894.7     0.1       0  2167.4    0.12       0
  2538.5    0.05       0  2607.4    0.03       0  8100.1    0.12       0
Bank Sta=2607.4,8100.1
Exp/Cntr=0.3,0.1

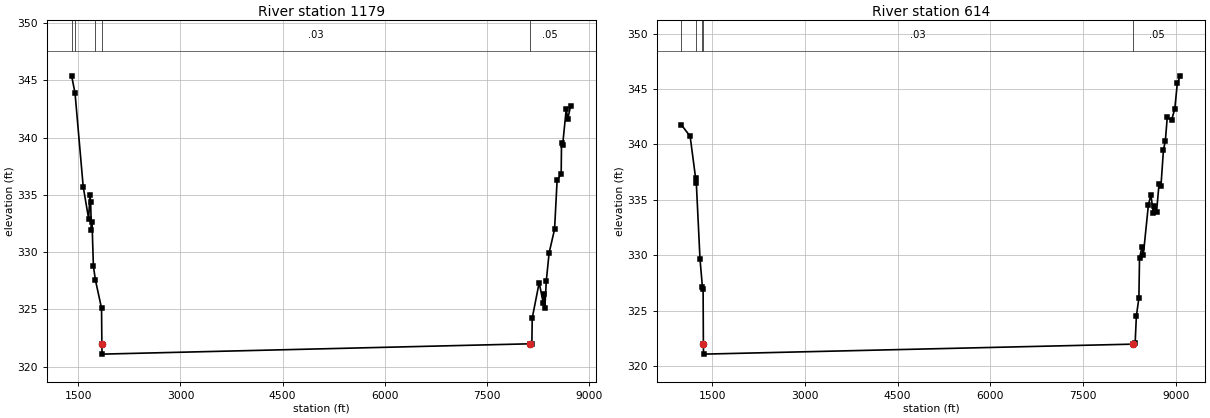
Type RM Length L Ch R = 1,1179,565,565,565
BEGIN DESCRIPTION:
Clear Creek 2.0
END DESCRIPTION:
XS GIS Cut Line= 3
      2726776.03      6767061.00      2723176.00      6767061.00
      2722050.40      6770622.01
#Sta/Elev= 30
  1400.0  345.39  1450.2  343.88  1570.0  335.73  1650.0  332.92  1670.0  334.99
  1680.0  334.39  1690.0  331.96  1700.0  332.62  1720.0  328.79  1749.1  327.59
  1840.0  325.10  1844.5  322.00  1847.5  321.10  8130.7  322.00  8165.4  322.00
  8170.6  324.24  8272.8  327.34  8332.2  325.58  8345.6  326.38  8356.1  325.12
  8377.1  327.48  8419.0  329.94  8499.1  332.00  8536.6  336.30  8596.0  336.81
  8601.3  339.56  8618.3  339.39  8671.2  342.52  8691.7  341.60  8734.7  342.75
#Mann=5,-1,0
  1400.0    0.05       0  1450.2    0.12       0  1749.1    0.05       0
  1844.5    0.03       0  8130.7    0.05       0
Bank Sta=1844.5,8130.7
Exp/Cntr=0.3,0.1

Type RM Length L Ch R = 1,614,0,0,0
BEGIN DESCRIPTION:
Clear Creek 1.0
END DESCRIPTION:
XS GIS Cut Line= 3
      2726776.00      6766661.00      2722776.00      6766661.00
      2721976.00      6770660.99
#Sta/Elev= 30
  1000.0  341.76  1140.0  340.74  1229.2  336.95  1240.0  336.56  1300.0  329.66
  1339.6  327.12  1350.0  326.98  1354.5  322.00  1357.5  321.10  8310.2  322.00
  8345.0  322.06  8365.4  324.54  8406.1  326.16  8416.3  329.76  8457.1  330.79
  8477.5  330.03  8559.1  334.51  8599.9  335.47  8640.7  333.81  8650.9  334.48
  8691.7  333.91  8732.5  336.45  8763.1  336.24  8803.9  339.53  8834.5  340.33
  8865.1  342.44  8936.4  342.22  8987.4  343.22  9028.2  345.53  9079.2  346.19
#Mann=5,-1,0
  1000.0    0.05       0  1229.2    0.12       0  1339.6    0.05       0
  1354.5    0.03       0  8310.2    0.05       0
Bank Sta=1354.5,8310.2
Exp/Cntr=0.3,0.1

Chan Stop Cuts=-1