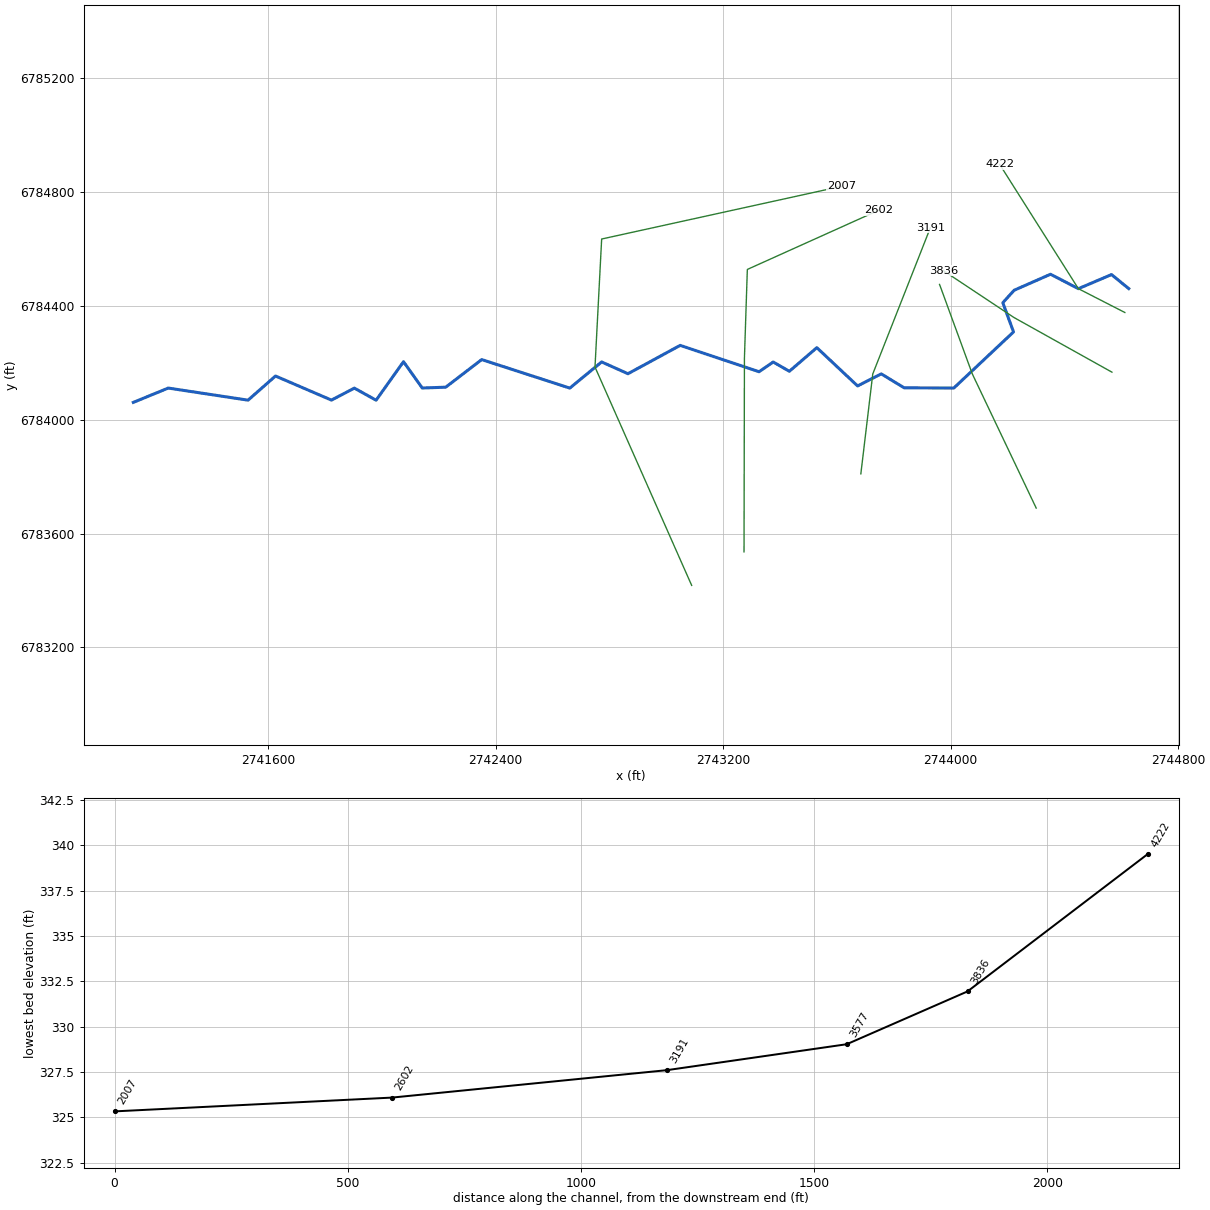
--- Clear Creek T 1.prj (project) ---

Proj Title=Clear Creek T 1 Base Level Engineering
Current Plan=p01
Default Exp/Contr=0.3,0.1
English Units
Geom File=g01
Flow File=f01
Plan File=p01
BEGIN DESCRIPTION:
Clear Creek T 1
END DESCRIPTION:

--- Clear Creek T 1.p01 (plan) ---

Plan Title=Multiple Run
Short Identifier=Multiple
Geom File=g01
Flow File=f01
Subcritical Flow
K Sum by GR= 0
Std Step Tol= 0.01
Critical Tol= 0.01
Num of Std Step Trials= 20
Max Error Tol= 0.3
Flow Tol Ratio= 0.001
Split Flow NTrial= 30
Split Flow Tol= 0.02
Split Flow Ratio= 0.02
Log Output Level= 0
Friction Slope Method= 1
Unsteady Friction Slope Method= 2
Unsteady Bridges Friction Slope Method= 1
Parabolic Critical Depth
Global Vel Dist=  1 , 1 , 1
Global Log Level= 0
CheckData=True
Encroach Param= -1, 0, 0, 0
BEGIN DESCRIPTION:
Multiple Run
END DESCRIPTION:

--- Clear Creek T 1.f01 (steady flow) ---

Flow Title=Multiple
Number of Profiles=7
Profile Names=10-year,25-year,50-year,1pct_min,100-year,1pct_plu,500-year
River Rch & RM= Clear Creek T 1,Reach-1,4222
     534     722     876     529    1055    2106    1536
Boundary for River Rch & Prof#=Clear Creek T 1,Reach-1,1
Up Type=0
Dn Type=3
Dn Slope=0.005
Boundary for River Rch & Prof#=Clear Creek T 1,Reach-1,2
Up Type=0
Dn Type=3
Dn Slope=0.005
Boundary for River Rch & Prof#=Clear Creek T 1,Reach-1,3
Up Type=0
Dn Type=3
Dn Slope=0.005
Boundary for River Rch & Prof#=Clear Creek T 1,Reach-1,4
Up Type=0
Dn Type=3
Dn Slope=0.005
Boundary for River Rch & Prof#=Clear Creek T 1,Reach-1,5
Up Type=0
Dn Type=3
Dn Slope=0.005
Boundary for River Rch & Prof#=Clear Creek T 1,Reach-1,6
Up Type=0
Dn Type=3
Dn Slope=0.005
Boundary for River Rch & Prof#=Clear Creek T 1,Reach-1,7
Up Type=0
Dn Type=3
Dn Slope=0.005

--- Clear Creek T 1.g01 (geometry) ---

Geom Title=Existing Conditions

River Reach=Clear Creek T 1,Reach-1
Reach XY= 30
      2744626.00      6784461.00      2744565.41      6784510.23
      2744448.93      6784460.67      2744351.01      6784511.40
      2744223.14      6784455.18      2744183.26      6784411.30
      2744220.88      6784308.71      2744010.84      6784111.38
      2743836.50      6784112.24      2743755.79      6784161.21
      2743672.59      6784118.82      2743529.33      6784253.39
      2743432.67      6784170.33      2743376.01      6784202.96
      2743326.10      6784168.78      2743048.80      6784261.39
      2742865.30      6784161.80      2742772.60      6784203.17
      2742660.78      6784111.25      2742350.96      6784211.49
      2742224.43      6784114.44      2742141.89      6784111.55
      2742075.99      6784204.07      2741979.66      6784068.72
      2741903.21      6784111.19      2741822.71      6784069.10
      2741625.90      6784153.66      2741529.42      6784068.83
      2741248.84      6784111.37      2741126.00      6784061.00

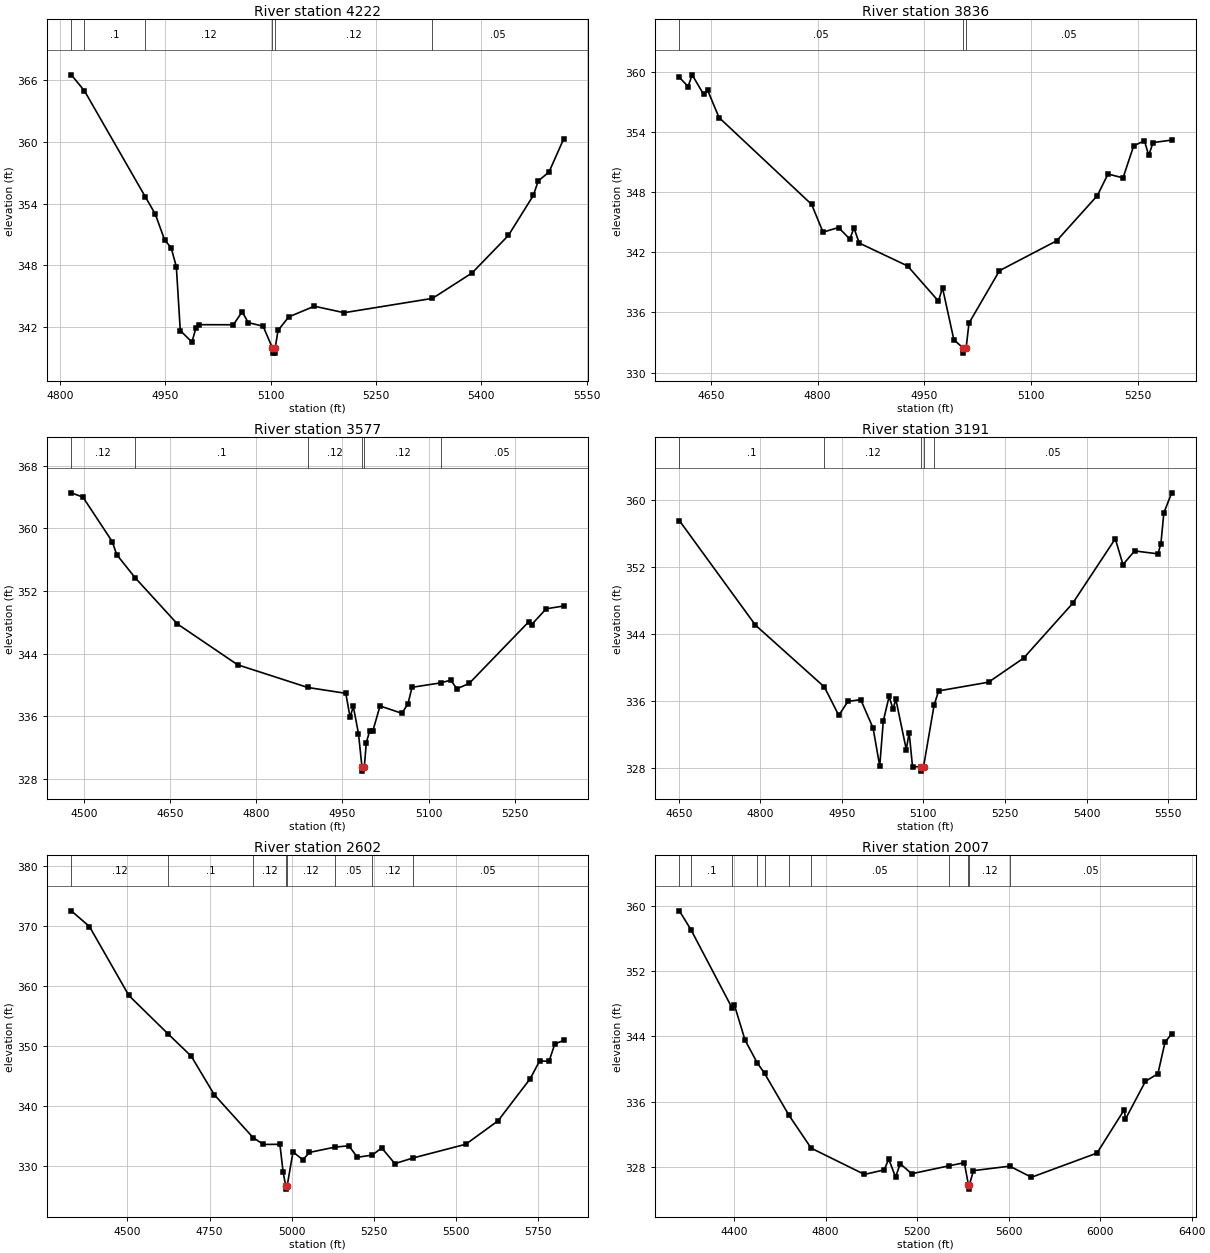
Type RM Length L Ch R = 1,4222,386,386,386
BEGIN DESCRIPTION:
Clear Creek T 1 5.0
END DESCRIPTION:
XS GIS Cut Line= 3
      2744612.34      6784376.96      2744448.93      6784460.67
      2744172.20      6784897.49
#Sta/Elev= 30
  4816.4  366.49  4835.2  364.93  4921.9  354.64  4935.9  352.99  4949.3  350.46
  4958.4  349.74  4965.9  347.88  4971.5  341.69  4988.1  340.57  4993.7  341.93
  4998.8  342.26  5047.0  342.25  5059.6  343.51  5068.2  342.46  5089.4  342.11
  5102.6  340.00  5102.9  339.50  5106.4  339.50  5106.6  340.00  5110.6  341.70
  5125.8  343.01  5162.3  344.05  5204.6  343.42  5330.4  344.81  5386.8  347.28
  5438.4  350.91  5473.9  354.79  5480.9  356.20  5496.2  357.06  5517.1  360.27
#Mann=6,-1,0
  4816.4    0.12       0  4835.2     0.1       0  4921.9    0.12       0
  5102.6    0.07       0  5106.6    0.12       0  5330.4    0.05       0
Bank Sta=5102.6,5106.6
Exp/Cntr=0.3,0.1

Type RM Length L Ch R = 1,3836,259,259,259
BEGIN DESCRIPTION:
Clear Creek T 1 4.0
END DESCRIPTION:
XS GIS Cut Line= 3
      2744566.87      6784167.27      2744222.41      6784359.36
      2743974.18      6784524.07
#Sta/Elev= 30
  4605.6  359.50  4617.9  358.58  4623.6  359.75  4639.6  357.81  4645.4  358.21
  4661.4  355.48  4791.6  346.80  4807.6  344.03  4829.4  344.49  4845.3  343.34
  4851.1  344.45  4858.5  342.94  4926.5  340.65  4969.9  337.14  4975.6  338.47
  4991.6  333.27  5004.8  332.44  5005.1  331.94  5008.8  332.44  5012.8  334.93
  5055.7  340.18  5136.2  343.17  5193.3  347.68  5208.3  349.84  5229.4  349.45
  5244.4  352.65  5259.5  353.17  5265.5  351.70  5271.7  352.98  5297.9  353.23
#Mann=3,-1,0
  4605.6    0.05       0  5004.8    0.05       0  5008.8    0.05       0
Bank Sta=5004.8,5008.8
Exp/Cntr=0.3,0.1

Type RM Length L Ch R = 1,3577,386,386,386
BEGIN DESCRIPTION:
Clear Creek T 1 3.0
END DESCRIPTION:
XS GIS Cut Line= 3
      2744300.60      6783689.57      2744076.00      6784161.00
      2743960.83      6784475.59
#Sta/Elev= 30
  4478.1  364.52  4498.4  363.97  4549.3  358.31  4557.2  356.64  4589.0  353.71
  4662.8  347.80  4767.7  342.59  4889.7  339.70  4956.0  338.95  4963.5  335.88
  4969.0  337.30  4978.1  333.80  4984.2  329.53  4984.4  329.03  4988.2  329.53
  4991.7  332.67  4997.5  334.14  5003.0  334.14  5015.6  337.34  5053.5  336.41
  5064.2  337.60  5071.3  339.72  5120.9  340.28  5138.7  340.63  5149.4  339.53
  5170.7  340.21  5274.2  348.05  5279.6  347.72  5304.8  349.73  5335.3  350.09
#Mann=6,-1,0
  4478.1    0.12       0  4589.0     0.1       0  4889.7    0.12       0
  4984.2    0.07       0  4988.2    0.12       0  5120.9    0.05       0
Bank Sta=4984.2,4988.2
Exp/Cntr=0.3,0.1

Type RM Length L Ch R = 1,3191,589,589,589
BEGIN DESCRIPTION:
Clear Creek T 1 2.0
END DESCRIPTION:
XS GIS Cut Line= 3
      2743684.06      6783809.90      2743726.00      6784161.00
      2743928.31      6784674.48
#Sta/Elev= 30
  4651.2  357.49  4791.1  345.02  4917.9  337.64  4944.4  334.25  4961.1  335.91
  4984.7  336.13  5007.5  332.73  5019.7  328.20  5026.3  333.59  5037.0  336.51
  5044.1  335.00  5049.4  336.16  5068.5  330.18  5073.8  332.19  5080.0  328.14
  5096.2  328.10  5096.5  327.60  5100.2  328.10  5119.7  335.47  5128.0  337.17
  5219.8  338.21  5284.3  341.08  5374.3  347.60  5452.9  355.32  5467.0  352.24
  5488.5  353.87  5531.4  353.52  5536.8  354.74  5542.2  358.41  5556.7  360.80
#Mann=5,-1,0
  4651.2     0.1       0  4917.9    0.12       0  5096.2    0.07       0
  5100.2    0.12       0  5119.7    0.05       0
Bank Sta=5096.2,5100.2
Exp/Cntr=0.3,0.1

Type RM Length L Ch R = 1,2602,595,595,595
BEGIN DESCRIPTION:
Mapping XS 254fe594
END DESCRIPTION:
XS GIS Cut Line= 4
      2743273.31      6783535.70      2743274.73      6784216.31
      2743284.95      6784528.28      2743747.11      6784736.38
#Sta/Elev= 30
  4328.8  372.58  4384.1  369.96  4504.1  358.44  4622.5  352.08  4694.1  348.30
  4764.1  341.88  4882.4  334.70  4914.1  333.55  4964.1  333.58  4974.1  328.87
  4982.1  326.59  4982.4  326.09  4986.1  326.59  5004.1  332.31  5034.1  330.98
  5054.1  332.22  5131.8  333.11  5174.2  333.33  5200.1  331.41  5245.4  331.78
  5274.2  332.97  5314.3  330.35  5368.7  331.28  5530.4  333.59  5628.5  337.50
  5726.5  344.54  5755.2  347.51  5783.8  347.44  5801.4  350.34  5828.4  350.93
#Mann=8,-1,0
  4328.8    0.12       0  4622.5     0.1       0  4882.4    0.12       0
  4982.1    0.07       0  4986.1    0.12       0  5131.8    0.05       0
  5245.4    0.12       0  5368.7    0.05       0
Bank Sta=4982.1,4986.1
Exp/Cntr=0.3,0.1

Type RM Length L Ch R = 1,2007,0,0,0
BEGIN DESCRIPTION:
Clear Creek T 1 1.0
END DESCRIPTION:
XS GIS Cut Line= 4
      2743089.24      6783417.81      2742749.34      6784185.21
      2742772.74      6784635.22      2743614.96      6784820.17
#Sta/Elev= 30
  4160.7  359.36  4211.5  357.05  4391.3  347.47  4401.3  347.85  4447.9  343.55
  4500.5  340.81  4533.2  339.48  4639.2  334.39  4736.9  330.34  4969.6  327.13
  5055.9  327.68  5075.9  329.00  5105.9  326.79  5126.0  328.45  5176.0  327.21
  5337.5  328.17  5406.3  328.56  5424.4  325.83  5424.6  325.33  5428.4  325.83
  5446.0  327.59  5604.9  328.14  5699.7  326.78  5986.3  329.74  6105.5  335.04
  6110.7  333.90  6198.2  338.52  6252.5  339.44  6283.3  343.27  6312.9  344.34
#Mann=11,-1,0
  4160.7    0.12       0  4211.5     0.1       0  4391.3    0.12       0
  4500.5    0.05       0  4533.2    0.12       0  4639.2     0.1       0
  4736.9    0.05       0  5337.5    0.12       0  5424.4    0.05       0
  5428.4    0.12       0  5604.9    0.05       0
Bank Sta=5424.4,5428.4
Exp/Cntr=0.3,0.1

Chan Stop Cuts=-1