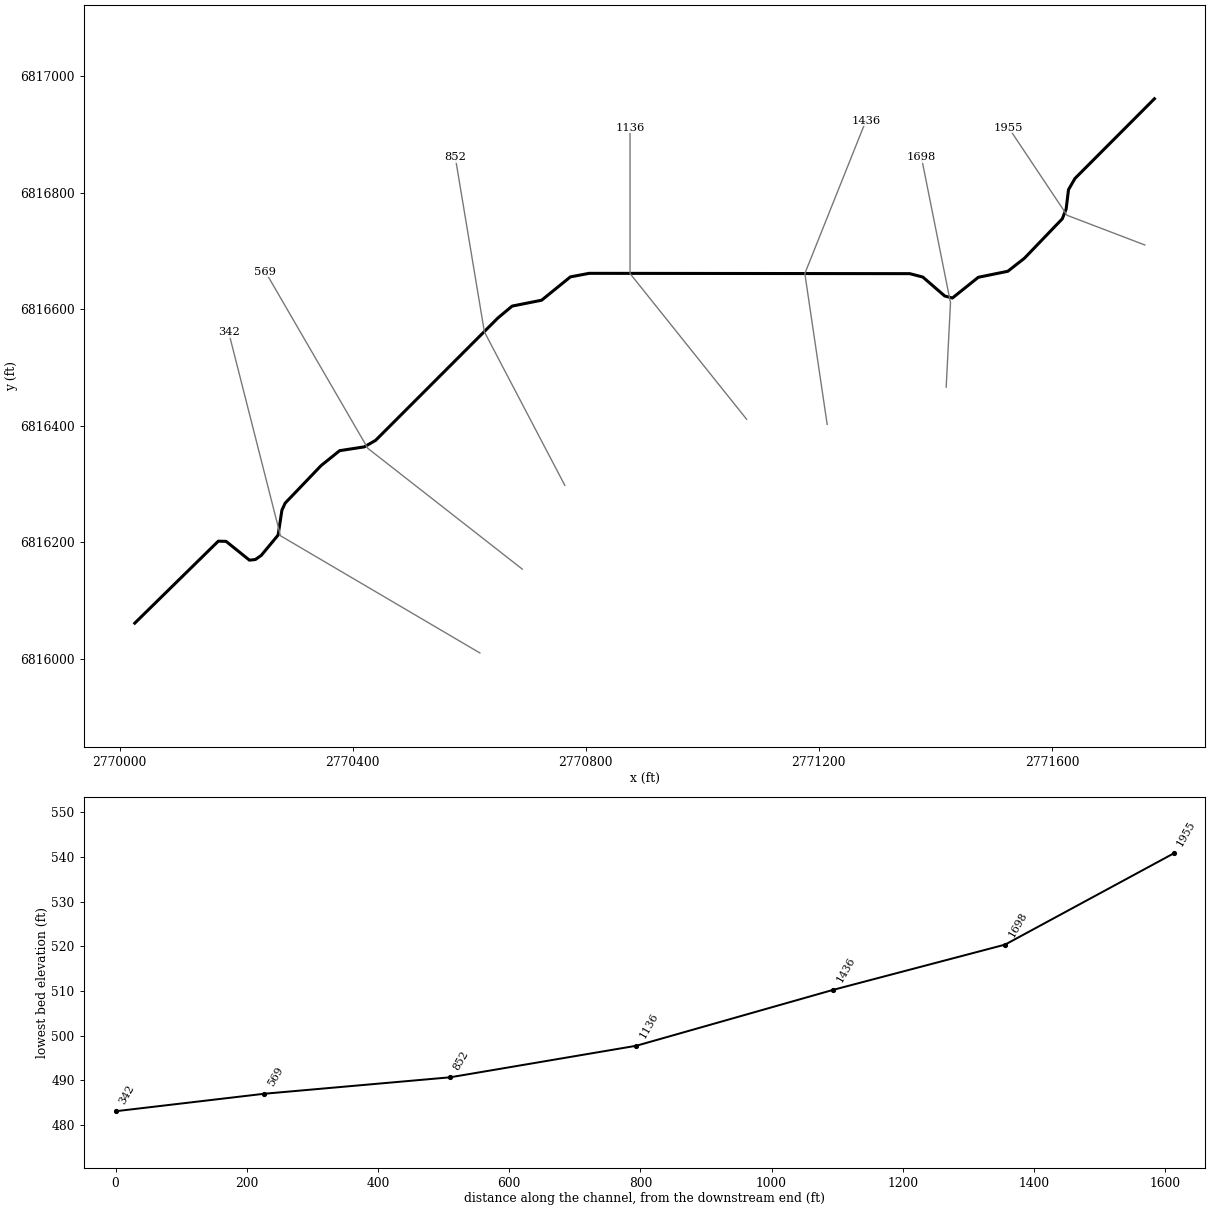
--- Clear Creek T 11.prj (project) ---

Proj Title=Clear Creek T 11 Base Level Engineering
Current Plan=p01
Default Exp/Contr=0.3,0.1
English Units
Geom File=g01
Flow File=f01
Plan File=p01
BEGIN DESCRIPTION:
Clear Creek T 11
END DESCRIPTION:

--- Clear Creek T 11.p01 (plan) ---

Plan Title=Multiple Run
Short Identifier=Multiple
Geom File=g01
Flow File=f01
Subcritical Flow
K Sum by GR= 0
Std Step Tol= 0.01
Critical Tol= 0.01
Num of Std Step Trials= 20
Max Error Tol= 0.3
Flow Tol Ratio= 0.001
Split Flow NTrial= 30
Split Flow Tol= 0.02
Split Flow Ratio= 0.02
Log Output Level= 0
Friction Slope Method= 1
Unsteady Friction Slope Method= 2
Unsteady Bridges Friction Slope Method= 1
Parabolic Critical Depth
Global Vel Dist=  1 , 1 , 1
Global Log Level= 0
CheckData=True
Encroach Param= -1, 0, 0, 0
BEGIN DESCRIPTION:
Multiple Run
END DESCRIPTION:

--- Clear Creek T 11.f01 (steady flow) ---

Flow Title=Multiple
Number of Profiles=7
Profile Names=10-year,25-year,50-year,1pct_min,100-year,1pct_plu,500-year
River Rch & RM= Clear Creek T 11,Reach-1,1955
     235     304     359     213     424     847     590
Boundary for River Rch & Prof#=Clear Creek T 11,Reach-1,1
Up Type=0
Dn Type=3
Dn Slope=0.005
Boundary for River Rch & Prof#=Clear Creek T 11,Reach-1,2
Up Type=0
Dn Type=3
Dn Slope=0.005
Boundary for River Rch & Prof#=Clear Creek T 11,Reach-1,3
Up Type=0
Dn Type=3
Dn Slope=0.005
Boundary for River Rch & Prof#=Clear Creek T 11,Reach-1,4
Up Type=0
Dn Type=3
Dn Slope=0.005
Boundary for River Rch & Prof#=Clear Creek T 11,Reach-1,5
Up Type=0
Dn Type=3
Dn Slope=0.005
Boundary for River Rch & Prof#=Clear Creek T 11,Reach-1,6
Up Type=0
Dn Type=3
Dn Slope=0.005
Boundary for River Rch & Prof#=Clear Creek T 11,Reach-1,7
Up Type=0
Dn Type=3
Dn Slope=0.005

--- Clear Creek T 11.g01 (geometry) ---

Geom Title=Existing Conditions

River Reach=Clear Creek T 11,Reach-1
Reach XY= 30
      2771776.00      6816961.00      2771639.63      6816824.21
      2771628.53      6816804.95      2771624.46      6816771.63
      2771617.85      6816754.93      2771552.88      6816687.26
      2771524.36      6816664.91      2771473.72      6816654.59
      2771429.32      6816619.04      2771416.10      6816622.46
      2771378.45      6816654.98      2771356.02      6816660.82
      2770805.85      6816661.36      2770773.65      6816655.29
      2770724.25      6816615.22      2770673.70      6816605.17
      2770649.18      6816584.71      2770439.21      6816374.63
      2770419.95      6816363.54      2770377.64      6816357.03
      2770345.77      6816331.41      2770284.15      6816267.03
      2770278.53      6816254.88      2770272.02      6816212.18
      2770243.04      6816177.24      2770232.95      6816170.19
      2770222.85      6816169.08      2770182.68      6816201.38
      2770169.34      6816201.70      2770026.00      6816061.00

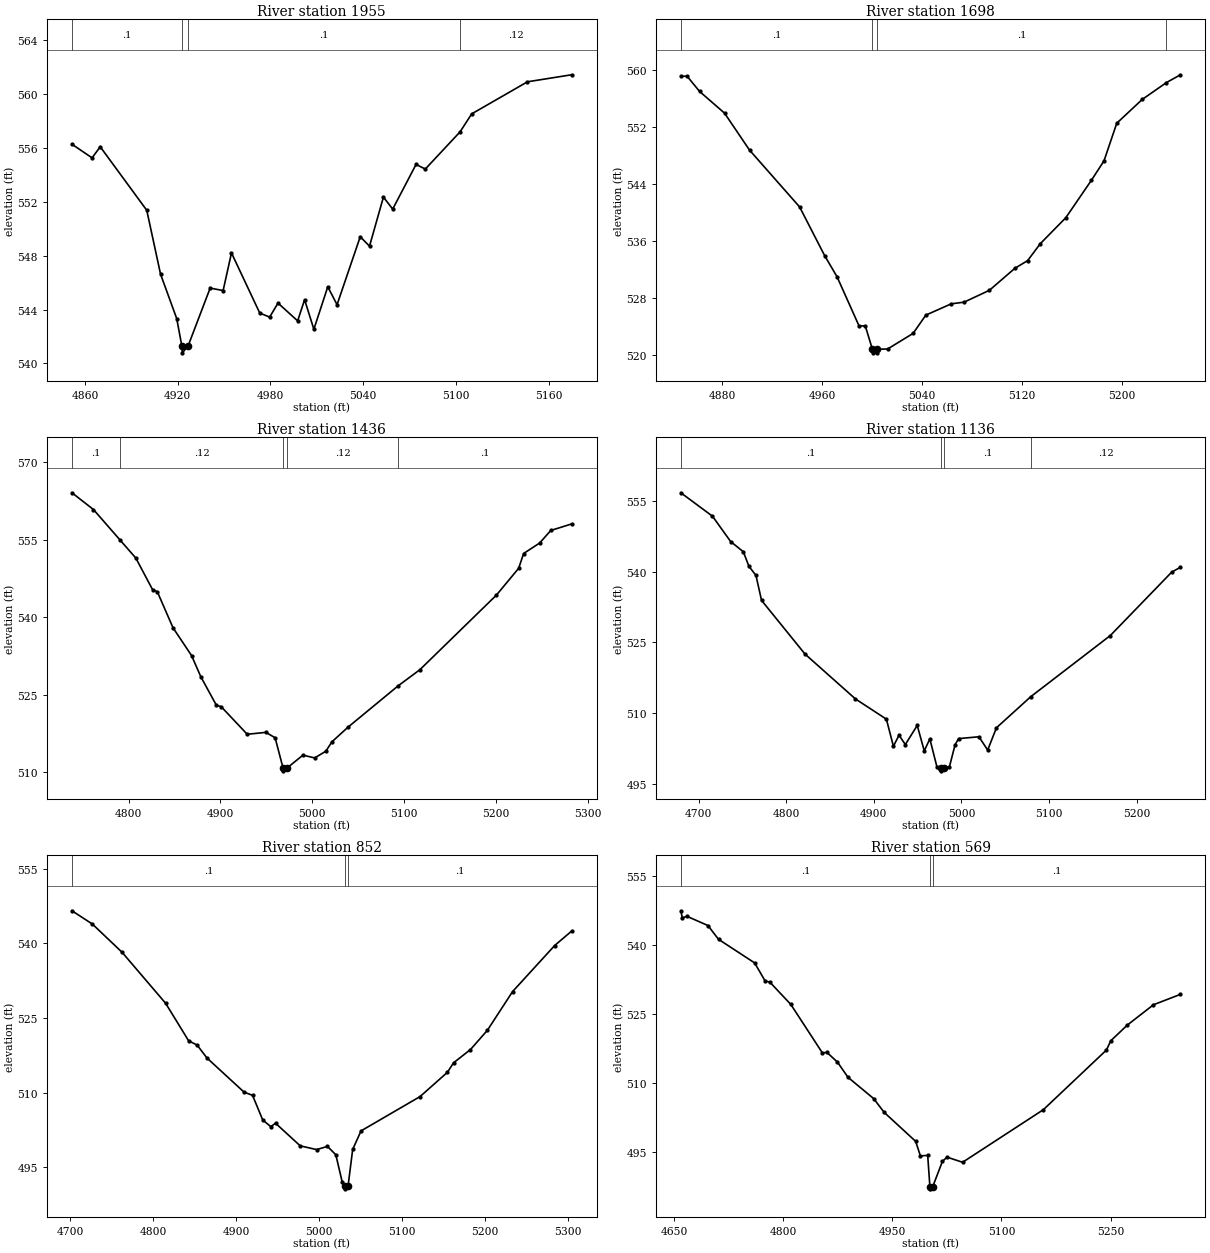
Type RM Length L Ch R = 1,1955,257,257,257
BEGIN DESCRIPTION:
Clear Creek T 11 7.0
END DESCRIPTION:
XS GIS Cut Line= 3
      2771759.55      6816710.01      2771626.00      6816761.00
      2771526.02      6816910.98
#Sta/Elev= 30
  4851.6  556.26  4864.6  555.25  4869.9  556.07  4900.0  551.36  4908.9  546.63
  4919.4  543.32  4922.7  541.29  4923.0  540.79  4926.7  541.29  4941.0  545.59
  4949.4  545.41  4954.8  548.20  4973.1  543.74  4979.5  543.44  4984.9  544.48
  4997.6  543.16  5002.1  544.73  5008.1  542.54  5017.1  545.69  5023.1  544.36
  5038.1  549.40  5044.1  548.70  5053.1  552.34  5059.1  551.45  5074.2  554.76
  5080.2  554.42  5102.7  557.18  5110.2  558.51  5146.3  560.89  5174.8  561.41
#Mann=4,-1,0
  4851.6     0.1       0  4922.7    0.07       0  4926.7     0.1       0
  5102.7    0.12       0
Bank Sta=4922.7,4926.7
Exp/Cntr=0.3,0.1

Type RM Length L Ch R = 1,1698,262,262,262
BEGIN DESCRIPTION:
Clear Creek T 11 6.0
END DESCRIPTION:
XS GIS Cut Line= 3
      2771418.59      6816466.02      2771426.00      6816611.00
      2771376.00      6816860.98
#Sta/Elev= 30
  4846.9  559.07  4851.9  559.07  4861.9  556.94  4881.9  553.90  4901.9  548.73
  4942.0  540.78  4962.0  533.98  4972.0  531.00  4989.6  524.13  4994.6  524.13
  5000.3  520.86  5000.5  520.36  5004.0  520.36  5004.3  520.86  5012.5  520.90
  5032.9  523.08  5043.1  525.64  5063.5  527.22  5073.7  527.45  5094.0  529.11
  5114.4  532.19  5124.6  533.26  5134.8  535.64  5155.2  539.27  5175.6  544.48
  5185.8  547.23  5196.0  552.49  5216.4  555.82  5235.8  558.18  5247.0  559.27
#Mann=4,-1,0
  4846.9     0.1       0  5000.3    0.07       0  5004.3     0.1       0
  5235.8    0.12       0
Bank Sta=5000.3,5004.3
Exp/Cntr=0.3,0.1

Type RM Length L Ch R = 1,1436,300,300,300
BEGIN DESCRIPTION:
Clear Creek T 11 5.0
END DESCRIPTION:
XS GIS Cut Line= 3
      2771214.33      6816402.13      2771176.00      6816661.00
      2771280.84      6816923.33
#Sta/Elev= 30
  4738.3  564.08  4761.7  560.84  4790.9  554.89  4807.9  551.43  4826.2  545.29
  4831.3  544.91  4848.4  537.93  4868.6  532.55  4878.7  528.44  4895.7  522.91
  4900.8  522.67  4929.2  517.31  4949.5  517.68  4959.6  516.64  4968.3  510.73
  4968.5  510.23  4972.3  510.73  4989.9  513.27  5002.7  512.73  5014.8  514.02
  5021.5  515.85  5039.1  518.70  5093.8  526.72  5117.2  529.80  5200.7  544.27
  5224.9  549.46  5230.3  552.32  5247.7  554.34  5259.9  556.78  5282.5  558.04
#Mann=5,-1,0
  4738.3     0.1       0  4790.9    0.12       0  4968.3    0.07       0
  4972.3    0.12       0  5093.8     0.1       0
Bank Sta=4968.3,4972.3
Exp/Cntr=0.3,0.1

Type RM Length L Ch R = 1,1136,284,284,284
BEGIN DESCRIPTION:
Clear Creek T 11 4.0
END DESCRIPTION:
XS GIS Cut Line= 3
      2771076.03      6816410.97      2770876.00      6816661.00
      2770876.00      6816911.00
#Sta/Elev= 30
  4679.7  556.81  4715.8  551.83  4736.6  546.43  4751.0  544.28  4757.4  541.17
  4765.4  539.26  4771.8  533.94  4821.4  522.53  4879.0  512.99  4914.3  508.69
  4922.3  502.93  4928.7  505.28  4935.9  503.30  4949.5  507.36  4957.5  501.96
  4963.9  504.50  4971.9  498.60  4976.3  498.21  4976.5  497.71  4980.3  498.21
  4986.3  498.62  4992.7  503.26  4996.7  504.56  5019.9  504.95  5029.9  502.13
  5039.9  506.86  5079.0  513.46  5169.9  526.47  5239.9  539.94  5249.9  540.98
#Mann=4,-1,0
  4679.7     0.1       0  4976.3    0.07       0  4980.3     0.1       0
  5079.0    0.12       0
Bank Sta=4976.3,4980.3
Exp/Cntr=0.3,0.1

Type RM Length L Ch R = 1,852,283,283,283
BEGIN DESCRIPTION:
Clear Creek T 11 3.0
END DESCRIPTION:
XS GIS Cut Line= 3
      2770764.08      6816297.46      2770626.00      6816561.00
      2770575.99      6816861.04
#Sta/Elev= 30
  4702.2  546.53  4726.8  543.86  4762.6  538.18  4815.0  527.94  4842.7  520.40
  4853.0  519.53  4864.8  516.94  4909.4  510.09  4919.7  509.43  4932.0  504.47
  4941.7  503.14  4947.4  503.83  4977.1  499.28  4996.9  498.53  5009.9  499.17
  5020.0  497.49  5027.6  492.08  5030.7  491.14  5030.9  490.64  5034.7  491.14
  5040.3  498.56  5050.4  502.29  5121.4  509.18  5154.3  514.05  5161.9  515.99
  5182.2  518.64  5202.5  522.50  5232.9  530.29  5283.6  539.55  5303.9  542.43
#Mann=3,-1,0
  4702.2     0.1       0  5030.7    0.07       0  5034.7     0.1       0
Bank Sta=5030.7,5034.7
Exp/Cntr=0.3,0.1

Type RM Length L Ch R = 1,569,227,227,227
BEGIN DESCRIPTION:
Clear Creek T 11 2.0
END DESCRIPTION:
XS GIS Cut Line= 3
      2770691.17      6816153.65      2770426.00      6816361.00
      2770250.12      6816664.16
#Sta/Elev= 30
  4659.0  547.38  4661.0  545.85  4667.4  546.18  4696.3  544.17  4710.8  541.18
  4760.5  536.05  4775.0  532.10  4781.3  531.89  4810.2  527.04  4853.6  516.51
  4860.0  516.59  4874.4  514.50  4888.9  511.19  4924.2  506.57  4938.6  503.58
  4982.0  497.27  4988.4  494.12  4998.5  494.22  5001.5  487.46  5001.7  486.96
  5005.5  487.46  5018.7  492.91  5025.0  493.85  5046.5  492.73  5157.5  504.15
  5244.4  517.13  5250.2  519.12  5273.1  522.55  5309.0  526.96  5346.1  529.22
#Mann=3,-1,0
  4659.0     0.1       0  5001.5    0.07       0  5005.5     0.1       0
Bank Sta=5001.5,5005.5
Exp/Cntr=0.3,0.1

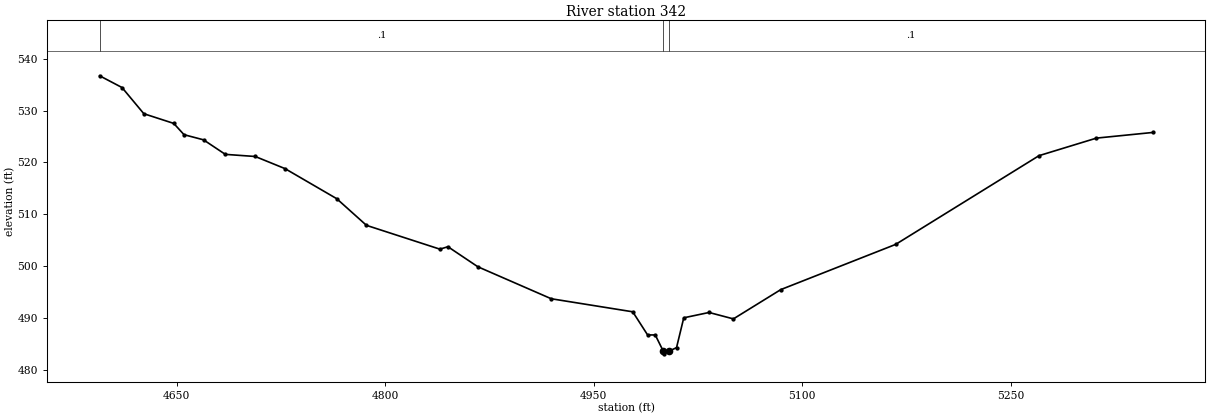
Type RM Length L Ch R = 1,342,0,0,0
BEGIN DESCRIPTION:
Clear Creek T 11 1.0
END DESCRIPTION:
XS GIS Cut Line= 3
      2770618.29      6816009.82      2770276.00      6816211.00
      2770187.14      6816560.24
#Sta/Elev= 30
  4594.7  536.75  4610.8  534.48  4626.5  529.42  4648.0  527.55  4655.4  525.37
  4669.4  524.38  4685.1  521.57  4706.6  521.16  4728.0  518.82  4765.2  513.01
  4786.6  507.86  4839.4  503.26  4845.2  503.73  4866.7  499.86  4919.5  493.68
  4978.1  491.16  4988.8  486.69  4994.3  486.69  5000.1  483.54  5000.3  483.04
  5004.1  483.54  5009.6  484.24  5014.8  490.00  5033.0  491.03  5050.5  489.79
  5084.6  495.45  5167.2  504.18  5270.3  521.32  5311.6  524.71  5352.1  525.80
#Mann=3,-1,0
  4594.7     0.1       0  5000.1    0.07       0  5004.1     0.1       0
Bank Sta=5000.1,5004.1
Exp/Cntr=0.3,0.1

Chan Stop Cuts=-1