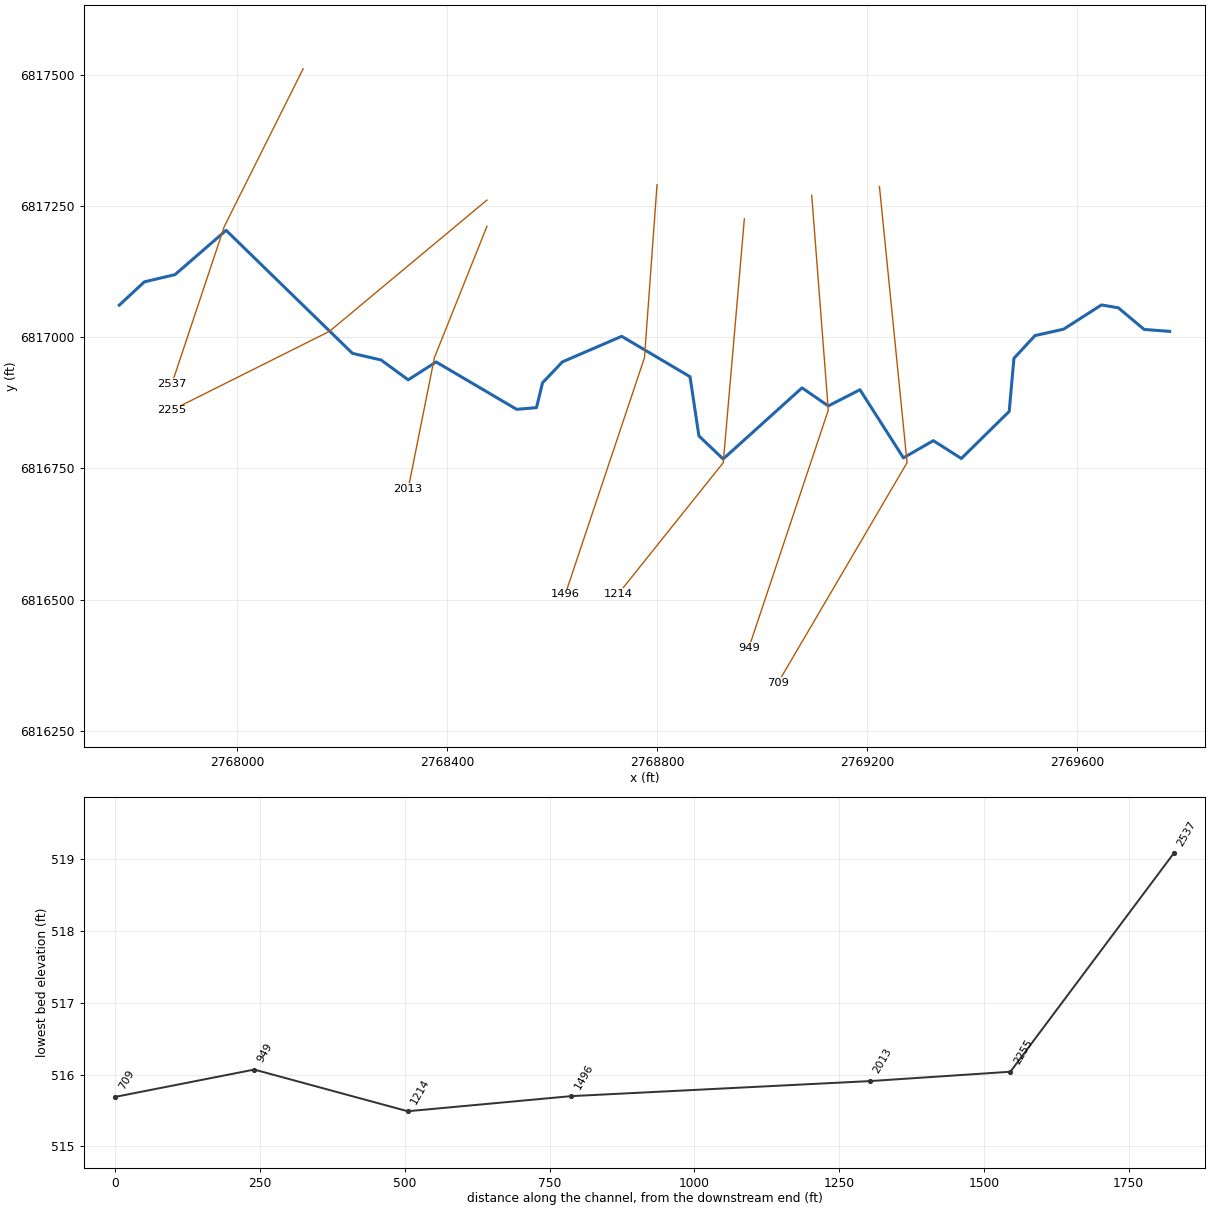
--- Clear Creek T 12.prj (project) ---

Proj Title=Clear Creek T 12 Base Level Engineering
Current Plan=p01
Default Exp/Contr=0.3,0.1
English Units
Geom File=g01
Flow File=f01
Plan File=p01
BEGIN DESCRIPTION:
Clear Creek T 12
END DESCRIPTION:

--- Clear Creek T 12.p01 (plan) ---

Plan Title=Multiple Run
Short Identifier=Multiple
Geom File=g01
Flow File=f01
Subcritical Flow
K Sum by GR= 0
Std Step Tol= 0.01
Critical Tol= 0.01
Num of Std Step Trials= 20
Max Error Tol= 0.3
Flow Tol Ratio= 0.001
Split Flow NTrial= 30
Split Flow Tol= 0.02
Split Flow Ratio= 0.02
Log Output Level= 0
Friction Slope Method= 1
Unsteady Friction Slope Method= 2
Unsteady Bridges Friction Slope Method= 1
Parabolic Critical Depth
Global Vel Dist=  1 , 1 , 1
Global Log Level= 0
CheckData=True
Encroach Param= -1, 0, 0, 0
BEGIN DESCRIPTION:
Multiple Run
END DESCRIPTION:

--- Clear Creek T 12.f01 (steady flow) ---

Flow Title=Multiple
Number of Profiles=7
Profile Names=10-year,25-year,50-year,1pct_min,100-year,1pct_plu,500-year
River Rch & RM= Clear Creek T 12,Reach-1,2537
     404     537     645     386     770    1536    1098
Boundary for River Rch & Prof#=Clear Creek T 12,Reach-1,1
Up Type=0
Dn Type=3
Dn Slope=0.005
Boundary for River Rch & Prof#=Clear Creek T 12,Reach-1,2
Up Type=0
Dn Type=3
Dn Slope=0.005
Boundary for River Rch & Prof#=Clear Creek T 12,Reach-1,3
Up Type=0
Dn Type=3
Dn Slope=0.005
Boundary for River Rch & Prof#=Clear Creek T 12,Reach-1,4
Up Type=0
Dn Type=3
Dn Slope=0.005
Boundary for River Rch & Prof#=Clear Creek T 12,Reach-1,5
Up Type=0
Dn Type=3
Dn Slope=0.005
Boundary for River Rch & Prof#=Clear Creek T 12,Reach-1,6
Up Type=0
Dn Type=3
Dn Slope=0.005
Boundary for River Rch & Prof#=Clear Creek T 12,Reach-1,7
Up Type=0
Dn Type=3
Dn Slope=0.005

--- Clear Creek T 12.g01 (geometry) ---

Geom Title=Existing Conditions

River Reach=Clear Creek T 12,Reach-1
Reach XY= 30
      2767776.00      6817061.00      2767823.65      6817105.30
      2767882.09      6817119.09      2767979.34      6817203.41
      2768219.95      6816969.12      2768274.35      6816956.56
      2768326.08      6816918.76      2768379.23      6816952.76
      2768532.50      6816862.60      2768570.38      6816865.80
      2768581.89      6816913.08      2768619.69      6816952.94
      2768732.61      6817001.61      2768862.74      6816924.66
      2768879.62      6816812.01      2768925.76      6816767.97
      2769076.00      6816903.46      2769126.01      6816869.06
      2769186.32      6816899.90      2769269.05      6816770.17
      2769325.99      6816802.94      2769379.35      6816768.98
      2769470.47      6816858.55      2769479.53      6816959.72
      2769519.62      6817003.00      2769574.23      6817015.26
      2769646.17      6817061.35      2769678.25      6817055.88
      2769727.49      6817014.69      2769776.00      6817011.00

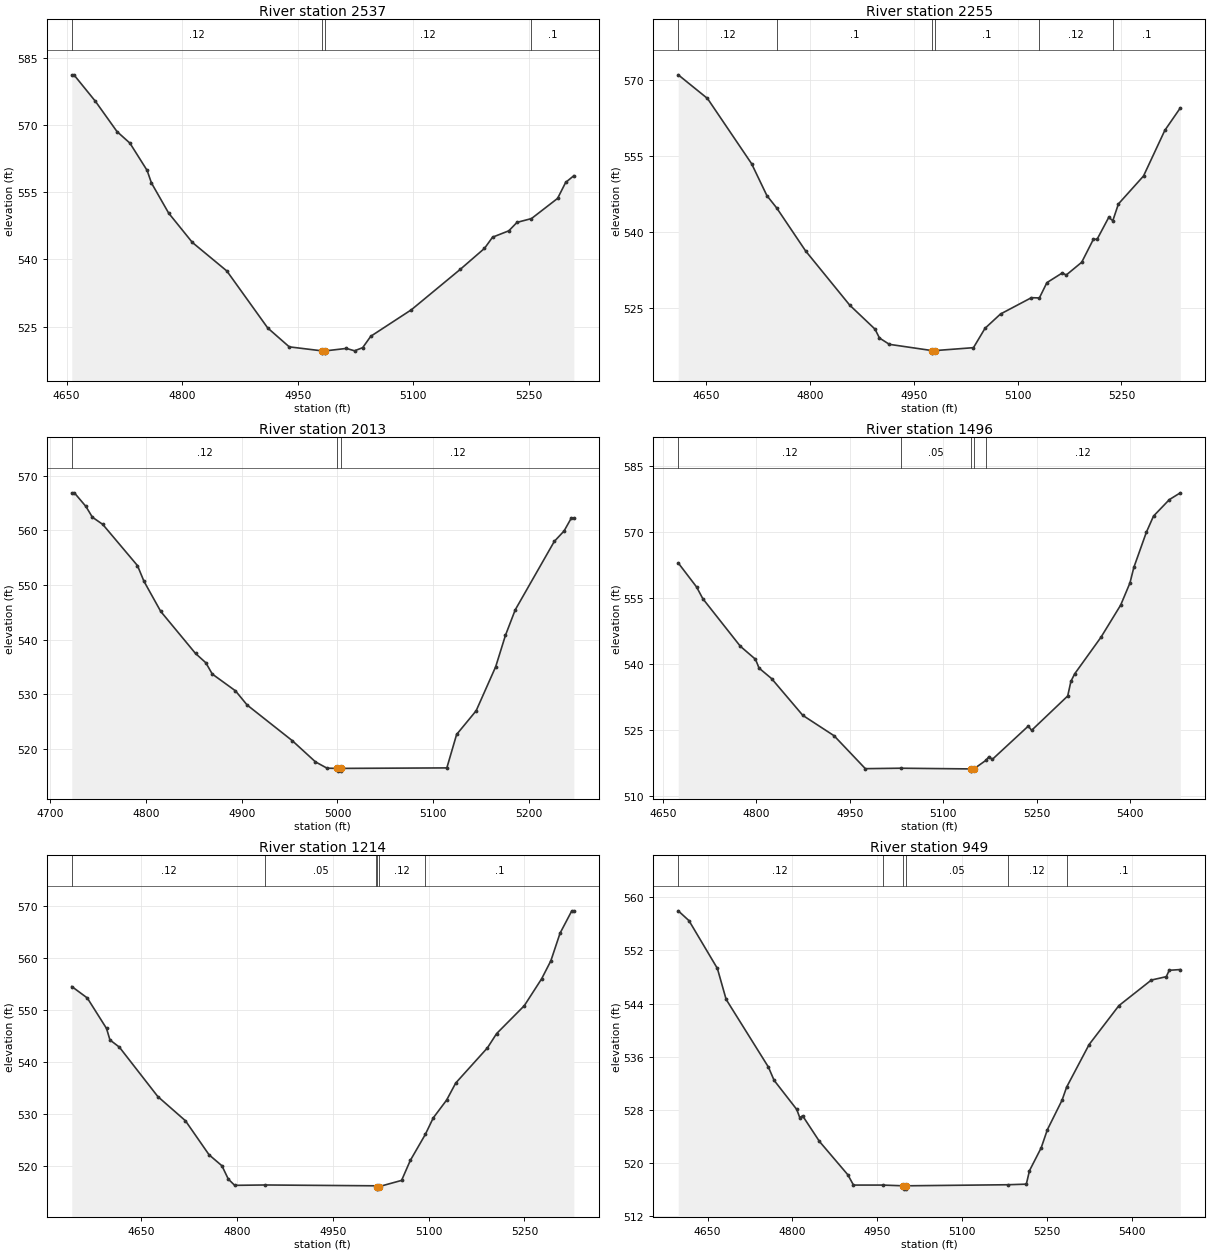
Type RM Length L Ch R = 1,2537,282,282,282
BEGIN DESCRIPTION:
Clear Creek T 12 7.0
END DESCRIPTION:
XS GIS Cut Line= 3
      2768126.01      6817511.02      2767976.00      6817211.00
      2767875.99      6816910.96
#Sta/Elev= 30
  4656.7  581.15  4659.5  581.15  4687.5  575.22  4715.4  568.50  4732.2  565.91
  4754.5  559.83  4760.1  557.04  4782.5  550.30  4813.2  543.77  4858.0  537.40
  4911.1  524.68  4939.0  520.48  4981.7  519.58  4982.0  519.08  4985.5  519.08
  4985.7  519.58  5013.2  520.13  5023.7  519.60  5034.3  520.30  5044.8  522.84
  5097.5  528.75  5160.8  537.74  5192.4  542.44  5202.9  544.94  5224.0  546.36
  5234.6  548.24  5253.4  549.09  5287.3  553.59  5297.8  557.16  5308.4  558.65
#Mann=4,-1,0
  4656.7    0.12       0  4981.7    0.07       0  4985.7    0.12       0
  5253.4     0.1       0
Bank Sta=4981.7,4985.7
Exp/Cntr=0.3,0.1

Type RM Length L Ch R = 1,2255,242,242,242
BEGIN DESCRIPTION:
Clear Creek T 12 6.0
END DESCRIPTION:
XS GIS Cut Line= 3
      2768476.02      6817261.02      2768176.00      6817011.00
      2767875.96      6816860.98
#Sta/Elev= 30
  4609.2  571.11  4651.5  566.43  4715.3  553.52  4737.4  547.21  4751.4  544.80
  4793.4  536.26  4857.2  525.53  4893.7  520.79  4900.2  519.03  4914.5  517.78
  4976.3  516.54  4976.5  516.04  4980.3  516.54  5036.1  517.12  5052.8  520.95
  5075.2  523.78  5119.9  527.01  5131.4  526.96  5142.3  529.99  5164.7  531.92
  5170.2  531.49  5192.6  534.02  5209.4  538.54  5215.0  538.60  5231.7  542.90
  5237.6  542.25  5245.7  545.56  5282.0  551.09  5312.8  560.12  5335.2  564.56
#Mann=6,-1,0
  4609.2    0.12       0  4751.4     0.1       0  4976.3    0.07       0
  4980.3     0.1       0  5131.4    0.12       0  5237.6     0.1       0
Bank Sta=4976.3,4980.3
Exp/Cntr=0.3,0.1

Type RM Length L Ch R = 1,2013,517,517,517
BEGIN DESCRIPTION:
Clear Creek T 12 5.0
END DESCRIPTION:
XS GIS Cut Line= 3
      2768475.98      6817210.96      2768376.00      6816961.00
      2768325.99      6816710.97
#Sta/Elev= 30
  4722.6  566.85  4725.3  566.85  4737.4  564.35  4744.1  562.39  4754.9  561.08
  4791.2  553.53  4798.0  550.65  4815.5  545.14  4851.8  537.45  4862.6  535.74
  4869.3  533.68  4893.5  530.61  4905.7  528.01  4952.8  521.49  4977.0  517.61
  4989.1  516.45  5000.0  516.41  5000.3  515.91  5003.8  515.91  5004.0  516.41
  5114.2  516.50  5124.4  522.62  5144.8  526.96  5165.2  535.02  5175.4  540.77
  5185.6  545.43  5226.4  557.96  5236.6  559.87  5244.2  562.25  5246.8  562.25
#Mann=3,-1,0
  4722.6    0.12       0  5000.0    0.07       0  5004.0    0.12       0
Bank Sta=5000,5004
Exp/Cntr=0.3,0.1

Type RM Length L Ch R = 1,1496,282,282,282
BEGIN DESCRIPTION:
Clear Creek T 12 4.0
END DESCRIPTION:
XS GIS Cut Line= 3
      2768799.91      6817290.37      2768776.00      6816961.00
      2768625.10      6816510.22
#Sta/Elev= 30
  4674.9  562.97  4704.3  557.52  4714.4  554.84  4774.5  544.06  4798.8  541.10
  4804.6  539.09  4824.7  536.71  4874.8  528.36  4924.9  523.74  4975.1  516.26
  5031.7  516.36  5145.2  516.20  5145.4  515.70  5149.2  516.20  5168.5  518.14
  5173.5  518.99  5178.8  518.36  5236.6  525.93  5241.9  524.96  5299.8  532.76
  5305.0  536.10  5311.0  537.79  5353.1  546.08  5384.8  553.40  5399.7  558.43
  5405.9  561.94  5426.0  569.93  5437.5  573.61  5462.9  577.35  5480.5  578.89
#Mann=5,-1,0
  4674.9    0.12       0  5031.7    0.05       0  5145.2    0.07       0
  5149.2    0.05       0  5168.5    0.12       0
Bank Sta=5145.2,5149.2
Exp/Cntr=0.3,0.1

Type RM Length L Ch R = 1,1214,265,265,265
BEGIN DESCRIPTION:
Clear Creek T 12 3.0
END DESCRIPTION:
XS GIS Cut Line= 3
      2768966.18      6817225.20      2768926.00      6816761.00
      2768725.99      6816510.99
#Sta/Elev= 30
  4541.2  554.53  4565.5  552.32  4595.6  546.45  4601.0  544.23  4615.7  542.85
  4675.9  533.33  4719.2  528.66  4756.2  522.10  4776.3  519.99  4786.3  517.42
  4796.3  516.22  4844.4  516.29  5017.5  516.13  5018.7  515.99  5019.0  515.49
  5022.7  515.99  5057.6  517.17  5071.2  521.01  5094.7  526.02  5107.2  529.22
  5128.0  532.63  5142.4  535.94  5192.0  542.71  5206.4  545.46  5249.7  550.83
  5276.9  556.02  5291.3  559.48  5305.7  564.80  5324.1  569.11  5327.3  569.11
#Mann=6,-1,0
  4541.2    0.12       0  4844.4    0.05       0  5017.5    0.12       0
  5018.7    0.03       0  5022.7    0.12       0  5094.7     0.1       0
Bank Sta=5018.7,5022.7
Exp/Cntr=0.3,0.1

Type RM Length L Ch R = 1,949,240,240,240
BEGIN DESCRIPTION:
Clear Creek T 12 2.0
END DESCRIPTION:
XS GIS Cut Line= 3
      2769094.46      6817269.97      2769126.00      6816861.00
      2768974.60      6816408.01
#Sta/Elev= 30
  4598.0  557.96  4617.0  556.48  4667.2  549.29  4682.7  544.63  4757.4  534.45
  4767.5  532.45  4807.6  528.06  4812.9  526.83  4817.9  527.11  4847.7  523.25
  4897.9  518.23  4907.9  516.68  4959.2  516.68  4996.2  516.57  4996.4  516.07
  4999.9  516.07  5000.2  516.57  5180.7  516.73  5213.5  516.82  5219.1  518.85
  5239.8  522.29  5250.7  525.01  5276.7  529.46  5284.8  531.43  5324.5  537.83
  5377.2  543.69  5434.6  547.54  5461.0  548.05  5466.2  549.01  5485.8  549.12
#Mann=6,-1,0
  4598.0    0.12       0  4959.2    0.05       0  4996.2    0.03       0
  5000.2    0.05       0  5180.7    0.12       0  5284.8     0.1       0
Bank Sta=4996.2,5000.2
Exp/Cntr=0.3,0.1

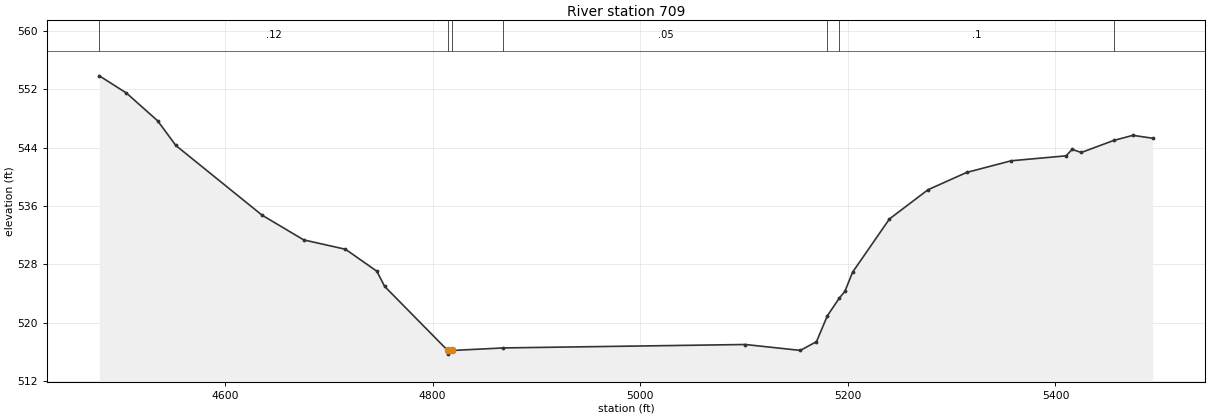
Type RM Length L Ch R = 1,709,0,0,0
BEGIN DESCRIPTION:
Clear Creek T 12 1.0
END DESCRIPTION:
XS GIS Cut Line= 3
      2769223.42      6817286.94      2769276.00      6816761.00
      2769030.12      6816341.62
#Sta/Elev= 30
  4479.0  553.85  4505.1  551.49  4535.2  547.68  4552.7  544.30  4635.7  534.75
  4675.9  531.35  4716.1  530.07  4746.3  527.06  4753.8  524.98  4814.6  516.19
  4814.9  515.69  4818.6  516.19  4868.3  516.54  5101.3  517.01  5154.2  516.20
  5169.8  517.40  5180.3  520.95  5191.8  523.38  5197.1  524.28  5204.6  526.93
  5240.1  534.23  5277.2  538.23  5314.4  540.60  5357.3  542.20  5410.2  542.88
  5416.0  543.76  5424.9  543.34  5456.1  544.99  5474.6  545.69  5493.7  545.29
#Mann=7,-1,0
  4479.0    0.12       0  4814.6    0.03       0  4818.6    0.12       0
  4868.3    0.05       0  5180.3    0.12       0  5191.8     0.1       0
  5456.1    0.05       0
Bank Sta=4814.6,4818.6
Exp/Cntr=0.3,0.1

Chan Stop Cuts=-1