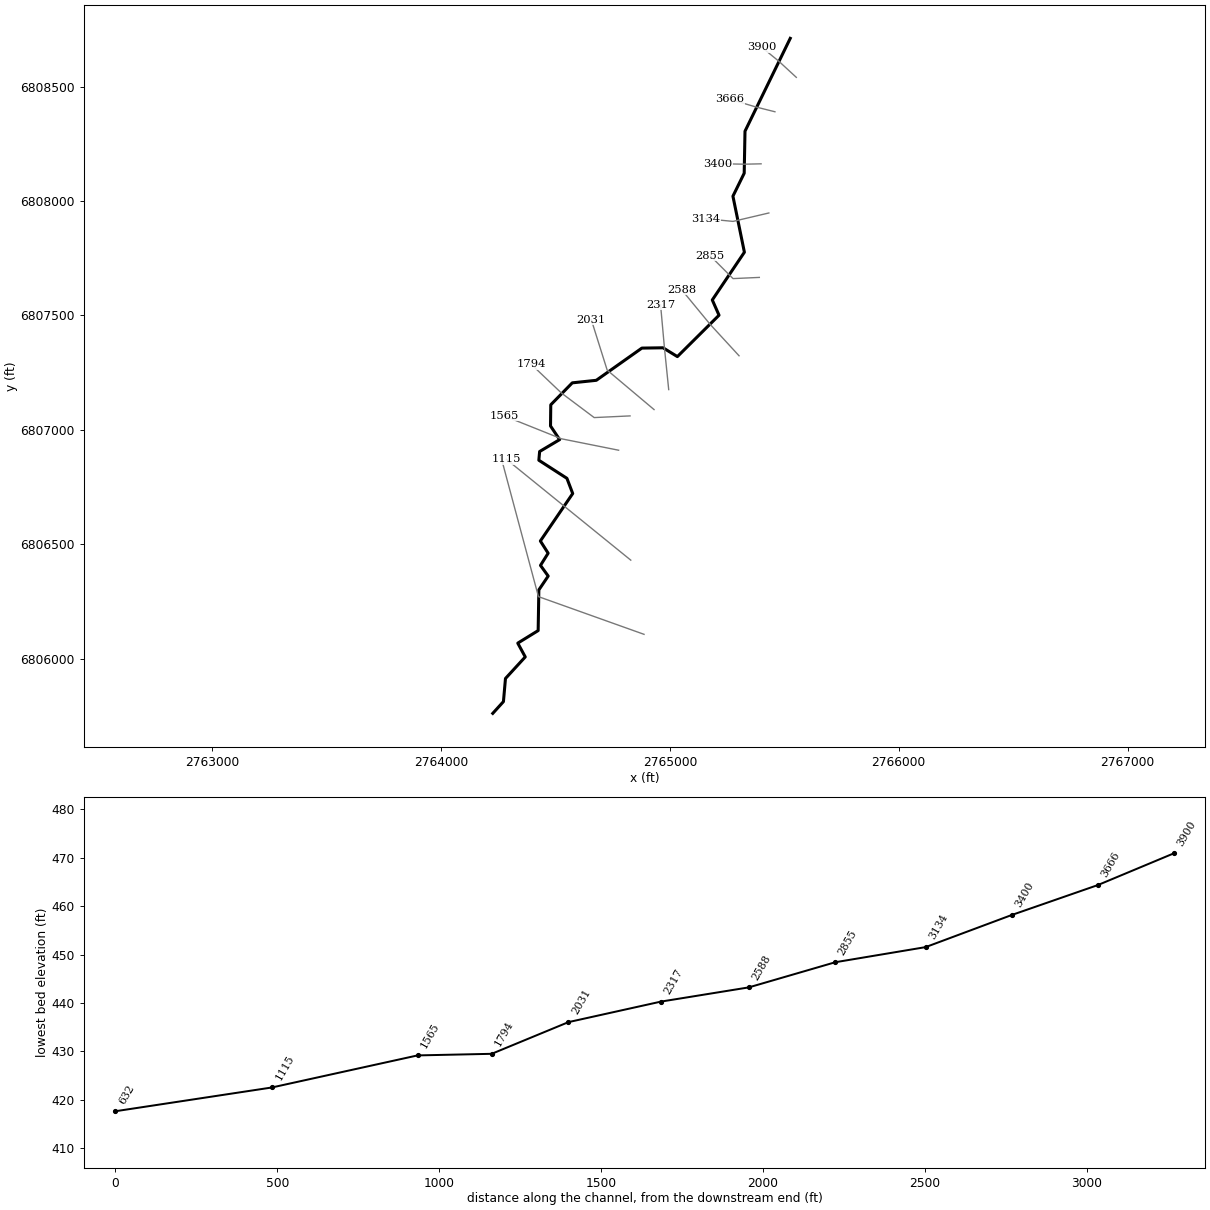
--- Clear Creek T 13.prj (project) ---

Proj Title=Clear Creek T 13 Base Level Engineering
Current Plan=p01
Default Exp/Contr=0.3,0.1
English Units
Geom File=g01
Flow File=f01
Plan File=p01
BEGIN DESCRIPTION:
Clear Creek T 13
END DESCRIPTION:

--- Clear Creek T 13.p01 (plan) ---

Plan Title=Multiple Run
Short Identifier=Multiple
Geom File=g01
Flow File=f01
Subcritical Flow
K Sum by GR= 0
Std Step Tol= 0.01
Critical Tol= 0.01
Num of Std Step Trials= 20
Max Error Tol= 0.3
Flow Tol Ratio= 0.001
Split Flow NTrial= 30
Split Flow Tol= 0.02
Split Flow Ratio= 0.02
Log Output Level= 0
Friction Slope Method= 1
Unsteady Friction Slope Method= 2
Unsteady Bridges Friction Slope Method= 1
Parabolic Critical Depth
Global Vel Dist=  1 , 1 , 1
Global Log Level= 0
CheckData=True
Encroach Param= -1, 0, 0, 0
BEGIN DESCRIPTION:
Multiple Run
END DESCRIPTION:

--- Clear Creek T 13.f01 (steady flow) ---

Flow Title=Multiple
Number of Profiles=7
Profile Names=10-year,25-year,50-year,1pct_min,100-year,1pct_plu,500-year
River Rch & RM= Clear Creek T 13,Reach-1,3900
     172     216     249     144     287     573     381
Boundary for River Rch & Prof#=Clear Creek T 13,Reach-1,1
Up Type=0
Dn Type=3
Dn Slope=0.005
Boundary for River Rch & Prof#=Clear Creek T 13,Reach-1,2
Up Type=0
Dn Type=3
Dn Slope=0.005
Boundary for River Rch & Prof#=Clear Creek T 13,Reach-1,3
Up Type=0
Dn Type=3
Dn Slope=0.005
Boundary for River Rch & Prof#=Clear Creek T 13,Reach-1,4
Up Type=0
Dn Type=3
Dn Slope=0.005
Boundary for River Rch & Prof#=Clear Creek T 13,Reach-1,5
Up Type=0
Dn Type=3
Dn Slope=0.005
Boundary for River Rch & Prof#=Clear Creek T 13,Reach-1,6
Up Type=0
Dn Type=3
Dn Slope=0.005
Boundary for River Rch & Prof#=Clear Creek T 13,Reach-1,7
Up Type=0
Dn Type=3
Dn Slope=0.005

--- Clear Creek T 13.g01 (geometry) ---

Geom Title=Existing Conditions

River Reach=Clear Creek T 13,Reach-1
Reach XY= 30
      2765526.00      6808711.00      2765328.26      6808305.06
      2765324.78      6808121.51      2765275.50      6808021.17
      2765325.63      6807776.27      2765185.32      6807567.66
      2765214.76      6807501.00      2765032.74      6807320.13
      2764970.11      6807358.63      2764877.59      6807357.32
      2764678.42      6807216.54      2764573.56      6807205.48
      2764479.46      6807109.51      2764478.37      6807016.88
      2764518.26      6806957.35      2764430.79      6806905.35
      2764427.35      6806867.25      2764550.08      6806788.14
      2764575.32      6806721.75      2764434.00      6806514.33
      2764467.97      6806461.00      2764434.54      6806407.67
      2764468.22      6806361.10      2764427.38      6806300.56
      2764424.34      6806122.83      2764335.23      6806067.93
      2764367.98      6806007.68      2764281.53      6805913.44
      2764272.61      6805812.41      2764226.00      6805761.00

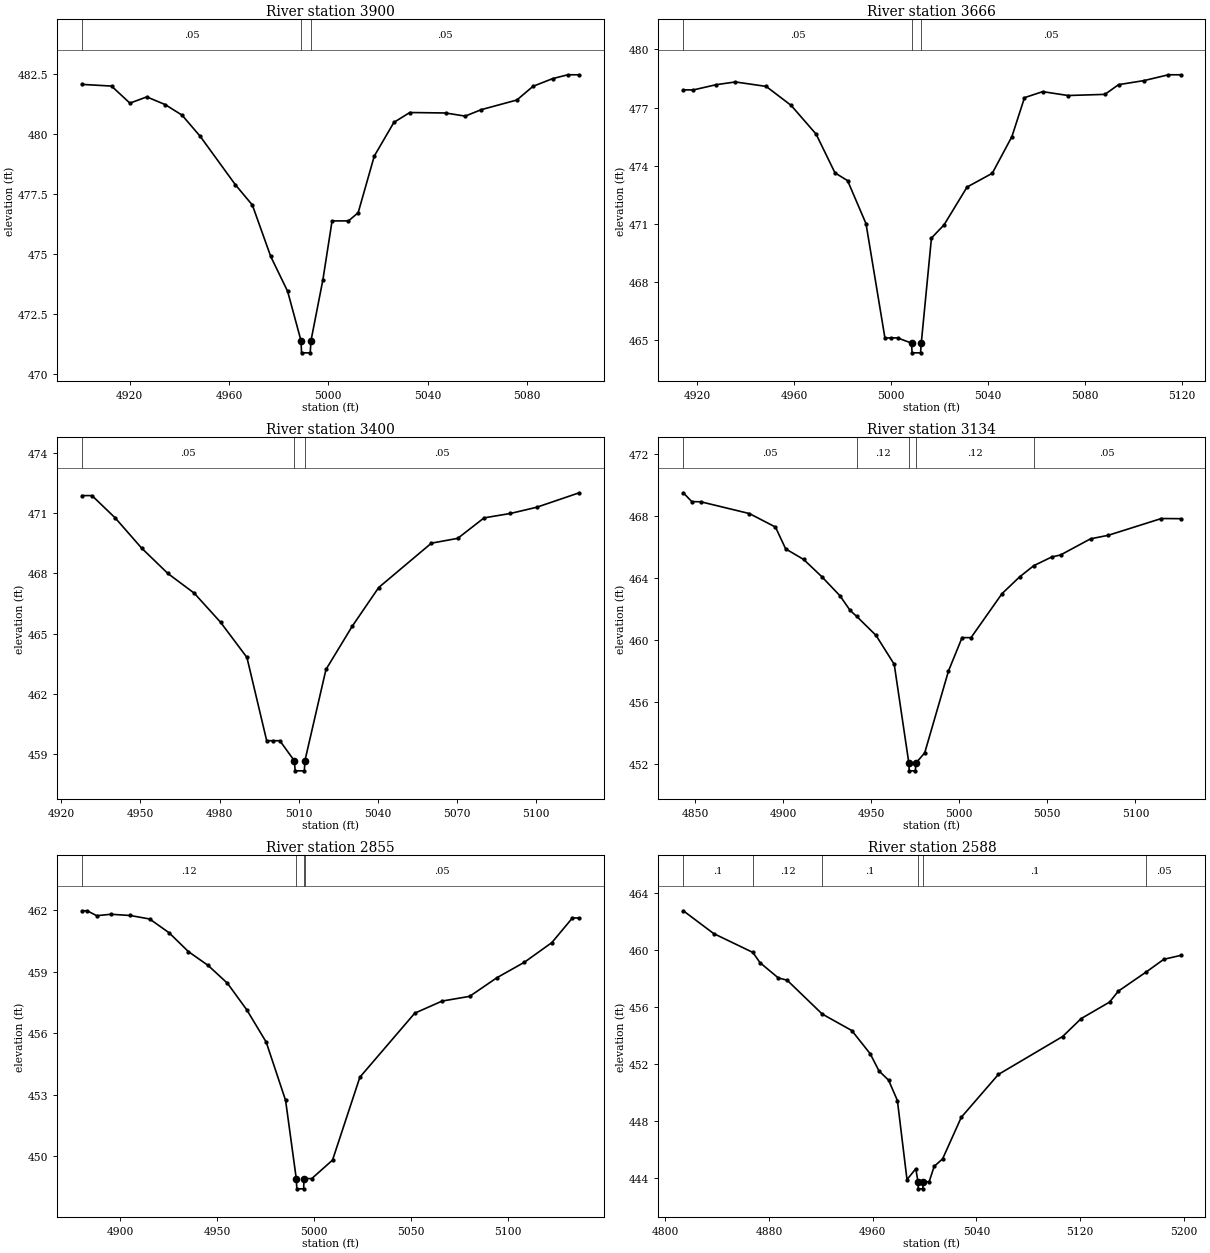
Type RM Length L Ch R = 1,3900,234,234,234
BEGIN DESCRIPTION:
Clear Creek T 13 11.0
END DESCRIPTION:
XS GIS Cut Line= 3
      2765552.51      6808540.48      2765476.00      6808611.00
      2765401.53      6808671.82
#Sta/Elev= 30
  4900.8  482.05  4912.7  481.98  4920.1  481.27  4926.9  481.53  4934.3  481.21
  4941.1  480.77  4948.4  479.89  4962.6  477.87  4969.4  477.03  4976.8  474.89
  4983.6  473.44  4989.0  471.38  4989.2  470.88  4992.7  470.88  4993.0  471.38
  4997.8  473.92  5001.5  476.37  5008.1  476.37  5012.0  476.71  5018.5  479.07
  5026.4  480.47  5032.8  480.88  5047.2  480.86  5055.1  480.73  5061.6  481.00
  5075.9  481.40  5082.4  481.97  5090.3  482.29  5096.4  482.45  5101.0  482.45
#Mann=3,-1,0
  4900.8    0.05       0  4989.0    0.04       0  4993.0    0.05       0
Bank Sta=4989,4993
Exp/Cntr=0.3,0.1

Type RM Length L Ch R = 1,3666,266,266,266
BEGIN DESCRIPTION:
Clear Creek T 13 10.0
END DESCRIPTION:
XS GIS Cut Line= 3
      2765459.17      6808390.09      2765376.00      6808411.00
      2765261.50      6808444.99
#Sta/Elev= 30
  4914.2  477.91  4918.4  477.91  4927.8  478.18  4935.7  478.32  4948.4  478.09
  4958.7  477.11  4969.0  475.63  4976.8  473.63  4982.0  473.23  4989.6  471.01
  4997.4  465.12  5000.0  465.12  5002.6  465.12  5008.4  464.85  5008.6  464.35
  5012.1  464.35  5012.4  464.85  5016.6  470.27  5021.8  470.95  5031.3  472.90
  5041.7  473.61  5049.8  475.50  5055.0  477.51  5062.5  477.82  5073.0  477.62
  5088.2  477.68  5093.8  478.18  5104.3  478.39  5114.4  478.69  5119.4  478.69
#Mann=3,-1,0
  4914.2    0.05       0  5008.4    0.04       0  5012.4    0.05       0
Bank Sta=5008.4,5012.4
Exp/Cntr=0.3,0.1

Type RM Length L Ch R = 1,3400,266,266,266
BEGIN DESCRIPTION:
Clear Creek T 13 9.0
END DESCRIPTION:
XS GIS Cut Line= 3
      2765398.58      6808162.60      2765326.00      6808161.00
      2765209.92      6808163.12
#Sta/Elev= 24
  4927.8  471.88  4931.6  471.88  4940.4  470.77  4950.4  469.27  4960.4  468.00
  4970.4  467.02  4980.4  465.57  4990.4  463.82  4997.9  459.67  5000.4  459.67
  5002.9  459.67  5008.4  458.67  5008.7  458.17  5012.2  458.17  5012.4  458.67
  5020.4  463.22  5030.4  465.38  5040.4  467.30  5060.4  469.51  5070.4  469.75
  5080.4  470.77  5090.4  470.99  5100.4  471.30  5116.5  472.02
#Mann=3,-1,0
  4927.8    0.05       0  5008.4    0.05       0  5012.4    0.05       0
Bank Sta=5008.4,5012.4
Exp/Cntr=0.3,0.1

Type RM Length L Ch R = 1,3134,279,279,279
BEGIN DESCRIPTION:
Clear Creek T 13 8.0
END DESCRIPTION:
XS GIS Cut Line= 3
      2765432.52      6807947.82      2765276.00      6807911.00
      2765155.17      6807922.83
#Sta/Elev= 30
  4843.4  469.47  4848.2  468.90  4853.3  468.89  4880.9  468.13  4895.7  467.26
  4901.5  465.85  4911.7  465.17  4922.0  464.06  4932.3  462.83  4938.1  461.88
  4941.8  461.50  4952.8  460.27  4963.1  458.41  4971.4  452.04  4971.6  451.54
  4975.1  451.54  4975.4  452.04  4980.4  452.70  4993.9  457.98  5001.6  460.13
  5006.7  460.13  5024.3  462.97  5034.3  464.05  5042.3  464.77  5052.5  465.33
  5057.5  465.46  5074.5  466.50  5084.6  466.73  5114.7  467.81  5125.6  467.80
#Mann=5,-1,0
  4843.4    0.05       0  4941.8    0.12       0  4971.4    0.07       0
  4975.4    0.12       0  5042.3    0.05       0
Bank Sta=4971.4,4975.4
Exp/Cntr=0.3,0.1

Type RM Length L Ch R = 1,2855,267,267,267
BEGIN DESCRIPTION:
Clear Creek T 13 7.0
END DESCRIPTION:
XS GIS Cut Line= 3
      2765390.89      6807666.24      2765276.00      6807661.00
      2765176.02      6807760.98
#Sta/Elev= 30
  4880.2  461.97  4882.9  461.97  4887.8  461.73  4895.1  461.80  4905.1  461.74
  4915.1  461.57  4925.1  460.90  4935.1  459.98  4945.2  459.31  4955.2  458.44
  4965.2  457.14  4975.2  455.57  4985.2  452.73  4990.7  448.92  4991.0  448.42
  4994.5  448.42  4994.7  448.92  4995.2  448.92  4995.3  448.92  4998.7  448.92
  5009.4  449.82  5023.5  453.86  5051.8  456.98  5065.9  457.57  5080.1  457.80
  5094.2  458.71  5108.3  459.46  5122.5  460.42  5133.1  461.62  5136.6  461.62
#Mann=4,-1,0
  4880.2    0.12       0  4990.7    0.05       0  4994.7    0.12       0
  4995.3    0.05       0
Bank Sta=4990.7,4994.7
Exp/Cntr=0.3,0.1

Type RM Length L Ch R = 1,2588,271,271,271
BEGIN DESCRIPTION:
Clear Creek T 13 6.0
END DESCRIPTION:
XS GIS Cut Line= 3
      2765302.25      6807323.78      2765176.00      6807461.00
      2765050.65      6807613.28
#Sta/Elev= 30
  4813.9  462.78  4837.3  461.18  4867.6  459.85  4873.1  459.13  4887.2  458.06
  4894.0  457.90  4921.1  455.52  4943.9  454.36  4958.1  452.73  4964.9  451.52
  4972.3  450.87  4979.1  449.44  4986.5  443.88  4993.3  444.64  4995.0  443.73
  4995.2  443.23  4998.7  443.23  4999.0  443.73  5003.6  443.73  5007.5  444.81
  5014.0  445.34  5028.4  448.26  5057.0  451.27  5106.6  453.94  5120.9  455.20
  5142.8  456.36  5149.6  457.13  5171.3  458.49  5184.7  459.37  5197.6  459.64
#Mann=6,-1,0
  4813.9     0.1       0  4867.6    0.12       0  4921.1     0.1       0
  4995.0    0.07       0  4999.0     0.1       0  5171.3    0.05       0
Bank Sta=4995,4999
Exp/Cntr=0.3,0.1

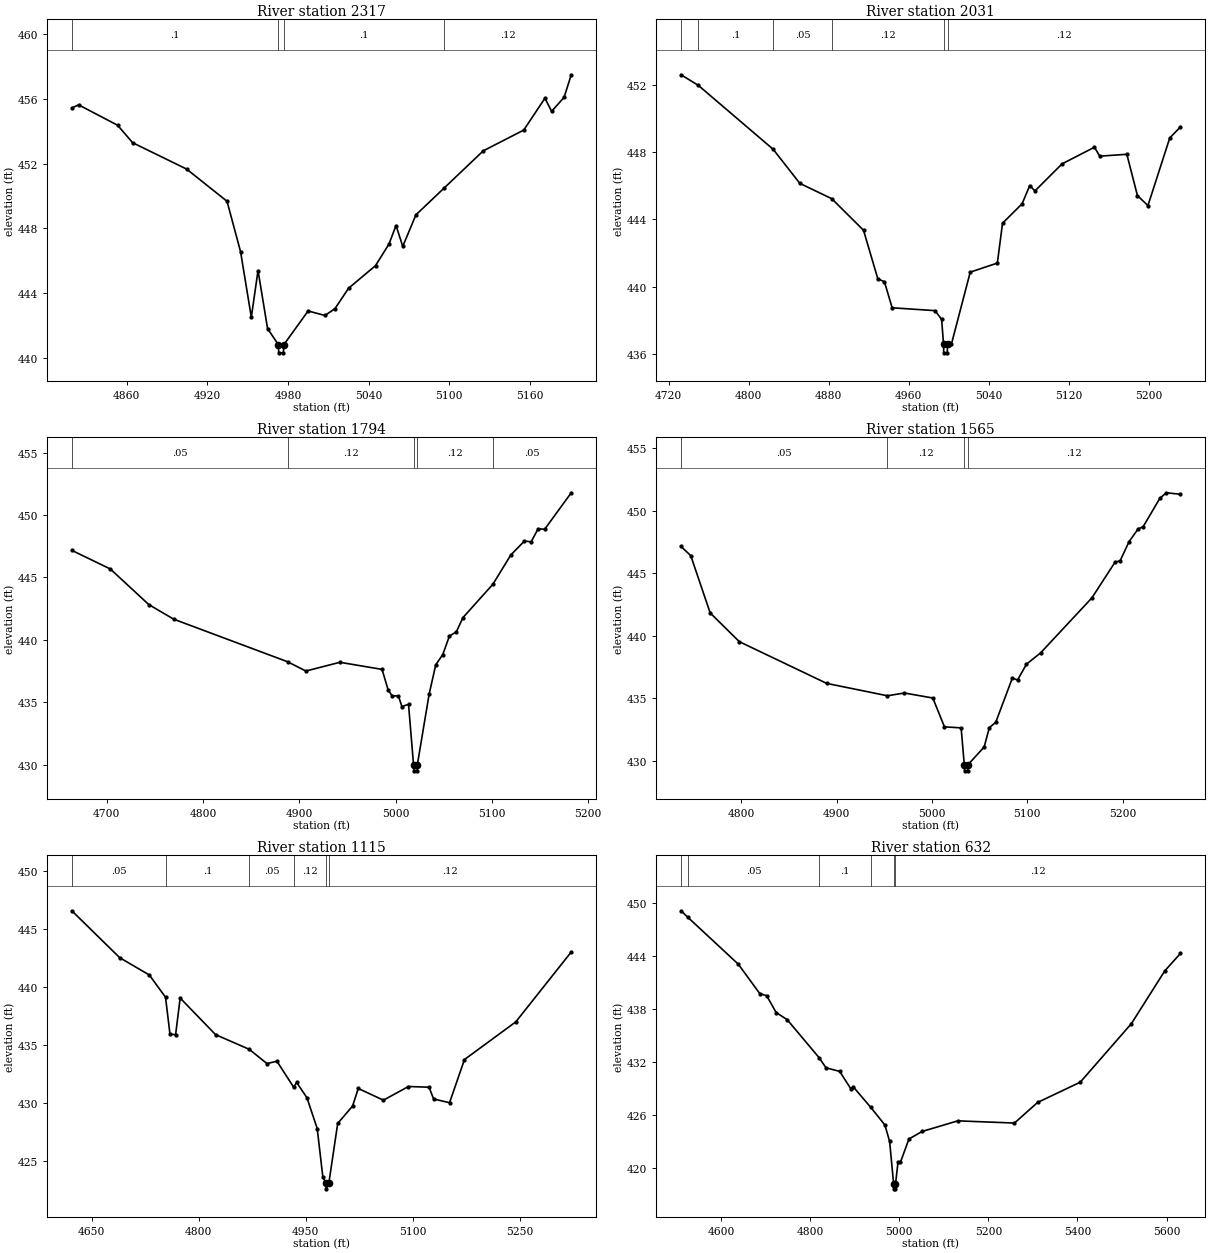
Type RM Length L Ch R = 1,2317,286,286,286
BEGIN DESCRIPTION:
Clear Creek T 13 5.0
END DESCRIPTION:
XS GIS Cut Line= 3
      2764994.85      6807175.95      2764976.00      6807361.00
      2764959.31      6807546.24
#Sta/Elev= 30
  4819.0  455.44  4824.1  455.63  4853.1  454.37  4864.3  453.29  4904.5  451.66
  4934.6  449.67  4944.7  446.55  4952.7  442.50  4957.7  445.39  4964.8  441.80
  4972.9  440.80  4973.1  440.30  4976.6  440.30  4976.9  440.80  4995.0  442.89
  5007.5  442.61  5015.0  443.03  5025.1  444.29  5045.2  445.69  5055.2  447.02
  5060.5  448.17  5065.5  446.88  5075.3  448.83  5096.1  450.47  5125.5  452.79
  5155.6  454.07  5171.4  456.04  5176.4  455.23  5185.7  456.10  5191.0  457.49
#Mann=4,-1,0
  4819.0     0.1       0  4972.9    0.07       0  4976.9     0.1       0
  5096.1    0.12       0
Bank Sta=4972.9,4976.9
Exp/Cntr=0.3,0.1

Type RM Length L Ch R = 1,2031,237,237,237
BEGIN DESCRIPTION:
Clear Creek T 13 4.0
END DESCRIPTION:
XS GIS Cut Line= 3
      2764930.84      6807088.62      2764726.00      6807261.00
      2764656.44      6807481.99
#Sta/Elev= 30
  4732.3  452.60  4749.6  451.97  4824.4  448.17  4851.1  446.14  4883.0  445.23
  4914.8  443.35  4929.1  440.46  4935.7  440.29  4943.4  438.74  4986.3  438.57
  4992.9  438.05  4994.8  436.56  4995.0  436.06  4998.5  436.06  4998.8  436.56
  5002.6  436.56  5021.5  440.86  5048.6  441.40  5053.8  443.77  5073.4  444.93
  5081.0  446.01  5086.2  445.69  5113.3  447.30  5145.7  448.29  5151.0  447.76
  5178.1  447.87  5188.7  445.41  5199.2  444.82  5221.0  448.84  5231.7  449.50
#Mann=6,-1,0
  4732.3    0.05       0  4749.6     0.1       0  4824.4    0.05       0
  4883.0    0.12       0  4994.8    0.07       0  4998.8    0.12       0
Bank Sta=4994.8,4998.8
Exp/Cntr=0.3,0.1

Type RM Length L Ch R = 1,1794,229,229,229
BEGIN DESCRIPTION:
Clear Creek T 13 3.0
END DESCRIPTION:
XS GIS Cut Line= 4
      2764825.96      6807061.00      2764669.16      6807053.64
      2764526.00      6807161.00      2764393.36      6807287.20
#Sta/Elev= 30
  4663.6  447.17  4703.6  445.68  4743.6  442.83  4769.5  441.66  4887.9  438.25
  4906.8  437.51  4942.2  438.21  4986.0  437.64  4992.2  436.03  4996.4  435.52
  5003.0  435.52  5006.6  434.67  5013.5  434.84  5018.7  430.02  5019.0  429.52
  5022.5  429.52  5022.7  430.02  5034.9  435.65  5041.8  438.01  5049.1  438.83
  5056.0  440.31  5063.2  440.65  5070.1  441.79  5101.2  444.46  5119.8  446.80
  5134.0  447.92  5140.9  447.85  5148.1  448.89  5155.0  448.86  5182.6  451.78
#Mann=5,-1,0
  4663.6    0.05       0  4887.9    0.12       0  5018.7    0.07       0
  5022.7    0.12       0  5101.2    0.05       0
Bank Sta=5018.7,5022.7
Exp/Cntr=0.3,0.1

Type RM Length L Ch R = 1,1565,450,450,450
BEGIN DESCRIPTION:
Clear Creek T 13 2.0
END DESCRIPTION:
XS GIS Cut Line= 3
      2764775.97      6806911.01      2764526.00      6806961.00
      2764275.98      6807061.01
#Sta/Elev= 30
  4736.6  447.15  4746.8  446.42  4767.2  441.83  4797.8  439.53  4889.5  436.19
  4953.2  435.20  4971.1  435.42  5000.9  435.02  5013.1  432.71  5030.6  432.63
  5033.9  429.69  5034.2  429.19  5037.7  429.19  5037.9  429.69  5054.8  431.10
  5060.2  432.65  5066.9  433.07  5084.4  436.62  5089.8  436.46  5099.2  437.73
  5114.0  438.63  5167.9  443.04  5192.1  445.89  5197.5  446.01  5206.9  447.54
  5216.3  448.55  5221.7  448.74  5239.2  451.01  5246.0  451.45  5260.8  451.33
#Mann=4,-1,0
  4736.6    0.05       0  4953.2    0.12       0  5033.9    0.07       0
  5037.9    0.12       0
Bank Sta=5033.9,5037.9
Exp/Cntr=0.3,0.1

Type RM Length L Ch R = 1,1115,483,483,483
BEGIN DESCRIPTION:
Mapping XS cafdd9f8
END DESCRIPTION:
XS GIS Cut Line= 2
      2764829.07      6806430.60      2764285.88      6806871.02
#Sta/Elev= 30
  4622.3  446.59  4689.3  442.54  4730.9  441.04  4753.5  439.12  4759.7  435.95
  4767.6  435.88  4774.0  439.05  4823.6  435.89  4870.8  434.62  4895.5  433.39
  4909.5  433.59  4932.8  431.36  4937.1  431.76  4951.5  430.44  4965.9  427.78
  4973.8  423.58  4978.2  423.07  4978.5  422.57  4982.2  423.07  4994.6  428.22
  5015.4  429.72  5023.4  431.24  5058.6  430.23  5093.7  431.41  5122.5  431.35
  5128.9  430.33  5151.2  430.01  5172.1  433.74  5243.9  436.99  5321.6  443.03
#Mann=6,-1,0
  4622.3    0.05       0  4753.5     0.1       0  4870.8    0.05       0
  4932.8    0.12       0  4978.2    0.07       0  4982.2    0.12       0
Bank Sta=4978.2,4982.2
Exp/Cntr=0.3,0.1

Type RM Length L Ch R = 1,632,0,0,0
BEGIN DESCRIPTION:
Clear Creek T 13 1.0
END DESCRIPTION:
XS GIS Cut Line= 3
      2764887.07      6806106.43      2764425.60      6806271.20
      2764262.10      6806880.86
#Sta/Elev= 30
  4510.0  449.16  4524.7  448.45  4638.6  443.11  4686.7  439.79  4702.3  439.54
  4723.5  437.64  4748.3  436.83  4820.2  432.51  4835.4  431.38  4866.2  430.97
  4891.7  428.96  4897.0  429.20  4936.1  426.89  4967.7  424.90  4978.3  423.04
  4987.4  418.17  4987.7  417.67  4991.2  417.67  4991.4  418.17  4997.1  420.67
  5002.5  420.67  5021.7  423.32  5051.4  424.17  5131.4  425.37  5258.6  425.12
  5310.4  427.45  5406.3  429.75  5521.1  436.38  5596.0  442.35  5631.2  444.33
#Mann=6,-1,0
  4510.0    0.12       0  4524.7    0.05       0  4820.2     0.1       0
  4936.1    0.12       0  4987.4    0.07       0  4991.4    0.12       0
Bank Sta=4987.4,4991.4
Exp/Cntr=0.3,0.1

Chan Stop Cuts=-1