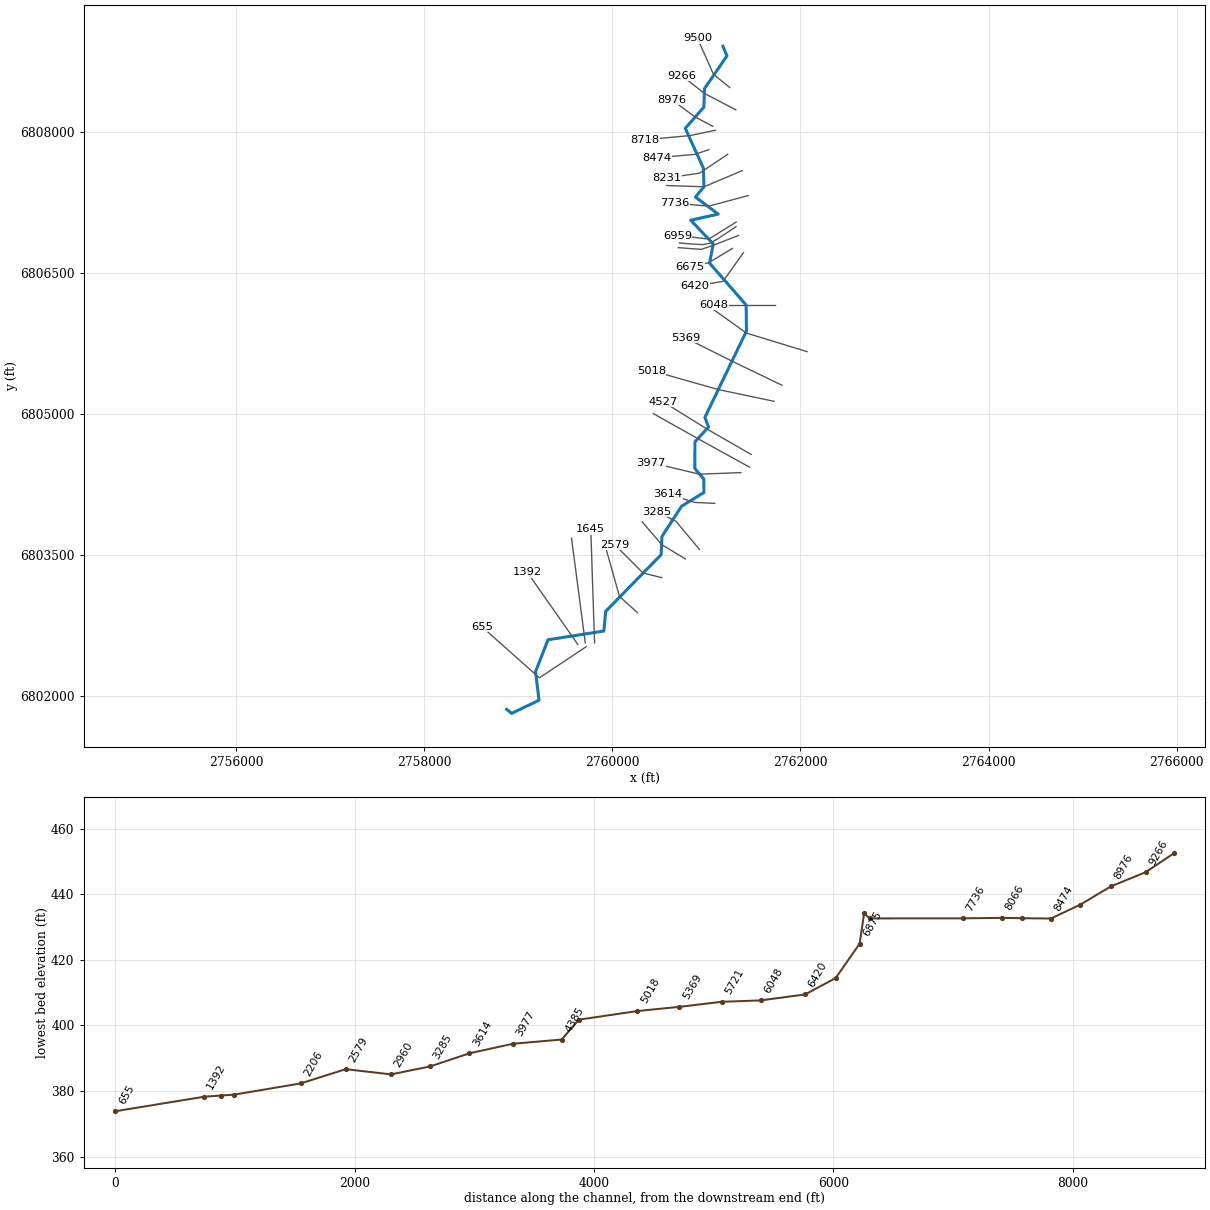
--- Clear Creek T 14.prj (project) ---

Proj Title=Clear Creek T 14 Base Level Engineering
Current Plan=p01
Default Exp/Contr=0.3,0.1
English Units
Geom File=g01
Flow File=f01
Plan File=p01
BEGIN DESCRIPTION:
Clear Creek T 14
END DESCRIPTION:

--- Clear Creek T 14.p01 (plan) ---

Plan Title=Multiple Run
Short Identifier=Multiple
Geom File=g01
Flow File=f01
Subcritical Flow
K Sum by GR= 0
Std Step Tol= 0.01
Critical Tol= 0.01
Num of Std Step Trials= 20
Max Error Tol= 0.3
Flow Tol Ratio= 0.001
Split Flow NTrial= 30
Split Flow Tol= 0.02
Split Flow Ratio= 0.02
Log Output Level= 0
Friction Slope Method= 1
Unsteady Friction Slope Method= 2
Unsteady Bridges Friction Slope Method= 1
Parabolic Critical Depth
Global Vel Dist=  1 , 1 , 1
Global Log Level= 0
CheckData=True
Encroach Param= -1, 0, 0, 0
BEGIN DESCRIPTION:
Multiple Run
END DESCRIPTION:

--- Clear Creek T 14.f01 (steady flow) ---

Flow Title=Multiple
Number of Profiles=7
Profile Names=10-year,25-year,50-year,1pct_min,100-year,1pct_plu,500-year
River Rch & RM= Clear Creek T 14,Reach-1,9500
     294     381     450     265     528    1054     729
River Rch & RM= Clear Creek T 14,Reach-1,6959
     396     523     624     371     741    1478    1044
River Rch & RM= Clear Creek T 14,Reach-1,4527
     550     740     894     537    1072    2139    1544
Boundary for River Rch & Prof#=Clear Creek T 14,Reach-1,1
Up Type=0
Dn Type=3
Dn Slope=0.005
Boundary for River Rch & Prof#=Clear Creek T 14,Reach-1,2
Up Type=0
Dn Type=3
Dn Slope=0.005
Boundary for River Rch & Prof#=Clear Creek T 14,Reach-1,3
Up Type=0
Dn Type=3
Dn Slope=0.005
Boundary for River Rch & Prof#=Clear Creek T 14,Reach-1,4
Up Type=0
Dn Type=3
Dn Slope=0.005
Boundary for River Rch & Prof#=Clear Creek T 14,Reach-1,5
Up Type=0
Dn Type=3
Dn Slope=0.005
Boundary for River Rch & Prof#=Clear Creek T 14,Reach-1,6
Up Type=0
Dn Type=3
Dn Slope=0.005
Boundary for River Rch & Prof#=Clear Creek T 14,Reach-1,7
Up Type=0
Dn Type=3
Dn Slope=0.005

--- Clear Creek T 14.g01 (geometry) ---

Geom Title=Existing Conditions

River Reach=Clear Creek T 14,Reach-1
Reach XY= 30
      2761176.00      6808911.00      2761218.15      6808807.72
      2760979.55      6808459.53      2760972.46      6808262.46
      2760775.44      6808038.20      2760967.99      6807614.33
      2760973.90      6807416.48      2760883.49      6807307.41
      2761125.64      6807125.94      2760832.98      6807061.28
      2761072.54      6806809.50      2761033.48      6806604.94
      2761422.63      6806159.27      2761426.12      6805883.70
      2760983.84      6804964.40      2761022.84      6804862.65
      2760878.17      6804705.56      2760877.06      6804421.44
      2760972.46      6804309.53      2760973.85      6804166.44
      2760736.36      6804021.16      2760527.87      6803699.85
      2760518.19      6803504.81      2759929.26      6802902.98
      2759909.76      6802693.77      2759315.82      6802600.68
      2759183.53      6802261.01      2759220.66      6801958.26
      2758929.33      6801818.27      2758876.00      6801861.00

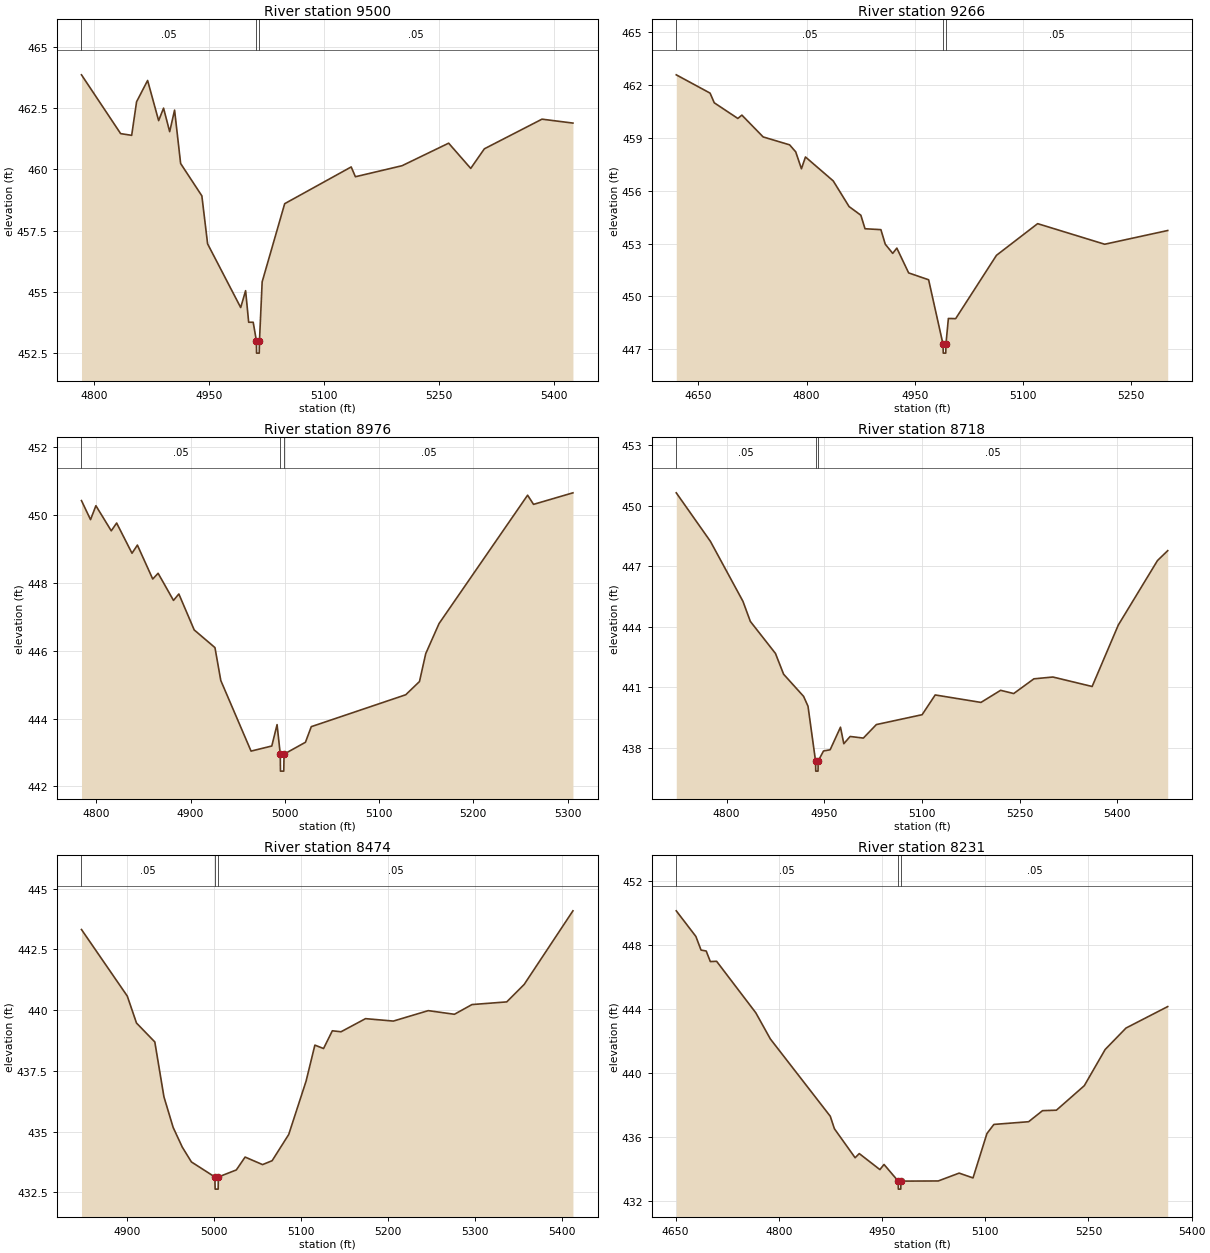
Type RM Length L Ch R = 1,9500,234,234,234
BEGIN DESCRIPTION:
Clear Creek T 14 24.0
END DESCRIPTION:
XS GIS Cut Line= 3
      2761248.09      6808471.71      2761076.00      6808611.00
      2760905.42      6808994.80
#Sta/Elev= 30
  4783.2  463.86  4834.3  461.46  4848.7  461.39  4855.1  462.76  4869.5  463.63
  4883.9  461.99  4890.3  462.50  4898.3  461.54  4904.7  462.42  4912.6  460.24
  4940.3  458.92  4947.8  456.96  4991.0  454.36  4997.4  455.05  5001.4  453.76
  5007.3  453.76  5011.5  453.00  5011.7  452.50  5015.2  452.50  5015.5  453.00
  5019.0  455.41  5048.4  458.60  5135.2  460.10  5140.7  459.70  5201.6  460.15
  5262.4  461.07  5291.2  460.04  5309.0  460.84  5384.2  462.05  5424.6  461.89
#Mann=3,-1,0
  4783.2    0.05       0  5011.5    0.05       0  5015.5    0.05       0
Bank Sta=5011.5,5015.5
Exp/Cntr=0.3,0.1

Type RM Length L Ch R = 1,9266,290,290,290
BEGIN DESCRIPTION:
Clear Creek T 14 23.0
END DESCRIPTION:
XS GIS Cut Line= 3
      2761312.71      6808234.31      2760976.00      6808411.00
      2760739.84      6808598.19
#Sta/Elev= 30
  4619.2  462.59  4666.1  461.55  4671.9  461.00  4704.6  460.11  4710.2  460.30
  4739.7  459.06  4776.4  458.61  4784.9  458.21  4792.8  457.25  4798.4  457.92
  4836.9  456.56  4858.9  455.10  4875.2  454.61  4881.0  453.84  4903.0  453.79
  4909.1  452.96  4919.4  452.44  4925.1  452.74  4941.5  451.33  4969.2  450.94
  4989.2  447.27  4989.5  446.77  4993.0  446.77  4993.2  447.27  4996.6  448.74
  5006.7  448.73  5063.3  452.33  5120.4  454.13  5213.4  452.96  5300.8  453.74
#Mann=3,-1,0
  4619.2    0.05       0  4989.2    0.04       0  4993.2    0.05       0
Bank Sta=4989.2,4993.2
Exp/Cntr=0.3,0.1

Type RM Length L Ch R = 1,8976,258,258,258
BEGIN DESCRIPTION:
Clear Creek T 14 22.0
END DESCRIPTION:
XS GIS Cut Line= 3
      2761066.52      6808059.89      2760876.00      6808161.00
      2760630.60      6808343.32
#Sta/Elev= 30
  4784.3  450.42  4793.9  449.86  4799.6  450.27  4815.9  449.53  4821.6  449.76
  4837.9  448.87  4843.6  449.11  4859.9  448.11  4865.6  448.28  4881.9  447.48
  4887.6  447.67  4903.9  446.61  4925.9  446.09  4932.1  445.12  4964.2  443.04
  4986.2  443.19  4991.8  443.82  4995.2  442.95  4995.4  442.45  4998.9  442.45
  4999.2  442.95  5021.9  443.30  5028.1  443.76  5128.3  444.70  5142.9  445.09
  5149.5  445.91  5163.7  446.80  5257.6  450.58  5263.9  450.31  5305.7  450.65
#Mann=3,-1,0
  4784.3    0.05       0  4995.2    0.04       0  4999.2    0.05       0
Bank Sta=4995.2,4999.2
Exp/Cntr=0.3,0.1

Type RM Length L Ch R = 1,8718,244,244,244
BEGIN DESCRIPTION:
Clear Creek T 14 21.0
END DESCRIPTION:
XS GIS Cut Line= 3
      2761097.44      6808017.78      2760826.00      6807961.00
      2760350.39      6807916.44
#Sta/Elev= 30
  4722.6  450.65  4775.1  448.24  4825.0  445.27  4836.4  444.27  4875.0  442.68
  4887.5  441.65  4918.2  440.55  4925.0  440.06  4936.6  437.34  4936.9  436.84
  4940.4  436.84  4940.6  437.34  4948.8  437.84  4959.0  437.90  4974.9  439.02
  4980.0  438.20  4989.7  438.56  5010.0  438.48  5030.0  439.15  5100.3  439.64
  5120.4  440.62  5190.7  440.25  5220.9  440.85  5241.0  440.69  5272.0  441.42
  5301.2  441.51  5361.5  441.04  5401.7  444.09  5461.9  447.29  5477.6  447.78
#Mann=3,-1,0
  4722.6    0.05       0  4936.6    0.04       0  4940.6    0.05       0
Bank Sta=4936.6,4940.6
Exp/Cntr=0.3,0.1

Type RM Length L Ch R = 1,8474,243,243,243
BEGIN DESCRIPTION:
Clear Creek T 14 20.0
END DESCRIPTION:
XS GIS Cut Line= 3
      2761026.04      6807811.01      2760876.00      6807761.00
      2760470.12      6807725.42
#Sta/Elev= 30
  4847.5  443.32  4900.2  440.58  4910.8  439.47  4931.9  438.69  4942.4  436.43
  4953.0  435.17  4963.5  434.36  4974.0  433.75  5001.0  433.13  5001.3  432.63
  5004.8  432.63  5005.0  433.13  5025.7  433.42  5035.8  433.95  5055.9  433.64
  5066.9  433.80  5086.0  434.88  5106.0  437.08  5116.1  438.56  5126.1  438.42
  5136.2  439.15  5146.2  439.11  5174.4  439.65  5206.4  439.55  5246.6  439.98
  5276.7  439.83  5296.9  440.23  5336.9  440.34  5357.0  441.06  5413.1  444.09
#Mann=3,-1,0
  4847.5    0.05       0  5001.0   0.035       0  5005.0    0.05       0
Bank Sta=5001,5005
Exp/Cntr=0.3,0.1

Type RM Length L Ch R = 1,8231,165,165,165
BEGIN DESCRIPTION:
Clear Creek T 14 19.0
END DESCRIPTION:
XS GIS Cut Line= 3
      2761225.97      6807760.98      2760926.00      6807561.00
      2760575.97      6807511.00
#Sta/Elev= 30
  4651.1  450.11  4679.6  448.51  4687.1  447.66  4694.6  447.60  4700.6  446.94
  4709.7  446.96  4766.7  443.74  4787.8  442.11  4874.9  437.28  4880.9  436.50
  4911.0  434.69  4917.0  434.95  4947.0  433.95  4953.0  434.27  4973.6  433.23
  4973.8  432.73  4977.3  432.73  4977.6  433.23  5031.8  433.24  5062.1  433.73
  5082.3  433.43  5102.5  436.20  5112.6  436.77  5163.1  436.94  5183.3  437.63
  5203.5  437.66  5244.0  439.19  5274.3  441.45  5304.6  442.79  5365.2  444.13
#Mann=3,-1,0
  4651.1    0.05       0  4973.6    0.04       0  4977.6    0.05       0
Bank Sta=4973.6,4977.6
Exp/Cntr=0.3,0.1

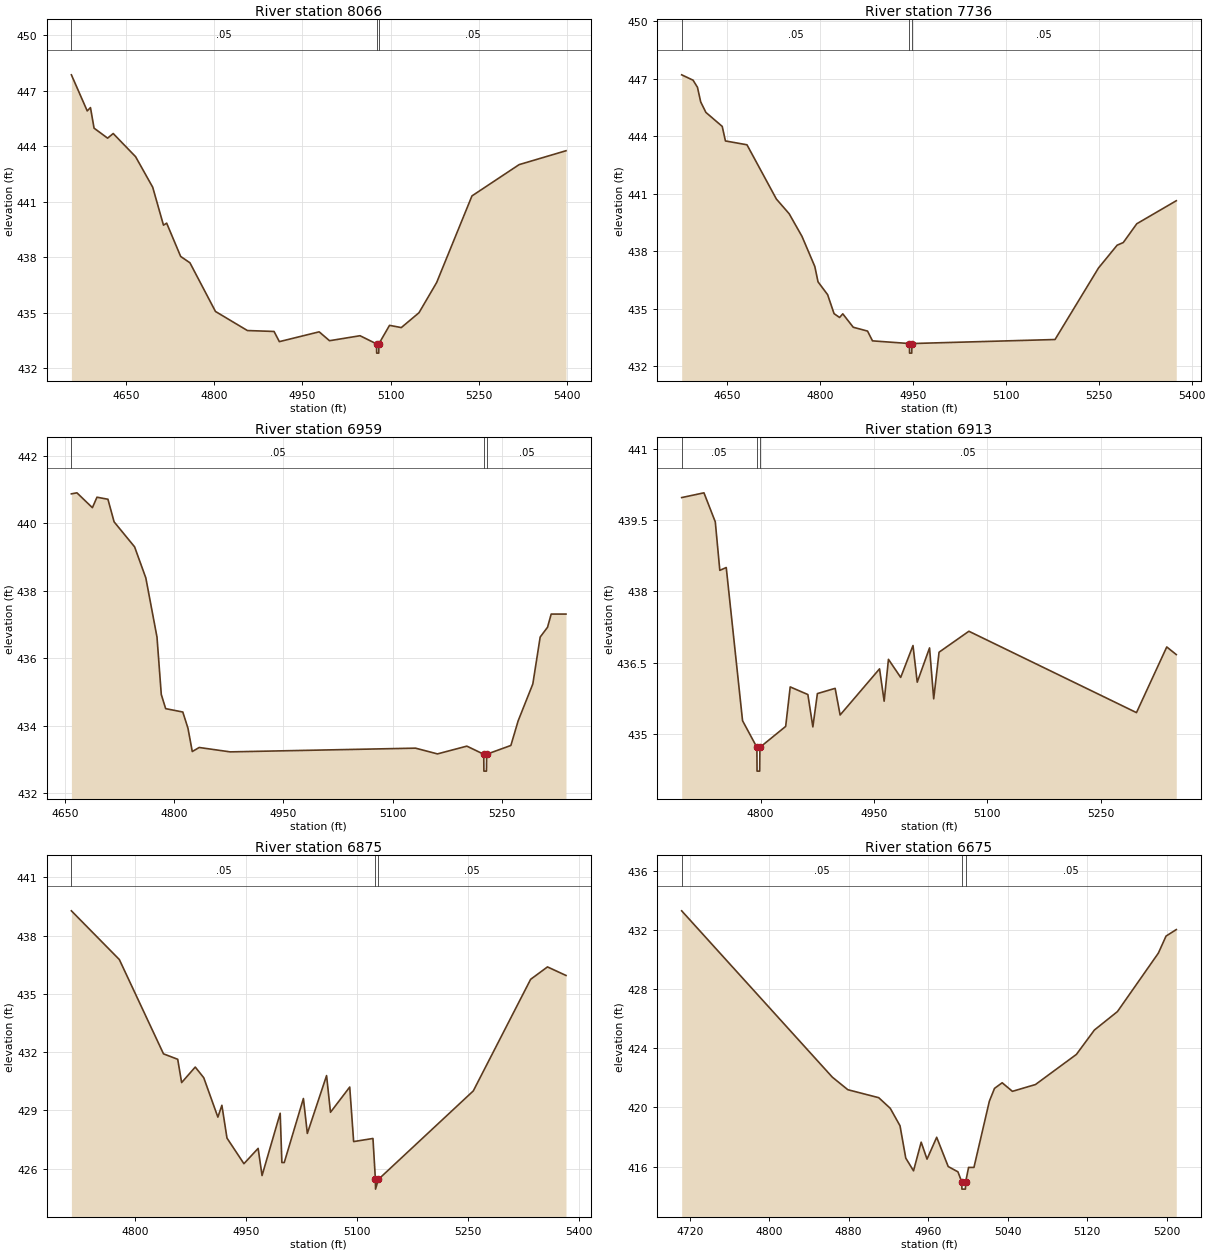
Type RM Length L Ch R = 1,8066,330,330,330
BEGIN DESCRIPTION:
Clear Creek T 14 18.0
END DESCRIPTION:
XS GIS Cut Line= 3
      2761381.46      6807588.31      2760973.90      6807416.48
      2760576.43      6807430.08
#Sta/Elev= 30
  4557.7  447.86  4584.6  445.91  4590.1  446.09  4596.2  444.98  4619.2  444.44
  4628.7  444.69  4666.7  443.44  4695.8  441.79  4714.1  439.74  4719.5  439.85
  4743.3  438.05  4759.0  437.71  4802.4  435.08  4856.6  434.05  4901.9  434.00
  4910.9  433.45  4978.5  433.98  4996.1  433.50  5047.9  433.77  5075.9  433.33
  5076.2  432.83  5079.7  432.83  5079.9  433.33  5098.0  434.33  5118.0  434.21
  5148.0  435.01  5178.0  436.64  5238.0  441.32  5318.1  443.01  5397.7  443.76
#Mann=3,-1,0
  4557.7    0.05       0  5075.9    0.04       0  5079.9    0.05       0
Bank Sta=5075.9,5079.9
Exp/Cntr=0.3,0.1

Type RM Length L Ch R = 1,7736,777,777,777
BEGIN DESCRIPTION:
Clear Creek T 14 17.0
END DESCRIPTION:
XS GIS Cut Line= 3
      2761443.77      6807323.11      2761026.00      6807211.00
      2760660.74      6807241.61
#Sta/Elev= 30
  4576.1  447.21  4594.5  446.93  4601.6  446.56  4606.8  445.80  4615.2  445.25
  4641.6  444.52  4646.8  443.76  4681.6  443.56  4729.1  440.73  4749.8  439.96
  4770.5  438.78  4791.2  437.21  4796.4  436.41  4811.9  435.74  4822.3  434.75
  4831.2  434.55  4836.4  434.74  4853.3  434.04  4876.4  433.84  4884.4  433.33
  4944.1  433.19  4944.3  432.69  4947.8  432.69  4948.1  433.19  5179.3  433.40
  5249.5  437.13  5279.6  438.32  5289.6  438.46  5311.4  439.44  5375.2  440.64
#Mann=3,-1,0
  4576.1    0.05       0  4944.1    0.03       0  4948.1    0.05       0
Bank Sta=4944.1,4948.1
Exp/Cntr=0.3,0.1

Type RM Length L Ch R = 1,6959,46,46,46
BEGIN DESCRIPTION:
Clear Creek T 14 16.0
END DESCRIPTION:
XS GIS Cut Line= 3
      2761315.79      6807041.04      2761026.00      6806861.00
      2760690.82      6806898.24
#Sta/Elev= 30
  4659.1  440.87  4666.7  440.90  4687.9  440.46  4694.2  440.77  4709.2  440.71
  4717.7  440.04  4745.8  439.30  4761.2  438.38  4776.5  436.63  4782.4  434.93
  4788.4  434.51  4811.9  434.41  4819.0  433.93  4824.9  433.24  4834.4  433.36
  4876.9  433.23  5131.1  433.34  5161.2  433.17  5201.5  433.40  5224.7  433.16
  5224.9  432.66  5228.4  432.66  5228.7  433.16  5261.9  433.42  5271.9  434.15
  5292.0  435.24  5302.1  436.63  5312.2  436.92  5317.2  437.31  5337.5  437.31
#Mann=3,-1,0
  4659.1    0.05       0  5224.7    0.03       0  5228.7    0.05       0
Bank Sta=5224.7,5228.7
Exp/Cntr=0.3,0.1

Type RM Length L Ch R = 1,6913,38,38,38
BEGIN DESCRIPTION:
Mapping XS be19bcbc
END DESCRIPTION:
XS GIS Cut Line= 6
      2761315.07      6806992.64      2761115.39      6806859.62
      2761031.20      6806814.27      2760960.91      6806802.16
      2760884.35      6806805.49      2760713.47      6806818.63
#Sta/Elev= 30
  4695.4  439.97  4724.9  440.07  4739.9  439.46  4745.9  438.44  4754.4  438.50
  4776.0  435.28  4795.0  434.72  4795.2  434.22  4798.7  434.22  4799.0  434.72
  4833.1  435.16  4839.1  435.99  4862.5  435.83  4869.1  435.15  4875.1  435.85
  4898.6  435.96  4905.2  435.40  4957.4  436.37  4963.5  435.69  4969.2  436.57
  4985.4  436.19  5001.7  436.86  5007.3  436.09  5023.6  436.81  5029.1  435.74
  5036.2  436.72  5075.7  437.16  5297.6  435.45  5337.7  436.83  5350.3  436.67
#Mann=3,-1,0
  4695.4    0.05       0  4795.0    0.03       0  4799.0    0.05       0
Bank Sta=4795,4799
Exp/Cntr=0.3,0.1

Type RM Length L Ch R = 1,6875,200,200,200
BEGIN DESCRIPTION:
Mapping XS 1def88e1
END DESCRIPTION:
XS GIS Cut Line= 4
      2761341.95      6806899.35      2761076.82      6806795.90
      2760945.55      6806751.13      2760701.03      6806769.40
#Sta/Elev= 30
  4714.3  439.28  4779.1  436.77  4838.8  431.91  4858.0  431.63  4863.3  430.43
  4881.7  431.23  4893.2  430.68  4912.3  428.65  4917.7  429.26  4924.6  427.57
  4947.5  426.25  4966.7  427.04  4972.0  425.64  4996.5  428.85  4998.8  426.31
  5002.0  426.31  5027.9  429.61  5033.2  427.81  5059.2  430.79  5064.5  428.90
  5090.5  430.20  5095.8  427.39  5121.9  427.55  5125.2  425.44  5125.4  424.94
  5129.2  425.44  5257.5  430.00  5335.0  435.75  5357.8  436.39  5382.8  435.95
#Mann=3,-1,0
  4714.3    0.05       0  5125.2    0.03       0  5129.2    0.05       0
Bank Sta=5125.2,5129.2
Exp/Cntr=0.3,0.1

Type RM Length L Ch R = 1,6675,255,255,255
BEGIN DESCRIPTION:
Clear Creek T 14 15.0
END DESCRIPTION:
XS GIS Cut Line= 3
      2761276.02      6806761.01      2761026.00      6806611.00
      2760826.02      6806561.01
#Sta/Elev= 30
  4712.0  433.31  4863.6  422.05  4879.2  421.20  4910.3  420.66  4921.9  419.94
  4931.7  418.76  4937.5  416.57  4945.3  415.71  4953.0  417.65  4958.9  416.50
  4968.6  417.98  4980.2  416.00  4990.0  415.64  4993.8  414.97  4994.0  414.47
  4997.5  414.47  4997.8  414.97  5000.7  415.94  5006.1  415.94  5021.6  420.42
  5026.8  421.29  5034.5  421.67  5044.8  421.09  5068.0  421.55  5109.2  423.59
  5127.3  425.24  5150.5  426.49  5191.7  430.45  5199.4  431.60  5209.7  432.04
#Mann=3,-1,0
  4712.0    0.05       0  4993.8   0.035       0  4997.8    0.05       0
Bank Sta=4993.8,4997.8
Exp/Cntr=0.3,0.1

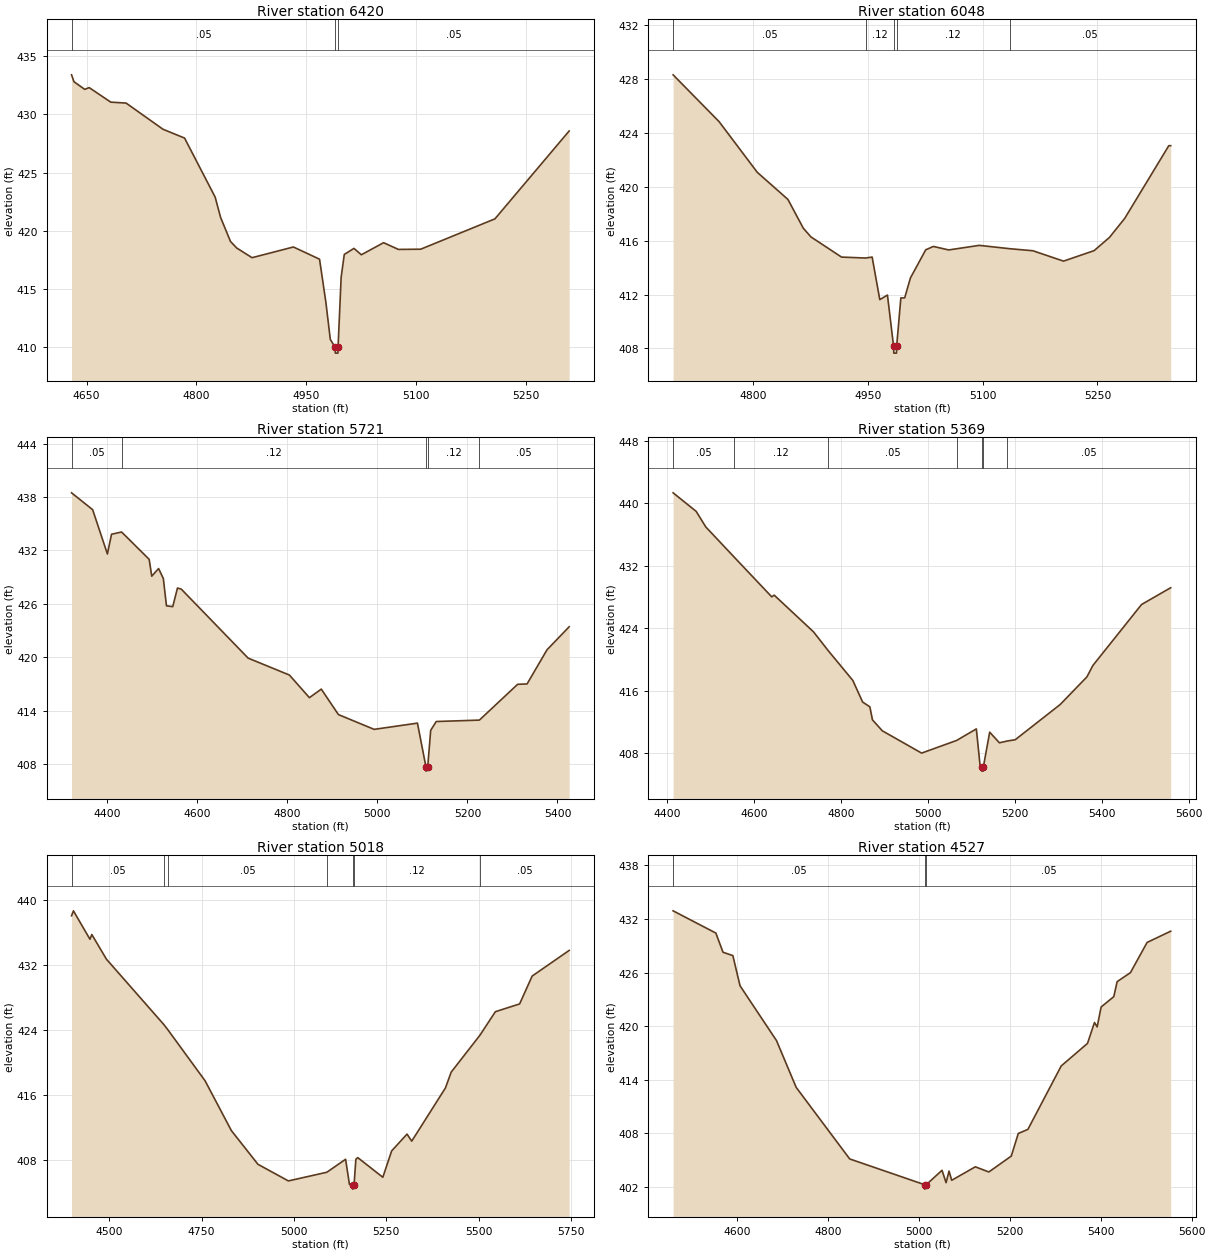
Type RM Length L Ch R = 1,6420,372,372,372
BEGIN DESCRIPTION:
Clear Creek T 14 14.0
END DESCRIPTION:
XS GIS Cut Line= 3
      2761394.27      6806716.71      2761176.00      6806411.00
      2760875.98      6806361.00
#Sta/Elev= 30
  4629.5  433.41  4632.8  432.82  4647.5  432.16  4653.6  432.31  4683.1  431.06
  4704.0  430.98  4754.4  428.73  4783.9  427.97  4825.7  422.89  4833.1  421.15
  4846.6  419.08  4855.2  418.51  4876.1  417.68  4932.6  418.60  4968.3  417.55
  4976.9  413.87  4983.0  410.65  4989.6  409.97  4989.9  409.47  4993.4  409.47
  4993.6  409.97  4997.8  415.99  5002.1  417.96  5015.3  418.48  5025.4  417.93
  5055.8  418.97  5076.1  418.39  5106.5  418.41  5207.9  421.02  5309.3  428.58
#Mann=3,-1,0
  4629.5    0.05       0  4989.6   0.035       0  4993.6    0.05       0
Bank Sta=4989.6,4993.6
Exp/Cntr=0.3,0.1

Type RM Length L Ch R = 1,6048,327,327,327
BEGIN DESCRIPTION:
Clear Creek T 14 13.0
END DESCRIPTION:
XS GIS Cut Line= 3
      2761726.05      6806161.00      2761426.00      6806161.00
      2761076.05      6806161.00
#Sta/Elev= 30
  4695.7  428.31  4755.7  424.84  4805.7  421.07  4845.7  419.06  4865.7  416.93
  4875.7  416.28  4915.7  414.78  4947.2  414.71  4955.7  414.78  4965.7  411.62
  4975.7  411.96  4983.7  408.15  4984.0  407.65  4987.5  407.65  4987.7  408.15
  4993.2  411.75  4998.2  411.75  5005.7  413.23  5025.7  415.32  5035.7  415.57
  5055.7  415.31  5095.7  415.65  5135.6  415.40  5165.7  415.25  5205.7  414.48
  5245.7  415.26  5265.7  416.24  5285.7  417.66  5343.2  423.05  5345.7  423.05
#Mann=5,-1,0
  4695.7    0.05       0  4947.2    0.12       0  4983.7    0.07       0
  4987.7    0.12       0  5135.6    0.05       0
Bank Sta=4983.7,4987.7
Exp/Cntr=0.3,0.1

Type RM Length L Ch R = 1,5721,352,352,352
BEGIN DESCRIPTION:
Clear Creek T 14 12.0
END DESCRIPTION:
XS GIS Cut Line= 3
      2762070.79      6805663.84      2761426.00      6805861.00
      2761075.98      6806111.02
#Sta/Elev= 30
  4321.5  438.47  4368.3  436.58  4401.1  431.60  4410.2  433.82  4432.6  434.07
  4493.8  431.00  4499.5  429.11  4514.7  429.97  4525.2  428.85  4532.2  425.78
  4546.1  425.69  4556.6  427.78  4565.0  427.66  4713.4  419.91  4805.0  418.01
  4849.4  415.47  4875.8  416.43  4913.8  413.57  4993.1  411.91  5089.2  412.61
  5108.0  407.72  5108.3  407.22  5112.0  407.72  5118.6  411.80  5130.9  412.79
  5226.7  412.95  5311.6  416.97  5332.5  417.01  5376.7  420.84  5425.9  423.43
#Mann=5,-1,0
  4321.5    0.05       0  4432.6    0.12       0  5108.0    0.07       0
  5112.0    0.12       0  5226.7    0.05       0
Bank Sta=5108,5112
Exp/Cntr=0.3,0.1

Type RM Length L Ch R = 1,5369,351,351,351
BEGIN DESCRIPTION:
Clear Creek T 14 11.0
END DESCRIPTION:
XS GIS Cut Line= 3
      2761803.78      6805306.61      2761276.00      6805561.00
      2760776.00      6805811.00
#Sta/Elev= 30
  4414.1  441.34  4467.1  438.97  4489.3  436.97  4554.5  433.11  4641.1  428.01
  4646.7  428.23  4737.1  423.53  4771.4  421.09  4827.6  417.30  4850.2  414.53
  4866.8  413.92  4872.8  412.25  4895.4  410.85  4985.9  407.99  5066.4  409.61
  5111.8  411.09  5120.2  406.51  5123.8  406.18  5124.0  405.68  5127.5  405.68
  5127.8  406.18  5142.5  410.67  5164.9  409.31  5183.0  409.54  5201.2  409.70
  5304.6  414.21  5366.1  417.75  5380.1  419.23  5491.9  427.03  5559.0  429.18
#Mann=7,-1,0
  4414.1    0.05       0  4554.5    0.12       0  4771.4    0.05       0
  5066.4    0.12       0  5123.8    0.05       0  5127.8    0.12       0
  5183.0    0.05       0
Bank Sta=5123.8,5127.8
Exp/Cntr=0.3,0.1

Type RM Length L Ch R = 1,5018,491,491,491
BEGIN DESCRIPTION:
Clear Creek T 14 10.0
END DESCRIPTION:
XS GIS Cut Line= 3
      2761719.69      6805135.71      2761126.00      6805261.00
      2760413.80      6805463.15
#Sta/Elev= 30
  4397.9  438.08  4403.0  438.69  4447.7  435.19  4452.8  435.77  4492.4  432.73
  4647.9  424.67  4658.9  424.02  4759.4  417.75  4830.5  411.62  4902.5  407.46
  4984.9  405.41  5089.1  406.48  5139.8  408.08  5150.2  404.98  5158.6  404.90
  5158.8  404.40  5162.6  404.90  5167.6  408.07  5172.8  408.28  5240.6  405.86
  5264.5  409.11  5306.1  411.18  5318.8  410.31  5410.1  416.87  5425.7  418.82
  5503.4  423.36  5545.2  426.26  5610.9  427.22  5644.8  430.65  5745.0  433.81
#Mann=7,-1,0
  4397.9    0.05       0  4647.9    0.12       0  4658.9    0.05       0
  5089.1    0.12       0  5158.6    0.05       0  5162.6    0.12       0
  5503.4    0.05       0
Bank Sta=5158.6,5162.6
Exp/Cntr=0.3,0.1

Type RM Length L Ch R = 1,4527,142,142,142
BEGIN DESCRIPTION:
Clear Creek T 14 9.0
END DESCRIPTION:
XS GIS Cut Line= 3
      2761475.64      6804570.78      2761006.56      6804840.91
      2760535.80      6805132.78
#Sta/Elev= 30
  4458.7  432.92  4552.8  430.43  4568.6  428.28  4590.2  427.91  4606.0  424.53
  4686.4  418.38  4729.6  413.15  4847.4  405.14  5012.0  402.26  5012.2  401.76
  5016.0  402.26  5050.6  403.87  5059.5  402.48  5066.0  403.78  5071.9  402.75
  5123.9  404.26  5153.6  403.68  5203.0  405.46  5218.4  407.99  5239.6  408.45
  5312.9  415.55  5370.8  418.08  5386.1  420.42  5392.0  419.92  5400.7  422.15
  5428.6  423.31  5436.0  424.99  5465.3  426.00  5501.9  429.38  5553.9  430.64
#Mann=3,-1,0
  4458.7    0.05       0  5012.0    0.03       0  5016.0    0.05       0
Bank Sta=5012,5016
Exp/Cntr=0.3,0.1

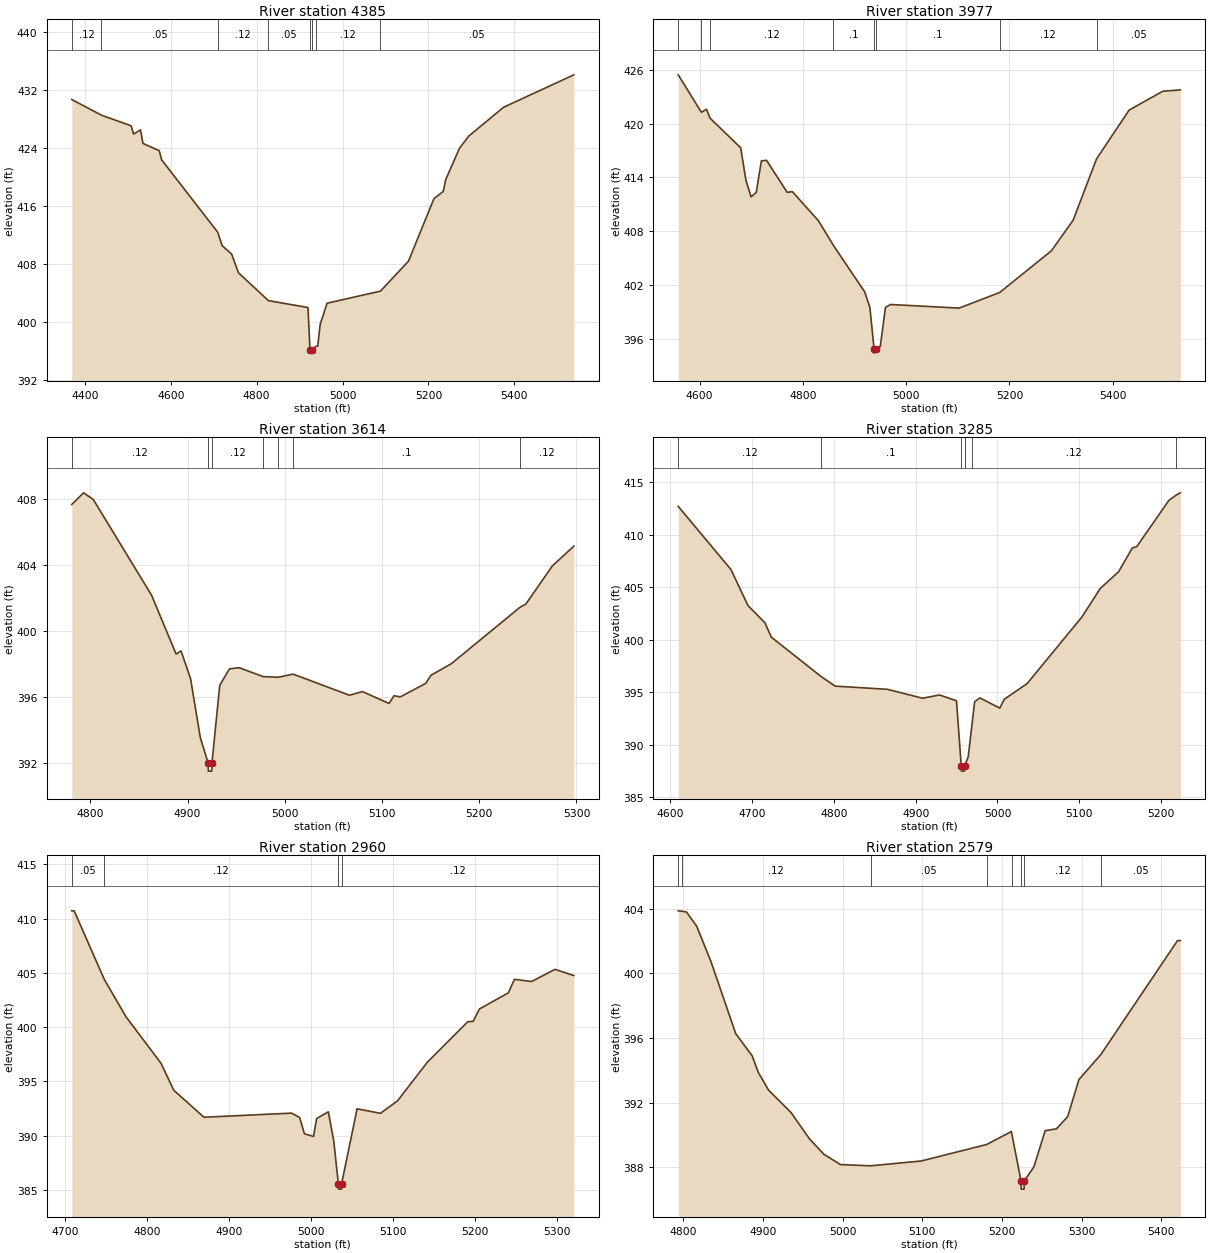
Type RM Length L Ch R = 1,4385,408,408,408
BEGIN DESCRIPTION:
Clear Creek T 14 8.0
END DESCRIPTION:
XS GIS Cut Line= 3
      2761457.31      6804436.58      2760905.51      6804741.20
      2760436.03      6805004.75
#Sta/Elev= 30
  4369.7  430.73  4438.8  428.57  4507.9  427.10  4513.7  425.96  4529.7  426.54
  4535.4  424.67  4573.3  423.67  4579.0  422.39  4709.3  412.42  4719.9  410.54
  4741.7  409.40  4757.7  406.81  4827.4  402.96  4919.5  402.01  4924.2  396.21
  4924.4  395.71  4928.2  396.21  4938.4  396.66  4942.2  396.67  4947.9  399.68
  4964.0  402.60  5088.2  404.27  5153.5  408.41  5212.8  417.05  5234.5  418.04
  5240.3  419.69  5272.2  424.00  5293.8  425.68  5374.8  429.66  5538.4  434.14
#Mann=8,-1,0
  4369.7    0.12       0  4438.8    0.05       0  4709.3    0.12       0
  4827.4    0.05       0  4924.2    0.07       0  4928.2    0.05       0
  4938.4    0.12       0  5088.2    0.05       0
Bank Sta=4924.2,4928.2
Exp/Cntr=0.3,0.1

Type RM Length L Ch R = 1,3977,363,363,363
BEGIN DESCRIPTION:
Clear Creek T 14 7.0
END DESCRIPTION:
XS GIS Cut Line= 3
      2761366.86      6804378.07      2760926.00      6804361.00
      2760409.59      6804484.23
#Sta/Elev= 30
  4558.8  425.44  4603.5  421.27  4613.5  421.60  4620.5  420.60  4679.7  417.31
  4689.8  413.71  4699.8  411.84  4709.8  412.33  4719.8  415.85  4729.8  415.91
  4769.8  412.34  4779.8  412.42  4829.9  409.20  4859.3  406.43  4919.9  401.24
  4929.9  399.50  4937.9  394.92  4938.2  394.42  4941.9  394.92  4950.0  395.16
  4960.0  399.52  4970.0  399.84  5102.7  399.44  5181.2  401.18  5281.4  405.83
  5323.5  409.25  5368.7  416.07  5431.8  421.51  5497.0  423.61  5530.9  423.76
#Mann=8,-1,0
  4558.8    0.12       0  4603.5     0.1       0  4620.5    0.12       0
  4859.3     0.1       0  4937.9    0.07       0  4941.9     0.1       0
  5181.2    0.12       0  5368.7    0.05       0
Bank Sta=4937.9,4941.9
Exp/Cntr=0.3,0.1

Type RM Length L Ch R = 1,3614,329,329,329
BEGIN DESCRIPTION:
Clear Creek T 14 6.0
END DESCRIPTION:
XS GIS Cut Line= 3
      2761088.05      6804050.87      2760876.00      6804061.00
      2760585.56      6804151.15
#Sta/Elev= 30
  4780.9  407.69  4793.0  408.40  4803.0  408.00  4863.0  402.18  4888.2  398.61
  4893.3  398.80  4903.1  397.11  4913.1  393.54  4921.1  392.00  4921.4  391.50
  4924.9  391.50  4925.1  392.00  4933.1  396.71  4943.1  397.71  4953.1  397.78
  4977.7  397.24  4993.3  397.20  5008.6  397.39  5066.5  396.11  5079.9  396.33
  5107.2  395.61  5112.4  396.08  5118.8  396.01  5145.0  396.83  5150.3  397.32
  5171.2  398.02  5241.5  401.43  5248.0  401.65  5275.3  403.97  5297.3  405.16
#Mann=7,-1,0
  4780.9    0.12       0  4921.1    0.07       0  4925.1    0.12       0
  4977.7     0.1       0  4993.3    0.12       0  5008.6     0.1       0
  5241.5    0.12       0
Bank Sta=4921.1,4925.1
Exp/Cntr=0.3,0.1

Type RM Length L Ch R = 1,3285,325,325,325
BEGIN DESCRIPTION:
Clear Creek T 14 5.0
END DESCRIPTION:
XS GIS Cut Line= 3
      2760926.02      6803560.97      2760676.00      6803861.00
      2760475.96      6803961.02
#Sta/Elev= 30
  4609.5  412.70  4674.0  406.69  4694.8  403.26  4715.6  401.62  4723.4  400.25
  4784.2  396.51  4801.5  395.59  4865.3  395.29  4908.3  394.44  4929.1  394.75
  4949.9  394.20  4955.7  388.00  4956.0  387.50  4959.5  387.50  4959.7  388.00
  4964.2  388.84  4969.0  392.04  4972.1  394.10  4978.6  394.47  5002.8  393.50
  5008.4  394.34  5036.4  395.84  5103.5  402.19  5125.8  404.89  5148.2  406.48
  5165.0  408.74  5170.5  408.88  5209.7  413.27  5218.3  413.76  5223.7  413.99
#Mann=6,-1,0
  4609.5    0.12       0  4784.2     0.1       0  4955.7    0.07       0
  4959.7     0.1       0  4969.0    0.12       0  5218.3    0.05       0
Bank Sta=4955.7,4959.7
Exp/Cntr=0.3,0.1

Type RM Length L Ch R = 1,2960,381,381,381
BEGIN DESCRIPTION:
Clear Creek T 14 4.0
END DESCRIPTION:
XS GIS Cut Line= 3
      2760776.01      6803460.99      2760526.00      6803611.00
      2760316.98      6803854.54
#Sta/Elev= 30
  4708.4  410.71  4711.3  410.71  4748.1  404.39  4774.5  400.96  4817.3  396.67
  4832.8  394.19  4869.7  391.70  4976.6  392.08  4986.4  391.67  4992.2  390.18
  5003.3  389.93  5007.1  391.58  5021.4  392.20  5028.0  389.53  5033.6  385.58
  5033.9  385.08  5037.4  385.08  5037.6  385.58  5056.5  392.48  5085.0  392.06
  5105.9  393.22  5142.1  396.76  5191.5  400.50  5198.1  400.53  5205.7  401.67
  5240.9  403.15  5248.5  404.40  5269.4  404.20  5297.9  405.32  5320.9  404.75
#Mann=4,-1,0
  4708.4    0.05       0  4748.1    0.12       0  5033.6    0.07       0
  5037.6    0.12       0
Bank Sta=5033.6,5037.6
Exp/Cntr=0.3,0.1

Type RM Length L Ch R = 1,2579,373,373,373
BEGIN DESCRIPTION:
Clear Creek T 14 3.0
END DESCRIPTION:
XS GIS Cut Line= 3
      2760526.01      6803261.00      2760326.00      6803311.00
      2760026.02      6803610.98
#Sta/Elev= 30
  4793.6  403.86  4797.9  403.84  4803.9  403.79  4816.8  402.91  4834.8  400.71
  4865.8  396.27  4886.4  394.90  4894.1  393.88  4907.0  392.78  4935.3  391.39
  4958.5  389.76  4976.6  388.81  4997.2  388.18  5035.1  388.10  5098.8  388.40
  5181.0  389.42  5211.9  390.22  5212.9  389.97  5224.0  387.16  5224.3  386.66
  5227.8  386.66  5228.0  387.16  5240.2  388.04  5254.3  390.27  5268.5  390.39
  5282.6  391.14  5296.7  393.43  5324.4  394.99  5420.5  402.02  5424.0  402.02
#Mann=8,-1,0
  4793.6    0.05       0  4797.9    0.12       0  5035.1    0.05       0
  5181.0     0.1       0  5212.9    0.12       0  5224.0    0.07       0
  5228.0    0.12       0  5324.4    0.05       0
Bank Sta=5224,5228
Exp/Cntr=0.3,0.1

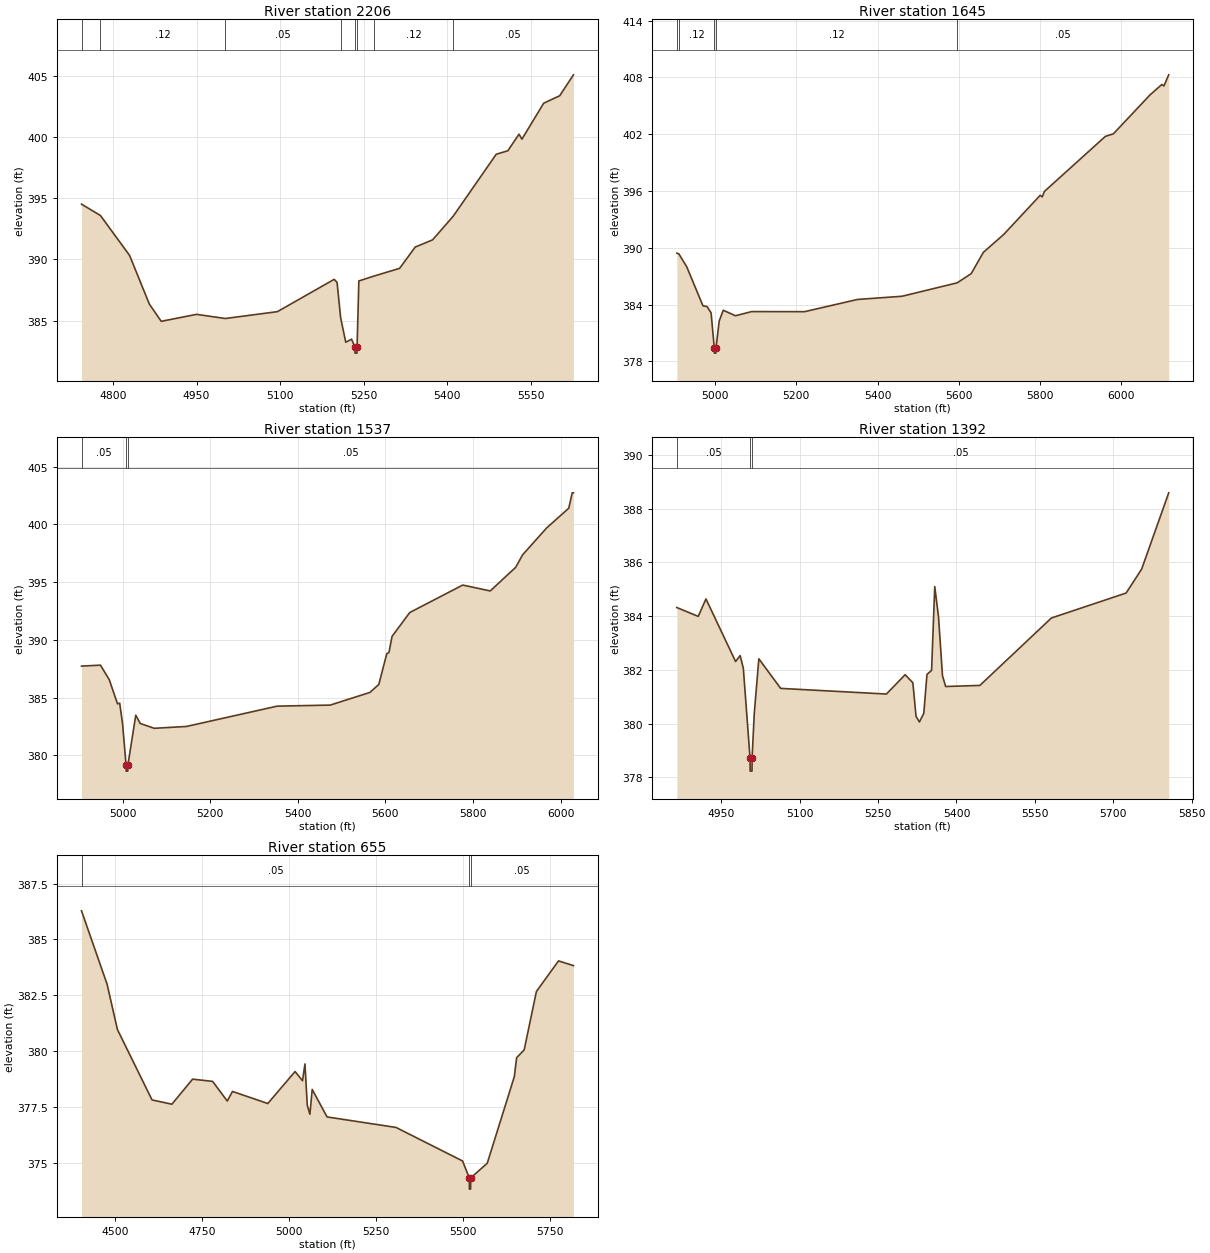
Type RM Length L Ch R = 1,2206,561,561,561
BEGIN DESCRIPTION:
Clear Creek T 14 2.0
END DESCRIPTION:
XS GIS Cut Line= 3
      2760266.54      6802889.55      2760076.00      6803061.00
      2759905.68      6803664.41
#Sta/Elev= 30
  4743.4  394.52  4777.4  393.59  4829.7  390.33  4865.2  386.35  4886.5  384.94
  4950.0  385.51  5001.5  385.17  5095.1  385.73  5197.1  388.37  5202.3  388.12
  5208.7  385.23  5217.9  383.23  5228.3  383.48  5234.2  382.84  5234.5  382.34
  5238.0  382.34  5238.2  382.84  5241.4  388.24  5269.4  388.65  5314.6  389.27
  5342.6  391.01  5373.8  391.60  5410.8  393.53  5488.1  398.60  5508.9  398.88
  5529.0  400.24  5534.2  399.83  5573.3  402.77  5602.1  403.38  5626.7  405.09
#Mann=8,-1,0
  4743.4    0.05       0  4777.4    0.12       0  5001.5    0.05       0
  5208.7     0.1       0  5234.2    0.07       0  5238.2     0.1       0
  5269.4    0.12       0  5410.8    0.05       0
Bank Sta=5234.2,5238.2
Exp/Cntr=0.3,0.1

Type RM Length L Ch R = 1,1645,108,108,108
BEGIN DESCRIPTION:
Mapping XS e4ecd696
END DESCRIPTION:
XS GIS Cut Line= 2
      2759811.11      6802566.68      2759770.57      6803777.00
#Sta/Elev= 30
  4905.9  389.43  4910.9  389.36  4930.2  388.01  4970.3  383.87  4980.3  383.79
  4990.3  383.13  4998.3  379.37  4998.5  378.87  5002.0  378.87  5002.3  379.37
  5010.3  382.27  5020.3  383.40  5050.3  382.82  5090.3  383.26  5220.4  383.25
  5350.5  384.54  5460.5  384.88  5596.2  386.30  5630.6  387.27  5660.6  389.52
  5710.7  391.41  5800.5  395.55  5805.5  395.38  5810.7  395.95  5960.8  401.77
  5980.8  402.05  6070.9  406.16  6100.0  407.26  6105.0  407.10  6116.9  408.28
#Mann=5,-1,0
  4905.9    0.05       0  4910.9    0.12       0  4998.3    0.07       0
  5002.3    0.12       0  5596.2    0.05       0
Bank Sta=4998.3,5002.3
Exp/Cntr=0.3,0.1

Type RM Length L Ch R = 1,1537,145,145,145
BEGIN DESCRIPTION:
Mapping XS 6ffe89ab
END DESCRIPTION:
XS GIS Cut Line= 2
      2759712.18      6802568.11      2759565.90      6803681.55
#Sta/Elev= 30
  4906.3  387.73  4949.6  387.81  4969.7  386.55  4988.5  384.46  4993.5  384.52
  5000.0  382.74  5008.1  379.13  5008.3  378.63  5011.8  378.63  5012.1  379.13
  5030.2  383.48  5040.3  382.76  5072.3  382.34  5145.9  382.50  5353.0  384.26
  5474.0  384.35  5564.8  385.45  5585.0  386.14  5603.2  388.80  5608.2  388.91
  5615.2  390.30  5655.6  392.37  5776.6  394.75  5839.4  394.24  5897.6  396.29
  5913.1  397.36  5968.2  399.70  6018.7  401.41  6026.5  402.74  6029.3  402.74
#Mann=3,-1,0
  4906.3    0.05       0  5008.1    0.04       0  5012.1    0.05       0
Bank Sta=5008.1,5012.1
Exp/Cntr=0.3,0.1

Type RM Length L Ch R = 1,1392,737,737,737
BEGIN DESCRIPTION:
Mapping XS 55a44d81
END DESCRIPTION:
XS GIS Cut Line= 2
      2759633.20      6802550.57      2759093.72      6803321.94
#Sta/Elev= 30
  4864.8  384.32  4905.8  383.99  4920.6  384.64  4977.3  382.31  4986.0  382.53
  4992.1  382.06  5004.9  378.73  5005.2  378.23  5008.7  378.23  5008.9  378.73
  5013.0  380.37  5021.8  382.41  5063.6  381.31  5265.9  381.10  5301.7  381.82
  5316.5  381.52  5322.6  380.27  5329.0  380.06  5337.4  380.38  5343.5  381.83
  5352.3  381.98  5358.4  385.10  5365.6  383.97  5373.2  381.78  5379.3  381.38
  5444.7  381.42  5581.6  383.93  5724.6  384.86  5754.3  385.75  5806.1  388.59
#Mann=3,-1,0
  4864.8    0.05       0  5004.9    0.04       0  5008.9    0.05       0
Bank Sta=5004.9,5008.9
Exp/Cntr=0.3,0.1

Type RM Length L Ch R = 1,655,0,0,0
BEGIN DESCRIPTION:
Clear Creek T 14 1.0
END DESCRIPTION:
XS GIS Cut Line= 3
      2759722.05      6802526.81      2759224.39      6802195.90
      2758613.73      6802738.76
#Sta/Elev= 30
  4403.4  386.28  4476.9  383.00  4506.7  380.97  4606.2  377.82  4663.3  377.63
  4722.9  378.75  4780.5  378.65  4822.6  377.77  4837.6  378.20  4939.1  377.66
  5017.6  379.09  5039.0  378.68  5046.0  379.43  5052.7  377.58  5060.2  377.18
  5066.9  378.29  5109.6  377.06  5307.8  376.59  5499.2  375.09  5518.7  374.33
  5518.9  373.83  5522.4  373.83  5522.7  374.33  5570.3  374.99  5648.1  378.86
  5654.8  379.71  5676.5  380.06  5711.6  382.67  5775.2  384.04  5818.1  383.83
#Mann=3,-1,0
  4403.4    0.05       0  5518.7    0.04       0  5522.7    0.05       0
Bank Sta=5518.7,5522.7
Exp/Cntr=0.3,0.1

Chan Stop Cuts=-1