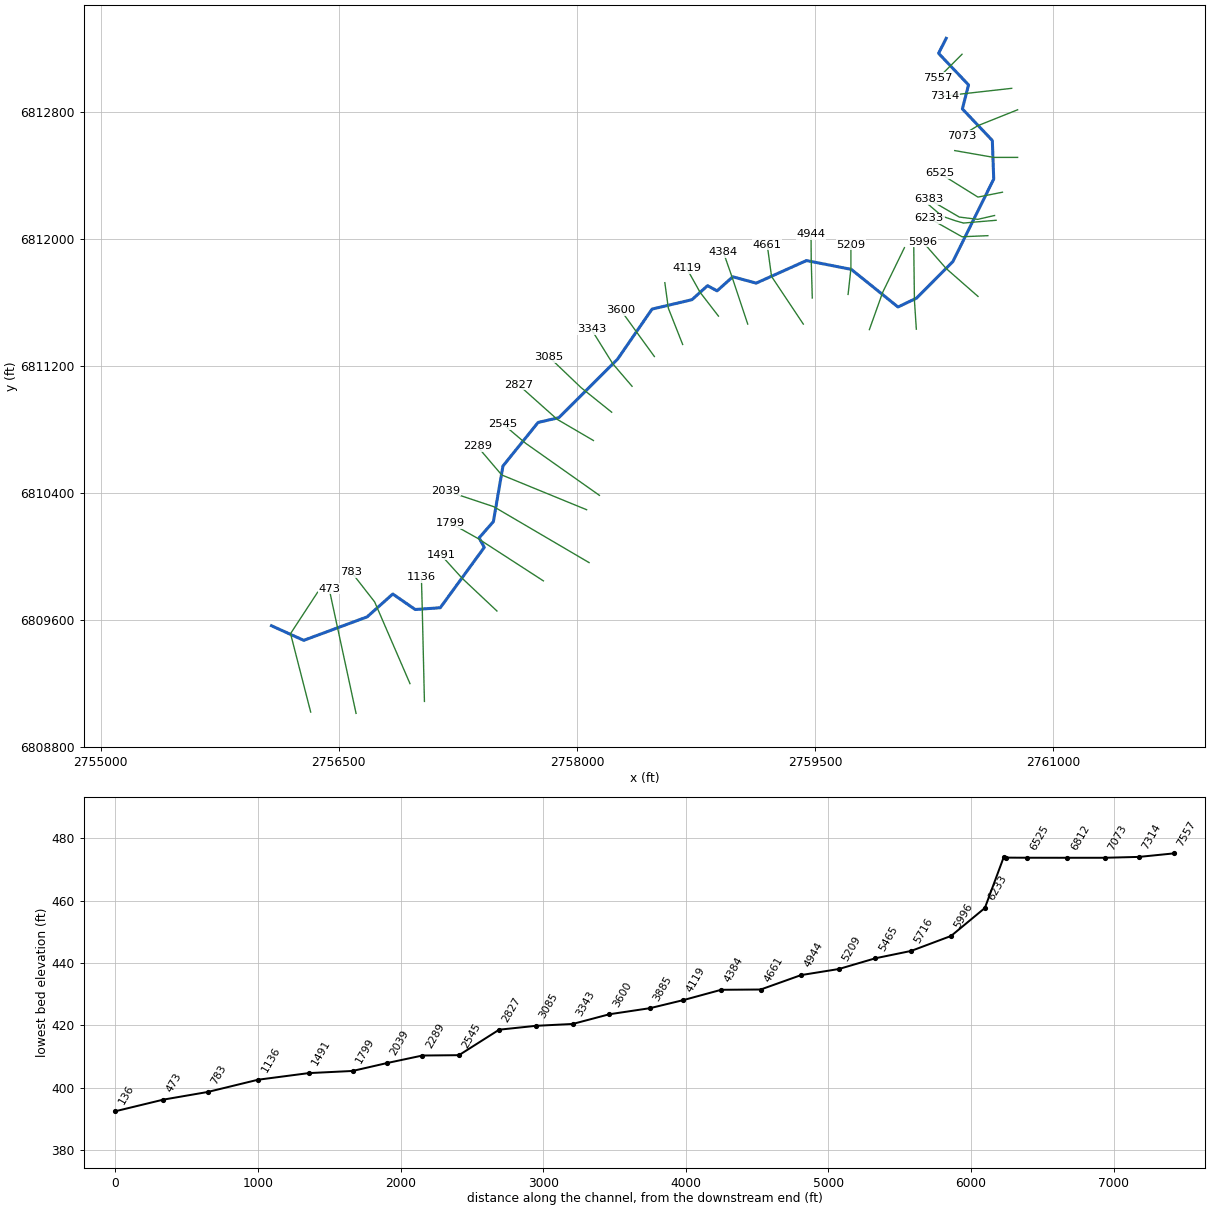
--- Clear Creek T 15.prj (project) ---

Proj Title=Clear Creek T 15 Base Level Engineering
Current Plan=p01
Default Exp/Contr=0.3,0.1
English Units
Geom File=g01
Flow File=f01
Plan File=p01
BEGIN DESCRIPTION:
Clear Creek T 15
END DESCRIPTION:

--- Clear Creek T 15.p01 (plan) ---

Plan Title=Multiple Run
Short Identifier=Multiple
Geom File=g01
Flow File=f01
Subcritical Flow
K Sum by GR= 0
Std Step Tol= 0.01
Critical Tol= 0.01
Num of Std Step Trials= 20
Max Error Tol= 0.3
Flow Tol Ratio= 0.001
Split Flow NTrial= 30
Split Flow Tol= 0.02
Split Flow Ratio= 0.02
Log Output Level= 0
Friction Slope Method= 1
Unsteady Friction Slope Method= 2
Unsteady Bridges Friction Slope Method= 1
Parabolic Critical Depth
Global Vel Dist=  1 , 1 , 1
Global Log Level= 0
CheckData=True
Encroach Param= -1, 0, 0, 0
BEGIN DESCRIPTION:
Multiple Run
END DESCRIPTION:

--- Clear Creek T 15.f01 (steady flow) ---

Flow Title=Multiple
Number of Profiles=7
Profile Names=10-year,25-year,50-year,1pct_min,100-year,1pct_plu,500-year
River Rch & RM= Clear Creek T 15,Reach-1,7557
     236     306     361     214     427     851     594
River Rch & RM= Clear Creek T 15,Reach-1,5996
     433     581     702     423     845    1685    1222
River Rch & RM= Clear Creek T 15,Reach-1,1491
     553     753     918     558    1113    2220    1638
Boundary for River Rch & Prof#=Clear Creek T 15,Reach-1,1
Up Type=0
Dn Type=3
Dn Slope=0.005
Boundary for River Rch & Prof#=Clear Creek T 15,Reach-1,2
Up Type=0
Dn Type=3
Dn Slope=0.005
Boundary for River Rch & Prof#=Clear Creek T 15,Reach-1,3
Up Type=0
Dn Type=3
Dn Slope=0.005
Boundary for River Rch & Prof#=Clear Creek T 15,Reach-1,4
Up Type=0
Dn Type=3
Dn Slope=0.005
Boundary for River Rch & Prof#=Clear Creek T 15,Reach-1,5
Up Type=0
Dn Type=3
Dn Slope=0.005
Boundary for River Rch & Prof#=Clear Creek T 15,Reach-1,6
Up Type=0
Dn Type=3
Dn Slope=0.005
Boundary for River Rch & Prof#=Clear Creek T 15,Reach-1,7
Up Type=0
Dn Type=3
Dn Slope=0.005

--- Clear Creek T 15.g01 (geometry) ---

Geom Title=Existing Conditions

River Reach=Clear Creek T 15,Reach-1
Reach XY= 30
      2760326.00      6813261.00      2760278.21      6813166.57
      2760466.87      6812967.75      2760428.08      6812816.48
      2760616.70      6812617.67      2760625.47      6812374.87
      2760368.14      6811854.83      2760139.21      6811624.60
      2760022.59      6811568.77      2759728.45      6811805.53
      2759446.18      6811861.28      2759129.32      6811719.05
      2758981.89      6811759.02      2758882.66      6811670.32
      2758822.67      6811702.98      2758724.50      6811614.64
      2758473.33      6811555.58      2758256.37      6811240.53
      2757886.10      6810871.39      2757755.46      6810841.53
      2757534.14      6810567.06      2757473.84      6810216.89
      2757384.01      6810114.33      2757416.41      6810054.45
      2757139.34      6809674.36      2756981.45      6809663.17
      2756840.10      6809760.84      2756678.53      6809616.76
      2756279.31      6809469.02      2756076.00      6809561.00

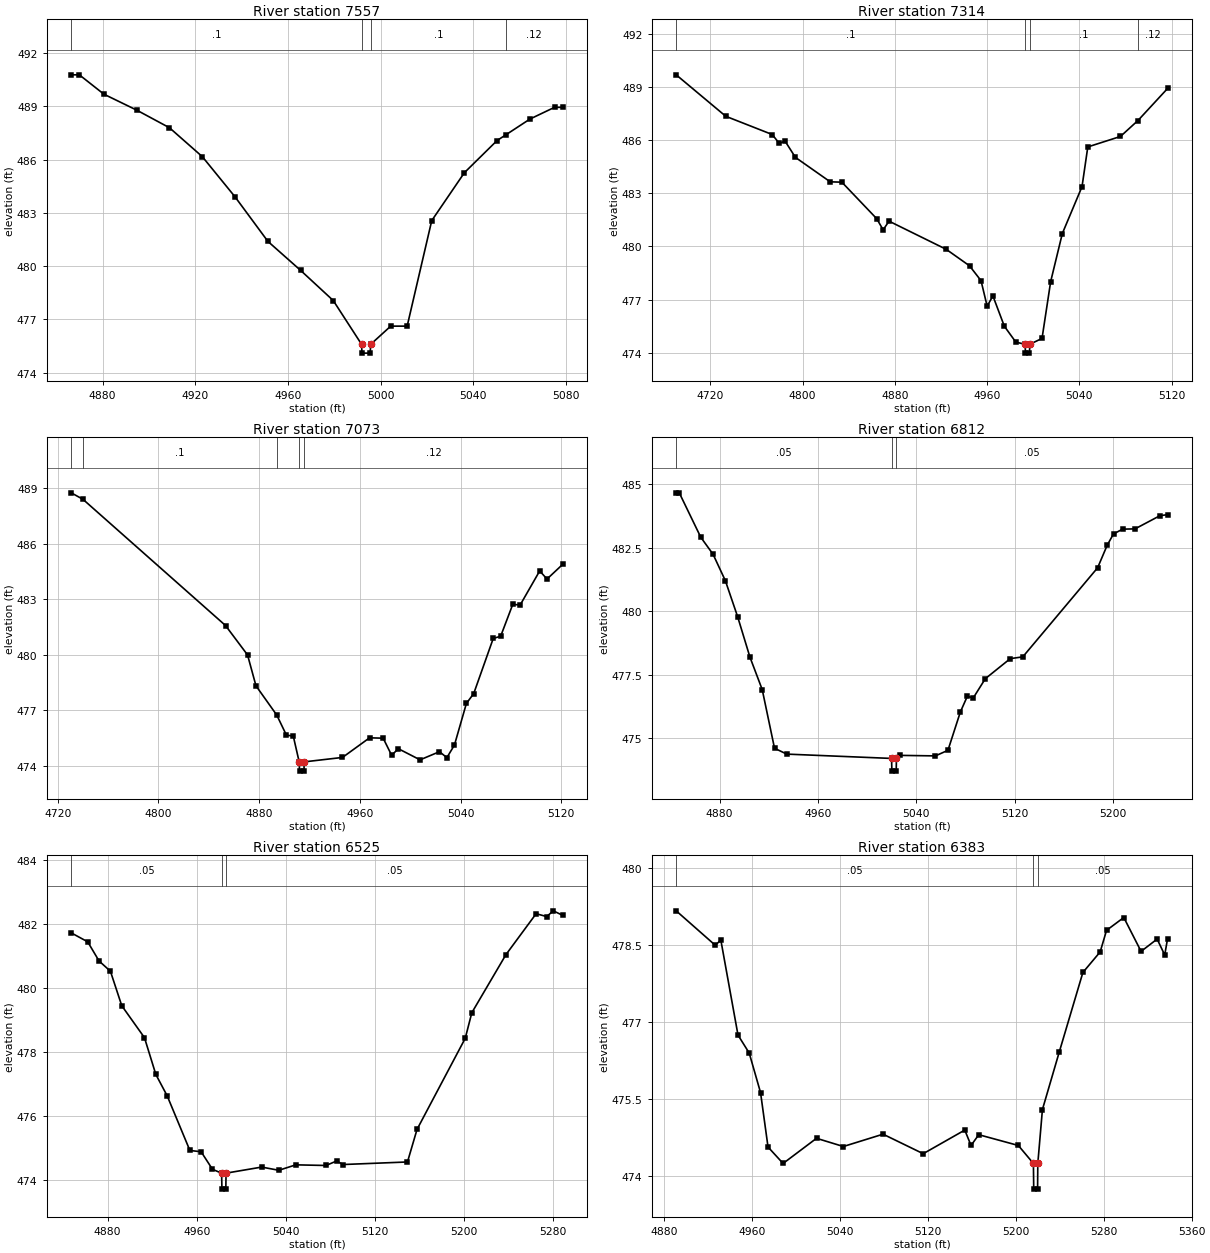
Type RM Length L Ch R = 1,7557,243,243,243
BEGIN DESCRIPTION:
Clear Creek T 15 27.0
END DESCRIPTION:
XS GIS Cut Line= 3
      2760426.00      6813161.00      2760326.00      6813061.00
      2760276.02      6813011.02
#Sta/Elev= 23
  4866.5  490.77  4870.0  490.77  4880.6  489.68  4894.8  488.78  4908.9  487.79
  4923.1  486.16  4937.2  483.90  4951.4  481.39  4965.5  479.76  4979.6  478.06
  4991.8  475.60  4992.0  475.10  4995.5  475.10  4995.8  475.60  5004.4  476.62
  5011.5  476.62  5022.1  482.56  5036.2  485.26  5050.3  487.07  5054.2  487.40
  5064.5  488.28  5075.1  488.94  5078.6  488.94
#Mann=4,-1,0
  4866.5     0.1       0  4991.8    0.07       0  4995.8     0.1       0
  5054.2    0.12       0
Bank Sta=4991.8,4995.8
Exp/Cntr=0.3,0.1

Type RM Length L Ch R = 1,7314,241,241,241
BEGIN DESCRIPTION:
Clear Creek T 15 26.0
END DESCRIPTION:
XS GIS Cut Line= 3
      2760738.78      6812946.08      2760426.00      6812911.00
      2760315.45      6812896.78
#Sta/Elev= 30
  4690.3  489.69  4733.3  487.35  4773.6  486.32  4779.7  485.82  4784.7  485.95
  4793.7  485.03  4823.9  483.65  4834.0  483.63  4864.2  481.57  4869.8  480.94
  4874.9  481.43  4924.5  479.84  4944.7  478.91  4954.7  478.07  4960.0  476.63
  4965.0  477.21  4974.9  475.50  4984.9  474.60  4993.0  474.48  4993.2  473.98
  4996.7  473.98  4997.0  474.48  5007.6  474.81  5015.1  478.02  5025.2  480.73
  5042.3  483.38  5047.3  485.62  5075.6  486.21  5090.8  487.11  5116.5  488.92
#Mann=4,-1,0
  4690.3     0.1       0  4993.0    0.07       0  4997.0     0.1       0
  5090.8    0.12       0
Bank Sta=4993,4997
Exp/Cntr=0.3,0.1

Type RM Length L Ch R = 1,7073,261,261,261
BEGIN DESCRIPTION:
Clear Creek T 15 25.0
END DESCRIPTION:
XS GIS Cut Line= 3
      2760775.96      6812810.98      2760526.00      6812711.00
      2760422.55      6812648.26
#Sta/Elev= 30
  4730.8  488.74  4740.1  488.39  4853.3  481.57  4870.8  479.98  4877.5  478.31
  4894.0  476.73  4901.7  475.64  4907.1  475.60  4911.8  474.20  4912.1  473.70
  4915.6  473.70  4915.8  474.20  4946.2  474.44  4967.7  475.50  4978.5  475.48
  4985.2  474.56  4990.6  474.91  5007.8  474.31  5023.2  474.75  5029.1  474.43
  5035.1  475.11  5044.6  477.36  5050.4  477.89  5065.9  480.87  5071.8  480.99
  5081.4  482.71  5087.3  482.68  5102.8  484.52  5108.6  484.08  5121.0  484.87
#Mann=5,-1,0
  4730.8    0.05       0  4740.1     0.1       0  4894.0    0.12       0
  4911.8    0.07       0  4915.8    0.12       0
Bank Sta=4911.8,4915.8
Exp/Cntr=0.3,0.1

Type RM Length L Ch R = 1,6812,287,287,287
BEGIN DESCRIPTION:
Clear Creek T 15 24.0
END DESCRIPTION:
XS GIS Cut Line= 3
      2760776.01      6812511.00      2760626.00      6812511.00
      2760379.93      6812553.96
#Sta/Elev= 30
  4844.7  484.66  4847.2  484.66  4864.7  482.91  4874.7  482.24  4884.7  481.20
  4894.7  479.78  4904.7  478.19  4914.7  476.91  4924.7  474.60  4934.7  474.37
  5019.9  474.20  5020.2  473.70  5023.7  473.70  5023.9  474.20  5027.0  474.32
  5055.6  474.30  5065.8  474.52  5075.9  476.03  5081.5  476.64  5086.5  476.59
  5096.2  477.34  5116.5  478.13  5126.7  478.20  5187.6  481.71  5195.4  482.60
  5200.5  483.04  5207.9  483.23  5218.0  483.24  5238.3  483.76  5244.5  483.80
#Mann=3,-1,0
  4844.7    0.05       0  5019.9    0.03       0  5023.9    0.05       0
Bank Sta=5019.9,5023.9
Exp/Cntr=0.3,0.1

Type RM Length L Ch R = 1,6525,142,142,142
BEGIN DESCRIPTION:
Clear Creek T 15 23.0
END DESCRIPTION:
XS GIS Cut Line= 3
      2760680.48      6812291.90      2760526.00      6812261.00
      2760284.98      6812411.14
#Sta/Elev= 30
  4847.3  481.73  4862.1  481.45  4872.3  480.85  4882.5  480.53  4892.7  479.45
  4913.1  478.45  4923.3  477.30  4933.5  476.63  4953.9  474.92  4964.0  474.88
  4974.2  474.33  4982.4  474.21  4982.7  473.71  4986.2  473.71  4986.4  474.21
  5018.4  474.40  5033.8  474.30  5049.1  474.47  5076.2  474.45  5085.7  474.59
  5091.6  474.48  5149.4  474.56  5158.0  475.58  5201.3  478.43  5207.2  479.23
  5237.9  481.05  5265.0  482.33  5274.5  482.24  5280.4  482.42  5288.8  482.28
#Mann=3,-1,0
  4847.3    0.05       0  4982.4    0.03       0  4986.4    0.05       0
Bank Sta=4982.4,4986.4
Exp/Cntr=0.3,0.1

Type RM Length L Ch R = 1,6383,18,18,18
BEGIN DESCRIPTION:
Mapping XS 28b8d475
END DESCRIPTION:
XS GIS Cut Line= 4
      2760630.76      6812145.00      2760524.73      6812120.76
      2760408.58      6812135.25      2760217.77      6812246.73
#Sta/Elev= 30
  4891.3  479.17  4926.8  478.50  4931.9  478.60  4947.5  476.75  4957.7  476.40
  4968.0  475.63  4974.8  474.57  4988.5  474.25  5018.9  474.74  5043.3  474.58
  5079.4  474.82  5115.9  474.44  5153.7  474.90  5159.4  474.60  5166.4  474.81
  5202.4  474.60  5216.1  474.25  5216.4  473.75  5219.9  473.75  5220.1  474.25
  5224.3  475.30  5239.6  476.42  5261.1  477.97  5276.8  478.37  5282.6  478.79
  5298.3  479.04  5314.0  478.38  5328.6  478.62  5335.5  478.31  5338.1  478.63
#Mann=3,-1,0
  4891.3    0.05       0  5216.1    0.03       0  5220.1    0.05       0
Bank Sta=5216.1,5220.1
Exp/Cntr=0.3,0.1

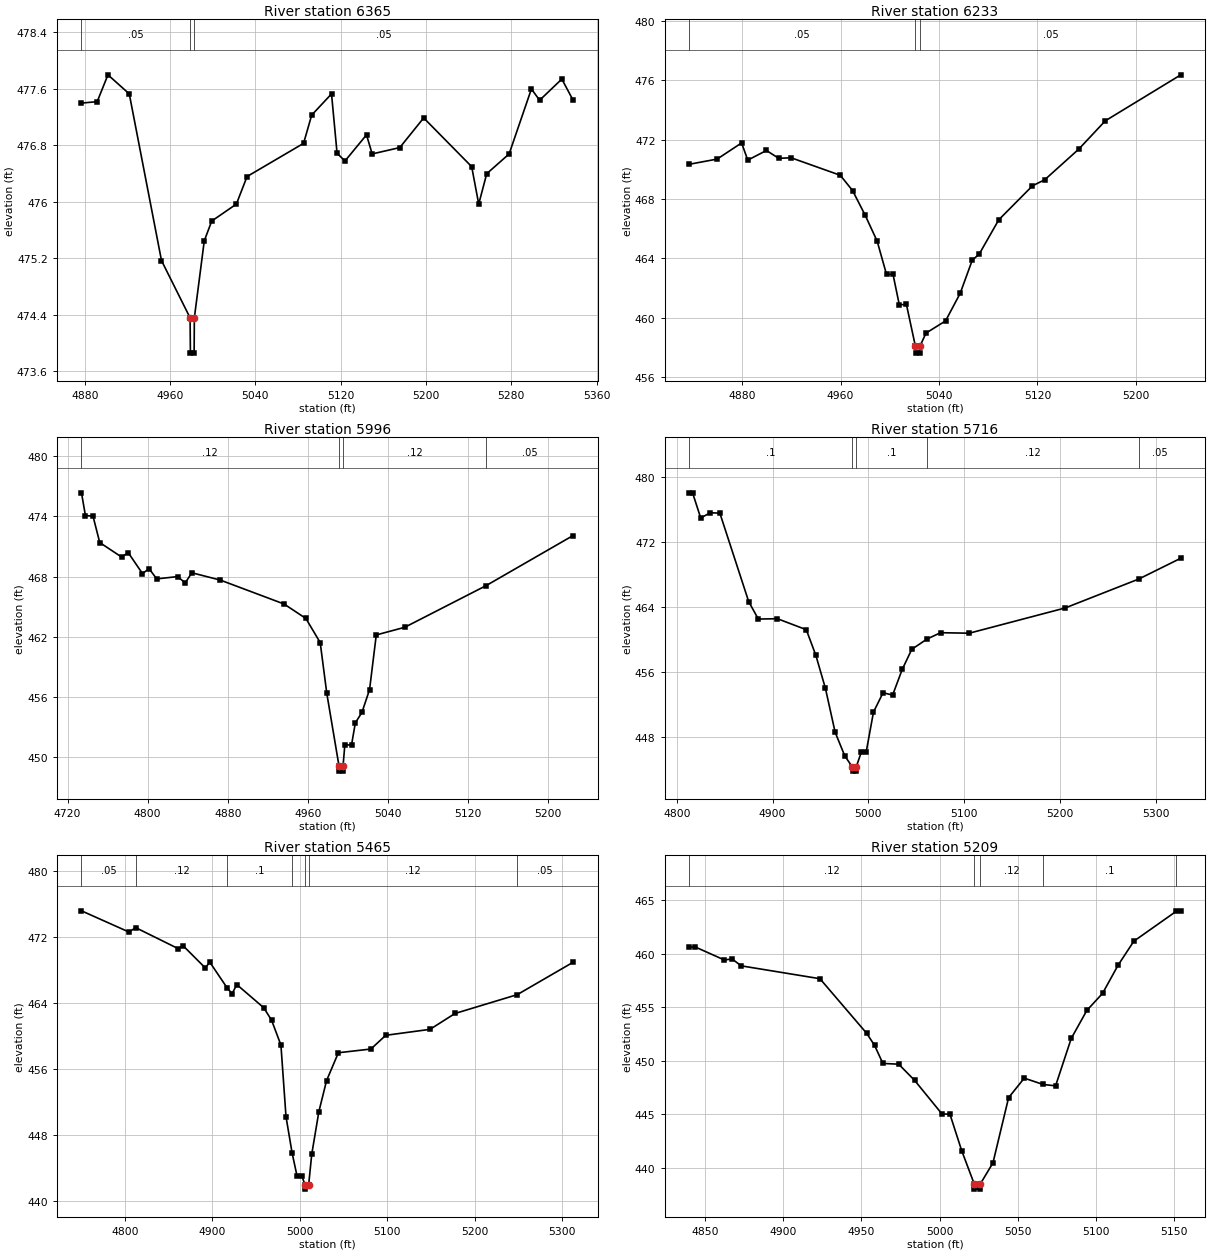
Type RM Length L Ch R = 1,6365,132,132,132
BEGIN DESCRIPTION:
Mapping XS a8164961
END DESCRIPTION:
XS GIS Cut Line= 6
      2760640.69      6812114.94      2760517.09      6812104.63
      2760435.66      6812097.45      2760384.58      6812111.79
      2760300.06      6812140.90      2760214.44      6812214.15
#Sta/Elev= 30
  4877.0  477.40  4891.7  477.42  4901.8  477.80  4921.8  477.53  4952.0  475.17
  4978.8  474.36  4979.1  473.86  4982.6  473.86  4982.8  474.36  4992.1  475.45
  4999.1  475.73  5022.2  475.97  5032.2  476.36  5085.2  476.83  5092.8  477.23
  5111.4  477.53  5116.6  476.69  5124.0  476.58  5144.2  476.95  5149.5  476.68
  5175.4  476.77  5197.8  477.19  5242.8  476.50  5249.4  475.97  5256.9  476.40
  5277.9  476.68  5298.8  477.60  5306.5  477.44  5327.3  477.74  5337.9  477.44
#Mann=3,-1,0
  4877.0    0.05       0  4978.8    0.03       0  4982.8    0.05       0
Bank Sta=4978.8,4982.8
Exp/Cntr=0.3,0.1

Type RM Length L Ch R = 1,6233,237,237,237
BEGIN DESCRIPTION:
Clear Creek T 15 22.0
END DESCRIPTION:
XS GIS Cut Line= 3
      2760588.70      6812018.06      2760426.00      6812011.00
      2760219.70      6812127.34
#Sta/Elev= 30
  4836.9  470.33  4859.6  470.68  4879.5  471.77  4884.5  470.61  4899.7  471.26
  4909.7  470.73  4919.7  470.77  4959.7  469.59  4969.7  468.56  4979.7  466.94
  4989.7  465.15  4997.3  462.91  5002.6  462.91  5007.7  460.86  5013.5  460.88
  5020.7  458.10  5021.0  457.60  5024.5  457.60  5024.7  458.10  5029.4  458.95
  5045.3  459.77  5057.2  461.63  5067.0  463.86  5072.7  464.28  5088.6  466.59
  5116.0  468.88  5126.0  469.29  5153.6  471.35  5175.2  473.26  5236.6  476.36
#Mann=3,-1,0
  4836.9    0.05       0  5020.7    0.04       0  5024.7    0.05       0
Bank Sta=5020.7,5024.7
Exp/Cntr=0.3,0.1

Type RM Length L Ch R = 1,5996,280,280,280
BEGIN DESCRIPTION:
Clear Creek T 15 21.0
END DESCRIPTION:
XS GIS Cut Line= 3
      2760526.37      6811635.51      2760326.00      6811811.00
      2760177.89      6811979.90
#Sta/Elev= 30
  4733.9  476.35  4737.8  474.09  4745.4  474.03  4752.1  471.40  4773.9  469.96
  4780.6  470.39  4794.8  468.31  4801.4  468.80  4809.0  467.78  4829.9  468.01
  4837.5  467.38  4844.1  468.39  4872.6  467.66  4936.2  465.28  4958.0  463.84
  4972.3  461.44  4978.9  456.37  4991.1  449.14  4991.4  448.64  4994.9  448.64
  4995.1  449.14  4996.9  451.25  5003.6  451.25  5007.4  453.45  5014.0  454.49
  5021.6  456.76  5028.3  462.20  5056.7  462.96  5138.0  467.11  5224.9  472.10
#Mann=4,-1,0
  4733.9    0.12       0  4991.1    0.07       0  4995.1    0.12       0
  5138.0    0.05       0
Bank Sta=4991.1,4995.1
Exp/Cntr=0.3,0.1

Type RM Length L Ch R = 1,5716,251,251,251
BEGIN DESCRIPTION:
Clear Creek T 15 20.0
END DESCRIPTION:
XS GIS Cut Line= 3
      2760138.03      6811429.07      2760126.00      6811611.00
      2760121.85      6811941.75
#Sta/Elev= 30
  4813.0  478.06  4816.5  478.06  4825.0  474.97  4835.0  475.61  4845.0  475.56
  4875.1  464.68  4885.1  462.54  4905.1  462.58  4935.2  461.23  4945.2  458.07
  4955.2  454.00  4965.3  448.62  4975.3  445.73  4983.3  444.34  4983.6  443.84
  4987.1  443.84  4987.3  444.34  4992.8  446.25  4997.8  446.25  5005.3  451.09
  5015.3  453.48  5025.3  453.19  5035.3  456.34  5045.3  458.82  5061.2  460.08
  5075.3  460.86  5105.3  460.80  5205.3  463.90  5282.2  467.46  5326.1  470.02
#Mann=5,-1,0
  4813.0     0.1       0  4983.3    0.07       0  4987.3     0.1       0
  5061.2    0.12       0  5282.2    0.05       0
Bank Sta=4983.3,4987.3
Exp/Cntr=0.3,0.1

Type RM Length L Ch R = 1,5465,256,256,256
BEGIN DESCRIPTION:
Clear Creek T 15 19.0
END DESCRIPTION:
XS GIS Cut Line= 3
      2759842.19      6811426.22      2759926.00      6811661.00
      2760063.00      6811942.43
#Sta/Elev= 30
  4750.5  475.15  4804.9  472.58  4812.4  473.12  4861.2  470.57  4866.5  470.95
  4892.0  468.25  4897.3  468.93  4917.3  465.79  4922.8  465.13  4928.1  466.23
  4958.9  463.43  4967.9  461.92  4978.6  458.91  4984.4  450.25  4991.4  445.85
  4997.1  443.03  5002.6  443.03  5006.3  441.98  5006.5  441.48  5010.3  441.98
  5013.8  445.67  5022.0  450.86  5030.8  454.61  5044.3  457.98  5081.5  458.43
  5098.5  460.09  5149.1  460.81  5177.7  462.73  5248.9  465.01  5312.8  468.93
#Mann=7,-1,0
  4750.5    0.05       0  4812.4    0.12       0  4917.3     0.1       0
  4991.4    0.12       0  5006.3    0.07       0  5010.3    0.12       0
  5248.9    0.05       0
Bank Sta=5006.3,5010.3
Exp/Cntr=0.3,0.1

Type RM Length L Ch R = 1,5209,265,265,265
BEGIN DESCRIPTION:
Clear Creek T 15 18.0
END DESCRIPTION:
XS GIS Cut Line= 3
      2759708.10      6811648.00      2759726.00      6811811.00
      2759726.00      6811961.02
#Sta/Elev= 30
  4840.1  460.61  4844.1  460.61  4862.5  459.41  4867.5  459.50  4873.3  458.86
  4923.6  457.66  4953.5  452.56  4958.5  451.44  4963.8  449.76  4973.9  449.69
  4984.0  448.19  5001.6  445.04  5006.6  445.04  5014.1  441.64  5022.1  438.54
  5022.3  438.04  5025.8  438.04  5026.1  438.54  5034.1  440.49  5044.1  446.57
  5054.1  448.39  5066.1  447.80  5074.1  447.67  5084.1  452.09  5094.1  454.71
  5104.1  456.29  5114.1  458.94  5124.1  461.16  5151.2  463.95  5154.1  463.99
#Mann=5,-1,0
  4840.1    0.12       0  5022.1    0.07       0  5026.1    0.12       0
  5066.1     0.1       0  5151.2    0.05       0
Bank Sta=5022.1,5026.1
Exp/Cntr=0.3,0.1

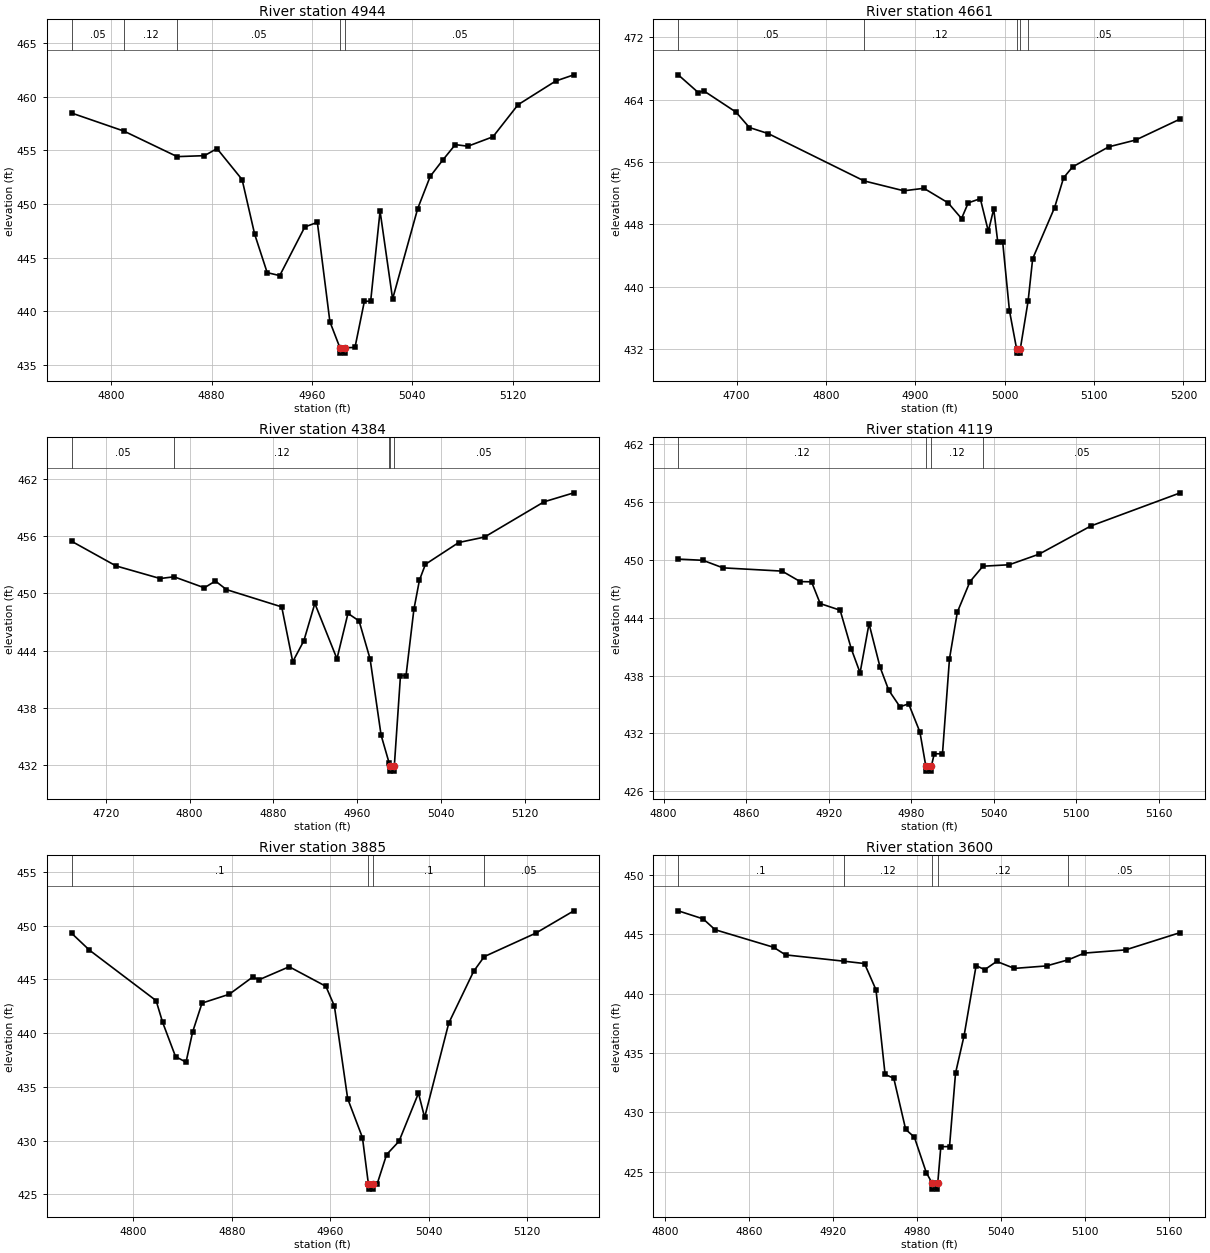
Type RM Length L Ch R = 1,4944,283,283,283
BEGIN DESCRIPTION:
Clear Creek T 15 17.0
END DESCRIPTION:
XS GIS Cut Line= 3
      2759482.57      6811625.27      2759476.00      6811861.00
      2759474.65      6812025.47
#Sta/Elev= 30
  4768.5  458.48  4810.1  456.80  4852.5  454.42  4874.3  454.51  4884.3  455.17
  4904.3  452.28  4914.3  447.19  4924.3  443.60  4934.3  443.32  4954.3  447.86
  4964.3  448.29  4974.3  439.02  4982.3  436.59  4982.6  436.09  4986.1  436.09
  4986.3  436.59  4994.3  436.62  5001.8  440.93  5006.8  440.93  5014.3  449.34
  5024.3  441.14  5044.3  449.57  5054.3  452.58  5064.3  454.10  5074.3  455.54
  5084.3  455.39  5104.3  456.27  5124.3  459.26  5154.3  461.47  5168.8  462.05
#Mann=5,-1,0
  4768.5    0.05       0  4810.1    0.12       0  4852.5    0.05       0
  4982.3    0.04       0  4986.3    0.05       0
Bank Sta=4982.3,4986.3
Exp/Cntr=0.3,0.1

Type RM Length L Ch R = 1,4661,277,277,277
BEGIN DESCRIPTION:
Clear Creek T 15 16.0
END DESCRIPTION:
XS GIS Cut Line= 3
      2759426.00      6811461.00      2759226.00      6811761.00
      2759198.69      6811960.38
#Sta/Elev= 30
  4634.7  467.18  4657.2  464.90  4663.2  465.13  4699.3  462.40  4714.3  460.42
  4735.4  459.64  4842.6  453.57  4887.1  452.30  4909.6  452.62  4936.7  450.75
  4951.7  448.74  4959.2  450.75  4972.7  451.29  4981.7  447.10  4987.7  449.96
  4992.3  445.67  4997.8  445.67  5005.3  436.93  5013.4  431.97  5013.7  431.47
  5017.2  431.47  5017.4  431.97  5026.2  438.16  5031.3  443.59  5055.8  450.14
  5065.9  453.97  5076.0  455.37  5116.4  457.94  5146.7  458.82  5196.5  461.52
#Mann=5,-1,0
  4634.7    0.05       0  4842.6    0.12       0  5013.4    0.07       0
  5017.4    0.12       0  5026.2    0.05       0
Bank Sta=5013.4,5017.4
Exp/Cntr=0.3,0.1

Type RM Length L Ch R = 1,4384,265,265,265
BEGIN DESCRIPTION:
Clear Creek T 15 15.0
END DESCRIPTION:
XS GIS Cut Line= 3
      2759076.00      6811461.00      2758976.00      6811761.00
      2758922.26      6811914.65
#Sta/Elev= 30
  4687.6  455.43  4729.8  452.86  4771.9  451.54  4785.2  451.72  4814.1  450.57
  4824.6  451.28  4835.2  450.38  4887.9  448.57  4898.4  442.83  4909.0  445.02
  4919.5  448.93  4940.6  443.14  4951.1  447.89  4961.7  447.10  4972.2  443.13
  4982.7  435.15  4990.3  432.26  4991.3  431.88  4991.5  431.38  4995.0  431.38
  4995.3  431.88  5001.2  441.38  5006.5  441.38  5014.0  448.31  5019.3  451.37
  5025.0  453.03  5056.8  455.31  5081.4  455.88  5138.2  459.57  5166.6  460.51
#Mann=5,-1,0
  4687.6    0.05       0  4785.2    0.12       0  4990.3    0.05       0
  4991.3    0.04       0  4995.3    0.05       0
Bank Sta=4991.3,4995.3
Exp/Cntr=0.3,0.1

Type RM Length L Ch R = 1,4119,234,234,234
BEGIN DESCRIPTION:
Clear Creek T 15 14.0
END DESCRIPTION:
XS GIS Cut Line= 3
      2758891.66      6811511.24      2758776.00      6811661.00
      2758690.22      6811814.42
#Sta/Elev= 30
  4810.7  450.10  4828.7  449.97  4843.2  449.19  4886.2  448.85  4899.4  447.76
  4907.6  447.74  4913.9  445.48  4928.4  444.79  4936.5  440.78  4942.9  438.29
  4949.4  443.39  4957.4  438.89  4963.7  436.49  4971.9  434.76  4978.2  435.07
  4986.4  432.14  4990.7  428.58  4990.9  428.08  4994.4  428.08  4994.7  428.58
  4996.8  429.88  5002.8  429.88  5007.9  439.76  5013.6  444.59  5022.8  447.76
  5032.2  449.36  5051.3  449.51  5073.0  450.61  5110.7  453.54  5175.7  456.98
#Mann=4,-1,0
  4810.7    0.12       0  4990.7    0.07       0  4994.7    0.12       0
  5032.2    0.05       0
Bank Sta=4990.7,4994.7
Exp/Cntr=0.3,0.1

Type RM Length L Ch R = 1,3885,285,285,285
BEGIN DESCRIPTION:
Clear Creek T 15 13.0
END DESCRIPTION:
XS GIS Cut Line= 3
      2758666.25      6811332.58      2758576.00      6811561.00
      2758553.84      6811721.68
#Sta/Elev= 30
  4750.0  449.27  4764.4  447.71  4818.5  443.02  4823.8  441.00  4834.3  437.81
  4842.8  437.30  4848.2  440.12  4855.8  442.79  4877.9  443.61  4896.9  445.21
  4902.3  444.97  4926.6  446.17  4956.4  444.35  4963.3  442.52  4974.1  433.90
  4986.1  430.28  4990.9  425.99  4991.2  425.49  4994.7  425.49  4994.9  425.99
  4998.1  425.99  5005.7  428.70  5015.8  429.94  5031.6  434.41  5036.6  432.16
  5056.2  440.93  5076.4  445.74  5085.0  447.11  5126.8  449.29  5157.8  451.37
#Mann=4,-1,0
  4750.0     0.1       0  4990.9    0.07       0  4994.9     0.1       0
  5085.0    0.05       0
Bank Sta=4990.9,4994.9
Exp/Cntr=0.3,0.1

Type RM Length L Ch R = 1,3600,257,257,257
BEGIN DESCRIPTION:
Clear Creek T 15 12.0
END DESCRIPTION:
XS GIS Cut Line= 3
      2758487.99      6811256.76      2758376.00      6811411.00
      2758277.67      6811547.08
#Sta/Elev= 30
  4809.6  446.98  4827.4  446.30  4835.9  445.39  4877.7  443.91  4886.2  443.27
  4927.7  442.74  4942.6  442.54  4950.8  440.33  4957.3  433.20  4963.5  432.88
  4972.0  428.57  4978.2  427.92  4986.7  424.94  4990.9  424.04  4991.1  423.54
  4994.6  423.54  4994.9  424.04  4997.1  427.12  5003.3  427.12  5007.6  433.31
  5013.7  436.46  5022.3  442.37  5028.4  442.02  5037.0  442.72  5049.6  442.13
  5072.6  442.34  5088.2  442.86  5099.6  443.42  5129.0  443.69  5168.1  445.15
#Mann=5,-1,0
  4809.6     0.1       0  4927.7    0.12       0  4990.9    0.07       0
  4994.9    0.12       0  5088.2    0.05       0
Bank Sta=4990.9,4994.9
Exp/Cntr=0.3,0.1

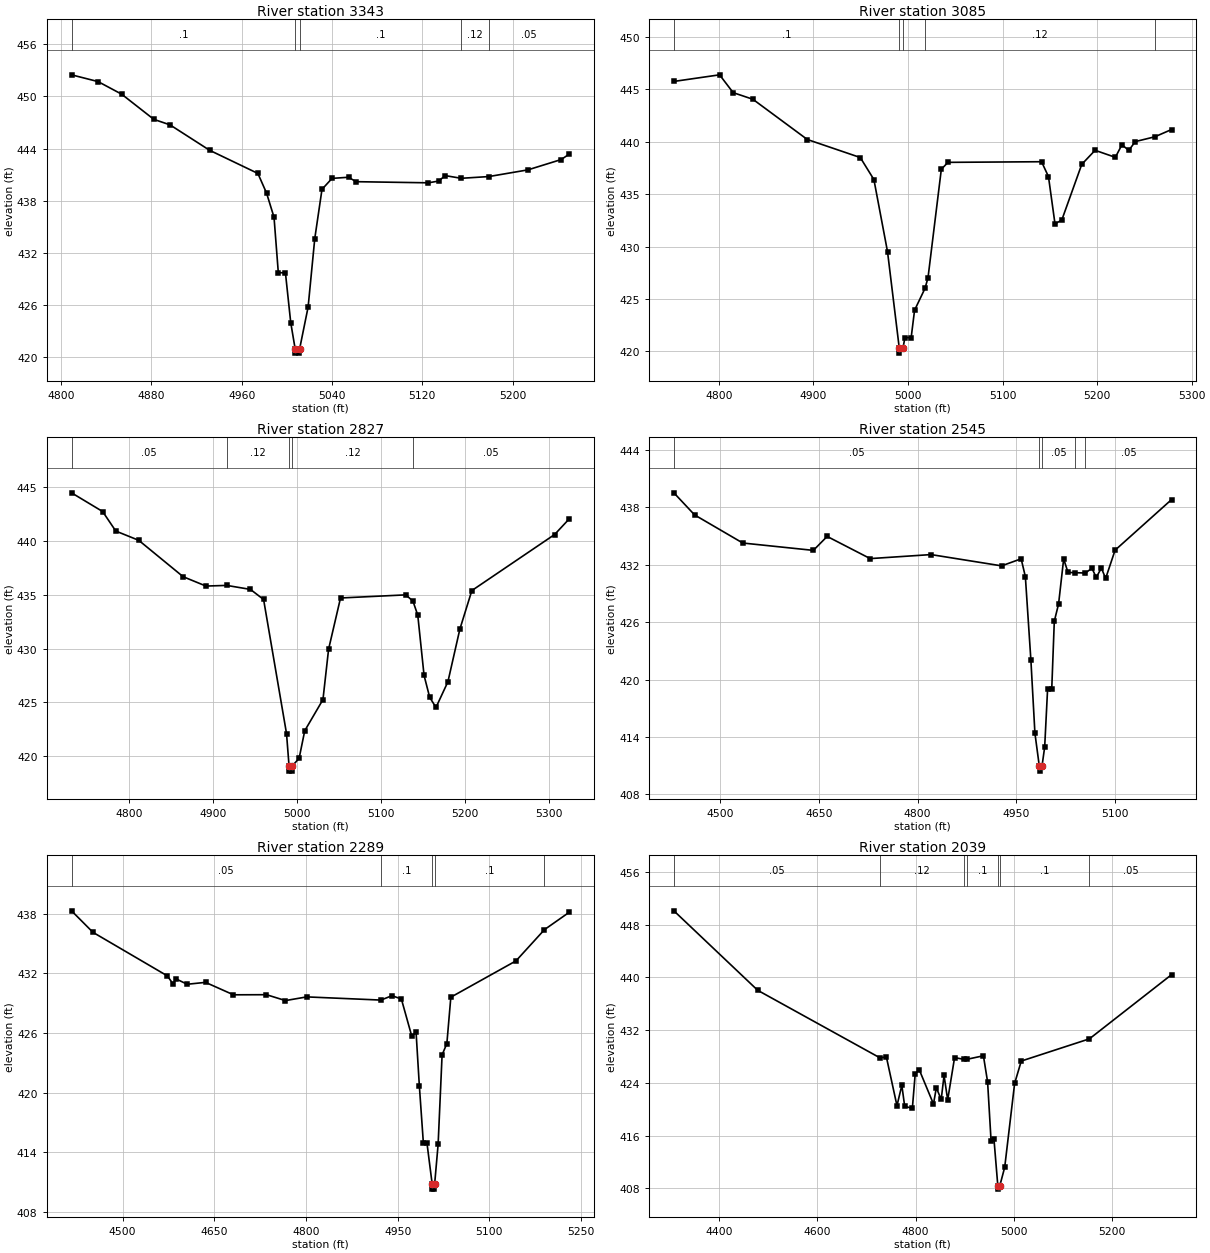
Type RM Length L Ch R = 1,3343,258,258,258
BEGIN DESCRIPTION:
Clear Creek T 15 11.0
END DESCRIPTION:
XS GIS Cut Line= 3
      2758347.34      6811069.33      2758226.00      6811211.00
      2758091.65      6811426.99
#Sta/Elev= 30
  4809.2  452.49  4832.7  451.71  4853.6  450.26  4882.1  447.36  4896.4  446.73
  4931.5  443.80  4974.3  441.13  4982.0  438.86  4988.6  436.08  4992.4  429.69
  4998.7  429.69  5003.4  423.95  5007.3  420.93  5007.5  420.43  5011.0  420.43
  5011.3  420.93  5018.8  425.74  5024.7  433.63  5031.1  439.30  5040.0  440.56
  5054.6  440.69  5061.3  440.18  5125.3  440.05  5134.4  440.25  5140.3  440.88
  5154.4  440.57  5178.9  440.77  5213.5  441.54  5243.0  442.73  5250.1  443.35
#Mann=5,-1,0
  4809.2     0.1       0  5007.3    0.07       0  5011.3     0.1       0
  5154.4    0.12       0  5178.9    0.05       0
Bank Sta=5007.3,5011.3
Exp/Cntr=0.3,0.1

Type RM Length L Ch R = 1,3085,258,258,258
BEGIN DESCRIPTION:
Clear Creek T 15 10.0
END DESCRIPTION:
XS GIS Cut Line= 3
      2758218.95      6810906.04      2758026.00      6811061.00
      2757824.52      6811253.61
#Sta/Elev= 30
  4752.5  445.75  4800.8  446.38  4815.2  444.68  4836.0  444.05  4893.6  440.21
  4949.6  438.49  4964.0  436.39  4978.4  429.51  4990.8  420.33  4991.0  419.83
  4994.8  420.33  4996.8  421.31  5003.4  421.31  5007.0  423.92  5018.0  426.00
  5021.2  427.01  5035.3  437.37  5042.3  438.03  5141.3  438.09  5148.6  436.67
  5155.5  432.16  5162.7  432.53  5183.8  437.84  5197.9  439.18  5219.3  438.51
  5226.3  439.71  5233.5  439.17  5240.4  440.01  5261.1  440.47  5278.7  441.16
#Mann=5,-1,0
  4752.5     0.1       0  4990.8    0.07       0  4994.8     0.1       0
  5018.0    0.12       0  5261.1    0.05       0
Bank Sta=4990.8,4994.8
Exp/Cntr=0.3,0.1

Type RM Length L Ch R = 1,2827,282,282,282
BEGIN DESCRIPTION:
Clear Creek T 15 9.0
END DESCRIPTION:
XS GIS Cut Line= 3
      2758103.83      6810727.88      2757876.00      6810861.00
      2757630.59      6811079.71
#Sta/Elev= 30
  4731.8  444.50  4768.8  442.76  4784.5  440.94  4811.8  440.08  4864.7  436.69
  4891.9  435.82  4916.6  435.88  4944.8  435.51  4960.5  434.57  4987.8  422.09
  4990.8  419.09  4991.0  418.59  4994.5  418.59  4994.8  419.09  5002.8  419.78
  5009.5  422.35  5031.2  425.25  5037.9  429.94  5052.1  434.71  5129.9  435.00
  5138.4  434.41  5144.1  433.11  5151.6  427.50  5158.3  425.46  5165.8  424.52
  5180.0  426.91  5194.2  431.80  5208.5  435.40  5307.1  440.62  5324.4  442.07
#Mann=5,-1,0
  4731.8    0.05       0  4916.6    0.12       0  4990.8    0.07       0
  4994.8    0.12       0  5138.4    0.05       0
Bank Sta=4990.8,4994.8
Exp/Cntr=0.3,0.1

Type RM Length L Ch R = 1,2545,256,256,256
BEGIN DESCRIPTION:
Clear Creek T 15 8.0
END DESCRIPTION:
XS GIS Cut Line= 3
      2758141.67      6810382.42      2757676.00      6810711.00
      2757535.18      6810830.94
#Sta/Elev= 30
  4430.3  439.53  4461.7  437.22  4534.8  434.28  4641.9  433.51  4662.8  434.97
  4728.1  432.65  4820.4  433.07  4927.5  431.89  4957.1  432.63  4963.5  430.76
  4971.9  422.01  4978.0  414.38  4984.7  410.92  4985.0  410.42  4988.7  410.92
  4992.8  412.94  4997.2  418.97  5003.5  418.97  5007.4  426.10  5013.9  427.91
  5021.6  432.61  5028.2  431.20  5038.6  431.18  5054.4  431.14  5064.5  431.64
  5071.0  430.68  5078.8  431.66  5085.3  430.58  5099.6  433.53  5185.2  438.82
#Mann=5,-1,0
  4430.3    0.05       0  4984.7    0.04       0  4988.7    0.05       0
  5038.6     0.1       0  5054.4    0.05       0
Bank Sta=4984.7,4988.7
Exp/Cntr=0.3,0.1

Type RM Length L Ch R = 1,2289,250,250,250
BEGIN DESCRIPTION:
Clear Creek T 15 7.0
END DESCRIPTION:
XS GIS Cut Line= 3
      2758061.08      6810291.75      2757526.00      6810511.00
      2757373.17      6810690.62
#Sta/Elev= 30
  4416.4  438.28  4451.4  436.12  4573.2  431.74  4582.2  430.95  4587.6  431.43
  4605.6  430.90  4635.6  431.09  4681.3  429.84  4735.3  429.85  4766.4  429.26
  4801.2  429.63  4922.5  429.31  4940.6  429.75  4956.0  429.42  4973.0  425.68
  4980.0  426.12  4985.4  420.69  4992.0  414.92  4997.9  414.92  5006.4  410.81
  5006.6  410.31  5010.1  410.31  5010.4  410.81  5016.1  414.80  5022.6  423.80
  5030.4  424.94  5036.9  429.60  5143.5  433.25  5190.1  436.39  5230.5  438.13
#Mann=5,-1,0
  4416.4    0.05       0  4922.5     0.1       0  5006.4    0.07       0
  5010.4     0.1       0  5190.1    0.05       0
Bank Sta=5006.4,5010.4
Exp/Cntr=0.3,0.1

Type RM Length L Ch R = 1,2039,240,240,240
BEGIN DESCRIPTION:
Clear Creek T 15 6.0
END DESCRIPTION:
XS GIS Cut Line= 3
      2758076.55      6809958.75      2757476.00      6810311.00
      2757175.97      6810411.01
#Sta/Elev= 30
  4308.2  450.10  4478.8  438.04  4727.2  427.81  4740.6  427.92  4762.1  420.54
  4772.0  423.63  4777.8  420.45  4793.4  420.13  4799.2  425.37  4807.4  426.00
  4836.4  420.79  4842.2  423.26  4852.1  421.48  4857.9  425.12  4865.3  421.42
  4879.3  427.83  4898.6  427.57  4904.1  427.57  4938.0  428.11  4946.5  424.15
  4953.6  415.17  4959.4  415.52  4967.3  408.38  4967.6  407.88  4971.3  408.38
  4981.3  411.19  5001.5  423.92  5015.0  427.31  5153.7  430.68  5320.7  440.41
#Mann=7,-1,0
  4308.2    0.05       0  4727.2    0.12       0  4898.6    0.05       0
  4904.1     0.1       0  4967.3    0.07       0  4971.3     0.1       0
  5153.7    0.05       0
Bank Sta=4967.3,4971.3
Exp/Cntr=0.3,0.1

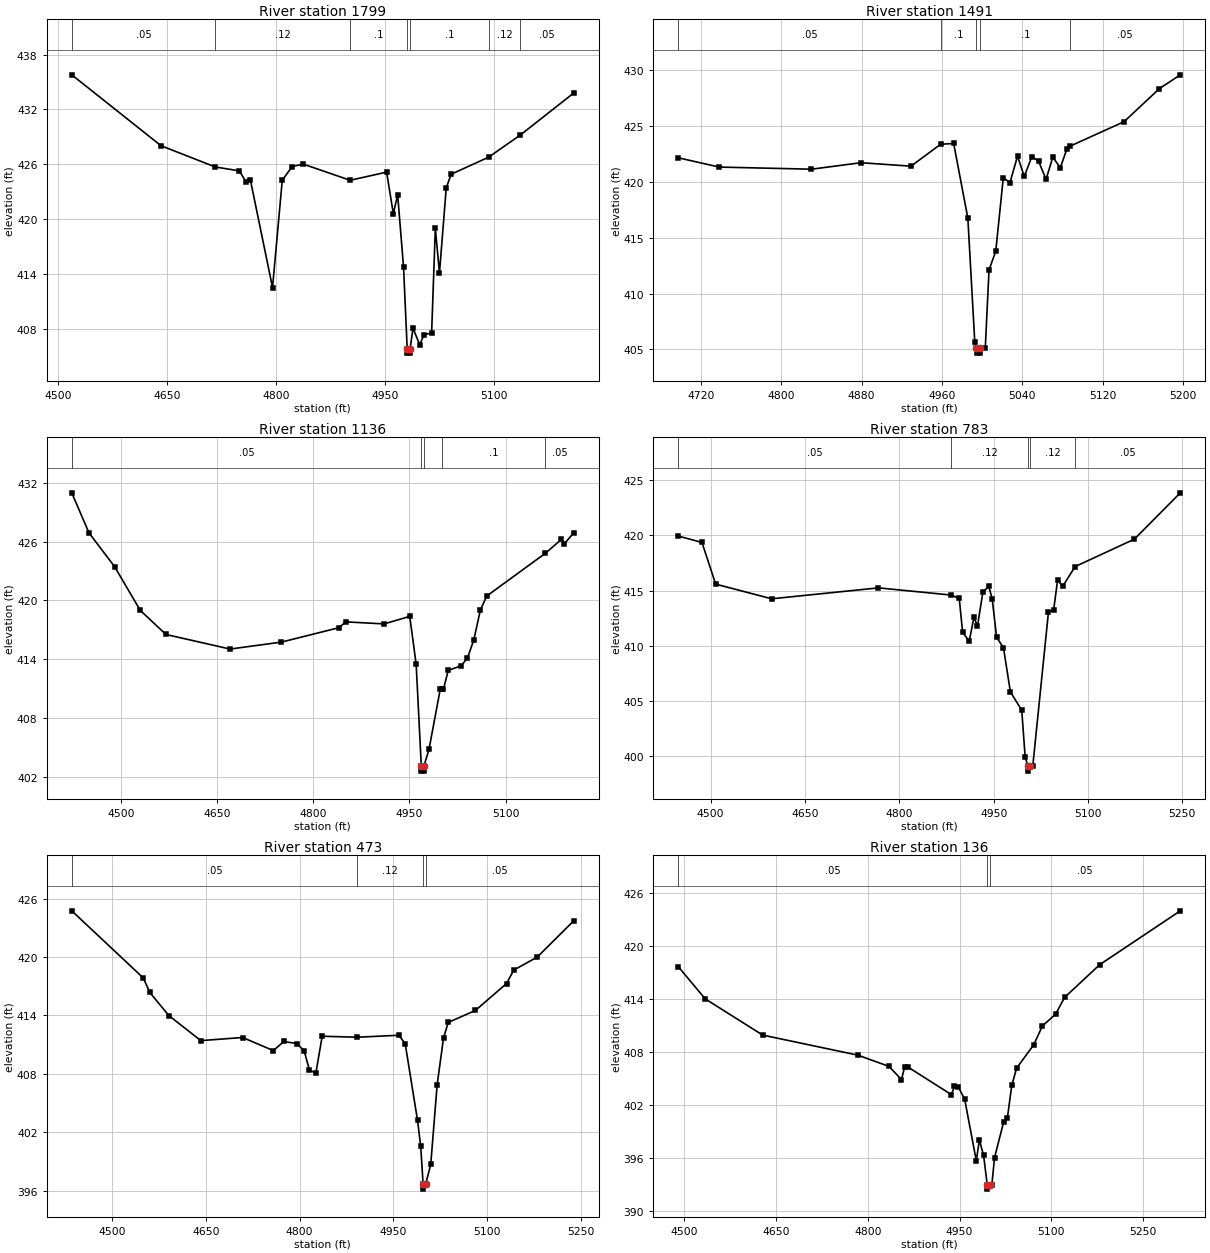
Type RM Length L Ch R = 1,1799,308,308,308
BEGIN DESCRIPTION:
Clear Creek T 15 5.0
END DESCRIPTION:
XS GIS Cut Line= 3
      2757788.96      6809843.49      2757376.00      6810111.00
      2757202.90      6810208.09
#Sta/Elev= 30
  4519.1  435.79  4641.8  428.04  4716.6  425.71  4749.7  425.29  4758.9  424.05
  4764.8  424.28  4795.2  412.53  4808.6  424.27  4822.2  425.76  4837.4  426.03
  4901.9  424.26  4952.1  425.15  4961.3  420.62  4967.3  422.66  4975.4  414.76
  4980.4  405.86  4980.7  405.36  4984.2  405.36  4984.4  405.86  4988.4  408.07
  4997.6  406.29  5003.6  407.36  5014.0  407.57  5019.1  419.00  5024.8  414.14
  5034.1  423.42  5040.8  424.92  5092.3  426.78  5136.2  429.22  5209.6  433.81
#Mann=7,-1,0
  4519.1    0.05       0  4716.6    0.12       0  4901.9     0.1       0
  4980.4    0.07       0  4984.4     0.1       0  5092.3    0.12       0
  5136.2    0.05       0
Bank Sta=4980.4,4984.4
Exp/Cntr=0.3,0.1

Type RM Length L Ch R = 1,1491,355,355,355
BEGIN DESCRIPTION:
Clear Creek T 15 4.0
END DESCRIPTION:
XS GIS Cut Line= 3
      2757496.26      6809653.81      2757276.00      6809861.00
      2757143.34      6810007.45
#Sta/Elev= 30
  4697.4  422.14  4738.2  421.31  4830.1  421.12  4879.4  421.70  4929.2  421.39
  4958.7  423.35  4971.7  423.42  4985.8  416.75  4992.7  405.69  4994.4  405.17
  4994.6  404.67  4998.1  404.67  4998.4  405.17  5003.2  405.17  5006.9  412.11
  5013.6  413.78  5021.1  420.34  5027.8  419.93  5035.3  422.29  5042.0  420.47
  5049.5  422.23  5056.2  421.85  5063.7  420.21  5070.4  422.20  5077.9  421.25
  5084.6  422.97  5087.6  423.18  5141.4  425.37  5176.5  428.32  5197.4  429.56
#Mann=5,-1,0
  4697.4    0.05       0  4958.7     0.1       0  4994.4    0.07       0
  4998.4     0.1       0  5087.6    0.05       0
Bank Sta=4994.4,4998.4
Exp/Cntr=0.3,0.1

Type RM Length L Ch R = 1,1136,353,353,353
BEGIN DESCRIPTION:
Clear Creek T 15 3.0
END DESCRIPTION:
XS GIS Cut Line= 3
      2757039.53      6809084.24      2757026.00      6809661.00
      2757020.51      6809866.71
#Sta/Elev= 30
  4423.6  431.00  4450.4  426.91  4490.4  423.45  4530.4  418.98  4570.4  416.52
  4670.4  415.03  4750.4  415.74  4840.5  417.22  4850.5  417.81  4910.5  417.60
  4950.5  418.37  4960.5  413.46  4968.5  403.05  4968.8  402.55  4972.3  402.55
  4972.5  403.05  4980.5  404.77  4998.0  410.92  5000.3  410.92  5003.0  410.92
  5010.5  412.85  5030.5  413.31  5040.5  414.12  5050.5  416.00  5060.5  419.00
  5070.5  420.45  5161.9  424.82  5186.7  426.23  5191.7  425.80  5206.3  426.93
#Mann=5,-1,0
  4423.6    0.05       0  4968.5    0.04       0  4972.5    0.05       0
  5000.3     0.1       0  5161.9    0.05       0
Bank Sta=4968.5,4972.5
Exp/Cntr=0.3,0.1

Type RM Length L Ch R = 1,783,310,310,310
BEGIN DESCRIPTION:
Clear Creek T 15 2.0
END DESCRIPTION:
XS GIS Cut Line= 3
      2756948.54      6809196.41      2756726.00      6809711.00
      2756579.79      6809898.35
#Sta/Elev= 30
  4448.5  419.94  4486.2  419.36  4508.0  415.58  4597.0  414.25  4766.9  415.24
  4882.3  414.59  4895.3  414.28  4900.7  411.20  4911.1  410.41  4918.8  412.59
  4924.2  411.74  4932.9  414.86  4942.3  415.37  4947.7  414.25  4954.7  410.75
  4965.6  409.82  4976.6  405.81  4994.7  404.14  5000.1  399.89  5004.4  399.12
  5004.7  398.62  5008.4  399.12  5012.3  399.12  5037.2  413.07  5045.3  413.19
  5051.7  415.95  5059.8  415.38  5079.5  417.17  5173.8  419.66  5246.8  423.86
#Mann=5,-1,0
  4448.5    0.05       0  4882.3    0.12       0  5004.4    0.07       0
  5008.4    0.12       0  5079.5    0.05       0
Bank Sta=5004.4,5008.4
Exp/Cntr=0.3,0.1

Type RM Length L Ch R = 1,473,337,337,337
BEGIN DESCRIPTION:
Mapping XS 4197bc3e
END DESCRIPTION:
XS GIS Cut Line= 2
      2756608.87      6809008.96      2756439.04      6809795.02
#Sta/Elev= 30
  4435.1  424.74  4549.7  417.85  4560.0  416.37  4590.6  413.99  4641.8  411.42
  4708.7  411.74  4758.0  410.40  4774.8  411.33  4795.3  411.12  4807.2  410.40
  4815.7  408.42  4826.0  408.06  4836.2  411.87  4892.6  411.77  4959.0  411.97
  4969.2  411.10  4988.9  403.24  4994.0  400.58  4997.9  396.68  4998.1  396.18
  5001.9  396.68  5010.1  398.72  5020.3  406.87  5030.6  411.71  5038.2  413.29
  5081.7  414.52  5131.5  417.28  5143.1  418.66  5180.8  420.00  5239.3  423.73
#Mann=4,-1,0
  4435.1    0.05       0  4892.6    0.12       0  4997.9    0.05       0
  5001.9    0.05       0
Bank Sta=4997.9,5001.9
Exp/Cntr=0.3,0.1

Type RM Length L Ch R = 1,136,0,0,0
BEGIN DESCRIPTION:
Clear Creek T 15 1.0
END DESCRIPTION:
XS GIS Cut Line= 3
      2756323.00      6809017.25      2756196.21      6809511.34
      2756366.45      6809771.60
#Sta/Elev= 30
  4489.9  417.70  4534.0  414.04  4628.0  409.93  4783.8  407.65  4834.5  406.38
  4855.0  404.88  4860.1  406.30  4865.4  406.31  4936.5  403.18  4941.7  404.10
  4948.0  404.04  4958.4  402.63  4977.3  395.68  4982.4  398.01  4989.3  396.27
  4995.2  392.95  4995.5  392.45  4999.2  392.95  5002.8  392.95  5007.2  396.03
  5022.3  400.12  5028.2  400.52  5035.4  404.25  5043.4  406.19  5071.3  408.83
  5085.5  410.97  5107.1  412.31  5121.7  414.20  5179.0  417.91  5311.0  424.03
#Mann=3,-1,0
  4489.9    0.05       0  4995.2    0.05       0  4999.2    0.05       0
Bank Sta=4995.2,4999.2
Exp/Cntr=0.3,0.1

Chan Stop Cuts=-1