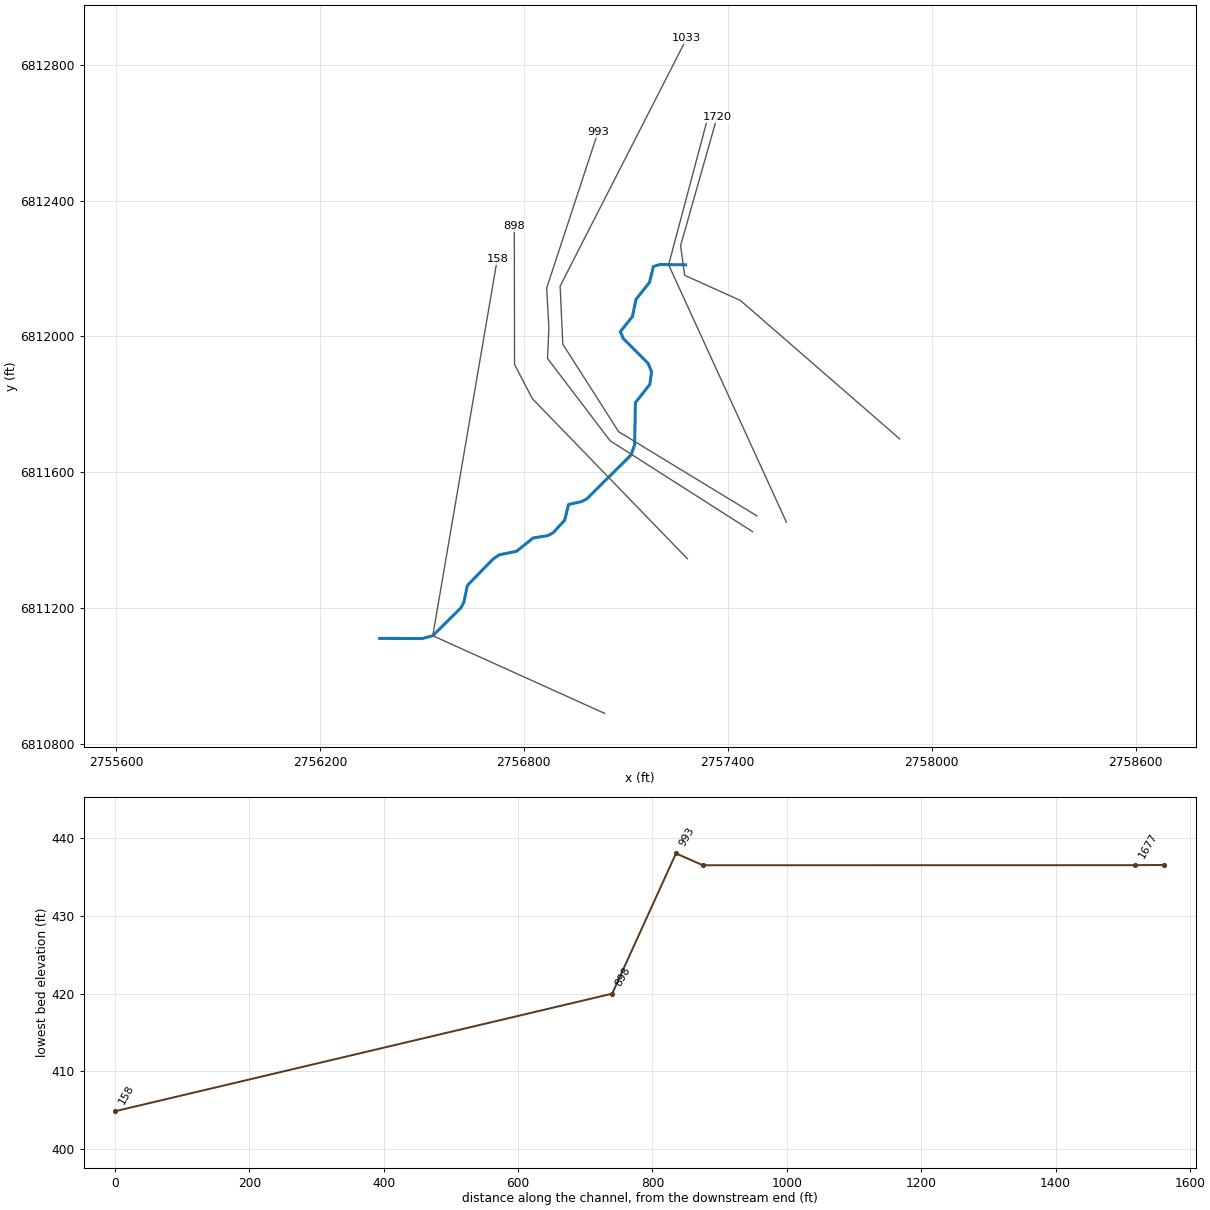
--- Clear Creek T 16.prj (project) ---

Proj Title=Clear Creek T 16 Base Level Engineering
Current Plan=p01
Default Exp/Contr=0.3,0.1
English Units
Geom File=g01
Flow File=f01
Plan File=p01
BEGIN DESCRIPTION:
Clear Creek T 16
END DESCRIPTION:

--- Clear Creek T 16.p01 (plan) ---

Plan Title=Multiple Run
Short Identifier=Multiple
Geom File=g01
Flow File=f01
Subcritical Flow
K Sum by GR= 0
Std Step Tol= 0.01
Critical Tol= 0.01
Num of Std Step Trials= 20
Max Error Tol= 0.3
Flow Tol Ratio= 0.001
Split Flow NTrial= 30
Split Flow Tol= 0.02
Split Flow Ratio= 0.02
Log Output Level= 0
Friction Slope Method= 1
Unsteady Friction Slope Method= 2
Unsteady Bridges Friction Slope Method= 1
Parabolic Critical Depth
Global Vel Dist=  1 , 1 , 1
Global Log Level= 0
CheckData=True
Encroach Param= -1, 0, 0, 0
BEGIN DESCRIPTION:
Multiple Run
END DESCRIPTION:

--- Clear Creek T 16.f01 (steady flow) ---

Flow Title=Multiple
Number of Profiles=7
Profile Names=10-year,25-year,50-year,1pct_min,100-year,1pct_plu,500-year
River Rch & RM= Clear Creek T 16,Reach-1,1720
     266     346     410     243     486     969     679
Boundary for River Rch & Prof#=Clear Creek T 16,Reach-1,1
Up Type=0
Dn Type=3
Dn Slope=0.005
Boundary for River Rch & Prof#=Clear Creek T 16,Reach-1,2
Up Type=0
Dn Type=3
Dn Slope=0.005
Boundary for River Rch & Prof#=Clear Creek T 16,Reach-1,3
Up Type=0
Dn Type=3
Dn Slope=0.005
Boundary for River Rch & Prof#=Clear Creek T 16,Reach-1,4
Up Type=0
Dn Type=3
Dn Slope=0.005
Boundary for River Rch & Prof#=Clear Creek T 16,Reach-1,5
Up Type=0
Dn Type=3
Dn Slope=0.005
Boundary for River Rch & Prof#=Clear Creek T 16,Reach-1,6
Up Type=0
Dn Type=3
Dn Slope=0.005
Boundary for River Rch & Prof#=Clear Creek T 16,Reach-1,7
Up Type=0
Dn Type=3
Dn Slope=0.005

--- Clear Creek T 16.g01 (geometry) ---

Geom Title=Existing Conditions

River Reach=Clear Creek T 16,Reach-1
Reach XY= 30
      2757276.00      6812211.00      2757200.43      6812211.73
      2757181.27      6812206.01      2757169.78      6812159.17
      2757130.11      6812109.30      2757119.59      6812058.70
      2757083.85      6812014.23      2757092.32      6811994.31
      2757165.77      6811920.68      2757176.04      6811895.66
      2757170.65      6811858.83      2757128.30      6811805.07
      2757126.02      6811680.99      2757115.52      6811651.20
      2756985.42      6811521.89      2756969.57      6811513.69
      2756931.63      6811505.35      2756920.11      6811458.79
      2756885.98      6811421.69      2756870.14      6811413.45
      2756827.76      6811406.80      2756778.19      6811367.10
      2756727.62      6811357.06      2756709.29      6811344.37
      2756634.15      6811267.06      2756623.47      6811217.04
      2756615.23      6811201.30      2756532.22      6811118.78
      2756501.16      6811110.62      2756376.00      6811111.00

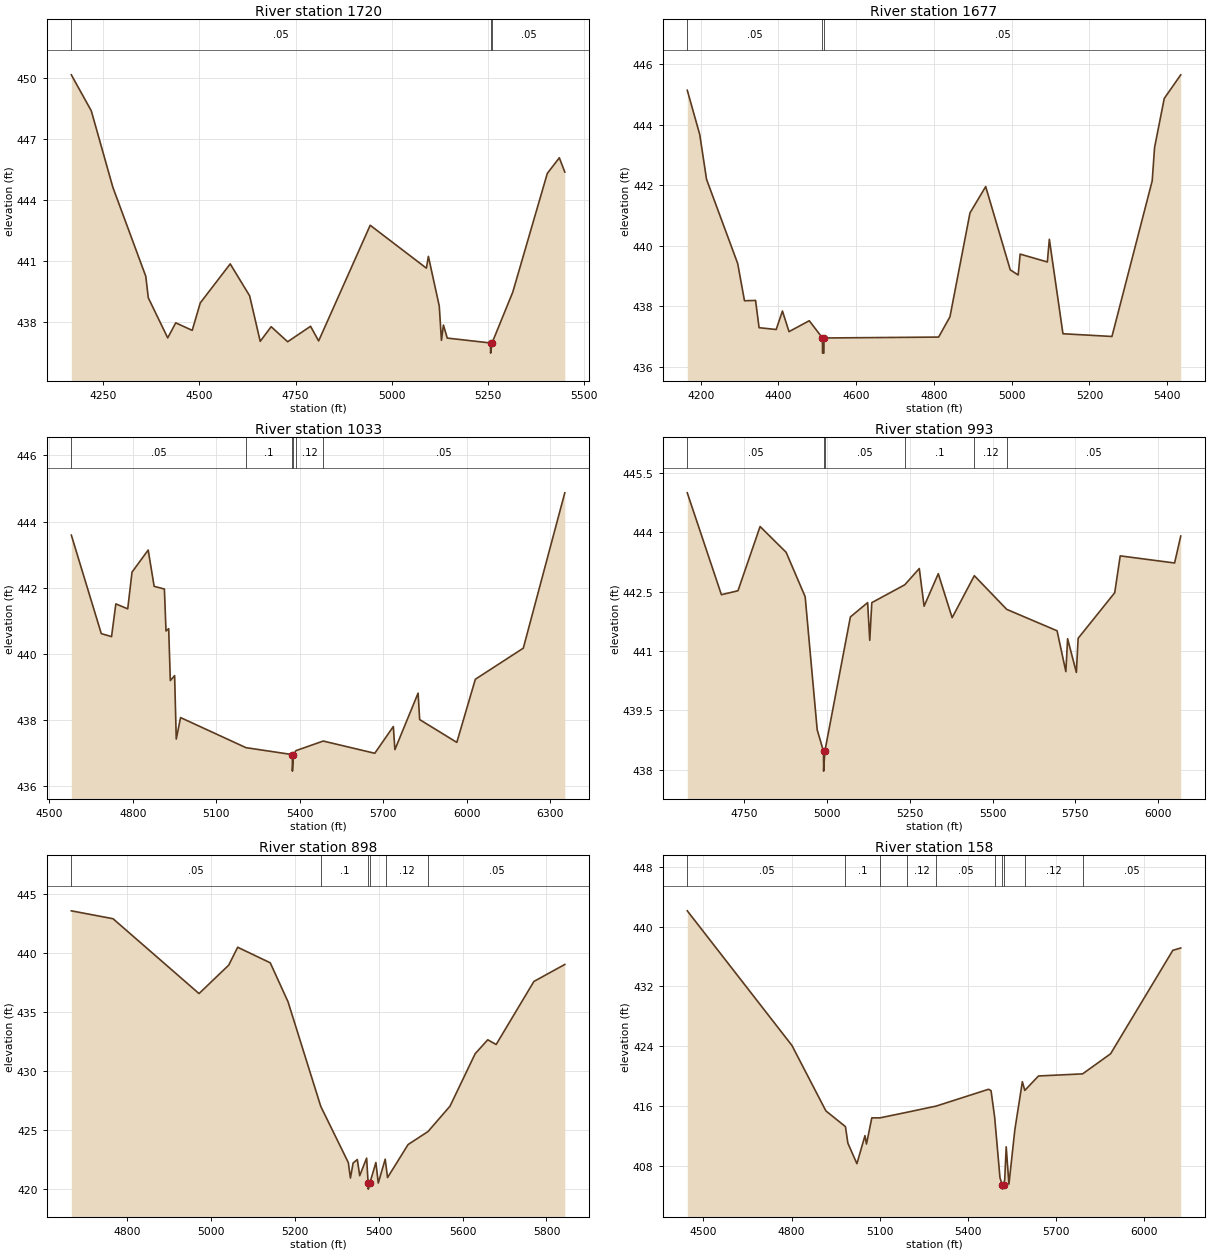
Type RM Length L Ch R = 1,1720,43,43,43
BEGIN DESCRIPTION:
2486
END DESCRIPTION:
XS GIS Cut Line= 5
      2757905.87      6811698.30      2757437.18      6812106.00
      2757273.28      6812179.95      2757261.28      6812267.50
      2757368.21      6812644.66
#Sta/Elev= 30
  4167.6  450.18  4219.4  448.41  4275.4  444.65  4360.9  440.27  4367.5  439.21
  4417.9  437.24  4438.7  437.98  4481.5  437.61  4502.4  438.96  4580.2  440.88
  4630.6  439.31  4658.1  437.07  4686.5  437.79  4729.3  437.05  4788.8  437.81
  4809.8  437.09  4943.7  442.78  5089.6  440.67  5094.8  441.25  5123.0  438.81
  5128.7  437.12  5133.9  437.87  5143.8  437.23  5256.1  436.99  5256.4  436.49
  5260.1  436.99  5313.9  439.49  5403.6  445.33  5434.8  446.10  5449.0  445.40
#Mann=3,-1,0
  4167.6    0.05       0  5256.1    0.04       0  5260.1    0.05       0
Bank Sta=5256.1,5260.1
Exp/Cntr=0.3,0.1

Type RM Length L Ch R = 1,1677,644,644,644
BEGIN DESCRIPTION:
2076
END DESCRIPTION:
XS GIS Cut Line= 3
      2757572.55      6811453.09      2757226.00      6812211.00
      2757338.04      6812631.97
#Sta/Elev= 30
  4165.7  445.14  4197.7  443.68  4215.2  442.20  4295.3  439.42  4312.8  438.19
  4341.3  438.20  4350.3  437.30  4394.3  437.24  4410.4  437.85  4427.3  437.17
  4479.4  437.53  4513.3  436.96  4513.5  436.46  4517.0  436.46  4517.3  436.96
  4812.1  436.99  4841.2  437.66  4892.7  441.09  4933.1  441.96  4996.3  439.21
  5016.6  439.04  5021.7  439.73  5091.7  439.47  5096.8  440.22  5131.8  437.10
  5257.8  437.01  5361.3  442.15  5367.4  443.25  5392.3  444.87  5434.7  445.65
#Mann=3,-1,0
  4165.7    0.05       0  4513.3    0.04       0  4517.3    0.05       0
Bank Sta=4513.3,4517.3
Exp/Cntr=0.3,0.1

Type RM Length L Ch R = 1,1033,40,40,40
BEGIN DESCRIPTION:
2387
END DESCRIPTION:
XS GIS Cut Line= 5
      2757485.70      6811471.76      2757079.00      6811719.46
      2756914.66      6811977.41      2756906.83      6812148.23
      2757279.23      6812877.73
#Sta/Elev= 30
  4579.3  443.59  4686.9  440.61  4723.7  440.52  4739.1  441.51  4781.8  441.36
  4797.2  442.47  4855.3  443.14  4876.7  442.04  4913.5  441.96  4919.3  440.69
  4928.9  440.76  4934.8  439.19  4950.2  439.34  4956.1  437.42  4971.6  438.07
  5206.4  437.16  5373.0  436.95  5373.2  436.45  5377.0  436.95  5386.0  437.07
  5483.9  437.36  5669.0  436.99  5735.7  437.80  5741.3  437.10  5824.6  438.81
  5830.2  438.01  5963.6  437.32  6030.2  439.23  6202.4  440.17  6351.4  444.87
#Mann=6,-1,0
  4579.3    0.05       0  5206.4     0.1       0  5373.0    0.04       0
  5377.0     0.1       0  5386.0    0.12       0  5483.9    0.05       0
Bank Sta=5373,5377
Exp/Cntr=0.3,0.1

Type RM Length L Ch R = 1,993,95,95,95
BEGIN DESCRIPTION:
2265
END DESCRIPTION:
XS GIS Cut Line= 6
      2757472.85      6811425.32      2757053.91      6811692.88
      2756869.73      6811935.18      2756873.75      6812025.56
      2756867.23      6812142.30      2757017.84      6812600.55
#Sta/Elev= 30
  4577.4  444.99  4680.5  442.42  4730.6  442.52  4797.4  444.14  4876.1  443.49
  4933.6  442.37  4970.0  439.01  4989.1  438.47  4989.4  437.97  4993.1  438.47
  5070.3  441.86  5122.4  442.22  5128.8  441.27  5135.0  442.22  5234.6  442.67
  5278.5  443.08  5293.0  442.13  5335.9  442.95  5377.8  441.84  5444.8  442.90
  5542.8  442.05  5694.9  441.51  5721.4  440.48  5726.7  441.31  5753.2  440.46
  5758.5  441.32  5869.1  442.47  5885.7  443.40  6050.0  443.22  6068.6  443.90
#Mann=6,-1,0
  4577.4    0.05       0  4989.1    0.04       0  4993.1    0.05       0
  5234.6     0.1       0  5444.8    0.12       0  5542.8    0.05       0
Bank Sta=4989.1,4993.1
Exp/Cntr=0.3,0.1

Type RM Length L Ch R = 1,898,740,740,740
BEGIN DESCRIPTION:
2386
END DESCRIPTION:
XS GIS Cut Line= 4
      2757281.05      6811345.58      2756824.81      6811817.19
      2756772.74      6811917.67      2756772.04      6812324.62
#Sta/Elev= 30
  4667.4  443.59  4766.8  442.92  4971.8  436.57  5042.5  438.98  5063.9  440.50
  5141.6  439.18  5184.0  435.87  5262.0  427.00  5327.7  422.23  5332.7  420.92
  5339.1  422.20  5349.2  422.49  5354.8  421.12  5371.3  422.61  5374.9  420.48
  5375.2  419.98  5378.9  420.48  5393.4  422.24  5399.1  420.50  5415.6  422.52
  5417.9  421.88  5421.2  420.96  5470.1  423.76  5517.8  424.87  5570.1  427.02
  5630.1  431.47  5660.1  432.65  5680.1  432.25  5770.1  437.60  5843.7  439.04
#Mann=6,-1,0
  4667.4    0.05       0  5262.0     0.1       0  5374.9    0.04       0
  5378.9     0.1       0  5417.9    0.12       0  5517.8    0.05       0
Bank Sta=5374.9,5378.9
Exp/Cntr=0.3,0.1

Type RM Length L Ch R = 1,158,0,0,0
BEGIN DESCRIPTION:
2075
END DESCRIPTION:
XS GIS Cut Line= 3
      2757037.75      6810890.22      2756532.22      6811118.78
      2756721.90      6812227.47
#Sta/Elev= 30
  4445.2  442.11  4801.4  424.11  4917.0  415.36  4983.5  413.26  4991.8  411.05
  5022.5  408.30  5050.0  412.05  5055.1  410.93  5073.3  414.43  5101.1  414.43
  5192.2  415.17  5292.0  416.00  5470.6  418.25  5479.1  418.07  5491.5  414.49
  5509.5  406.43  5517.7  405.40  5517.9  404.90  5521.7  405.40  5525.6  406.13
  5530.7  410.56  5540.0  405.57  5560.2  412.86  5585.7  419.26  5594.0  418.10
  5640.7  420.03  5790.8  420.31  5886.1  423.00  6097.9  436.83  6124.8  437.14
#Mann=10,-1,0
  4445.2    0.05       0  4983.5     0.1       0  5101.1    0.05       0
  5192.2    0.12       0  5292.0    0.05       0  5491.5     0.1       0
  5517.7    0.07       0  5521.7     0.1       0  5594.0    0.12       0
  5790.8    0.05       0
Bank Sta=5517.7,5521.7
Exp/Cntr=0.3,0.1

Chan Stop Cuts=-1