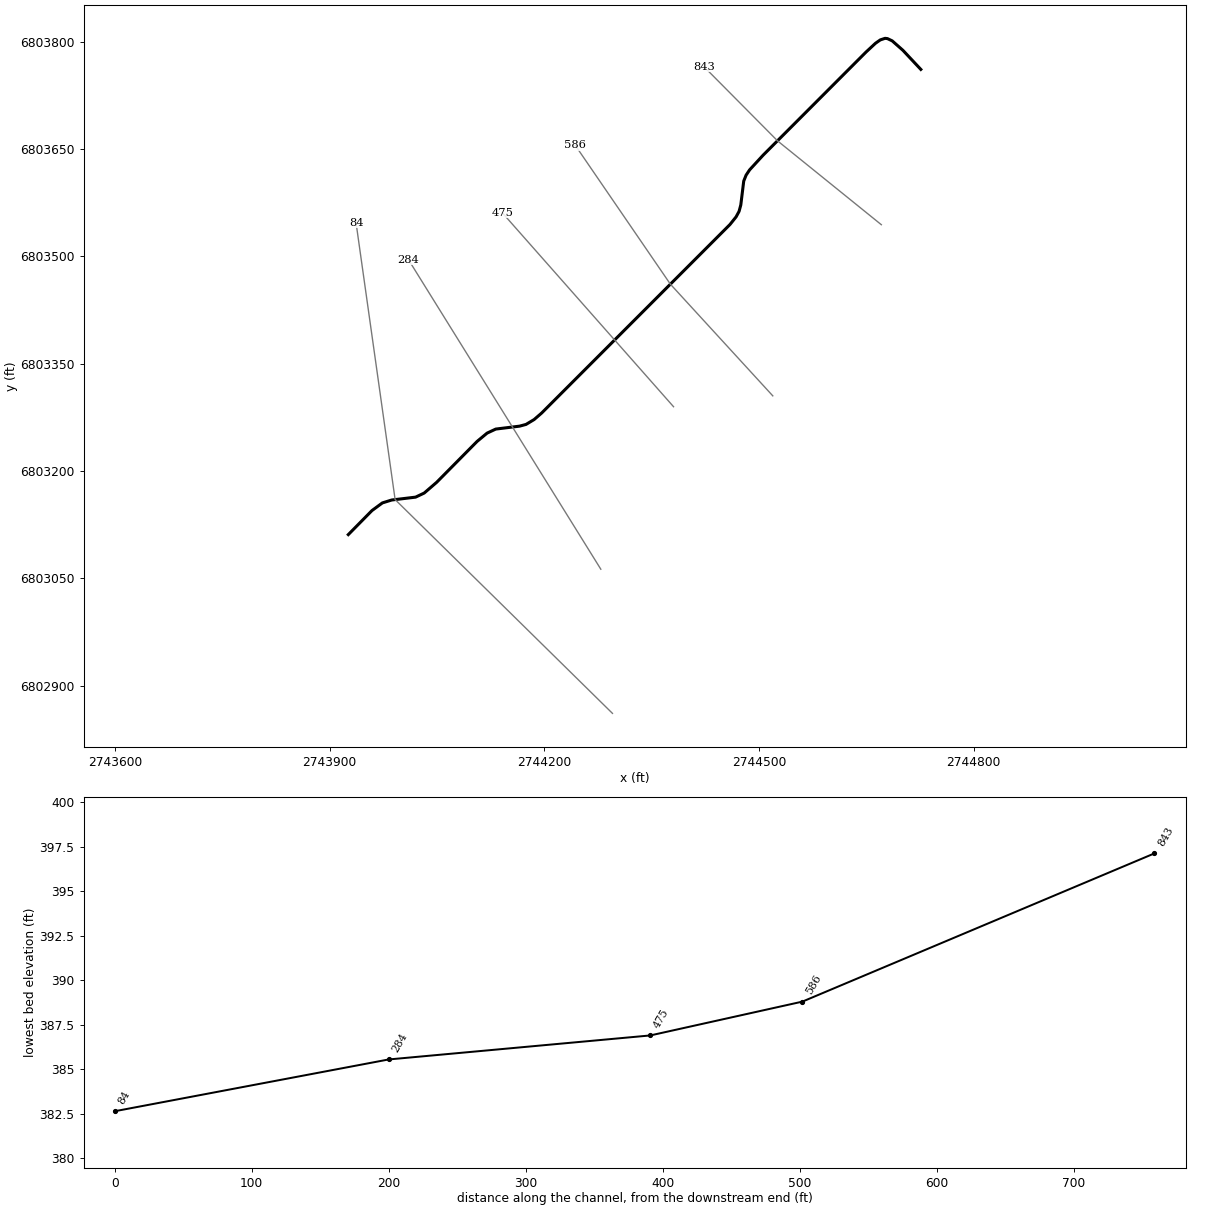
--- Clear Creek T 17.prj (project) ---

Proj Title=Clear Creek T 17 Base Level Engineering
Current Plan=p01
Default Exp/Contr=0.3,0.1
English Units
Geom File=g01
Flow File=f01
Plan File=p01
BEGIN DESCRIPTION:
Clear Creek T 17
END DESCRIPTION:

--- Clear Creek T 17.p01 (plan) ---

Plan Title=Multiple Run
Short Identifier=Multiple
Geom File=g01
Flow File=f01
Subcritical Flow
K Sum by GR= 0
Std Step Tol= 0.01
Critical Tol= 0.01
Num of Std Step Trials= 20
Max Error Tol= 0.3
Flow Tol Ratio= 0.001
Split Flow NTrial= 30
Split Flow Tol= 0.02
Split Flow Ratio= 0.02
Log Output Level= 0
Friction Slope Method= 1
Unsteady Friction Slope Method= 2
Unsteady Bridges Friction Slope Method= 1
Parabolic Critical Depth
Global Vel Dist=  1 , 1 , 1
Global Log Level= 0
CheckData=True
Encroach Param= -1, 0, 0, 0
BEGIN DESCRIPTION:
Multiple Run
END DESCRIPTION:

--- Clear Creek T 17.f01 (steady flow) ---

Flow Title=Multiple
Number of Profiles=7
Profile Names=10-year,25-year,50-year,1pct_min,100-year,1pct_plu,500-year
River Rch & RM= Clear Creek T 17,Reach-1,843
      98     117     132      74     148     295     186
Boundary for River Rch & Prof#=Clear Creek T 17,Reach-1,1
Up Type=0
Dn Type=3
Dn Slope=0.005
Boundary for River Rch & Prof#=Clear Creek T 17,Reach-1,2
Up Type=0
Dn Type=3
Dn Slope=0.005
Boundary for River Rch & Prof#=Clear Creek T 17,Reach-1,3
Up Type=0
Dn Type=3
Dn Slope=0.005
Boundary for River Rch & Prof#=Clear Creek T 17,Reach-1,4
Up Type=0
Dn Type=3
Dn Slope=0.005
Boundary for River Rch & Prof#=Clear Creek T 17,Reach-1,5
Up Type=0
Dn Type=3
Dn Slope=0.005
Boundary for River Rch & Prof#=Clear Creek T 17,Reach-1,6
Up Type=0
Dn Type=3
Dn Slope=0.005
Boundary for River Rch & Prof#=Clear Creek T 17,Reach-1,7
Up Type=0
Dn Type=3
Dn Slope=0.005

--- Clear Creek T 17.g01 (geometry) ---

Geom Title=Existing Conditions

River Reach=Clear Creek T 17,Reach-1
Reach XY= 30
      2744726.00      6803761.00      2744700.94      6803787.72
      2744686.00      6803800.90      2744679.33      6803804.06
      2744676.00      6803804.43      2744669.33      6803802.23
      2744662.67      6803797.56      2744649.33      6803785.17
      2744505.62      6803641.16      2744486.78      6803620.68
      2744481.86      6803613.29      2744478.53      6803604.95
      2744474.45      6803571.64      2744472.02      6803562.65
      2744467.84      6803554.95      2744459.35      6803544.33
      2744196.09      6803280.79      2744185.68      6803271.78
      2744174.35      6803264.97      2744165.36      6803262.55
      2744132.05      6803258.46      2744119.96      6803252.82
      2744105.93      6803241.17      2744049.45      6803184.05
      2744032.08      6803169.07      2744020.03      6803163.35
      2743986.68      6803159.35      2743973.65      6803155.30
      2743959.08      6803144.58      2743926.00      6803111.00

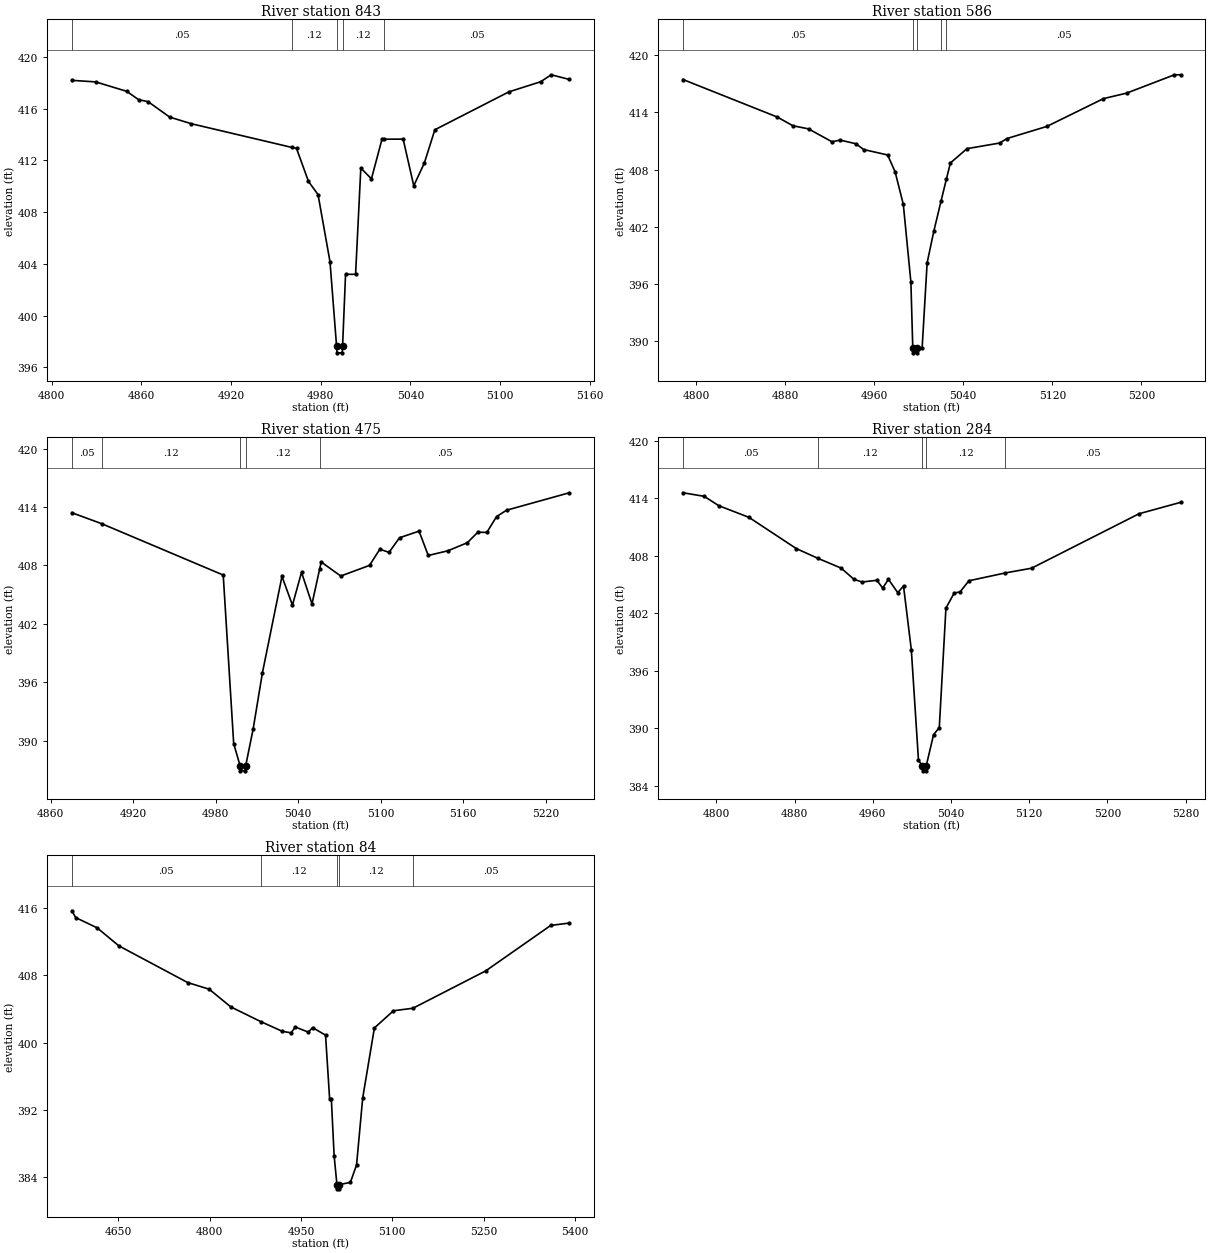
Type RM Length L Ch R = 1,843,257,257,257
BEGIN DESCRIPTION:
Clear Creek T 17 3.0
END DESCRIPTION:
XS GIS Cut Line= 3
      2744670.82      6803544.01      2744526.00      6803661.00
      2744422.86      6803764.94
#Sta/Elev= 30
  4813.6  418.19  4829.5  418.07  4850.3  417.34  4858.2  416.70  4864.6  416.54
  4879.0  415.35  4893.4  414.84  4960.9  413.00  4963.8  412.93  4971.8  410.38
  4978.2  409.36  4986.2  404.17  4990.6  397.63  4990.8  397.13  4994.3  397.13
  4994.6  397.63  4996.6  403.20  5003.3  403.20  5006.8  411.41  5013.9  410.58
  5021.0  413.66  5022.2  413.64  5035.1  413.65  5042.2  410.04  5049.3  411.81
  5056.3  414.37  5105.8  417.30  5127.0  418.08  5134.1  418.62  5146.2  418.26
#Mann=5,-1,0
  4813.6    0.05       0  4960.9    0.12       0  4990.6    0.07       0
  4994.6    0.12       0  5022.2    0.05       0
Bank Sta=4990.6,4994.6
Exp/Cntr=0.3,0.1

Type RM Length L Ch R = 1,586,111,111,111
BEGIN DESCRIPTION:
Clear Creek T 17 2.0
END DESCRIPTION:
XS GIS Cut Line= 3
      2744519.14      6803304.88      2744376.00      6803461.00
      2744243.09      6803655.03
#Sta/Elev= 30
  4788.2  417.43  4872.7  413.51  4886.9  412.59  4901.0  412.26  4922.0  410.91
  4929.4  411.09  4943.6  410.70  4950.4  410.10  4972.0  409.53  4978.7  407.77
  4986.1  404.35  4992.9  396.21  4994.6  389.30  4994.9  388.80  4998.4  388.80
  4998.6  389.30  5003.0  389.30  5007.5  398.23  5013.5  401.54  5020.1  404.75
  5024.8  407.00  5028.4  408.69  5043.3  410.19  5072.7  410.78  5079.2  411.25
  5115.1  412.52  5165.9  415.43  5186.8  416.01  5229.7  417.93  5235.2  417.93
#Mann=5,-1,0
  4788.2    0.05       0  4994.6    0.04       0  4998.6    0.05       0
  5020.1    0.12       0  5024.8    0.05       0
Bank Sta=4994.6,4998.6
Exp/Cntr=0.3,0.1

Type RM Length L Ch R = 1,475,191,191,191
BEGIN DESCRIPTION:
Mapping XS d63c5242
END DESCRIPTION:
XS GIS Cut Line= 2
      2744380.47      6803289.70      2744141.20      6803560.69
#Sta/Elev= 30
  4875.5  413.41  4897.1  412.29  4985.5  407.01  4993.1  389.70  4997.8  387.40
  4998.0  386.90  5001.5  386.90  5001.8  387.40  5007.3  391.24  5014.0  396.98
  5028.2  406.87  5035.8  403.92  5042.4  407.29  5050.0  404.04  5055.5  407.58
  5056.7  408.35  5070.9  406.91  5091.8  408.00  5099.3  409.66  5106.0  409.34
  5113.6  410.84  5127.8  411.52  5134.5  409.02  5148.7  409.50  5162.9  410.33
  5170.5  411.41  5177.1  411.39  5184.1  413.01  5191.4  413.67  5237.0  415.46
#Mann=5,-1,0
  4875.5    0.05       0  4897.1    0.12       0  4997.8    0.07       0
  5001.8    0.12       0  5055.5    0.05       0
Bank Sta=4997.8,5001.8
Exp/Cntr=0.3,0.1

Type RM Length L Ch R = 1,284,200,200,200
BEGIN DESCRIPTION:
Mapping XS f16d4750
END DESCRIPTION:
XS GIS Cut Line= 2
      2744278.85      6803062.64      2744010.26      6803494.88
#Sta/Elev= 30
  4766.0  414.56  4787.6  414.19  4802.6  413.21  4833.3  412.00  4881.8  408.74
  4904.2  407.71  4927.7  406.70  4940.7  405.54  4949.0  405.25  4964.2  405.43
  4970.2  404.62  4976.1  405.53  4985.6  404.14  4991.5  404.83  4999.5  398.17
  5006.8  386.67  5010.7  386.05  5011.0  385.55  5014.5  385.55  5014.7  386.05
  5022.2  389.31  5028.1  390.07  5034.9  402.53  5043.4  404.11  5049.3  404.21
  5058.4  405.38  5095.8  406.20  5122.5  406.69  5232.4  412.37  5274.9  413.56
#Mann=5,-1,0
  4766.0    0.05       0  4904.2    0.12       0  5010.7    0.07       0
  5014.7    0.12       0  5095.8    0.05       0
Bank Sta=5010.7,5014.7
Exp/Cntr=0.3,0.1

Type RM Length L Ch R = 1,84,0,0,0
BEGIN DESCRIPTION:
Clear Creek T 17 1.0
END DESCRIPTION:
XS GIS Cut Line= 3
      2744295.12      6802861.21      2743991.43      6803159.96
      2743936.83      6803546.82
#Sta/Elev= 30
  4574.0  415.68  4580.3  414.87  4615.6  413.65  4651.0  411.52  4764.2  407.15
  4799.5  406.36  4834.9  404.26  4884.2  402.51  4919.7  401.35  4933.9  401.18
  4940.9  401.87  4962.2  401.26  4969.2  401.80  4990.5  400.90  4997.2  393.33
  5000.0  393.33  5004.6  386.55  5009.2  383.14  5009.4  382.64  5012.9  382.64
  5013.2  383.14  5031.3  383.41  5041.4  385.48  5051.5  393.44  5070.7  401.76
  5102.0  403.80  5134.0  404.10  5253.5  408.54  5360.2  413.94  5390.7  414.22
#Mann=5,-1,0
  4574.0    0.05       0  4884.2    0.12       0  5009.2    0.07       0
  5013.2    0.12       0  5134.0    0.05       0
Bank Sta=5009.2,5013.2
Exp/Cntr=0.3,0.1

Chan Stop Cuts=-1