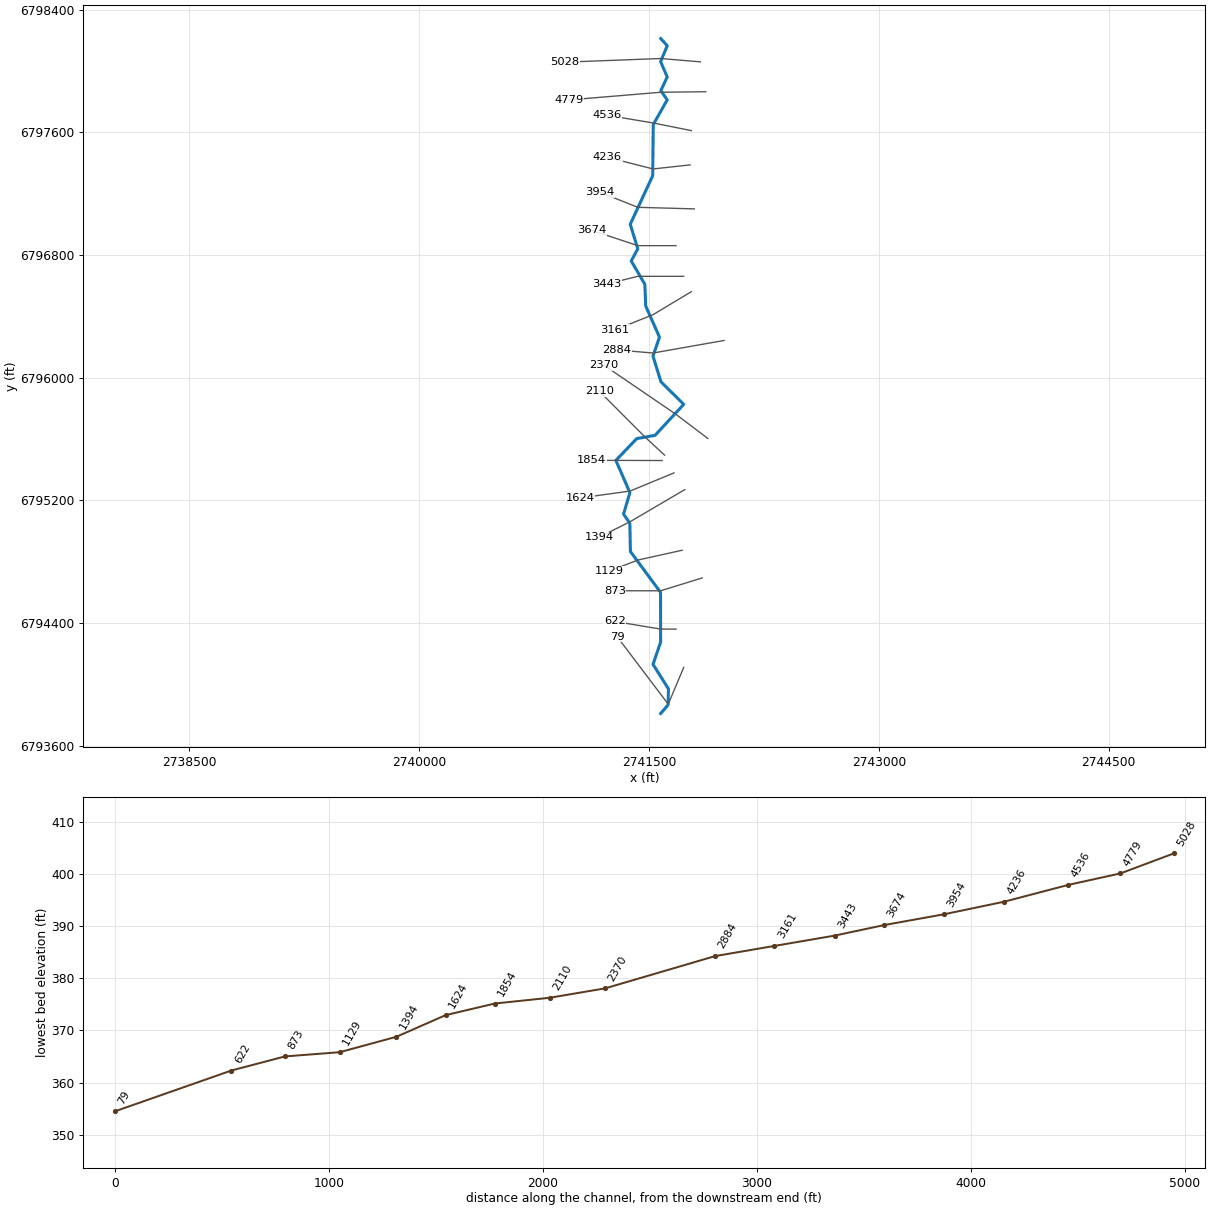
--- Clear Creek T 18.prj (project) ---

Proj Title=Clear Creek T 18 Base Level Engineering
Current Plan=p01
Default Exp/Contr=0.3,0.1
English Units
Geom File=g01
Flow File=f01
Plan File=p01
BEGIN DESCRIPTION:
Clear Creek T 18
END DESCRIPTION:

--- Clear Creek T 18.p01 (plan) ---

Plan Title=Multiple Run
Short Identifier=Multiple
Geom File=g01
Flow File=f01
Subcritical Flow
K Sum by GR= 0
Std Step Tol= 0.01
Critical Tol= 0.01
Num of Std Step Trials= 20
Max Error Tol= 0.3
Flow Tol Ratio= 0.001
Split Flow NTrial= 30
Split Flow Tol= 0.02
Split Flow Ratio= 0.02
Log Output Level= 0
Friction Slope Method= 1
Unsteady Friction Slope Method= 2
Unsteady Bridges Friction Slope Method= 1
Parabolic Critical Depth
Global Vel Dist=  1 , 1 , 1
Global Log Level= 0
CheckData=True
Encroach Param= -1, 0, 0, 0
BEGIN DESCRIPTION:
Multiple Run
END DESCRIPTION:

--- Clear Creek T 18.f01 (steady flow) ---

Flow Title=Multiple
Number of Profiles=7
Profile Names=10-year,25-year,50-year,1pct_min,100-year,1pct_plu,500-year
River Rch & RM= Clear Creek T 18,Reach-1,5028
     173     216     248     142     284     566     371
River Rch & RM= Clear Creek T 18,Reach-1,1129
     210     265     308     178     355     709     474
Boundary for River Rch & Prof#=Clear Creek T 18,Reach-1,1
Up Type=0
Dn Type=3
Dn Slope=0.005
Boundary for River Rch & Prof#=Clear Creek T 18,Reach-1,2
Up Type=0
Dn Type=3
Dn Slope=0.005
Boundary for River Rch & Prof#=Clear Creek T 18,Reach-1,3
Up Type=0
Dn Type=3
Dn Slope=0.005
Boundary for River Rch & Prof#=Clear Creek T 18,Reach-1,4
Up Type=0
Dn Type=3
Dn Slope=0.005
Boundary for River Rch & Prof#=Clear Creek T 18,Reach-1,5
Up Type=0
Dn Type=3
Dn Slope=0.005
Boundary for River Rch & Prof#=Clear Creek T 18,Reach-1,6
Up Type=0
Dn Type=3
Dn Slope=0.005
Boundary for River Rch & Prof#=Clear Creek T 18,Reach-1,7
Up Type=0
Dn Type=3
Dn Slope=0.005

--- Clear Creek T 18.g01 (geometry) ---

Geom Title=Existing Conditions

River Reach=Clear Creek T 18,Reach-1
Reach XY= 30
      2741576.00      6798211.00      2741618.76      6798164.45
      2741575.24      6798061.00      2741618.41      6797960.99
      2741576.98      6797871.64      2741618.44      6797811.00
      2741527.20      6797650.50      2741523.74      6797316.94
      2741377.09      6797000.46      2741426.21      6796840.79
      2741383.56      6796761.00      2741472.24      6796609.44
      2741478.27      6796466.94      2741567.92      6796264.30
      2741525.42      6796140.96      2741577.74      6795972.87
      2741726.11      6795826.36      2741539.30      6795624.40
      2741419.83      6795603.14      2741283.31      6795461.10
      2741374.89      6795250.45      2741333.56      6795111.00
      2741374.62      6795050.56      2741378.24      6794866.93
      2741574.95      6794600.57      2741575.48      6794276.22
      2741525.79      6794131.05      2741626.55      6793971.19
      2741624.12      6793866.79      2741576.00      6793811.00

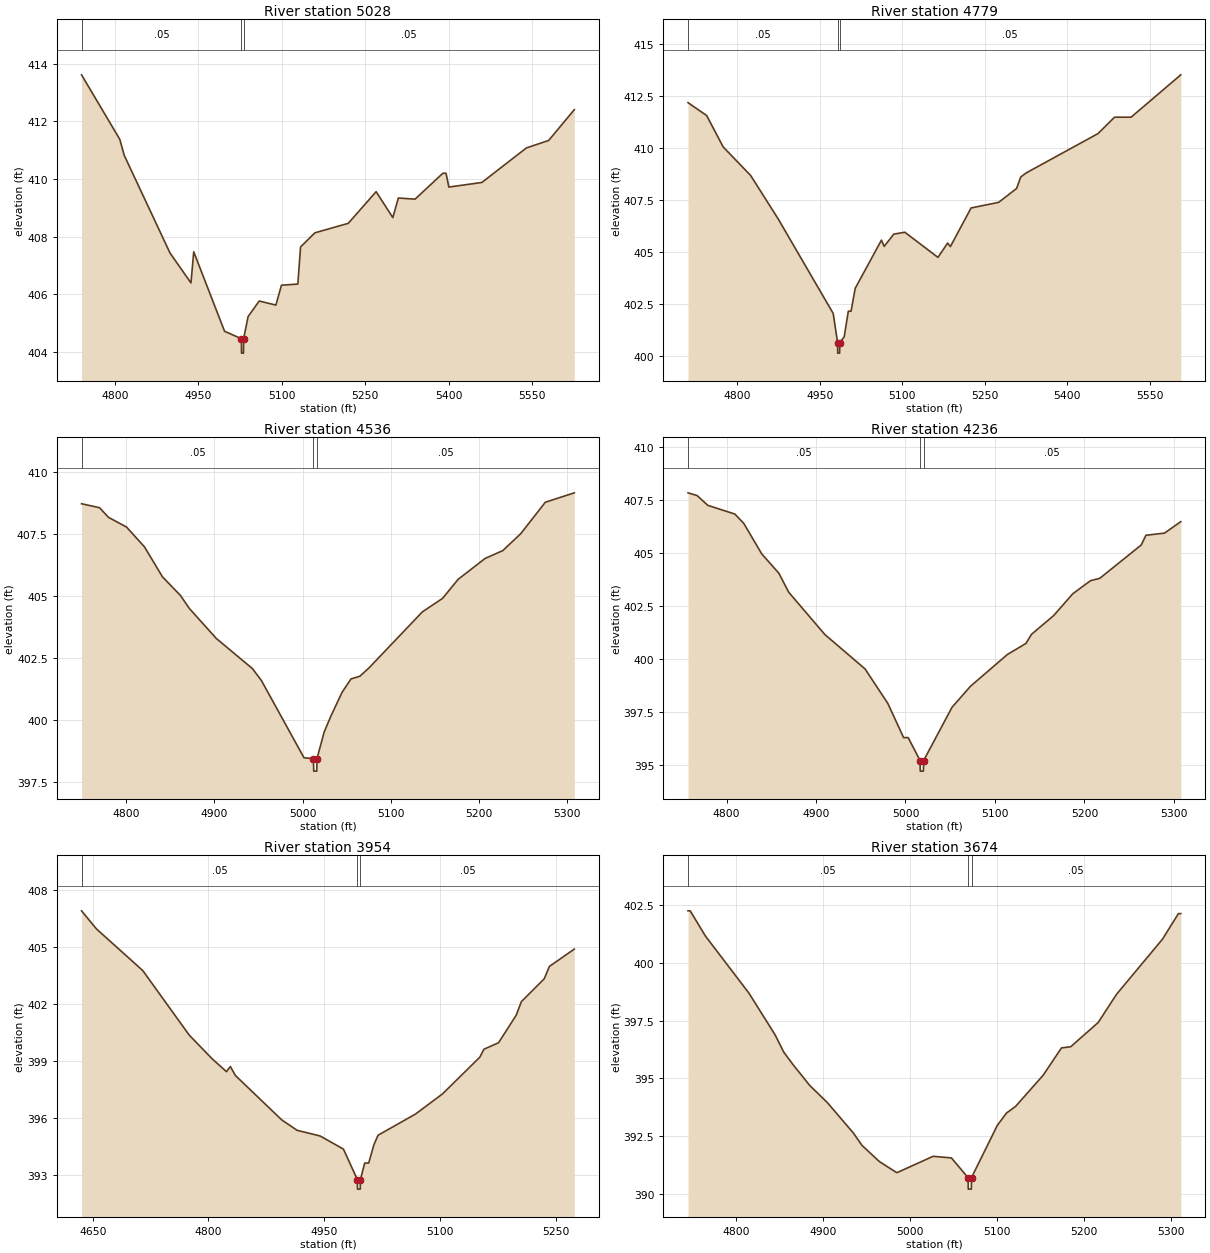
Type RM Length L Ch R = 1,5028,249,249,249
BEGIN DESCRIPTION:
Clear Creek T 18 18.0
END DESCRIPTION:
XS GIS Cut Line= 3
      2741834.45      6798059.32      2741575.47      6798081.07
      2740949.92      6798057.25
#Sta/Elev= 30
  4740.1  413.62  4808.8  411.38  4816.9  410.82  4899.1  407.43  4936.8  406.39
  4941.8  407.47  4997.2  404.71  5027.5  404.45  5027.7  403.95  5031.2  403.95
  5031.5  404.45  5039.5  405.22  5059.5  405.76  5089.5  405.62  5099.5  406.31
  5128.9  406.35  5133.9  407.64  5159.6  408.13  5219.6  408.46  5269.7  409.56
  5299.7  408.66  5309.7  409.34  5339.7  409.30  5389.7  410.20  5395.4  410.20
  5400.4  409.72  5459.8  409.88  5539.9  411.08  5579.9  411.34  5626.0  412.41
#Mann=3,-1,0
  4740.1    0.05       0  5027.5    0.05       0  5031.5    0.05       0
Bank Sta=5027.5,5031.5
Exp/Cntr=0.3,0.1

Type RM Length L Ch R = 1,4779,243,243,243
BEGIN DESCRIPTION:
Clear Creek T 18 17.0
END DESCRIPTION:
XS GIS Cut Line= 3
      2741869.94      6797864.47      2741576.00      6797861.00
      2740976.04      6797811.00
#Sta/Elev= 30
  4710.5  412.18  4744.4  411.56  4774.4  410.05  4824.5  408.67  4874.5  406.58
  4974.5  402.03  4982.5  400.62  4982.7  400.12  4986.2  400.12  4986.5  400.62
  4994.5  400.91  5002.0  402.14  5007.0  402.14  5014.5  403.24  5062.2  405.56
  5067.2  405.26  5084.7  405.85  5104.8  405.94  5165.0  404.73  5182.6  405.42
  5187.6  405.25  5225.2  407.11  5275.4  407.38  5308.0  408.05  5315.5  408.60
  5325.6  408.80  5456.0  410.69  5486.1  411.48  5516.2  411.48  5606.5  413.52
#Mann=3,-1,0
  4710.5    0.05       0  4982.5    0.04       0  4986.5    0.05       0
Bank Sta=4982.5,4986.5
Exp/Cntr=0.3,0.1

Type RM Length L Ch R = 1,4536,300,300,300
BEGIN DESCRIPTION:
Clear Creek T 18 16.0
END DESCRIPTION:
XS GIS Cut Line= 3
      2741776.05      6797610.99      2741526.00      6797661.00
      2741226.04      6797710.99
#Sta/Elev= 30
  4749.2  408.72  4769.6  408.56  4779.8  408.17  4800.2  407.78  4820.6  406.98
  4841.0  405.77  4861.4  405.02  4871.6  404.49  4902.2  403.28  4943.0  402.07
  4953.2  401.59  5001.6  398.47  5012.3  398.43  5012.6  397.93  5016.1  397.93
  5016.3  398.43  5024.5  399.51  5032.1  400.15  5044.8  401.11  5054.9  401.65
  5065.0  401.76  5075.2  402.09  5136.0  404.36  5158.8  404.90  5176.5  405.67
  5207.0  406.51  5227.2  406.83  5247.5  407.51  5275.4  408.78  5308.3  409.16
#Mann=3,-1,0
  4749.2    0.05       0  5012.3    0.05       0  5016.3    0.05       0
Bank Sta=5012.3,5016.3
Exp/Cntr=0.3,0.1

Type RM Length L Ch R = 1,4236,282,282,282
BEGIN DESCRIPTION:
Clear Creek T 18 15.0
END DESCRIPTION:
XS GIS Cut Line= 3
      2741767.96      6797387.46      2741526.00      6797361.00
      2741228.34      6797436.95
#Sta/Elev= 30
  4757.0  407.82  4767.2  407.69  4779.1  407.23  4809.3  406.82  4819.3  406.38
  4839.4  404.94  4858.5  404.03  4869.6  403.13  4909.9  401.14  4954.8  399.52
  4980.3  397.89  4997.9  396.28  5003.0  396.28  5016.3  395.20  5016.5  394.70
  5020.0  394.70  5020.3  395.20  5052.0  397.71  5072.6  398.70  5113.9  400.20
  5134.6  400.72  5140.8  401.15  5165.5  402.03  5186.9  403.06  5206.8  403.68
  5217.1  403.79  5263.4  405.36  5268.7  405.82  5289.4  405.92  5307.6  406.46
#Mann=3,-1,0
  4757.0    0.05       0  5016.3    0.04       0  5020.3    0.05       0
Bank Sta=5016.3,5020.3
Exp/Cntr=0.3,0.1

Type RM Length L Ch R = 1,3954,280,280,280
BEGIN DESCRIPTION:
Clear Creek T 18 14.0
END DESCRIPTION:
XS GIS Cut Line= 3
      2741795.33      6797100.63      2741426.00      6797111.00
      2741176.03      6797210.99
#Sta/Elev= 30
  4635.5  406.90  4654.8  405.95  4714.9  403.76  4774.9  400.38  4804.9  399.12
  4823.4  398.45  4828.4  398.72  4834.9  398.25  4894.9  395.92  4914.9  395.37
  4944.9  395.07  4975.0  394.38  4993.0  392.78  4993.2  392.28  4996.7  392.28
  4997.0  392.78  5002.5  393.65  5007.7  393.65  5014.4  394.61  5019.8  395.11
  5068.2  396.22  5103.3  397.28  5151.7  399.21  5157.1  399.63  5176.0  399.97
  5198.8  401.41  5205.6  402.13  5235.2  403.33  5241.9  403.98  5274.2  404.89
#Mann=3,-1,0
  4635.5    0.05       0  4993.0    0.04       0  4997.0    0.05       0
Bank Sta=4993,4997
Exp/Cntr=0.3,0.1

Type RM Length L Ch R = 1,3674,231,231,231
BEGIN DESCRIPTION:
Clear Creek T 18 13.0
END DESCRIPTION:
XS GIS Cut Line= 3
      2741676.04      6796861.00      2741426.00      6796861.00
      2741125.97      6796961.01
#Sta/Elev= 30
  4744.5  402.25  4747.0  402.25  4764.5  401.16  4814.5  398.69  4844.5  396.89
  4854.5  396.14  4864.5  395.63  4884.5  394.69  4904.5  393.96  4934.5  392.64
  4944.5  392.10  4964.5  391.40  4984.5  390.92  5026.2  391.63  5047.2  391.56
  5066.3  390.71  5066.6  390.21  5070.1  390.21  5070.3  390.71  5100.0  392.97
  5110.5  393.50  5121.0  393.79  5152.7  395.14  5173.7  396.32  5184.3  396.37
  5215.9  397.42  5237.0  398.64  5289.7  401.02  5308.1  402.13  5310.8  402.13
#Mann=3,-1,0
  4744.5    0.05       0  5066.3    0.04       0  5070.3    0.05       0
Bank Sta=5066.3,5070.3
Exp/Cntr=0.3,0.1

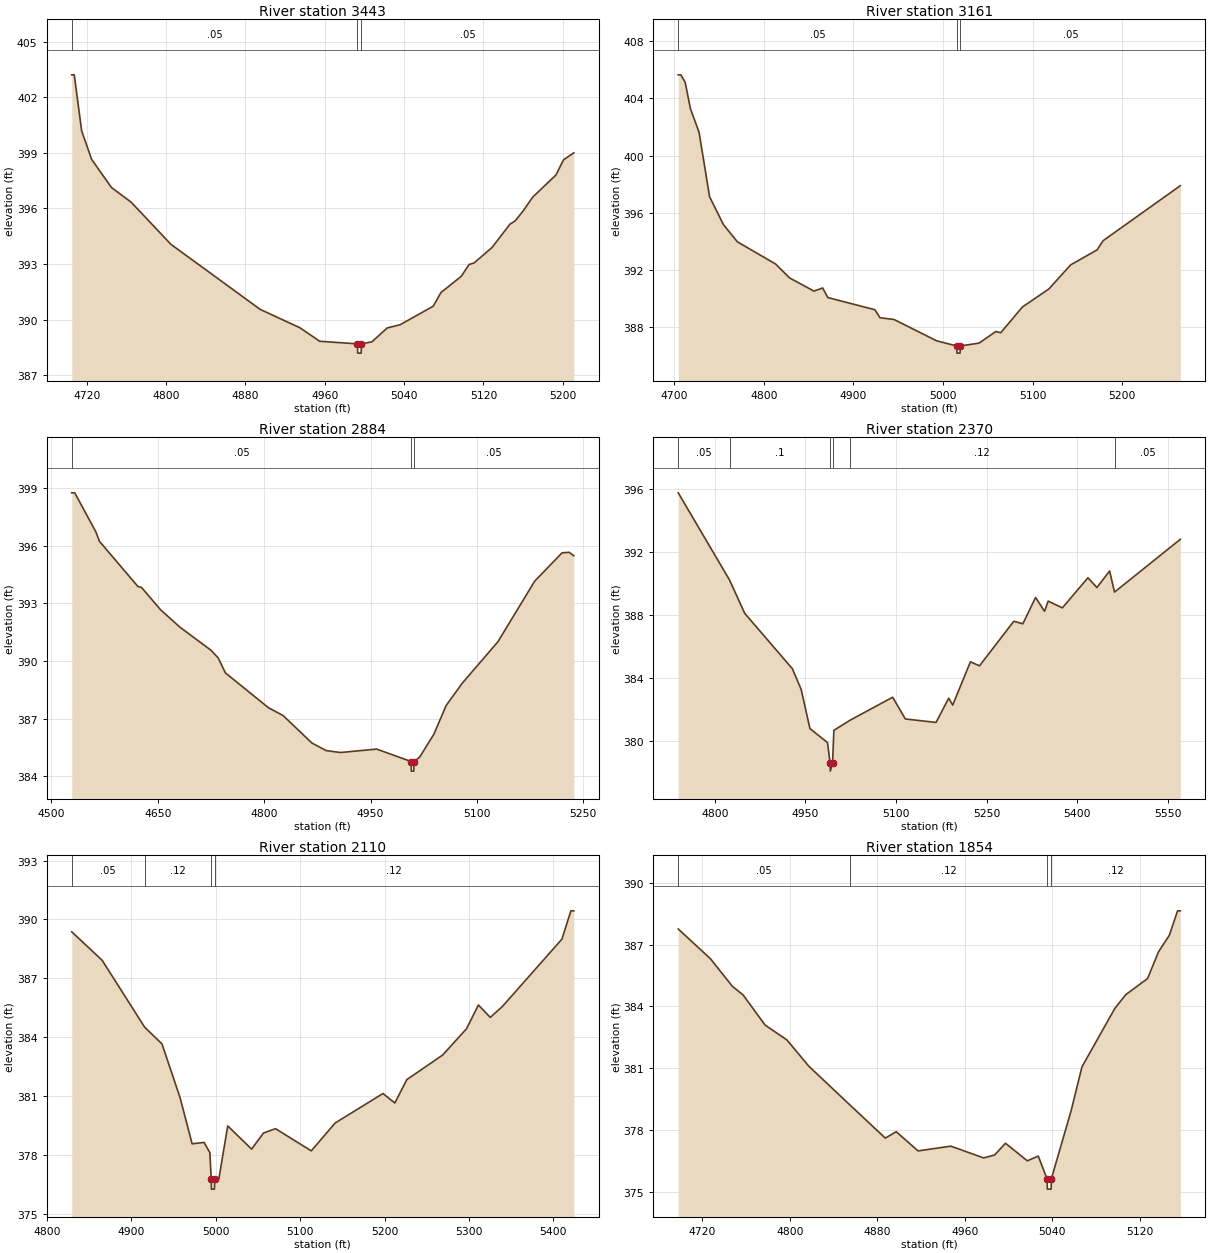
Type RM Length L Ch R = 1,3443,282,282,282
BEGIN DESCRIPTION:
Clear Creek T 18 12.0
END DESCRIPTION:
XS GIS Cut Line= 3
      2741726.02      6796661.00      2741426.00      6796661.00
      2741225.98      6796610.99
#Sta/Elev= 30
  4705.0  403.21  4707.5  403.21  4715.0  400.18  4725.0  398.65  4745.0  397.13
  4765.0  396.33  4805.0  394.06  4895.0  390.55  4935.0  389.56  4955.0  388.83
  4993.0  388.69  4993.3  388.19  4996.8  388.19  4997.0  388.69  5007.6  388.80
  5023.1  389.55  5035.9  389.72  5069.4  390.72  5077.2  391.46  5097.8  392.34
  5105.5  392.97  5110.7  393.06  5128.7  393.89  5146.8  395.15  5151.9  395.32
  5159.6  395.83  5169.9  396.62  5193.1  397.80  5200.9  398.63  5211.2  399.00
#Mann=3,-1,0
  4705.0    0.05       0  4993.0    0.04       0  4997.0    0.05       0
Bank Sta=4993,4997
Exp/Cntr=0.3,0.1

Type RM Length L Ch R = 1,3161,277,277,277
BEGIN DESCRIPTION:
Clear Creek T 18 11.0
END DESCRIPTION:
XS GIS Cut Line= 3
      2741775.98      6796560.99      2741526.00      6796411.00
      2741275.98      6796310.99
#Sta/Elev= 30
  4704.3  405.64  4707.2  405.64  4712.1  405.11  4717.9  403.28  4727.6  401.62
  4739.3  397.13  4754.8  395.18  4770.4  393.98  4813.1  392.43  4828.7  391.46
  4855.9  390.54  4865.6  390.76  4871.4  390.09  4923.9  389.24  4929.7  388.68
  4945.3  388.56  4992.9  387.07  5015.4  386.71  5015.6  386.21  5019.1  386.21
  5019.4  386.71  5040.3  386.91  5059.1  387.72  5064.5  387.63  5088.7  389.43
  5118.3  390.69  5142.6  392.37  5172.2  393.42  5178.9  394.06  5265.1  397.90
#Mann=3,-1,0
  4704.3    0.05       0  5015.4    0.04       0  5019.4    0.05       0
Bank Sta=5015.4,5019.4
Exp/Cntr=0.3,0.1

Type RM Length L Ch R = 1,2884,514,514,514
BEGIN DESCRIPTION:
Clear Creek T 18 10.0
END DESCRIPTION:
XS GIS Cut Line= 3
      2741989.37      6796242.81      2741526.00      6796161.00
      2741289.37      6796180.93
#Sta/Elev= 30
  4528.7  398.77  4532.9  398.77  4562.6  396.74  4567.8  396.24  4621.9  393.89
  4627.0  393.84  4654.0  392.67  4681.1  391.77  4725.1  390.56  4735.2  390.16
  4745.4  389.38  4806.3  387.56  4826.6  387.16  4867.2  385.73  4887.5  385.33
  4907.8  385.23  4958.6  385.41  5007.3  384.76  5007.5  384.26  5011.0  384.26
  5011.3  384.76  5019.3  384.99  5039.4  386.19  5056.6  387.68  5079.5  388.85
  5129.7  391.01  5181.4  394.16  5220.0  395.64  5230.0  395.67  5236.7  395.49
#Mann=3,-1,0
  4528.7    0.05       0  5007.3    0.04       0  5011.3    0.05       0
Bank Sta=5007.3,5011.3
Exp/Cntr=0.3,0.1

Type RM Length L Ch R = 1,2370,260,260,260
BEGIN DESCRIPTION:
Clear Creek T 18 9.0
END DESCRIPTION:
XS GIS Cut Line= 3
      2741883.74      6795603.50      2741676.00      6795761.00
      2741204.69      6796082.12
#Sta/Elev= 30
  4739.6  395.73  4824.5  390.20  4849.7  388.08  4928.5  384.57  4943.1  383.25
  4957.6  380.77  4986.7  379.88  4991.0  378.57  4991.3  378.07  4995.0  378.57
  4997.2  380.66  5024.0  381.30  5094.5  382.76  5115.5  381.38  5166.3  381.16
  5187.3  382.70  5193.9  382.26  5223.2  385.01  5238.2  384.75  5295.0  387.58
  5310.0  387.42  5331.0  389.09  5345.9  388.21  5351.9  388.86  5375.4  388.43
  5417.7  390.34  5432.6  389.72  5453.6  390.77  5461.7  389.43  5570.6  392.78
#Mann=6,-1,0
  4739.6    0.05       0  4824.5     0.1       0  4991.0    0.07       0
  4995.0     0.1       0  5024.0    0.12       0  5461.7    0.05       0
Bank Sta=4991,4995
Exp/Cntr=0.3,0.1

Type RM Length L Ch R = 1,2110,256,256,256
BEGIN DESCRIPTION:
Clear Creek T 18 8.0
END DESCRIPTION:
XS GIS Cut Line= 3
      2741601.25      6795495.06      2741476.00      6795611.00
      2741176.03      6795910.97
#Sta/Elev= 30
  4829.3  389.37  4865.3  387.92  4915.7  384.51  4936.2  383.66  4957.7  380.91
  4971.9  378.57  4986.1  378.64  4992.9  378.12  4994.6  376.76  4994.8  376.26
  4998.3  376.26  4998.6  376.76  5003.5  376.76  5014.1  379.48  5042.4  378.30
  5056.5  379.12  5070.7  379.34  5113.1  378.21  5141.4  379.63  5198.0  381.13
  5212.1  380.65  5226.3  381.84  5268.7  383.09  5297.0  384.43  5311.1  385.64
  5325.2  385.01  5339.4  385.56  5410.1  389.00  5420.7  390.44  5424.2  390.44
#Mann=4,-1,0
  4829.3    0.05       0  4915.7    0.12       0  4994.6    0.07       0
  4998.6    0.12       0
Bank Sta=4994.6,4998.6
Exp/Cntr=0.3,0.1

Type RM Length L Ch R = 1,1854,230,230,230
BEGIN DESCRIPTION:
Clear Creek T 18 7.0
END DESCRIPTION:
XS GIS Cut Line= 3
      2741585.53      6795460.02      2741276.00      6795461.00
      2741126.03      6795461.00
#Sta/Elev= 30
  4697.8  387.75  4727.3  386.31  4747.3  384.98  4757.3  384.55  4777.3  383.10
  4797.3  382.38  4817.3  381.11  4854.8  379.24  4887.3  377.63  4897.3  377.94
  4917.3  377.01  4947.3  377.24  4977.3  376.67  4987.3  376.81  4997.3  377.38
  5017.3  376.53  5027.3  376.76  5035.3  375.66  5035.6  375.16  5039.1  375.16
  5039.3  375.66  5057.3  378.94  5067.3  381.08  5097.3  383.90  5107.3  384.57
  5127.3  385.35  5137.3  386.64  5147.3  387.45  5154.8  388.63  5157.3  388.63
#Mann=4,-1,0
  4697.8    0.05       0  4854.8    0.12       0  5035.3    0.07       0
  5039.3    0.12       0
Bank Sta=5035.3,5039.3
Exp/Cntr=0.3,0.1

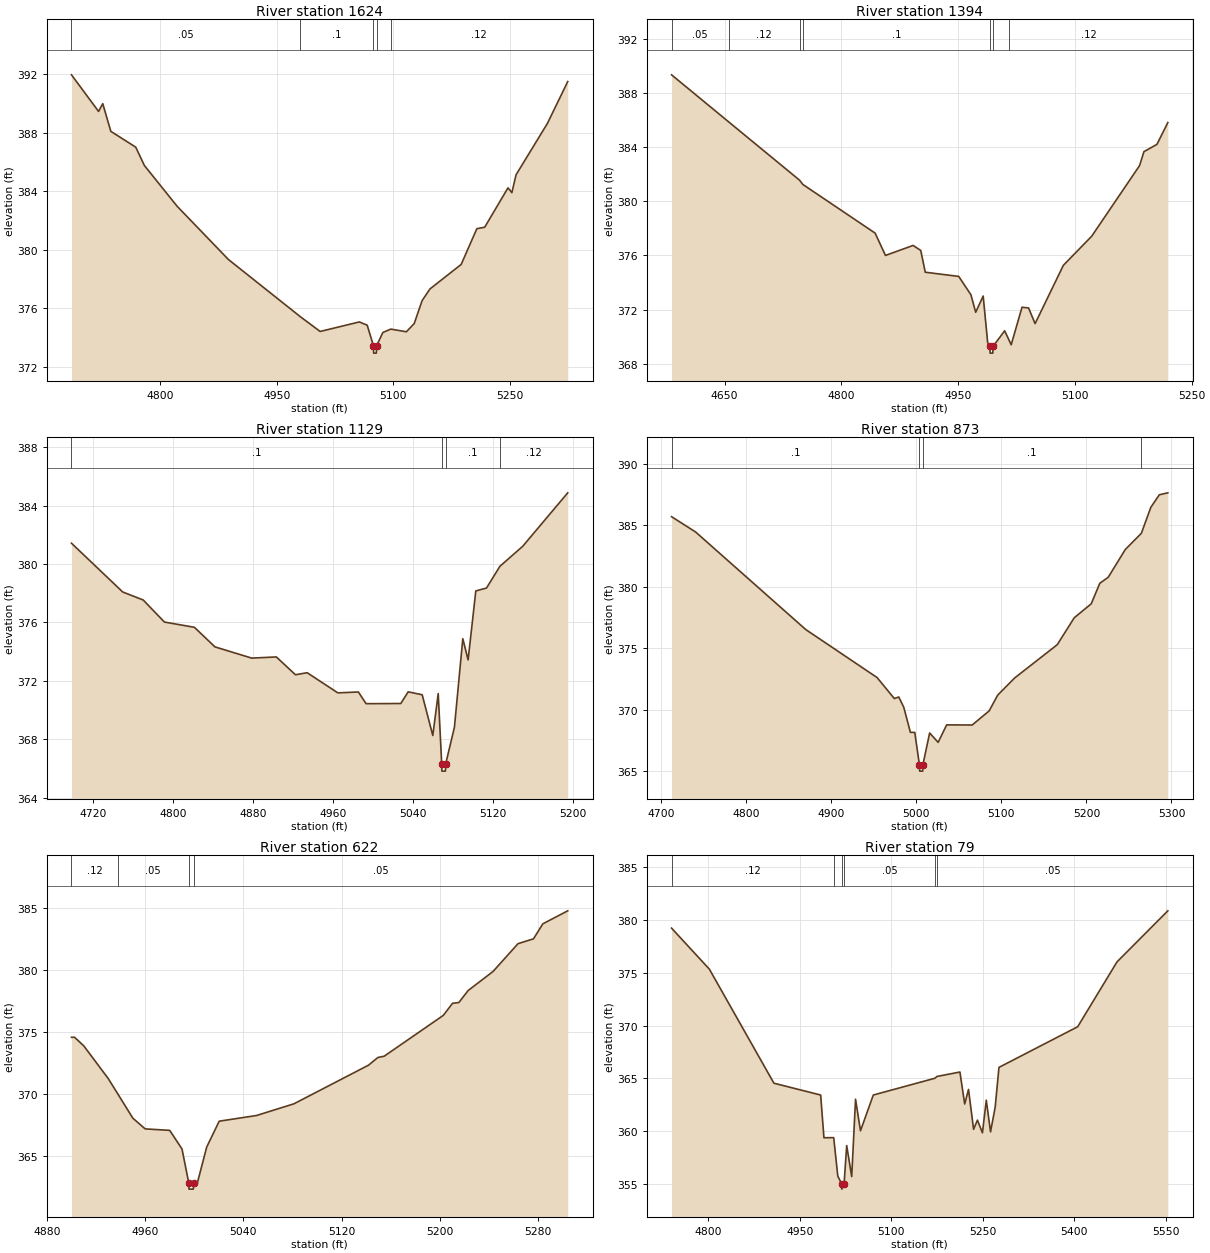
Type RM Length L Ch R = 1,1624,230,230,230
BEGIN DESCRIPTION:
Clear Creek T 18 6.0
END DESCRIPTION:
XS GIS Cut Line= 3
      2741662.81      6795379.54      2741376.00      6795261.00
      2741050.01      6795216.14
#Sta/Elev= 30
  4685.4  391.94  4720.3  389.44  4725.7  389.97  4736.1  388.08  4768.2  387.00
  4779.3  385.75  4821.4  382.97  4887.5  379.33  4980.0  375.43  5005.8  374.41
  5056.3  375.06  5066.4  374.84  5074.5  373.43  5074.7  372.93  5078.2  372.93
  5078.5  373.43  5086.6  374.34  5096.8  374.57  5116.9  374.39  5127.0  374.95
  5137.1  376.51  5147.2  377.31  5187.5  378.99  5207.7  381.43  5217.8  381.53
  5247.8  384.22  5252.8  383.89  5258.2  385.11  5298.6  388.62  5324.8  391.48
#Mann=5,-1,0
  4685.4    0.05       0  4980.0     0.1       0  5074.5    0.07       0
  5078.5     0.1       0  5096.8    0.12       0
Bank Sta=5074.5,5078.5
Exp/Cntr=0.3,0.1

Type RM Length L Ch R = 1,1394,265,265,265
BEGIN DESCRIPTION:
Clear Creek T 18 5.0
END DESCRIPTION:
XS GIS Cut Line= 3
      2741733.04      6795270.36      2741376.00      6795061.00
      2741176.00      6794961.00
#Sta/Elev= 30
  4581.8  389.35  4655.0  385.88  4746.3  381.56  4750.4  381.25  4843.3  377.65
  4856.6  376.00  4892.1  376.74  4901.9  376.37  4907.7  374.76  4950.7  374.45
  4966.4  373.09  4972.5  371.80  4982.1  373.00  4987.9  369.55  4990.8  369.28
  4991.0  368.78  4994.5  368.78  4994.8  369.28  5009.7  370.43  5015.5  369.72
  5018.1  369.40  5032.0  372.17  5040.4  372.12  5048.8  370.96  5085.1  375.27
  5121.5  377.42  5183.0  382.64  5188.6  383.67  5205.3  384.21  5219.3  385.82
#Mann=7,-1,0
  4581.8    0.05       0  4655.0    0.12       0  4746.3    0.05       0
  4750.4     0.1       0  4990.8    0.07       0  4994.8     0.1       0
  5015.5    0.12       0
Bank Sta=4990.8,4994.8
Exp/Cntr=0.3,0.1

Type RM Length L Ch R = 1,1129,256,256,256
BEGIN DESCRIPTION:
Clear Creek T 18 4.0
END DESCRIPTION:
XS GIS Cut Line= 3
      2741716.02      6794875.11      2741426.00      6794811.00
      2741240.27      6794739.32
#Sta/Elev= 30
  4698.4  381.43  4749.6  378.09  4770.1  377.54  4791.3  376.03  4821.3  375.67
  4841.8  374.33  4878.6  373.56  4903.2  373.64  4922.3  372.42  4934.0  372.56
  4964.7  371.18  4985.2  371.24  4992.9  370.44  5027.6  370.45  5035.0  371.25
  5049.0  371.05  5059.6  368.26  5065.0  371.13  5068.5  366.32  5068.7  365.82
  5072.2  365.82  5072.5  366.32  5081.2  368.82  5089.6  374.89  5094.9  373.44
  5102.6  378.16  5113.3  378.36  5126.7  379.85  5149.5  381.22  5194.5  384.88
#Mann=4,-1,0
  4698.4     0.1       0  5068.5    0.07       0  5072.5     0.1       0
  5126.7    0.12       0
Bank Sta=5068.5,5072.5
Exp/Cntr=0.3,0.1

Type RM Length L Ch R = 1,873,251,251,251
BEGIN DESCRIPTION:
Clear Creek T 18 3.0
END DESCRIPTION:
XS GIS Cut Line= 3
      2741846.82      6794694.65      2741576.00      6794611.00
      2741276.04      6794611.00
#Sta/Elev= 30
  4712.3  385.70  4740.5  384.46  4870.1  376.52  4953.9  372.62  4974.2  370.91
  4979.4  371.04  4985.3  370.20  4993.1  368.16  4998.2  368.16  5003.7  365.51
  5004.0  365.01  5007.5  365.01  5007.7  365.51  5015.7  368.11  5025.7  367.35
  5035.7  368.77  5065.7  368.76  5085.7  369.91  5095.7  371.19  5115.7  372.59
  5165.7  375.29  5185.7  377.48  5205.7  378.62  5215.7  380.28  5225.7  380.78
  5245.7  383.03  5264.6  384.35  5275.7  386.46  5285.7  387.48  5295.7  387.64
#Mann=4,-1,0
  4712.3     0.1       0  5003.7    0.07       0  5007.7     0.1       0
  5264.6    0.12       0
Bank Sta=5003.7,5007.7
Exp/Cntr=0.3,0.1

Type RM Length L Ch R = 1,622,543,543,543
BEGIN DESCRIPTION:
Clear Creek T 18 2.0
END DESCRIPTION:
XS GIS Cut Line= 3
      2741675.98      6794361.00      2741576.00      6794361.00
      2741276.01      6794411.00
#Sta/Elev= 30
  4900.1  374.55  4902.6  374.55  4910.1  373.86  4930.1  371.21  4937.7  370.00
  4950.1  368.02  4960.1  367.16  4980.1  367.04  4990.1  365.54  4995.6  362.80
  4995.8  362.30  4999.3  362.30  4999.6  362.80  5002.6  362.80  5010.2  365.69
  5020.4  367.78  5050.8  368.24  5081.2  369.18  5142.0  372.30  5149.6  372.92
  5154.7  373.02  5202.8  376.31  5210.4  377.29  5215.5  377.35  5223.1  378.32
  5243.4  379.86  5263.7  382.10  5276.3  382.49  5283.9  383.70  5304.2  384.75
#Mann=4,-1,0
  4900.1    0.12       0  4937.7    0.05       0  4995.6    0.04       0
  4999.6    0.05       0
Bank Sta=4995.6,4999.6
Exp/Cntr=0.3,0.1

Type RM Length L Ch R = 1,79,0,0,0
BEGIN DESCRIPTION:
Clear Creek T 18 1.0
END DESCRIPTION:
XS GIS Cut Line= 3
      2741726.00      6794111.01      2741625.05      6793871.41
      2741290.90      6794312.66
#Sta/Elev= 30
  4740.0  379.23  4802.0  375.34  4907.8  364.53  4984.4  363.41  4989.8  359.36
  5005.8  359.37  5012.5  355.73  5018.8  354.99  5019.0  354.49  5022.8  354.99
  5027.1  358.62  5035.3  355.68  5041.6  363.01  5049.7  360.02  5070.7  363.41
  5171.7  365.00  5175.1  365.17  5212.7  365.59  5220.5  362.56  5226.8  363.94
  5235.1  360.16  5241.4  361.03  5249.6  359.83  5255.9  362.92  5262.9  359.92
  5270.5  362.26  5276.7  366.03  5405.7  369.88  5470.2  376.03  5553.5  380.87
#Mann=6,-1,0
  4740.0    0.12       0  5005.8    0.05       0  5018.8    0.07       0
  5022.8    0.05       0  5171.7    0.12       0  5175.1    0.05       0
Bank Sta=5018.8,5022.8
Exp/Cntr=0.3,0.1

Chan Stop Cuts=-1