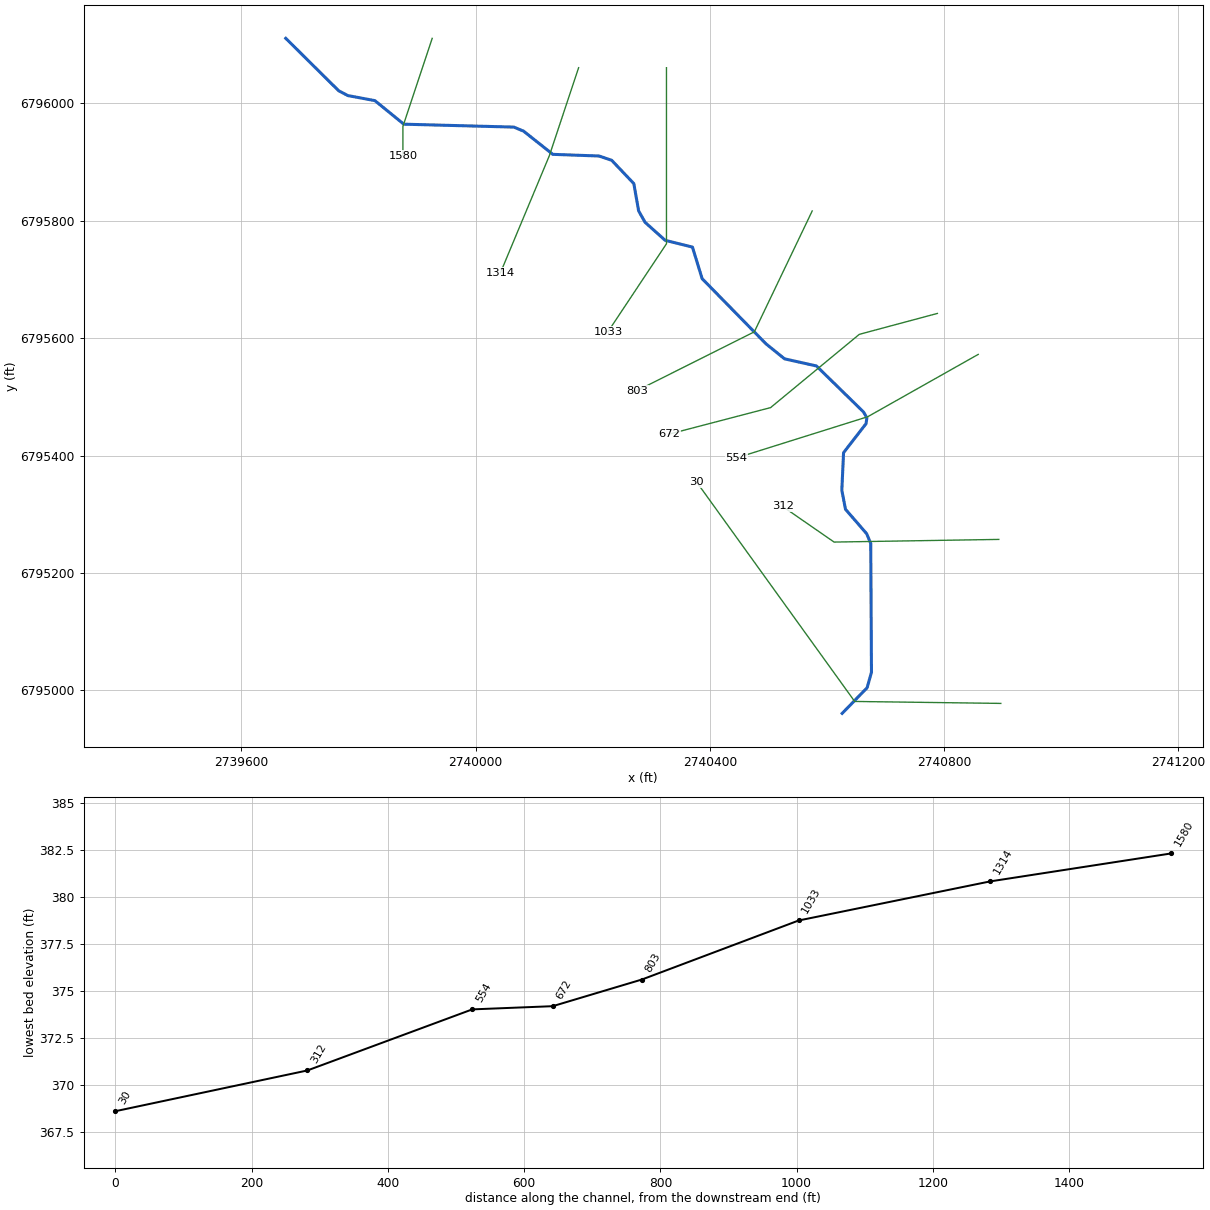
--- Clear Creek T 19.prj (project) ---

Proj Title=Clear Creek T 19 Base Level Engineering
Current Plan=p01
Default Exp/Contr=0.3,0.1
English Units
Geom File=g01
Flow File=f01
Plan File=p01
Y Axis Title=Elevation
X Axis Title(PF)=Main Channel Distance
X Axis Title(XS)=Station
BEGIN DESCRIPTION:
Clear Creek T 19
END DESCRIPTION:
DSS File=dss
DSS Export Rating Curves= 0
DSS Export Rating Curve Sorted= 0
DSS Export Volume Flow Curves= 0
DXF OffsetX= 0
DXF OffsetY= 0
DXF ScaleX= 1
DXF ScaleY= 10

--- Clear Creek T 19.p01 (plan) ---

Plan Title=Multiple Run
Program Version=4.10
Short Identifier=Multiple Run
Geom File=g01
Flow File=f01
Subcritical Flow
K Sum by GR= 0
Std Step Tol= 0.01
Critical Tol= 0.01
Num of Std Step Trials= 20
Max Error Tol= 0.3
Flow Tol Ratio= 0.001
Split Flow NTrial= 30
Split Flow Tol= 0.02
Split Flow Ratio= 0.02
Log Output Level= 0
Friction Slope Method= 1
Unsteady Friction Slope Method= 2
Unsteady Bridges Friction Slope Method= 1
Parabolic Critical Depth
Global Vel Dist= 1 , 1 , 1
Global Log Level= 0
CheckData=True
Encroach Param=-1 ,0,0, 0
BEGIN DESCRIPTION:
Multiple Run
END DESCRIPTION:
Computation Interval=1HOUR
Output Interval=1HOUR
Run HTab= 0
Run UNet= 0
Run PostProcess= 0
Run WQNet= 0
UNET Theta= 1
UNET Theta Warmup= 1
UNET ZTol= 0.02
UNET ZSATol= 0.05
UNET MxIter= 20
UNET MaxInSteps= 0
UNET DtIC= 0
UNET DtMin= 0
UNET MaxCRTS= 20
UNET WFStab= 2
UNET SFStab= 1
UNET WFX= 1
UNET SFX= 1
UNET DSS MLevel= 4
UNET DZMax Abort= 100
UNET Convert EG Bridges= 0
UNET Use Existing IB Tables=-1
UNET Froude Reduction=False
UNET Froude Limit= 1
UNET Froude Power= 10
UNET Time Slicing=0,0, 5
UNET Junction Losses=0
Instantaneous Interval=1HOUR
DSS File=dss
Write IC File= 0
Write IC File at Sim End=0
Echo Input=False
Echo Parameters=False
Echo Output=False
Write Detailed= 0
WQ AD Non Conservative
WQ ULTIMATE=-1
WQ Max Comp Step=1HOUR
WQ Output Interval=15MIN
WQ Output Selected Increments= 0
WQ Output face flow=0
WQ Output face velocity=0
WQ Output face area=0
WQ Output face dispersion=0
WQ Output cell volume=0
WQ Output cell surface area=0
WQ Output cell continuity=0
WQ Output cumulative cell continuity=0
WQ Output face conc=0
WQ Output face dconc_dx=0
WQ Output face courant=0
WQ Output face peclet=0
WQ Output face adv mass=0
WQ Output face disp mass=0
WQ Output cell mass=0
WQ Output cell source sink temp=0
WQ Output cell source sink nsm=0
WQ Output MaxMinRange=-1
WQ Daily Max Min Mean=-1
WQ Daily Range=0
WQ Daily Time=0
WQ Create Restart=0
WQ Fixed Restart=0
WQ System Summary=0
WQ Use Fixed Temperature=0
Sorting and Armoring Iterations= 10
XS Update Threshold= 0.02
Hydraulics Update Threshold= 0.02
Energy Slope Method= 1
Volume Change Method= 0
XS Weighting Method= 0
Number of US Weighted Cross Sections= 1
Number of DS Weighted Cross Sections= 1
Upstream XS Weight=0.25
Main XS Weight=0.5
Downstream XS Weight=0.25
Number of DS XS's Weighted with US Boundary= 1
Upstream Boundary Weight= 1
Weight of XSs Associated with US Boundary= 0
Number of US XS's Weighted with DS Boundary= 1
Downstream Boundary Weight= 0.5
Weight of XSs Associated with DS Boundary= 0.5
Sediment Output Level= 4
Mass or Volume Output= 0
Output Increment Type= 1
Profile and TS Output Increment= 10
XS Output Flag= 0
XS Output Increment= 10
Disregard all LS=0
Disregard all Conn=0
Disregard all Breaches=0
Disregard all Pumps=0

--- Clear Creek T 19.f01 (steady flow) ---

Flow Title=Multiple
Program Version=4.10
Number of Profiles= 7
Profile Names=10-year,25-year,50-year,1pct_min,100-year,1pct_plu,500-year
River Rch & RM=Clear Creek T 19,Reach-1         ,1580
     332     429     505     295     589    1176     801
River Rch & RM=Clear Creek T 19,Reach-1         ,30
     435     572     681     403     805    1605    1120
Boundary for River Rch & Prof#=Clear Creek T 19,Reach-1         , 1
Up Type= 0
Dn Type= 3
Dn Slope=0.01
Boundary for River Rch & Prof#=Clear Creek T 19,Reach-1         , 2
Up Type= 0
Dn Type= 3
Dn Slope=0.01
Boundary for River Rch & Prof#=Clear Creek T 19,Reach-1         , 3
Up Type= 0
Dn Type= 3
Dn Slope=0.01
Boundary for River Rch & Prof#=Clear Creek T 19,Reach-1         , 4
Up Type= 0
Dn Type= 3
Dn Slope=0.01
Boundary for River Rch & Prof#=Clear Creek T 19,Reach-1         , 5
Up Type= 0
Dn Type= 3
Dn Slope=0.01
Boundary for River Rch & Prof#=Clear Creek T 19,Reach-1         , 6
Up Type= 0
Dn Type= 3
Dn Slope=0.01
Boundary for River Rch & Prof#=Clear Creek T 19,Reach-1         , 7
Up Type= 0
Dn Type= 3
Dn Slope=0.01
DSS Import GetInterval= 0
DSS Import GetPeak= 0
DSS Import FillOption= 0

--- Clear Creek T 19.g01 (geometry) ---

Geom Title=Existing Conditions
Program Version=4.10

River Reach=Clear Creek T 19,Reach-1
Reach XY= 30
        2739676.        6796111.      2739766.29       6796021.7
      2739782.03      6796013.48      2739828.17      6796004.87
      2739877.55      6795964.75       2740065.5      6795959.78
      2740082.06      6795952.86      2740131.98      6795913.36
      2740210.91      6795910.53      2740232.45      6795903.25
      2740270.25      6795863.55       2740278.5      6795816.92
      2740289.56      6795797.48       2740323.8      6795766.89
      2740370.35      6795755.37      2740386.89      6795701.58
      2740495.84      6795590.61      2740527.65      6795564.98
      2740582.09      6795552.84      2740662.48      6795474.41
      2740668.21      6795464.43      2740666.71      6795454.48
      2740628.37      6795405.11      2740625.42      6795340.96
      2740631.69      6795308.69      2740667.85      6795267.06
      2740674.78       6795250.5      2740676.02      6795030.99
      2740668.57      6795004.65        2740626.        6794961.

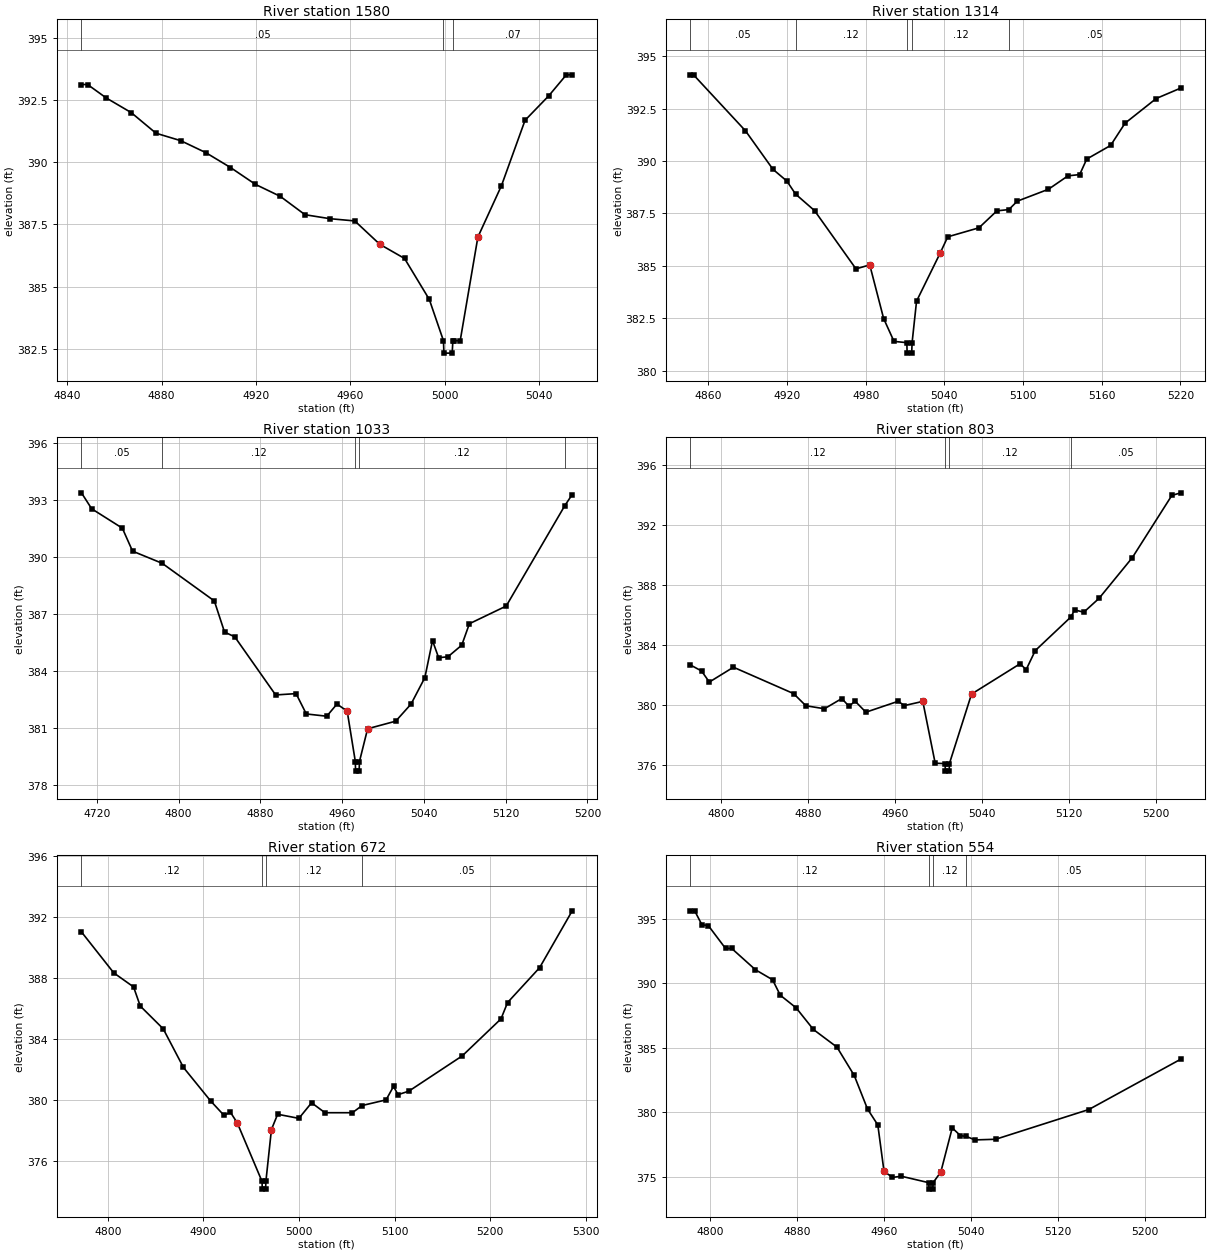
Type RM Length L Ch R = 1 ,1580    ,266,266,266
BEGIN DESCRIPTION:
Clear Creek T 19 5.0
END DESCRIPTION:
XS GIS Cut Line= 3
      2739925.99      6796110.98        2739876.        6795961.
        2739876.      6795910.99
#Sta/Elev= 28
    4846  393.13  4848.6  393.13  4856.5  392.59  4867.1     392  4877.6  391.17
  4888.1  390.87  4898.7  390.39  4909.2  389.79  4919.8  389.11  4930.3  388.63
  4940.8  387.89  4951.4  387.73  4961.9  387.64  4972.5   386.7    4983  386.13
  4993.5  384.48  4999.5  382.82  4999.7  382.32  5003.2  382.32  5003.5  382.82
  5004.1  382.82  5006.6  382.82  5014.1  386.99  5024.1  389.06  5034.1  391.69
  5044.1  392.67  5051.6  393.52  5054.1  393.52
#Mann= 3 ,-1 , 0
    4846     .05       0  4999.5     .04       0  5003.5     .07       0
Bank Sta=4972.5,5014.1
XS Rating Curve= 0 ,0
Exp/Cntr=0.3,0.1

Type RM Length L Ch R = 1 ,1314    ,281,281,281
BEGIN DESCRIPTION:
Clear Creek T 19 4.0
END DESCRIPTION:
XS GIS Cut Line= 3
        2740176.        6796061.        2740126.        6795911.
      2740042.51      6795711.58
#Sta/Elev= 30
  4846.1  394.11  4848.7  394.11  4888.3  391.44  4909.3   389.6  4919.9  389.04
  4926.5  388.42    4941  387.63  4972.6  384.85  4983.1  385.04  4993.7  382.48
  5001.6  381.39  5011.4  381.33  5011.6  380.83  5015.1  380.83  5015.4  381.33
  5018.8  383.31  5036.7  385.59  5042.6  386.38  5066.4  386.81  5080.1  387.62
  5089.2  387.68  5095.6  388.08  5119.4  388.65  5134.3  389.29  5143.2  389.35
  5148.6  390.09  5166.8  390.74  5177.8   391.8  5201.6  392.98  5220.4  393.48
#Mann= 5 ,-1 , 0
  4846.1     .05       0  4926.5     .12       0  5011.4     .07       0
  5015.4     .12       0  5089.2     .05       0
Bank Sta=4983.1,5036.7
XS Rating Curve= 0 ,0
Exp/Cntr=0.3,0.1

Type RM Length L Ch R = 1 ,1033    ,230,230,230
BEGIN DESCRIPTION:
Clear Creek T 19 3.0
END DESCRIPTION:
XS GIS Cut Line= 3
        2740326.      6796060.97        2740326.        6795761.
      2740226.03      6795611.04
#Sta/Elev= 30
  4704.9   393.4  4714.9  392.56  4744.9  391.54  4754.9  390.33  4783.9  389.69
  4834.9  387.71  4844.9  386.07  4854.9  385.82  4894.9  382.76  4914.9  382.83
  4924.9  381.76  4944.9  381.64  4954.9  382.28  4964.9  381.91  4972.9  379.25
  4973.1  378.75  4976.6  378.75  4976.9  379.25  4984.9  380.98  5012.4  381.38
  5027.4  382.28  5040.9  383.67  5048.4  385.62  5054.4  384.72  5063.5  384.77
    5077  385.38  5084.5  386.51  5120.5  387.44  5177.9  392.73  5185.1  393.31
#Mann= 5 ,-1 , 0
  4704.9     .05       0  4783.9     .12       0  4972.9     .07       0
  4976.9     .12       0  5177.9     .05       0
Bank Sta=4964.9,4984.9
XS Rating Curve= 0 ,0
Exp/Cntr=0.3,0.1

Type RM Length L Ch R = 1 ,803     ,131,131,131
BEGIN DESCRIPTION:
Clear Creek T 19 2.0
END DESCRIPTION:
XS GIS Cut Line= 3
      2740574.85      6795816.93        2740476.        6795611.
      2740276.03      6795511.02
#Sta/Elev= 30
  4771.3   382.7  4781.8  382.29    4789  381.55  4811.2  382.54  4866.6  380.78
  4877.9  379.97    4895  379.77    4911  380.45  4917.7  379.93  4923.2  380.28
  4933.2  379.54    4963  380.27  4968.5  379.98  4985.6  380.26    4997  376.14
  5006.1  376.11  5006.4  375.61  5009.9  375.61  5010.1  376.11  5030.5  380.75
  5075.2  382.77  5080.8  382.38  5089.2  383.65    5122  385.89  5125.5  386.36
  5133.9  386.21  5147.9  387.13  5178.6  389.85    5215     394  5223.3  394.17
#Mann= 4 ,-1 , 0
  4771.3     .12       0  5006.1     .07       0  5010.1     .12       0
    5122     .05       0
Bank Sta=4985.6,5030.5
XS Rating Curve= 0 ,0
Exp/Cntr=0.3,0.1

Type RM Length L Ch R = 1 ,672     ,118,118,118
BEGIN DESCRIPTION:
Mapping XS cf284a42
END DESCRIPTION:
XS GIS Cut Line= 4
      2740788.61      6795642.36      2740655.26      6795606.72
      2740503.76      6795481.89      2740330.58      6795436.75
#Sta/Elev= 30
  4772.5  391.02  4806.3  388.34    4827  387.42    4834  386.17    4858  384.68
  4879.2  382.15  4907.6  379.96  4921.7  379.01  4928.2  379.23  4935.5  378.52
  4961.4  374.69  4961.6  374.19  4965.1  374.19  4965.4  374.69  4971.2  378.09
  4977.7  379.09  4999.9  378.82  5013.2  379.84  5027.2  379.19  5055.9  379.19
    5066  379.66  5091.1  380.03  5098.9  380.91  5103.6  380.37  5114.9   380.6
  5170.8  382.91  5211.3  385.33  5218.2   386.4  5251.7  388.68  5285.8   392.4
#Mann= 4 ,-1 , 0
  4772.5     .12       0  4961.4     .07       0  4965.4     .12       0
    5066     .05       0
Bank Sta=4935.5,4971.2
XS Rating Curve= 0 ,0
Exp/Cntr=0.3,0.1

Type RM Length L Ch R = 1 ,554     ,242,242,242
BEGIN DESCRIPTION:
Mapping XS 75e61f60
END DESCRIPTION:
XS GIS Cut Line= 3
      2740858.34      6795572.58      2740669.63      6795466.35
      2740445.13      6795396.08
#Sta/Elev= 30
  4781.4  395.62  4785.6  395.62  4792.3  394.53  4798.1  394.48    4814   392.7
  4819.7   392.7  4841.5  391.05  4857.3  390.27  4864.4  389.07    4879  388.09
  4894.9  386.41  4916.6  385.04  4932.5  382.84  4944.7  380.24  4954.2     379
  4959.9   375.4  4967.7  374.93  4975.9  375.02  5001.1  374.52  5001.3  374.02
  5004.8  374.02  5005.1  374.52  5012.2  375.35  5022.7  378.77  5030.3  378.17
  5035.6  378.11  5043.7  377.84  5062.7  377.89  5148.5   380.2  5233.2  384.11
#Mann= 4 ,-1 , 0
  4781.4     .12       0  5001.1     .07       0  5005.1     .12       0
  5035.6     .05       0
Bank Sta=4959.9,5012.2
XS Rating Curve= 0 ,0
Exp/Cntr=0.3,0.1

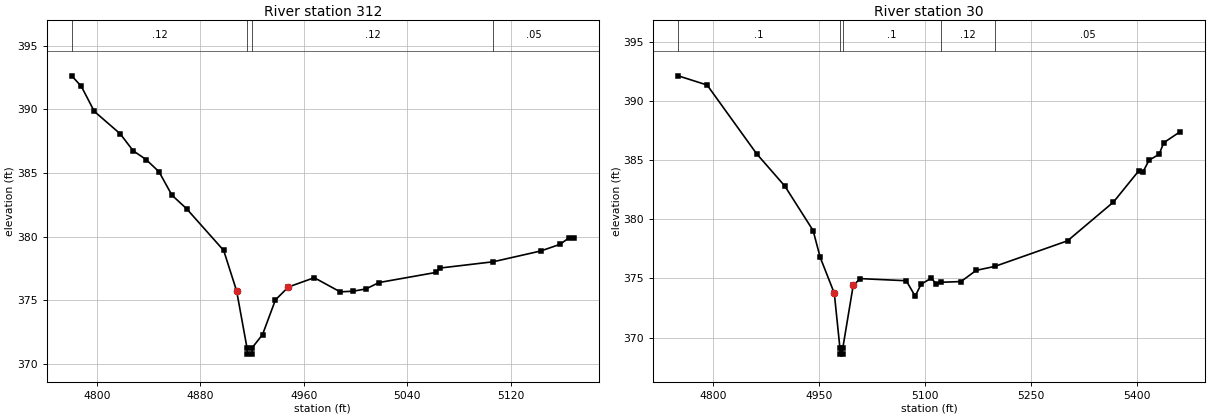
Type RM Length L Ch R = 1 ,312     ,282,282,282
BEGIN DESCRIPTION:
Mapping XS 2db26af3
END DESCRIPTION:
XS GIS Cut Line= 3
      2740893.39      6795257.37      2740612.19      6795252.84
      2740524.34      6795313.51
#Sta/Elev= 30
  4780.6  392.62    4788  391.79    4798  389.83    4818  388.07    4828  386.74
    4838  386.05    4848  385.09    4858  383.25  4869.3  382.19    4898  378.91
    4908  375.73    4916  371.27  4916.3  370.77  4919.8  370.77    4920  371.27
    4928   372.3    4938  375.03    4948  376.04    4968  376.77    4988  375.66
    4998  375.71    5008  375.89    5018  376.39  5061.8  377.18  5065.3  377.53
  5106.2  378.02  5143.1  378.87  5157.9  379.39  5164.6  379.88  5168.6  379.88
#Mann= 4 ,-1 , 0
  4780.6     .12       0    4916     .07       0    4920     .12       0
  5106.2     .05       0
Bank Sta=4908,4948
XS Rating Curve= 0 ,0
Exp/Cntr=0.3,0.1

Type RM Length L Ch R = 1 ,30      ,0,0,0
BEGIN DESCRIPTION:
Clear Creek T 19 1.0
END DESCRIPTION:
XS GIS Cut Line= 3
      2740896.87      6794977.97      2740647.39      6794981.32
      2740377.41      6795355.25
#Sta/Elev= 30
  4750.5  392.15  4791.4  391.37  4861.4  385.56  4901.4  382.82  4941.4  379.06
  4951.4   376.8  4971.4  373.75  4979.4   369.1  4979.6   368.6  4983.1   368.6
  4983.4   369.1  4998.2  374.42  5008.3  374.99  5073.3  374.81  5085.9   373.5
  5094.2  374.51  5108.9  375.04  5115.1  374.55  5122.3  374.68  5150.7  374.74
  5172.3  375.69  5198.5  376.02  5301.6  378.19  5366.6  381.47  5402.1  384.09
  5408.3  384.01  5416.9  385.01  5431.3  385.51  5437.7  386.49  5461.2  387.43
#Mann= 5 ,-1 , 0
  4750.5      .1       0  4979.4     .07       0  4983.4      .1       0
  5122.3     .12       0  5198.5     .05       0
Bank Sta=4971.4,4998.2
XS Rating Curve= 0 ,0
Exp/Cntr=0.3,0.1

Chan Stop Cuts=-1
Use User Specified Reach Order=0
Composite Channel Slope=5