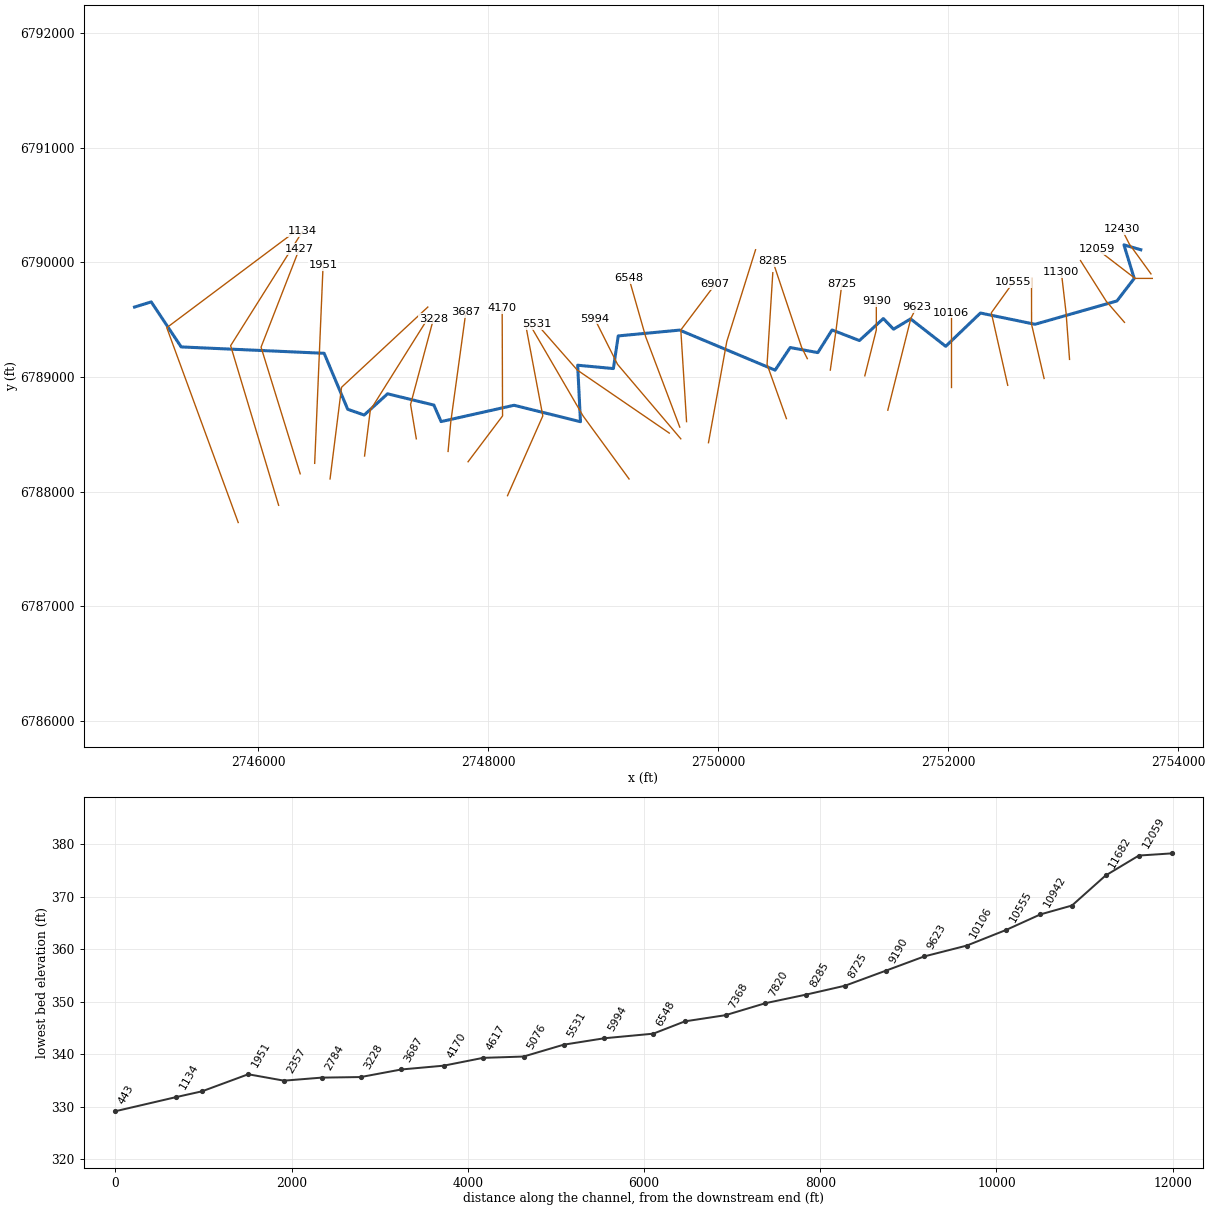
--- Clear Creek T 2.prj (project) ---

Proj Title=Clear Creek T 2 Base Level Engineering
Current Plan=p01
Default Exp/Contr=0.3,0.1
English Units
Geom File=g01
Flow File=f01
Plan File=p01
Y Axis Title=Elevation
X Axis Title(PF)=Main Channel Distance
X Axis Title(XS)=Station
BEGIN DESCRIPTION:
Clear Creek T 2
END DESCRIPTION:
DSS Export Rating Curves= 0
DSS Export Rating Curve Sorted= 0
DSS Export Volume Flow Curves= 0
DXF OffsetX= 0
DXF OffsetY= 0
DXF ScaleX= 1
DXF ScaleY= 10

--- Clear Creek T 2.p01 (plan) ---

Plan Title=Multiple Run
Program Version=4.10
Short Identifier=Multiple
Geom File=g01
Flow File=f01
Subcritical Flow
K Sum by GR= 0
Std Step Tol= 0.01
Critical Tol= 0.01
Num of Std Step Trials= 20
Max Error Tol= 0.3
Flow Tol Ratio= 0.001
Split Flow NTrial= 30
Split Flow Tol= 0.02
Split Flow Ratio= 0.02
Log Output Level= 0
Friction Slope Method= 1
Unsteady Friction Slope Method= 2
Unsteady Bridges Friction Slope Method= 1
Parabolic Critical Depth
Global Vel Dist= 1 , 1 , 1
Global Log Level= 0
CheckData=True
Encroach Param=-1 ,0,0, 0
BEGIN DESCRIPTION:
Multiple Run
END DESCRIPTION:
Computation Interval=1HOUR
Output Interval=1HOUR
Run HTab= 0
Run UNet= 0
Run PostProcess= 0
Run WQNet= 0
UNET Theta= 1
UNET Theta Warmup= 1
UNET ZTol= 0.02
UNET ZSATol= 0.05
UNET MxIter= 20
UNET MaxInSteps= 0
UNET DtIC= 0
UNET DtMin= 0
UNET MaxCRTS= 20
UNET WFStab= 2
UNET SFStab= 1
UNET WFX= 1
UNET SFX= 1
UNET DSS MLevel= 4
UNET DZMax Abort= 100
UNET Convert EG Bridges= 0
UNET Use Existing IB Tables=-1
UNET Froude Reduction=False
UNET Froude Limit= 1
UNET Froude Power= 10
UNET Time Slicing=0,0, 5
UNET Junction Losses=0
Instantaneous Interval=1HOUR
Write IC File= 0
Write IC File at Sim End=0
Echo Input=False
Echo Parameters=False
Echo Output=False
Write Detailed= 0
WQ AD Non Conservative
WQ ULTIMATE=-1
WQ Max Comp Step=1HOUR
WQ Output Interval=15MIN
WQ Output Selected Increments= 0
WQ Output face flow=0
WQ Output face velocity=0
WQ Output face area=0
WQ Output face dispersion=0
WQ Output cell volume=0
WQ Output cell surface area=0
WQ Output cell continuity=0
WQ Output cumulative cell continuity=0
WQ Output face conc=0
WQ Output face dconc_dx=0
WQ Output face courant=0
WQ Output face peclet=0
WQ Output face adv mass=0
WQ Output face disp mass=0
WQ Output cell mass=0
WQ Output cell source sink temp=0
WQ Output cell source sink nsm=0
WQ Output MaxMinRange=-1
WQ Daily Max Min Mean=-1
WQ Daily Range=0
WQ Daily Time=0
WQ Create Restart=0
WQ Fixed Restart=0
WQ System Summary=0
WQ Use Fixed Temperature=0
Sorting and Armoring Iterations= 10
XS Update Threshold= 0.02
Hydraulics Update Threshold= 0.02
Energy Slope Method= 1
Volume Change Method= 0
XS Weighting Method= 0
Number of US Weighted Cross Sections= 1
Number of DS Weighted Cross Sections= 1
Upstream XS Weight=0.25
Main XS Weight=0.5
Downstream XS Weight=0.25
Number of DS XS's Weighted with US Boundary= 1
Upstream Boundary Weight= 1
Weight of XSs Associated with US Boundary= 0
Number of US XS's Weighted with DS Boundary= 1
Downstream Boundary Weight= 0.5
Weight of XSs Associated with DS Boundary= 0.5
Sediment Output Level= 4
Mass or Volume Output= 0
Output Increment Type= 1
Profile and TS Output Increment= 10
XS Output Flag= 0
XS Output Increment= 10
Disregard all LS=0
Disregard all Conn=0
Disregard all Breaches=0
Disregard all Pumps=0

--- Clear Creek T 2.f01 (steady flow) ---

Flow Title=Multiple
Number of Profiles=7
Profile Names=10-year,25-year,50-year,1pct_min,100-year,1pct_plu,500-year
River Rch & RM= Clear Creek T 2,Reach-1,12430
     648     884    1080     656    1309    2613    1929
River Rch & RM= Clear Creek T 2,Reach-1,10106
     723     991    1214     739    1475    2943    2182
River Rch & RM= Clear Creek T 2,Reach-1,6907
     908    1258    1551     949    1894    3779    2834
River Rch & RM= Clear Creek T 2,Reach-1,4170
    1033    1430    1761    1076    2147    4284    3199
Boundary for River Rch & Prof#=Clear Creek T 2,Reach-1,1
Up Type=0
Dn Type=3
Dn Slope=0.005
Boundary for River Rch & Prof#=Clear Creek T 2,Reach-1,2
Up Type=0
Dn Type=3
Dn Slope=0.005
Boundary for River Rch & Prof#=Clear Creek T 2,Reach-1,3
Up Type=0
Dn Type=3
Dn Slope=0.005
Boundary for River Rch & Prof#=Clear Creek T 2,Reach-1,4
Up Type=0
Dn Type=3
Dn Slope=0.005
Boundary for River Rch & Prof#=Clear Creek T 2,Reach-1,5
Up Type=0
Dn Type=3
Dn Slope=0.005
Boundary for River Rch & Prof#=Clear Creek T 2,Reach-1,6
Up Type=0
Dn Type=3
Dn Slope=0.005
Boundary for River Rch & Prof#=Clear Creek T 2,Reach-1,7
Up Type=0
Dn Type=3
Dn Slope=0.005

--- Clear Creek T 2.g01 (geometry) ---

Geom Title=Existing Conditions

River Reach=Clear Creek T 2,Reach-1
Reach XY= 30
      2753676.00      6790111.00      2753529.11      6790153.74
      2753618.69      6789860.89      2753468.29      6789664.16
      2752756.04      6789460.75      2752281.44      6789558.83
      2751979.58      6789268.49      2751674.26      6789507.69
      2751525.79      6789418.03      2751436.87      6789510.66
      2751229.23      6789318.85      2750991.24      6789411.04
      2750867.54      6789213.62      2750627.23      6789257.57
      2750496.13      6789060.45      2749665.45      6789409.92
      2749131.66      6789359.11      2749089.77      6789074.24
      2748779.08      6789103.32      2748803.43      6788610.44
      2748226.00      6788753.90      2747591.58      6788611.56
      2747528.73      6788755.65      2747125.99      6788853.92
      2746922.78      6788668.87      2746779.53      6788718.85
      2746574.55      6789207.47      2745331.27      6789263.12
      2745070.92      6789656.06      2744926.00      6789611.00

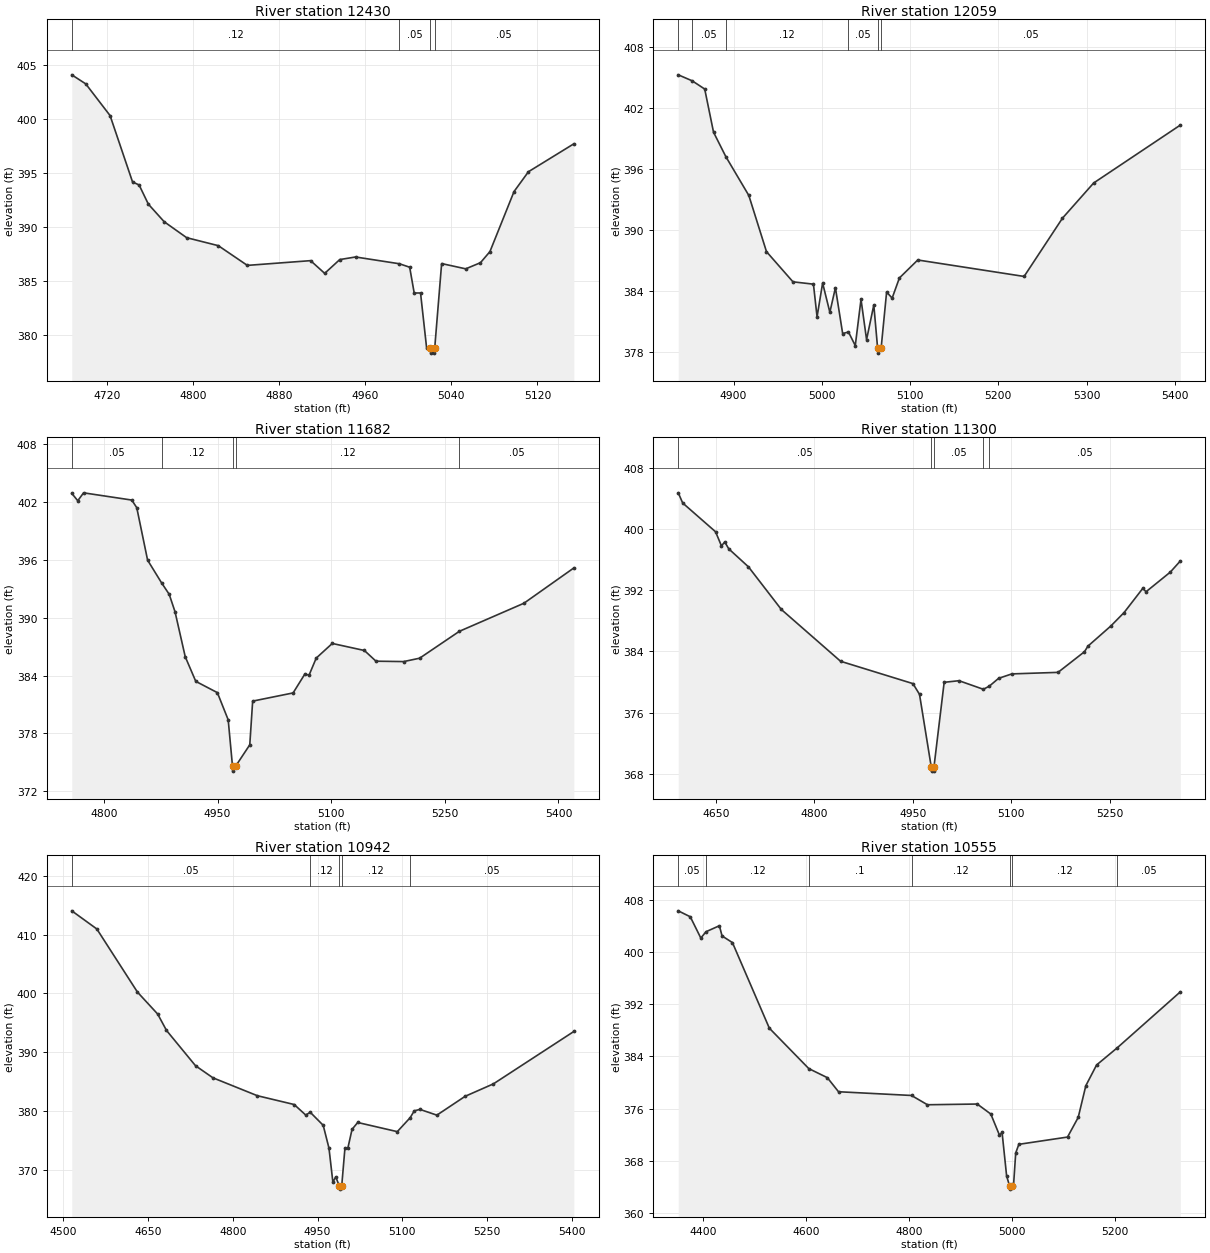
Type RM Length L Ch R = 1,12430,371,371,371
BEGIN DESCRIPTION:
Clear Creek T 2 26.0
END DESCRIPTION:
XS GIS Cut Line= 3
      2753764.27      6789900.49      2753576.00      6790161.00
      2753510.40      6790290.63
#Sta/Elev= 30
  4687.2  404.12  4700.2  403.28  4722.8  400.34  4743.7  394.18  4749.8  393.90
  4758.4  392.12  4773.1  390.49  4794.0  389.01  4823.4  388.27  4850.4  386.44
  4909.2  386.88  4922.3  385.70  4936.3  386.98  4951.0  387.22  4991.8  386.59
  5001.3  386.27  5005.5  383.88  5011.4  383.88  5017.0  378.82  5020.6  378.80
  5020.8  378.30  5024.3  378.30  5024.6  378.80  5031.0  386.61  5053.4  386.12
  5067.1  386.69  5075.9  387.72  5098.3  393.29  5111.7  395.13  5153.9  397.72
#Mann=4,-1,0
  4687.2    0.12       0  4991.8    0.05       0  5020.6    0.04       0
  5024.6    0.05       0
Bank Sta=5020.6,5024.6
Exp/Cntr=0.3,0.1

Type RM Length L Ch R = 1,12059,377,377,377
BEGIN DESCRIPTION:
Clear Creek T 2 25.0
END DESCRIPTION:
XS GIS Cut Line= 3
      2753776.04      6789861.00      2753626.00      6789861.00
      2753294.38      6790116.88
#Sta/Elev= 30
  4837.3  405.29  4853.1  404.70  4867.3  403.89  4877.3  399.64  4891.2  397.24
  4917.3  393.41  4937.3  387.88  4967.3  384.91  4990.5  384.68  4994.6  381.46
  5000.9  384.79  5009.1  381.91  5015.4  384.33  5023.6  379.82  5030.2  379.97
  5037.9  378.63  5044.4  383.18  5050.7  379.22  5058.9  382.63  5063.2  378.39
  5063.5  377.89  5067.2  378.39  5073.4  383.90  5079.7  383.31  5087.9  385.29
  5108.7  387.06  5229.2  385.44  5272.7  391.18  5308.0  394.64  5406.2  400.34
#Mann=6,-1,0
  4837.3    0.12       0  4853.1    0.05       0  4891.2    0.12       0
  5030.2    0.05       0  5063.2    0.07       0  5067.2    0.05       0
Bank Sta=5063.2,5067.2
Exp/Cntr=0.3,0.1

Type RM Length L Ch R = 1,11682,382,382,382
BEGIN DESCRIPTION:
Clear Creek T 2 24.0
END DESCRIPTION:
XS GIS Cut Line= 3
      2753533.94      6789477.45      2753376.00      6789661.00
      2753151.43      6790016.69
#Sta/Elev= 30
  4757.5  402.90  4765.4  402.13  4773.1  402.95  4836.7  402.20  4843.3  401.41
  4857.6  395.97  4876.0  393.62  4886.1  392.43  4893.8  390.62  4907.3  385.95
  4921.2  383.40  4949.7  382.23  4964.0  379.41  4969.7  374.59  4969.9  374.09
  4973.7  374.59  4992.5  376.82  4996.3  381.35  5049.7  382.20  5064.9  384.12
  5070.9  384.07  5080.2  385.81  5101.4  387.33  5143.8  386.60  5159.1  385.49
  5195.6  385.45  5216.7  385.80  5269.2  388.59  5354.4  391.50  5420.3  395.16
#Mann=5,-1,0
  4757.5    0.05       0  4876.0    0.12       0  4969.7    0.07       0
  4973.7    0.12       0  5269.2    0.05       0
Bank Sta=4969.7,4973.7
Exp/Cntr=0.3,0.1

Type RM Length L Ch R = 1,11300,358,358,358
BEGIN DESCRIPTION:
Clear Creek T 2 23.0
END DESCRIPTION:
XS GIS Cut Line= 3
      2753056.16      6789154.21      2753026.00      6789561.00
      2752984.79      6789916.11
#Sta/Elev= 30
  4592.5  404.74  4599.3  403.41  4649.4  399.65  4658.4  397.80  4663.4  398.32
  4669.5  397.42  4699.6  395.06  4749.7  389.49  4840.0  382.72  4950.3  379.80
  4960.3  378.40  4978.3  368.86  4978.6  368.36  4982.1  368.36  4982.3  368.86
  4997.9  379.97  5020.5  380.18  5057.6  379.06  5066.6  379.46  5080.9  380.49
  5101.1  381.07  5171.5  381.27  5211.8  383.97  5217.1  384.70  5252.1  387.34
  5272.2  389.09  5300.7  392.25  5305.7  391.81  5342.7  394.38  5357.9  395.83
#Mann=5,-1,0
  4592.5    0.05       0  4978.3    0.04       0  4982.3    0.05       0
  5057.6    0.12       0  5066.6    0.05       0
Bank Sta=4978.3,4982.3
Exp/Cntr=0.3,0.1

Type RM Length L Ch R = 1,10942,387,387,387
BEGIN DESCRIPTION:
Clear Creek T 2 22.0
END DESCRIPTION:
XS GIS Cut Line= 3
      2752835.05      6788987.79      2752726.00      6789461.00
      2752725.62      6789863.19
#Sta/Elev= 30
  4515.3  414.07  4559.6  410.98  4631.5  400.22  4667.2  396.49  4682.8  393.70
  4734.1  387.69  4764.9  385.63  4843.5  382.58  4908.6  381.08  4929.0  379.29
  4937.0  379.76  4959.9  377.54  4970.1  373.65  4977.0  367.86  4982.1  368.75
  4988.6  367.17  4988.9  366.67  4992.6  367.17  4998.3  373.61  5003.4  373.61
  5010.9  376.85  5020.9  378.02  5090.9  376.46  5113.7  378.84  5120.9  380.00
  5130.9  380.25  5160.9  379.27  5210.9  382.48  5260.9  384.60  5403.1  393.52
#Mann=5,-1,0
  4515.3    0.05       0  4937.0    0.12       0  4988.6    0.07       0
  4992.6    0.12       0  5113.7    0.05       0
Bank Sta=4988.6,4992.6
Exp/Cntr=0.3,0.1

Type RM Length L Ch R = 1,10555,449,449,449
BEGIN DESCRIPTION:
Clear Creek T 2 21.0
END DESCRIPTION:
XS GIS Cut Line= 3
      2752518.66      6788928.19      2752376.00      6789561.00
      2752566.77      6789827.09
#Sta/Elev= 30
  4351.2  406.27  4374.6  405.36  4395.1  402.11  4405.3  403.08  4431.2  403.99
  4436.4  402.43  4456.6  401.41  4528.3  388.33  4605.0  382.15  4641.1  380.76
  4662.8  378.61  4804.7  378.04  4835.7  376.62  4932.5  376.73  4958.9  375.20
  4975.7  371.97  4980.8  372.39  4989.6  365.75  4995.3  364.22  4995.6  363.72
  4999.3  364.22  5003.0  364.22  5007.3  369.25  5013.4  370.57  5108.0  371.68
  5128.8  374.68  5143.6  379.53  5164.5  382.70  5204.6  385.32  5327.3  393.88
#Mann=7,-1,0
  4351.2    0.05       0  4405.3    0.12       0  4605.0     0.1       0
  4804.7    0.12       0  4995.3    0.07       0  4999.3    0.12       0
  5204.6    0.05       0
Bank Sta=4995.3,4999.3
Exp/Cntr=0.3,0.1

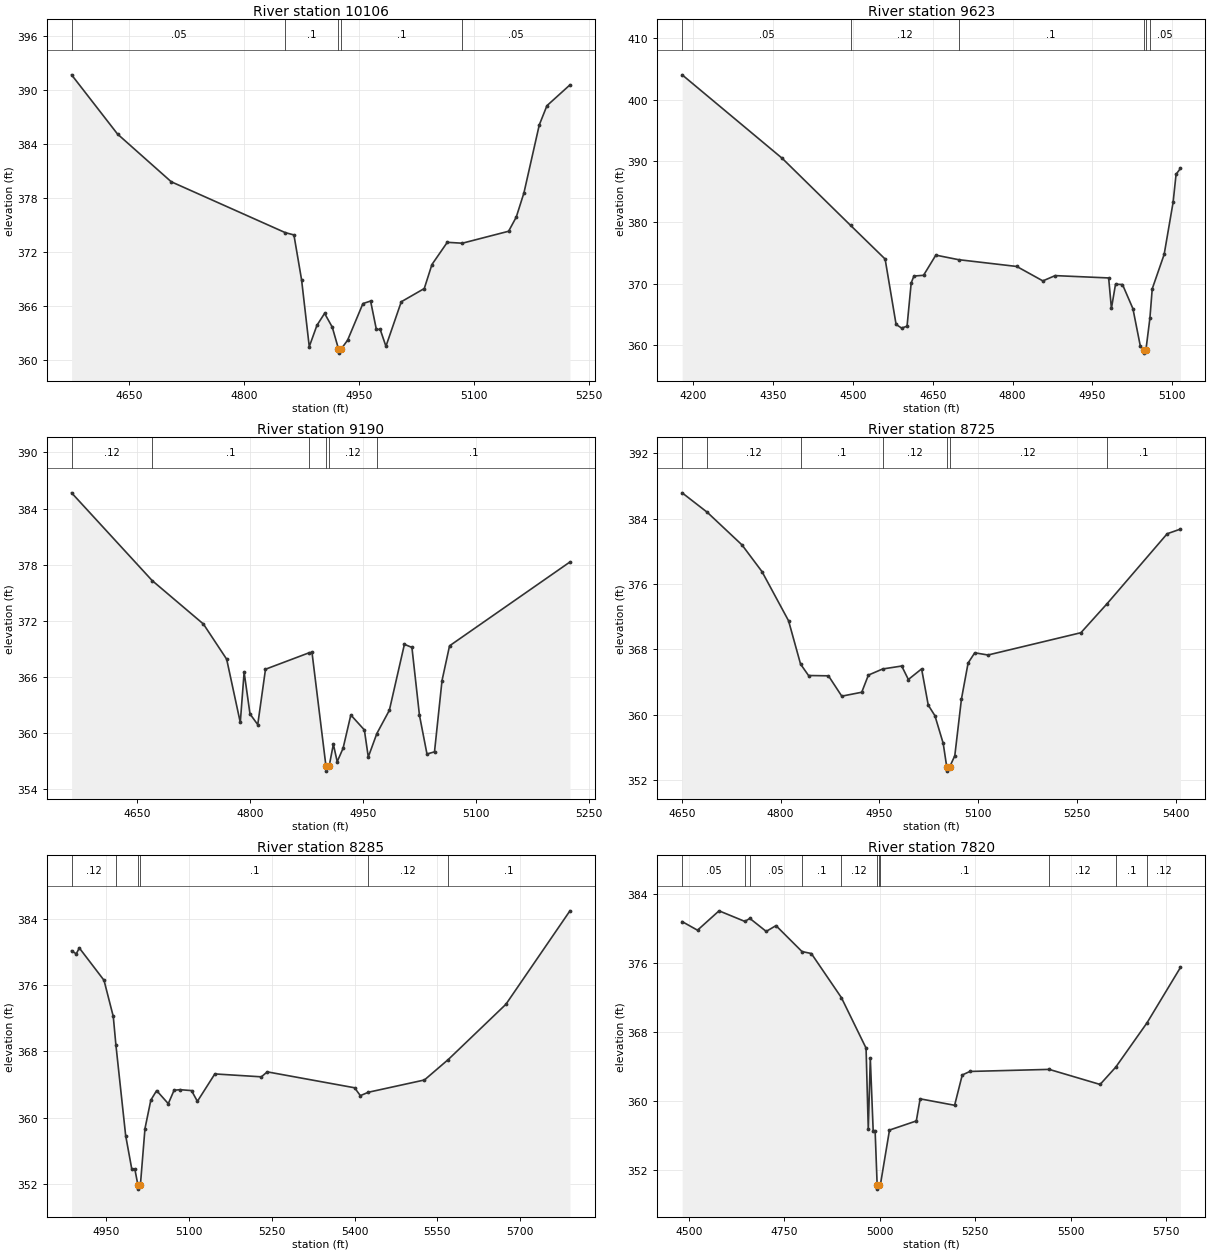
Type RM Length L Ch R = 1,10106,483,483,483
BEGIN DESCRIPTION:
Clear Creek T 2 20.0
END DESCRIPTION:
XS GIS Cut Line= 3
      2752026.00      6788911.04      2752026.00      6789311.00
      2752026.00      6789561.04
#Sta/Elev= 30
  4574.7  391.66  4634.7  385.07  4704.7  379.77  4853.3  374.12  4864.7  373.86
  4874.7  368.86  4884.7  361.44  4894.7  363.81  4904.7  365.14  4914.7  363.61
  4922.7  361.22  4922.9  360.72  4926.7  361.22  4934.7  362.16  4954.7  366.23
  4964.7  366.51  4972.2  363.36  4977.2  363.36  4984.7  361.48  5004.7  366.43
  5034.7  367.90  5044.7  370.57  5064.7  373.04  5084.3  372.94  5144.7  374.27
  5154.7  375.85  5164.7  378.54  5184.7  386.09  5194.7  388.23  5224.7  390.54
#Mann=5,-1,0
  4574.7    0.05       0  4853.3     0.1       0  4922.7    0.07       0
  4926.7     0.1       0  5084.3    0.05       0
Bank Sta=4922.7,4926.7
Exp/Cntr=0.3,0.1

Type RM Length L Ch R = 1,9623,433,433,433
BEGIN DESCRIPTION:
Clear Creek T 2 19.0
END DESCRIPTION:
XS GIS Cut Line= 3
      2751476.00      6788710.99      2751676.00      6789511.00
      2751725.98      6789610.96
#Sta/Elev= 30
  4179.2  404.03  4367.3  390.41  4495.8  379.47  4560.6  373.99  4581.2  363.33
  4591.5  362.74  4601.8  363.04  4609.6  370.10  4614.7  371.22  4632.8  371.34
  4655.9  374.63  4698.5  373.89  4808.0  372.78  4857.0  370.43  4880.1  371.29
  4980.6  370.91  4985.8  365.94  4993.5  369.88  5006.6  369.84  5026.2  365.90
  5040.2  359.76  5046.5  359.15  5046.8  358.65  5050.6  359.15  5058.1  364.33
  5062.5  369.14  5084.9  374.75  5101.7  383.24  5107.3  387.81  5115.6  388.78
#Mann=6,-1,0
  4179.2    0.05       0  4495.8    0.12       0  4698.5     0.1       0
  5046.5    0.07       0  5050.6     0.1       0  5058.1    0.05       0
Bank Sta=5046.5,5050.6
Exp/Cntr=0.3,0.1

Type RM Length L Ch R = 1,9190,465,465,465
BEGIN DESCRIPTION:
Clear Creek T 2 18.0
END DESCRIPTION:
XS GIS Cut Line= 3
      2751276.00      6789011.02      2751376.00      6789411.00
      2751376.00      6789661.01
#Sta/Elev= 30
  4562.8  385.69  4669.8  376.32  4738.0  371.67  4768.9  367.91  4787.0  361.15
  4792.1  366.53  4799.9  362.06  4810.2  360.92  4820.5  366.84  4878.2  368.59
  4882.3  368.64  4900.9  356.45  4901.2  355.95  4905.0  356.45  4910.7  358.82
  4915.8  356.96  4923.6  358.39  4933.9  361.95  4951.9  360.35  4957.1  357.46
  4968.5  359.97  4985.1  362.45  5005.1  369.50  5015.1  369.17  5025.1  361.93
  5035.1  357.78  5045.1  358.01  5055.1  365.63  5065.1  369.34  5225.1  378.30
#Mann=6,-1,0
  4562.8    0.12       0  4669.8     0.1       0  4878.2    0.12       0
  4900.9    0.07       0  4905.0    0.12       0  4968.5     0.1       0
Bank Sta=4900.9,4905
Exp/Cntr=0.3,0.1

Type RM Length L Ch R = 1,8725,440,440,440
BEGIN DESCRIPTION:
Clear Creek T 2 17.0
END DESCRIPTION:
XS GIS Cut Line= 3
      2750976.00      6789061.00      2751026.00      6789411.00
      2751076.00      6789811.03
#Sta/Elev= 30
  4650.6  387.15  4688.7  384.77  4741.5  380.77  4771.8  377.51  4812.2  371.48
  4830.4  366.18  4842.5  364.78  4872.8  364.74  4893.0  362.25  4923.3  362.73
  4933.4  364.83  4955.1  365.58  4984.0  365.94  4994.1  364.29  5014.2  365.59
  5024.3  361.15  5034.4  359.86  5047.0  356.47  5052.4  353.57  5052.7  353.07
  5056.7  353.57  5064.6  354.95  5074.7  361.90  5084.8  366.31  5094.9  367.56
  5115.0  367.29  5256.1  370.02  5295.9  373.58  5387.1  382.14  5407.3  382.71
#Mann=7,-1,0
  4650.6    0.05       0  4688.7    0.12       0  4830.4     0.1       0
  4955.1    0.12       0  5052.4    0.07       0  5056.7    0.12       0
  5295.9     0.1       0
Bank Sta=5052.4,5056.7
Exp/Cntr=0.3,0.1

Type RM Length L Ch R = 1,8285,465,465,465
BEGIN DESCRIPTION:
Clear Creek T 2 16.0
END DESCRIPTION:
XS GIS Cut Line= 3
      2750776.01      6789160.98      2750726.00      6789261.00
      2750476.00      6790011.00
#Sta/Elev= 30
  4887.7  380.14  4896.1  379.77  4901.7  380.48  4946.4  376.58  4963.2  372.21
  4967.9  368.81  4985.6  357.85  4996.7  353.80  5002.2  353.80  5007.8  351.88
  5008.3  351.38  5012.3  351.88  5020.6  358.69  5031.2  362.12  5041.7  363.27
  5062.8  361.69  5073.3  363.31  5083.9  363.38  5104.9  363.27  5115.5  361.97
  5147.1  365.28  5231.4  364.93  5242.0  365.53  5400.1  363.61  5410.6  362.66
  5425.1  363.07  5526.6  364.55  5569.8  367.02  5674.1  373.68  5790.1  384.96
#Mann=6,-1,0
  4887.7    0.12       0  4967.9     0.1       0  5007.8    0.07       0
  5012.3     0.1       0  5425.1    0.12       0  5569.8     0.1       0
Bank Sta=5007.8,5012.3
Exp/Cntr=0.3,0.1

Type RM Length L Ch R = 1,7820,452,452,452
BEGIN DESCRIPTION:
Clear Creek T 2 15.0
END DESCRIPTION:
XS GIS Cut Line= 3
      2750594.21      6788637.45      2750426.00      6789111.00
      2750476.00      6789911.00
#Sta/Elev= 30
  4482.7  380.81  4522.9  379.81  4579.3  382.06  4646.8  380.83  4659.9  381.18
  4702.7  379.67  4728.3  380.34  4796.3  377.33  4820.8  377.10  4899.4  371.98
  4964.0  366.11  4969.8  356.68  4975.1  364.92  4982.6  356.52  4987.7  356.52
  4993.0  350.23  4993.5  349.73  4997.5  350.23  5001.6  350.27  5025.3  356.59
  5095.5  357.65  5105.5  360.22  5195.7  359.47  5215.7  362.99  5235.7  363.40
  5443.2  363.64  5576.4  361.89  5617.5  363.91  5699.2  369.05  5786.8  375.49
#Mann=11,-1,0
  4482.7    0.05       0  4646.8    0.12       0  4659.9    0.05       0
  4796.3     0.1       0  4899.4    0.12       0  4993.0    0.07       0
  4997.5    0.12       0  5001.6     0.1       0  5443.2    0.12       0
  5617.5     0.1       0  5699.2    0.12       0
Bank Sta=4993,4997.5
Exp/Cntr=0.3,0.1

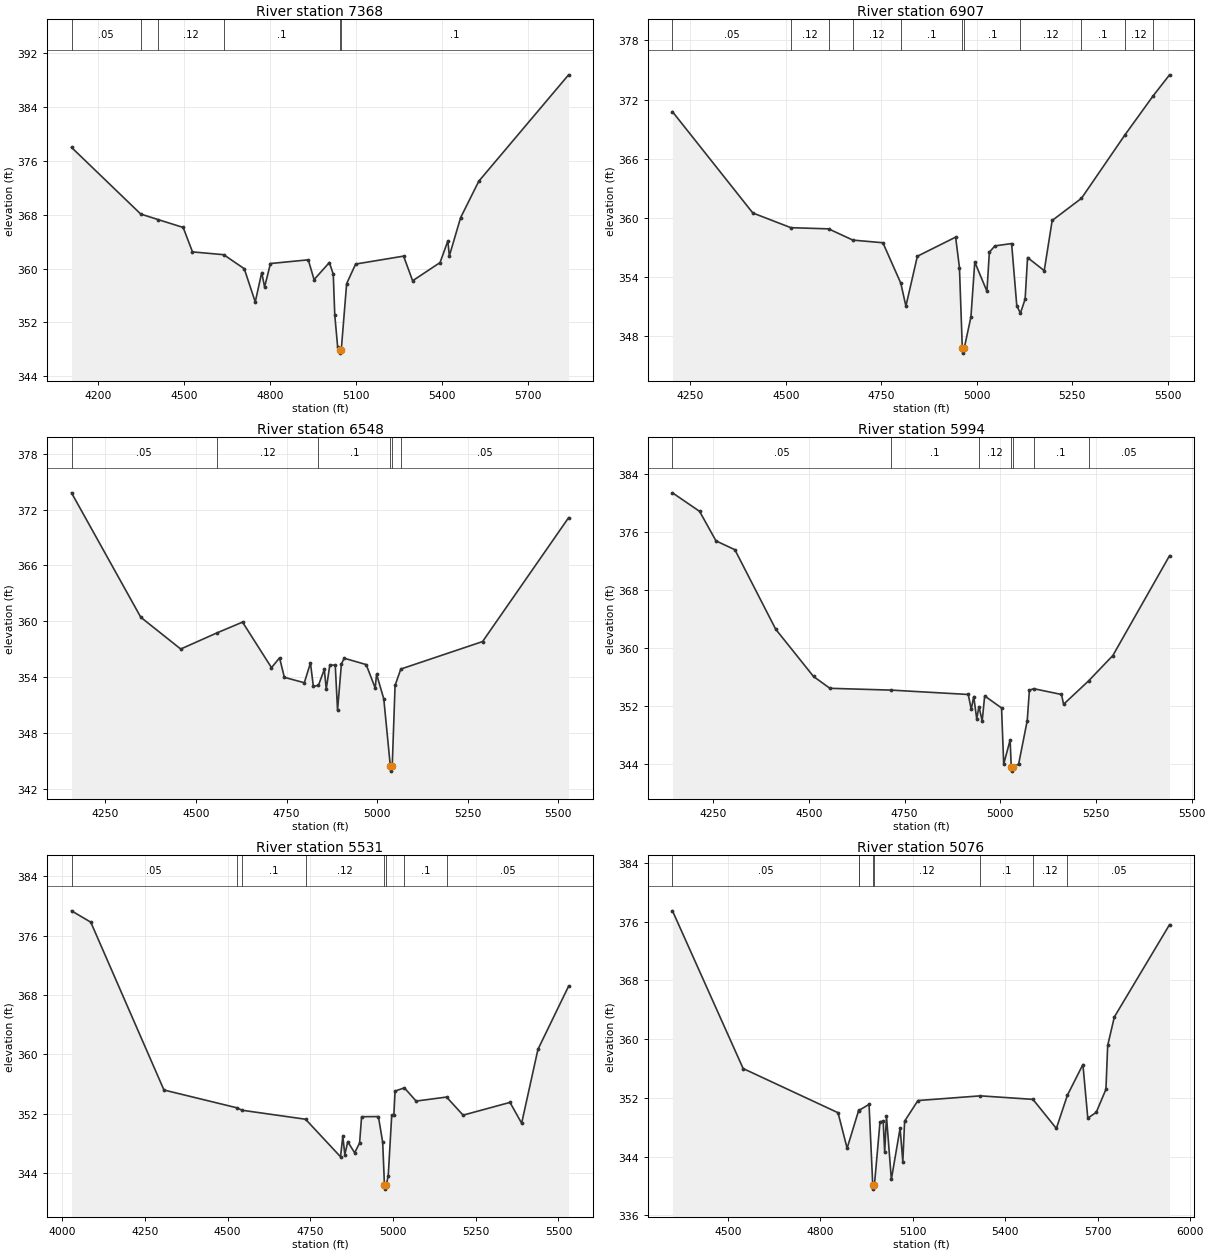
Type RM Length L Ch R = 1,7368,461,461,461
BEGIN DESCRIPTION:
Clear Creek T 2 14.0
END DESCRIPTION:
XS GIS Cut Line= 3
      2749916.52      6788427.17      2750076.00      6789311.00
      2750326.01      6790111.05
#Sta/Elev= 30
  4106.7  378.01  4348.5  368.11  4409.1  367.29  4496.7  366.12  4529.2  362.49
  4638.4  362.07  4710.1  359.99  4748.5  355.05  4771.1  359.42  4781.2  357.27
  4801.6  360.76  4933.7  361.31  4954.0  358.37  5007.4  360.91  5021.0  359.17
  5026.3  353.09  5036.2  348.43  5044.5  347.95  5044.9  347.45  5049.0  347.95
  5067.7  357.77  5099.1  360.68  5266.7  361.86  5298.2  358.20  5394.0  360.90
  5421.3  364.12  5426.5  361.89  5465.8  367.57  5529.2  372.98  5843.0  388.79
#Mann=6,-1,0
  4106.7    0.05       0  4348.5     0.1       0  4409.1    0.12       0
  4638.4     0.1       0  5044.5    0.07       0  5049.0     0.1       0
Bank Sta=5044.5,5049
Exp/Cntr=0.3,0.1

Type RM Length L Ch R = 1,6907,359,359,359
BEGIN DESCRIPTION:
Clear Creek T 2 13.0
END DESCRIPTION:
XS GIS Cut Line= 3
      2749726.00      6788611.03      2749676.00      6789411.00
      2749975.98      6789810.98
#Sta/Elev= 30
  4203.1  370.77  4413.5  360.49  4513.1  359.00  4611.9  358.88  4675.4  357.74
  4754.1  357.47  4801.0  353.36  4814.3  351.04  4844.3  356.10  4944.5  358.04
  4954.5  354.95  4962.0  346.77  4962.7  346.27  4967.0  346.77  4984.6  349.94
  4994.6  355.51  5026.5  352.55  5032.8  356.51  5047.3  357.15  5091.1  357.39
  5104.6  351.09  5114.2  350.32  5126.5  351.76  5132.8  355.97  5176.5  354.64
  5197.3  359.73  5274.0  361.98  5387.9  368.42  5461.9  372.39  5504.6  374.51
#Mann=11,-1,0
  4203.1    0.05       0  4513.1    0.12       0  4611.9     0.1       0
  4675.4    0.12       0  4801.0     0.1       0  4962.0    0.07       0
  4967.0     0.1       0  5114.2    0.12       0  5274.0     0.1       0
  5387.9    0.12       0  5461.9     0.1       0
Bank Sta=4962,4967
Exp/Cntr=0.3,0.1

Type RM Length L Ch R = 1,6548,554,554,554
BEGIN DESCRIPTION:
Clear Creek T 2 12.0
END DESCRIPTION:
XS GIS Cut Line= 3
      2749666.94      6788563.27      2749370.07      6789353.12
      2749225.17      6789861.89
#Sta/Elev= 30
  4156.2  373.80  4347.5  360.44  4457.8  357.03  4557.2  358.75  4628.5  359.92
  4708.5  355.03  4730.7  356.08  4744.1  353.99  4799.2  353.41  4816.1  355.54
  4824.1  353.02  4838.1  353.13  4854.4  354.84  4859.7  352.73  4869.5  355.30
  4884.6  355.30  4890.9  350.46  4901.6  355.44  4909.5  356.04  4970.0  355.36
  4994.9  352.85  4998.7  354.33  5018.6  351.68  5036.8  344.42  5037.5  343.92
  5041.9  344.42  5049.8  353.12  5065.6  354.88  5291.4  357.83  5529.0  371.13
#Mann=6,-1,0
  4156.2    0.05       0  4557.2    0.12       0  4838.1     0.1       0
  5036.8    0.07       0  5041.9     0.1       0  5065.6    0.05       0
Bank Sta=5036.8,5041.9
Exp/Cntr=0.3,0.1

Type RM Length L Ch R = 1,5994,463,463,463
BEGIN DESCRIPTION:
Clear Creek T 2 11.0
END DESCRIPTION:
XS GIS Cut Line= 3
      2749675.98      6788461.02      2749126.00      6789111.00
      2748925.98      6789511.04
#Sta/Elev= 30
  4143.5  381.39  4214.3  378.84  4257.2  374.77  4306.6  373.55  4413.2  362.60
  4512.0  356.09  4554.9  354.46  4715.6  354.21  4916.3  353.61  4924.1  351.56
  4930.6  353.33  4938.4  350.25  4944.2  351.94  4952.7  349.96  4959.2  353.41
  5003.3  351.75  5008.9  344.02  5025.7  347.34  5028.7  343.55  5029.4  343.05
  5033.9  343.55  5048.0  344.04  5070.4  350.01  5076.0  354.18  5087.1  354.41
  5159.9  353.61  5165.4  352.26  5230.6  355.48  5294.0  358.97  5442.2  372.73
#Mann=7,-1,0
  4143.5    0.05       0  4715.6     0.1       0  4944.2    0.12       0
  5028.7    0.07       0  5033.9    0.12       0  5087.1     0.1       0
  5230.6    0.05       0
Bank Sta=5028.7,5033.9
Exp/Cntr=0.3,0.1

Type RM Length L Ch R = 1,5531,455,455,455
BEGIN DESCRIPTION:
Clear Creek T 2 10.0
END DESCRIPTION:
XS GIS Cut Line= 3
      2749576.02      6788510.98      2748776.00      6789061.00
      2748425.97      6789461.03
#Sta/Elev= 30
  4028.1  379.33  4086.3  377.80  4307.5  355.18  4527.2  352.79  4543.9  352.45
  4735.5  351.24  4841.2  346.18  4848.1  348.94  4854.2  346.47  4863.0  348.21
  4883.9  346.72  4898.8  348.04  4904.9  351.58  4955.7  351.60  4968.6  348.14
  4974.0  342.32  4974.7  341.82  4979.2  342.32  4985.4  343.63  4995.9  351.77
  5002.3  351.77  5006.1  355.04  5034.2  355.47  5069.7  353.69  5161.7  354.23
  5211.6  351.79  5353.4  353.51  5388.6  350.70  5437.9  360.66  5530.5  369.17
#Mann=8,-1,0
  4028.1    0.05       0  4527.2    0.12       0  4543.9     0.1       0
  4735.5    0.12       0  4974.0    0.07       0  4979.2    0.12       0
  5034.2     0.1       0  5161.7    0.05       0
Bank Sta=4974,4979.2
Exp/Cntr=0.3,0.1

Type RM Length L Ch R = 1,5076,459,459,459
BEGIN DESCRIPTION:
Clear Creek T 2 9.0
END DESCRIPTION:
XS GIS Cut Line= 3
      2749226.00      6788111.00      2748826.00      6788661.00
      2748358.72      6789466.50
#Sta/Elev= 30
  4320.8  377.48  4549.9  355.99  4857.5  349.97  4886.9  345.13  4924.1  350.25
  4926.3  350.31  4958.0  351.11  4970.1  340.06  4970.8  339.56  4975.3  340.06
  4993.5  348.71  5003.8  348.85  5008.7  344.60  5014.5  349.50  5030.3  340.88
  5058.7  347.86  5067.5  343.29  5073.3  348.82  5116.5  351.63  5318.7  352.27
  5489.3  351.79  5565.2  347.83  5601.0  352.36  5651.3  356.54  5667.1  349.24
  5694.5  350.02  5725.9  353.16  5731.6  359.14  5753.2  363.02  5932.1  375.60
#Mann=8,-1,0
  4320.8    0.05       0  4924.1     0.1       0  4926.3    0.12       0
  4970.1    0.07       0  4975.3    0.12       0  5318.7     0.1       0
  5489.3    0.12       0  5601.0    0.05       0
Bank Sta=4970.1,4975.3
Exp/Cntr=0.3,0.1

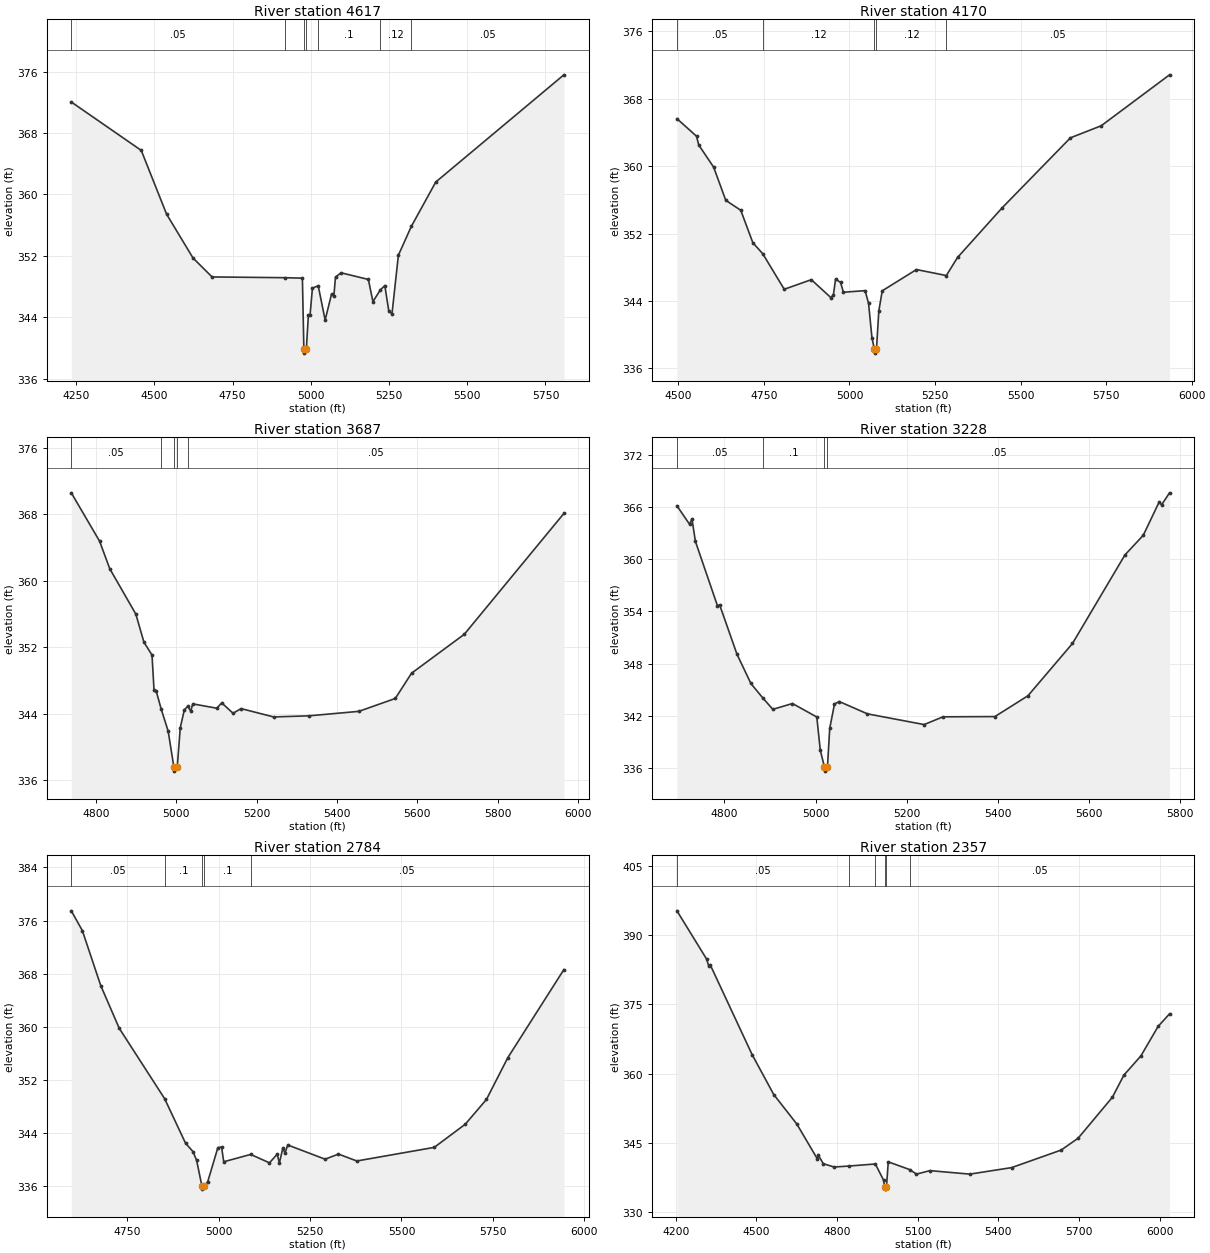
Type RM Length L Ch R = 1,4617,447,447,447
BEGIN DESCRIPTION:
Clear Creek T 2 8.0
END DESCRIPTION:
XS GIS Cut Line= 3
      2748169.17      6787965.07      2748476.00      6788661.00
      2748326.00      6789460.99
#Sta/Elev= 30
  4234.4  372.04  4458.0  365.73  4538.9  357.43  4623.4  351.71  4684.3  349.24
  4918.0  349.14  4973.1  349.08  4977.8  339.81  4978.6  339.31  4983.4  339.81
  4986.0  340.06  4992.2  344.22  4997.5  344.22  5005.1  347.77  5023.6  348.10
  5045.8  343.62  5066.2  347.00  5073.8  346.82  5078.9  349.22  5096.7  349.78
  5184.0  348.91  5198.5  346.02  5222.0  347.53  5236.6  348.12  5249.3  344.77
  5259.5  344.45  5279.9  352.07  5321.2  355.82  5399.4  361.61  5808.9  375.58
#Mann=7,-1,0
  4234.4    0.05       0  4918.0    0.12       0  4977.8    0.07       0
  4983.4    0.12       0  5023.6     0.1       0  5222.0    0.12       0
  5321.2    0.05       0
Bank Sta=4977.8,4983.4
Exp/Cntr=0.3,0.1

Type RM Length L Ch R = 1,4170,483,483,483
BEGIN DESCRIPTION:
Clear Creek T 2 7.0
END DESCRIPTION:
XS GIS Cut Line= 3
      2747825.98      6788260.98      2748126.00      6788661.00
      2748122.55      6789600.57
#Sta/Elev= 30
  4495.7  365.62  4553.0  363.54  4559.3  362.51  4603.0  359.87  4638.4  355.94
  4682.2  354.76  4717.6  350.91  4746.6  349.60  4809.3  345.39  4888.4  346.53
  4945.7  344.40  4953.0  344.73  4959.3  346.60  4973.9  346.20  4982.2  345.04
  5045.7  345.23  5055.7  343.72  5065.7  339.63  5072.5  338.32  5073.5  337.82
  5078.9  338.32  5085.7  342.81  5095.7  345.21  5195.7  347.73  5283.0  347.02
  5315.7  349.16  5445.7  355.03  5645.7  363.35  5735.7  364.78  5935.3  370.82
#Mann=5,-1,0
  4495.7    0.05       0  4746.6    0.12       0  5072.5    0.07       0
  5078.9    0.12       0  5283.0    0.05       0
Bank Sta=5072.5,5078.9
Exp/Cntr=0.3,0.1

Type RM Length L Ch R = 1,3687,459,459,459
BEGIN DESCRIPTION:
Clear Creek T 2 6.0
END DESCRIPTION:
XS GIS Cut Line= 3
      2747652.26      6788351.04      2747676.00      6788611.00
      2747806.94      6789566.52
#Sta/Elev= 30
  4739.1  370.57  4809.4  364.76  4834.8  361.44  4899.7  355.98  4919.8  352.60
  4939.9  351.06  4945.0  346.79  4950.1  346.76  4962.9  344.53  4980.1  341.90
  4994.3  337.59  4995.3  337.09  5001.0  337.59  5002.7  337.59  5010.2  342.31
  5020.3  344.45  5028.9  344.90  5036.2  344.31  5041.3  345.18  5101.1  344.66
  5113.4  345.30  5141.5  344.05  5161.6  344.61  5242.4  343.61  5329.9  343.74
  5454.4  344.28  5545.2  345.83  5585.6  348.87  5716.8  353.55  5964.6  368.09
#Mann=5,-1,0
  4739.1    0.05       0  4962.9    0.12       0  4994.3    0.07       0
  5001.0    0.12       0  5028.9    0.05       0
Bank Sta=4994.3,5001
Exp/Cntr=0.3,0.1

Type RM Length L Ch R = 1,3228,444,444,444
BEGIN DESCRIPTION:
Clear Creek T 2 5.0
END DESCRIPTION:
XS GIS Cut Line= 3
      2747375.99      6788461.05      2747326.00      6788761.00
      2747526.00      6789511.00
#Sta/Elev= 30
  4696.0  366.14  4723.8  364.01  4728.9  364.65  4736.5  362.05  4784.7  354.68
  4789.7  354.75  4827.7  349.08  4858.2  345.72  4884.6  344.04  4906.3  342.75
  4949.4  343.42  5002.7  341.87  5010.4  338.05  5019.4  336.15  5020.4  335.65
  5026.1  336.15  5031.1  340.56  5041.5  343.36  5051.8  343.65  5113.9  342.23
  5238.1  341.00  5279.5  341.89  5393.4  341.92  5465.8  344.31  5563.5  350.32
  5678.6  360.50  5718.7  362.75  5753.7  366.59  5758.8  366.24  5776.3  367.63
#Mann=4,-1,0
  4696.0    0.05       0  4884.6     0.1       0  5019.4    0.07       0
  5026.1    0.05       0
Bank Sta=5019.4,5026.1
Exp/Cntr=0.3,0.1

Type RM Length L Ch R = 1,2784,427,427,427
BEGIN DESCRIPTION:
Clear Creek T 2 4.0
END DESCRIPTION:
XS GIS Cut Line= 3
      2746926.00      6788311.00      2746976.00      6788711.00
      2747476.00      6789510.99
#Sta/Elev= 30
  4597.5  377.47  4627.7  374.49  4678.1  366.19  4728.5  359.78  4852.7  349.16
  4909.9  342.45  4930.1  341.20  4940.1  339.87  4954.4  336.04  4955.5  335.54
  4961.1  336.04  4970.4  336.65  4998.1  341.78  5008.3  341.89  5014.2  339.66
  5087.8  340.77  5139.2  339.50  5160.4  340.81  5166.3  339.47  5175.7  341.73
  5181.6  340.97  5189.3  342.19  5291.3  340.05  5327.8  340.82  5378.0  339.78
  5589.6  341.83  5674.5  345.32  5732.3  349.05  5790.7  355.34  5944.0  368.62
#Mann=5,-1,0
  4597.5    0.05       0  4852.7     0.1       0  4954.4    0.07       0
  4961.1     0.1       0  5087.8    0.05       0
Bank Sta=4954.4,4961.1
Exp/Cntr=0.3,0.1

Type RM Length L Ch R = 1,2357,406,406,406
BEGIN DESCRIPTION:
Clear Creek T 2 3.0
END DESCRIPTION:
XS GIS Cut Line= 3
      2746626.00      6788111.04      2746726.00      6788911.00
      2747476.00      6789611.00
#Sta/Elev= 30
  4204.5  395.27  4315.3  384.77  4322.9  383.25  4327.9  383.62  4484.1  364.11
  4564.7  355.45  4650.4  349.07  4726.0  341.59  4731.0  342.26  4748.7  340.48
  4789.0  339.75  4843.4  339.96  4942.4  340.41  4972.9  336.92  4977.1  335.46
  4978.2  334.96  4983.9  335.46  4990.5  340.87  5070.9  339.18  5095.4  338.21
  5145.3  338.97  5293.8  338.21  5449.1  339.62  5633.3  343.42  5696.8  346.00
  5824.3  354.89  5866.8  359.66  5930.3  363.84  5994.3  370.24  6036.6  372.94
#Mann=6,-1,0
  4204.5    0.05       0  4843.4     0.1       0  4942.4    0.12       0
  4977.1    0.07       0  4983.9    0.12       0  5070.9    0.05       0
Bank Sta=4977.1,4983.9
Exp/Cntr=0.3,0.1

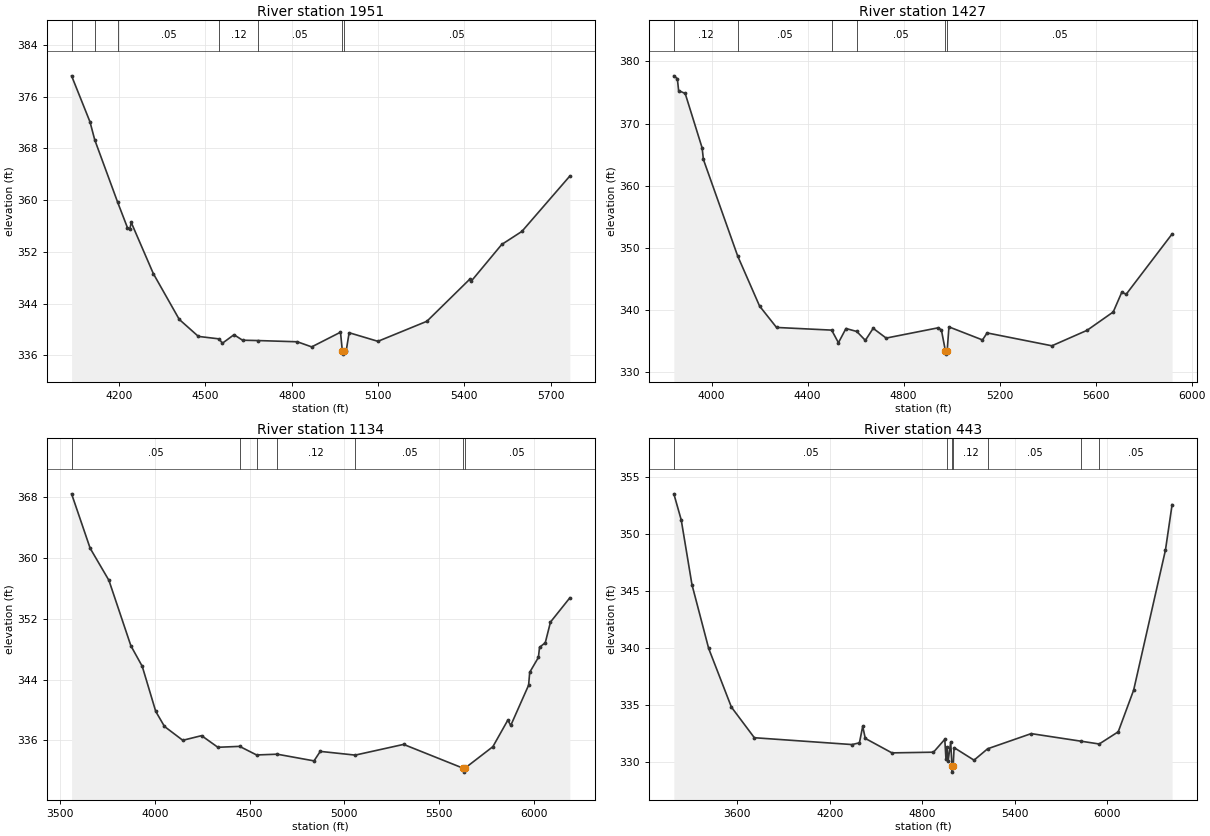
Type RM Length L Ch R = 1,1951,524,524,524
BEGIN DESCRIPTION:
Mapping XS c7926be4
END DESCRIPTION:
XS GIS Cut Line= 2
      2746492.30      6788247.04      2746565.51      6789977.50
#Sta/Elev= 30
  4034.7  379.22  4098.7  372.10  4115.2  369.32  4195.1  359.64  4228.8  355.75
  4237.1  355.54  4242.1  356.54  4318.9  348.63  4409.0  341.55  4475.5  338.92
  4546.9  338.54  4559.1  337.87  4599.2  339.18  4629.2  338.33  4682.3  338.28
  4819.4  338.09  4869.4  337.30  4969.5  339.57  4975.9  336.68  4977.0  336.18
  4983.0  336.68  4989.5  336.74  4999.5  339.49  5099.6  338.16  5269.8  341.26
  5419.1  347.78  5424.1  347.47  5530.0  353.14  5600.1  355.16  5766.7  363.72
#Mann=7,-1,0
  4034.7    0.05       0  4115.2    0.12       0  4195.1    0.05       0
  4546.9    0.12       0  4682.3    0.05       0  4975.9    0.04       0
  4983.0    0.05       0
Bank Sta=4975.9,4983
Exp/Cntr=0.3,0.1

Type RM Length L Ch R = 1,1427,293,293,293
BEGIN DESCRIPTION:
Clear Creek T 2 2.0
END DESCRIPTION:
XS GIS Cut Line= 3
      2746366.46      6788155.76      2746026.00      6789261.00
      2746358.50      6790117.75
#Sta/Elev= 30
  3843.0  377.68  3857.6  377.22  3862.9  375.31  3890.3  374.84  3960.9  366.08
  3966.1  364.24  4109.0  348.70  4200.1  340.66  4270.7  337.22  4500.5  336.79
  4528.6  334.76  4560.0  337.05  4605.1  336.57  4640.7  335.14  4673.3  337.08
  4727.4  335.51  4945.2  337.17  4957.6  336.79  4974.4  333.43  4975.5  332.93
  4981.5  333.43  4989.0  337.31  5128.7  335.21  5147.9  336.34  5417.8  334.27
  5564.4  336.76  5673.3  339.71  5708.6  342.85  5727.7  342.58  5918.5  352.25
#Mann=6,-1,0
  3843.0    0.12       0  4109.0    0.05       0  4500.5    0.12       0
  4605.1    0.05       0  4974.4    0.04       0  4981.5    0.05       0
Bank Sta=4974.4,4981.5
Exp/Cntr=0.3,0.1

Type RM Length L Ch R = 1,1134,691,691,691
BEGIN DESCRIPTION:
Mapping XS 69699b9b
END DESCRIPTION:
XS GIS Cut Line= 3
      2746178.81      6787881.10      2745761.41      6789273.84
      2746386.44      6790270.77
#Sta/Elev= 30
  3560.4  368.46  3658.4  361.30  3757.6  357.07  3873.5  348.46  3933.4  345.76
  4004.8  339.82  4050.9  337.84  4147.5  336.02  4246.8  336.63  4332.8  335.10
  4447.6  335.22  4537.2  334.09  4646.0  334.19  4840.4  333.31  4873.4  334.56
  5057.9  334.07  5313.4  335.48  5629.2  332.33  5630.3  331.83  5636.3  332.33
  5784.7  335.18  5863.7  338.68  5879.0  337.97  5973.3  343.27  5979.2  344.97
  6025.1  346.93  6031.0  348.25  6061.4  348.87  6088.8  351.58  6191.0  354.77
#Mann=7,-1,0
  3560.4    0.05       0  4447.6    0.12       0  4537.2    0.05       0
  4646.0    0.12       0  5057.9    0.05       0  5629.2    0.07       0
  5636.3    0.05       0
Bank Sta=5629.2,5636.3
Exp/Cntr=0.3,0.1

Type RM Length L Ch R = 1,443,0,0,0
BEGIN DESCRIPTION:
Clear Creek T 2 1.0
END DESCRIPTION:
XS GIS Cut Line= 3
      2745827.30      6787730.63      2745206.16      6789430.93
      2746341.94      6790284.55
#Sta/Elev= 30
  3189.8  353.56  3237.7  351.27  3307.3  345.59  3415.6  339.99  3563.0  334.84
  3711.9  332.15  4345.0  331.55  4393.2  331.70  4414.5  333.15  4431.3  332.09
  4603.9  330.82  4873.5  330.88  4946.8  332.01  4954.5  330.27  4962.0  331.31
  4968.1  330.07  4985.0  331.76  4993.8  329.63  4994.9  329.13  5001.0  329.63
  5007.2  331.28  5136.4  330.18  5224.7  331.18  5507.1  332.51  5832.8  331.84
  5948.2  331.60  6071.5  332.67  6171.5  336.33  6377.7  348.62  6420.8  352.61
#Mann=7,-1,0
  3189.8    0.05       0  4962.0    0.12       0  4993.8    0.07       0
  5001.0    0.12       0  5224.7    0.05       0  5832.8    0.12       0
  5948.2    0.05       0
Bank Sta=4993.8,5001
Exp/Cntr=0.3,0.1

Chan Stop Cuts=-1