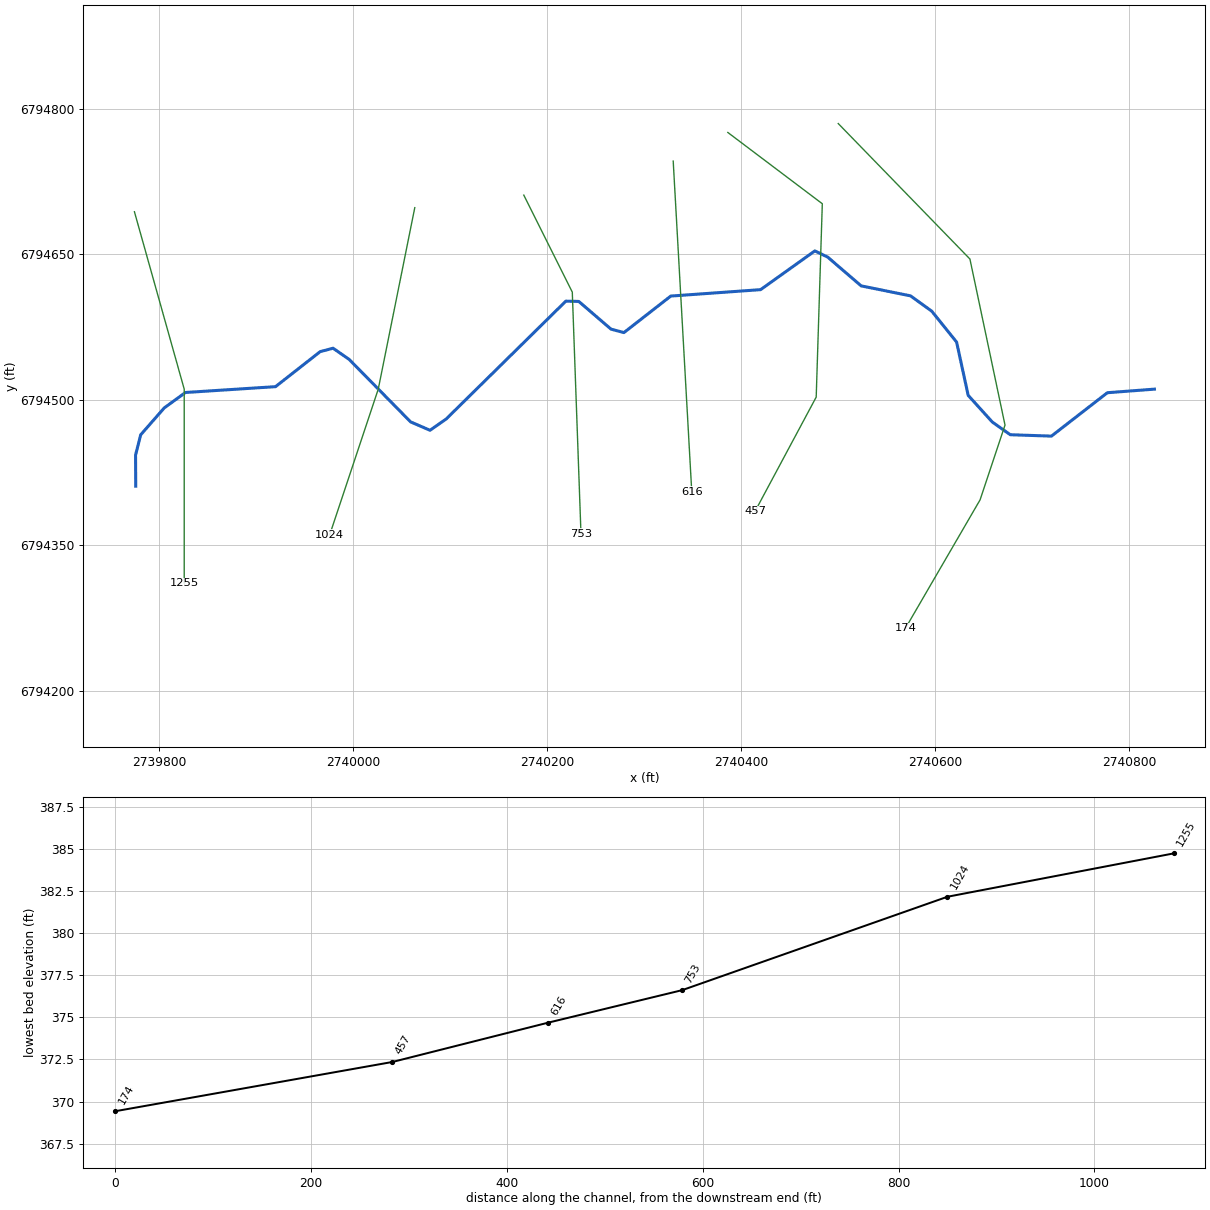
--- Clear Creek T 20.prj (project) ---

Proj Title=Clear Creek T 20 Base Level Engineering
Current Plan=p01
Default Exp/Contr=0.3,0.1
English Units
Geom File=g01
Flow File=f01
Plan File=p01
BEGIN DESCRIPTION:
Clear Creek T 20
END DESCRIPTION:

--- Clear Creek T 20.p01 (plan) ---

Plan Title=Multiple Run
Short Identifier=Multiple
Geom File=g01
Flow File=f01
Subcritical Flow
K Sum by GR= 0
Std Step Tol= 0.01
Critical Tol= 0.01
Num of Std Step Trials= 20
Max Error Tol= 0.3
Flow Tol Ratio= 0.001
Split Flow NTrial= 30
Split Flow Tol= 0.02
Split Flow Ratio= 0.02
Log Output Level= 0
Friction Slope Method= 1
Unsteady Friction Slope Method= 2
Unsteady Bridges Friction Slope Method= 1
Parabolic Critical Depth
Global Vel Dist=  1 , 1 , 1
Global Log Level= 0
CheckData=True
Encroach Param= -1, 0, 0, 0
BEGIN DESCRIPTION:
Multiple Run
END DESCRIPTION:

--- Clear Creek T 20.f01 (steady flow) ---

Flow Title=Multiple
Number of Profiles=7
Profile Names=10-year,25-year,50-year,1pct_min,100-year,1pct_plu,500-year
River Rch & RM= Clear Creek T 20,Reach-1,1255
     125     151     170      96     191     382     240
Boundary for River Rch & Prof#=Clear Creek T 20,Reach-1,1
Up Type=0
Dn Type=3
Dn Slope=0.005
Boundary for River Rch & Prof#=Clear Creek T 20,Reach-1,2
Up Type=0
Dn Type=3
Dn Slope=0.005
Boundary for River Rch & Prof#=Clear Creek T 20,Reach-1,3
Up Type=0
Dn Type=3
Dn Slope=0.005
Boundary for River Rch & Prof#=Clear Creek T 20,Reach-1,4
Up Type=0
Dn Type=3
Dn Slope=0.005
Boundary for River Rch & Prof#=Clear Creek T 20,Reach-1,5
Up Type=0
Dn Type=3
Dn Slope=0.005
Boundary for River Rch & Prof#=Clear Creek T 20,Reach-1,6
Up Type=0
Dn Type=3
Dn Slope=0.005
Boundary for River Rch & Prof#=Clear Creek T 20,Reach-1,7
Up Type=0
Dn Type=3
Dn Slope=0.005

--- Clear Creek T 20.g01 (geometry) ---

Geom Title=Existing Conditions

River Reach=Clear Creek T 20,Reach-1
Reach XY= 30
      2739776.00      6794411.00      2739775.85      6794443.07
      2739781.13      6794463.94      2739805.45      6794491.69
      2739827.30      6794507.55      2739920.11      6794513.56
      2739966.15      6794549.66      2739979.42      6794553.18
      2739996.03      6794541.62      2740059.33      6794477.26
      2740079.33      6794468.61      2740096.00      6794480.22
      2740219.33      6794601.70      2740232.66      6794601.40
      2740265.94      6794572.85      2740279.22      6794569.29
      2740327.50      6794606.93      2740420.10      6794613.55
      2740476.01      6794653.47      2740489.24      6794647.12
      2740523.74      6794617.42      2740574.57      6794607.17
      2740596.47      6794591.38      2740622.10      6794559.53
      2740634.05      6794504.59      2740658.94      6794477.06
      2740677.41      6794464.02      2740719.86      6794462.58
      2740777.49      6794507.31      2740826.00      6794511.00

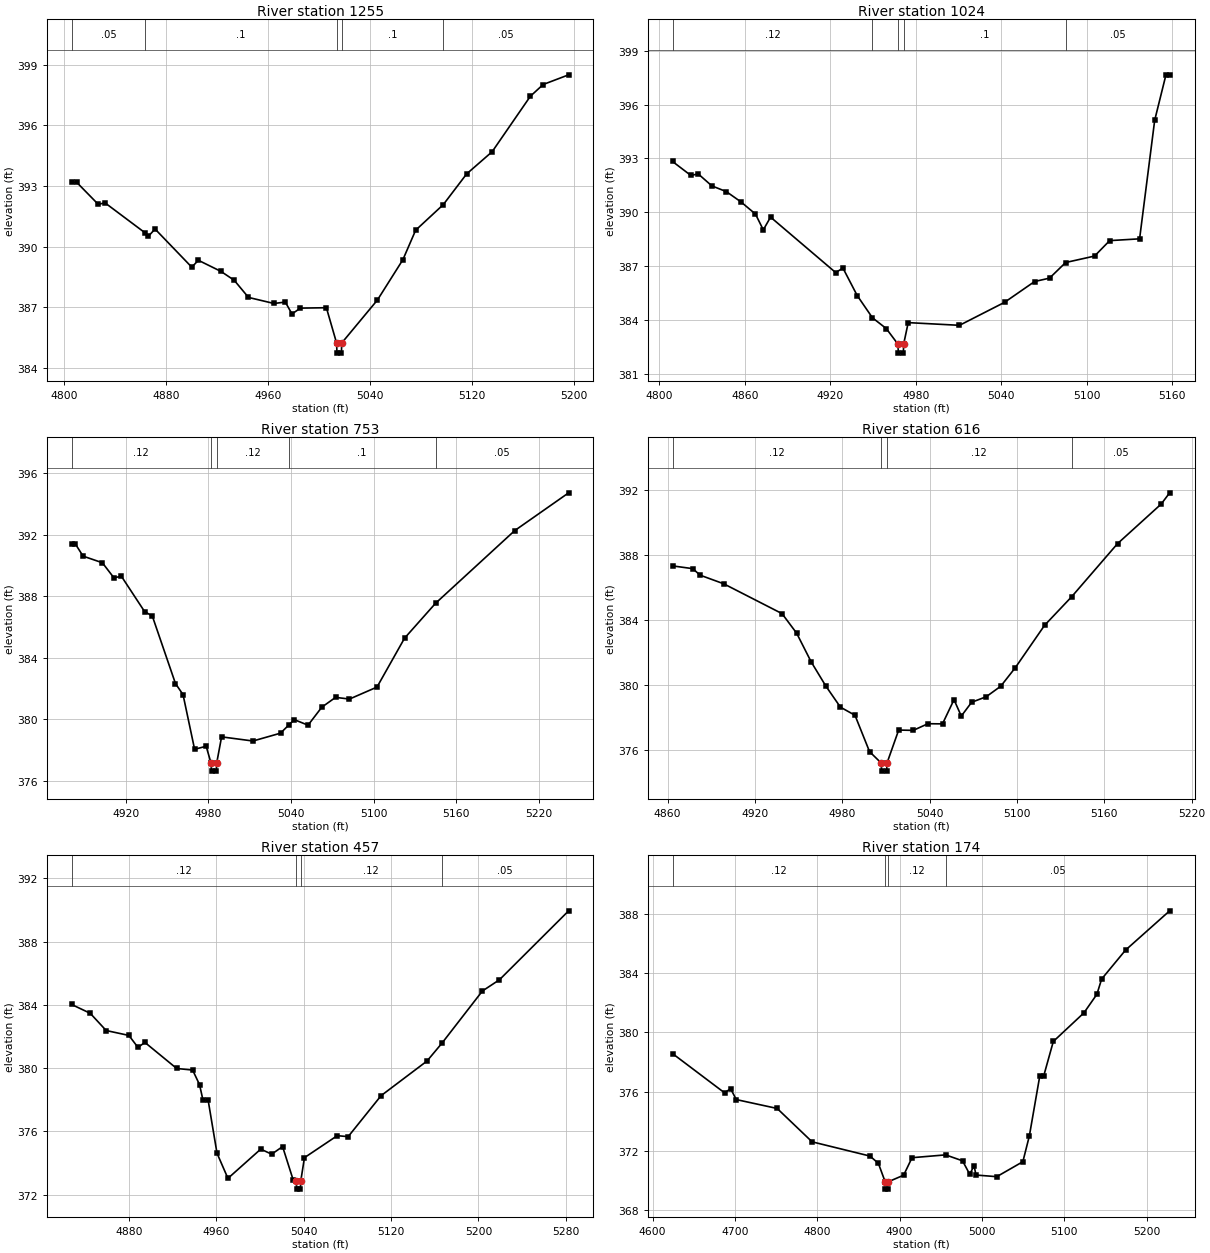
Type RM Length L Ch R = 1,1255,231,231,231
BEGIN DESCRIPTION:
Clear Creek T 20 4.0
END DESCRIPTION:
XS GIS Cut Line= 3
      2739774.67      6794693.86      2739826.00      6794511.00
      2739826.00      6794311.03
#Sta/Elev= 30
  4806.0  393.18  4810.1  393.18  4827.0  392.09  4832.2  392.17  4863.9  390.67
  4866.3  390.51  4871.5  390.87  4900.3  388.98  4905.5  389.32  4923.2  388.77
  4933.6  388.33  4944.8  387.48  4964.8  387.18  4973.7  387.25  4978.9  386.66
  4985.5  386.95  5005.9  386.97  5013.9  385.22  5014.2  384.72  5017.7  384.72
  5017.9  385.22  5045.9  387.35  5065.9  389.35  5075.9  390.81  5097.6  392.08
  5115.9  393.60  5135.9  394.70  5165.9  397.45  5175.9  398.03  5195.9  398.51
#Mann=5,-1,0
  4806.0    0.05       0  4863.9     0.1       0  5013.9    0.07       0
  5017.9     0.1       0  5097.6    0.05       0
Bank Sta=5013.9,5017.9
Exp/Cntr=0.3,0.1

Type RM Length L Ch R = 1,1024,271,271,271
BEGIN DESCRIPTION:
Clear Creek T 20 3.0
END DESCRIPTION:
XS GIS Cut Line= 3
      2740063.65      6794698.06      2740026.00      6794511.00
      2739976.01      6794361.02
#Sta/Elev= 30
  4809.2  392.83  4822.1  392.05  4827.2  392.14  4836.8  391.47  4847.0  391.15
  4857.2  390.58  4867.4  389.90  4872.9  389.02  4878.0  389.73  4923.7  386.64
  4928.8  386.89  4938.8  385.36  4949.5  384.12  4959.2  383.52  4967.4  382.65
  4967.7  382.15  4971.2  382.15  4971.4  382.65  4974.6  383.85  5010.6  383.70
  5042.2  384.98  5063.3  386.14  5073.8  386.33  5085.1  387.20  5105.4  387.56
  5116.0  388.42  5137.0  388.52  5147.6  395.13  5155.5  397.66  5158.1  397.66
#Mann=5,-1,0
  4809.2    0.12       0  4949.5     0.1       0  4967.4    0.07       0
  4971.4     0.1       0  5085.1    0.05       0
Bank Sta=4967.4,4971.4
Exp/Cntr=0.3,0.1

Type RM Length L Ch R = 1,753,137,137,137
BEGIN DESCRIPTION:
Clear Creek T 20 2.0
END DESCRIPTION:
XS GIS Cut Line= 3
      2740176.00      6794710.99      2740226.00      6794611.00
      2740234.95      6794361.86
#Sta/Elev= 30
  4880.6  391.39  4883.4  391.39  4889.0  390.60  4903.0  390.17  4911.3  389.20
  4916.9  389.28  4933.7  386.99  4939.3  386.70  4956.1  382.31  4961.6  381.59
  4970.0  378.03  4978.4  378.23  4982.0  377.11  4982.3  376.61  4985.8  376.61
  4986.0  377.11  4989.6  378.84  5012.4  378.57  5032.4  379.08  5038.3  379.60
  5042.4  379.96  5052.4  379.60  5062.4  380.77  5072.4  381.41  5082.5  381.30
  5102.5  382.08  5122.5  385.26  5145.0  387.53  5202.5  392.26  5241.7  394.72
#Mann=5,-1,0
  4880.6    0.12       0  4982.0    0.07       0  4986.0    0.12       0
  5038.3     0.1       0  5145.0    0.05       0
Bank Sta=4982,4986
Exp/Cntr=0.3,0.1

Type RM Length L Ch R = 1,616,159,159,159
BEGIN DESCRIPTION:
Mapping XS a5b56158
END DESCRIPTION:
XS GIS Cut Line= 2
      2740330.01      6794746.07      2740349.13      6794405.21
#Sta/Elev= 30
  4863.4  387.32  4877.3  387.15  4882.3  386.75  4898.5  386.22  4938.6  384.38
  4948.6  383.18  4958.6  381.41  4968.6  379.93  4978.7  378.62  4988.7  378.12
  4998.7  375.88  5006.7  375.18  5007.0  374.68  5010.5  374.68  5010.7  375.18
  5018.7  377.21  5028.7  377.19  5038.8  377.60  5048.8  377.59  5056.7  379.08
  5061.7  378.07  5068.8  378.92  5078.8  379.26  5088.8  379.91  5098.8  381.05
  5118.9  383.66  5137.5  385.42  5169.0  388.69  5199.0  391.13  5204.8  391.82
#Mann=4,-1,0
  4863.4    0.12       0  5006.7    0.07       0  5010.7    0.12       0
  5137.5    0.05       0
Bank Sta=5006.7,5010.7
Exp/Cntr=0.3,0.1

Type RM Length L Ch R = 1,457,283,283,283
BEGIN DESCRIPTION:
Mapping XS f4a7c06e
END DESCRIPTION:
XS GIS Cut Line= 4
      2740386.31      6794775.56      2740483.69      6794702.10
      2740477.40      6794502.80      2740414.43      6794385.18
#Sta/Elev= 30
  4827.7  384.03  4844.8  383.47  4859.4  382.38  4880.2  382.07  4888.5  381.31
  4894.8  381.63  4923.9  379.98  4938.5  379.88  4944.8  378.96  4948.0  377.97
  4952.7  377.97  4960.8  374.62  4970.8  373.03  5000.8  374.88  5010.8  374.56
  5020.8  375.04  5030.4  372.95  5033.4  372.85  5033.6  372.35  5037.1  372.35
  5037.4  372.85  5040.8  374.34  5070.8  375.73  5080.8  375.67  5110.9  378.26
  5152.9  380.45  5166.6  381.58  5203.6  384.88  5219.2  385.59  5282.5  389.95
#Mann=4,-1,0
  4827.7    0.12       0  5033.4    0.07       0  5037.4    0.12       0
  5166.6    0.05       0
Bank Sta=5033.4,5037.4
Exp/Cntr=0.3,0.1

Type RM Length L Ch R = 1,174,0,0,0
BEGIN DESCRIPTION:
Clear Creek T 20 1.0
END DESCRIPTION:
XS GIS Cut Line= 5
      2740500.14      6794784.73      2740635.84      6794645.11
      2740672.00      6794473.98      2740646.31      6794396.89
      2740569.47      6794264.66
#Sta/Elev= 30
  4624.2  378.57  4687.5  375.92  4694.7  376.21  4701.6  375.47  4751.3  374.87
  4793.7  372.62  4864.0  371.66  4874.2  371.17  4882.4  369.93  4882.7  369.43
  4886.2  369.43  4886.4  369.93  4904.9  370.37  4915.1  371.55  4955.9  371.74
  4976.4  371.34  4985.2  370.43  4990.4  371.01  4992.8  370.38  5018.0  370.27
  5049.7  371.28  5057.6  373.02  5070.3  377.08  5075.1  377.08  5086.7  379.39
  5123.9  381.32  5139.6  382.57  5145.4  383.60  5174.4  385.55  5228.0  388.20
#Mann=4,-1,0
  4624.2    0.12       0  4882.4    0.04       0  4886.4    0.12       0
  4955.9    0.05       0
Bank Sta=4882.4,4886.4
Exp/Cntr=0.3,0.1

Chan Stop Cuts=-1