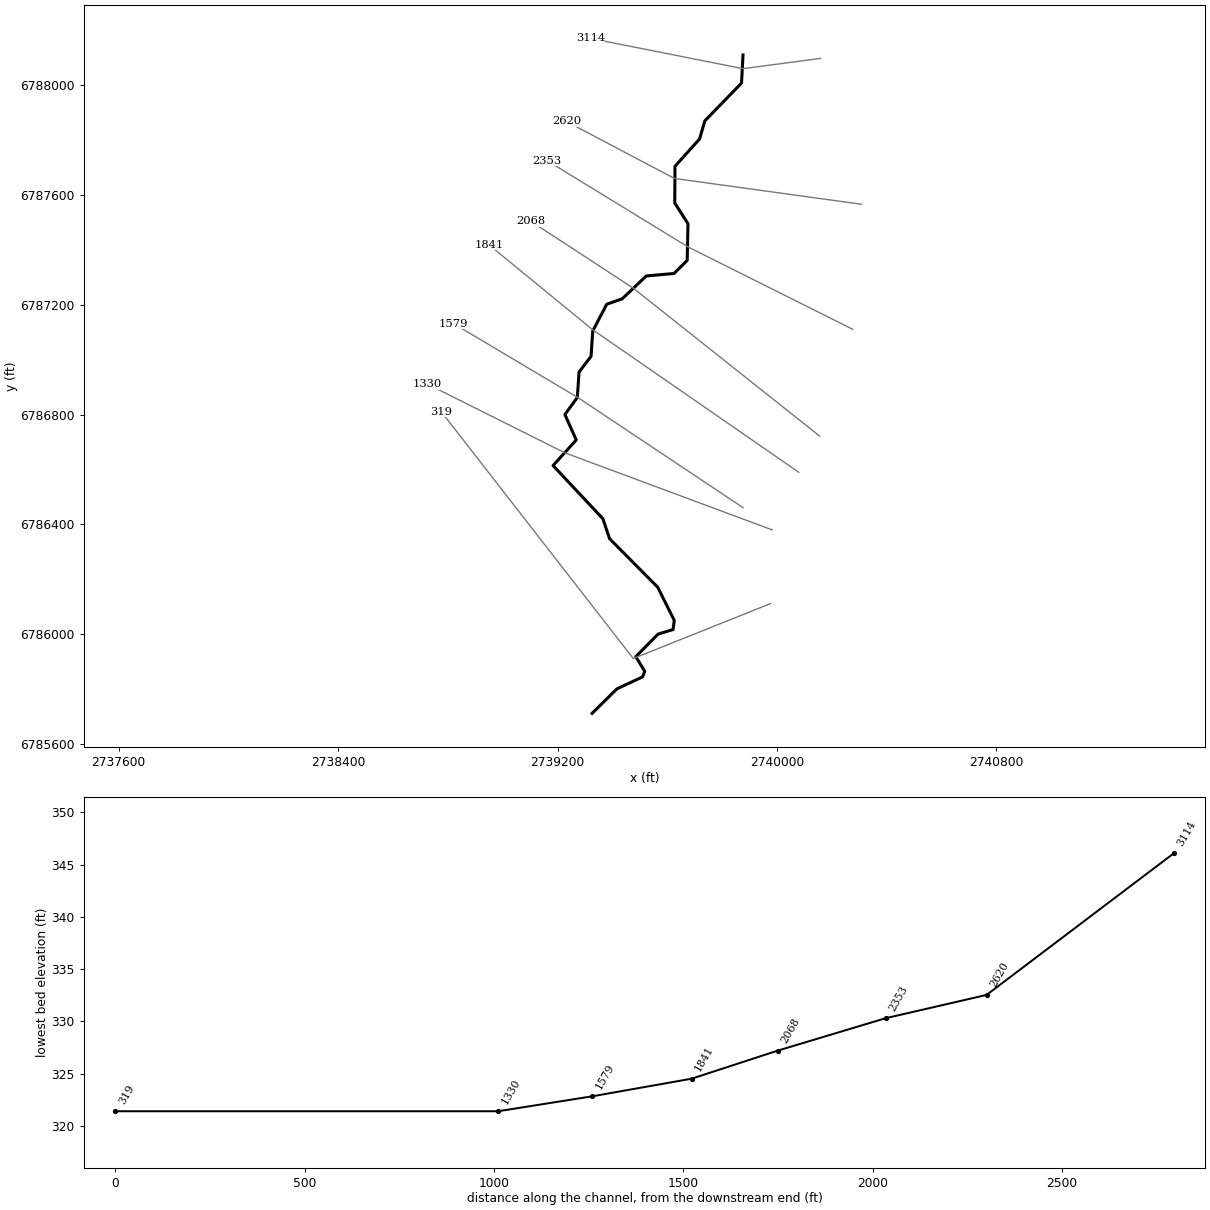
--- Clear Creek T 21.prj (project) ---

Proj Title=Clear Creek T 21 Base Level Engineering
Current Plan=p01
Default Exp/Contr=0.3,0.1
English Units
Geom File=g01
Flow File=f01
Plan File=p01
BEGIN DESCRIPTION:
Clear Creek T 21
END DESCRIPTION:

--- Clear Creek T 21.p01 (plan) ---

Plan Title=Multiple Run
Short Identifier=Multiple
Geom File=g01
Flow File=f01
Subcritical Flow
K Sum by GR= 0
Std Step Tol= 0.01
Critical Tol= 0.01
Num of Std Step Trials= 20
Max Error Tol= 0.3
Flow Tol Ratio= 0.001
Split Flow NTrial= 30
Split Flow Tol= 0.02
Split Flow Ratio= 0.02
Log Output Level= 0
Friction Slope Method= 1
Unsteady Friction Slope Method= 2
Unsteady Bridges Friction Slope Method= 1
Parabolic Critical Depth
Global Vel Dist=  1 , 1 , 1
Global Log Level= 0
CheckData=True
Encroach Param= -1, 0, 0, 0
BEGIN DESCRIPTION:
Multiple Run
END DESCRIPTION:

--- Clear Creek T 21.f01 (steady flow) ---

Flow Title=Multiple
Number of Profiles=7
Profile Names=10-year,25-year,50-year,1pct_min,100-year,1pct_plu,500-year
River Rch & RM= Clear Creek T 21,Reach-1,3114
     224     284     329     191     380     759     506
Boundary for River Rch & Prof#=Clear Creek T 21,Reach-1,1
Up Type=0
Dn Type=3
Dn Slope=0.005
Boundary for River Rch & Prof#=Clear Creek T 21,Reach-1,2
Up Type=0
Dn Type=3
Dn Slope=0.005
Boundary for River Rch & Prof#=Clear Creek T 21,Reach-1,3
Up Type=0
Dn Type=3
Dn Slope=0.005
Boundary for River Rch & Prof#=Clear Creek T 21,Reach-1,4
Up Type=0
Dn Type=3
Dn Slope=0.005
Boundary for River Rch & Prof#=Clear Creek T 21,Reach-1,5
Up Type=0
Dn Type=3
Dn Slope=0.005
Boundary for River Rch & Prof#=Clear Creek T 21,Reach-1,6
Up Type=0
Dn Type=3
Dn Slope=0.005
Boundary for River Rch & Prof#=Clear Creek T 21,Reach-1,7
Up Type=0
Dn Type=3
Dn Slope=0.005

--- Clear Creek T 21.g01 (geometry) ---

Geom Title=Existing Conditions

River Reach=Clear Creek T 21,Reach-1
Reach XY= 30
      2739876.00      6788111.00      2739870.65      6788008.50
      2739736.78      6787870.68      2739717.82      6787804.96
      2739628.05      6787705.14      2739627.21      6787571.51
      2739675.49      6787495.78      2739672.57      6787362.23
      2739624.75      6787314.51      2739523.58      6787305.46
      2739435.40      6787221.91      2739379.51      6787202.52
      2739328.32      6787105.06      2739322.15      6787012.60
      2739278.35      6786955.03      2739272.11      6786862.58
      2739226.82      6786800.29      2739268.15      6786707.59
      2739183.62      6786614.33      2739365.22      6786420.68
      2739389.63      6786347.79      2739565.24      6786170.68
      2739625.46      6786049.91      2739621.23      6786016.61
      2739566.62      6786000.11      2739485.30      6785917.68
      2739517.92      6785864.15      2739509.77      6785843.96
      2739416.33      6785800.28      2739326.00      6785711.00

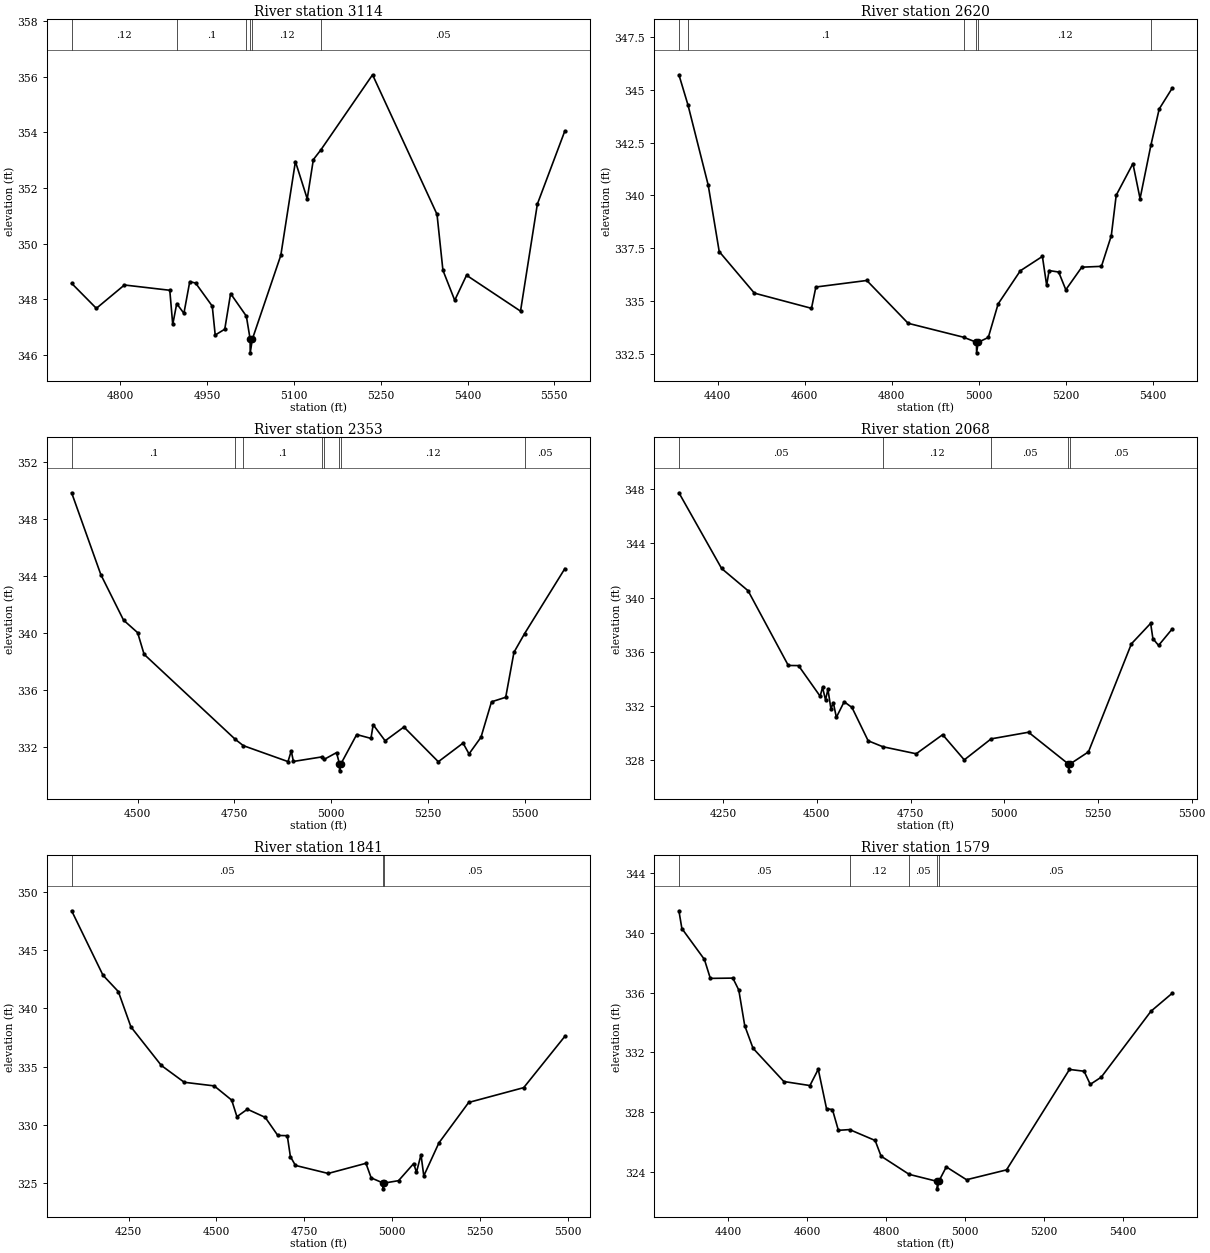
Type RM Length L Ch R = 1,3114,494,494,494
BEGIN DESCRIPTION:
Clear Creek T 21 8.0
END DESCRIPTION:
XS GIS Cut Line= 3
      2740158.32      6788098.38      2739876.00      6788061.00
      2739319.37      6788171.62
#Sta/Elev= 30
  4715.9  348.57  4758.6  347.67  4807.1  348.51  4885.5  348.32  4890.6  347.09
  4897.5  347.84  4909.9  347.49  4920.0  348.63  4930.1  348.58  4958.9  347.75
  4964.0  346.71  4980.5  346.92  4990.6  348.20  5017.8  347.39  5024.3  346.57
  5024.5  346.07  5028.3  346.57  5077.4  349.58  5102.6  352.95  5123.0  351.61
  5133.6  353.02  5146.6  353.37  5235.9  356.07  5347.3  351.05  5357.5  349.04
  5377.9  347.96  5398.3  348.86  5491.6  347.57  5520.7  351.42  5568.2  354.05
#Mann=6,-1,0
  4715.9    0.12       0  4897.5     0.1       0  5017.8    0.12       0
  5024.3    0.07       0  5028.3    0.12       0  5146.6    0.05       0
Bank Sta=5024.3,5028.3
Exp/Cntr=0.3,0.1

Type RM Length L Ch R = 1,2620,267,267,267
BEGIN DESCRIPTION:
Clear Creek T 21 7.0
END DESCRIPTION:
XS GIS Cut Line= 3
      2740307.77      6787566.80      2739626.00      6787661.00
      2739232.32      6787868.56
#Sta/Elev= 30
  4311.2  345.72  4332.0  344.29  4378.5  340.49  4403.8  337.34  4484.6  335.37
  4615.8  334.65  4625.9  335.66  4742.9  335.97  4837.9  333.94  4965.2  333.28
  4994.9  333.04  4995.2  332.54  4998.9  333.04  5022.1  333.27  5044.7  334.86
  5095.7  336.43  5146.4  337.11  5156.2  335.74  5161.8  336.44  5183.8  336.37
  5200.2  335.53  5236.9  336.60  5282.1  336.64  5304.7  338.09  5316.0  340.01
  5354.4  341.51  5370.8  339.85  5395.8  342.39  5414.8  344.10  5444.5  345.08
#Mann=6,-1,0
  4311.2    0.12       0  4332.0     0.1       0  4965.2    0.12       0
  4994.9    0.07       0  4998.9    0.12       0  5395.8    0.05       0
Bank Sta=4994.9,4998.9
Exp/Cntr=0.3,0.1

Type RM Length L Ch R = 1,2353,285,285,285
BEGIN DESCRIPTION:
Clear Creek T 21 6.0
END DESCRIPTION:
XS GIS Cut Line= 3
      2740275.97      6787111.01      2739676.00      6787411.00
      2739161.32      6787726.17
#Sta/Elev= 30
  4329.8  349.85  4405.2  344.10  4463.9  340.90  4500.3  340.02  4517.0  338.50
  4752.7  332.52  4773.4  332.08  4888.8  330.96  4897.2  331.71  4902.8  330.97
  4976.6  331.29  4982.5  331.12  5014.2  331.59  5021.7  330.81  5022.0  330.31
  5025.7  330.81  5066.3  332.86  5103.1  332.59  5108.9  333.55  5139.8  332.42
  5188.3  333.39  5277.2  330.95  5341.1  332.26  5356.5  331.50  5387.4  332.67
  5414.6  335.16  5451.3  335.48  5472.6  338.64  5500.0  339.95  5604.1  344.52
#Mann=8,-1,0
  4329.8     0.1       0  4752.7    0.05       0  4773.4     0.1       0
  4976.6    0.05       0  4982.5    0.12       0  5021.7    0.07       0
  5025.7    0.12       0  5500.0    0.05       0
Bank Sta=5021.7,5025.7
Exp/Cntr=0.3,0.1

Type RM Length L Ch R = 1,2068,227,227,227
BEGIN DESCRIPTION:
Clear Creek T 21 5.0
END DESCRIPTION:
XS GIS Cut Line= 3
      2740155.68      6786721.55      2739476.00      6787261.00
      2739100.95      6787505.96
#Sta/Elev= 30
  4132.2  347.74  4246.1  342.15  4316.6  340.51  4424.0  334.99  4451.2  334.98
  4508.9  332.72  4515.3  333.37  4523.3  332.45  4529.7  333.23  4537.7  331.79
  4544.1  332.24  4552.2  331.16  4573.0  332.31  4593.8  331.89  4637.0  329.43
  4676.1  328.99  4765.2  328.47  4835.7  329.88  4893.4  328.02  4965.0  329.57
  5064.8  330.06  5171.4  327.71  5171.6  327.21  5175.4  327.71  5224.7  328.61
  5339.3  336.59  5390.6  338.10  5396.6  336.97  5411.7  336.47  5447.9  337.68
#Mann=5,-1,0
  4132.2    0.05       0  4676.1    0.12       0  4965.0    0.05       0
  5171.4    0.04       0  5175.4    0.05       0
Bank Sta=5171.4,5175.4
Exp/Cntr=0.3,0.1

Type RM Length L Ch R = 1,1841,262,262,262
BEGIN DESCRIPTION:
Clear Creek T 21 4.0
END DESCRIPTION:
XS GIS Cut Line= 3
      2740079.37      6786589.83      2739326.00      6787111.00
      2738949.51      6787419.32
#Sta/Elev= 30
  4088.2  348.38  4177.4  342.85  4221.0  341.45  4256.8  338.42  4343.4  335.11
  4408.5  333.67  4493.6  333.36  4543.4  332.14  4558.3  330.72  4588.0  331.36
  4638.7  330.66  4674.5  329.11  4701.5  329.09  4710.3  327.30  4724.6  326.54
  4817.8  325.85  4925.2  326.72  4940.1  325.47  4973.9  325.03  4974.1  324.53
  4977.9  325.03  5017.9  325.23  5061.0  326.70  5068.9  325.95  5081.8  327.46
  5089.7  325.64  5132.7  328.47  5217.4  331.94  5373.9  333.21  5490.9  337.61
#Mann=3,-1,0
  4088.2    0.05       0  4973.9    0.04       0  4977.9    0.05       0
Bank Sta=4973.9,4977.9
Exp/Cntr=0.3,0.1

Type RM Length L Ch R = 1,1579,249,249,249
BEGIN DESCRIPTION:
Clear Creek T 21 3.0
END DESCRIPTION:
XS GIS Cut Line= 3
      2739876.01      6786460.99      2739276.00      6786861.00
      2738821.61      6787131.45
#Sta/Elev= 30
  4274.6  341.48  4282.1  340.29  4339.2  338.22  4354.2  336.95  4411.3  336.97
  4426.3  336.17  4441.4  333.78  4462.4  332.27  4540.5  330.04  4606.6  329.77
  4627.7  330.86  4648.7  328.22  4663.7  328.16  4678.7  326.77  4707.1  326.82
  4771.9  326.09  4786.9  325.04  4858.1  323.82  4929.1  323.35  4929.4  322.85
  4933.1  323.35  4952.2  324.32  5003.5  323.46  5104.8  324.12  5264.4  330.85
  5301.4  330.73  5317.0  329.85  5344.8  330.33  5470.9  334.75  5524.5  335.95
#Mann=5,-1,0
  4274.6    0.05       0  4707.1    0.12       0  4858.1    0.05       0
  4929.1    0.05       0  4933.1    0.05       0
Bank Sta=4929.1,4933.1
Exp/Cntr=0.3,0.1

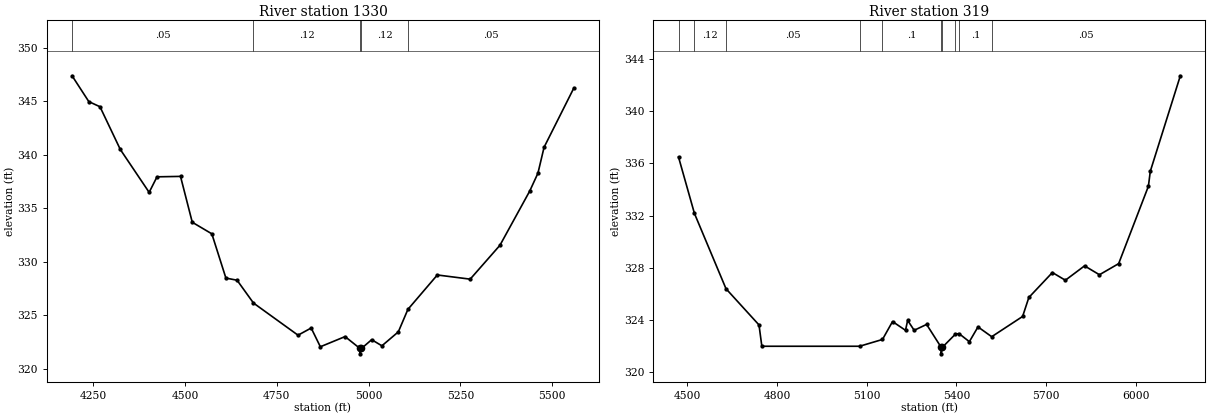
Type RM Length L Ch R = 1,1330,1011,1011,1011
BEGIN DESCRIPTION:
Clear Creek T 21 2.0
END DESCRIPTION:
XS GIS Cut Line= 3
      2739982.79      6786379.73      2739226.00      6786661.00
      2738725.99      6786911.01
#Sta/Elev= 30
  4192.6  347.37  4238.2  344.96  4268.6  344.48  4324.0  340.49  4402.5  336.49
  4423.9  337.94  4487.9  337.98  4519.9  333.70  4573.2  332.62  4611.5  328.49
  4641.9  328.29  4686.6  326.16  4807.9  323.16  4843.7  323.83  4868.7  322.08
  4936.0  323.03  4976.6  321.92  4976.9  321.42  4980.6  321.92  5008.4  322.74
  5036.3  322.17  5081.0  323.47  5107.1  325.57  5187.2  328.78  5276.7  328.39
  5357.7  331.55  5438.8  336.61  5461.2  338.28  5477.9  340.70  5559.0  346.23
#Mann=5,-1,0
  4192.6    0.05       0  4686.6    0.12       0  4976.6    0.07       0
  4980.6    0.12       0  5107.1    0.05       0
Bank Sta=4976.6,4980.6
Exp/Cntr=0.3,0.1

Type RM Length L Ch R = 1,319,0,0,0
BEGIN DESCRIPTION:
Clear Creek T 21 1.0
END DESCRIPTION:
XS GIS Cut Line= 3
      2739975.98      6786110.99      2739476.00      6785911.00
      2738775.98      6786811.02
#Sta/Elev= 30
  4470.1  336.47  4523.3  332.16  4628.9  326.40  4739.3  323.63  4748.8  322.00
  5075.8  322.00  5152.4  322.52  5186.0  323.89  5229.4  323.22  5236.6  323.98
  5258.4  323.22  5300.0  323.67  5348.7  321.92  5348.9  321.42  5352.7  321.92
  5396.0  322.92  5408.3  322.97  5443.0  322.35  5471.9  323.48  5517.8  322.73
  5621.2  324.28  5642.0  325.73  5720.8  327.64  5764.2  327.05  5828.4  328.15
  5878.2  327.47  5942.5  328.32  6042.0  334.24  6048.3  335.38  6148.8  342.69
#Mann=10,-1,0
  4470.1    0.05       0  4523.3    0.12       0  4628.9    0.05       0
  5075.8    0.12       0  5152.4     0.1       0  5348.7    0.03       0
  5352.7     0.1       0  5396.0    0.05       0  5408.3     0.1       0
  5517.8    0.05       0
Bank Sta=5348.7,5352.7
Exp/Cntr=0.3,0.1

Chan Stop Cuts=-1