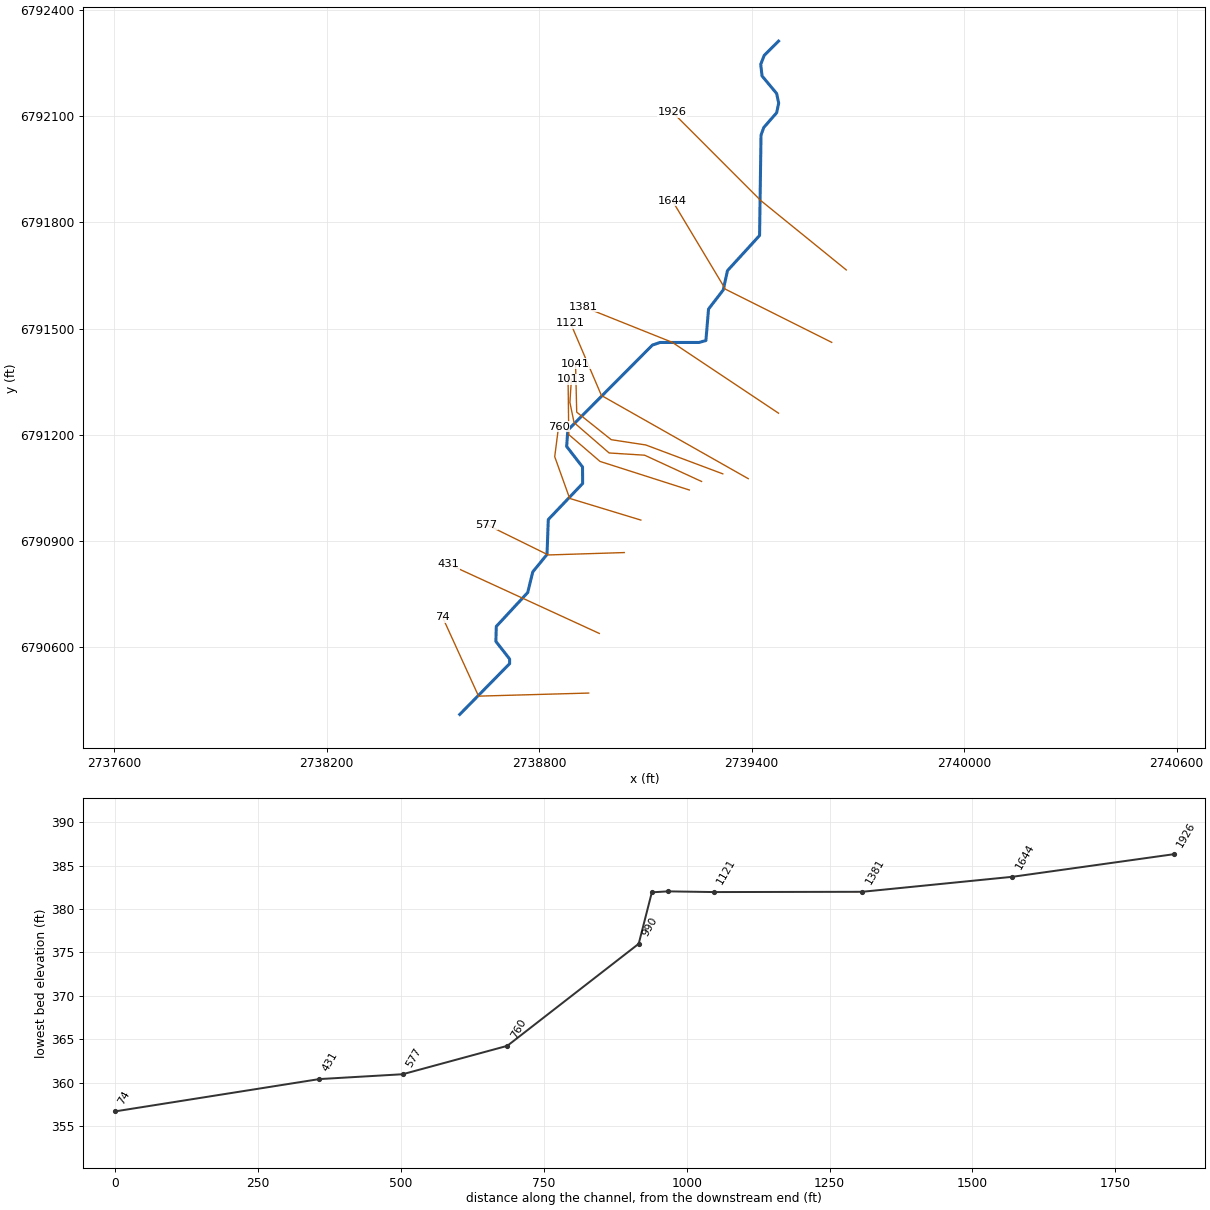
--- Clear Creek T 22.prj (project) ---

Proj Title=Clear Creek T 22 Base Level Engineering
Current Plan=p01
Default Exp/Contr=0.3,0.1
English Units
Geom File=g01
Flow File=f01
Plan File=p01
BEGIN DESCRIPTION:
Clear Creek T 22
END DESCRIPTION:

--- Clear Creek T 22.p01 (plan) ---

Plan Title=Multiple Run
Short Identifier=Multiple
Geom File=g01
Flow File=f01
Subcritical Flow
K Sum by GR= 0
Std Step Tol= 0.01
Critical Tol= 0.01
Num of Std Step Trials= 20
Max Error Tol= 0.3
Flow Tol Ratio= 0.001
Split Flow NTrial= 30
Split Flow Tol= 0.02
Split Flow Ratio= 0.02
Log Output Level= 0
Friction Slope Method= 1
Unsteady Friction Slope Method= 2
Unsteady Bridges Friction Slope Method= 1
Parabolic Critical Depth
Global Vel Dist=  1 , 1 , 1
Global Log Level= 0
CheckData=True
Encroach Param= -1, 0, 0, 0
BEGIN DESCRIPTION:
Multiple Run
END DESCRIPTION:

--- Clear Creek T 22.f01 (steady flow) ---

Flow Title=Multiple
Number of Profiles=7
Profile Names=10-year,25-year,50-year,1pct_min,100-year,1pct_plu,500-year
River Rch & RM= Clear Creek T 22,Reach-1,1926
     154     188     214     121     242     483     308
River Rch & RM= Clear Creek T 22,Reach-1,577
     242     309     360     209     417     833     559
Boundary for River Rch & Prof#=Clear Creek T 22,Reach-1,1
Up Type=0
Dn Type=3
Dn Slope=0.005
Boundary for River Rch & Prof#=Clear Creek T 22,Reach-1,2
Up Type=0
Dn Type=3
Dn Slope=0.005
Boundary for River Rch & Prof#=Clear Creek T 22,Reach-1,3
Up Type=0
Dn Type=3
Dn Slope=0.005
Boundary for River Rch & Prof#=Clear Creek T 22,Reach-1,4
Up Type=0
Dn Type=3
Dn Slope=0.005
Boundary for River Rch & Prof#=Clear Creek T 22,Reach-1,5
Up Type=0
Dn Type=3
Dn Slope=0.005
Boundary for River Rch & Prof#=Clear Creek T 22,Reach-1,6
Up Type=0
Dn Type=3
Dn Slope=0.005
Boundary for River Rch & Prof#=Clear Creek T 22,Reach-1,7
Up Type=0
Dn Type=3
Dn Slope=0.005

--- Clear Creek T 22.g01 (geometry) ---

Geom Title=Existing Conditions

River Reach=Clear Creek T 22,Reach-1
Reach XY= 30
      2739476.00      6792311.00      2739435.62      6792270.80
      2739425.76      6792245.60      2739429.38      6792212.67
      2739470.61      6792163.20      2739476.40      6792136.00
      2739470.62      6792108.82      2739434.19      6792067.08
      2739426.54      6792045.79      2739422.45      6791762.47
      2739331.85      6791663.29      2739319.86      6791608.82
      2739278.37      6791554.94      2739270.92      6791466.04
      2739251.38      6791460.62      2739141.18      6791460.60
      2739119.81      6791453.18      2738881.09      6791213.30
      2738877.81      6791167.12      2738922.63      6791109.27
      2738922.94      6791062.62      2738826.00      6790961.00
      2738822.37      6790862.50      2738782.11      6790813.18
      2738767.84      6790754.95      2738679.17      6790659.35
      2738677.99      6790617.05      2738716.67      6790567.55
      2738716.86      6790554.27      2738576.00      6790411.00

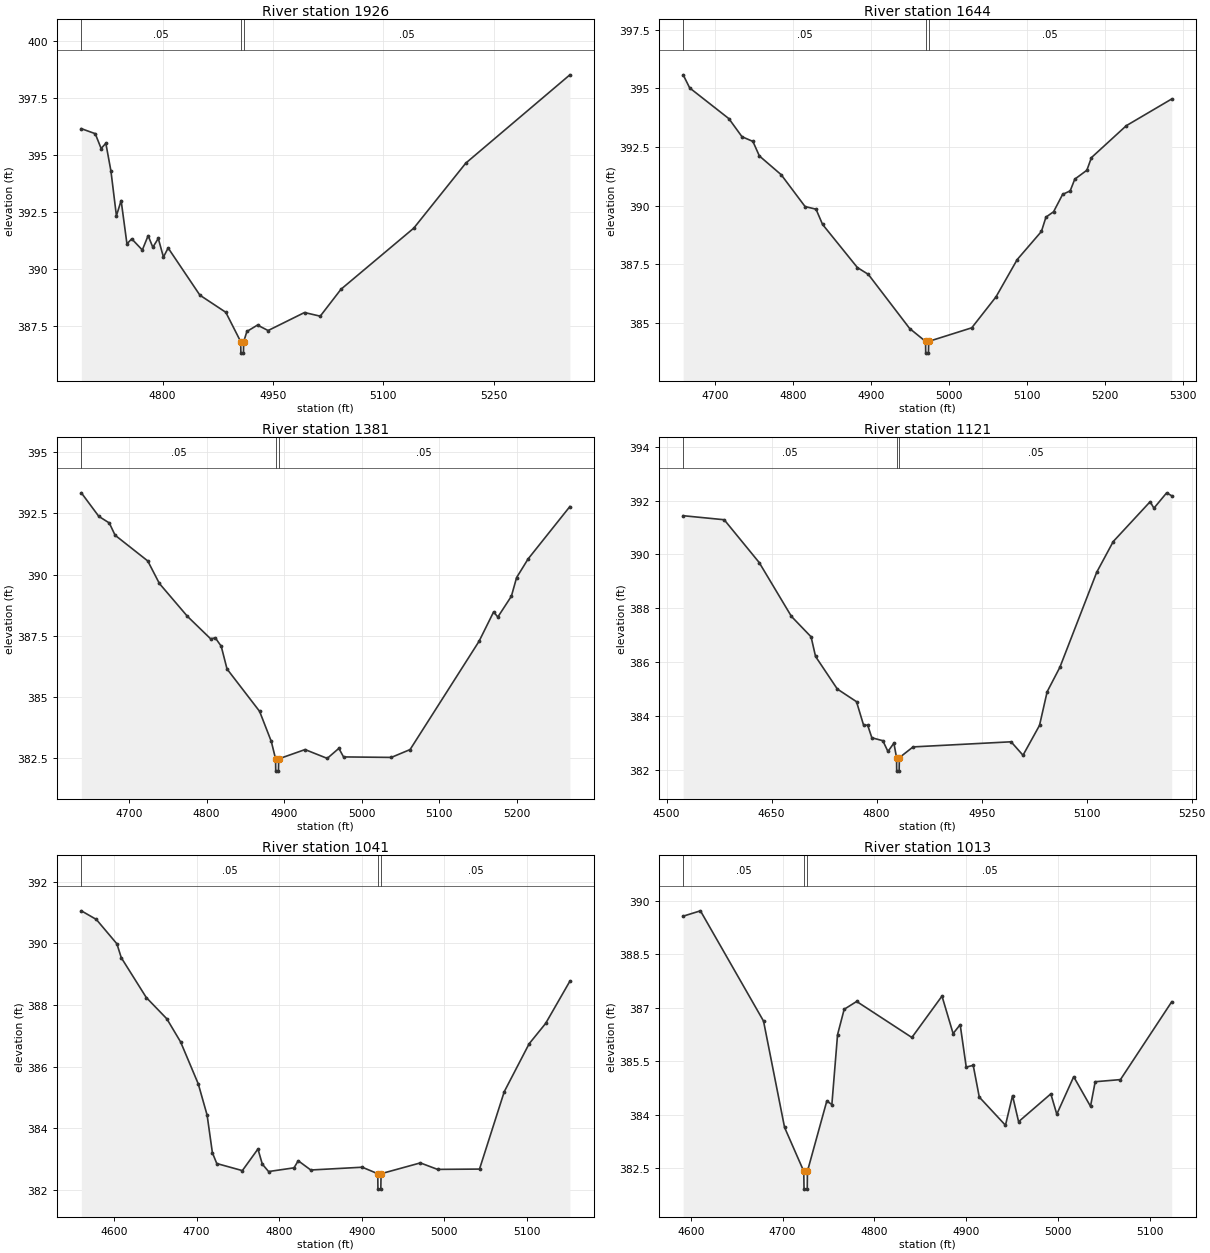
Type RM Length L Ch R = 1,1926,282,282,282
BEGIN DESCRIPTION:
Clear Creek T 22 7.0
END DESCRIPTION:
XS GIS Cut Line= 3
      2739667.23      6791665.33      2739426.00      6791861.00
      2739175.97      6792111.03
#Sta/Elev= 30
  4689.5  396.15  4708.4  395.93  4716.4  395.28  4722.8  395.51  4729.7  394.30
  4737.2  392.33  4743.6  393.00  4751.5  391.10  4758.0  391.32  4772.4  390.83
  4780.3  391.46  4786.7  390.95  4794.1  391.34  4801.1  390.52  4807.5  390.92
  4850.7  388.85  4885.9  388.10  4906.2  386.81  4906.4  386.31  4909.9  386.31
  4910.2  386.81  4914.6  387.26  4929.0  387.54  4943.4  387.30  4992.9  388.09
  5014.3  387.93  5042.5  389.11  5141.5  391.79  5212.2  394.64  5353.7  398.51
#Mann=3,-1,0
  4689.5    0.05       0  4906.2    0.04       0  4910.2    0.05       0
Bank Sta=4906.2,4910.2
Exp/Cntr=0.3,0.1

Type RM Length L Ch R = 1,1644,263,263,263
BEGIN DESCRIPTION:
Clear Creek T 22 6.0
END DESCRIPTION:
XS GIS Cut Line= 3
      2739626.01      6791460.99      2739326.00      6791611.00
      2739175.98      6791861.03
#Sta/Elev= 30
  4658.6  395.58  4667.0  395.02  4717.3  393.71  4734.1  392.94  4748.1  392.74
  4756.4  392.12  4784.4  391.32  4815.1  389.96  4829.1  389.85  4837.5  389.20
  4882.2  387.36  4896.2  387.07  4949.3  384.76  4969.7  384.21  4969.9  383.71
  4973.4  383.71  4973.7  384.21  5029.0  384.79  5060.1  386.11  5087.3  387.70
  5118.4  388.90  5124.2  389.51  5134.0  389.74  5145.6  390.48  5155.3  390.63
  5161.2  391.13  5176.7  391.51  5182.6  392.05  5227.3  393.41  5285.6  394.55
#Mann=3,-1,0
  4658.6    0.05       0  4969.7    0.04       0  4973.7    0.05       0
Bank Sta=4969.7,4973.7
Exp/Cntr=0.3,0.1

Type RM Length L Ch R = 1,1381,260,260,260
BEGIN DESCRIPTION:
Clear Creek T 22 5.0
END DESCRIPTION:
XS GIS Cut Line= 3
      2739475.98      6791261.01      2739176.00      6791461.00
      2738925.99      6791561.00
#Sta/Elev= 30
  4638.6  393.34  4661.1  392.38  4674.6  392.11  4682.1  391.61  4724.2  390.56
  4739.2  389.64  4775.3  388.30  4805.3  387.38  4811.3  387.42  4818.9  387.08
  4826.4  386.15  4868.4  384.42  4883.5  383.19  4889.0  382.48  4889.2  381.98
  4892.7  381.98  4893.0  382.48  4927.0  382.86  4955.6  382.50  4970.6  382.91
  4976.6  382.56  5038.2  382.54  5062.4  382.86  5151.3  387.28  5170.1  388.48
  5175.5  388.27  5193.0  389.12  5199.7  389.88  5214.5  390.64  5268.4  392.78
#Mann=3,-1,0
  4638.6    0.05       0  4889.0    0.04       0  4893.0    0.05       0
Bank Sta=4889,4893
Exp/Cntr=0.3,0.1

Type RM Length L Ch R = 1,1121,80,80,80
BEGIN DESCRIPTION:
Clear Creek T 22 4.0
END DESCRIPTION:
XS GIS Cut Line= 3
      2739390.51      6791076.27      2738976.00      6791311.00
      2738889.02      6791514.64
#Sta/Elev= 30
  4523.6  391.44  4582.2  391.29  4632.2  389.70  4678.2  387.70  4706.3  386.94
  4712.7  386.21  4743.8  385.00  4771.2  384.53  4781.4  383.65  4787.1  383.66
  4793.1  383.19  4808.8  383.08  4816.1  382.68  4824.6  382.99  4828.4  382.45
  4828.6  381.95  4832.1  381.95  4832.4  382.45  4852.0  382.85  4992.0  383.04
  5009.0  382.54  5032.6  383.65  5043.5  384.90  5061.7  385.81  5114.3  389.34
  5137.9  390.48  5190.6  391.96  5196.0  391.72  5214.2  392.29  5221.4  392.18
#Mann=3,-1,0
  4523.6    0.05       0  4828.4    0.04       0  4832.4    0.05       0
Bank Sta=4828.4,4832.4
Exp/Cntr=0.3,0.1

Type RM Length L Ch R = 1,1041,28,28,28
BEGIN DESCRIPTION:
Mapping XS ec70325a
END DESCRIPTION:
XS GIS Cut Line= 5
      2739318.65      6791089.86      2739101.49      6791171.31
      2739003.66      6791186.30      2738906.17      6791264.09
      2738902.94      6791400.43
#Sta/Elev= 30
  4560.3  391.05  4578.5  390.77  4603.4  389.98  4608.7  389.53  4639.0  388.24
  4663.9  387.55  4680.6  386.80  4702.0  385.44  4712.7  384.43  4719.1  383.21
  4724.4  382.86  4755.4  382.63  4774.3  383.33  4779.6  382.84  4787.2  382.60
  4818.0  382.72  4823.1  382.95  4838.3  382.65  4900.7  382.74  4919.5  382.53
  4919.7  382.03  4923.2  382.03  4923.5  382.53  4971.1  382.88  4991.9  382.67
  5042.8  382.68  5072.8  385.19  5102.9  386.74  5122.9  387.40  5152.3  388.77
#Mann=3,-1,0
  4560.3    0.05       0  4919.5    0.04       0  4923.5    0.05       0
Bank Sta=4919.5,4923.5
Exp/Cntr=0.3,0.1

Type RM Length L Ch R = 1,1013,23,23,23
BEGIN DESCRIPTION:
Mapping XS 8a1a2e3f
END DESCRIPTION:
XS GIS Cut Line= 6
      2739258.63      6791068.39      2739097.94      6791142.52
      2738997.74      6791148.80      2738898.71      6791234.47
      2738886.95      6791291.64      2738891.21      6791356.73
#Sta/Elev= 30
  4591.7  389.57  4610.5  389.72  4679.2  386.63  4702.1  383.65  4723.0  382.42
  4723.3  381.92  4726.8  381.92  4727.0  382.42  4748.1  384.39  4753.6  384.29
  4759.8  386.25  4767.0  386.96  4780.6  387.18  4840.7  386.17  4873.5  387.33
  4885.6  386.28  4893.3  386.53  4899.9  385.34  4907.5  385.39  4914.1  384.50
  4942.6  383.71  4950.3  384.54  4956.9  383.81  4992.0  384.59  4998.5  384.02
  5016.9  385.07  5035.2  384.24  5040.3  384.93  5067.8  384.99  5123.6  387.17
#Mann=3,-1,0
  4591.7    0.05       0  4723.0    0.04       0  4727.0    0.05       0
Bank Sta=4723,4727
Exp/Cntr=0.3,0.1

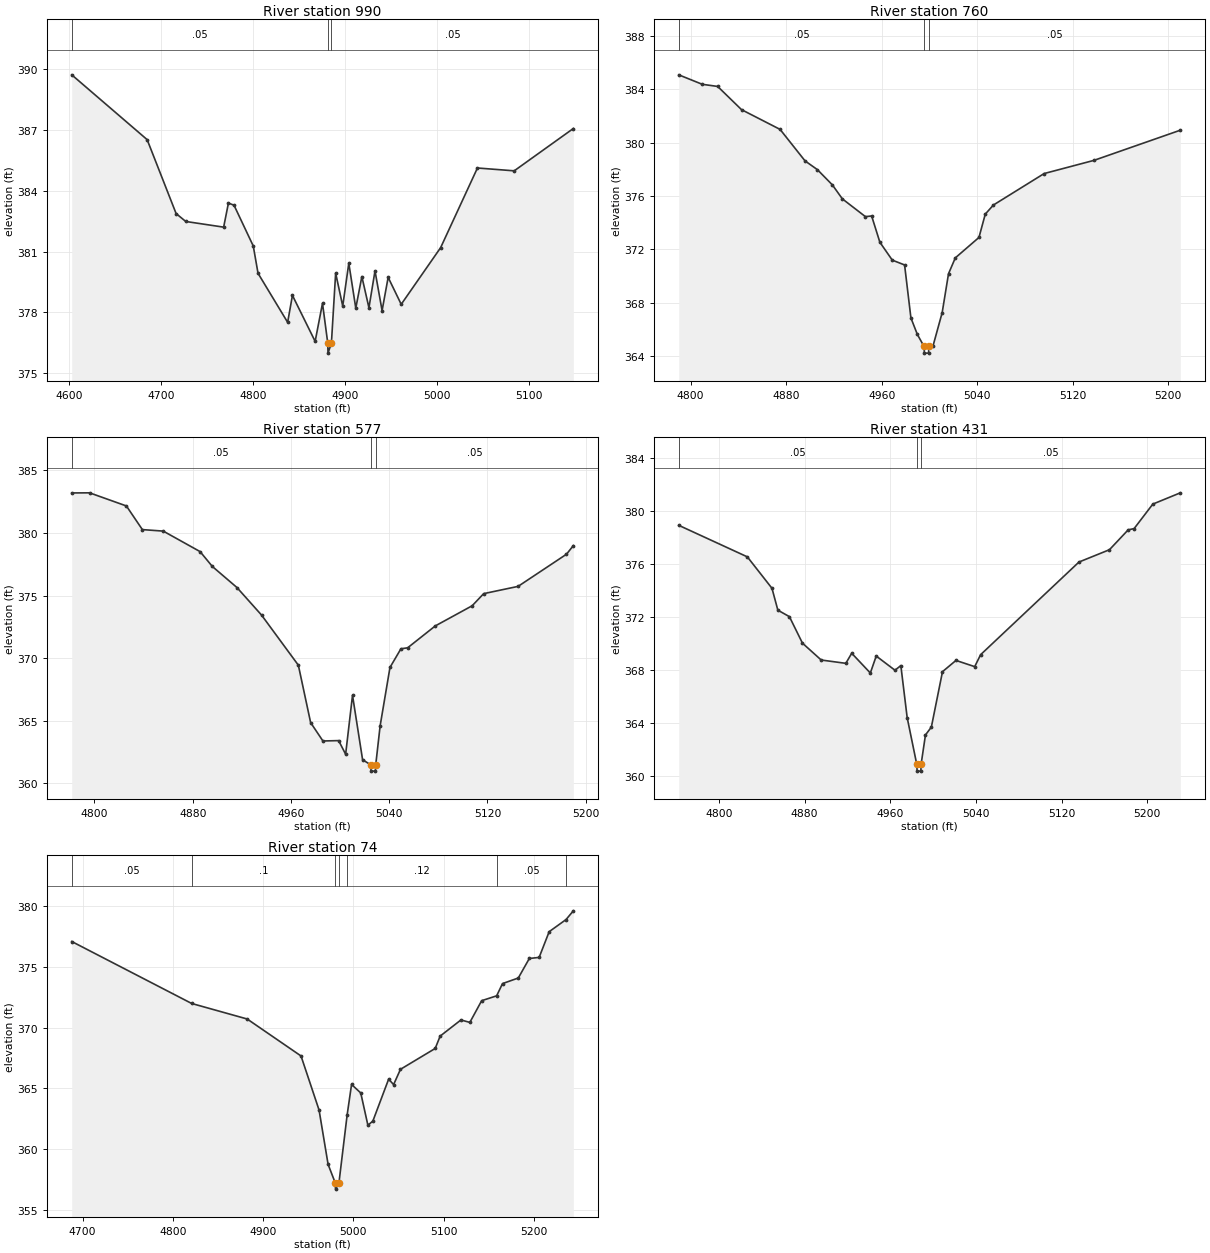
Type RM Length L Ch R = 1,990,230,230,230
BEGIN DESCRIPTION:
Mapping XS d8649c8c
END DESCRIPTION:
XS GIS Cut Line= 4
      2739224.09      6791044.32      2738972.01      6791124.94
      2738883.77      6791200.78      2738881.70      6791365.25
#Sta/Elev= 30
  4602.6  389.73  4684.6  386.53  4716.1  382.88  4726.6  382.49  4767.8  382.21
  4773.0  383.40  4779.1  383.29  4800.0  381.28  4805.2  379.93  4837.4  377.51
  4842.6  378.84  4867.3  376.57  4875.3  378.45  4881.0  376.49  4881.3  375.99
  4885.0  376.49  4889.6  379.94  4897.3  378.31  4903.9  380.43  4911.5  378.21
  4918.1  379.77  4925.8  378.23  4932.4  380.05  4940.1  378.09  4946.7  379.73
  4960.9  378.40  5003.8  381.20  5043.8  385.13  5083.8  384.99  5148.1  387.08
#Mann=3,-1,0
  4602.6    0.05       0  4881.0    0.04       0  4885.0    0.05       0
Bank Sta=4881,4885
Exp/Cntr=0.3,0.1

Type RM Length L Ch R = 1,760,183,183,183
BEGIN DESCRIPTION:
Clear Creek T 22 3.0
END DESCRIPTION:
XS GIS Cut Line= 4
      2739087.21      6790959.47      2738886.29      6791020.57
      2738844.12      6791138.29      2738854.95      6791222.75
#Sta/Elev= 30
  4790.0  385.09  4809.7  384.38  4822.6  384.22  4842.6  382.48  4874.9  381.00
  4895.8  378.64  4906.2  377.98  4918.7  376.84  4927.1  375.79  4946.4  374.46
  4951.6  374.51  4958.5  372.54  4968.9  371.20  4979.2  370.84  4984.5  366.87
  4989.9  365.63  4995.5  364.73  4995.8  364.23  4999.3  364.23  4999.5  364.73
  5002.9  364.73  5010.7  367.27  5016.0  370.18  5021.7  371.37  5041.5  372.90
  5046.8  374.65  5053.6  375.33  5096.1  377.69  5137.9  378.68  5210.2  380.94
#Mann=3,-1,0
  4790.0    0.05       0  4995.5    0.04       0  4999.5    0.05       0
Bank Sta=4995.5,4999.5
Exp/Cntr=0.3,0.1

Type RM Length L Ch R = 1,577,146,146,146
BEGIN DESCRIPTION:
Clear Creek T 22 2.0
END DESCRIPTION:
XS GIS Cut Line= 3
      2739040.44      6790867.75      2738826.00      6790861.00
      2738652.02      6790946.50
#Sta/Elev= 30
  4781.5  383.20  4796.0  383.21  4826.0  382.16  4839.0  380.27  4856.0  380.15
  4886.0  378.51  4896.0  377.32  4916.0  375.64  4936.0  373.44  4966.0  369.43
  4976.0  364.84  4986.0  363.37  4998.8  363.40  5004.5  362.31  5010.1  367.02
  5018.3  361.87  5025.0  361.46  5025.2  360.96  5028.7  360.96  5029.0  361.46
  5032.6  364.59  5040.6  369.25  5049.5  370.74  5055.0  370.82  5077.5  372.57
  5107.5  374.18  5116.9  375.15  5144.9  375.73  5184.3  378.30  5189.9  378.99
#Mann=3,-1,0
  4781.5    0.05       0  5025.0    0.04       0  5029.0    0.05       0
Bank Sta=5025,5029
Exp/Cntr=0.3,0.1

Type RM Length L Ch R = 1,431,357,357,357
BEGIN DESCRIPTION:
Mapping XS 39e2b4f0
END DESCRIPTION:
XS GIS Cut Line= 2
      2738969.95      6790639.56      2738544.10      6790835.12
#Sta/Elev= 30
  4762.4  378.94  4826.5  376.56  4849.5  374.19  4855.0  372.54  4865.8  372.05
  4878.0  370.05  4895.5  368.78  4918.5  368.53  4924.0  369.29  4941.4  367.80
  4946.9  369.08  4964.4  368.01  4969.9  368.36  4975.8  364.44  4984.8  360.90
  4985.1  360.40  4988.6  360.40  4988.8  360.90  4992.9  363.13  4998.4  363.72
  5008.8  367.90  5021.4  368.75  5038.9  368.28  5044.4  369.18  5136.3  376.17
  5164.8  377.10  5182.3  378.60  5187.8  378.69  5205.3  380.54  5231.0  381.39
#Mann=3,-1,0
  4762.4    0.05       0  4984.8    0.04       0  4988.8    0.05       0
Bank Sta=4984.8,4988.8
Exp/Cntr=0.3,0.1

Type RM Length L Ch R = 1,74,0,0,0
BEGIN DESCRIPTION:
Clear Creek T 22 1.0
END DESCRIPTION:
XS GIS Cut Line= 3
      2738940.03      6790471.29      2738629.08      6790462.61
      2738527.46      6790685.36
#Sta/Elev= 30
  4687.9  377.10  4820.8  371.99  4882.3  370.71  4942.0  367.66  4962.0  363.20
  4972.0  358.72  4980.0  357.18  4980.3  356.68  4984.0  357.18  4993.1  362.79
  4998.0  365.31  5008.2  364.61  5016.1  361.95  5021.6  362.29  5039.1  365.75
  5044.6  365.30  5052.2  366.56  5090.7  368.28  5096.2  369.30  5119.2  370.63
  5129.1  370.43  5142.2  372.22  5158.8  372.62  5165.3  373.63  5182.8  374.09
  5195.0  375.70  5205.9  375.79  5217.0  377.91  5235.7  378.91  5243.8  379.63
#Mann=7,-1,0
  4687.9    0.05       0  4820.8     0.1       0  4980.0    0.07       0
  4984.0     0.1       0  4993.1    0.12       0  5158.8    0.05       0
  5235.7     0.1       0
Bank Sta=4980,4984
Exp/Cntr=0.3,0.1

Chan Stop Cuts=-1