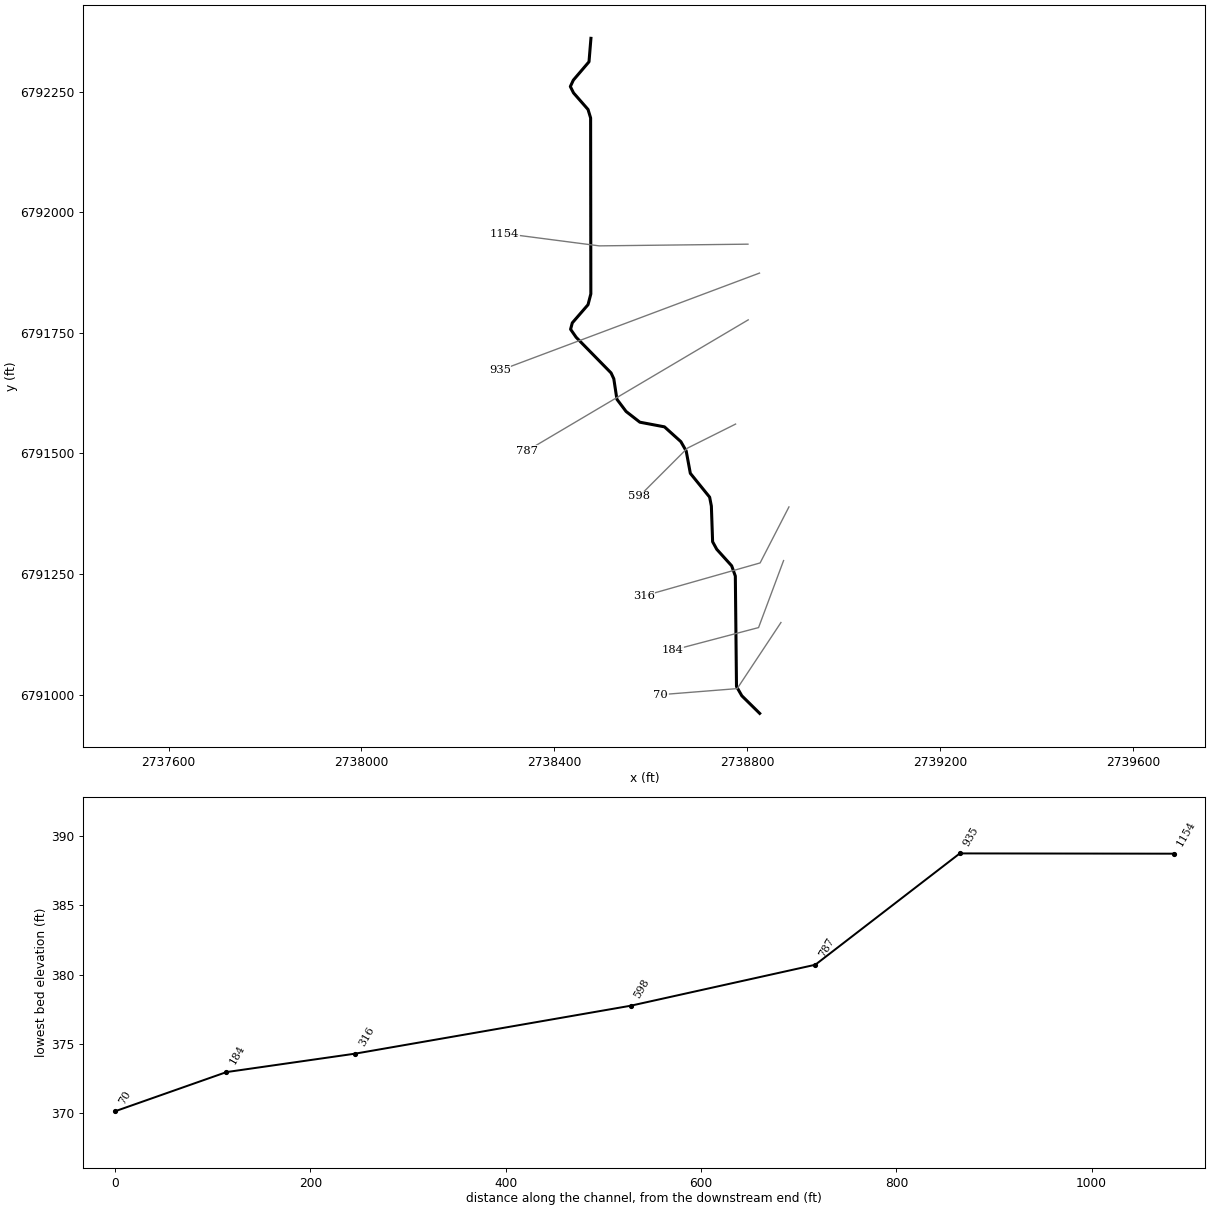
--- Clear Creek T 23.prj (project) ---

Proj Title=Clear Creek T 23 Base Level Engineering
Current Plan=p01
Default Exp/Contr=0.3,0.1
English Units
Geom File=g01
Flow File=f01
Plan File=p01
BEGIN DESCRIPTION:
Clear Creek T 23
END DESCRIPTION:

--- Clear Creek T 23.p01 (plan) ---

Plan Title=Multiple Run
Short Identifier=Multiple
Geom File=g01
Flow File=f01
Subcritical Flow
K Sum by GR= 0
Std Step Tol= 0.01
Critical Tol= 0.01
Num of Std Step Trials= 20
Max Error Tol= 0.3
Flow Tol Ratio= 0.001
Split Flow NTrial= 30
Split Flow Tol= 0.02
Split Flow Ratio= 0.02
Log Output Level= 0
Friction Slope Method= 1
Unsteady Friction Slope Method= 2
Unsteady Bridges Friction Slope Method= 1
Parabolic Critical Depth
Global Vel Dist=  1 , 1 , 1
Global Log Level= 0
CheckData=True
Encroach Param= -1, 0, 0, 0
BEGIN DESCRIPTION:
Multiple Run
END DESCRIPTION:

--- Clear Creek T 23.f01 (steady flow) ---

Flow Title=Multiple
Number of Profiles=7
Profile Names=10-year,25-year,50-year,1pct_min,100-year,1pct_plu,500-year
River Rch & RM= Clear Creek T 23,Reach-1,1154
      56      63      68      36      73     145      83
Boundary for River Rch & Prof#=Clear Creek T 23,Reach-1,1
Up Type=0
Dn Type=3
Dn Slope=0.005
Boundary for River Rch & Prof#=Clear Creek T 23,Reach-1,2
Up Type=0
Dn Type=3
Dn Slope=0.005
Boundary for River Rch & Prof#=Clear Creek T 23,Reach-1,3
Up Type=0
Dn Type=3
Dn Slope=0.005
Boundary for River Rch & Prof#=Clear Creek T 23,Reach-1,4
Up Type=0
Dn Type=3
Dn Slope=0.005
Boundary for River Rch & Prof#=Clear Creek T 23,Reach-1,5
Up Type=0
Dn Type=3
Dn Slope=0.005
Boundary for River Rch & Prof#=Clear Creek T 23,Reach-1,6
Up Type=0
Dn Type=3
Dn Slope=0.005
Boundary for River Rch & Prof#=Clear Creek T 23,Reach-1,7
Up Type=0
Dn Type=3
Dn Slope=0.005

--- Clear Creek T 23.g01 (geometry) ---

Geom Title=Existing Conditions

River Reach=Clear Creek T 23,Reach-1
Reach XY= 30
      2738476.00      6792361.00      2738472.00      6792312.36
      2738439.48      6792274.28      2738433.31      6792261.04
      2738439.91      6792247.82      2738470.00      6792213.45
      2738475.35      6792195.84      2738475.81      6791830.98
      2738469.97      6791808.55      2738437.33      6791770.85
      2738433.81      6791757.59      2738445.33      6791740.98
      2738517.80      6791667.03      2738523.43      6791654.91
      2738529.89      6791612.43      2738548.87      6791587.17
      2738577.46      6791564.90      2738628.51      6791555.24
      2738662.52      6791524.56      2738673.58      6791505.15
      2738682.15      6791458.85      2738722.18      6791409.42
      2738725.77      6791390.91      2738728.36      6791316.98
      2738736.89      6791301.37      2738767.86      6791267.06
      2738775.48      6791245.78      2738777.89      6791016.78
      2738788.92      6790997.49      2738826.00      6790961.00

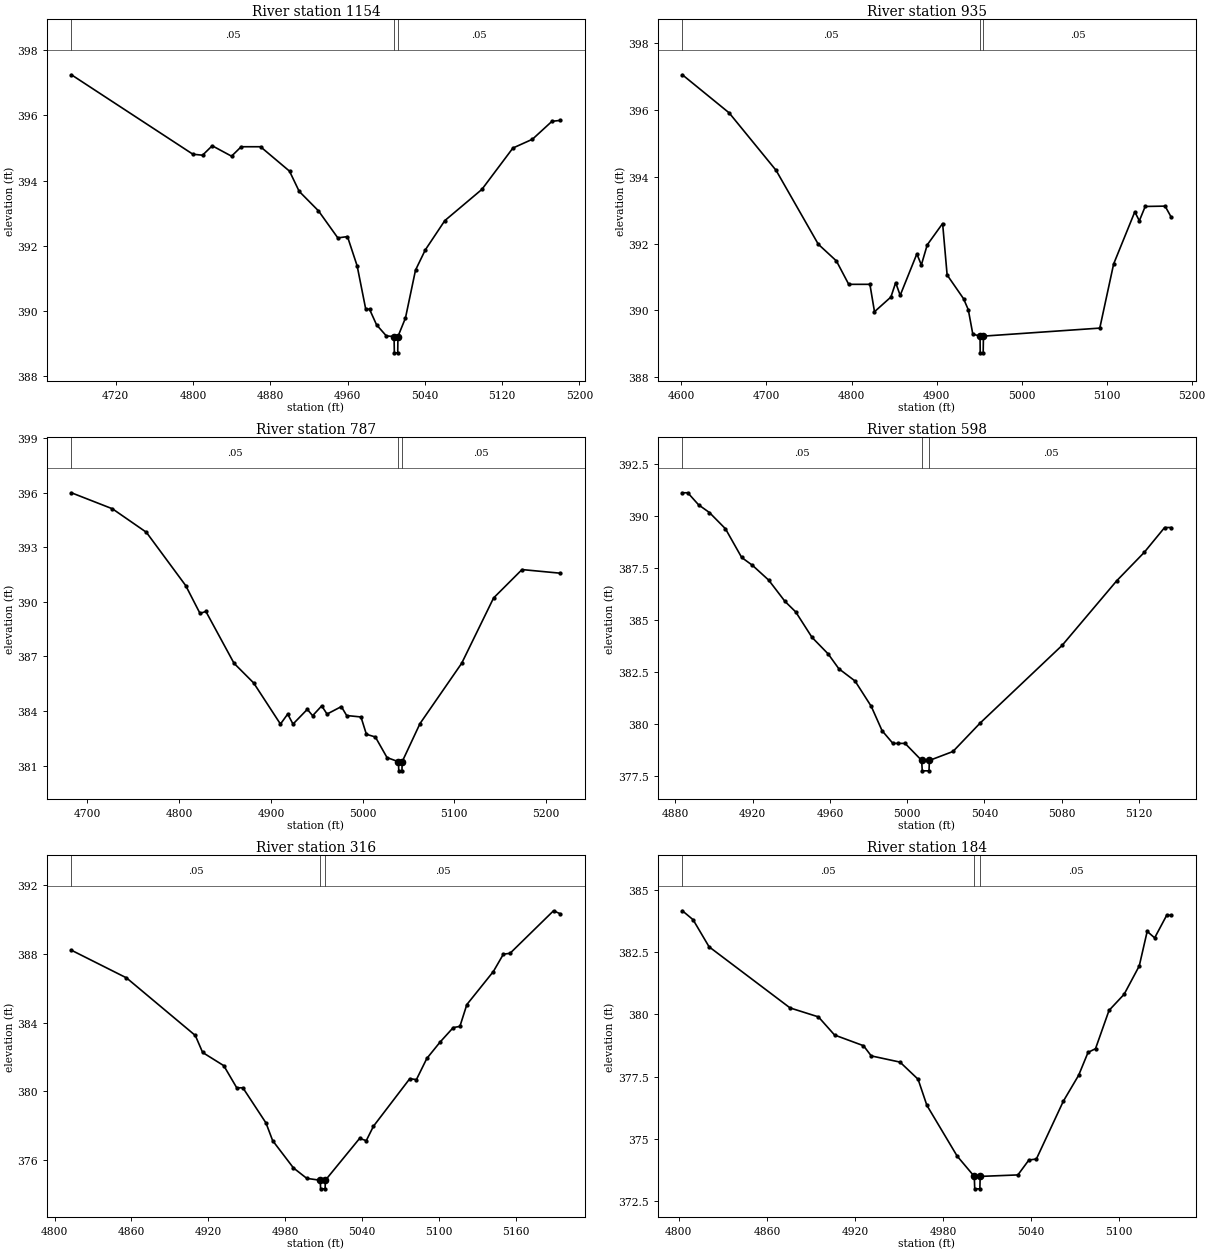
Type RM Length L Ch R = 1,1154,219,219,219
BEGIN DESCRIPTION:
2499
END DESCRIPTION:
XS GIS Cut Line= 3
      2738801.68      6791934.11      2738493.21      6791930.58
      2738297.26      6791956.09
#Sta/Elev= 30
  4674.2  397.25  4799.9  394.81  4809.9  394.78  4819.9  395.07  4839.9  394.75
  4849.9  395.04  4869.9  395.04  4899.9  394.29  4909.9  393.67  4929.9  393.07
  4949.9  392.24  4959.9  392.28  4969.9  391.38  4978.8  390.05  4982.7  390.05
  4990.0  389.57  5000.1  389.23  5008.1  389.21  5008.4  388.71  5011.9  388.71
  5012.1  389.21  5019.9  389.78  5030.3  391.25  5040.4  391.87  5060.6  392.77
  5099.0  393.73  5131.1  395.00  5151.3  395.27  5171.5  395.82  5180.3  395.85
#Mann=3,-1,0
  4674.2    0.05       0  5008.1    0.04       0  5012.1    0.05       0
Bank Sta=5008.1,5012.1
Exp/Cntr=0.3,0.1

Type RM Length L Ch R = 1,935,148,148,148
BEGIN DESCRIPTION:
2498
END DESCRIPTION:
XS GIS Cut Line= 2
      2738825.58      6791874.15      2738287.20      6791672.22
#Sta/Elev= 30
  4601.1  397.05  4656.1  395.91  4711.3  394.19  4760.9  391.98  4782.2  391.48
  4796.7  390.78  4821.6  390.78  4827.0  389.96  4846.3  390.40  4851.9  390.83
  4857.2  390.45  4876.8  391.69  4882.1  391.36  4889.0  391.96  4907.1  392.60
  4912.4  391.06  4931.7  390.35  4937.3  390.02  4942.6  389.29  4951.1  389.23
  4951.3  388.73  4954.8  388.73  4955.1  389.23  5091.9  389.47  5108.2  391.39
  5133.1  392.95  5138.4  392.68  5145.3  393.11  5168.7  393.12  5176.1  392.78
#Mann=3,-1,0
  4601.1    0.05       0  4951.1    0.04       0  4955.1    0.05       0
Bank Sta=4951.1,4955.1
Exp/Cntr=0.3,0.1

Type RM Length L Ch R = 1,787,189,189,189
BEGIN DESCRIPTION:
2497
END DESCRIPTION:
XS GIS Cut Line= 2
      2738802.17      6791777.12      2738343.28      6791505.60
#Sta/Elev= 30
  4682.5  395.99  4727.2  395.11  4764.2  393.82  4807.1  390.89  4822.7  389.36
  4829.1  389.47  4859.8  386.62  4881.2  385.54  4910.4  383.28  4918.3  383.83
  4924.1  383.28  4939.7  384.09  4945.5  383.74  4955.4  384.28  4961.2  383.83
  4976.8  384.24  4982.6  383.75  4998.2  383.67  5004.1  382.72  5013.9  382.57
  5026.6  381.44  5039.1  381.21  5039.4  380.71  5042.9  380.71  5043.1  381.21
  5062.6  383.31  5108.0  386.62  5142.8  390.21  5173.8  391.77  5215.7  391.57
#Mann=3,-1,0
  4682.5    0.05       0  5039.1    0.04       0  5043.1    0.05       0
Bank Sta=5039.1,5043.1
Exp/Cntr=0.3,0.1

Type RM Length L Ch R = 1,598,282,282,282
BEGIN DESCRIPTION:
2242
END DESCRIPTION:
XS GIS Cut Line= 3
      2738775.99      6791560.99      2738676.00      6791511.00
      2738576.01      6791411.01
#Sta/Elev= 30
  4883.6  391.13  4886.4  391.13  4892.0  390.55  4897.6  390.18  4905.9  389.40
  4914.3  388.02  4919.9  387.64  4928.3  386.93  4936.7  385.91  4942.3  385.40
  4950.7  384.18  4959.1  383.38  4964.6  382.67  4973.0  382.08  4981.4  380.86
  4987.0  379.69  4992.6  379.08  4995.4  379.08  4998.9  379.08  5007.5  378.26
  5007.8  377.76  5011.3  377.76  5011.5  378.26  5023.7  378.69  5037.8  380.06
  5080.2  383.79  5108.5  386.90  5122.7  388.26  5133.3  389.46  5136.8  389.46
#Mann=3,-1,0
  4883.6    0.05       0  5007.5    0.04       0  5011.5    0.05       0
Bank Sta=5007.5,5011.5
Exp/Cntr=0.3,0.1

Type RM Length L Ch R = 1,316,132,132,132
BEGIN DESCRIPTION:
2366
END DESCRIPTION:
XS GIS Cut Line= 3
      2738886.65      6791389.17      2738826.88      6791273.03
      2738585.74      6791204.53
#Sta/Elev= 30
  4813.2  388.22  4856.1  386.61  4909.8  383.25  4915.5  382.26  4932.0  381.49
  4942.1  380.20  4946.9  380.20  4964.9  378.15  4970.1  377.12  4986.3  375.53
  4996.7  374.92  5007.2  374.81  5007.5  374.31  5011.0  374.31  5011.2  374.81
  5037.9  377.25  5043.1  377.12  5048.7  377.96  5077.0  380.73  5082.2  380.68
  5090.3  381.91  5100.7  382.87  5110.9  383.71  5116.1  383.78  5121.5  385.05
  5142.2  386.98  5150.0  387.99  5155.2  388.04  5189.1  390.52  5194.5  390.34
#Mann=3,-1,0
  4813.2    0.05       0  5007.2    0.04       0  5011.2    0.05       0
Bank Sta=5007.2,5011.2
Exp/Cntr=0.3,0.1

Type RM Length L Ch R = 1,184,114,114,114
BEGIN DESCRIPTION:
2476
END DESCRIPTION:
XS GIS Cut Line= 3
      2738875.53      6791277.88      2738823.65      6791138.94
      2738644.86      6791091.83
#Sta/Elev= 30
  4802.4  384.17  4809.7  383.81  4820.6  382.72  4875.8  380.26  4895.1  379.90
  4906.1  379.17  4925.8  378.74  4931.1  378.33  4950.7  378.08  4963.0  377.39
  4969.0  376.34  4989.6  374.30  5001.3  373.48  5001.6  372.98  5005.1  372.98
  5005.3  373.48  5031.0  373.54  5038.5  374.14  5043.6  374.18  5062.0  376.51
  5072.4  377.55  5078.8  378.47  5083.9  378.62  5093.1  380.16  5103.4  380.81
  5113.7  381.95  5119.1  383.34  5124.2  383.08  5132.4  383.99  5135.6  383.99
#Mann=3,-1,0
  4802.4    0.05       0  5001.3    0.04       0  5005.3    0.05       0
Bank Sta=5001.3,5005.3
Exp/Cntr=0.3,0.1

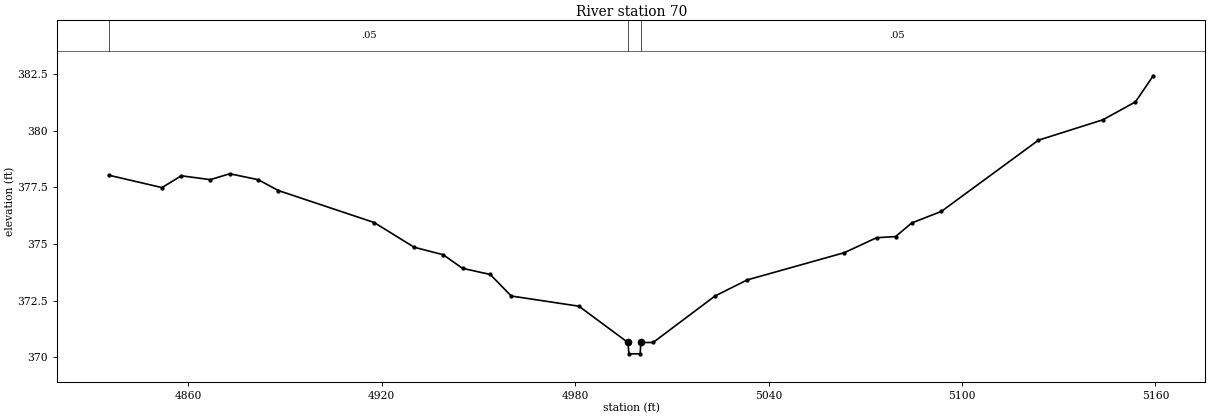
Type RM Length L Ch R = 1,70,0,0,0
BEGIN DESCRIPTION:
2241
END DESCRIPTION:
XS GIS Cut Line= 3
      2738870.07      6791149.42      2738779.29      6791012.36
      2738620.49      6790999.73
#Sta/Elev= 30
  4835.6  378.03  4851.9  377.49  4857.9  378.01  4866.9  377.84  4872.9  378.10
  4881.7  377.84  4888.0  377.36  4917.7  375.95  4930.1  374.86  4939.1  374.53
  4945.1  373.93  4953.7  373.66  4960.2  372.71  4981.2  372.26  4996.4  370.66
  4996.7  370.16  5000.2  370.16  5000.4  370.66  5004.2  370.66  5023.4  372.71
  5033.4  373.42  5063.5  374.62  5073.5  375.28  5079.4  375.33  5084.4  375.93
  5093.6  376.44  5123.7  379.58  5143.7  380.48  5153.8  381.27  5159.3  382.42
#Mann=3,-1,0
  4835.6    0.05       0  4996.4    0.04       0  5000.4    0.05       0
Bank Sta=4996.4,5000.4
Exp/Cntr=0.3,0.1

Chan Stop Cuts=-1