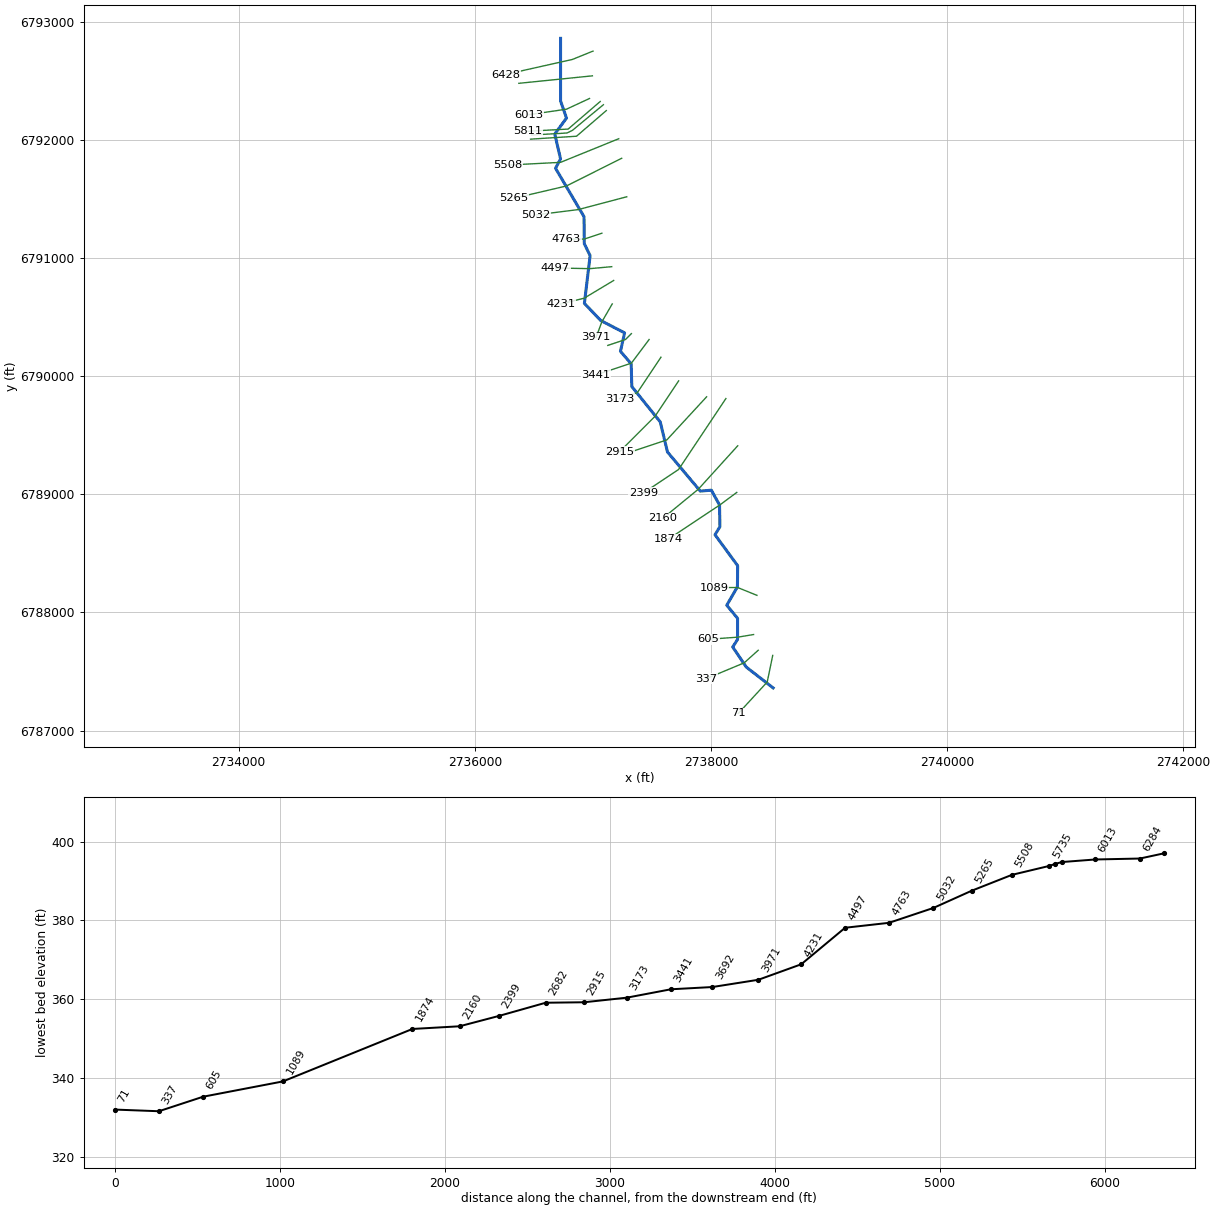
--- Clear Creek T 24.prj (project) ---

Proj Title=Clear Creek T 24 Base Level Engineering
Current Plan=p01
Default Exp/Contr=0.3,0.1
English Units
Geom File=g01
Flow File=f01
Plan File=p01
BEGIN DESCRIPTION:
Clear Creek T 24
END DESCRIPTION:

--- Clear Creek T 24.p01 (plan) ---

Plan Title=Multiple Run
Short Identifier=Multiple
Geom File=g01
Flow File=f01
Subcritical Flow
K Sum by GR= 0
Std Step Tol= 0.01
Critical Tol= 0.01
Num of Std Step Trials= 20
Max Error Tol= 0.3
Flow Tol Ratio= 0.001
Split Flow NTrial= 30
Split Flow Tol= 0.02
Split Flow Ratio= 0.02
Log Output Level= 0
Friction Slope Method= 1
Unsteady Friction Slope Method= 2
Unsteady Bridges Friction Slope Method= 1
Parabolic Critical Depth
Global Vel Dist=  1 , 1 , 1
Global Log Level= 0
CheckData=True
Encroach Param= -1, 0, 0, 0
BEGIN DESCRIPTION:
Multiple Run
END DESCRIPTION:

--- Clear Creek T 24.f01 (steady flow) ---

Flow Title=Multiple
Number of Profiles=7
Profile Names=10-year,25-year,50-year,1pct_min,100-year,1pct_plu,500-year
River Rch & RM= Clear Creek T 24,Reach-1,6428
     155     190     215     122     243     484     308
River Rch & RM= Clear Creek T 24,Reach-1,3971
     328     424     498     292     582    1161     792
Boundary for River Rch & Prof#=Clear Creek T 24,Reach-1,1
Up Type=0
Dn Type=3
Dn Slope=0.005
Boundary for River Rch & Prof#=Clear Creek T 24,Reach-1,2
Up Type=0
Dn Type=3
Dn Slope=0.005
Boundary for River Rch & Prof#=Clear Creek T 24,Reach-1,3
Up Type=0
Dn Type=3
Dn Slope=0.005
Boundary for River Rch & Prof#=Clear Creek T 24,Reach-1,4
Up Type=0
Dn Type=3
Dn Slope=0.005
Boundary for River Rch & Prof#=Clear Creek T 24,Reach-1,5
Up Type=0
Dn Type=3
Dn Slope=0.005
Boundary for River Rch & Prof#=Clear Creek T 24,Reach-1,6
Up Type=0
Dn Type=3
Dn Slope=0.005
Boundary for River Rch & Prof#=Clear Creek T 24,Reach-1,7
Up Type=0
Dn Type=3
Dn Slope=0.005

--- Clear Creek T 24.g01 (geometry) ---

Geom Title=Existing Conditions

River Reach=Clear Creek T 24,Reach-1
Reach XY= 30
      2736726.00      6792861.00      2736726.07      6792331.03
      2736776.49      6792185.96      2736677.04      6792050.56
      2736726.21      6791840.79      2736683.56      6791761.00
      2736924.95      6791350.56      2736927.22      6791121.50
      2736976.45      6791021.19      2736927.96      6790616.89
      2737066.32      6790471.76      2737268.36      6790367.46
      2737233.33      6790210.90      2737323.92      6790105.15
      2737329.55      6789912.47      2737570.17      6789613.30
      2737631.48      6789358.56      2737909.34      6789027.39
      2738002.99      6789035.36      2738072.25      6788909.45
      2738075.34      6788726.16      2738034.04      6788657.68
      2738225.62      6788395.84      2738223.76      6788216.93
      2738133.30      6788060.92      2738224.94      6787950.57
      2738224.61      6787771.43      2738183.81      6787707.59
      2738298.86      6787537.16      2738526.00      6787361.00

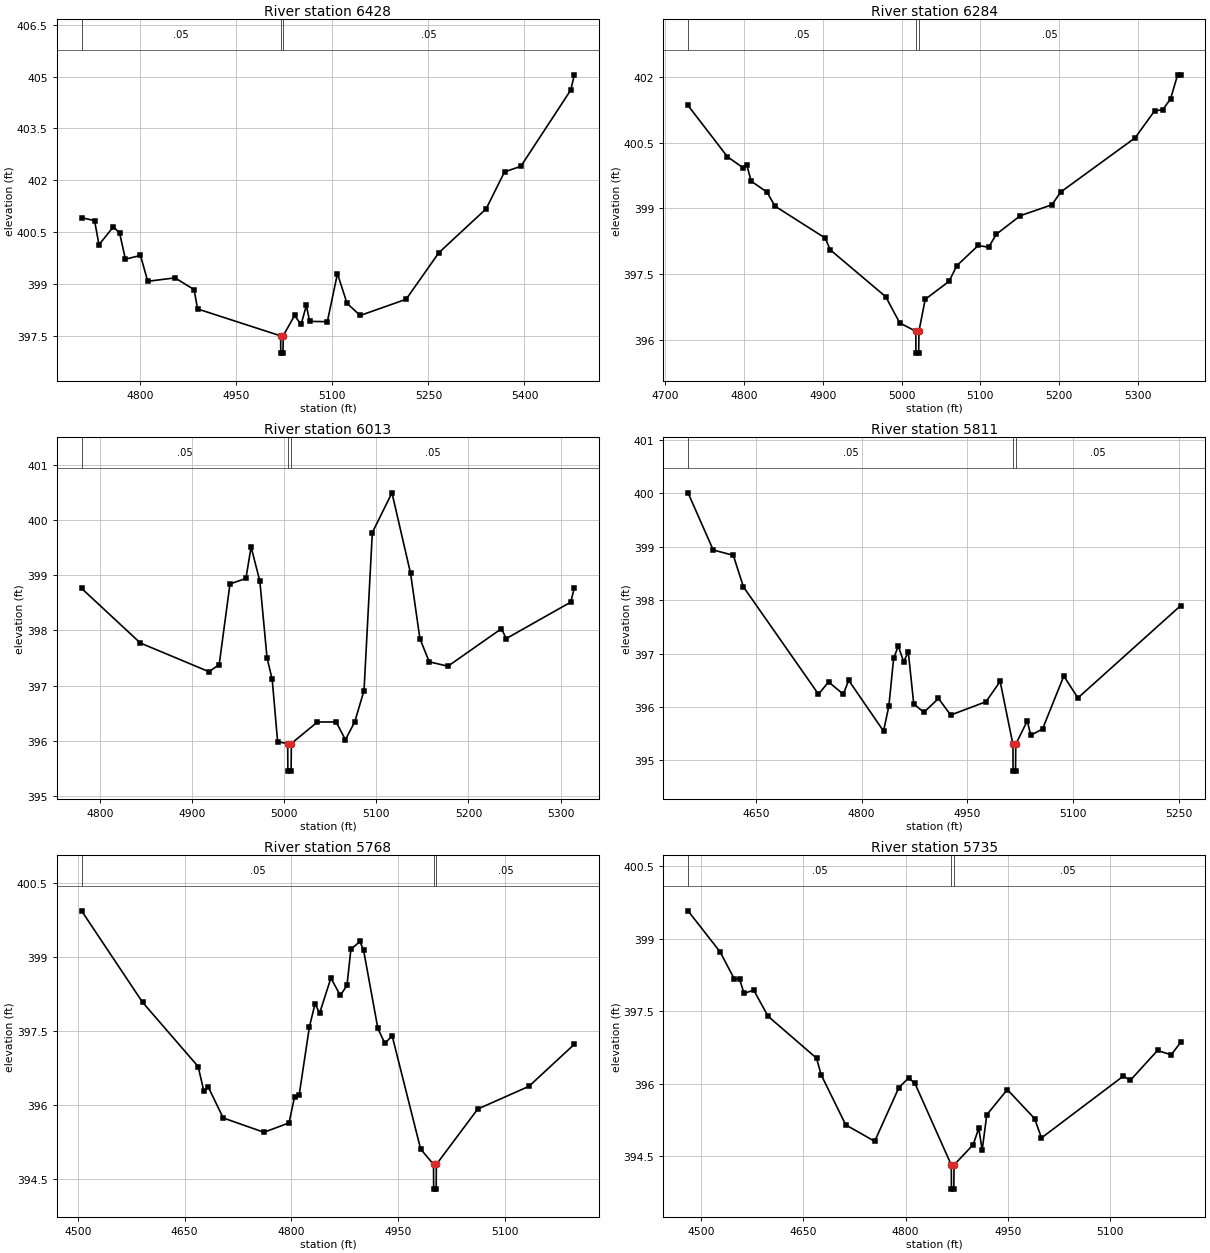
Type RM Length L Ch R = 1,6428,144,144,144
BEGIN DESCRIPTION:
2494
END DESCRIPTION:
XS GIS Cut Line= 4
      2737001.18      6792753.09      2736826.16      6792682.14
      2736341.27      6792573.52      2736260.14      6792553.59
#Sta/Elev= 30
  4708.5  400.91  4728.8  400.83  4735.7  400.13  4758.3  400.65  4768.0  400.46
  4777.0  399.71  4800.4  399.82  4811.9  399.07  4854.4  399.17  4884.2  398.83
  4889.6  398.27  5019.3  397.49  5019.5  396.99  5023.0  396.99  5023.3  397.49
  5041.0  398.08  5051.2  397.82  5059.5  398.37  5064.6  397.91  5092.2  397.90
  5108.0  399.29  5123.0  398.43  5143.5  398.08  5215.2  398.55  5266.4  399.90
  5340.2  401.17  5368.9  402.24  5394.3  402.40  5472.3  404.61  5477.8  405.05
#Mann=3,-1,0
  4708.5    0.05       0  5019.3    0.05       0  5023.3    0.05       0
Bank Sta=5019.3,5023.3
Exp/Cntr=0.3,0.1

Type RM Length L Ch R = 1,6284,271,271,271
BEGIN DESCRIPTION:
2493
END DESCRIPTION:
XS GIS Cut Line= 2
      2736995.79      6792543.47      2736373.10      6792480.16
#Sta/Elev= 30
  4728.8  401.35  4778.8  400.18  4798.3  399.93  4803.3  400.00  4809.0  399.62
  4829.1  399.37  4839.2  399.05  4903.0  398.32  4909.5  398.05  4979.9  396.98
  4997.7  396.38  5018.1  396.19  5018.3  395.69  5021.8  395.69  5022.1  396.19
  5030.1  396.92  5060.3  397.33  5070.3  397.69  5097.4  398.15  5110.6  398.11
  5120.6  398.41  5150.8  398.83  5191.0  399.08  5202.1  399.37  5296.7  400.61
  5321.6  401.23  5331.7  401.25  5341.7  401.50  5350.7  402.05  5354.7  402.05
#Mann=3,-1,0
  4728.8    0.05       0  5018.1   0.035       0  5022.1    0.05       0
Bank Sta=5018.1,5022.1
Exp/Cntr=0.3,0.1

Type RM Length L Ch R = 1,6013,202,202,202
BEGIN DESCRIPTION:
1976
END DESCRIPTION:
XS GIS Cut Line= 3
      2736971.43      6792351.71      2736776.00      6792261.00
      2736460.29      6792214.98
#Sta/Elev= 30
  4780.3  398.76  4844.1  397.77  4918.6  397.25  4929.6  397.38  4941.3  398.84
  4958.6  398.94  4964.2  399.51  4973.7  398.89  4981.5  397.50  4987.1  397.11
  4993.0  395.98  5003.9  395.95  5004.1  395.45  5007.6  395.45  5007.9  395.95
  5036.2  396.34  5056.4  396.34  5066.5  396.02  5076.6  396.34  5086.7  396.91
  5095.7  399.77  5117.0  400.49  5137.2  399.03  5147.3  397.85  5157.4  397.43
  5177.7  397.35  5235.8  398.03  5240.9  397.85  5310.9  398.51  5314.8  398.77
#Mann=3,-1,0
  4780.3    0.05       0  5003.9   0.035       0  5007.9    0.05       0
Bank Sta=5003.9,5007.9
Exp/Cntr=0.3,0.1

Type RM Length L Ch R = 1,5811,43,43,43
BEGIN DESCRIPTION:
2363
END DESCRIPTION:
XS GIS Cut Line= 3
      2737061.76      6792326.13      2736790.66      6792092.84
      2736450.42      6792074.41
#Sta/Elev= 30
  4554.0  400.01  4589.7  398.94  4618.2  398.84  4632.5  398.25  4738.9  396.24
  4753.2  396.47  4774.1  396.24  4781.7  396.50  4831.1  395.55  4838.7  396.02
  4845.4  396.91  4852.0  397.14  4859.6  396.85  4866.2  397.03  4873.9  396.06
  4888.2  395.90  4909.0  396.16  4926.3  395.85  4976.4  396.10  4996.4  396.48
  5014.5  395.30  5014.7  394.80  5018.2  394.80  5018.5  395.30  5034.8  395.74
  5039.8  395.47  5056.5  395.59  5086.6  396.58  5106.6  396.17  5252.4  397.90
#Mann=3,-1,0
  4554.0    0.05       0  5014.5   0.035       0  5018.5    0.05       0
Bank Sta=5014.5,5018.5
Exp/Cntr=0.3,0.1

Type RM Length L Ch R = 1,5768,33,33,33
BEGIN DESCRIPTION:
2361
END DESCRIPTION:
XS GIS Cut Line= 5
      2737088.89      6792299.07      2736826.24      6792081.55
      2736781.15      6792059.71      2736741.49      6792057.04
      2736480.49      6792042.22
#Sta/Elev= 30
  4505.2  399.93  4590.9  398.08  4669.0  396.78  4676.9  396.29  4683.4  396.36
  4704.2  395.74  4761.5  395.45  4796.7  395.64  4804.5  396.17  4811.0  396.21
  4825.3  397.58  4833.2  398.05  4839.7  397.86  4855.5  398.57  4868.7  398.22
  4878.1  398.42  4883.6  399.15  4896.3  399.31  4901.5  399.13  4921.5  397.55
  4931.3  397.25  4941.6  397.40  4981.6  395.11  4999.7  394.80  4999.9  394.30
  5003.4  394.30  5003.7  394.80  5061.8  395.92  5133.8  396.38  5197.5  397.23
#Mann=3,-1,0
  4505.2    0.05       0  4999.7   0.035       0  5003.7    0.05       0
Bank Sta=4999.7,5003.7
Exp/Cntr=0.3,0.1

Type RM Length L Ch R = 1,5735,227,227,227
BEGIN DESCRIPTION:
2362
END DESCRIPTION:
XS GIS Cut Line= 3
      2737113.55      6792249.39      2736861.25      6792032.16
      2736471.97      6792007.36
#Sta/Elev= 30
  4480.9  399.58  4528.0  398.73  4548.8  398.17  4556.5  398.17  4563.1  397.87
  4577.3  397.94  4598.2  397.40  4669.5  396.53  4676.1  396.19  4712.3  395.15
  4754.8  394.81  4790.2  395.92  4804.5  396.12  4813.8  396.01  4867.2  394.32
  4867.4  393.82  4870.9  393.82  4871.2  394.32  4899.3  394.74  4907.5  395.08
  4912.5  394.63  4919.3  395.36  4949.4  395.88  4989.4  395.28  4999.5  394.88
  5119.7  396.16  5129.7  396.07  5169.8  396.69  5189.8  396.60  5203.9  396.86
#Mann=3,-1,0
  4480.9    0.05       0  4867.2   0.035       0  4871.2    0.05       0
Bank Sta=4867.2,4871.2
Exp/Cntr=0.3,0.1

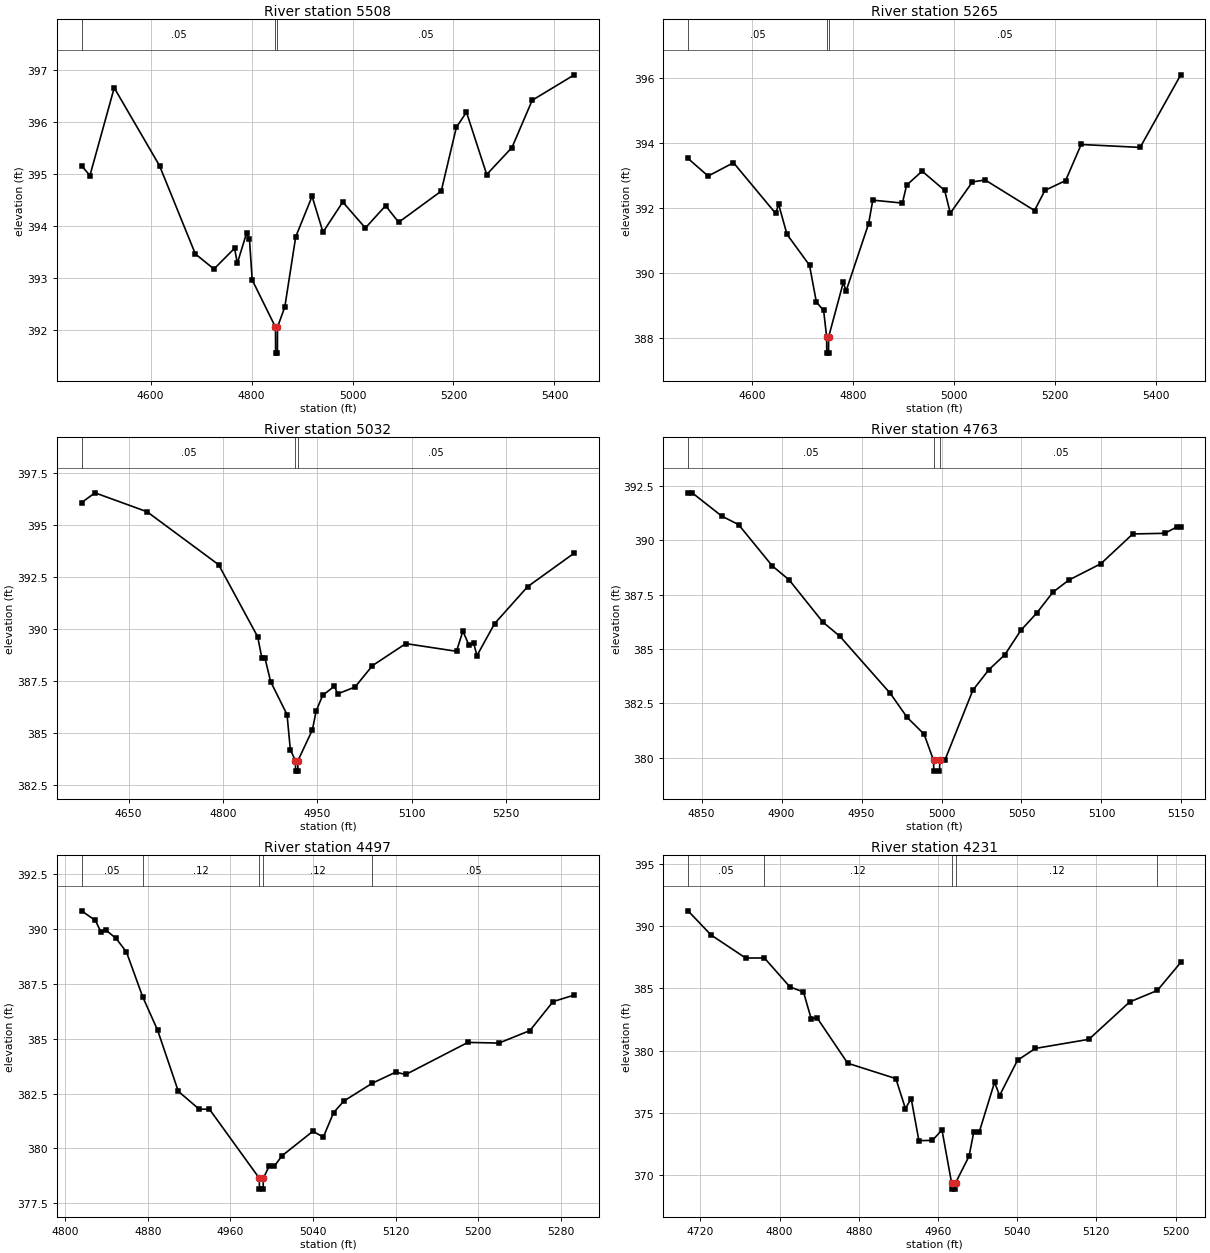
Type RM Length L Ch R = 1,5508,243,243,243
BEGIN DESCRIPTION:
1975
END DESCRIPTION:
XS GIS Cut Line= 3
      2737219.04      6792011.13      2736726.00      6791811.00
      2736282.70      6791788.10
#Sta/Elev= 30
  4463.3  395.16  4479.9  394.97  4528.0  396.66  4617.7  395.16  4688.7  393.46
  4725.6  393.17  4766.4  393.57  4771.8  393.28  4790.4  393.87  4795.9  393.74
  4801.3  392.96  4847.4  392.05  4847.7  391.55  4851.2  391.55  4851.4  392.05
  4865.9  392.44  4887.5  393.79  4919.9  394.57  4941.5  393.88  4980.7  394.46
  5025.5  393.96  5065.5  394.39  5091.4  394.07  5175.7  394.67  5205.7  395.90
  5225.7  396.19  5265.8  394.99  5315.8  395.51  5355.9  396.42  5439.3  396.91
#Mann=3,-1,0
  4463.3    0.05       0  4847.4    0.04       0  4851.4    0.05       0
Bank Sta=4847.4,4851.4
Exp/Cntr=0.3,0.1

Type RM Length L Ch R = 1,5265,233,233,233
BEGIN DESCRIPTION:
1974
END DESCRIPTION:
XS GIS Cut Line= 3
      2737243.59      6791845.47      2736776.00      6791611.00
      2736333.56      6791507.37
#Sta/Elev= 30
  4472.3  393.52  4512.2  392.98  4562.5  393.39  4646.3  391.83  4651.9  392.12
  4668.6  391.19  4713.3  390.24  4726.9  389.11  4741.3  388.85  4747.3  388.04
  4747.5  387.54  4751.0  387.54  4751.3  388.04  4780.3  389.71  4785.9  389.45
  4830.6  391.52  4838.8  392.24  4897.6  392.15  4905.9  392.70  4936.7  393.13
  4981.4  392.54  4992.6  391.84  5036.5  392.80  5061.7  392.86  5159.7  391.92
  5180.3  392.54  5221.3  392.84  5252.2  393.95  5369.2  393.86  5449.8  396.09
#Mann=3,-1,0
  4472.3    0.05       0  4747.3    0.04       0  4751.3    0.05       0
Bank Sta=4747.3,4751.3
Exp/Cntr=0.3,0.1

Type RM Length L Ch R = 1,5032,269,269,269
BEGIN DESCRIPTION:
1973
END DESCRIPTION:
XS GIS Cut Line= 3
      2737286.66      6791519.54      2736876.00      6791411.00
      2736520.14      6791366.39
#Sta/Elev= 30
  4575.3  396.09  4596.7  396.56  4679.4  395.65  4793.2  393.10  4855.3  389.63
  4861.8  388.63  4866.9  388.60  4875.9  387.47  4902.0  385.88  4907.2  384.20
  4915.3  383.66  4915.6  383.16  4919.1  383.16  4919.3  383.66  4942.3  385.15
  4948.3  386.06  4958.7  386.81  4977.3  387.25  4982.5  386.88  5010.1  387.21
  5037.8  388.24  5090.8  389.30  5171.4  388.93  5181.5  389.90  5191.5  389.21
  5198.8  389.31  5203.9  388.72  5231.9  390.26  5284.4  392.04  5358.7  393.66
#Mann=3,-1,0
  4575.3    0.05       0  4915.3    0.04       0  4919.3    0.05       0
Bank Sta=4915.3,4919.3
Exp/Cntr=0.3,0.1

Type RM Length L Ch R = 1,4763,266,266,266
BEGIN DESCRIPTION:
1972
END DESCRIPTION:
XS GIS Cut Line= 3
      2737075.98      6791210.99      2736926.00      6791161.00
      2736776.00      6791161.00
#Sta/Elev= 29
  4841.5  392.18  4844.1  392.18  4862.6  391.11  4873.1  390.72  4894.2  388.82
  4904.7  388.18  4925.8  386.24  4936.4  385.59  4968.0  382.96  4978.5  381.86
  4989.1  381.09  4995.0  379.89  4995.2  379.39  4998.7  379.39  4999.0  379.89
  4999.6  379.89  5002.1  379.89  5019.6  383.11  5029.6  384.05  5039.6  384.74
  5049.6  385.86  5059.6  386.66  5069.6  387.61  5079.6  388.17  5099.6  388.92
  5119.6  390.29  5139.6  390.32  5147.1  390.61  5149.6  390.61
#Mann=3,-1,0
  4841.5    0.05       0  4995.0    0.04       0  4999.0    0.05       0
Bank Sta=4995,4999
Exp/Cntr=0.3,0.1

Type RM Length L Ch R = 1,4497,266,266,266
BEGIN DESCRIPTION:
1971
END DESCRIPTION:
XS GIS Cut Line= 3
      2737159.36      6790927.70      2736976.00      6790911.00
      2736682.97      6790916.43
#Sta/Elev= 30
  4815.9  390.83  4829.3  390.39  4834.5  389.88  4839.5  389.95  4849.4  389.57
  4859.4  388.95  4875.1  386.91  4889.6  385.38  4909.6  382.60  4929.7  381.79
  4939.8  381.78  4988.0  378.64  4988.2  378.14  4991.7  378.14  4992.0  378.64
  4997.5  379.18  5002.5  379.18  5010.0  379.66  5040.0  380.78  5050.0  380.51
  5060.0  381.63  5070.0  382.16  5097.5  382.97  5120.0  383.47  5130.0  383.37
  5190.0  384.83  5220.1  384.80  5250.1  385.37  5272.5  386.69  5293.1  386.99
#Mann=5,-1,0
  4815.9    0.05       0  4875.1    0.12       0  4988.0    0.07       0
  4992.0    0.12       0  5097.5    0.05       0
Bank Sta=4988,4992
Exp/Cntr=0.3,0.1

Type RM Length L Ch R = 1,4231,260,260,260
BEGIN DESCRIPTION:
1970
END DESCRIPTION:
XS GIS Cut Line= 3
      2737175.98      6790810.99      2736926.00      6790661.00
      2736725.98      6790611.00
#Sta/Elev= 30
  4707.6  391.21  4730.9  389.27  4765.9  387.42  4784.7  387.43  4810.6  385.10
  4824.2  384.70  4832.0  382.55  4837.8  382.64  4868.9  378.98  4917.5  377.75
  4927.2  375.34  4933.0  376.15  4940.8  372.77  4954.4  372.79  4964.1  373.63
  4973.8  369.38  4974.1  368.88  4977.6  368.88  4977.8  369.38  4991.4  371.51
  4996.2  373.45  5001.7  373.45  5017.2  377.45  5022.3  376.39  5040.4  379.22
  5058.4  380.17  5112.5  380.90  5153.7  383.90  5181.6  384.82  5205.3  387.07
#Mann=5,-1,0
  4707.6    0.05       0  4784.7    0.12       0  4973.8    0.07       0
  4977.8    0.12       0  5181.6    0.05       0
Bank Sta=4973.8,4977.8
Exp/Cntr=0.3,0.1

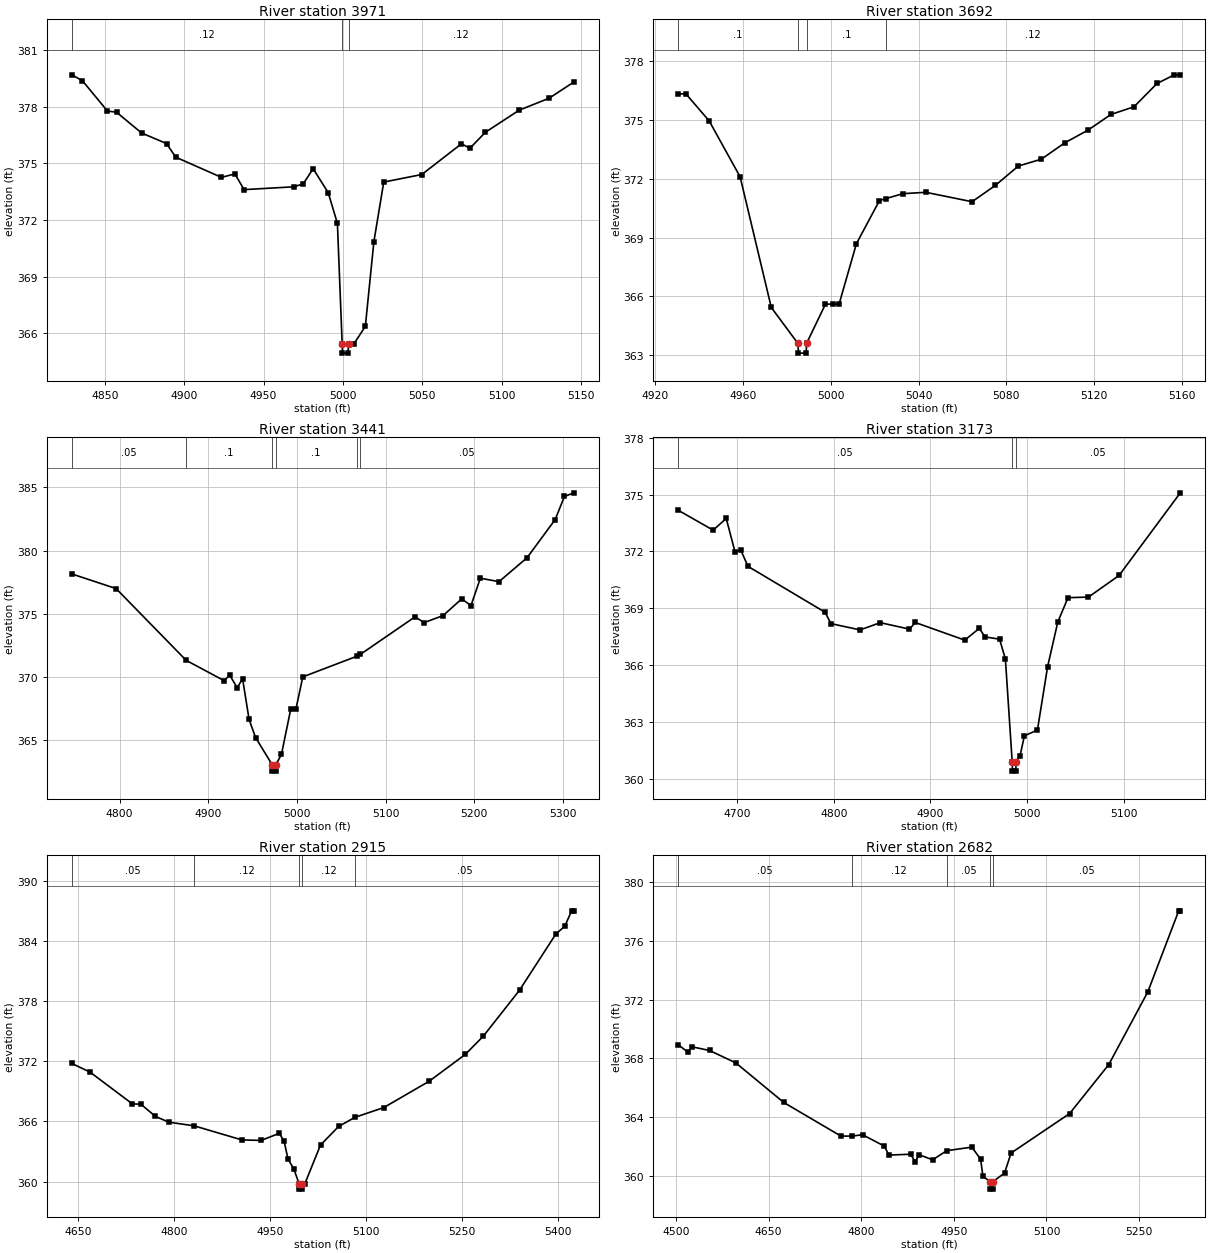
Type RM Length L Ch R = 1,3971,279,279,279
BEGIN DESCRIPTION:
1969
END DESCRIPTION:
XS GIS Cut Line= 3
      2737163.91      6790612.61      2737076.00      6790461.00
      2737026.46      6790328.83
#Sta/Elev= 30
  4829.1  379.69  4835.8  379.38  4851.6  377.77  4857.3  377.71  4873.1  376.61
  4888.8  376.05  4894.6  375.33  4923.4  374.26  4931.9  374.44  4937.7  373.61
  4969.2  373.76  4975.0  373.92  4981.2  374.72  4990.7  373.45  4996.5  371.82
  4999.5  365.45  4999.7  364.95  5003.2  364.95  5003.5  365.45  5007.0  365.45
  5014.1  366.37  5019.5  370.86  5025.7  374.01  5049.7  374.41  5074.7  376.04
  5080.0  375.80  5089.8  376.65  5111.1  377.82  5129.9  378.45  5145.5  379.31
#Mann=3,-1,0
  4829.1    0.12       0  4999.5    0.07       0  5003.5    0.12       0
Bank Sta=4999.5,5003.5
Exp/Cntr=0.3,0.1

Type RM Length L Ch R = 1,3692,251,251,251
BEGIN DESCRIPTION:
1968
END DESCRIPTION:
XS GIS Cut Line= 3
      2737325.97      6790360.97      2737276.00      6790311.00
      2737125.98      6790260.99
#Sta/Elev= 28
  4930.5  376.33  4934.0  376.33  4944.6  374.95  4958.7  372.10  4972.9  365.44
  4985.0  363.61  4985.3  363.11  4988.8  363.11  4989.0  363.61  4997.6  365.61
  5001.2  365.61  5003.8  365.61  5011.7  368.69  5022.2  370.89  5025.2  370.99
  5032.8  371.24  5043.3  371.31  5064.4  370.83  5075.0  371.66  5085.5  372.65
  5096.0  373.00  5106.6  373.83  5117.1  374.47  5127.7  375.28  5138.2  375.67
  5148.7  376.86  5156.6  377.30  5159.3  377.30
#Mann=4,-1,0
  4930.5     0.1       0  4985.0    0.07       0  4989.0     0.1       0
  5025.2    0.12       0
Bank Sta=4985,4989
Exp/Cntr=0.3,0.1

Type RM Length L Ch R = 1,3441,268,268,268
BEGIN DESCRIPTION:
1967
END DESCRIPTION:
XS GIS Cut Line= 3
      2737476.01      6790311.02      2737326.00      6790111.00
      2737025.95      6790010.98
#Sta/Elev= 30
  4746.1  378.15  4796.1  376.99  4875.1  371.31  4918.0  369.70  4924.2  370.14
  4932.6  369.15  4938.8  369.84  4946.1  366.63  4953.4  365.20  4972.2  363.04
  4972.5  362.54  4976.0  362.54  4976.2  363.04  4982.6  363.86  4993.0  367.42
  4998.8  367.42  5006.7  370.00  5067.5  371.63  5071.6  371.78  5133.2  374.75
  5143.7  374.30  5164.8  374.85  5185.9  376.17  5196.4  375.65  5206.9  377.81
  5228.0  377.54  5259.6  379.43  5291.3  382.45  5301.8  384.28  5312.4  384.57
#Mann=6,-1,0
  4746.1    0.05       0  4875.1     0.1       0  4972.2    0.07       0
  4976.2     0.1       0  5067.5    0.12       0  5071.6    0.05       0
Bank Sta=4972.2,4976.2
Exp/Cntr=0.3,0.1

Type RM Length L Ch R = 1,3173,258,258,258
BEGIN DESCRIPTION:
1966
END DESCRIPTION:
XS GIS Cut Line= 3
      2737576.01      6790161.01      2737376.00      6789861.00
      2737225.98      6789810.99
#Sta/Elev= 30
  4639.4  374.17  4675.5  373.12  4689.0  373.74  4698.0  371.98  4704.0  372.07
  4711.5  371.21  4791.1  368.79  4797.2  368.19  4827.2  367.86  4848.2  368.24
  4878.3  367.90  4884.3  368.25  4935.4  367.32  4950.4  367.94  4956.4  367.49
  4971.4  367.37  4977.4  366.32  4984.4  360.91  4984.7  360.41  4988.2  360.41
  4988.4  360.91  4992.5  361.21  4997.0  362.27  5010.5  362.58  5021.0  365.92
  5031.6  368.29  5042.1  369.56  5063.2  369.59  5094.8  370.73  5158.1  375.09
#Mann=3,-1,0
  4639.4    0.05       0  4984.4    0.05       0  4988.4    0.05       0
Bank Sta=4984.4,4988.4
Exp/Cntr=0.3,0.1

Type RM Length L Ch R = 1,2915,233,233,233
BEGIN DESCRIPTION:
1965
END DESCRIPTION:
XS GIS Cut Line= 3
      2737725.99      6789960.98      2737526.00      6789661.00
      2737226.00      6789361.00
#Sta/Elev= 30
  4639.7  371.79  4668.2  370.93  4734.3  367.76  4747.8  367.72  4770.4  366.51
  4791.4  365.93  4830.7  365.57  4905.6  364.16  4935.6  364.11  4964.2  364.82
  4971.7  364.01  4977.7  362.25  4986.7  361.28  4995.2  359.75  4995.5  359.25
  4999.0  359.25  4999.2  359.75  5003.8  359.75  5028.5  363.65  5056.8  365.50
  5082.5  366.42  5127.5  367.39  5198.2  370.01  5254.8  372.69  5283.1  374.52
  5339.6  379.10  5396.2  384.69  5410.4  385.49  5421.0  387.02  5424.5  387.02
#Mann=5,-1,0
  4639.7    0.05       0  4830.7    0.12       0  4995.2    0.07       0
  4999.2    0.12       0  5082.5    0.05       0
Bank Sta=4995.2,4999.2
Exp/Cntr=0.3,0.1

Type RM Length L Ch R = 1,2682,283,283,283
BEGIN DESCRIPTION:
1964
END DESCRIPTION:
XS GIS Cut Line= 3
      2737962.88      6789825.99      2737626.00      6789461.00
      2737326.02      6789361.01
#Sta/Elev= 30
  4503.8  368.93  4519.4  368.43  4526.2  368.79  4554.5  368.54  4597.0  367.70
  4674.7  365.01  4767.2  362.73  4784.8  362.73  4802.3  362.82  4837.5  362.05
  4844.8  361.44  4880.0  361.50  4887.4  360.99  4894.2  361.46  4915.7  361.12
  4938.5  361.74  4979.2  361.98  4993.4  361.16  4997.1  360.00  5009.0  359.63
  5009.3  359.13  5012.8  359.13  5013.0  359.63  5032.1  360.22  5042.7  361.58
  5137.5  364.26  5200.8  367.58  5264.0  372.51  5314.1  378.02  5316.7  378.02
#Mann=5,-1,0
  4503.8    0.05       0  4784.8    0.12       0  4938.5    0.05       0
  5009.0    0.04       0  5013.0    0.05       0
Bank Sta=5009,5013
Exp/Cntr=0.3,0.1

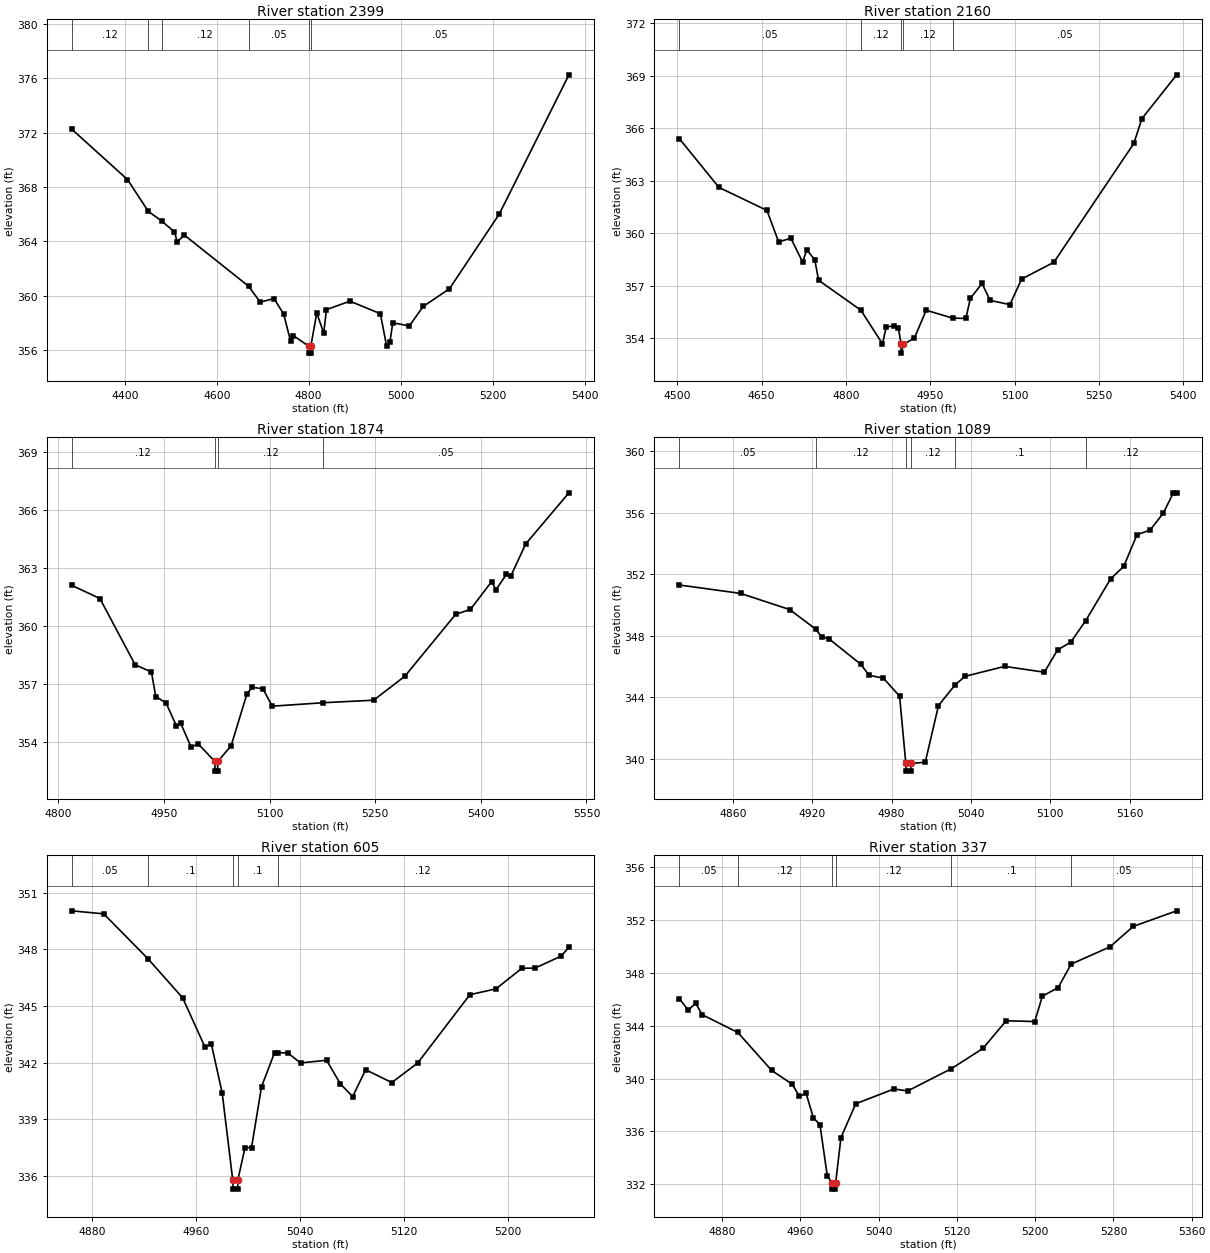
Type RM Length L Ch R = 1,2399,239,239,239
BEGIN DESCRIPTION:
1963
END DESCRIPTION:
XS GIS Cut Line= 3
      2738126.03      6789811.04      2737726.00      6789211.00
      2737426.01      6789011.01
#Sta/Elev= 30
  4284.3  372.27  4406.0  368.55  4451.1  366.22  4480.8  365.49  4508.2  364.70
  4514.2  363.96  4529.2  364.48  4669.6  360.70  4694.5  359.54  4724.5  359.80
  4745.6  358.67  4760.6  356.68  4766.6  357.08  4800.6  356.29  4800.9  355.79
  4804.4  355.79  4804.6  356.29  4817.7  358.74  4832.7  357.26  4838.7  358.99
  4889.8  359.61  4955.9  358.69  4969.4  356.33  4976.9  356.64  4982.9  358.02
  5019.0  357.79  5049.0  359.22  5106.1  360.52  5214.3  366.00  5366.0  376.25
#Mann=6,-1,0
  4284.3    0.12       0  4451.1    0.05       0  4480.8    0.12       0
  4669.6    0.05       0  4800.6    0.04       0  4804.6    0.05       0
Bank Sta=4800.6,4804.6
Exp/Cntr=0.3,0.1

Type RM Length L Ch R = 1,2160,286,286,286
BEGIN DESCRIPTION:
1962
END DESCRIPTION:
XS GIS Cut Line= 3
      2738226.02      6789411.02      2737892.67      6789043.48
      2737592.40      6788797.44
#Sta/Elev= 30
  4503.8  365.41  4574.4  362.62  4659.6  361.31  4680.5  359.51  4702.2  359.72
  4723.1  358.36  4730.6  359.06  4744.8  358.48  4751.5  357.32  4826.7  355.61
  4865.1  353.69  4871.8  354.67  4886.0  354.70  4893.4  354.61  4898.2  353.66
  4898.4  353.16  4902.2  353.66  4921.8  354.02  4942.8  355.61  4989.7  355.16
  5013.4  355.14  5021.3  356.28  5042.1  357.14  5056.5  356.17  5091.7  355.93
  5112.5  357.39  5169.9  358.35  5312.0  365.13  5326.4  366.55  5388.2  369.05
#Mann=5,-1,0
  4503.8    0.05       0  4826.7    0.12       0  4898.2    0.04       0
  4902.2    0.12       0  4989.7    0.05       0
Bank Sta=4898.2,4902.2
Exp/Cntr=0.3,0.1

Type RM Length L Ch R = 1,1874,785,785,785
BEGIN DESCRIPTION:
1961
END DESCRIPTION:
XS GIS Cut Line= 3
      2738218.25      6789016.36      2738076.00      6788911.00
      2737634.96      6788618.38
#Sta/Elev= 30
  4818.8  362.10  4859.1  361.41  4909.2  357.98  4932.2  357.61  4938.4  356.34
  4953.0  356.01  4967.7  354.82  4973.9  354.95  4988.5  353.73  4998.8  353.88
  5022.4  352.98  5022.6  352.48  5026.1  352.48  5026.4  352.98  5045.4  353.79
  5067.8  356.47  5075.5  356.82  5090.6  356.74  5103.8  355.84  5176.4  356.02
  5247.8  356.15  5292.1  357.39  5364.2  360.59  5385.3  360.85  5415.4  362.29
  5421.4  361.86  5436.4  362.66  5442.4  362.56  5463.8  364.24  5525.1  366.88
#Mann=4,-1,0
  4818.8    0.12       0  5022.4    0.07       0  5026.4    0.12       0
  5176.4    0.05       0
Bank Sta=5022.4,5026.4
Exp/Cntr=0.3,0.1

Type RM Length L Ch R = 1,1089,484,484,484
BEGIN DESCRIPTION:
1960
END DESCRIPTION:
XS GIS Cut Line= 3
      2738389.00      6788144.95      2738226.00      6788211.00
      2738025.97      6788211.00
#Sta/Elev= 30
  4819.6  351.30  4866.0  350.75  4903.0  349.70  4922.8  348.42  4927.1  347.92
  4932.5  347.81  4956.6  346.15  4963.1  345.42  4973.9  345.23  4986.1  344.06
  4990.8  339.68  4991.0  339.18  4994.5  339.18  4994.8  339.68  5005.5  339.76
  5015.5  343.45  5027.8  344.77  5035.5  345.35  5065.5  346.00  5095.5  345.62
  5105.5  347.07  5115.5  347.58  5126.7  348.97  5145.5  351.69  5155.5  352.51
  5165.5  354.57  5175.5  354.88  5185.5  355.99  5193.0  357.30  5195.5  357.30
#Mann=6,-1,0
  4819.6    0.05       0  4922.8    0.12       0  4990.8    0.07       0
  4994.8    0.12       0  5027.8     0.1       0  5126.7    0.12       0
Bank Sta=4990.8,4994.8
Exp/Cntr=0.3,0.1

Type RM Length L Ch R = 1,605,268,268,268
BEGIN DESCRIPTION:
1959
END DESCRIPTION:
XS GIS Cut Line= 3
      2738360.44      6787813.11      2738226.28      6787790.82
      2737979.93      6787772.97
#Sta/Elev= 30
  4864.0  350.03  4888.8  349.87  4922.9  347.49  4949.6  345.42  4966.6  342.84
  4971.7  342.97  4980.0  340.39  4988.1  335.80  4988.4  335.30  4991.9  335.30
  4992.1  335.80  4997.6  337.50  5002.6  337.50  5010.3  340.72  5020.3  342.52
  5022.6  342.52  5030.4  342.51  5040.4  341.98  5060.4  342.12  5071.1  340.86
  5080.5  340.20  5090.5  341.62  5110.6  340.94  5130.6  341.98  5170.7  345.59
  5190.8  345.90  5210.8  346.99  5220.9  347.00  5240.9  347.63  5247.0  348.10
#Mann=5,-1,0
  4864.0    0.05       0  4922.9     0.1       0  4988.1    0.07       0
  4992.1     0.1       0  5022.6    0.12       0
Bank Sta=4988.1,4992.1
Exp/Cntr=0.3,0.1

Type RM Length L Ch R = 1,337,266,266,266
BEGIN DESCRIPTION:
2360
END DESCRIPTION:
XS GIS Cut Line= 3
      2738400.01      6787680.26      2738281.12      6787573.51
      2737959.29      6787439.24
#Sta/Elev= 30
  4836.2  346.06  4845.4  345.18  4852.9  345.71  4859.6  344.84  4896.1  343.49
  4930.7  340.61  4951.6  339.58  4959.1  338.64  4965.8  338.89  4973.3  337.02
  4980.0  336.51  4987.5  332.63  4992.1  332.12  4992.4  331.62  4995.9  331.62
  4996.1  332.12  5001.5  335.53  5016.6  338.09  5055.7  339.21  5069.7  339.06
  5114.4  340.75  5146.6  342.28  5170.4  344.38  5199.6  344.32  5207.4  346.24
  5223.5  346.89  5236.8  348.67  5276.5  349.98  5300.3  351.53  5344.7  352.71
#Mann=6,-1,0
  4836.2    0.05       0  4896.1    0.12       0  4992.1    0.07       0
  4996.1    0.12       0  5114.4     0.1       0  5236.8    0.05       0
Bank Sta=4992.1,4996.1
Exp/Cntr=0.3,0.1

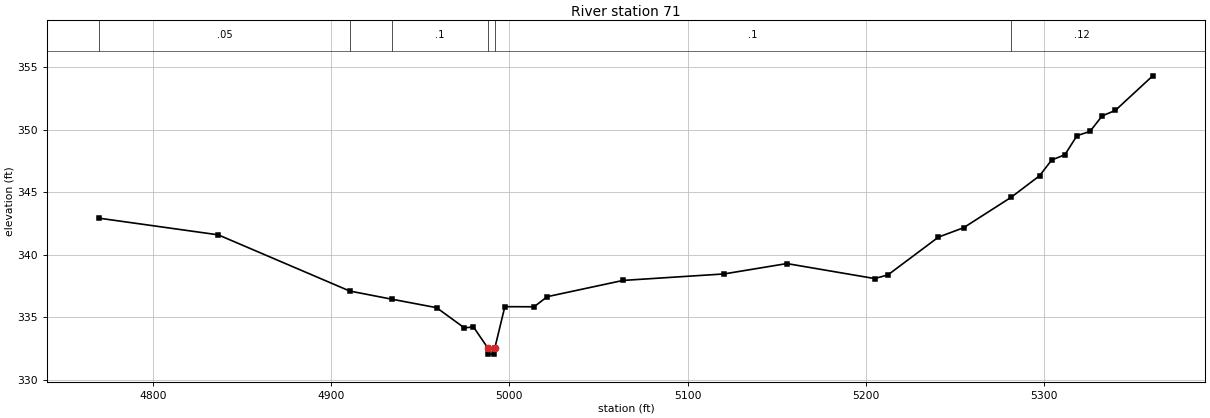
Type RM Length L Ch R = 1,71,0,0,0
BEGIN DESCRIPTION:
1958
END DESCRIPTION:
XS GIS Cut Line= 3
      2738522.42      6787636.34      2738475.98      6787411.08
      2738231.38      6787145.57
#Sta/Elev= 30
  4770.0  342.92  4836.7  341.59  4910.5  337.09  4934.0  336.44  4959.2  335.76
  4974.8  334.14  4979.9  334.22  4987.9  332.54  4988.1  332.04  4991.6  332.04
  4991.9  332.54  4997.5  335.84  5013.9  335.83  5021.3  336.64  5063.8  337.94
  5120.5  338.46  5155.7  339.29  5205.0  338.09  5212.4  338.38  5240.8  341.41
  5254.9  342.16  5281.6  344.60  5297.5  346.32  5304.3  347.58  5311.7  348.00
  5318.5  349.53  5325.8  349.87  5332.6  351.11  5340.0  351.55  5361.0  354.32
#Mann=6,-1,0
  4770.0    0.05       0  4910.5    0.12       0  4934.0     0.1       0
  4987.9    0.07       0  4991.9     0.1       0  5281.6    0.12       0
Bank Sta=4987.9,4991.9
Exp/Cntr=0.3,0.1

Chan Stop Cuts=-1