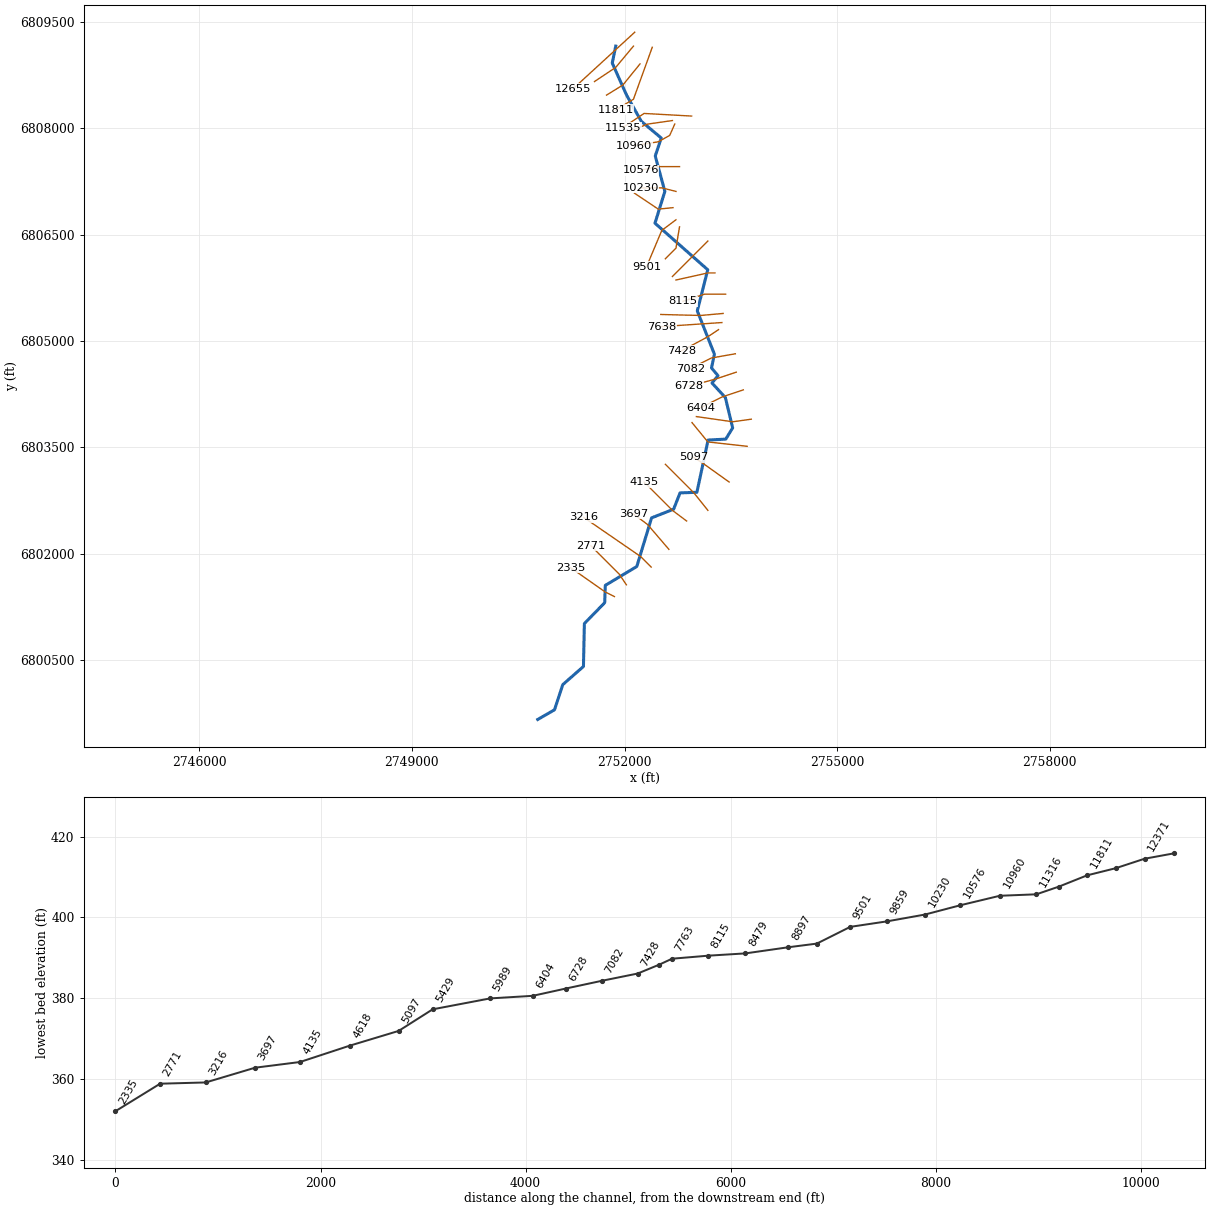
--- Clear Creek T 25.prj (project) ---

Proj Title=Clear Creek T 25 Base Level Engineering
Current Plan=p01
Default Exp/Contr=0.3,0.1
English Units
Geom File=g01
Flow File=f01
Plan File=p01
BEGIN DESCRIPTION:
Clear Creek T 25
END DESCRIPTION:

--- Clear Creek T 25.p01 (plan) ---

Plan Title=Multiple Run
Short Identifier=Multiple
Geom File=g01
Flow File=f01
Subcritical Flow
K Sum by GR= 0
Std Step Tol= 0.01
Critical Tol= 0.01
Num of Std Step Trials= 20
Max Error Tol= 0.3
Flow Tol Ratio= 0.001
Split Flow NTrial= 30
Split Flow Tol= 0.02
Split Flow Ratio= 0.02
Log Output Level= 0
Friction Slope Method= 1
Unsteady Friction Slope Method= 2
Unsteady Bridges Friction Slope Method= 1
Parabolic Critical Depth
Global Vel Dist=  1 , 1 , 1
Global Log Level= 0
CheckData=True
Encroach Param= -1, 0, 0, 0
BEGIN DESCRIPTION:
Multiple Run
END DESCRIPTION:

--- Clear Creek T 25.f01 (steady flow) ---

Flow Title=Multiple
Number of Profiles=7
Profile Names=10-year,25-year,50-year,1pct_min,100-year,1pct_plu,500-year
River Rch & RM= Clear Creek T 25,Reach-1,12655
     226     286     332     193     384     767     514
River Rch & RM= Clear Creek T 25,Reach-1,10960
     413     543     646     383     764    1524    1068
River Rch & RM= Clear Creek T 25,Reach-1,8479
     518     690     830     496     989    1973    1408
River Rch & RM= Clear Creek T 25,Reach-1,5989
     703     955    1161     701    1399    2792    2037
Boundary for River Rch & Prof#=Clear Creek T 25,Reach-1,1
Up Type=0
Dn Type=3
Dn Slope=0.005
Boundary for River Rch & Prof#=Clear Creek T 25,Reach-1,2
Up Type=0
Dn Type=3
Dn Slope=0.005
Boundary for River Rch & Prof#=Clear Creek T 25,Reach-1,3
Up Type=0
Dn Type=3
Dn Slope=0.005
Boundary for River Rch & Prof#=Clear Creek T 25,Reach-1,4
Up Type=0
Dn Type=3
Dn Slope=0.005
Boundary for River Rch & Prof#=Clear Creek T 25,Reach-1,5
Up Type=0
Dn Type=3
Dn Slope=0.005
Boundary for River Rch & Prof#=Clear Creek T 25,Reach-1,6
Up Type=0
Dn Type=3
Dn Slope=0.005
Boundary for River Rch & Prof#=Clear Creek T 25,Reach-1,7
Up Type=0
Dn Type=3
Dn Slope=0.005

--- Clear Creek T 25.g01 (geometry) ---

Geom Title=Existing Conditions

River Reach=Clear Creek T 25,Reach-1
Reach XY= 30
      2751876.00      6809161.00      2751826.75      6808921.68
      2752029.35      6808469.06      2752236.08      6808101.01
      2752518.21      6807864.43      2752433.56      6807611.00
      2752568.97      6807110.79      2752429.53      6806662.47
      2753174.32      6806005.55      2753026.55      6805424.98
      2753268.19      6804814.41      2753227.21      6804620.59
      2753318.89      6804511.00      2753233.85      6804407.77
      2753422.76      6804202.99      2753525.47      6803774.97
      2753428.70      6803616.36      2753179.00      6803603.05
      2753021.00      6802866.00      2752783.62      6802857.93
      2752692.71      6802627.63      2752381.58      6802505.42
      2752172.97      6801819.01      2751728.91      6801553.09
      2751720.54      6801308.55      2751433.73      6801014.63
      2751420.53      6800408.55      2751129.06      6800152.72
      2751012.38      6799797.76      2750776.00      6799661.00

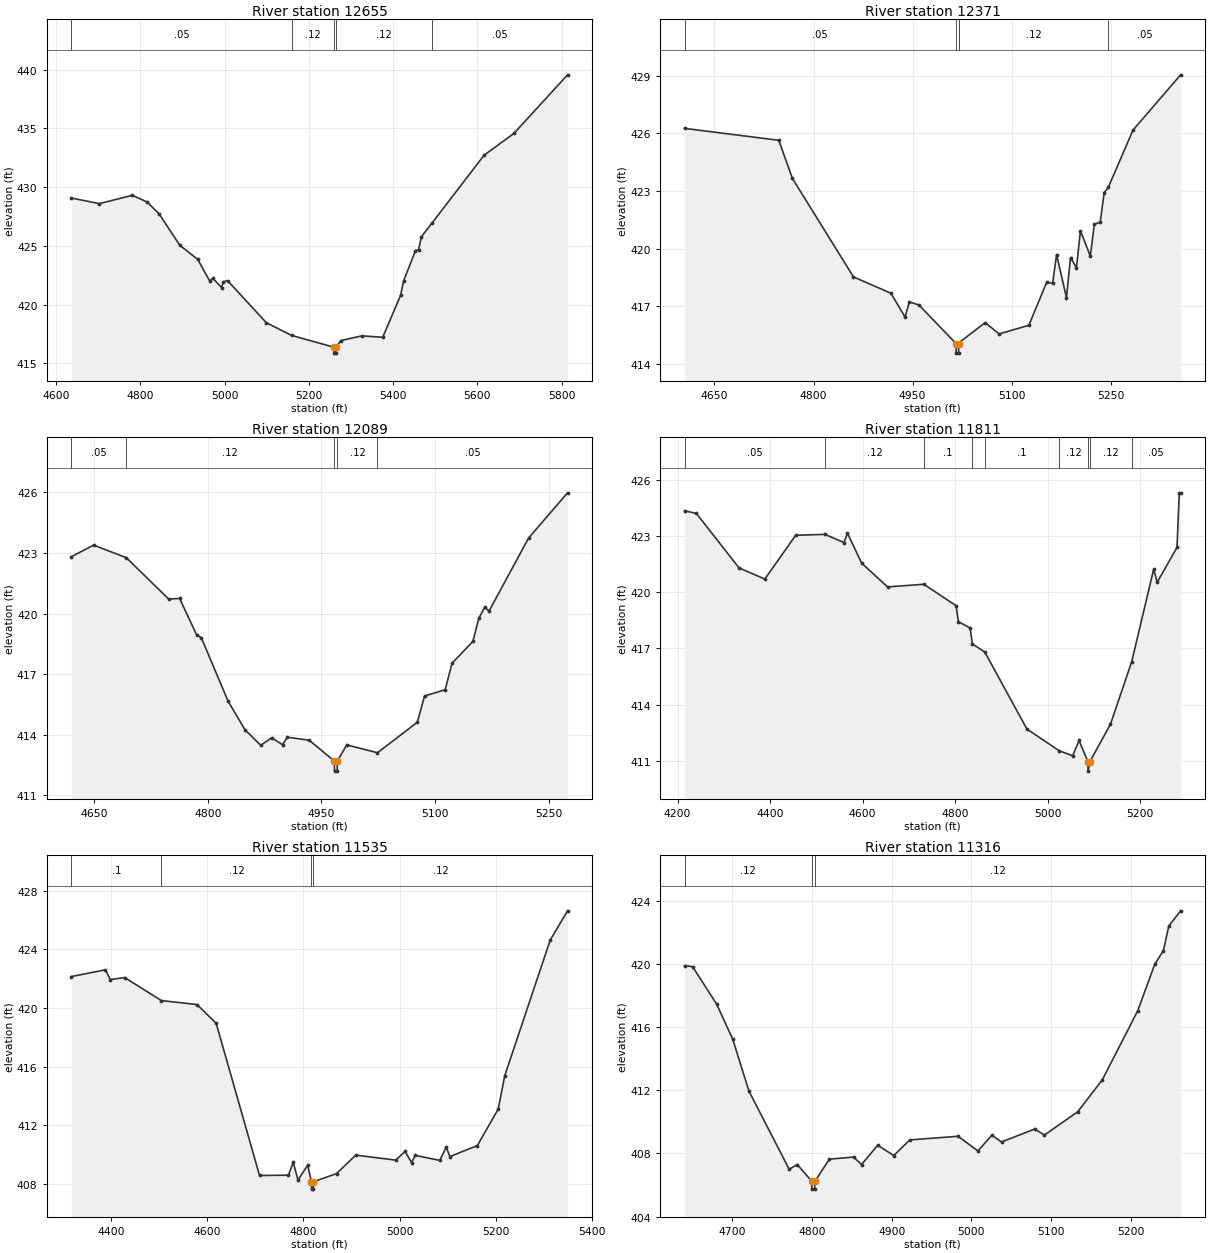
Type RM Length L Ch R = 1,12655,284,284,284
BEGIN DESCRIPTION:
Clear Creek T 25 33.0
END DESCRIPTION:
XS GIS Cut Line= 3
      2752144.07      6809356.72      2751876.00      6809111.00
      2751276.00      6808561.00
#Sta/Elev= 30
  4636.5  429.08  4702.6  428.60  4780.9  429.31  4816.1  428.74  4844.5  427.73
  4893.8  425.05  4936.3  423.85  4964.7  422.01  4972.1  422.24  4993.1  421.45
  4996.8  421.95  5007.2  422.04  5099.1  418.46  5158.9  417.38  5259.9  416.37
  5260.2  415.87  5263.7  415.87  5263.9  416.37  5276.1  416.94  5325.7  417.34
  5375.4  417.22  5417.9  420.80  5424.7  422.00  5453.1  424.60  5460.5  424.67
  5467.2  425.78  5491.8  426.92  5615.9  432.72  5686.8  434.58  5814.1  439.57
#Mann=5,-1,0
  4636.5    0.05       0  5158.9    0.12       0  5259.9    0.05       0
  5263.9    0.12       0  5491.8    0.05       0
Bank Sta=5259.9,5263.9
Exp/Cntr=0.3,0.1

Type RM Length L Ch R = 1,12371,282,282,282
BEGIN DESCRIPTION:
Clear Creek T 25 32.0
END DESCRIPTION:
XS GIS Cut Line= 3
      2752126.03      6809161.03      2751876.00      6808861.00
      2751576.01      6808661.01
#Sta/Elev= 30
  4604.7  426.26  4747.3  425.64  4768.1  423.65  4860.5  418.52  4917.2  417.67
  4938.6  416.43  4945.1  417.22  4959.5  417.06  5015.8  415.05  5016.0  414.55
  5019.5  414.55  5019.8  415.05  5020.5  415.10  5059.9  416.14  5080.9  415.55
  5126.0  416.00  5153.0  418.24  5162.0  418.19  5168.0  419.68  5183.0  417.44
  5189.1  419.53  5198.1  419.00  5204.1  420.92  5219.1  419.61  5225.1  421.26
  5234.1  421.38  5240.1  422.91  5246.2  423.18  5283.7  426.17  5355.8  429.05
#Mann=5,-1,0
  4604.7    0.05       0  5015.8    0.05       0  5019.8    0.05       0
  5020.5    0.12       0  5246.2    0.05       0
Bank Sta=5015.8,5019.8
Exp/Cntr=0.3,0.1

Type RM Length L Ch R = 1,12089,278,278,278
BEGIN DESCRIPTION:
Clear Creek T 25 31.0
END DESCRIPTION:
XS GIS Cut Line= 3
      2752218.54      6808909.74      2751976.00      6808611.00
      2751746.13      6808469.74
#Sta/Elev= 30
  4620.1  422.82  4649.3  423.39  4692.4  422.77  4748.4  420.72  4762.8  420.75
  4785.1  418.96  4791.5  418.80  4826.7  415.67  4849.0  414.25  4869.8  413.48
  4884.2  413.85  4898.6  413.51  4905.0  413.88  4933.8  413.73  4967.0  412.70
  4967.2  412.20  4970.7  412.20  4971.0  412.70  4983.3  413.50  5023.9  413.11
  5076.5  414.62  5086.0  415.92  5113.2  416.23  5122.3  417.54  5149.9  418.63
  5157.5  419.76  5165.3  420.31  5171.2  420.13  5223.3  423.74  5274.7  425.98
#Mann=5,-1,0
  4620.1    0.05       0  4692.4    0.12       0  4967.0    0.07       0
  4971.0    0.12       0  5023.9    0.05       0
Bank Sta=4967,4971
Exp/Cntr=0.3,0.1

Type RM Length L Ch R = 1,11811,276,276,276
BEGIN DESCRIPTION:
Clear Creek T 25 30.0
END DESCRIPTION:
XS GIS Cut Line= 3
      2752391.53      6809145.10      2752126.00      6808411.00
      2751876.00      6808261.00
#Sta/Elev= 30
  4215.1  424.36  4240.7  424.22  4332.7  421.31  4388.7  420.71  4455.3  423.05
  4518.5  423.10  4559.8  422.66  4567.3  423.16  4597.9  421.56  4653.9  420.29
  4732.3  420.43  4801.8  419.29  4807.2  418.43  4832.5  418.09  4837.3  417.24
  4864.0  416.81  4955.1  412.69  5024.8  411.53  5054.1  411.26  5067.7  412.08
  5087.0  410.94  5087.3  410.44  5091.0  410.94  5135.7  412.95  5181.6  416.29
  5229.0  421.23  5236.8  420.54  5279.5  422.40  5284.4  425.32  5287.3  425.32
#Mann=9,-1,0
  4215.1    0.05       0  4518.5    0.12       0  4732.3     0.1       0
  4837.3    0.12       0  4864.0     0.1       0  5024.8    0.12       0
  5087.0    0.07       0  5091.0    0.12       0  5181.6    0.05       0
Bank Sta=5087,5091
Exp/Cntr=0.3,0.1

Type RM Length L Ch R = 1,11535,219,219,219
BEGIN DESCRIPTION:
Clear Creek T 25 29.0
END DESCRIPTION:
XS GIS Cut Line= 3
      2752946.67      6808174.01      2752276.00      6808211.00
      2751976.04      6808011.02
#Sta/Elev= 30
  4317.3  422.14  4388.1  422.60  4398.1  421.93  4428.1  422.07  4504.3  420.50
  4578.4  420.23  4618.4  418.95  4708.6  408.57  4768.7  408.59  4778.7  409.47
  4788.7  408.26  4808.7  409.27  4816.7  408.14  4817.0  407.64  4820.5  407.64
  4820.7  408.14  4868.8  408.70  4908.9  409.96  4992.0  409.62  5011.5  410.21
  5025.0  409.45  5032.6  409.94  5083.6  409.60  5097.2  410.50  5104.7  409.86
  5161.8  410.61  5205.3  413.10  5218.8  415.37  5313.5  424.63  5349.5  426.62
#Mann=4,-1,0
  4317.3     0.1       0  4504.3    0.12       0  4816.7    0.07       0
  4820.7    0.12       0
Bank Sta=4816.7,4820.7
Exp/Cntr=0.3,0.1

Type RM Length L Ch R = 1,11316,356,356,356
BEGIN DESCRIPTION:
Clear Creek T 25 28.0
END DESCRIPTION:
XS GIS Cut Line= 3
      2752676.04      6808111.01      2752326.00      6808061.00
      2752075.96      6807960.98
#Sta/Elev= 30
  4639.8  419.91  4649.9  419.84  4680.2  417.46  4700.4  415.23  4720.7  411.95
  4771.2  407.00  4781.3  407.30  4799.5  406.24  4799.7  405.74  4803.2  405.74
  4803.5  406.24  4821.7  407.64  4852.0  407.77  4862.1  407.30  4882.3  408.52
  4902.5  407.87  4922.7  408.86  4983.3  409.09  5008.2  408.16  5025.7  409.16
  5037.8  408.73  5079.6  409.55  5091.7  409.17  5133.4  410.64  5164.4  412.67
  5208.8  417.04  5230.3  420.00  5241.1  420.86  5247.8  422.41  5262.7  423.38
#Mann=3,-1,0
  4639.8    0.12       0  4799.5    0.07       0  4803.5    0.12       0
Bank Sta=4799.5,4803.5
Exp/Cntr=0.3,0.1

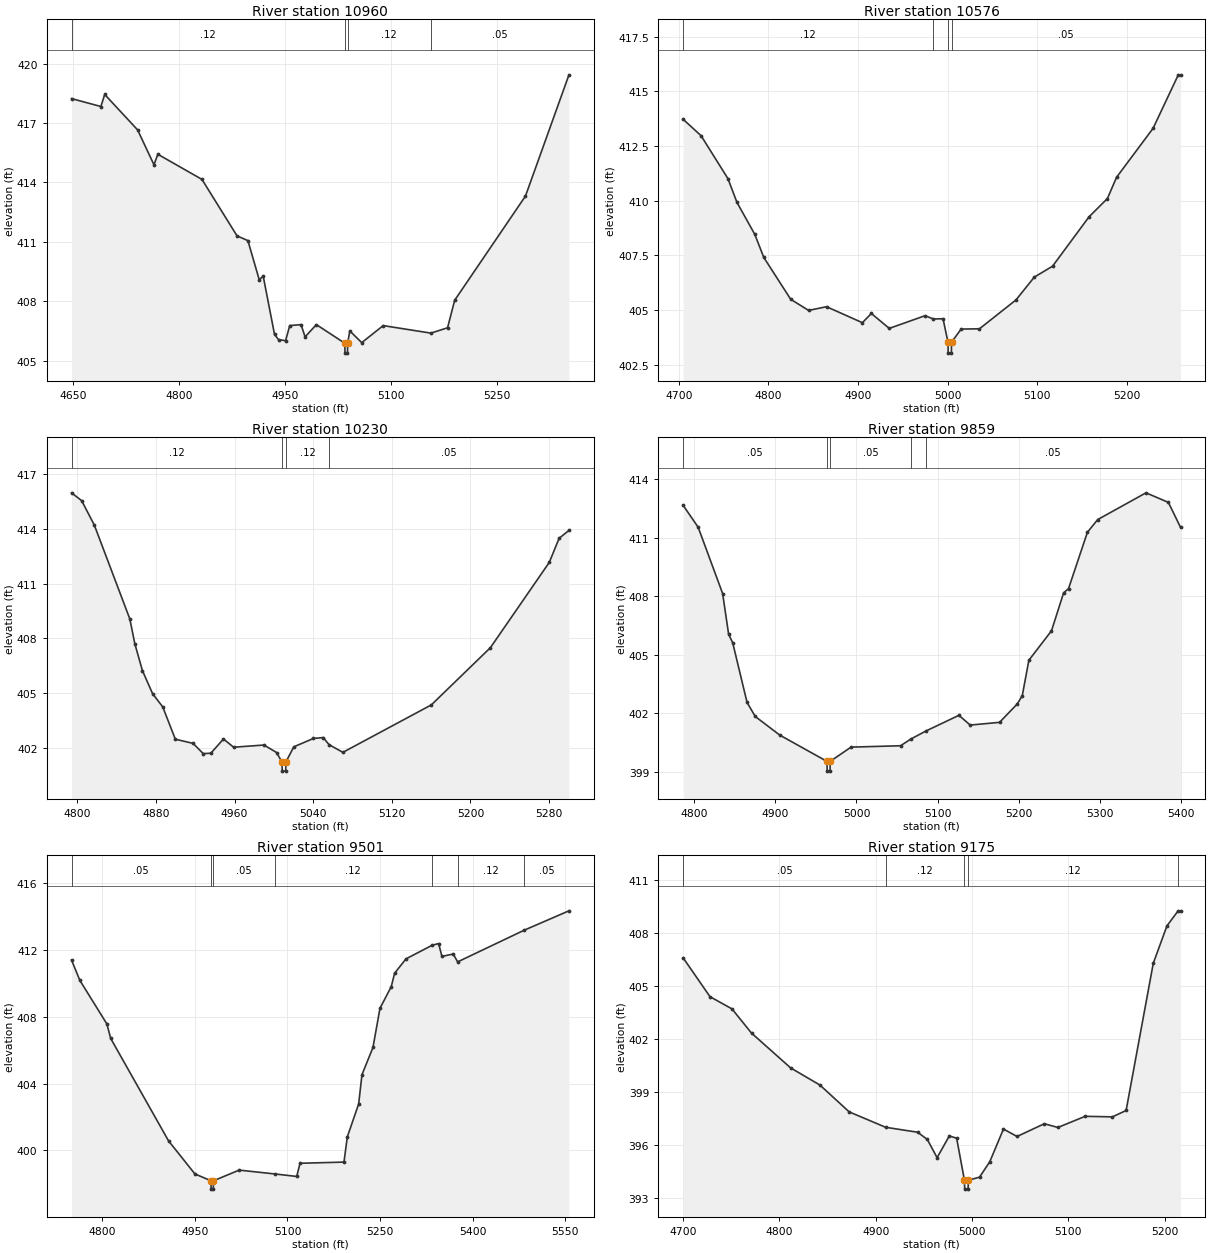
Type RM Length L Ch R = 1,10960,384,384,384
BEGIN DESCRIPTION:
Clear Creek T 25 27.0
END DESCRIPTION:
XS GIS Cut Line= 4
      2752708.88      6808061.72      2752637.77      6807901.58
      2752476.00      6807811.00      2752136.08      6807756.97
#Sta/Elev= 30
  4647.4  418.23  4689.0  417.83  4694.4  418.44  4741.0  416.65  4764.2  414.89
  4769.7  415.42  4832.2  414.15  4881.9  411.30  4897.3  411.06  4913.3  409.09
  4919.0  409.26  4935.0  406.33  4940.7  406.06  4950.7  406.01  4956.6  406.77
  4972.6  406.82  4978.3  406.20  4994.3  406.82  5034.6  405.88  5034.9  405.38
  5038.4  405.38  5038.6  405.88  5041.7  406.50  5058.6  405.91  5089.0  406.77
  5156.6  406.39  5180.2  406.66  5190.3  408.05  5290.6  413.31  5352.2  419.43
#Mann=4,-1,0
  4647.4    0.12       0  5034.6    0.07       0  5038.6    0.12       0
  5156.6    0.05       0
Bank Sta=5034.6,5038.6
Exp/Cntr=0.3,0.1

Type RM Length L Ch R = 1,10576,346,346,346
BEGIN DESCRIPTION:
Clear Creek T 25 26.0
END DESCRIPTION:
XS GIS Cut Line= 3
      2752776.05      6807461.00      2752476.00      6807461.00
      2752226.00      6807411.00
#Sta/Elev= 30
  4704.8  413.72  4724.8  412.97  4754.8  411.01  4764.8  409.93  4784.8  408.46
  4794.8  407.41  4824.8  405.50  4844.8  404.99  4864.8  405.16  4904.8  404.43
  4914.8  404.85  4934.8  404.17  4974.8  404.75  4983.9  404.60  4994.8  404.61
  5000.3  403.54  5000.6  403.04  5004.1  403.04  5004.3  403.54  5015.0  404.14
  5035.4  404.15  5076.2  405.47  5096.6  406.51  5117.0  407.01  5157.8  409.27
  5178.2  410.10  5188.4  411.07  5229.2  413.31  5257.3  415.75  5259.8  415.75
#Mann=4,-1,0
  4704.8    0.12       0  4983.9    0.05       0  5000.3    0.05       0
  5004.3    0.05       0
Bank Sta=5000.3,5004.3
Exp/Cntr=0.3,0.1

Type RM Length L Ch R = 1,10230,371,371,371
BEGIN DESCRIPTION:
Clear Creek T 25 25.0
END DESCRIPTION:
XS GIS Cut Line= 3
      2752725.99      6807111.00      2752526.00      6807161.00
      2752226.05      6807161.00
#Sta/Elev= 30
  4794.1  415.98  4804.4  415.55  4817.3  414.21  4853.4  409.07  4858.5  407.71
  4866.2  406.24  4876.6  404.97  4886.9  404.25  4899.7  402.48  4917.8  402.25
  4928.1  401.69  4935.8  401.71  4948.7  402.49  4959.0  402.04  4989.9  402.16
  5002.7  401.75  5008.2  401.23  5008.5  400.73  5012.0  400.73  5012.2  401.23
  5020.2  402.06  5040.2  402.52  5050.2  402.57  5056.1  402.18  5070.2  401.76
  5160.2  404.36  5220.2  407.49  5280.2  412.17  5290.2  413.49  5300.2  413.92
#Mann=4,-1,0
  4794.1    0.12       0  5008.2    0.07       0  5012.2    0.12       0
  5056.1    0.05       0
Bank Sta=5008.2,5012.2
Exp/Cntr=0.3,0.1

Type RM Length L Ch R = 1,9859,358,358,358
BEGIN DESCRIPTION:
Clear Creek T 25 24.0
END DESCRIPTION:
XS GIS Cut Line= 3
      2752684.44      6806881.80      2752476.00      6806861.00
      2752140.64      6807085.78
#Sta/Elev= 30
  4786.3  412.66  4804.8  411.54  4835.0  408.14  4842.4  406.05  4847.4  405.62
  4865.1  402.56  4875.2  401.84  4905.3  400.89  4963.6  399.54  4963.9  399.04
  4967.4  399.04  4967.6  399.54  4993.3  400.27  5054.3  400.34  5067.3  400.69
  5085.8  401.10  5126.3  401.90  5140.2  401.40  5176.4  401.54  5198.4  402.49
  5204.4  402.91  5212.5  404.72  5240.4  406.23  5255.4  408.18  5261.4  408.39
  5284.7  411.28  5297.4  411.93  5356.9  413.30  5384.5  412.81  5399.5  411.53
#Mann=5,-1,0
  4786.3    0.05       0  4963.6    0.03       0  4967.6    0.05       0
  5067.3    0.12       0  5085.8    0.05       0
Bank Sta=4963.6,4967.6
Exp/Cntr=0.3,0.1

Type RM Length L Ch R = 1,9501,326,326,326
BEGIN DESCRIPTION:
Clear Creek T 25 23.0
END DESCRIPTION:
XS GIS Cut Line= 3
      2752725.97      6806710.98      2752526.00      6806561.00
      2752310.39      6806048.14
#Sta/Elev= 30
  4750.0  411.41  4763.5  410.19  4807.3  407.58  4813.5  406.71  4907.3  400.57
  4950.0  398.59  4976.1  398.18  4976.3  397.68  4979.8  397.68  4980.1  398.18
  5021.7  398.82  5079.5  398.59  5115.0  398.44  5120.4  399.23  5191.6  399.30
  5197.1  400.82  5215.4  402.78  5220.8  404.54  5238.6  406.17  5250.0  408.52
  5268.3  409.82  5273.7  410.62  5292.1  411.48  5334.2  412.29  5345.0  412.40
  5350.4  411.63  5368.7  411.77  5375.9  411.30  5483.2  413.19  5556.3  414.36
#Mann=7,-1,0
  4750.0    0.05       0  4976.1    0.04       0  4980.1    0.05       0
  5079.5    0.12       0  5334.2     0.1       0  5375.9    0.12       0
  5483.2    0.05       0
Bank Sta=4976.1,4980.1
Exp/Cntr=0.3,0.1

Type RM Length L Ch R = 1,9175,278,278,278
BEGIN DESCRIPTION:
Clear Creek T 25 22.0
END DESCRIPTION:
XS GIS Cut Line= 3
      2752776.01      6806611.05      2752726.00      6806311.00
      2752576.01      6806161.01
#Sta/Elev= 30
  4700.1  406.62  4728.0  404.42  4750.8  403.73  4771.1  402.36  4811.7  400.39
  4842.1  399.42  4872.5  397.90  4910.3  397.03  4943.5  396.75  4953.6  396.34
  4963.7  395.31  4976.4  396.54  4984.0  396.41  4992.1  394.03  4992.4  393.53
  4995.9  393.53  4996.1  394.03  5007.8  394.21  5018.4  395.08  5032.6  396.93
  5046.7  396.51  5075.0  397.23  5089.1  397.02  5117.4  397.65  5145.7  397.62
  5159.9  397.98  5188.1  406.31  5202.3  408.43  5213.9  409.28  5216.4  409.28
#Mann=5,-1,0
  4700.1    0.05       0  4910.3    0.12       0  4992.1    0.07       0
  4996.1    0.12       0  5213.9    0.05       0
Bank Sta=4992.1,4996.1
Exp/Cntr=0.3,0.1

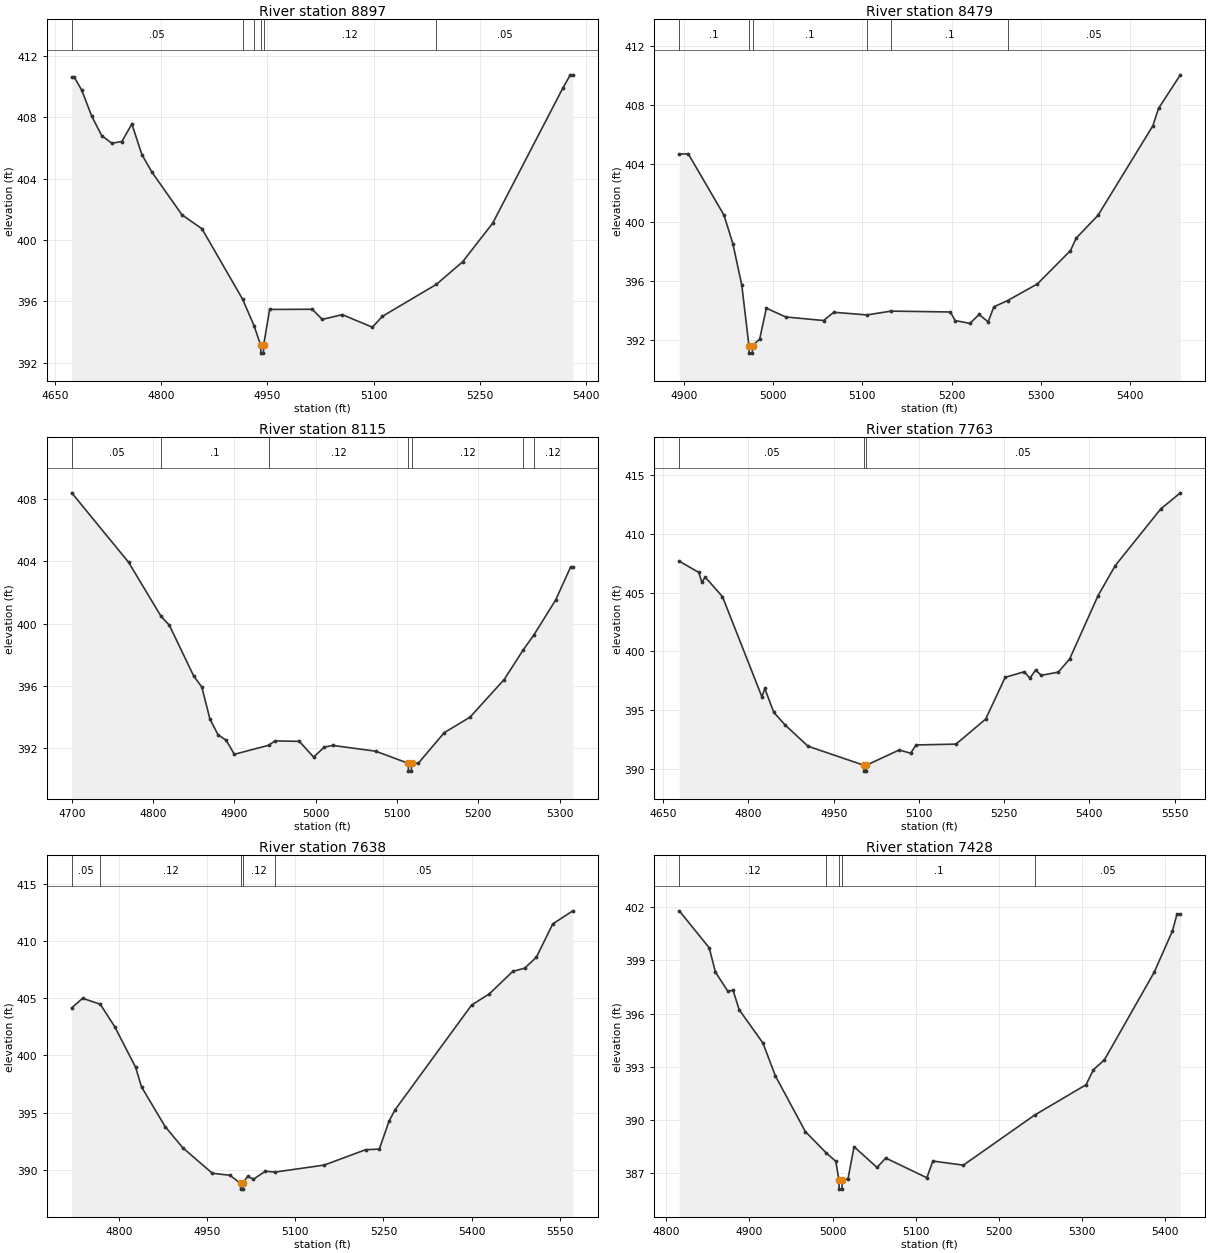
Type RM Length L Ch R = 1,8897,418,418,418
BEGIN DESCRIPTION:
Clear Creek T 25 21.0
END DESCRIPTION:
XS GIS Cut Line= 3
      2753176.00      6806411.00      2752976.00      6806211.00
      2752676.01      6805911.01
#Sta/Elev= 30
  4673.9  410.64  4677.4  410.64  4688.0  409.78  4702.2  408.08  4716.3  406.81
  4730.5  406.32  4744.6  406.43  4758.8  407.57  4772.9  405.58  4787.0  404.44
  4829.5  401.65  4857.7  400.74  4914.9  396.16  4931.3  394.41  4940.6  393.13
  4940.9  392.63  4944.4  392.63  4944.6  393.13  4953.2  395.48  5013.3  395.49
  5027.5  394.83  5055.7  395.14  5098.2  394.32  5112.3  395.03  5188.3  397.11
  5225.4  398.58  5267.9  401.10  5366.9  409.91  5377.5  410.78  5381.0  410.78
#Mann=6,-1,0
  4673.9    0.05       0  4914.9     0.1       0  4931.3    0.12       0
  4940.6    0.07       0  4944.6    0.12       0  5188.3    0.05       0
Bank Sta=4940.6,4944.6
Exp/Cntr=0.3,0.1

Type RM Length L Ch R = 1,8479,364,364,364
BEGIN DESCRIPTION:
Clear Creek T 25 20.0
END DESCRIPTION:
XS GIS Cut Line= 3
      2753275.99      6805961.00      2753176.00      6805961.00
      2752725.97      6805860.99
#Sta/Elev= 30
  4895.1  404.65  4905.1  404.68  4945.1  400.51  4955.1  398.56  4965.1  395.73
  4973.1  391.61  4973.3  391.11  4976.8  391.11  4977.1  391.61  4985.1  392.07
  4992.6  394.17  5014.3  393.57  5056.6  393.33  5068.1  393.89  5105.2  393.71
  5132.2  393.97  5198.7  393.91  5203.8  393.33  5220.5  393.13  5230.7  393.74
  5240.9  393.24  5247.3  394.26  5262.8  394.69  5296.0  395.82  5333.1  398.09
  5339.5  398.94  5363.9  400.49  5425.3  406.58  5431.7  407.77  5456.1  410.05
#Mann=6,-1,0
  4895.1     0.1       0  4973.1    0.07       0  4977.1     0.1       0
  5105.2    0.12       0  5132.2     0.1       0  5262.8    0.05       0
Bank Sta=4973.1,4977.1
Exp/Cntr=0.3,0.1

Type RM Length L Ch R = 1,8115,352,352,352
BEGIN DESCRIPTION:
Clear Creek T 25 19.0
END DESCRIPTION:
XS GIS Cut Line= 3
      2753426.05      6805661.00      2753126.00      6805661.00
      2752825.98      6805560.99
#Sta/Elev= 30
  4700.0  408.40  4770.0  403.94  4809.8  400.48  4820.0  399.91  4850.0  396.65
  4860.0  395.94  4870.0  393.88  4880.0  392.87  4890.0  392.52  4900.0  391.62
  4942.3  392.20  4950.0  392.48  4980.0  392.45  4997.5  391.44  5010.6  392.08
  5021.1  392.19  5073.8  391.82  5114.0  391.04  5114.2  390.54  5117.7  390.54
  5118.0  391.04  5126.5  391.06  5158.2  393.01  5189.8  394.00  5231.9  396.42
  5255.3  398.32  5268.3  399.27  5295.2  401.52  5313.6  403.64  5316.3  403.64
#Mann=7,-1,0
  4700.0    0.05       0  4809.8     0.1       0  4942.3    0.12       0
  5114.0    0.07       0  5118.0    0.12       0  5255.3    0.05       0
  5268.3    0.12       0
Bank Sta=5114,5118
Exp/Cntr=0.3,0.1

Type RM Length L Ch R = 1,7763,125,125,125
BEGIN DESCRIPTION:
Clear Creek T 25 18.0
END DESCRIPTION:
XS GIS Cut Line= 4
      2753391.71      6805389.41      2753076.00      6805361.00
      2752817.97      6805366.88      2752511.26      6805375.06
#Sta/Elev= 30
  4678.3  407.67  4712.7  406.71  4717.8  405.90  4724.2  406.30  4754.3  404.65
  4823.8  396.11  4828.8  396.83  4844.7  394.79  4864.8  393.71  4904.9  391.91
  5003.3  390.29  5003.5  389.79  5007.0  389.79  5007.3  390.29  5065.3  391.59
  5085.3  391.32  5095.3  392.02  5165.3  392.09  5217.5  394.22  5251.9  397.78
  5285.4  398.25  5295.4  397.71  5305.4  398.39  5315.4  397.95  5345.4  398.22
  5365.4  399.35  5415.4  404.74  5445.4  407.28  5525.5  412.11  5560.2  413.49
#Mann=3,-1,0
  4678.3    0.05       0  5003.3    0.03       0  5007.3    0.05       0
Bank Sta=5003.3,5007.3
Exp/Cntr=0.3,0.1

Type RM Length L Ch R = 1,7638,210,210,210
BEGIN DESCRIPTION:
Mapping XS 00c1a37e
END DESCRIPTION:
XS GIS Cut Line= 2
      2753374.45      6805260.84      2752524.25      6805203.92
#Sta/Elev= 30
  4720.0  404.15  4738.5  404.99  4768.6  404.47  4793.1  402.51  4828.7  398.96
  4838.7  397.25  4878.8  393.79  4908.9  391.93  4959.0  389.71  4989.1  389.53
  5007.1  388.82  5007.3  388.32  5010.8  388.32  5011.1  388.82  5019.1  389.43
  5029.1  389.19  5049.2  389.88  5065.8  389.81  5149.4  390.42  5219.6  391.76
  5243.1  391.82  5259.7  394.27  5269.7  395.24  5400.0  404.40  5430.0  405.37
  5470.1  407.34  5490.2  407.62  5510.2  408.58  5538.1  411.49  5572.1  412.63
#Mann=5,-1,0
  4720.0    0.05       0  4768.6    0.12       0  5007.1    0.07       0
  5011.1    0.12       0  5065.8    0.05       0
Bank Sta=5007.1,5011.1
Exp/Cntr=0.3,0.1

Type RM Length L Ch R = 1,7428,346,346,346
BEGIN DESCRIPTION:
Clear Creek T 25 17.0
END DESCRIPTION:
XS GIS Cut Line= 3
      2753325.98      6805160.99      2753176.00      6805061.00
      2752803.75      6804860.86
#Sta/Elev= 30
  4815.6  401.79  4851.6  399.71  4859.1  398.34  4874.2  397.25  4880.2  397.33
  4887.7  396.22  4916.2  394.35  4931.3  392.49  4967.3  389.36  4992.2  388.17
  5004.0  387.68  5007.7  386.62  5007.9  386.12  5011.4  386.12  5011.7  386.62
  5018.6  386.70  5025.9  388.51  5053.5  387.34  5064.0  387.87  5113.5  386.76
  5120.7  387.70  5157.4  387.47  5243.2  390.29  5305.1  392.00  5313.8  392.84
  5327.0  393.39  5387.0  398.33  5409.0  400.66  5414.4  401.60  5418.5  401.60
#Mann=5,-1,0
  4815.6    0.12       0  4992.2     0.1       0  5007.7    0.07       0
  5011.7     0.1       0  5243.2    0.05       0
Bank Sta=5007.7,5011.7
Exp/Cntr=0.3,0.1

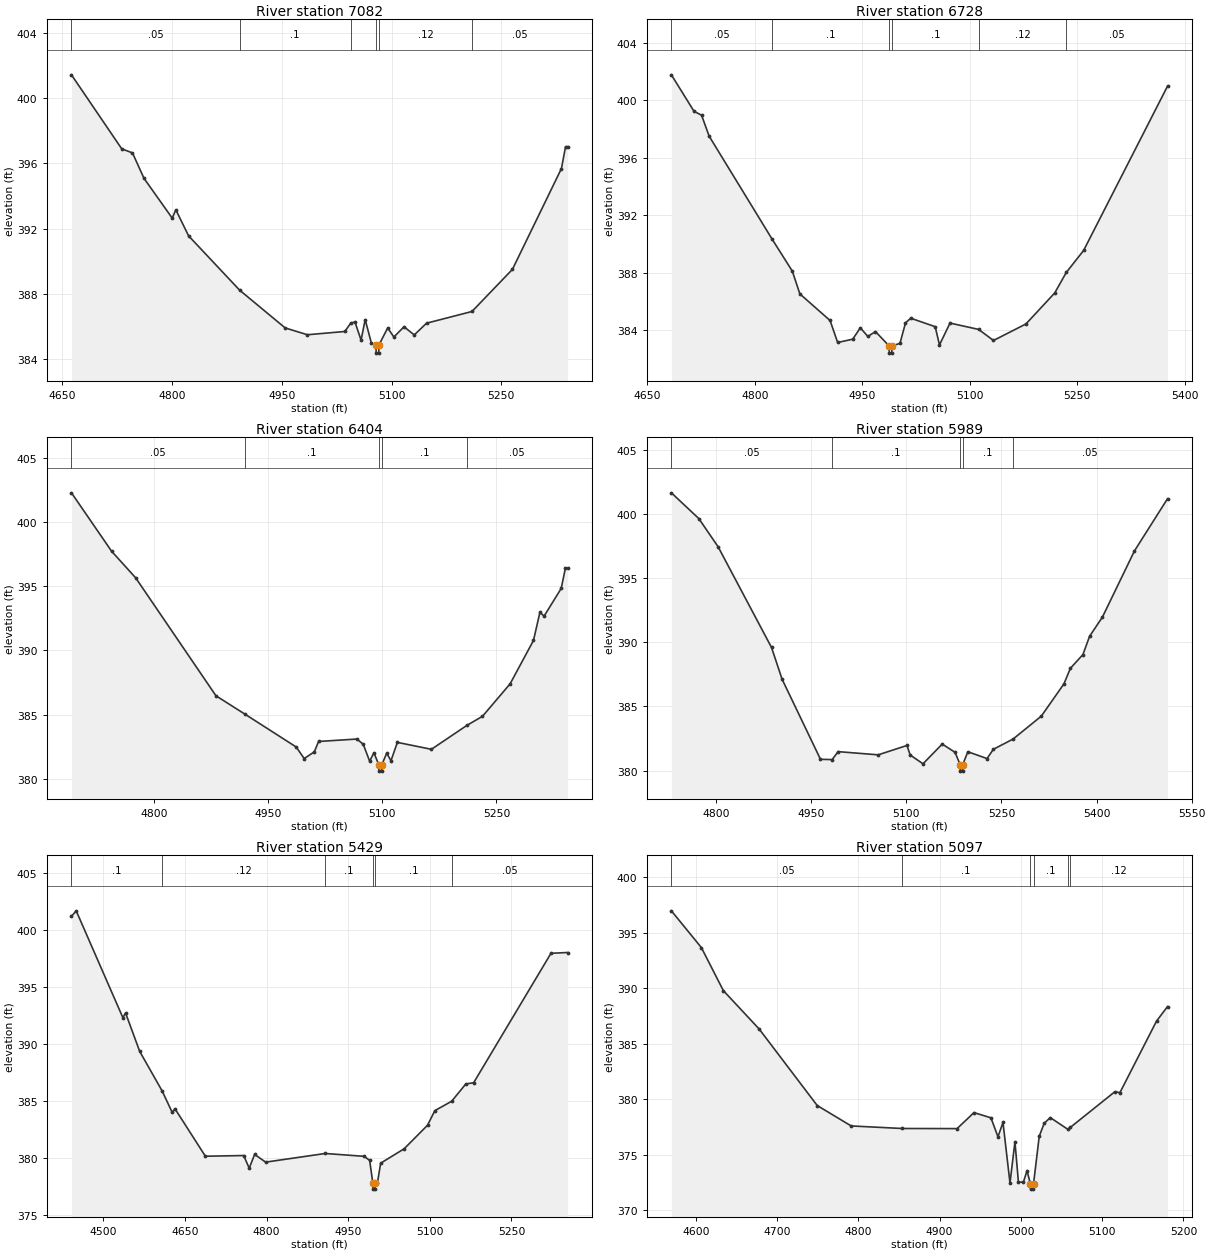
Type RM Length L Ch R = 1,7082,354,354,354
BEGIN DESCRIPTION:
Clear Creek T 25 16.0
END DESCRIPTION:
XS GIS Cut Line= 3
      2753563.65      6804820.35      2753226.00      6804761.00
      2752926.03      6804611.01
#Sta/Elev= 30
  4662.5  401.45  4731.2  396.90  4745.9  396.65  4761.6  395.09  4800.2  392.64
  4805.2  393.15  4822.6  391.55  4892.4  388.21  4954.6  385.89  4985.0  385.47
  5036.1  385.67  5044.1  386.17  5050.0  386.26  5058.4  385.14  5064.0  386.40
  5072.4  384.97  5078.8  384.84  5079.0  384.34  5082.5  384.34  5082.8  384.84
  5094.8  385.89  5103.2  385.33  5117.1  385.96  5131.1  385.46  5147.9  386.18
  5210.0  386.90  5265.3  389.49  5332.3  395.69  5337.9  397.03  5340.7  397.03
#Mann=6,-1,0
  4662.5    0.05       0  4892.4     0.1       0  5044.1    0.12       0
  5078.8    0.07       0  5082.8    0.12       0  5210.0    0.05       0
Bank Sta=5078.8,5082.8
Exp/Cntr=0.3,0.1

Type RM Length L Ch R = 1,6728,324,324,324
BEGIN DESCRIPTION:
Clear Creek T 25 15.0
END DESCRIPTION:
XS GIS Cut Line= 3
      2753575.97      6804560.99      2753276.00      6804461.00
      2752912.84      6804364.73
#Sta/Elev= 30
  4683.8  401.77  4715.4  399.23  4725.9  398.96  4736.5  397.50  4824.5  390.32
  4852.4  388.12  4863.0  386.53  4905.1  384.68  4915.7  383.15  4936.7  383.38
  4947.3  384.17  4957.8  383.57  4968.4  383.91  4987.5  382.91  4987.7  382.41
  4991.2  382.41  4991.5  382.91  5002.6  383.09  5010.3  384.51  5017.5  384.84
  5051.7  384.25  5057.7  382.98  5072.4  384.50  5112.3  384.06  5133.0  383.29
  5178.3  384.44  5218.5  386.60  5234.5  388.02  5258.7  389.55  5375.7  400.98
#Mann=6,-1,0
  4683.8    0.05       0  4824.5     0.1       0  4987.5    0.07       0
  4991.5     0.1       0  5112.3    0.12       0  5234.5    0.05       0
Bank Sta=4987.5,4991.5
Exp/Cntr=0.3,0.1

Type RM Length L Ch R = 1,6404,415,415,415
BEGIN DESCRIPTION:
Clear Creek T 25 14.0
END DESCRIPTION:
XS GIS Cut Line= 3
      2753676.02      6804311.01      2753376.00      6804211.00
      2753075.96      6804060.98
#Sta/Elev= 30
  4691.7  402.28  4744.4  397.73  4776.0  395.66  4881.5  386.47  4919.8  385.03
  4986.9  382.48  4997.4  381.58  5010.7  382.10  5016.3  382.91  5066.6  383.10
  5075.0  382.69  5083.4  381.37  5089.0  382.03  5095.4  381.10  5095.6  380.60
  5099.1  380.60  5099.4  381.10  5105.8  382.00  5111.4  381.41  5119.8  382.84
  5164.5  382.30  5211.3  384.17  5231.6  384.87  5267.9  387.40  5298.6  390.78
  5307.0  392.96  5312.6  392.68  5335.0  394.83  5340.6  396.43  5343.4  396.43
#Mann=5,-1,0
  4691.7    0.05       0  4919.8     0.1       0  5095.4    0.07       0
  5099.4     0.1       0  5211.3    0.05       0
Bank Sta=5095.4,5099.4
Exp/Cntr=0.3,0.1

Type RM Length L Ch R = 1,5989,560,560,560
BEGIN DESCRIPTION:
Clear Creek T 25 13.0
END DESCRIPTION:
XS GIS Cut Line= 3
      2753788.86      6803897.53      2753526.00      6803861.00
      2753014.40      6803934.22
#Sta/Elev= 30
  4729.7  401.66  4773.0  399.65  4803.3  397.46  4887.6  389.60  4904.2  387.13
  4964.8  380.88  4983.2  380.86  4992.6  381.48  5055.7  381.23  5101.1  381.96
  5106.2  381.22  5126.4  380.53  5156.7  382.07  5176.9  381.43  5185.0  380.46
  5185.3  379.96  5188.8  379.96  5189.0  380.46  5197.1  381.47  5227.4  380.94
  5237.3  381.66  5268.4  382.46  5313.0  384.25  5348.7  386.77  5358.8  387.98
  5378.6  389.05  5389.1  390.48  5409.3  391.97  5459.8  397.13  5511.9  401.20
#Mann=5,-1,0
  4729.7    0.05       0  4983.2     0.1       0  5185.0    0.07       0
  5189.0     0.1       0  5268.4    0.05       0
Bank Sta=5185,5189
Exp/Cntr=0.3,0.1

Type RM Length L Ch R = 1,5429,332,332,332
BEGIN DESCRIPTION:
Clear Creek T 25 12.0
END DESCRIPTION:
XS GIS Cut Line= 3
      2753730.49      6803515.13      2753175.59      6803576.58
      2752951.69      6803849.62
#Sta/Elev= 30
  4441.7  401.22  4450.4  401.70  4536.1  392.32  4541.1  392.73  4567.0  389.36
  4608.4  385.87  4626.8  383.99  4631.8  384.32  4687.7  380.15  4758.1  380.21
  4768.2  379.10  4778.2  380.31  4798.4  379.63  4907.9  380.39  4979.5  380.14
  4989.5  379.78  4995.4  377.76  4995.6  377.26  4999.1  377.26  4999.4  377.76
  5003.6  377.76  5009.7  379.54  5052.8  380.80  5095.8  382.87  5109.2  384.15
  5140.2  384.98  5166.2  386.50  5180.5  386.60  5322.6  397.97  5353.1  398.04
#Mann=6,-1,0
  4441.7     0.1       0  4608.4    0.12       0  4907.9     0.1       0
  4995.4    0.07       0  4999.4     0.1       0  5140.2    0.05       0
Bank Sta=4995.4,4999.4
Exp/Cntr=0.3,0.1

Type RM Length L Ch R = 1,5097,479,479,479
BEGIN DESCRIPTION:
Clear Creek T 25 11.0
END DESCRIPTION:
XS GIS Cut Line= 3
      2753475.99      6803011.01      2753126.00      6803261.00
      2752975.99      6803361.01
#Sta/Elev= 30
  4570.0  396.97  4606.9  393.66  4633.9  389.79  4678.1  386.32  4749.4  379.44
  4791.2  377.60  4853.9  377.37  4921.5  377.36  4942.3  378.80  4963.2  378.33
  4971.8  376.62  4978.0  377.91  4986.6  372.47  4992.7  376.17  4997.0  372.54
  5003.1  372.54  5007.6  373.57  5011.6  372.41  5011.9  371.91  5015.4  371.91
  5015.6  372.41  5022.6  376.67  5028.7  377.84  5036.2  378.35  5057.9  377.29
  5060.7  377.46  5115.8  380.69  5121.8  380.59  5166.9  387.04  5180.4  388.35
#Mann=6,-1,0
  4570.0    0.05       0  4853.9     0.1       0  5011.6    0.07       0
  5015.6     0.1       0  5057.9    0.05       0  5060.7    0.12       0
Bank Sta=5011.6,5015.6
Exp/Cntr=0.3,0.1

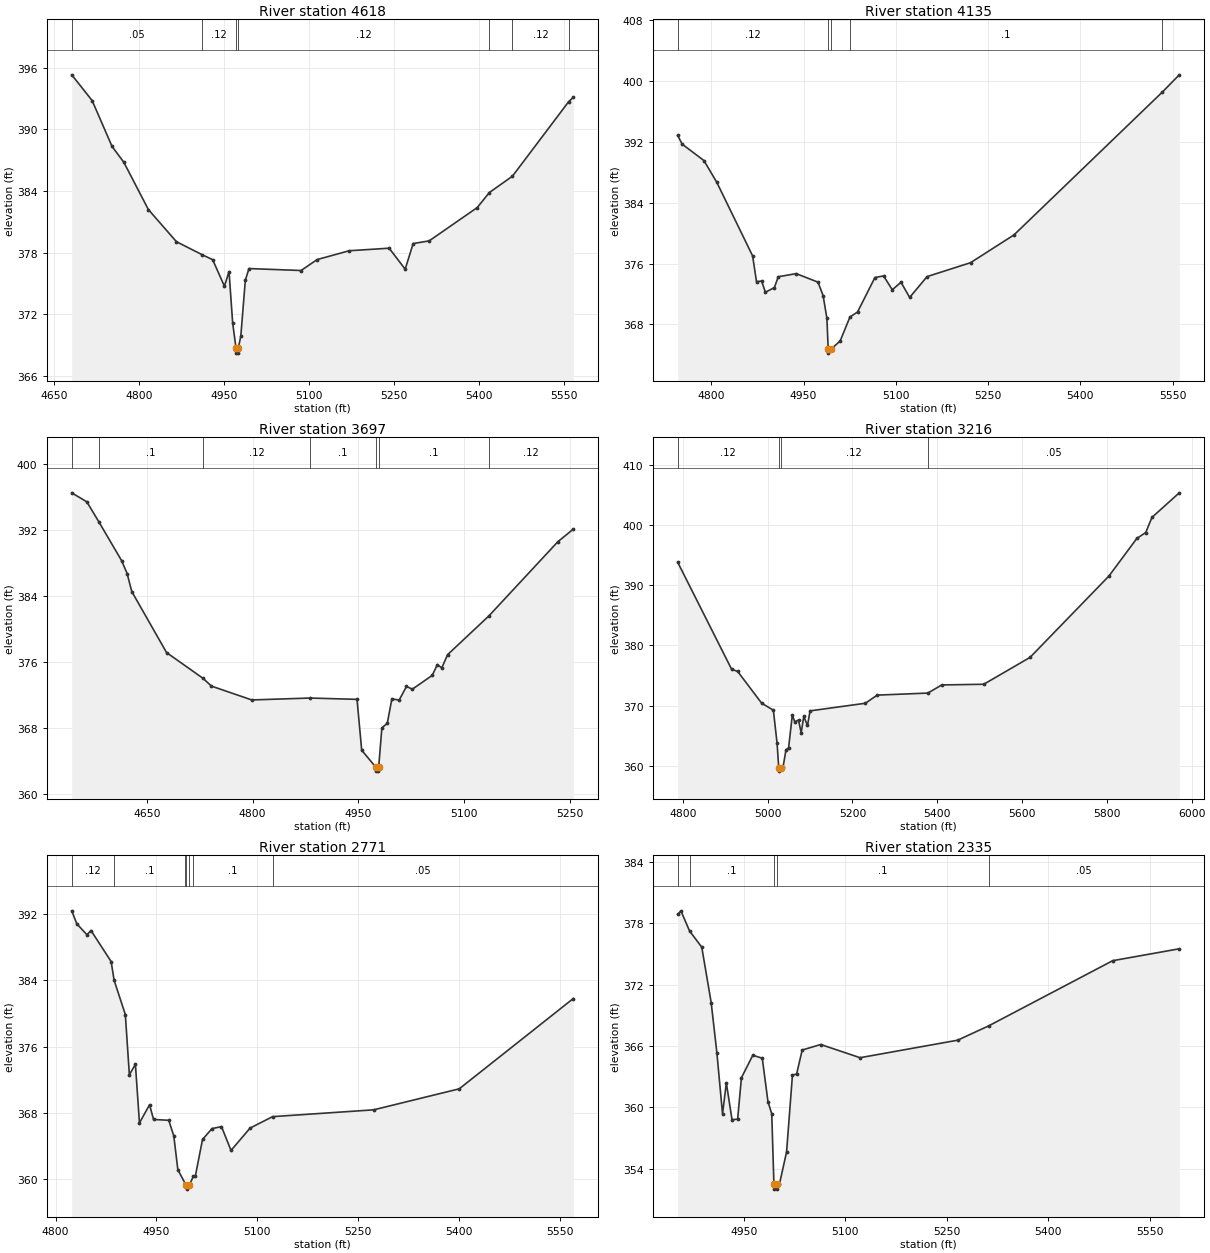
Type RM Length L Ch R = 1,4618,483,483,483
BEGIN DESCRIPTION:
Clear Creek T 25 10.0
END DESCRIPTION:
XS GIS Cut Line= 3
      2753176.01      6802610.99      2752976.00      6802861.00
      2752575.97      6803261.03
#Sta/Elev= 30
  4680.6  395.29  4716.6  392.79  4751.8  388.33  4772.7  386.78  4815.9  382.20
  4865.5  379.07  4910.8  377.81  4929.5  377.32  4950.3  374.74  4958.4  376.17
  4964.8  371.18  4970.7  368.74  4971.0  368.24  4974.5  368.24  4974.8  368.74
  4979.2  369.89  4987.2  375.33  4993.6  376.46  5085.6  376.27  5113.9  377.33
  5170.5  378.19  5241.2  378.44  5269.5  376.40  5283.6  378.89  5311.9  379.15
  5396.8  382.39  5418.2  383.85  5459.0  385.44  5558.4  392.69  5566.5  393.10
#Mann=7,-1,0
  4680.6    0.05       0  4910.8    0.12       0  4970.7    0.07       0
  4974.8    0.12       0  5418.2     0.1       0  5459.0    0.12       0
  5558.4     0.1       0
Bank Sta=4970.7,4974.8
Exp/Cntr=0.3,0.1

Type RM Length L Ch R = 1,4135,438,438,438
BEGIN DESCRIPTION:
Clear Creek T 25 9.0
END DESCRIPTION:
XS GIS Cut Line= 3
      2752876.03      6802460.98      2752676.00      6802611.00
      2752276.02      6803010.98
#Sta/Elev= 30
  4745.2  392.85  4752.5  391.71  4787.9  389.55  4808.8  386.69  4867.1  377.00
  4873.4  373.61  4881.7  373.70  4887.9  372.22  4902.5  372.84  4908.8  374.26
  4937.9  374.67  4973.4  373.55  4981.7  371.79  4987.9  368.79  4990.0  364.71
  4990.3  364.21  4994.2  364.71  5009.4  365.80  5025.4  368.97  5037.7  369.62
  5066.0  374.16  5080.1  374.37  5094.2  372.55  5108.4  373.53  5122.5  371.54
  5150.8  374.28  5221.5  376.11  5292.2  379.77  5533.4  398.56  5560.9  400.83
#Mann=5,-1,0
  4745.2    0.12       0  4990.0    0.07       0  4994.2    0.12       0
  5025.4     0.1       0  5533.4    0.05       0
Bank Sta=4990,4994.2
Exp/Cntr=0.3,0.1

Type RM Length L Ch R = 1,3697,481,481,481
BEGIN DESCRIPTION:
Clear Creek T 25 8.0
END DESCRIPTION:
XS GIS Cut Line= 3
      2752626.00      6802061.00      2752326.00      6802411.00
      2752125.98      6802561.02
#Sta/Elev= 30
  4543.7  396.46  4565.1  395.37  4582.0  392.97  4614.5  388.24  4622.2  386.70
  4628.8  384.52  4678.1  377.14  4729.7  374.03  4741.8  373.08  4798.9  371.41
  4881.7  371.64  4948.1  371.48  4954.7  365.33  4974.5  363.30  4974.9  362.80
  4978.5  362.80  4978.8  363.30  4983.3  368.02  4991.0  368.59  4997.5  371.54
  5007.8  371.39  5018.2  373.04  5026.5  372.71  5054.7  374.38  5062.0  375.69
  5068.2  375.28  5076.5  376.89  5135.1  381.58  5232.8  390.55  5254.7  392.07
#Mann=7,-1,0
  4543.7    0.05       0  4582.0     0.1       0  4729.7    0.12       0
  4881.7     0.1       0  4974.5    0.07       0  4978.8     0.1       0
  5135.1    0.12       0
Bank Sta=4974.5,4978.8
Exp/Cntr=0.3,0.1

Type RM Length L Ch R = 1,3216,445,445,445
BEGIN DESCRIPTION:
Clear Creek T 25 7.0
END DESCRIPTION:
XS GIS Cut Line= 3
      2752376.04      6801810.96      2752226.00      6801961.00
      2751426.01      6802511.00
#Sta/Elev= 30
  4787.8  393.81  4915.1  376.04  4929.3  375.69  4985.8  370.43  5013.5  369.26
  5022.3  363.76  5026.2  359.65  5026.6  359.15  5030.5  359.65  5036.4  359.85
  5043.3  362.69  5049.4  363.01  5058.2  368.44  5064.2  367.31  5072.8  367.63
  5079.1  365.50  5085.2  368.22  5094.0  366.72  5100.1  369.15  5230.6  370.41
  5258.4  371.76  5377.9  372.10  5410.7  373.45  5509.7  373.56  5618.9  378.02
  5805.0  391.52  5870.7  397.75  5891.7  398.73  5906.5  401.25  5970.8  405.32
#Mann=4,-1,0
  4787.8    0.12       0  5026.2    0.07       0  5030.5    0.12       0
  5377.9    0.05       0
Bank Sta=5026.2,5030.5
Exp/Cntr=0.3,0.1

Type RM Length L Ch R = 1,2771,436,436,436
BEGIN DESCRIPTION:
Clear Creek T 25 6.0
END DESCRIPTION:
XS GIS Cut Line= 3
      2752026.02      6801560.97      2751926.00      6801711.00
      2751526.00      6802111.00
#Sta/Elev= 30
  4824.0  392.36  4831.5  390.80  4846.6  389.48  4852.6  389.99  4882.6  386.25
  4887.0  384.00  4903.7  379.87  4909.7  372.62  4918.7  373.87  4924.7  366.81
  4939.7  369.00  4945.7  367.23  4968.3  367.13  4975.8  365.24  4981.8  361.19
  4993.1  359.45  4994.4  359.34  4994.9  358.84  4999.1  359.34  5004.9  360.40
  5007.8  360.40  5018.5  364.82  5032.6  366.13  5046.7  366.37  5060.9  363.50
  5089.2  366.19  5122.7  367.57  5273.0  368.39  5400.3  370.92  5570.0  381.80
#Mann=7,-1,0
  4824.0    0.12       0  4887.0     0.1       0  4993.1    0.12       0
  4994.4    0.07       0  4999.1    0.12       0  5004.9     0.1       0
  5122.7    0.05       0
Bank Sta=4994.4,4999.1
Exp/Cntr=0.3,0.1

Type RM Length L Ch R = 1,2335,499,499,499
BEGIN DESCRIPTION:
Clear Creek T 25 5.0
END DESCRIPTION:
XS GIS Cut Line= 3
      2751857.84      6801395.17      2751726.00      6801461.00
      2751240.04      6801802.12
#Sta/Elev= 30
  4852.5  378.86  4857.3  379.21  4870.0  377.25  4888.1  375.66  4902.0  370.25
  4910.4  365.36  4918.8  359.36  4924.4  362.40  4932.8  358.81  4941.1  358.85
  4946.7  362.90  4963.5  365.10  4977.5  364.81  4985.9  360.57  4991.5  359.38
  4994.7  352.52  4995.2  352.02  4998.9  352.02  4999.4  352.52  5002.9  352.52
  5013.4  355.65  5022.1  363.18  5028.2  363.25  5036.5  365.61  5063.9  366.15
  5122.0  364.86  5266.1  366.57  5312.0  367.97  5495.3  374.34  5593.6  375.50
#Mann=5,-1,0
  4852.5    0.12       0  4870.0     0.1       0  4994.7    0.07       0
  4999.4     0.1       0  5312.0    0.05       0
Bank Sta=4994.7,4999.4
Exp/Cntr=0.3,0.1