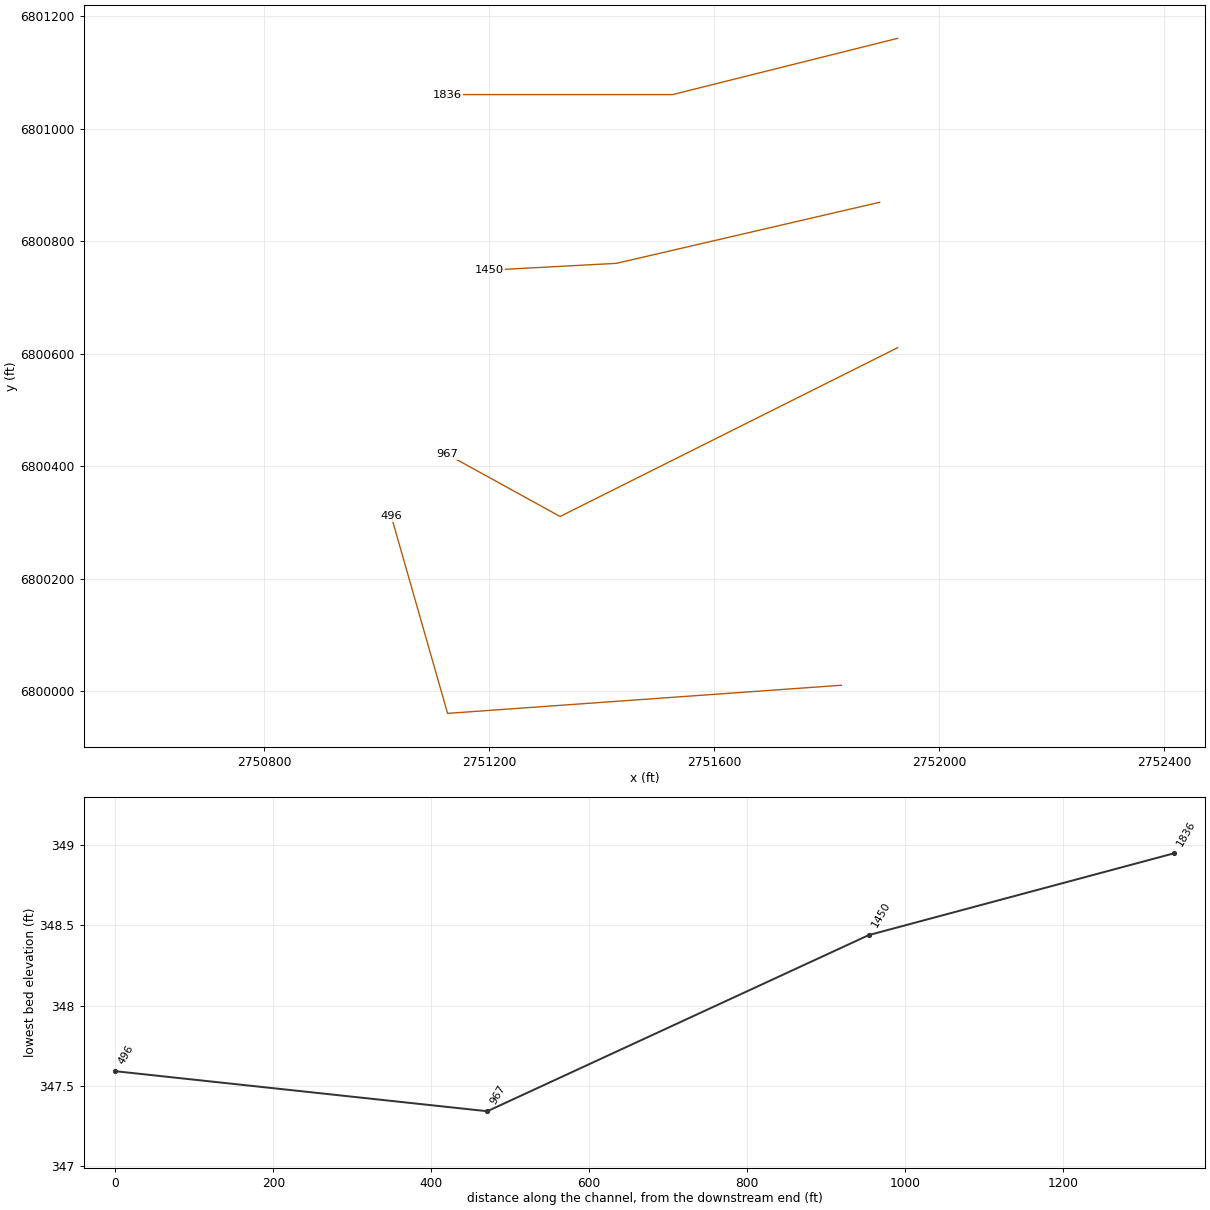
HEC-RAS study Clear Creek T 25.prj: Clear Creek T 25 Base Level Engineering

--- Clear Creek T 25.g01 (geometry) --- (continued)

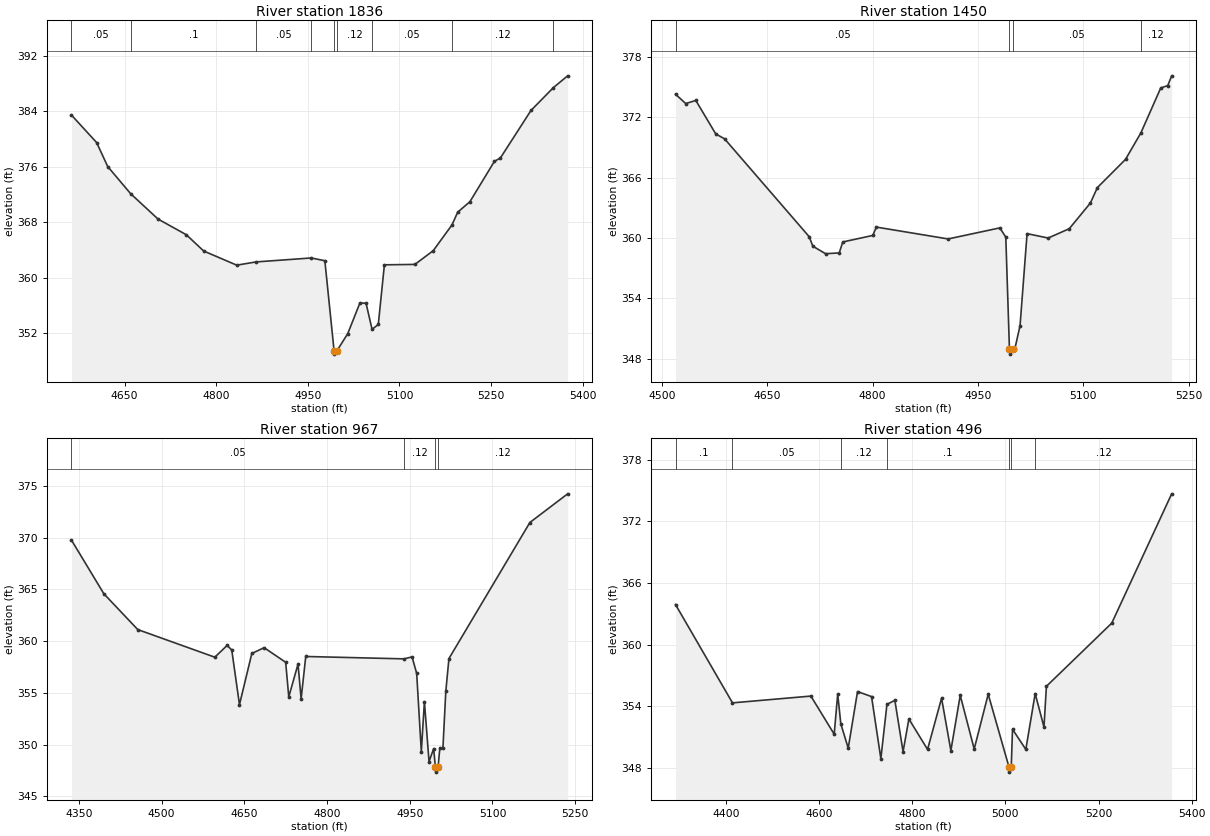
Type RM Length L Ch R = 1,1836,386,386,386
BEGIN DESCRIPTION:
Clear Creek T 25 4.0
END DESCRIPTION:
XS GIS Cut Line= 3
      2751925.99      6801161.00      2751526.00      6801061.00
      2751126.00      6801061.00
#Sta/Elev= 30
  4563.0  383.48  4604.2  379.51  4622.3  376.05  4659.9  372.12  4704.7  368.46
  4751.1  366.19  4779.5  363.84  4833.6  361.80  4865.2  362.27  4955.6  362.84
  4977.8  362.44  4992.9  349.45  4993.5  348.95  4997.7  349.45  5015.3  351.91
  5035.3  356.36  5045.3  356.29  5055.1  352.53  5065.3  353.23  5075.3  361.85
  5125.3  361.91  5155.3  363.90  5185.9  367.61  5195.3  369.45  5215.3  370.97
  5255.3  376.78  5265.3  377.30  5315.3  384.15  5352.0  387.45  5375.3  389.15
#Mann=9,-1,0
  4563.0    0.05       0  4659.9     0.1       0  4865.2    0.05       0
  4955.6    0.12       0  4992.9    0.07       0  4997.7    0.12       0
  5055.1    0.05       0  5185.9    0.12       0  5352.0    0.05       0
Bank Sta=4992.9,4997.7
Exp/Cntr=0.3,0.1

Type RM Length L Ch R = 1,1450,483,483,483
BEGIN DESCRIPTION:
Clear Creek T 25 3.0
END DESCRIPTION:
XS GIS Cut Line= 3
      2751894.13      6800869.56      2751426.00      6800761.00
      2751200.38      6800748.92
#Sta/Elev= 30
  4519.4  374.30  4534.0  373.37  4548.3  373.68  4576.7  370.35  4589.3  369.86
  4709.8  360.12  4714.9  359.18  4733.1  358.43  4752.5  358.51  4757.6  359.60
  4800.3  360.25  4805.4  361.08  4907.6  359.90  4981.2  361.00  4989.7  360.08
  4994.9  348.94  4995.5  348.44  4999.8  348.94  5002.5  348.94  5010.0  351.27
  5020.0  360.43  5050.0  359.99  5080.1  360.92  5110.1  363.47  5120.1  365.01
  5160.2  367.82  5182.1  370.46  5210.3  374.92  5220.3  375.16  5225.9  376.13
#Mann=4,-1,0
  4519.4    0.05       0  4994.9    0.04       0  4999.8    0.05       0
  5182.1    0.12       0
Bank Sta=4994.9,4999.8
Exp/Cntr=0.3,0.1

Type RM Length L Ch R = 1,967,471,471,471
BEGIN DESCRIPTION:
Clear Creek T 25 2.0
END DESCRIPTION:
XS GIS Cut Line= 3
      2751926.02      6800611.01      2751326.00      6800311.00
      2751125.36      6800421.49
#Sta/Elev= 30
  4336.4  369.75  4395.1  364.57  4456.6  361.11  4596.4  358.44  4618.7  359.58
  4627.1  359.14  4641.1  353.86  4663.5  358.80  4685.8  359.36  4724.9  357.95
  4730.5  354.61  4747.3  357.77  4752.9  354.41  4761.3  358.51  4939.7  358.28
  4954.1  358.47  4962.5  356.87  4970.9  349.33  4976.5  354.15  4984.9  348.36
  4993.3  349.61  4996.4  347.84  4997.0  347.34  5001.3  347.84  5004.5  349.66
  5010.1  349.66  5015.3  355.13  5021.0  358.31  5167.8  371.45  5236.3  374.22
#Mann=4,-1,0
  4336.4    0.05       0  4939.7    0.12       0  4996.4    0.07       0
  5001.3    0.12       0
Bank Sta=4996.4,5001.3
Exp/Cntr=0.3,0.1

Type RM Length L Ch R = 1,496,0,0,0
BEGIN DESCRIPTION:
Clear Creek T 25 1.0
END DESCRIPTION:
XS GIS Cut Line= 3
      2751826.02      6800011.00      2751126.00      6799961.00
      2751026.00      6800310.99
#Sta/Elev= 30
  4291.3  363.90  4413.7  354.33  4582.1  354.99  4632.2  351.28  4639.7  355.19
  4646.4  352.29  4662.3  349.92  4682.3  355.43  4712.4  354.94  4732.4  348.90
  4745.5  354.19  4762.5  354.57  4780.1  349.58  4792.6  352.76  4832.7  349.80
  4862.8  354.78  4882.8  349.69  4902.9  355.06  4932.9  349.84  4963.0  355.17
  5007.6  348.09  5008.2  347.59  5012.5  348.09  5015.2  351.76  5043.8  349.80
  5063.9  355.23  5082.8  351.97  5088.0  355.94  5228.4  362.09  5357.1  374.67
#Mann=7,-1,0
  4291.3     0.1       0  4413.7    0.05       0  4646.4    0.12       0
  4745.5     0.1       0  5007.6    0.07       0  5012.5     0.1       0
  5063.9    0.12       0
Bank Sta=5007.6,5012.5
Exp/Cntr=0.3,0.1

Chan Stop Cuts=-1