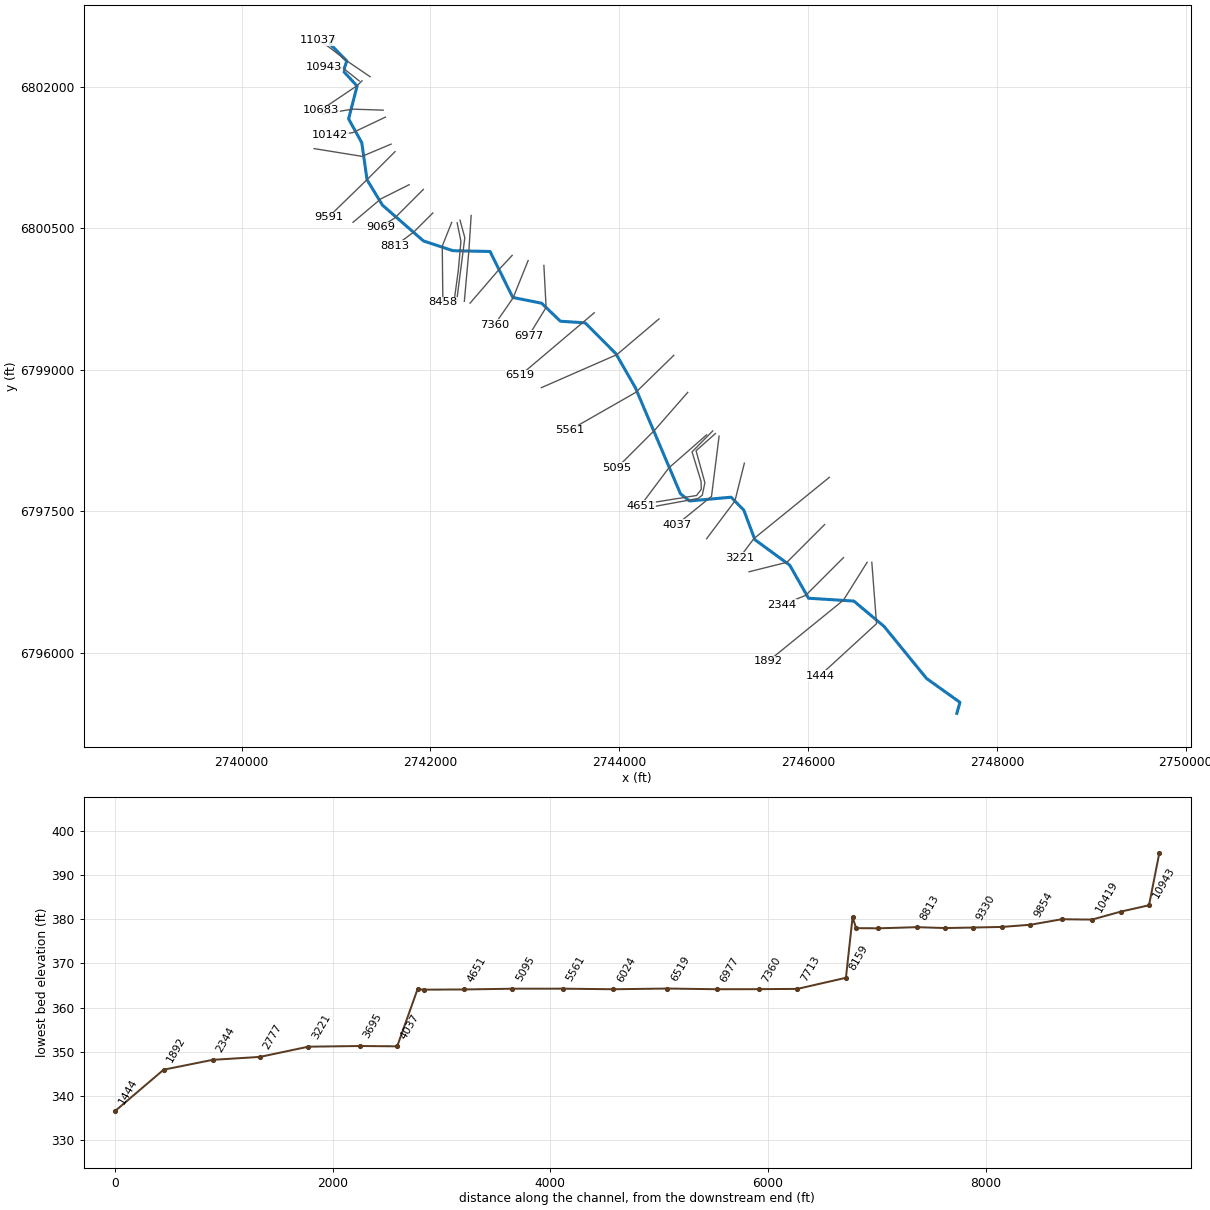
--- Clear Creek T 26.prj (project) ---

Proj Title=Clear Creek T 26 Base Level Engineering
Current Plan=p01
Default Exp/Contr=0.3,0.1
English Units
Geom File=g01
Flow File=f01
Plan File=p01
BEGIN DESCRIPTION:
Clear Creek T 26
END DESCRIPTION:

--- Clear Creek T 26.p01 (plan) ---

Plan Title=Multiple Run
Short Identifier=Multiple
Geom File=g01
Flow File=f01
Subcritical Flow
K Sum by GR= 0
Std Step Tol= 0.01
Critical Tol= 0.01
Num of Std Step Trials= 20
Max Error Tol= 0.3
Flow Tol Ratio= 0.001
Split Flow NTrial= 30
Split Flow Tol= 0.02
Split Flow Ratio= 0.02
Log Output Level= 0
Friction Slope Method= 1
Unsteady Friction Slope Method= 2
Unsteady Bridges Friction Slope Method= 1
Parabolic Critical Depth
Global Vel Dist=  1 , 1 , 1
Global Log Level= 0
CheckData=True
Encroach Param= -1, 0, 0, 0
BEGIN DESCRIPTION:
Multiple Run
END DESCRIPTION:

--- Clear Creek T 26.f01 (steady flow) ---

Flow Title=Multiple
Number of Profiles=7
Profile Names=10-year,25-year,50-year,1pct_min,100-year,1pct_plu,500-year
River Rch & RM= Clear Creek T 26,Reach-1,11037
     357     470     561     333     665    1328     937
River Rch & RM= Clear Creek T 26,Reach-1,8458
     701     953    1159     700    1396    2786    2025
River Rch & RM= Clear Creek T 26,Reach-1,6519
     992    1373    1692    1034    2063    4117    3079
Boundary for River Rch & Prof#=Clear Creek T 26,Reach-1,1
Up Type=0
Dn Type=3
Dn Slope=0.005
Boundary for River Rch & Prof#=Clear Creek T 26,Reach-1,2
Up Type=0
Dn Type=3
Dn Slope=0.005
Boundary for River Rch & Prof#=Clear Creek T 26,Reach-1,3
Up Type=0
Dn Type=3
Dn Slope=0.005
Boundary for River Rch & Prof#=Clear Creek T 26,Reach-1,4
Up Type=0
Dn Type=3
Dn Slope=0.005
Boundary for River Rch & Prof#=Clear Creek T 26,Reach-1,5
Up Type=0
Dn Type=3
Dn Slope=0.005
Boundary for River Rch & Prof#=Clear Creek T 26,Reach-1,6
Up Type=0
Dn Type=3
Dn Slope=0.005
Boundary for River Rch & Prof#=Clear Creek T 26,Reach-1,7
Up Type=0
Dn Type=3
Dn Slope=0.005

--- Clear Creek T 26.g01 (geometry) ---

Geom Title=Existing Conditions

River Reach=Clear Creek T 26,Reach-1
Reach XY= 30
      2740976.00      6802511.00      2740934.77      6802454.33
      2741114.89      6802271.05      2741079.36      6802162.71
      2741224.00      6802005.32      2741134.05      6801657.71
      2741273.82      6801405.55      2741329.61      6801012.50
      2741492.46      6800744.25      2741927.50      6800364.61
      2742239.92      6800261.68      2742632.48      6800253.31
      2742873.27      6799766.35      2743178.43      6799705.48
      2743377.46      6799514.53      2743639.27      6799497.53
      2743965.24      6799170.68      2744170.15      6798813.29
      2744648.99      6797687.48      2744744.21      6797611.09
      2745185.80      6797650.53      2745320.53      6797513.45
      2745436.78      6797201.32      2745806.18      6796930.97
      2746005.79      6796580.58      2746485.80      6796550.52
      2746806.37      6796281.47      2747255.57      6795730.73
      2747609.78      6795477.73      2747576.00      6795361.00

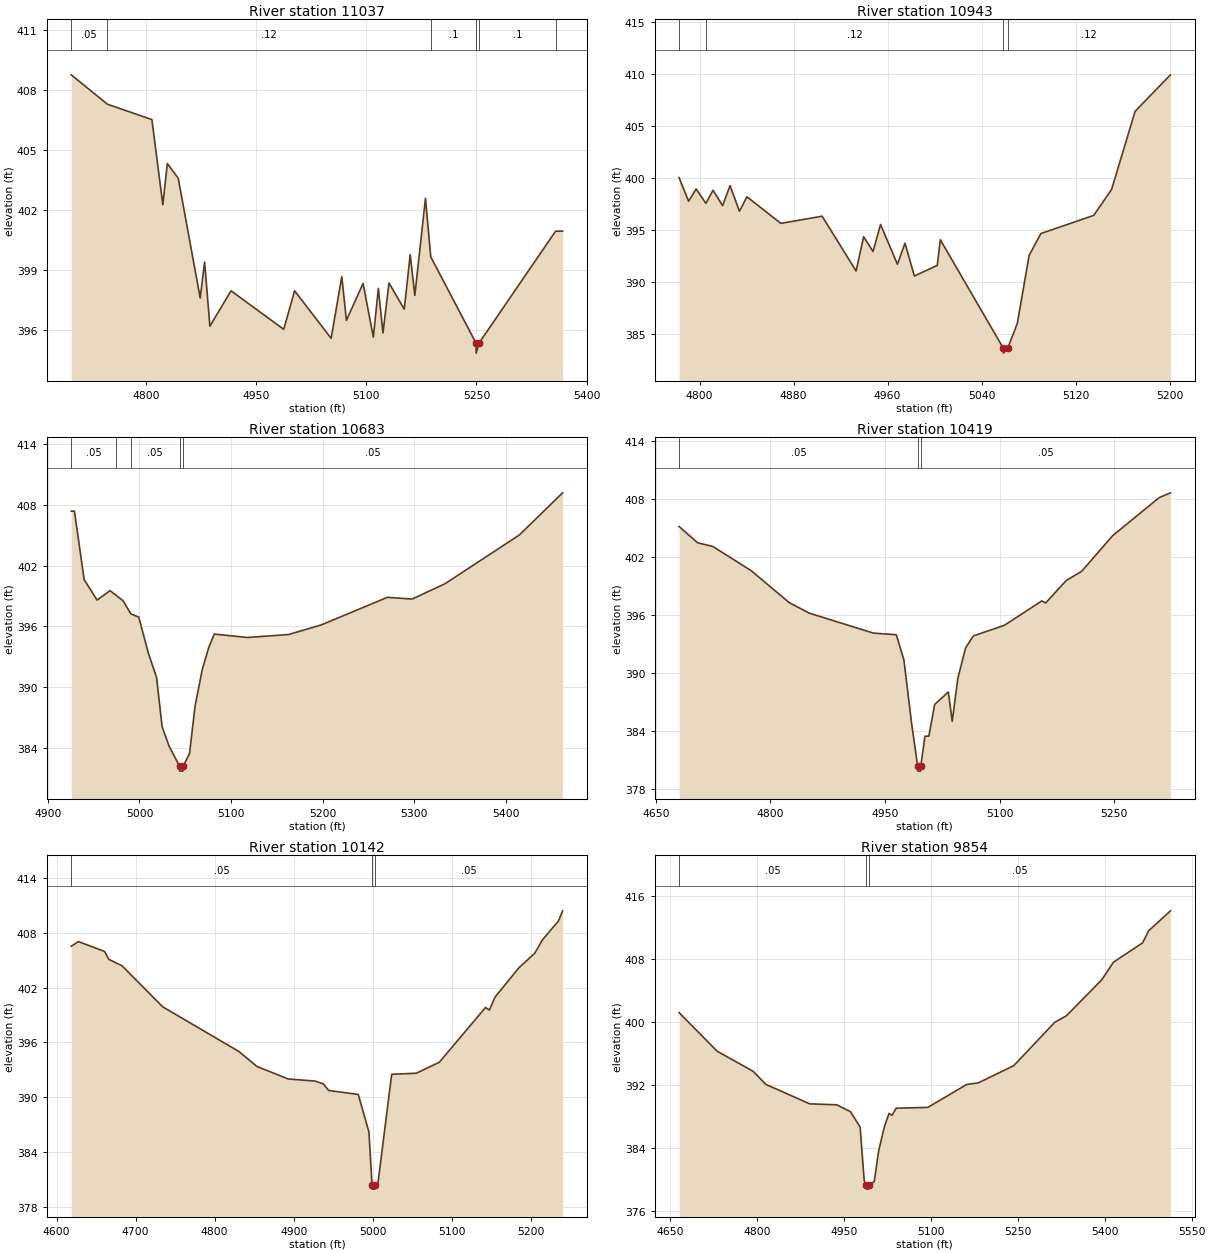
Type RM Length L Ch R = 1,11037,94,94,94
BEGIN DESCRIPTION:
Clear Creek T 26 27.0
END DESCRIPTION:
XS GIS Cut Line= 4
      2741362.20      6802104.40      2741112.46      6802274.38
      2740926.73      6802418.73      2740814.77      6802488.79
#Sta/Elev= 30
  4697.9  408.78  4747.1  407.31  4807.8  406.54  4822.7  402.28  4828.8  404.34
  4843.7  403.60  4873.6  397.61  4879.6  399.41  4886.8  396.20  4915.6  397.97
  4987.4  396.04  5002.2  397.97  5052.0  395.59  5066.5  398.68  5072.8  396.49
  5095.5  398.34  5109.5  395.65  5116.3  398.09  5122.6  395.86  5130.8  398.36
  5151.6  397.05  5159.7  399.78  5166.0  397.74  5180.5  402.60  5187.7  399.67
  5249.4  395.35  5249.6  394.85  5253.4  395.35  5357.7  400.95  5367.3  400.96
#Mann=6,-1,0
  4697.9    0.05       0  4747.1    0.12       0  5187.7     0.1       0
  5249.4    0.07       0  5253.4     0.1       0  5357.7    0.12       0
Bank Sta=5249.4,5253.4
Exp/Cntr=0.3,0.1

Type RM Length L Ch R = 1,10943,260,260,260
BEGIN DESCRIPTION:
Clear Creek T 26 26.0
END DESCRIPTION:
XS GIS Cut Line= 3
      2741246.31      6802060.09      2741076.23      6802195.66
      2740876.01      6802211.00
#Sta/Elev= 30
  4782.5  400.04  4790.6  397.76  4797.0  398.95  4805.3  397.56  4811.4  398.82
  4819.5  397.34  4825.9  399.27  4833.9  396.80  4840.3  398.19  4869.1  395.63
  4904.3  396.32  4933.2  391.04  4939.6  394.34  4947.6  392.92  4954.0  395.52
  4968.4  391.69  4974.8  393.72  4982.8  390.56  5002.3  391.58  5004.9  394.05
  5058.4  383.63  5058.7  383.13  5062.4  383.63  5070.4  385.98  5080.5  392.54
  5090.5  394.65  5135.5  396.40  5150.7  398.90  5170.7  406.42  5200.8  409.94
#Mann=4,-1,0
  4782.5    0.05       0  4805.3    0.12       0  5058.4    0.07       0
  5062.4    0.12       0
Bank Sta=5058.4,5062.4
Exp/Cntr=0.3,0.1

Type RM Length L Ch R = 1,10683,264,264,264
BEGIN DESCRIPTION:
Clear Creek T 26 25.0
END DESCRIPTION:
XS GIS Cut Line= 3
      2741275.97      6802060.97      2741226.00      6802011.00
      2740839.65      6801751.09
#Sta/Elev= 30
  4925.5  407.39  4929.0  407.39  4939.6  400.62  4953.7  398.60  4967.9  399.53
  4974.4  399.07  4982.0  398.54  4990.6  397.23  4999.2  396.92  5009.7  393.34
  5018.6  390.97  5024.7  386.10  5032.3  384.16  5043.7  382.19  5043.9  381.69
  5047.4  381.69  5047.7  382.19  5054.6  383.41  5060.7  388.14  5068.5  391.72
  5075.6  393.92  5081.7  395.24  5117.7  394.90  5162.6  395.19  5198.6  396.15
  5270.6  398.87  5297.6  398.70  5333.6  400.22  5414.6  405.03  5461.8  409.20
#Mann=5,-1,0
  4925.5    0.05       0  4974.4    0.12       0  4990.6    0.05       0
  5043.7    0.05       0  5047.7    0.05       0
Bank Sta=5043.7,5047.7
Exp/Cntr=0.3,0.1

Type RM Length L Ch R = 1,10419,277,277,277
BEGIN DESCRIPTION:
Clear Creek T 26 24.0
END DESCRIPTION:
XS GIS Cut Line= 3
      2741500.27      6801750.40      2741176.00      6801761.00
      2740861.38      6801709.21
#Sta/Elev= 30
  4680.5  405.14  4704.8  403.46  4724.8  403.08  4774.8  400.59  4824.8  397.28
  4850.9  396.20  4934.9  394.14  4964.9  393.97  4974.9  391.35  4984.9  384.83
  4992.9  380.39  4993.2  379.89  4996.7  379.89  4996.9  380.39  5002.4  383.50
  5007.5  383.50  5015.1  386.77  5033.0  388.06  5038.1  385.03  5045.5  389.48
  5055.6  392.61  5065.8  393.85  5106.3  394.94  5155.4  397.46  5160.4  397.25
  5187.4  399.57  5207.6  400.52  5248.2  404.20  5309.0  408.12  5323.8  408.62
#Mann=3,-1,0
  4680.5    0.05       0  4992.9    0.04       0  4996.9    0.05       0
Bank Sta=4992.9,4996.9
Exp/Cntr=0.3,0.1

Type RM Length L Ch R = 1,10142,288,288,288
BEGIN DESCRIPTION:
Clear Creek T 26 23.0
END DESCRIPTION:
XS GIS Cut Line= 3
      2741524.09      6801676.51      2741176.00      6801511.00
      2740940.86      6801486.02
#Sta/Elev= 30
  4618.5  406.52  4627.5  407.03  4660.7  405.95  4666.2  405.08  4682.8  404.38
  4734.4  399.89  4830.8  395.01  4853.5  393.38  4893.2  392.01  4927.2  391.78
  4937.5  391.48  4944.4  390.75  4981.8  390.32  4995.3  386.21  4999.2  380.47
  4999.4  379.97  5002.9  379.97  5003.2  380.47  5006.5  380.47  5024.1  392.52
  5055.3  392.64  5084.4  393.84  5142.8  399.82  5147.8  399.55  5154.8  400.95
  5185.0  404.15  5205.1  405.75  5215.1  407.24  5235.2  409.28  5240.4  410.39
#Mann=3,-1,0
  4618.5    0.05       0  4999.2    0.04       0  5003.2    0.05       0
Bank Sta=4999.2,5003.2
Exp/Cntr=0.3,0.1

Type RM Length L Ch R = 1,9854,263,263,263
BEGIN DESCRIPTION:
Clear Creek T 26 22.0
END DESCRIPTION:
XS GIS Cut Line= 3
      2741583.81      6801390.43      2741276.00      6801261.00
      2740769.11      6801342.97
#Sta/Elev= 30
  4666.0  401.19  4731.6  396.28  4793.8  393.72  4815.5  392.06  4891.4  389.58
  4937.8  389.46  4961.6  388.58  4978.2  386.63  4985.3  379.78  4988.8  379.23
  4989.0  378.73  4992.5  378.73  4992.8  379.23  5002.5  379.67  5010.1  383.56
  5020.2  386.71  5028.2  388.37  5033.3  388.12  5040.4  389.03  5095.0  389.13
  5162.0  392.04  5182.3  392.26  5243.0  394.43  5313.9  399.95  5334.2  400.80
  5395.0  405.37  5415.2  407.61  5465.3  410.06  5476.0  411.61  5513.4  414.14
#Mann=3,-1,0
  4666.0    0.05       0  4988.8    0.04       0  4992.8    0.05       0
Bank Sta=4988.8,4992.8
Exp/Cntr=0.3,0.1

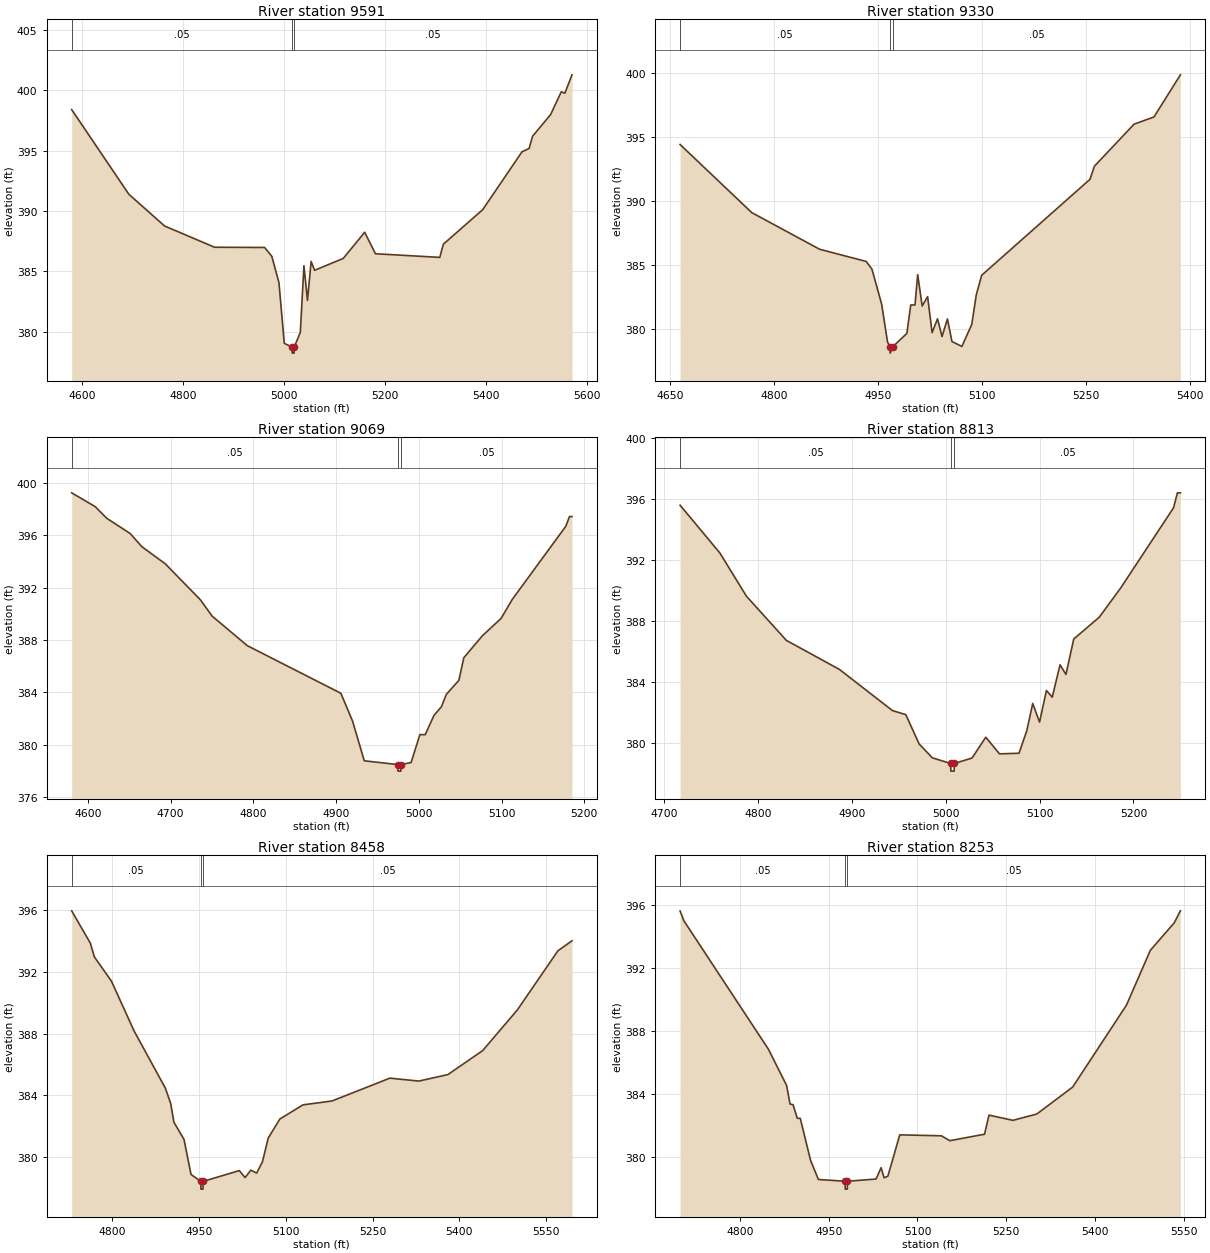
Type RM Length L Ch R = 1,9591,261,261,261
BEGIN DESCRIPTION:
Clear Creek T 26 21.0
END DESCRIPTION:
XS GIS Cut Line= 3
      2741625.99      6801310.99      2741326.00      6801011.00
      2740920.10      6800616.90
#Sta/Elev= 30
  4580.1  398.40  4693.2  391.39  4763.9  388.76  4862.9  387.00  4961.9  386.98
  4976.1  386.25  4990.2  384.08  5000.8  379.04  5016.4  378.73  5016.6  378.23
  5020.1  378.23  5020.4  378.73  5032.5  379.94  5039.7  385.47  5046.7  382.60
  5053.9  385.82  5060.8  385.09  5117.4  386.07  5159.9  388.24  5181.2  386.46
  5308.5  386.16  5315.5  387.25  5393.4  390.11  5471.1  394.90  5485.2  395.18
  5492.2  396.20  5527.7  397.98  5548.8  399.87  5556.0  399.76  5570.1  401.28
#Mann=3,-1,0
  4580.1    0.05       0  5016.4    0.04       0  5020.4    0.05       0
Bank Sta=5016.4,5020.4
Exp/Cntr=0.3,0.1

Type RM Length L Ch R = 1,9330,261,261,261
BEGIN DESCRIPTION:
Clear Creek T 26 20.0
END DESCRIPTION:
XS GIS Cut Line= 3
      2741776.00      6800961.00      2741476.00      6800811.00
      2741180.73      6800562.40
#Sta/Elev= 30
  4664.6  394.39  4768.0  389.07  4865.8  386.21  4932.9  385.26  4941.3  384.65
  4955.3  381.91  4963.7  378.97  4967.3  378.60  4967.5  378.10  4971.3  378.60
  4991.6  379.64  4997.2  381.86  5003.3  381.86  5007.2  384.23  5013.7  381.78
  5021.5  382.51  5028.0  379.70  5035.8  380.78  5042.3  379.39  5050.1  380.77
  5056.6  379.01  5070.9  378.62  5085.2  380.35  5091.7  382.66  5099.5  384.18
  5255.6  391.67  5262.1  392.70  5319.3  395.98  5347.9  396.54  5386.0  399.83
#Mann=3,-1,0
  4664.6    0.05       0  4967.3    0.04       0  4971.3    0.05       0
Bank Sta=4967.3,4971.3
Exp/Cntr=0.3,0.1

Type RM Length L Ch R = 1,9069,256,256,256
BEGIN DESCRIPTION:
Clear Creek T 26 19.0
END DESCRIPTION:
XS GIS Cut Line= 3
      2741926.02      6800911.02      2741626.00      6800611.00
      2741475.98      6800510.99
#Sta/Elev= 30
  4580.5  399.25  4608.8  398.20  4623.0  397.30  4651.2  396.14  4665.4  395.13
  4693.7  393.82  4736.1  391.07  4750.2  389.83  4792.7  387.57  4905.8  383.93
  4919.9  381.81  4934.1  378.77  4974.5  378.48  4974.8  377.98  4978.3  377.98
  4978.5  378.48  4990.7  378.64  5001.3  380.77  5007.8  380.77  5018.3  382.24
  5027.3  382.90  5033.3  383.85  5048.4  384.92  5054.4  386.65  5076.9  388.33
  5099.4  389.65  5113.0  391.11  5177.6  396.69  5182.1  397.44  5185.1  397.44
#Mann=3,-1,0
  4580.5    0.05       0  4974.5    0.04       0  4978.5    0.05       0
Bank Sta=4974.5,4978.5
Exp/Cntr=0.3,0.1

Type RM Length L Ch R = 1,8813,355,355,355
BEGIN DESCRIPTION:
Clear Creek T 26 18.0
END DESCRIPTION:
XS GIS Cut Line= 3
      2742026.01      6800661.01      2741826.00      6800461.00
      2741625.97      6800310.98
#Sta/Elev= 30
  4717.1  395.59  4759.5  392.46  4787.8  389.63  4830.3  386.74  4886.8  384.84
  4943.4  382.14  4957.5  381.88  4971.7  379.96  4985.8  379.05  5005.3  378.68
  5005.5  378.18  5009.0  378.18  5009.3  378.68  5028.1  379.04  5042.7  380.40
  5057.3  379.31  5078.1  379.35  5086.4  380.83  5092.7  382.61  5100.0  381.39
  5107.3  383.46  5113.5  383.02  5121.8  385.14  5128.1  384.51  5136.4  386.83
  5163.5  388.25  5186.4  390.17  5242.7  395.42  5246.8  396.40  5250.0  396.40
#Mann=3,-1,0
  4717.1    0.05       0  5005.3    0.04       0  5009.3    0.05       0
Bank Sta=5005.3,5009.3
Exp/Cntr=0.3,0.1

Type RM Length L Ch R = 1,8458,205,205,205
BEGIN DESCRIPTION:
Clear Creek T 26 17.0
END DESCRIPTION:
XS GIS Cut Line= 3
      2742226.01      6800561.02      2742126.00      6800311.00
      2742132.66      6799716.72
#Sta/Elev= 30
  4730.7  395.95  4763.0  393.85  4769.8  392.97  4799.4  391.39  4838.4  388.17
  4892.3  384.47  4901.7  383.46  4907.1  382.26  4924.6  381.14  4936.7  378.87
  4953.6  378.42  4953.8  377.92  4957.3  377.92  4957.6  378.42  5020.0  379.12
  5030.0  378.67  5040.0  379.15  5050.0  378.96  5060.0  379.69  5070.0  381.23
  5090.0  382.46  5130.0  383.38  5180.0  383.63  5280.0  385.11  5330.0  384.92
  5380.0  385.34  5440.0  386.89  5500.0  389.53  5570.0  393.36  5594.3  394.01
#Mann=3,-1,0
  4730.7    0.05       0  4953.6    0.04       0  4957.6    0.05       0
Bank Sta=4953.6,4957.6
Exp/Cntr=0.3,0.1

Type RM Length L Ch R = 1,8253,33,33,33
BEGIN DESCRIPTION:
Mapping XS f76a1077
END DESCRIPTION:
XS GIS Cut Line= 4
      2742283.82      6800557.31      2742323.81      6800360.86
      2742295.89      6800051.07      2742250.92      6799720.74
#Sta/Elev= 30
  4699.1  395.59  4705.5  394.97  4848.4  386.82  4879.0  384.53  4884.8  383.35
  4889.9  383.31  4897.0  382.45  4902.0  382.45  4919.5  379.78  4932.7  378.57
  4977.8  378.46  4978.0  377.96  4981.5  377.96  4981.8  378.46  5030.0  378.60
  5038.6  379.32  5043.6  378.68  5050.0  378.78  5070.1  381.40  5140.4  381.34
  5154.6  381.03  5213.2  381.44  5220.8  382.65  5261.2  382.32  5301.5  382.72
  5362.1  384.43  5452.9  389.62  5493.3  393.10  5533.6  394.84  5544.0  395.60
#Mann=3,-1,0
  4699.1    0.05       0  4977.8    0.04       0  4981.8    0.05       0
Bank Sta=4977.8,4981.8
Exp/Cntr=0.3,0.1

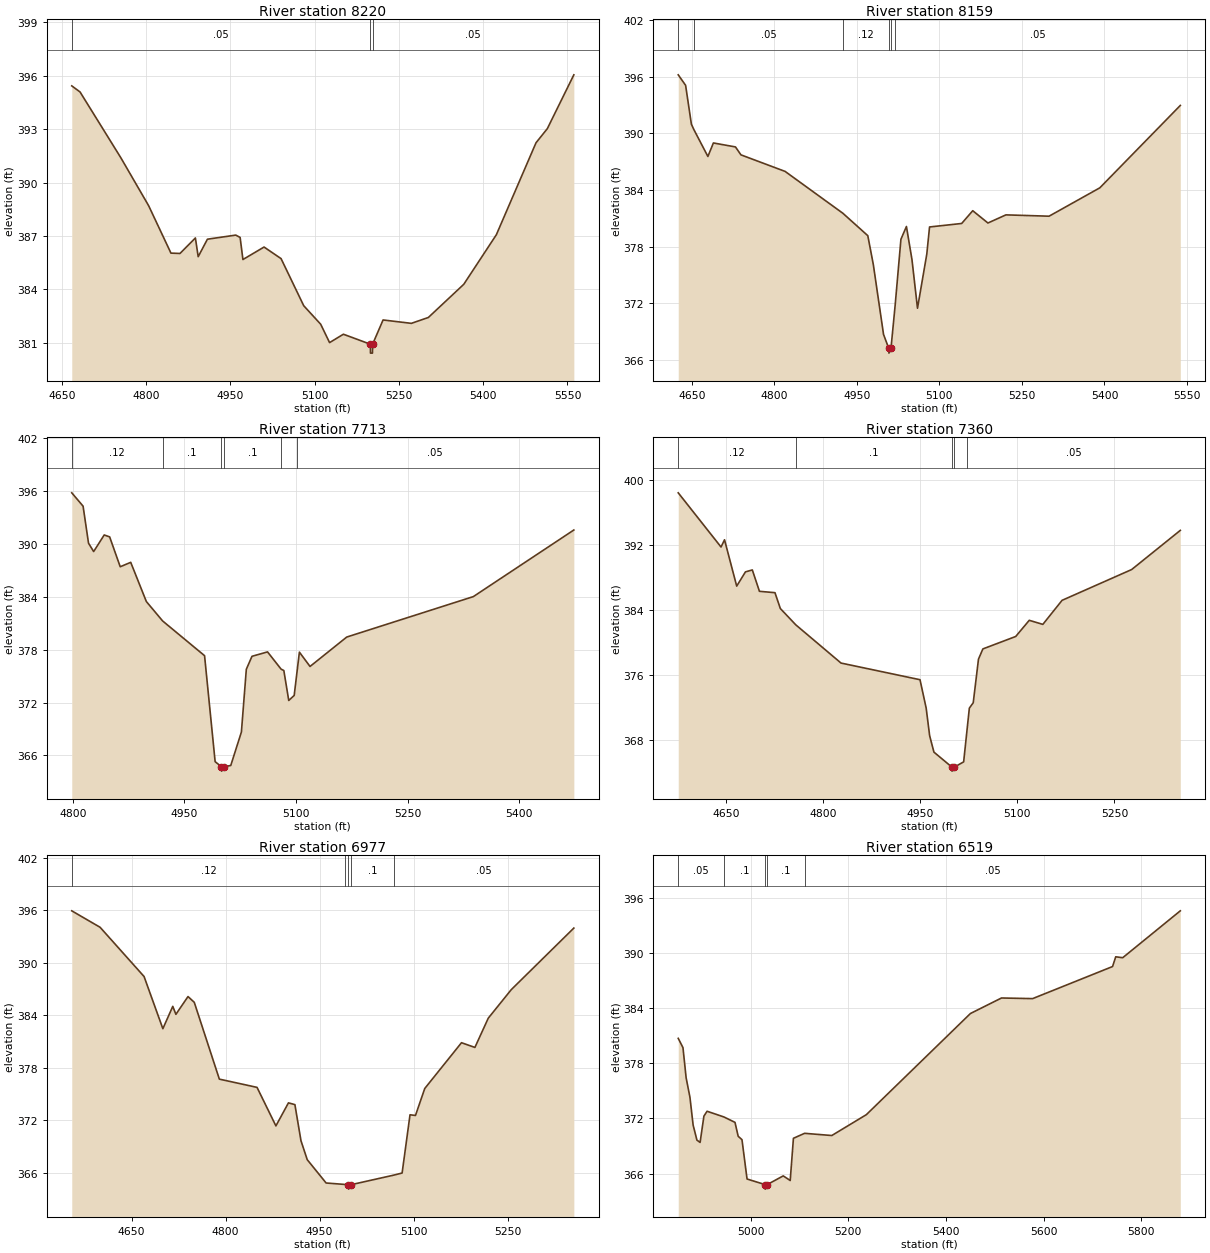
Type RM Length L Ch R = 1,8220,61,61,61
BEGIN DESCRIPTION:
Mapping XS dfcf01cd
END DESCRIPTION:
XS GIS Cut Line= 3
      2742314.21      6800585.20      2742364.97      6800399.42
      2742275.74      6799704.21
#Sta/Elev= 30
  4667.8  395.42  4682.5  395.08  4755.1  391.39  4804.6  388.70  4844.3  386.04
  4860.4  386.02  4887.8  386.89  4892.8  385.84  4909.2  386.82  4959.6  387.05
  4967.4  386.92  4972.4  385.68  5010.0  386.38  5040.3  385.73  5080.6  383.09
  5110.8  382.05  5126.6  381.02  5151.2  381.49  5199.2  380.93  5199.4  380.43
  5202.9  380.43  5203.2  380.93  5221.8  382.29  5272.2  382.10  5302.4  382.43
  5365.4  384.29  5423.4  387.07  5494.0  392.23  5514.1  393.02  5561.3  396.04
#Mann=3,-1,0
  4667.8    0.05       0  5199.2    0.04       0  5203.2    0.05       0
Bank Sta=5199.2,5203.2
Exp/Cntr=0.3,0.1

Type RM Length L Ch R = 1,8159,446,446,446
BEGIN DESCRIPTION:
Clear Creek T 26 16.0
END DESCRIPTION:
XS GIS Cut Line= 3
      2742432.16      6800634.80      2742407.87      6800258.96
      2742359.94      6799725.34
#Sta/Elev= 30
  4625.4  396.19  4638.8  395.08  4649.3  390.97  4653.6  390.42  4679.3  387.55
  4689.3  388.98  4729.4  388.56  4739.4  387.72  4819.6  385.97  4924.6  381.54
  4969.9  379.17  4979.9  376.12  4998.5  368.72  5008.0  367.24  5008.3  366.74
  5012.0  367.24  5019.5  371.74  5030.1  378.79  5040.1  380.14  5050.2  376.62
  5060.2  371.49  5077.1  377.22  5082.1  380.09  5140.5  380.46  5160.6  381.81
  5188.2  380.51  5220.9  381.37  5299.3  381.23  5391.5  384.23  5537.8  392.95
#Mann=6,-1,0
  4625.4    0.12       0  4653.6    0.05       0  4924.6    0.12       0
  5008.0    0.07       0  5012.0    0.12       0  5019.5    0.05       0
Bank Sta=5008,5012
Exp/Cntr=0.3,0.1

Type RM Length L Ch R = 1,7713,353,353,353
BEGIN DESCRIPTION:
Clear Creek T 26 15.0
END DESCRIPTION:
XS GIS Cut Line= 3
      2742866.73      6800212.12      2742726.00      6800061.00
      2742420.72      6799706.27
#Sta/Elev= 30
  4798.6  395.74  4813.8  394.23  4821.1  390.04  4828.0  389.09  4842.2  390.97
  4849.5  390.75  4863.7  387.37  4877.8  387.87  4898.8  383.43  4920.7  381.23
  4977.0  377.30  4991.2  365.30  4999.7  364.73  4999.9  364.23  5003.7  364.73
  5012.2  364.87  5026.5  368.66  5033.1  375.76  5040.7  377.23  5061.6  377.73
  5079.8  375.78  5083.5  375.62  5090.1  372.23  5097.4  372.80  5100.7  375.11
  5104.4  377.70  5118.7  376.08  5168.0  379.41  5338.1  383.99  5473.1  391.53
#Mann=6,-1,0
  4798.6    0.12       0  4920.7     0.1       0  4999.7    0.07       0
  5003.7     0.1       0  5079.8    0.12       0  5100.7    0.05       0
Bank Sta=4999.7,5003.7
Exp/Cntr=0.3,0.1

Type RM Length L Ch R = 1,7360,383,383,383
BEGIN DESCRIPTION:
Clear Creek T 26 14.0
END DESCRIPTION:
XS GIS Cut Line= 3
      2743035.74      6800157.28      2742876.00      6799761.00
      2742677.92      6799474.70
#Sta/Elev= 30
  4576.4  398.42  4642.5  391.75  4647.9  392.64  4666.7  386.94  4680.2  388.69
  4690.8  388.93  4701.8  386.30  4725.8  386.13  4734.1  384.18  4758.0  382.17
  4827.8  377.47  4949.8  375.42  4959.3  371.93  4964.7  368.52  4971.3  366.51
  4999.0  364.67  4999.2  364.17  5003.0  364.67  5017.2  365.31  5022.6  369.37
  5026.0  371.92  5032.0  372.59  5040.1  377.95  5046.9  379.21  5097.6  380.74
  5118.5  382.73  5139.5  382.23  5169.2  385.19  5276.7  388.98  5351.8  393.80
#Mann=5,-1,0
  4576.4    0.12       0  4758.0     0.1       0  4999.0    0.07       0
  5003.0     0.1       0  5022.6    0.05       0
Bank Sta=4999,5003
Exp/Cntr=0.3,0.1

Type RM Length L Ch R = 1,6977,458,458,458
BEGIN DESCRIPTION:
Clear Creek T 26 13.0
END DESCRIPTION:
XS GIS Cut Line= 3
      2743202.45      6800106.10      2743226.00      6799661.00
      2743040.54      6799358.21
#Sta/Elev= 30
  4554.7  395.93  4599.9  394.05  4670.0  388.43  4700.0  382.47  4715.8  385.02
  4720.8  384.11  4740.1  386.14  4750.1  385.48  4790.1  376.71  4850.2  375.77
  4880.3  371.37  4900.3  374.00  4910.6  373.80  4920.3  369.67  4930.3  367.51
  4960.4  364.85  4991.1  364.68  4995.9  364.65  4996.2  364.15  4999.9  364.65
  5069.0  365.76  5081.6  365.99  5094.2  372.64  5102.9  372.56  5117.7  375.64
  5176.3  380.87  5197.7  380.33  5219.0  383.67  5255.7  386.93  5355.5  393.96
#Mann=5,-1,0
  4554.7    0.12       0  4991.1     0.1       0  4995.9    0.07       0
  4999.9     0.1       0  5069.0    0.05       0
Bank Sta=4995.9,4999.9
Exp/Cntr=0.3,0.1

Type RM Length L Ch R = 1,6519,495,495,495
BEGIN DESCRIPTION:
Clear Creek T 26 12.0
END DESCRIPTION:
XS GIS Cut Line= 3
      2743736.31      6799604.00      2743626.00      6799511.00
      2742950.88      6798939.83
#Sta/Elev= 30
  4851.6  380.71  4861.3  379.70  4867.8  376.41  4875.6  374.30  4882.1  371.28
  4889.9  369.64  4896.4  369.39  4904.2  372.25  4910.7  372.78  4945.2  372.16
  4967.9  371.57  4974.4  370.06  4982.2  369.69  4992.6  365.41  5029.1  364.81
  5029.7  364.31  5034.1  364.81  5066.7  365.75  5081.0  365.25  5087.6  369.84
  5110.5  370.38  5166.2  370.14  5237.0  372.41  5450.2  383.41  5513.9  385.10
  5577.6  385.03  5741.4  388.52  5747.9  389.58  5762.2  389.48  5880.2  394.58
#Mann=5,-1,0
  4851.6    0.05       0  4945.2     0.1       0  5029.1    0.07       0
  5034.1     0.1       0  5110.5    0.05       0
Bank Sta=5029.1,5034.1
Exp/Cntr=0.3,0.1

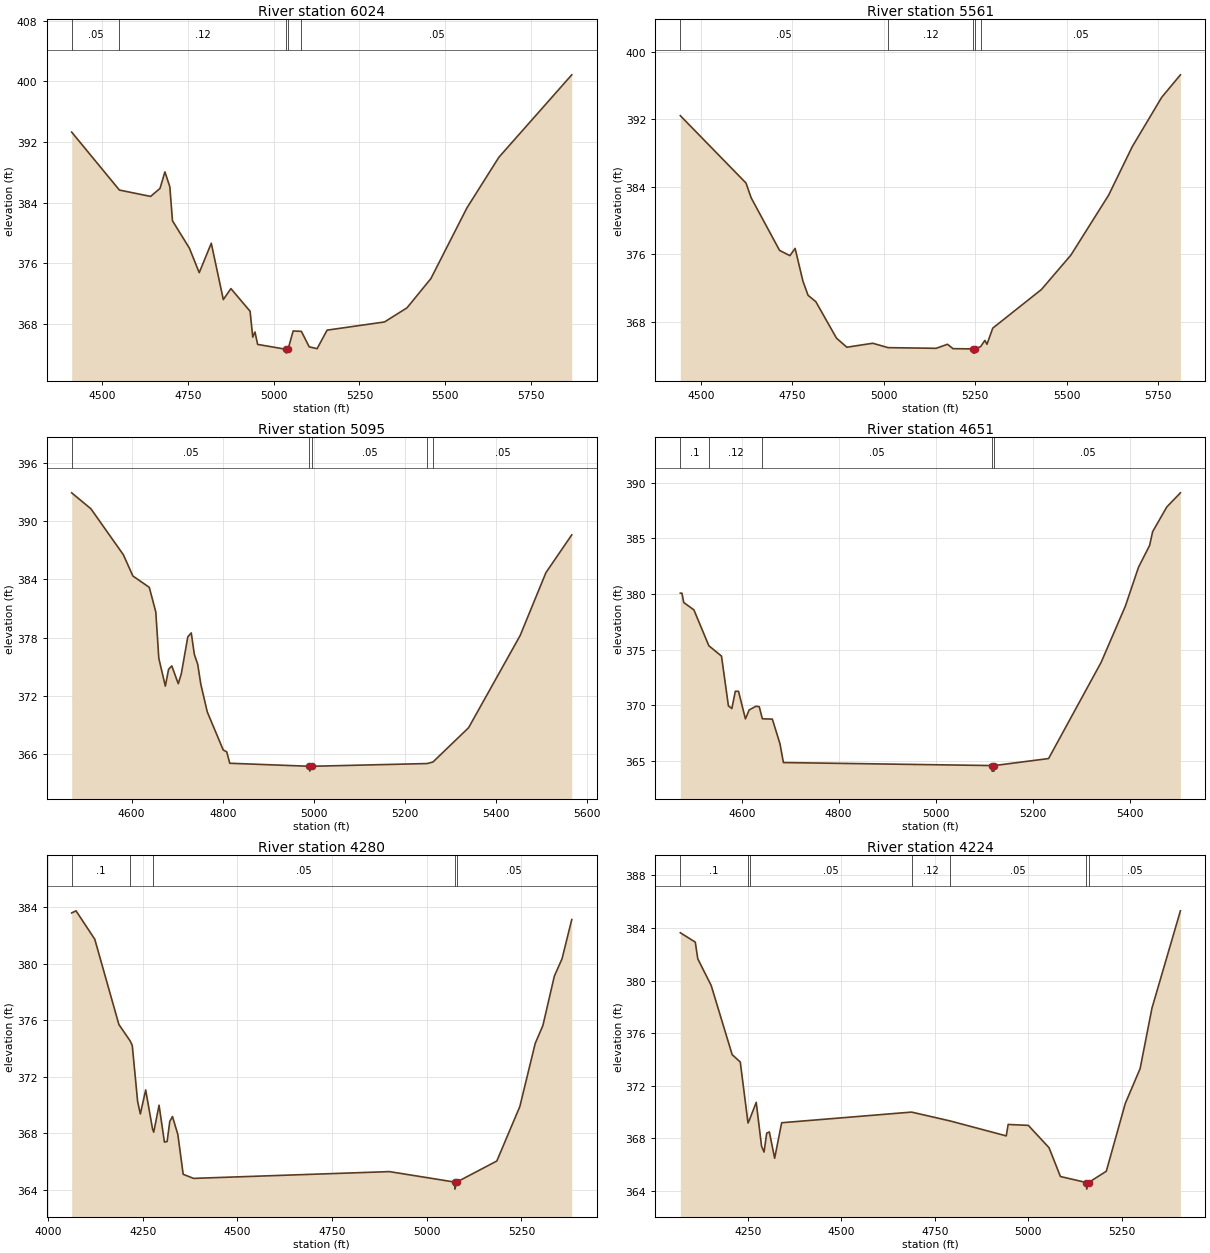
Type RM Length L Ch R = 1,6024,463,463,463
BEGIN DESCRIPTION:
Clear Creek T 26 11.0
END DESCRIPTION:
XS GIS Cut Line= 3
      2744421.67      6799538.90      2743976.00      6799161.00
      2743176.03      6798811.01
#Sta/Elev= 30
  4411.4  393.29  4550.5  385.65  4641.5  384.81  4668.9  385.87  4683.2  388.05
  4697.5  386.08  4705.2  381.60  4754.6  377.98  4783.2  374.76  4818.3  378.64
  4853.4  371.21  4875.5  372.66  4931.4  369.67  4939.2  366.26  4945.7  366.94
  4953.4  365.30  5036.8  364.65  5037.5  364.15  5042.0  364.65  5056.9  367.07
  5080.9  367.02  5103.7  364.98  5126.7  364.74  5155.9  367.18  5323.2  368.26
  5388.7  370.12  5458.4  373.98  5563.3  383.29  5656.5  389.97  5868.9  400.84
#Mann=5,-1,0
  4411.4    0.05       0  4550.5    0.12       0  5036.8    0.07       0
  5042.0    0.12       0  5080.9    0.05       0
Bank Sta=5036.8,5042
Exp/Cntr=0.3,0.1

Type RM Length L Ch R = 1,5561,466,466,466
BEGIN DESCRIPTION:
Clear Creek T 26 10.0
END DESCRIPTION:
XS GIS Cut Line= 3
      2744577.96      6799152.95      2744176.00      6798761.00
      2743476.04      6798361.02
#Sta/Elev= 30
  4443.6  392.41  4623.2  384.43  4637.3  382.68  4715.0  376.45  4743.3  375.83
  4757.5  376.69  4778.8  372.82  4792.9  371.13  4814.1  370.38  4870.6  366.06
  4898.9  364.98  4969.7  365.45  5011.8  364.93  5143.2  364.85  5174.2  365.33
  5189.3  364.81  5244.2  364.78  5245.0  364.28  5248.8  364.28  5249.5  364.78
  5264.8  365.05  5276.4  365.79  5282.2  365.33  5298.0  367.24  5431.2  371.82
  5511.8  375.90  5614.7  382.98  5679.5  388.74  5760.1  394.59  5811.2  397.25
#Mann=5,-1,0
  4443.6    0.05       0  5011.8    0.12       0  5244.2    0.03       0
  5249.5    0.12       0  5264.8    0.05       0
Bank Sta=5244.2,5249.5
Exp/Cntr=0.3,0.1

Type RM Length L Ch R = 1,5095,444,444,444
BEGIN DESCRIPTION:
Clear Creek T 26 9.0
END DESCRIPTION:
XS GIS Cut Line= 3
      2744725.98      6798760.98      2744376.00      6798361.00
      2743975.98      6797960.98
#Sta/Elev= 30
  4468.5  392.92  4510.7  391.28  4581.9  386.55  4602.8  384.36  4638.8  383.19
  4653.1  380.65  4659.7  375.89  4674.0  373.02  4681.1  374.75  4688.2  375.10
  4702.4  373.27  4709.1  374.30  4723.3  378.09  4730.9  378.50  4737.6  376.30
  4745.1  375.26  4751.8  373.23  4766.0  370.37  4801.1  366.44  4808.7  366.26
  4815.4  365.08  4990.2  364.77  4991.0  364.27  4995.5  364.77  5248.4  365.05
  5261.2  365.21  5339.4  368.74  5452.5  378.23  5509.1  384.71  5565.7  388.59
#Mann=5,-1,0
  4468.5    0.05       0  4990.2    0.03       0  4995.5    0.05       0
  5248.4    0.12       0  5261.2    0.05       0
Bank Sta=4990.2,4995.5
Exp/Cntr=0.3,0.1

Type RM Length L Ch R = 1,4651,371,371,371
BEGIN DESCRIPTION:
Clear Creek T 26 8.0
END DESCRIPTION:
XS GIS Cut Line= 3
      2744925.99      6798310.99      2744526.00      6797961.00
      2744226.00      6797560.99
#Sta/Elev= 30
  4473.4  380.08  4476.7  380.08  4480.5  379.24  4501.4  378.58  4532.2  375.36
  4558.3  374.43  4572.6  369.96  4579.7  369.72  4586.8  371.27  4593.4  371.27
  4607.7  368.79  4615.3  369.59  4629.5  369.93  4636.2  369.88  4642.6  368.80
  4663.2  368.77  4678.9  366.56  4686.0  364.87  5115.6  364.60  5116.5  364.10
  5120.4  364.10  5121.2  364.60  5233.0  365.23  5341.4  373.87  5391.4  378.92
  5418.4  382.40  5441.4  384.37  5447.6  385.60  5476.8  387.82  5504.9  389.09
#Mann=5,-1,0
  4473.4     0.1       0  4532.2    0.12       0  4642.6    0.05       0
  5115.6    0.03       0  5121.2    0.05       0
Bank Sta=5115.6,5121.2
Exp/Cntr=0.3,0.1

Type RM Length L Ch R = 1,4280,56,56,56
BEGIN DESCRIPTION:
Mapping XS 87c81075
END DESCRIPTION:
XS GIS Cut Line= 6
      2744990.84      6798352.46      2744771.81      6798130.75
      2744867.57      6797816.98      2744869.54      6797734.77
      2744819.64      6797668.63      2744310.71      6797587.23
#Sta/Elev= 30
  4062.5  383.61  4074.0  383.76  4123.5  381.75  4187.2  375.71  4216.7  374.56
  4222.5  374.23  4236.6  370.27  4243.8  369.38  4257.9  371.08  4276.0  368.32
  4279.1  368.09  4293.2  370.00  4307.4  367.39  4314.5  367.43  4321.5  368.85
  4328.6  369.20  4342.8  367.93  4356.9  365.11  4384.4  364.82  4901.4  365.30
  5073.5  364.56  5074.3  364.06  5079.1  364.56  5184.9  366.05  5245.7  369.91
  5286.2  374.37  5306.5  375.64  5336.8  379.14  5357.1  380.37  5382.7  383.14
#Mann=5,-1,0
  4062.5     0.1       0  4216.7    0.12       0  4276.0    0.05       0
  5073.5    0.03       0  5079.1    0.05       0
Bank Sta=5073.5,5079.1
Exp/Cntr=0.3,0.1

Type RM Length L Ch R = 1,4224,187,187,187
BEGIN DESCRIPTION:
Clear Creek T 26 7.0
END DESCRIPTION:
XS GIS Cut Line= 6
      2745018.84      6798324.38      2744814.33      6798142.87
      2744907.91      6797803.94      2744880.17      6797672.10
      2744835.77      6797637.26      2744331.44      6797545.11
#Sta/Elev= 30
  4068.8  383.64  4108.8  382.93  4115.5  381.66  4151.4  379.63  4207.5  374.37
  4229.2  373.81  4249.9  369.17  4253.9  369.42  4271.9  370.74  4286.1  367.41
  4292.8  366.96  4299.9  368.40  4307.0  368.49  4321.2  366.49  4339.9  369.19
  4687.5  370.00  4790.2  369.33  4940.9  368.19  4946.0  369.06  5000.0  368.99
  5055.4  367.29  5085.8  365.10  5155.4  364.64  5156.2  364.14  5161.0  364.64
  5208.6  365.50  5259.3  370.65  5299.1  373.31  5330.8  377.91  5406.9  385.31
#Mann=7,-1,0
  4068.8     0.1       0  4249.9    0.12       0  4253.9    0.05       0
  4687.5    0.12       0  4790.2    0.05       0  5155.4    0.03       0
  5161.0    0.05       0
Bank Sta=5155.4,5161
Exp/Cntr=0.3,0.1

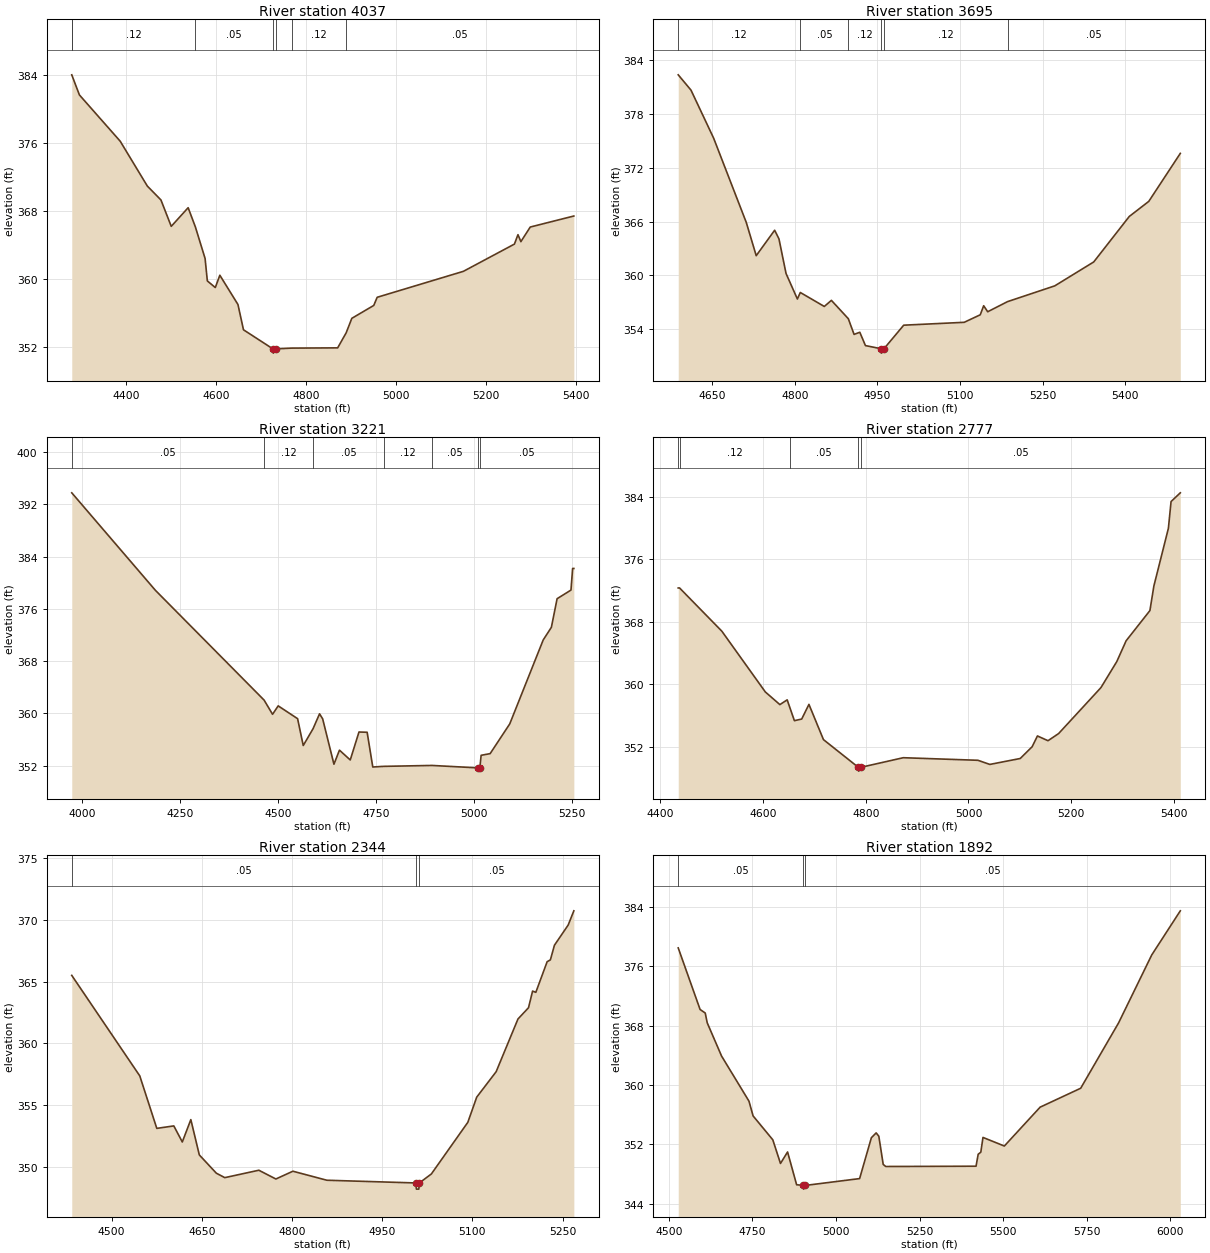
Type RM Length L Ch R = 1,4037,342,342,342
BEGIN DESCRIPTION:
Mapping XS 0f3d27f8
END DESCRIPTION:
XS GIS Cut Line= 3
      2745058.34      6798297.83      2744977.99      6797659.43
      2744610.48      6797360.92
#Sta/Elev= 30
  4279.2  384.05  4279.3  384.03  4296.2  381.68  4386.9  376.23  4447.3  370.94
  4477.6  369.30  4500.5  366.19  4538.1  368.39  4554.2  366.12  4575.8  362.40
  4580.8  359.76  4598.5  358.98  4608.6  360.43  4648.9  356.98  4661.2  354.00
  4726.7  351.75  4727.6  351.25  4732.5  351.75  4768.3  351.84  4870.7  351.87
  4889.6  353.64  4902.2  355.35  4951.0  356.87  4958.6  357.83  5150.4  360.89
  5263.9  364.10  5271.8  365.21  5278.3  364.39  5299.1  366.11  5396.1  367.41
#Mann=7,-1,0
  4279.2     0.1       0  4279.3    0.12       0  4554.2    0.05       0
  4726.7    0.04       0  4732.5    0.05       0  4768.3    0.12       0
  4889.6    0.05       0
Bank Sta=4726.7,4732.5
Exp/Cntr=0.3,0.1

Type RM Length L Ch R = 1,3695,474,474,474
BEGIN DESCRIPTION:
Clear Creek T 26 6.0
END DESCRIPTION:
XS GIS Cut Line= 3
      2745326.00      6798011.00      2745226.00      6797611.00
      2744926.01      6797211.01
#Sta/Elev= 30
  4588.0  382.39  4611.2  380.68  4652.4  375.31  4711.7  365.90  4729.7  362.20
  4763.2  365.04  4771.0  364.08  4783.9  360.21  4804.5  357.36  4809.8  358.09
  4853.4  356.53  4866.3  357.21  4897.1  355.16  4907.5  353.41  4917.9  353.65
  4928.2  352.16  4956.1  351.82  4957.1  351.32  4962.0  351.82  4997.7  354.44
  5107.6  354.76  5136.8  355.60  5143.0  356.61  5150.3  355.94  5186.4  357.07
  5272.2  358.83  5343.0  361.50  5407.6  366.58  5443.0  368.26  5500.3  373.62
#Mann=6,-1,0
  4588.0    0.12       0  4809.8    0.05       0  4897.1    0.12       0
  4956.1    0.07       0  4962.0    0.12       0  5186.4    0.05       0
Bank Sta=4956.1,4962
Exp/Cntr=0.3,0.1

Type RM Length L Ch R = 1,3221,444,444,444
BEGIN DESCRIPTION:
Clear Creek T 26 5.0
END DESCRIPTION:
XS GIS Cut Line= 3
      2746226.01      6797861.01      2745426.00      6797211.00
      2745276.00      6797010.99
#Sta/Elev= 30
  3973.8  393.78  4187.2  378.85  4464.5  362.04  4486.0  359.87  4500.4  361.16
  4549.9  359.20  4564.3  355.09  4589.3  357.66  4605.9  359.94  4613.8  359.18
  4642.6  352.23  4656.7  354.38  4684.2  352.88  4706.5  357.16  4727.3  357.12
  4741.7  351.80  4769.4  351.90  4892.9  352.04  5008.9  351.67  5009.9  351.17
  5014.8  351.67  5018.1  353.59  5041.1  353.85  5091.1  358.40  5176.5  371.26
  5197.3  373.19  5211.9  377.57  5247.3  378.89  5251.5  382.20  5254.6  382.20
#Mann=7,-1,0
  3973.8    0.05       0  4464.5    0.12       0  4589.3    0.05       0
  4769.4    0.12       0  4892.9    0.05       0  5008.9    0.04       0
  5014.8    0.05       0
Bank Sta=5008.9,5014.8
Exp/Cntr=0.3,0.1

Type RM Length L Ch R = 1,2777,433,433,433
BEGIN DESCRIPTION:
Clear Creek T 26 4.0
END DESCRIPTION:
XS GIS Cut Line= 3
      2746176.03      6797361.03      2745776.00      6796961.00
      2745376.04      6796861.01
#Sta/Elev= 30
  4434.7  372.35  4437.3  372.35  4519.6  366.81  4604.4  359.01  4632.7  357.39
  4646.9  358.00  4652.6  356.92  4661.0  355.33  4675.2  355.54  4689.3  357.42
  4717.6  352.90  4785.3  349.36  4786.3  348.86  4791.2  349.36  4873.1  350.58
  5018.5  350.25  5041.7  349.72  5100.9  350.48  5124.1  351.99  5134.4  353.37
  5155.0  352.76  5175.7  353.68  5258.1  359.57  5289.0  362.91  5307.1  365.57
  5353.5  369.45  5361.2  372.60  5389.5  380.00  5394.7  383.43  5412.7  384.55
#Mann=5,-1,0
  4434.7    0.05       0  4437.3    0.12       0  4652.6    0.05       0
  4785.3    0.04       0  4791.2    0.05       0
Bank Sta=4785.3,4791.2
Exp/Cntr=0.3,0.1

Type RM Length L Ch R = 1,2344,452,452,452
BEGIN DESCRIPTION:
Clear Creek T 26 3.0
END DESCRIPTION:
XS GIS Cut Line= 3
      2746375.99      6797010.99      2745976.00      6796611.00
      2745726.02      6796511.01
#Sta/Elev= 30
  4433.8  365.51  4546.9  357.37  4575.2  353.12  4603.5  353.32  4617.6  352.02
  4631.8  353.83  4645.9  350.97  4674.2  349.49  4688.3  349.13  4744.9  349.73
  4773.2  349.02  4801.5  349.65  4858.0  348.92  5005.9  348.70  5006.9  348.20
  5010.9  348.20  5011.8  348.70  5031.8  349.43  5092.4  353.61  5107.2  355.65
  5139.5  357.71  5175.8  361.98  5193.3  362.89  5200.1  364.24  5205.5  364.14
  5224.3  366.62  5229.7  366.77  5236.4  367.95  5259.3  369.59  5268.7  370.74
#Mann=3,-1,0
  4433.8    0.05       0  5005.9    0.04       0  5011.8    0.05       0
Bank Sta=5005.9,5011.8
Exp/Cntr=0.3,0.1

Type RM Length L Ch R = 1,1892,448,448,448
BEGIN DESCRIPTION:
Clear Creek T 26 2.0
END DESCRIPTION:
XS GIS Cut Line= 3
      2746625.99      6796960.98      2746376.00      6796561.00
      2745575.97      6795910.97
#Sta/Elev= 30
  4527.8  378.49  4593.2  370.19  4608.6  369.71  4614.5  368.40  4657.5  363.91
  4739.5  357.83  4751.8  355.84  4810.8  352.62  4833.8  349.43  4855.0  350.98
  4882.1  346.56  4902.0  346.47  4903.0  345.97  4908.2  346.47  5070.6  347.39
  5105.8  352.90  5120.1  353.55  5128.1  353.10  5141.2  349.30  5148.9  349.02
  5419.0  349.06  5425.4  350.67  5433.3  350.95  5439.8  352.94  5503.7  351.78
  5610.8  357.02  5732.2  359.57  5845.7  368.39  5944.8  377.54  6030.3  383.49
#Mann=3,-1,0
  4527.8    0.05       0  4902.0    0.04       0  4908.2    0.05       0
Bank Sta=4902,4908.2
Exp/Cntr=0.3,0.1

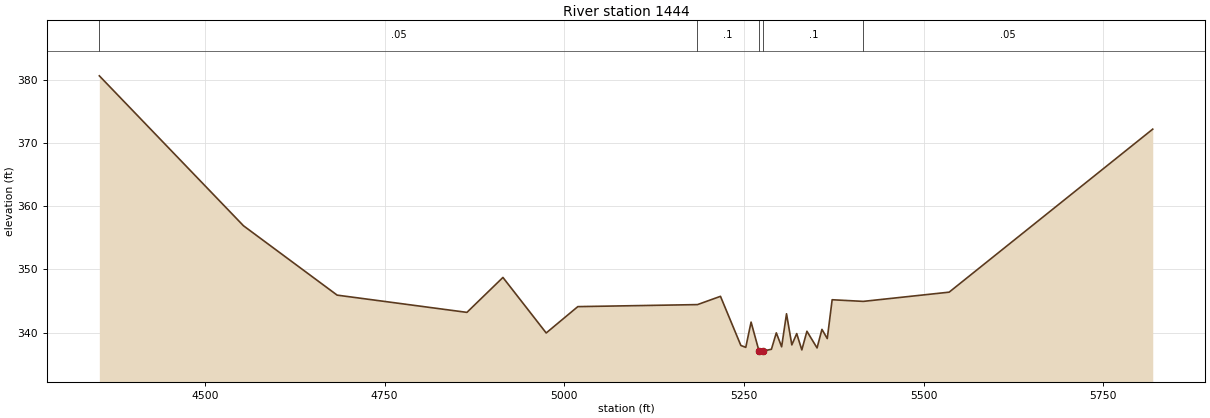
Type RM Length L Ch R = 1,1444,0,0,0
BEGIN DESCRIPTION:
Clear Creek T 26 1.0
END DESCRIPTION:
XS GIS Cut Line= 3
      2746676.00      6796960.96      2746726.00      6796311.00
      2746126.02      6795761.02
#Sta/Elev= 30
  4353.1  380.64  4553.7  356.90  4684.0  345.92  4864.6  343.19  4914.7  348.72
  4974.9  339.93  5018.9  344.10  5185.4  344.42  5217.4  345.73  5245.8  337.95
  5252.6  337.65  5260.0  341.65  5271.0  337.08  5272.0  336.58  5277.2  337.08
  5288.3  337.35  5295.1  339.95  5302.5  337.74  5309.3  342.97  5316.7  338.04
  5323.5  339.83  5330.6  337.25  5337.7  340.20  5351.8  337.56  5358.6  340.50
  5366.0  339.04  5372.8  345.19  5416.1  344.93  5535.6  346.39  5818.9  372.20
#Mann=5,-1,0
  4353.1    0.05       0  5185.4     0.1       0  5271.0    0.04       0
  5277.2     0.1       0  5416.1    0.05       0
Bank Sta=5271,5277.2
Exp/Cntr=0.3,0.1

Chan Stop Cuts=-1