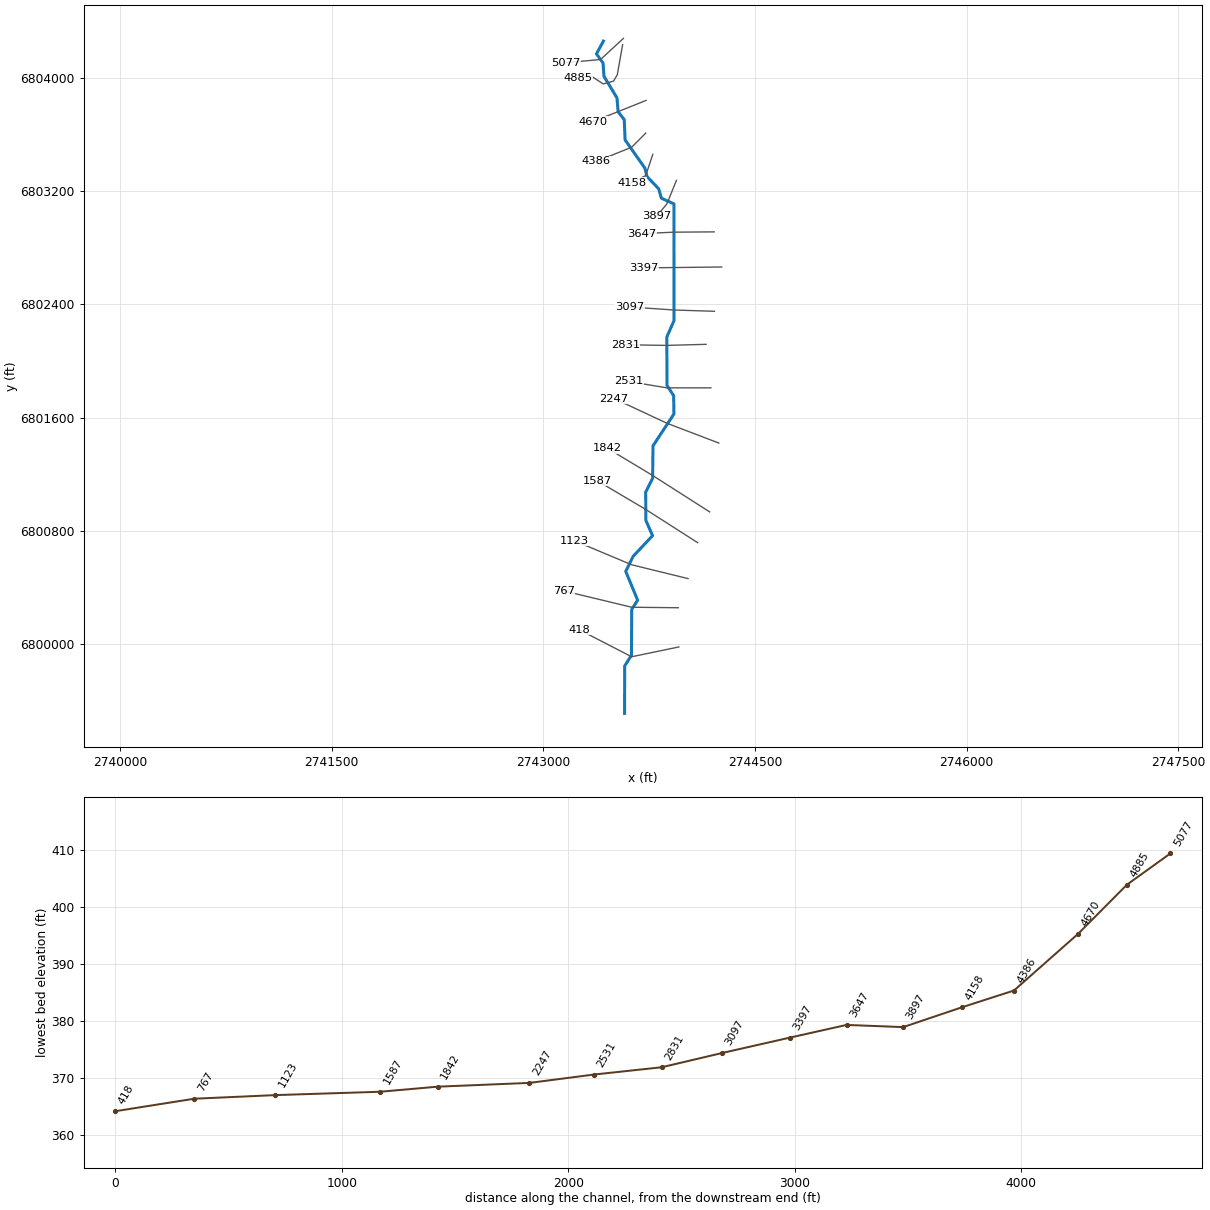
--- Clear Creek T 27.prj (project) ---

Proj Title=Clear Creek T 27 Base Level Engineering
Current Plan=p01
Default Exp/Contr=0.3,0.1
English Units
Geom File=g01
Flow File=f01
Plan File=p01
BEGIN DESCRIPTION:
Clear Creek T 27
END DESCRIPTION:

--- Clear Creek T 27.p01 (plan) ---

Plan Title=Multiple Run
Short Identifier=Multiple
Geom File=g01
Flow File=f01
Subcritical Flow
K Sum by GR= 0
Std Step Tol= 0.01
Critical Tol= 0.01
Num of Std Step Trials= 20
Max Error Tol= 0.3
Flow Tol Ratio= 0.001
Split Flow NTrial= 30
Split Flow Tol= 0.02
Split Flow Ratio= 0.02
Log Output Level= 0
Friction Slope Method= 1
Unsteady Friction Slope Method= 2
Unsteady Bridges Friction Slope Method= 1
Parabolic Critical Depth
Global Vel Dist=  1 , 1 , 1
Global Log Level= 0
CheckData=True
Encroach Param= -1, 0, 0, 0
BEGIN DESCRIPTION:
Multiple Run
END DESCRIPTION:

--- Clear Creek T 27.f01 (steady flow) ---

Flow Title=Multiple
Number of Profiles=7
Profile Names=10-year,25-year,50-year,1pct_min,100-year,1pct_plu,500-year
River Rch & RM= Clear Creek T 27,Reach-1,5077
     297     387     459     271     541    1080     754
River Rch & RM= Clear Creek T 27,Reach-1,3647
     442     590     709     425     847    1690    1211
Boundary for River Rch & Prof#=Clear Creek T 27,Reach-1,1
Up Type=0
Dn Type=3
Dn Slope=0.005
Boundary for River Rch & Prof#=Clear Creek T 27,Reach-1,2
Up Type=0
Dn Type=3
Dn Slope=0.005
Boundary for River Rch & Prof#=Clear Creek T 27,Reach-1,3
Up Type=0
Dn Type=3
Dn Slope=0.005
Boundary for River Rch & Prof#=Clear Creek T 27,Reach-1,4
Up Type=0
Dn Type=3
Dn Slope=0.005
Boundary for River Rch & Prof#=Clear Creek T 27,Reach-1,5
Up Type=0
Dn Type=3
Dn Slope=0.005
Boundary for River Rch & Prof#=Clear Creek T 27,Reach-1,6
Up Type=0
Dn Type=3
Dn Slope=0.005
Boundary for River Rch & Prof#=Clear Creek T 27,Reach-1,7
Up Type=0
Dn Type=3
Dn Slope=0.005

--- Clear Creek T 27.g01 (geometry) ---

Geom Title=Existing Conditions

River Reach=Clear Creek T 27,Reach-1
Reach XY= 30
      2743426.00      6804261.00      2743376.85      6804170.79
      2743423.52      6804105.45      2743429.83      6804012.58
      2743522.17      6803859.42      2743529.86      6803762.60
      2743573.61      6803705.47      2743579.76      6803562.56
      2743720.13      6803363.28      2743734.18      6803304.96
      2743817.83      6803217.03      2743836.56      6803151.03
      2743926.00      6803111.00      2743926.20      6802285.92
      2743875.55      6802171.19      2743876.21      6801829.27
      2743923.63      6801755.47      2743925.63      6801626.17
      2743777.36      6801401.35      2743774.78      6801171.50
      2743725.56      6801074.82      2743726.70      6800874.91
      2743774.27      6800766.62      2743636.75      6800620.68
      2743584.04      6800514.32      2743668.44      6800311.00
      2743626.66      6800245.84      2743624.78      6799921.50
      2743576.52      6799845.78      2743576.00      6799511.00

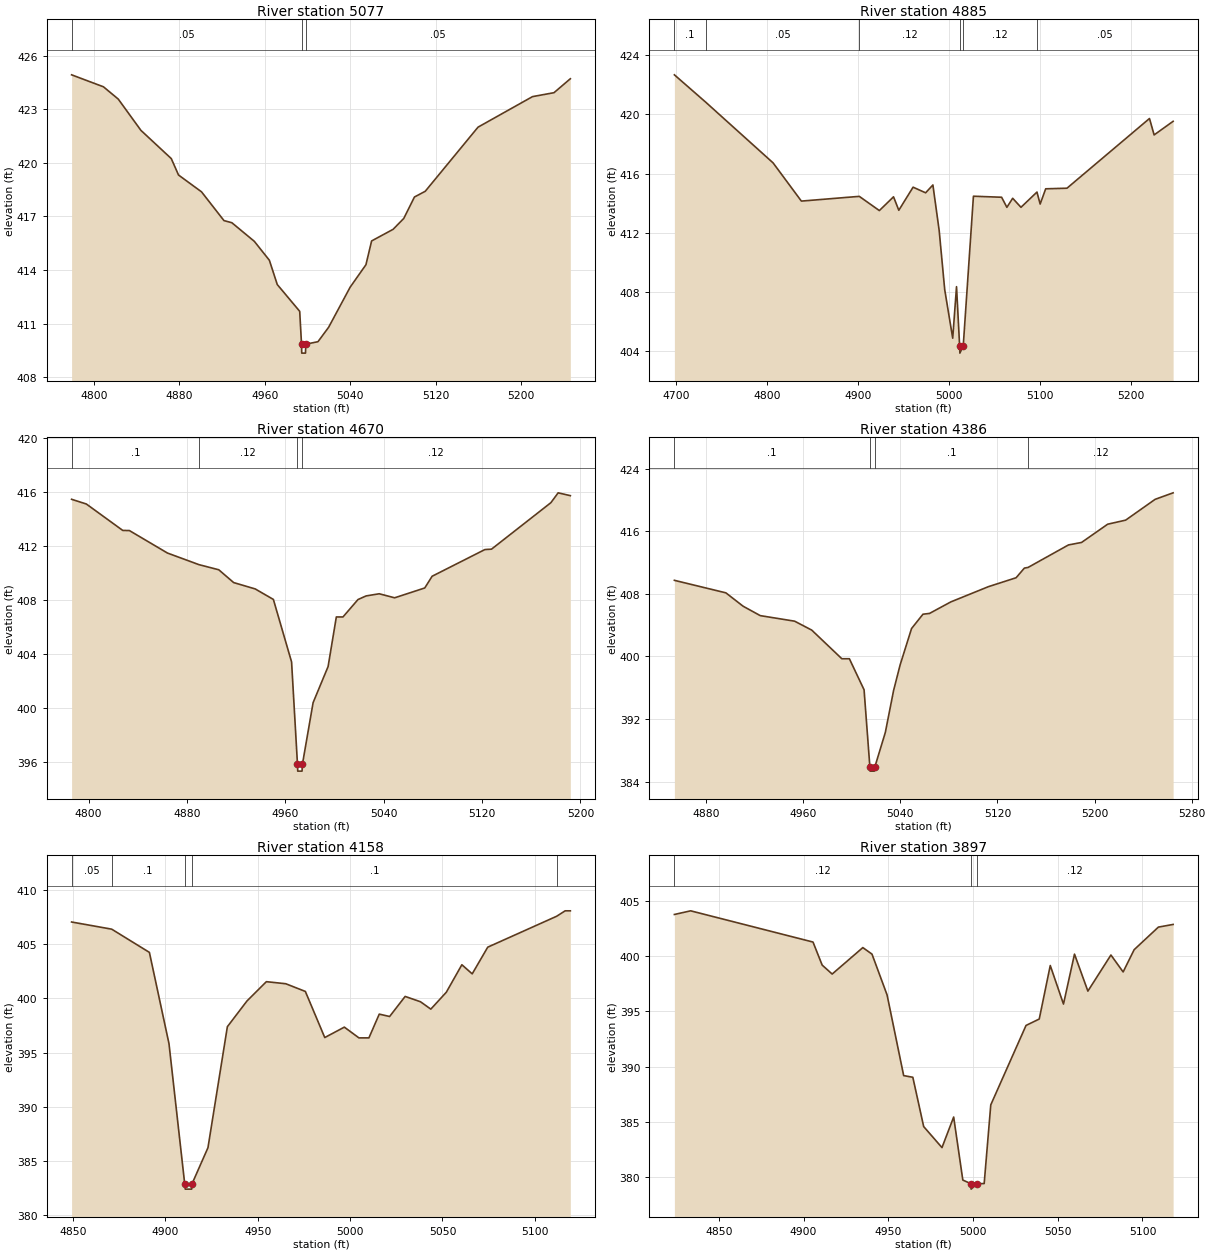
Type RM Length L Ch R = 1,5077,192,192,192
BEGIN DESCRIPTION:
Clear Creek T 27 16.0
END DESCRIPTION:
XS GIS Cut Line= 3
      2743568.14      6804280.53      2743405.82      6804131.00
      2743160.75      6804108.47
#Sta/Elev= 30
  4779.3  424.93  4809.1  424.26  4823.0  423.57  4844.2  421.82  4872.6  420.24
  4879.4  419.32  4900.9  418.38  4921.9  416.77  4929.3  416.65  4950.3  415.61
  4964.4  414.55  4971.8  413.19  4992.8  411.69  4994.5  409.85  4994.7  409.35
  4998.2  409.35  4998.5  409.85  5009.9  409.99  5019.9  410.80  5040.0  413.04
  5054.8  414.30  5060.1  415.63  5080.2  416.28  5090.2  416.89  5100.2  418.09
  5110.3  418.41  5159.7  422.00  5210.7  423.71  5230.8  423.93  5246.1  424.71
#Mann=3,-1,0
  4779.3    0.05       0  4994.5    0.04       0  4998.5    0.05       0
Bank Sta=4994.5,4998.5
Exp/Cntr=0.3,0.1

Type RM Length L Ch R = 1,4885,215,215,215
BEGIN DESCRIPTION:
Mapping XS 26148ccb
END DESCRIPTION:
XS GIS Cut Line= 6
      2743562.21      6804235.75      2743524.28      6804023.18
      2743497.78      6803978.38      2743424.35      6803958.45
      2743335.83      6804016.08      2743244.58      6804002.21
#Sta/Elev= 30
  4697.8  422.67  4732.3  420.82  4806.4  416.72  4837.5  414.14  4901.2  414.46
  4923.3  413.50  4938.9  414.43  4944.7  413.52  4960.4  415.08  4974.2  414.70
  4982.2  415.23  4989.1  412.16  4995.2  408.16  5004.0  404.88  5008.2  408.36
  5011.6  404.37  5011.9  403.87  5015.6  404.37  5026.8  414.47  5057.8  414.40
  5063.6  413.72  5070.0  414.33  5079.1  413.72  5096.7  414.75  5100.2  413.94
  5106.3  414.97  5129.7  415.01  5220.5  419.72  5225.6  418.61  5246.5  419.53
#Mann=6,-1,0
  4697.8     0.1       0  4732.3    0.05       0  4901.2    0.12       0
  5011.6    0.07       0  5015.6    0.12       0  5096.7    0.05       0
Bank Sta=5011.6,5015.6
Exp/Cntr=0.3,0.1

Type RM Length L Ch R = 1,4670,284,284,284
BEGIN DESCRIPTION:
Clear Creek T 27 15.0
END DESCRIPTION:
XS GIS Cut Line= 3
      2743728.39      6803841.96      2743526.00      6803761.00
      2743351.29      6803692.61
#Sta/Elev= 30
  4786.2  415.46  4798.2  415.11  4827.8  413.15  4833.2  413.14  4864.2  411.47
  4889.8  410.61  4905.9  410.23  4918.0  409.28  4935.5  408.81  4950.3  408.03
  4965.1  403.39  4969.9  395.79  4970.1  395.29  4973.6  395.29  4973.9  395.79
  4982.6  400.37  4994.8  403.05  5001.5  406.73  5006.9  406.73  5019.1  408.02
  5025.7  408.29  5036.4  408.45  5048.9  408.15  5073.4  408.88  5079.4  409.75
  5122.3  411.73  5127.7  411.76  5176.0  415.21  5181.9  415.94  5191.8  415.73
#Mann=4,-1,0
  4786.2     0.1       0  4889.8    0.12       0  4969.9    0.07       0
  4973.9    0.12       0
Bank Sta=4969.9,4973.9
Exp/Cntr=0.3,0.1

Type RM Length L Ch R = 1,4386,228,228,228
BEGIN DESCRIPTION:
Clear Creek T 27 14.0
END DESCRIPTION:
XS GIS Cut Line= 3
      2743726.01      6803611.01      2743626.00      6803511.00
      2743375.99      6803411.00
#Sta/Elev= 30
  4854.0  409.72  4896.4  408.12  4910.6  406.41  4924.7  405.21  4953.0  404.50
  4967.1  403.36  4991.9  399.70  4998.1  399.70  5010.2  395.73  5015.0  385.84
  5015.2  385.34  5018.7  385.34  5019.0  385.84  5027.7  390.28  5034.5  395.64
  5039.9  398.92  5049.3  403.56  5058.7  405.39  5064.1  405.49  5081.6  406.96
  5112.6  408.91  5135.4  410.05  5142.2  411.28  5145.3  411.37  5178.5  414.24
  5189.3  414.56  5210.8  416.89  5225.6  417.41  5249.9  420.07  5264.7  420.90
#Mann=4,-1,0
  4854.0     0.1       0  5015.0    0.07       0  5019.0     0.1       0
  5145.3    0.12       0
Bank Sta=5015,5019
Exp/Cntr=0.3,0.1

Type RM Length L Ch R = 1,4158,261,261,261
BEGIN DESCRIPTION:
Clear Creek T 27 13.0
END DESCRIPTION:
XS GIS Cut Line= 3
      2743775.99      6803460.98      2743726.00      6803311.00
      2743626.00      6803261.00
#Sta/Elev= 30
  4849.3  407.05  4871.0  406.39  4891.4  404.25  4902.0  395.84  4910.5  382.93
  4910.8  382.43  4914.3  382.43  4914.5  382.93  4923.1  386.25  4933.6  397.40
  4944.2  399.77  4954.7  401.55  4965.2  401.36  4975.8  400.65  4986.3  396.40
  4996.9  397.36  5004.8  396.37  5010.2  396.37  5015.8  398.56  5021.4  398.34
  5029.8  400.19  5038.1  399.70  5043.7  399.02  5052.1  400.58  5060.5  403.11
  5066.1  402.27  5074.5  404.73  5111.8  407.58  5116.4  408.08  5119.2  408.08
#Mann=5,-1,0
  4849.3    0.05       0  4871.0     0.1       0  4910.5    0.07       0
  4914.5     0.1       0  5111.8    0.12       0
Bank Sta=4910.5,4914.5
Exp/Cntr=0.3,0.1

Type RM Length L Ch R = 1,3897,250,250,250
BEGIN DESCRIPTION:
Clear Creek T 27 12.0
END DESCRIPTION:
XS GIS Cut Line= 3
      2743943.63      6803277.28      2743876.00      6803111.00
      2743802.60      6803022.75
#Sta/Elev= 30
  4823.8  403.74  4833.4  404.07  4905.6  401.25  4911.0  399.17  4916.9  398.36
  4935.0  400.75  4940.4  400.16  4949.3  396.48  4959.1  389.19  4964.5  389.04
  4970.9  384.59  4981.7  382.69  4988.6  385.45  4994.0  379.76  4998.6  379.44
  4998.9  378.94  5002.6  379.44  5006.6  379.44  5010.5  386.55  5031.3  393.72
  5039.1  394.30  5045.6  399.13  5053.4  395.65  5059.9  400.16  5067.8  396.82
  5081.4  400.08  5088.6  398.55  5095.1  400.56  5109.4  402.60  5118.1  402.84
#Mann=3,-1,0
  4823.8    0.12       0  4998.6    0.07       0  5002.6    0.12       0
Bank Sta=4998.6,5002.6
Exp/Cntr=0.3,0.1

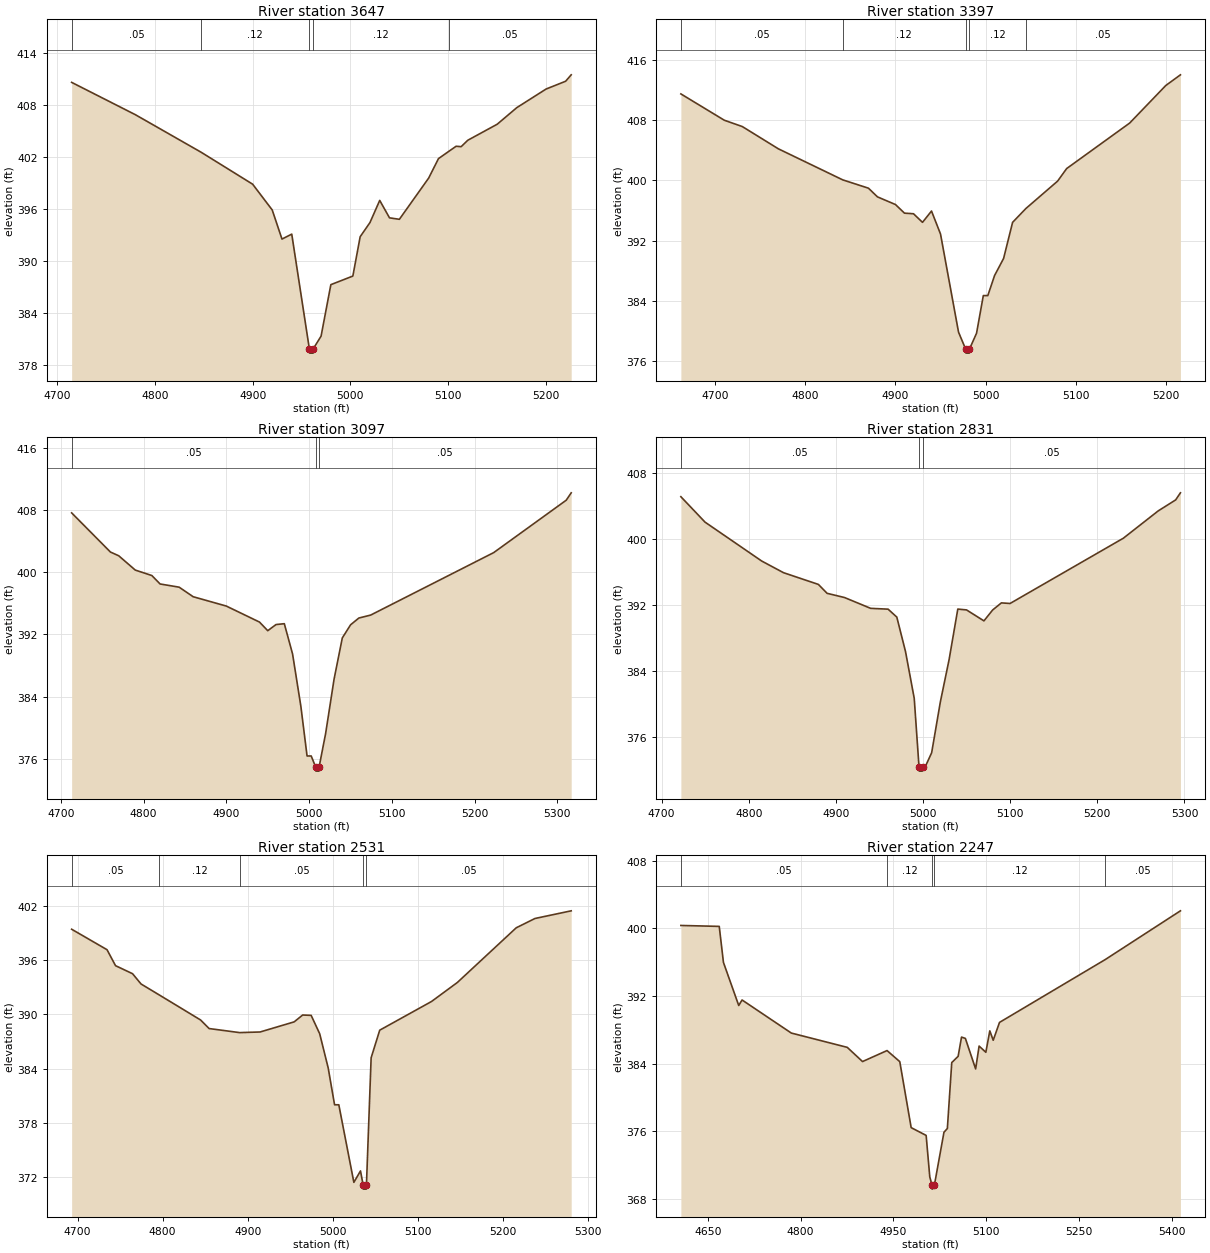
Type RM Length L Ch R = 1,3647,250,250,250
BEGIN DESCRIPTION:
Clear Creek T 27 11.0
END DESCRIPTION:
XS GIS Cut Line= 3
      2744211.20      6802913.05      2743926.00      6802911.00
      2743700.33      6802900.86
#Sta/Elev= 30
  4714.8  410.56  4780.0  406.83  4847.4  402.49  4900.0  398.81  4920.0  395.84
  4930.0  392.48  4940.0  393.05  4958.0  379.82  4958.3  379.32  4961.8  379.32
  4962.0  379.82  4970.0  381.28  4980.0  387.22  5002.5  388.21  5010.0  392.75
  5020.0  394.38  5030.0  396.94  5040.0  394.93  5050.1  394.76  5080.1  399.52
  5090.1  401.76  5100.8  402.61  5108.2  403.19  5113.3  403.14  5120.1  403.88
  5150.2  405.73  5170.2  407.64  5200.2  409.79  5220.2  410.69  5225.9  411.43
#Mann=5,-1,0
  4714.8    0.05       0  4847.4    0.12       0  4958.0    0.07       0
  4962.0    0.12       0  5100.8    0.05       0
Bank Sta=4958,4962
Exp/Cntr=0.3,0.1

Type RM Length L Ch R = 1,3397,300,300,300
BEGIN DESCRIPTION:
Clear Creek T 27 10.0
END DESCRIPTION:
XS GIS Cut Line= 3
      2744264.19      6802664.94      2743926.00      6802661.00
      2743709.72      6802658.60
#Sta/Elev= 30
  4661.8  411.47  4710.0  407.98  4730.0  407.14  4770.0  404.19  4841.5  400.07
  4870.0  398.97  4880.0  397.82  4900.0  396.80  4910.0  395.66  4920.0  395.58
  4930.0  394.44  4940.0  395.94  4950.0  392.89  4970.0  379.88  4978.0  377.60
  4978.3  377.10  4981.8  377.10  4982.0  377.60  4990.0  379.74  4997.5  384.73
  5002.5  384.73  5010.0  387.39  5020.0  389.65  5030.0  394.44  5044.8  396.28
  5080.0  399.91  5090.0  401.57  5160.0  407.61  5200.0  412.58  5216.3  414.00
#Mann=5,-1,0
  4661.8    0.05       0  4841.5    0.12       0  4978.0    0.07       0
  4982.0    0.12       0  5044.8    0.05       0
Bank Sta=4978,4982
Exp/Cntr=0.3,0.1

Type RM Length L Ch R = 1,3097,266,266,266
BEGIN DESCRIPTION:
Clear Creek T 27 9.0
END DESCRIPTION:
XS GIS Cut Line= 3
      2744212.85      6802351.99      2743926.00      6802361.00
      2743610.02      6802382.52
#Sta/Elev= 30
  4713.1  407.63  4760.0  402.59  4770.0  402.11  4790.0  400.27  4810.0  399.57
  4820.0  398.48  4843.0  398.07  4860.0  396.84  4900.0  395.64  4940.1  393.58
  4950.1  392.47  4960.1  393.26  4970.1  393.37  4980.1  389.47  4990.1  382.75
  4997.6  376.35  5002.6  376.35  5008.1  374.90  5008.4  374.40  5011.9  374.40
  5012.1  374.90  5020.1  379.28  5030.2  386.21  5040.2  391.54  5050.2  393.23
  5060.2  394.10  5074.5  394.48  5223.2  402.52  5310.8  409.26  5316.8  410.21
#Mann=3,-1,0
  4713.1    0.05       0  5008.1    0.04       0  5012.1    0.05       0
Bank Sta=5008.1,5012.1
Exp/Cntr=0.3,0.1

Type RM Length L Ch R = 1,2831,300,300,300
BEGIN DESCRIPTION:
Clear Creek T 27 8.0
END DESCRIPTION:
XS GIS Cut Line= 3
      2744153.71      6802118.51      2743876.00      6802111.00
      2743580.54      6802115.19
#Sta/Elev= 30
  4722.1  405.17  4749.8  402.09  4814.9  397.37  4839.9  395.96  4879.9  394.54
  4889.9  393.46  4909.9  392.95  4939.9  391.64  4959.9  391.54  4969.9  390.58
  4979.9  386.40  4989.9  380.73  4995.4  372.41  4995.7  371.91  4999.2  371.91
  4999.4  372.41  5002.4  372.41  5009.9  374.14  5019.9  380.31  5029.9  385.42
  5039.9  391.55  5049.9  391.45  5069.9  390.12  5079.9  391.44  5089.9  392.30
  5099.9  392.23  5229.9  400.14  5269.9  403.45  5289.9  404.78  5295.4  405.64
#Mann=3,-1,0
  4722.1    0.05       0  4995.4    0.04       0  4999.4    0.05       0
Bank Sta=4995.4,4999.4
Exp/Cntr=0.3,0.1

Type RM Length L Ch R = 1,2531,284,284,284
BEGIN DESCRIPTION:
Clear Creek T 27 7.0
END DESCRIPTION:
XS GIS Cut Line= 3
      2744187.57      6801811.06      2743876.00      6801811.00
      2743603.97      6801856.00
#Sta/Elev= 30
  4693.0  399.44  4734.6  397.17  4744.6  395.40  4764.6  394.51  4774.6  393.37
  4796.1  392.15  4844.6  389.38  4854.6  388.43  4890.5  387.98  4914.6  388.05
  4954.6  389.17  4964.6  389.93  4974.6  389.89  4984.6  387.86  4994.6  384.07
  5002.1  379.98  5007.1  379.98  5024.8  371.38  5032.6  372.65  5035.6  371.13
  5035.9  370.63  5039.4  370.63  5039.6  371.13  5045.1  385.19  5055.2  388.25
  5116.1  391.43  5146.5  393.54  5215.7  399.60  5237.7  400.63  5280.3  401.48
#Mann=5,-1,0
  4693.0    0.05       0  4796.1    0.12       0  4890.5    0.05       0
  5035.6    0.04       0  5039.6    0.05       0
Bank Sta=5035.6,5039.6
Exp/Cntr=0.3,0.1

Type RM Length L Ch R = 1,2247,405,405,405
BEGIN DESCRIPTION:
Clear Creek T 27 6.0
END DESCRIPTION:
XS GIS Cut Line= 3
      2744243.92      6801421.02      2743876.00      6801561.00
      2743500.97      6801735.77
#Sta/Elev= 30
  4606.4  400.34  4668.4  400.23  4675.2  395.97  4699.9  390.88  4705.3  391.53
  4784.9  387.62  4875.3  385.93  4900.0  384.25  4939.6  385.55  4960.2  384.24
  4978.6  376.44  5002.8  375.52  5008.7  370.61  5012.2  369.67  5012.5  369.17
  5016.2  369.67  5031.6  375.89  5037.1  376.34  5044.2  384.13  5054.5  384.87
  5060.0  387.14  5066.2  386.99  5082.8  383.38  5088.4  386.08  5099.3  385.35
  5105.7  387.88  5111.2  386.77  5121.4  388.88  5292.1  396.30  5413.8  402.07
#Mann=5,-1,0
  4606.4    0.05       0  4939.6    0.12       0  5012.2    0.07       0
  5016.2    0.12       0  5292.1    0.05       0
Bank Sta=5012.2,5016.2
Exp/Cntr=0.3,0.1

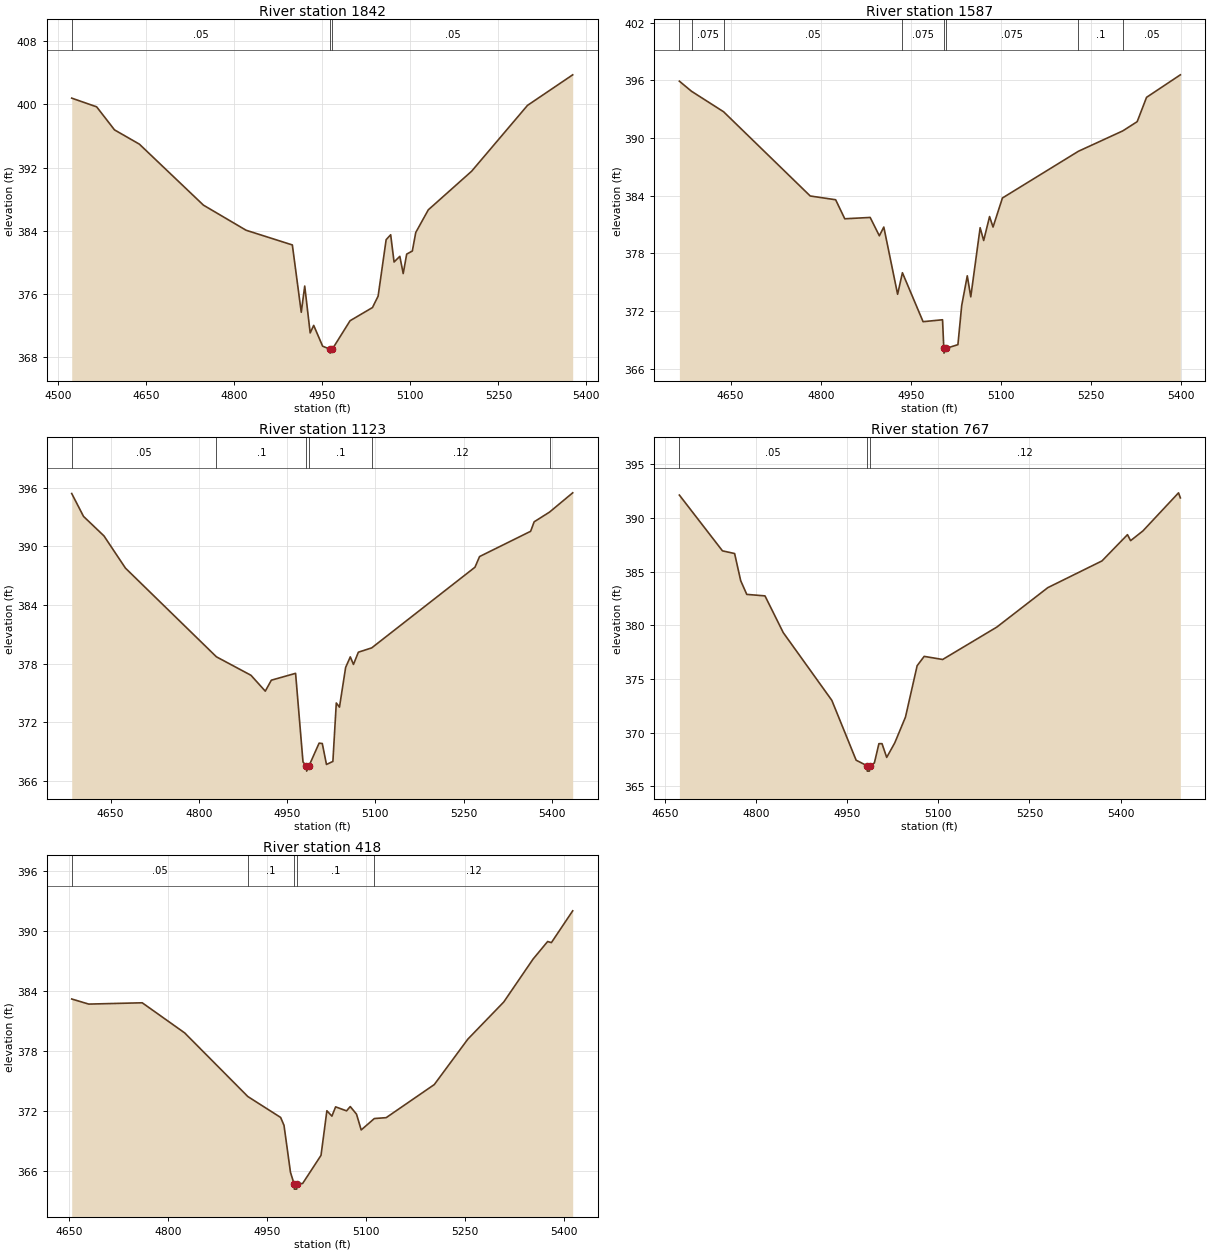
Type RM Length L Ch R = 1,1842,255,255,255
BEGIN DESCRIPTION:
Clear Creek T 27 5.0
END DESCRIPTION:
XS GIS Cut Line= 3
      2744179.02      6800934.58      2743776.36      6801190.85
      2743453.43      6801384.82
#Sta/Elev= 30
  4522.7  400.78  4565.2  399.68  4595.7  396.76  4638.0  394.96  4747.2  387.24
  4820.0  384.06  4898.8  382.20  4914.0  373.68  4919.9  377.00  4929.2  371.07
  4935.2  372.02  4950.4  369.39  4962.9  369.01  4963.1  368.51  4966.9  369.01
  4997.2  372.61  5035.4  374.28  5045.0  375.72  5058.7  382.87  5066.4  383.49
  5072.2  380.04  5082.0  380.76  5087.8  378.58  5093.7  381.04  5103.3  381.43
  5109.2  383.78  5130.5  386.64  5204.4  391.53  5299.6  399.86  5376.7  403.73
#Mann=3,-1,0
  4522.7    0.05       0  4962.9    0.03       0  4966.9    0.05       0
Bank Sta=4962.9,4966.9
Exp/Cntr=0.3,0.1

Type RM Length L Ch R = 1,1587,464,464,464
BEGIN DESCRIPTION:
Clear Creek T 27 4.0
END DESCRIPTION:
XS GIS Cut Line= 3
      2744093.01      6800717.78      2743725.89      6800951.87
      2743382.43      6801154.54
#Sta/Elev= 30
  4564.6  395.90  4584.8  394.85  4638.2  392.72  4782.5  383.96  4824.8  383.57
  4840.0  381.59  4882.3  381.73  4897.6  379.82  4905.0  380.73  4928.0  373.74
  4936.0  375.98  4970.4  370.89  5002.8  371.09  5004.9  368.12  5005.2  367.62
  5008.9  368.12  5028.4  368.50  5034.7  372.57  5044.0  375.66  5049.8  373.47
  5065.4  380.66  5071.3  379.33  5081.1  381.82  5086.9  380.73  5102.5  383.75
  5229.0  388.61  5302.9  390.73  5326.9  391.69  5342.5  394.22  5398.8  396.56
#Mann=8,-1,0
  4564.6    0.05       0  4584.8   0.075       0  4638.2    0.05       0
  4936.0   0.075       0  5004.9    0.07       0  5008.9   0.075       0
  5229.0     0.1       0  5302.9    0.05       0
Bank Sta=5004.9,5008.9
Exp/Cntr=0.3,0.1

Type RM Length L Ch R = 1,1123,356,356,356
BEGIN DESCRIPTION:
Clear Creek T 27 3.0
END DESCRIPTION:
XS GIS Cut Line= 3
      2744025.57      6800463.31      2743626.00      6800561.00
      2743220.03      6800731.09
#Sta/Elev= 30
  4583.9  395.39  4604.0  393.05  4638.7  391.06  4675.2  387.77  4829.8  378.71
  4888.6  376.82  4912.9  375.20  4923.2  376.32  4964.4  377.02  4977.0  367.97
  4982.9  367.53  4983.2  367.03  4986.9  367.53  5004.4  369.89  5009.8  369.85
  5016.9  367.71  5027.8  368.02  5033.6  373.99  5039.0  373.57  5049.5  377.63
  5057.4  378.70  5062.8  377.93  5071.1  379.18  5093.8  379.62  5269.3  387.86
  5277.1  388.95  5363.9  391.53  5369.9  392.50  5396.0  393.49  5435.4  395.46
#Mann=6,-1,0
  4583.9    0.05       0  4829.8     0.1       0  4982.9    0.07       0
  4986.9     0.1       0  5093.8    0.12       0  5396.0     0.1       0
Bank Sta=4982.9,4986.9
Exp/Cntr=0.3,0.1

Type RM Length L Ch R = 1,767,349,349,349
BEGIN DESCRIPTION:
Clear Creek T 27 2.0
END DESCRIPTION:
XS GIS Cut Line= 3
      2743956.92      6800257.31      2743626.00      6800261.00
      2743146.08      6800376.23
#Sta/Elev= 30
  4673.8  392.14  4744.7  386.94  4764.7  386.69  4774.7  384.16  4784.7  382.88
  4814.7  382.74  4844.7  379.32  4924.7  373.00  4964.7  367.42  4982.7  366.90
  4983.0  366.40  4986.5  366.40  4986.7  366.90  4994.7  367.16  5002.2  368.96
  5007.3  368.96  5015.0  367.68  5028.3  369.04  5045.9  371.44  5065.1  376.23
  5076.7  377.10  5107.1  376.81  5196.2  379.83  5280.2  383.51  5369.3  386.00
  5411.3  388.45  5416.4  387.89  5436.7  388.80  5495.3  392.35  5498.3  391.88
#Mann=3,-1,0
  4673.8    0.05       0  4982.7    0.07       0  4986.7    0.12       0
Bank Sta=4982.7,4986.7
Exp/Cntr=0.3,0.1

Type RM Length L Ch R = 1,418,0,0,0
BEGIN DESCRIPTION:
Clear Creek T 27 1.0
END DESCRIPTION:
XS GIS Cut Line= 3
      2743960.67      6799980.32      2743626.00      6799911.00
      2743254.61      6800102.00
#Sta/Elev= 30
  4654.1  383.23  4679.9  382.72  4761.0  382.85  4825.3  379.84  4921.1  373.47
  4970.8  371.38  4975.9  370.59  4985.7  365.89  4991.3  364.71  4991.6  364.21
  4995.1  364.21  4995.3  364.71  5004.2  364.78  5032.0  367.59  5040.9  372.05
  5048.5  371.51  5054.1  372.44  5070.7  372.04  5076.3  372.47  5085.8  371.71
  5092.9  370.13  5112.8  371.27  5130.8  371.36  5203.7  374.67  5254.5  379.21
  5309.0  382.93  5353.4  387.22  5375.5  388.98  5381.2  388.87  5413.5  392.05
#Mann=5,-1,0
  4654.1    0.05       0  4921.1     0.1       0  4991.3    0.07       0
  4995.3     0.1       0  5112.8    0.12       0
Bank Sta=4991.3,4995.3
Exp/Cntr=0.3,0.1

Chan Stop Cuts=-1