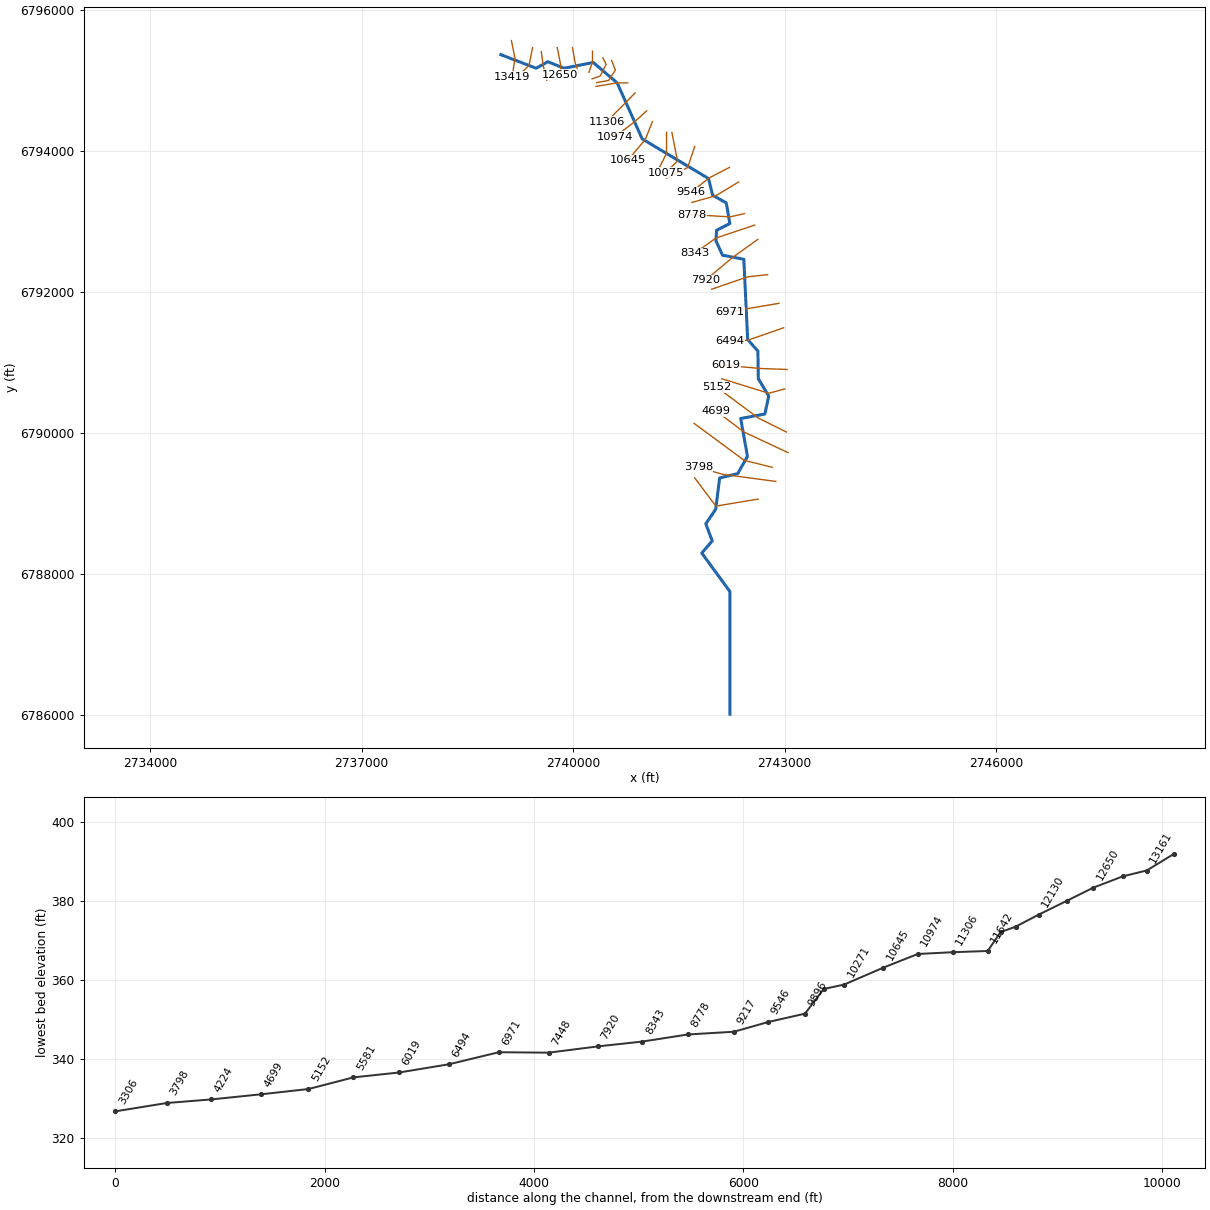
--- Clear Creek T 28.prj (project) ---

Proj Title=Clear Creek T 28 Base Level Engineering
Current Plan=p01
Default Exp/Contr=0.3,0.1
English Units
Geom File=g01
Flow File=f01
Plan File=p01
Y Axis Title=Elevation
X Axis Title(PF)=Main Channel Distance
X Axis Title(XS)=Station
BEGIN DESCRIPTION:
Clear Creek T 28
END DESCRIPTION:
DSS Export Rating Curves= 0
DSS Export Rating Curve Sorted= 0
DSS Export Volume Flow Curves= 0
DXF OffsetX= 0
DXF OffsetY= 0
DXF ScaleX= 1
DXF ScaleY= 10

--- Clear Creek T 28.p01 (plan) ---

Plan Title=Multiple Run
Short Identifier=Multiple
Geom File=g01
Flow File=f01
Subcritical Flow
K Sum by GR= 0
Std Step Tol= 0.01
Critical Tol= 0.01
Num of Std Step Trials= 20
Max Error Tol= 0.3
Flow Tol Ratio= 0.001
Split Flow NTrial= 30
Split Flow Tol= 0.02
Split Flow Ratio= 0.02
Log Output Level= 0
Friction Slope Method= 1
Unsteady Friction Slope Method= 2
Unsteady Bridges Friction Slope Method= 1
Parabolic Critical Depth
Global Vel Dist=  1 , 1 , 1
Global Log Level= 0
CheckData=True
Encroach Param= -1, 0, 0, 0
BEGIN DESCRIPTION:
Multiple Run
END DESCRIPTION:

--- Clear Creek T 28.f01 (steady flow) ---

Flow Title=Multiple
Number of Profiles=7
Profile Names=10-year,25-year,50-year,1pct_min,100-year,1pct_plu,500-year
River Rch & RM= Clear Creek T 28,Reach-1,13419
     133     160     179     101     201     400     249
River Rch & RM= Clear Creek T 28,Reach-1,11642
     435     572     681     403     805    1605    1120
River Rch & RM= Clear Creek T 28,Reach-1,10974
     502     666     798     474     947    1889    1332
River Rch & RM= Clear Creek T 28,Reach-1,9896
     593     805     981     594    1185    2364    1734
River Rch & RM= Clear Creek T 28,Reach-1,8778
     696     947    1153     697    1391    2776    2031
Boundary for River Rch & Prof#=Clear Creek T 28,Reach-1,1
Up Type=0
Dn Type=3
Dn Slope=0.005
Boundary for River Rch & Prof#=Clear Creek T 28,Reach-1,2
Up Type=0
Dn Type=3
Dn Slope=0.005
Boundary for River Rch & Prof#=Clear Creek T 28,Reach-1,3
Up Type=0
Dn Type=3
Dn Slope=0.005
Boundary for River Rch & Prof#=Clear Creek T 28,Reach-1,4
Up Type=0
Dn Type=3
Dn Slope=0.005
Boundary for River Rch & Prof#=Clear Creek T 28,Reach-1,5
Up Type=0
Dn Type=3
Dn Slope=0.005
Boundary for River Rch & Prof#=Clear Creek T 28,Reach-1,6
Up Type=0
Dn Type=3
Dn Slope=0.005
Boundary for River Rch & Prof#=Clear Creek T 28,Reach-1,7
Up Type=0
Dn Type=3
Dn Slope=0.005

--- Clear Creek T 28.g01 (geometry) ---

Geom Title=Existing Conditions

River Reach=Clear Creek T 28,Reach-1
Reach XY= 30
      2738976.00      6795361.00      2739476.00      6795168.50
      2739641.22      6795260.51      2739875.92      6795168.30
      2740286.38      6795250.03      2740626.00      6794961.00
      2740981.19      6794166.44      2741921.19      6793605.38
      2741979.70      6793369.18      2742172.93      6793259.57
      2742224.13      6792966.69      2742036.32      6792871.17
      2742027.20      6792721.51      2742119.50      6792518.72
      2742422.55      6792459.81      2742477.04      6791321.44
      2742622.39      6791159.50      2742627.91      6790766.72
      2742776.50      6790521.17      2742720.75      6790266.44
      2742378.47      6790202.91      2742473.83      6789666.45
      2742336.17      6789421.32      2742079.51      6789359.75
      2742023.65      6788916.52      2741883.32      6788711.09
      2741974.07      6788466.97      2741825.89      6788295.64
      2742224.80      6787750.50      2742226.00      6786011.00

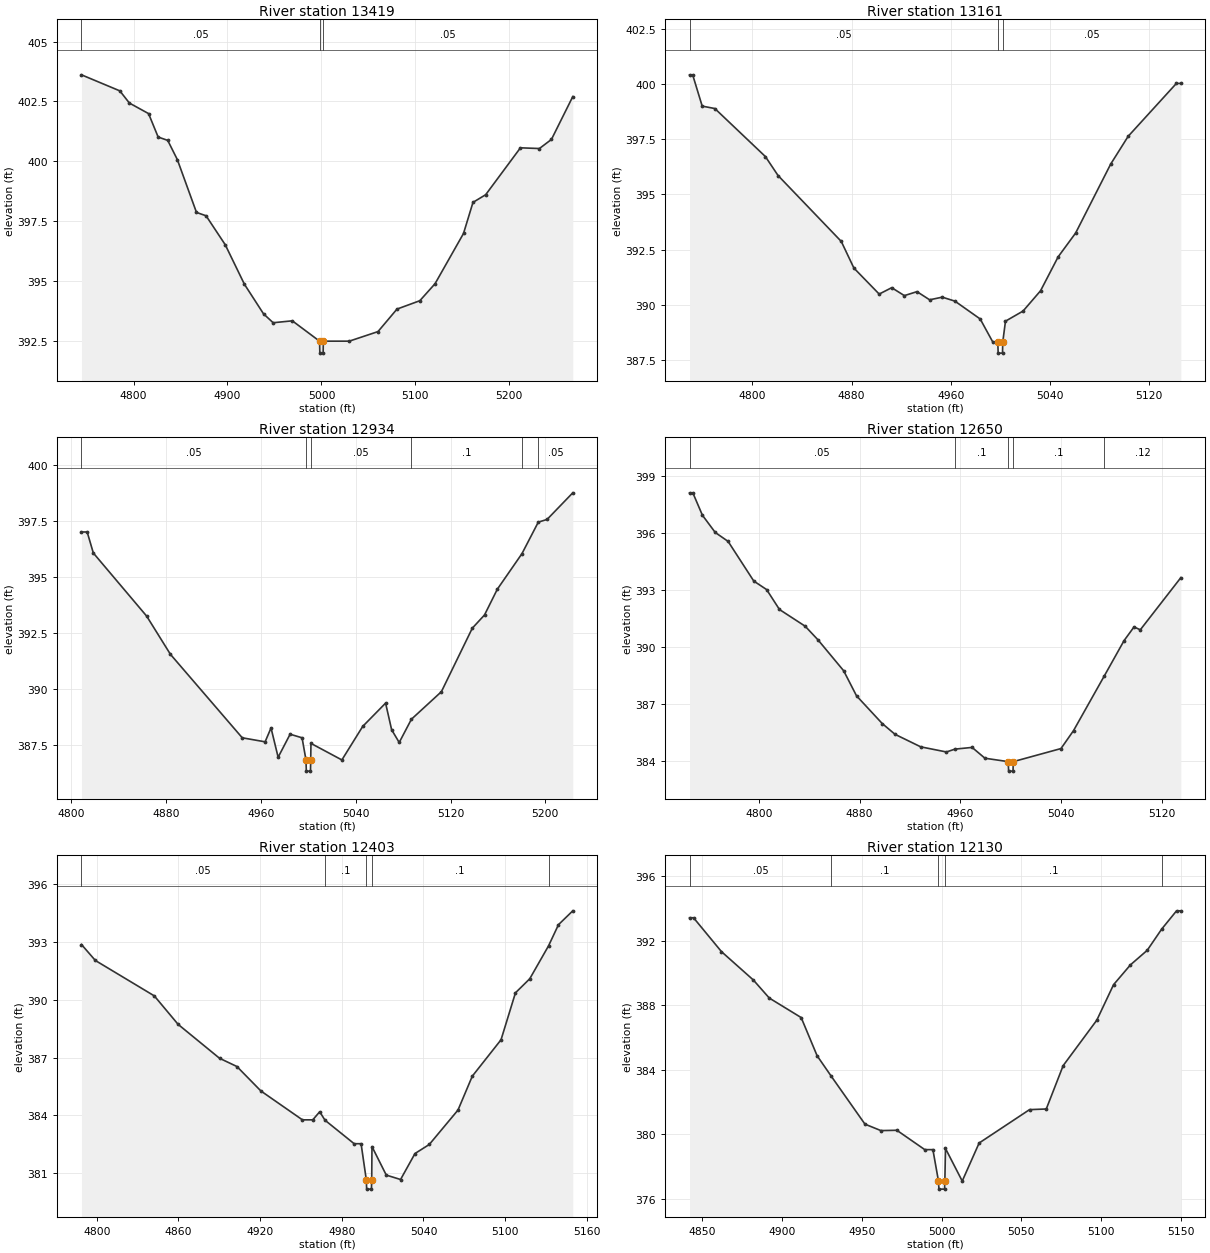
Type RM Length L Ch R = 1,13419,258,258,258
BEGIN DESCRIPTION:
Clear Creek T 28 31.0
END DESCRIPTION:
XS GIS Cut Line= 3
      2739125.99      6795561.05      2739176.00      6795311.00
      2739137.40      6795045.89
#Sta/Elev= 30
  4744.6  403.61  4785.4  402.94  4795.6  402.43  4816.0  401.99  4826.2  401.01
  4836.4  400.87  4846.6  400.07  4867.0  397.86  4877.2  397.72  4897.6  396.51
  4918.0  394.86  4938.4  393.62  4948.6  393.25  4969.0  393.33  4998.0  392.48
  4998.3  391.98  5001.8  391.98  5002.0  392.48  5029.6  392.48  5060.2  392.88
  5080.4  393.82  5104.7  394.17  5120.9  394.88  5151.2  396.98  5161.3  398.28
  5174.8  398.60  5211.8  400.56  5232.0  400.53  5244.8  400.91  5267.5  402.70
#Mann=3,-1,0
  4744.6    0.05       0  4998.0    0.04       0  5002.0    0.05       0
Bank Sta=4998,5002
Exp/Cntr=0.3,0.1

Type RM Length L Ch R = 1,13161,227,227,227
BEGIN DESCRIPTION:
Clear Creek T 28 30.0
END DESCRIPTION:
XS GIS Cut Line= 3
      2739426.00      6795460.98      2739376.00      6795211.00
      2739275.97      6795110.97
#Sta/Elev= 30
  4749.3  400.43  4751.8  400.43  4759.5  399.01  4769.7  398.90  4810.5  396.72
  4820.7  395.86  4871.7  392.87  4881.9  391.66  4902.3  390.48  4912.4  390.77
  4922.6  390.41  4932.8  390.59  4943.0  390.22  4953.2  390.34  4963.4  390.16
  4983.8  389.35  4994.0  388.30  4998.0  388.30  4998.3  387.80  5001.8  387.80
  5002.0  388.30  5004.2  389.25  5018.4  389.71  5032.5  390.63  5046.7  392.17
  5060.8  393.25  5089.1  396.38  5103.2  397.64  5142.1  400.04  5145.7  400.04
#Mann=3,-1,0
  4749.3    0.05       0  4998.0    0.04       0  5002.0    0.05       0
Bank Sta=4998,5002
Exp/Cntr=0.3,0.1

Type RM Length L Ch R = 1,12934,284,284,284
BEGIN DESCRIPTION:
Clear Creek T 28 29.0
END DESCRIPTION:
XS GIS Cut Line= 3
      2739549.60      6795405.46      2739576.00      6795211.00
      2739626.94      6794998.57
#Sta/Elev= 30
  4808.5  397.02  4813.3  397.02  4818.5  396.08  4863.5  393.26  4883.6  391.55
  4944.2  387.82  4963.5  387.64  4968.5  388.26  4974.5  386.95  4984.6  387.98
  4994.7  387.82  4998.0  386.83  4998.3  386.33  5001.8  386.33  5002.0  386.83
  5002.2  387.57  5028.3  386.83  5045.9  388.33  5065.2  389.37  5070.3  388.18
  5076.7  387.61  5087.0  388.65  5112.3  389.88  5138.4  392.72  5148.7  393.31
  5159.5  394.46  5180.3  396.05  5194.1  397.46  5201.5  397.58  5223.2  398.77
#Mann=6,-1,0
  4808.5    0.05       0  4998.0    0.04       0  5002.0    0.05       0
  5087.0     0.1       0  5180.3    0.12       0  5194.1    0.05       0
Bank Sta=4998,5002
Exp/Cntr=0.3,0.1

Type RM Length L Ch R = 1,12650,247,247,247
BEGIN DESCRIPTION:
Clear Creek T 28 28.0
END DESCRIPTION:
XS GIS Cut Line= 3
      2739776.00      6795461.02      2739826.00      6795211.00
      2739819.29      6795075.94
#Sta/Elev= 30
  4744.9  398.11  4747.5  398.11  4755.1  396.93  4765.3  396.02  4775.5  395.55
  4795.9  393.46  4806.1  393.01  4816.3  391.96  4836.7  391.08  4846.9  390.36
  4867.3  388.73  4877.5  387.41  4897.9  385.95  4908.1  385.38  4928.5  384.72
  4948.9  384.45  4955.7  384.60  4969.3  384.69  4979.5  384.12  4998.0  383.94
  4998.3  383.44  5001.8  383.44  5002.0  383.94  5039.9  384.63  5049.9  385.58
  5074.4  388.47  5090.0  390.32  5097.9  391.04  5102.9  390.89  5135.1  393.64
#Mann=5,-1,0
  4744.9    0.05       0  4955.7     0.1       0  4998.0    0.07       0
  5002.0     0.1       0  5074.4    0.12       0
Bank Sta=4998,5002
Exp/Cntr=0.3,0.1

Type RM Length L Ch R = 1,12403,273,273,273
BEGIN DESCRIPTION:
Clear Creek T 28 27.0
END DESCRIPTION:
XS GIS Cut Line= 3
      2739992.56      6795461.04      2740026.00      6795261.00
      2740075.99      6795111.03
#Sta/Elev= 30
  4788.8  392.88  4799.0  392.05  4842.3  390.21  4859.8  388.73  4890.2  386.97
  4903.0  386.54  4920.6  385.27  4951.1  383.77  4958.7  383.77  4963.8  384.19
  4967.7  383.75  4989.1  382.53  4994.2  382.53  4998.0  380.67  4998.3  380.17
  5001.8  380.17  5002.0  380.67  5002.2  382.38  5012.7  380.90  5023.2  380.67
  5033.8  382.02  5044.3  382.49  5065.4  384.28  5075.9  386.04  5097.0  387.93
  5107.6  390.37  5118.1  391.10  5131.9  392.81  5139.2  393.91  5149.7  394.63
#Mann=5,-1,0
  4788.8    0.05       0  4967.7     0.1       0  4998.0    0.07       0
  5002.0     0.1       0  5131.9    0.12       0
Bank Sta=4998,5002
Exp/Cntr=0.3,0.1

Type RM Length L Ch R = 1,12130,220,220,220
BEGIN DESCRIPTION:
Clear Creek T 28 26.0
END DESCRIPTION:
XS GIS Cut Line= 3
      2740276.00      6795410.96      2740276.00      6795261.00
      2740225.99      6795110.98
#Sta/Elev= 30
  4841.9  393.44  4844.4  393.44  4861.9  391.34  4881.9  389.58  4891.9  388.46
  4911.9  387.25  4921.9  384.88  4930.7  383.62  4951.9  380.64  4961.9  380.24
  4971.9  380.26  4989.4  379.06  4994.5  379.06  4998.0  377.11  4998.3  376.61
  5001.8  376.61  5002.0  377.11  5002.4  379.13  5012.9  377.11  5023.5  379.47
  5055.1  381.54  5065.6  381.58  5076.2  384.27  5097.3  387.09  5107.8  389.29
  5118.4  390.52  5128.9  391.42  5138.0  392.74  5147.3  393.87  5150.0  393.87
#Mann=5,-1,0
  4841.9    0.05       0  4930.7     0.1       0  4998.0    0.07       0
  5002.0     0.1       0  5138.0    0.12       0
Bank Sta=4998,5002
Exp/Cntr=0.3,0.1

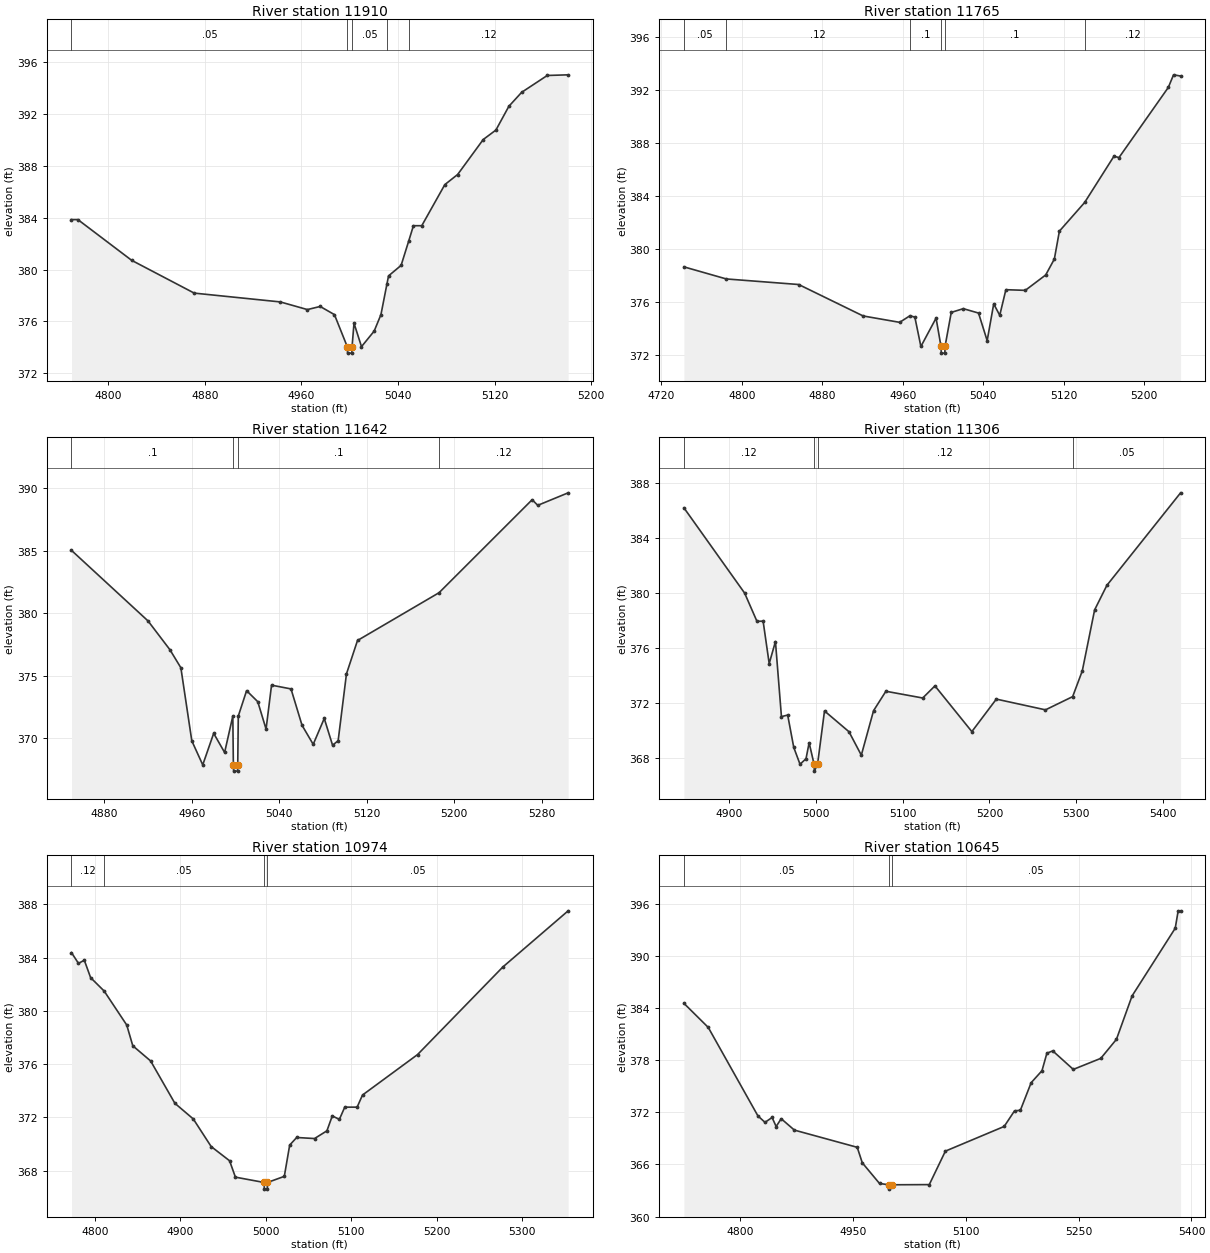
Type RM Length L Ch R = 1,11910,145,145,145
BEGIN DESCRIPTION:
Mapping XS 49787fcd
END DESCRIPTION:
XS GIS Cut Line= 4
      2740423.11      6795315.49      2740469.45      6795223.47
      2740386.93      6795059.15      2740269.70      6795017.83
#Sta/Elev= 30
  4769.7  383.86  4775.0  383.86  4819.5  380.72  4871.3  378.19  4942.6  377.51
  4965.0  376.92  4975.6  377.16  4987.4  376.53  4998.0  374.06  4998.3  373.56
  5001.8  373.56  5002.0  374.06  5003.6  375.87  5009.8  374.06  5020.3  375.26
  5025.9  376.53  5030.8  378.86  5032.2  379.52  5042.6  380.33  5048.8  382.18
  5052.8  383.39  5059.7  383.39  5078.8  386.56  5089.4  387.34  5110.6  390.04
  5121.1  390.77  5131.8  392.60  5142.4  393.68  5163.6  394.98  5180.9  395.03
#Mann=5,-1,0
  4769.7    0.05       0  4998.0    0.04       0  5002.0    0.05       0
  5030.8     0.1       0  5048.8    0.12       0
Bank Sta=4998,5002
Exp/Cntr=0.3,0.1

Type RM Length L Ch R = 1,11765,123,123,123
BEGIN DESCRIPTION:
Mapping XS a734dac3
END DESCRIPTION:
XS GIS Cut Line= 4
      2740547.25      6795277.27      2740600.11      6795142.15
      2740504.31      6794994.84      2740333.96      6794964.80
#Sta/Elev= 30
  4742.4  378.66  4784.5  377.75  4856.5  377.33  4920.6  374.96  4956.9  374.48
  4967.2  374.98  4972.0  374.87  4978.0  372.66  4993.1  374.80  4998.0  372.66
  4998.3  372.16  5001.8  372.16  5002.0  372.66  5008.2  375.23  5020.2  375.51
  5035.3  375.18  5043.9  373.10  5050.4  375.87  5056.4  375.01  5062.5  376.94
  5081.8  376.89  5102.1  378.05  5110.7  379.25  5115.7  381.35  5140.8  383.51
  5169.9  386.99  5175.0  386.90  5224.0  392.18  5229.2  393.13  5236.2  393.04
#Mann=6,-1,0
  4742.4    0.05       0  4784.5    0.12       0  4967.2     0.1       0
  4998.0    0.07       0  5002.0     0.1       0  5140.8    0.12       0
Bank Sta=4998,5002
Exp/Cntr=0.3,0.1

Type RM Length L Ch R = 1,11642,336,336,336
BEGIN DESCRIPTION:
Clear Creek T 28 24.0
END DESCRIPTION:
XS GIS Cut Line= 3
      2740776.00      6794961.00      2740626.00      6794961.00
      2740326.04      6794911.01
#Sta/Elev= 30
  4850.0  385.01  4920.0  379.37  4940.0  377.07  4950.0  375.63  4960.0  369.79
  4970.0  367.87  4980.0  370.39  4990.0  368.86  4997.5  371.77  4998.0  367.87
  4998.3  367.37  5001.8  367.37  5002.0  367.87  5002.5  371.77  5010.1  373.80
  5020.3  372.92  5027.9  370.73  5032.9  374.24  5050.7  373.94  5060.8  371.03
  5071.0  369.51  5081.1  371.58  5088.7  369.44  5093.8  369.80  5101.4  375.14
  5111.5  377.81  5186.1  381.63  5271.2  389.06  5276.3  388.61  5304.1  389.61
#Mann=4,-1,0
  4850.0     0.1       0  4998.0    0.07       0  5002.0     0.1       0
  5186.1    0.12       0
Bank Sta=4998,5002
Exp/Cntr=0.3,0.1

Type RM Length L Ch R = 1,11306,332,332,332
BEGIN DESCRIPTION:
Clear Creek T 28 23.0
END DESCRIPTION:
XS GIS Cut Line= 3
      2740878.80      6794817.07      2740776.00      6794711.00
      2740475.98      6794410.98
#Sta/Elev= 30
  4848.1  386.18  4918.0  379.99  4932.2  377.94  4939.3  377.95  4946.3  374.87
  4953.5  376.47  4960.4  371.02  4967.6  371.13  4974.6  368.78  4981.8  367.56
  4988.7  367.96  4992.3  369.12  4998.0  367.56  4998.3  367.06  5002.0  367.56
  5010.0  371.43  5038.2  369.92  5052.4  368.22  5066.5  371.45  5080.7  372.86
  5123.1  372.37  5137.2  373.25  5179.7  369.93  5207.9  372.29  5264.5  371.51
  5295.8  372.47  5306.9  374.34  5321.1  378.77  5335.2  380.55  5420.1  387.27
#Mann=4,-1,0
  4848.1    0.12       0  4998.0    0.07       0  5002.0    0.12       0
  5295.8    0.05       0
Bank Sta=4998,5002
Exp/Cntr=0.3,0.1

Type RM Length L Ch R = 1,10974,329,329,329
BEGIN DESCRIPTION:
Clear Creek T 28 22.0
END DESCRIPTION:
XS GIS Cut Line= 3
      2741043.68      6794564.68      2740876.00      6794411.00
      2740593.41      6794197.21
#Sta/Elev= 30
  4772.4  384.38  4780.6  383.57  4787.4  383.81  4794.8  382.50  4810.7  381.49
  4837.1  378.94  4844.2  377.38  4865.1  376.24  4893.5  373.06  4915.1  371.88
  4936.0  369.81  4957.6  368.74  4964.4  367.51  4998.0  367.11  4998.3  366.61
  5001.8  366.61  5002.0  367.11  5021.7  367.57  5028.0  369.92  5036.2  370.49
  5057.1  370.41  5071.6  370.99  5077.9  372.11  5086.2  371.85  5092.5  372.77
  5107.0  372.77  5113.3  373.68  5177.8  376.72  5277.7  383.30  5354.2  387.52
#Mann=4,-1,0
  4772.4    0.12       0  4810.7    0.05       0  4998.0    0.04       0
  5002.0    0.05       0
Bank Sta=4998,5002
Exp/Cntr=0.3,0.1

Type RM Length L Ch R = 1,10645,374,374,374
BEGIN DESCRIPTION:
Clear Creek T 28 21.0
END DESCRIPTION:
XS GIS Cut Line= 3
      2741125.99      6794410.97      2741026.00      6794161.00
      2740776.03      6793861.03
#Sta/Elev= 30
  4725.8  384.52  4758.1  381.75  4824.1  371.57  4833.5  370.83  4842.9  371.39
  4848.3  370.35  4855.0  371.25  4872.5  369.94  4956.0  367.96  4962.7  366.18
  4985.6  363.80  4998.0  363.65  4998.3  363.15  5002.0  363.65  5051.7  363.67
  5073.1  367.52  5151.2  370.36  5164.9  372.15  5172.7  372.22  5187.0  375.39
  5201.4  376.77  5207.9  378.78  5215.7  379.05  5243.0  376.92  5279.5  378.19
  5300.3  380.38  5321.1  385.38  5378.4  393.16  5382.3  395.16  5385.5  395.16
#Mann=3,-1,0
  4725.8    0.05       0  4998.0    0.04       0  5002.0    0.05       0
Bank Sta=4998,5002
Exp/Cntr=0.3,0.1

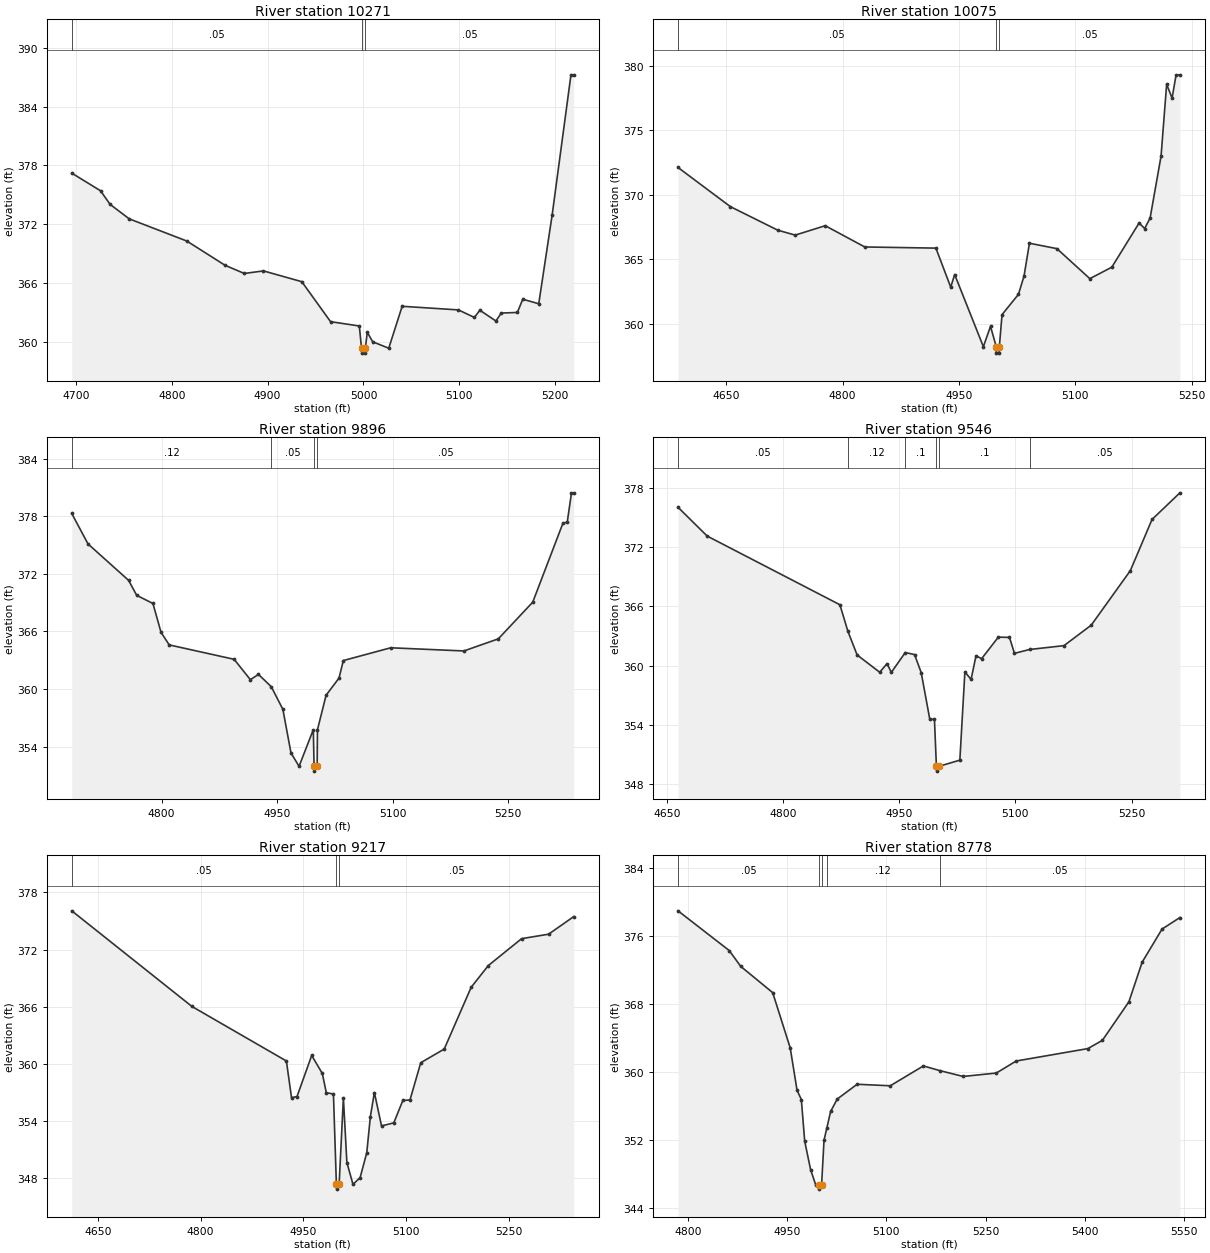
Type RM Length L Ch R = 1,10271,196,196,196
BEGIN DESCRIPTION:
Clear Creek T 28 20.0
END DESCRIPTION:
XS GIS Cut Line= 3
      2741326.00      6794260.95      2741326.00      6793961.00
      2741225.98      6793760.96
#Sta/Elev= 30
  4695.7  377.22  4725.7  375.42  4735.7  374.03  4755.7  372.55  4815.7  370.29
  4855.7  367.81  4875.7  366.98  4895.7  367.24  4935.7  366.14  4965.7  362.06
  4995.7  361.62  4998.0  359.35  4998.3  358.85  5001.8  358.85  5002.0  359.35
  5004.0  360.98  5009.6  360.01  5026.4  359.35  5040.4  363.63  5099.1  363.26
  5115.8  362.49  5121.4  363.23  5138.2  362.13  5143.8  362.94  5160.6  363.00
  5166.2  364.35  5182.9  363.89  5196.9  372.96  5216.5  387.25  5219.3  387.25
#Mann=3,-1,0
  4695.7    0.05       0  4998.0    0.04       0  5002.0    0.05       0
Bank Sta=4998,5002
Exp/Cntr=0.3,0.1

Type RM Length L Ch R = 1,10075,179,179,179
BEGIN DESCRIPTION:
Mapping XS 7df8ecbc
END DESCRIPTION:
XS GIS Cut Line= 3
      2741402.44      6794257.27      2741482.00      6793852.72
      2741313.92      6793688.76
#Sta/Elev= 30
  4587.7  372.13  4655.2  369.09  4716.4  367.26  4738.8  366.88  4777.5  367.61
  4828.5  365.96  4920.2  365.87  4939.3  362.84  4944.4  363.82  4981.4  358.22
  4990.6  359.80  4998.0  358.22  4998.3  357.72  5001.8  357.72  5002.0  358.22
  5005.5  360.71  5026.6  362.28  5033.8  363.69  5040.8  366.25  5076.2  365.83
  5118.7  363.50  5147.0  364.39  5182.2  367.82  5189.4  367.39  5196.4  368.21
  5210.5  373.01  5217.7  378.59  5224.7  377.51  5229.9  379.32  5234.8  379.32
#Mann=3,-1,0
  4587.7    0.05       0  4998.0    0.04       0  5002.0    0.05       0
Bank Sta=4998,5002
Exp/Cntr=0.3,0.1

Type RM Length L Ch R = 1,9896,350,350,350
BEGIN DESCRIPTION:
Clear Creek T 28 19.0
END DESCRIPTION:
XS GIS Cut Line= 3
      2741726.00      6794061.00      2741626.00      6793761.00
      2741326.03      6793611.02
#Sta/Elev= 30
  4683.4  378.28  4704.5  375.11  4757.2  371.32  4767.7  369.76  4788.8  368.91
  4799.3  365.91  4809.9  364.60  4894.2  363.10  4915.3  360.98  4925.8  361.53
  4942.4  360.25  4957.5  357.89  4968.0  353.36  4978.5  351.96  4997.0  355.77
  4998.0  351.96  4998.3  351.46  5002.0  351.96  5002.4  355.77  5013.6  359.36
  5030.4  361.15  5036.0  362.97  5097.5  364.30  5192.5  363.97  5237.2  365.23
  5281.9  369.05  5321.1  377.27  5326.7  377.38  5332.2  380.43  5335.0  380.43
#Mann=4,-1,0
  4683.4    0.12       0  4942.4    0.05       0  4998.0    0.05       0
  5002.0    0.05       0
Bank Sta=4998,5002
Exp/Cntr=0.3,0.1

Type RM Length L Ch R = 1,9546,329,329,329
BEGIN DESCRIPTION:
Clear Creek T 28 18.0
END DESCRIPTION:
XS GIS Cut Line= 3
      2742217.26      6793761.90      2741926.00      6793611.00
      2741675.99      6793410.99
#Sta/Elev= 30
  4664.3  376.01  4702.0  373.10  4873.4  366.16  4883.6  363.50  4895.6  361.09
  4924.8  359.34  4934.2  360.21  4939.8  359.33  4957.8  361.33  4969.8  361.13
  4978.4  359.30  4989.5  354.58  4995.5  354.58  4998.0  349.85  4998.3  349.35
  5002.0  349.85  5028.3  350.46  5034.8  359.37  5042.8  358.62  5049.2  361.01
  5056.4  360.71  5078.0  362.89  5092.4  362.86  5098.8  361.25  5118.3  361.64
  5162.8  362.03  5198.0  364.10  5248.5  369.61  5276.5  374.78  5312.5  377.47
#Mann=6,-1,0
  4664.3    0.05       0  4883.6    0.12       0  4957.8     0.1       0
  4998.0    0.07       0  5002.0     0.1       0  5118.3    0.05       0
Bank Sta=4998,5002
Exp/Cntr=0.3,0.1

Type RM Length L Ch R = 1,9217,439,439,439
BEGIN DESCRIPTION:
Clear Creek T 28 17.0
END DESCRIPTION:
XS GIS Cut Line= 3
      2742350.10      6793557.23      2742026.00      6793361.00
      2741686.19      6793266.07
#Sta/Elev= 30
  4612.2  376.06  4787.4  366.03  4925.1  360.31  4932.6  356.46  4940.6  356.58
  4962.0  360.89  4977.5  359.00  4983.3  356.98  4993.7  356.85  4998.0  347.37
  4998.3  346.87  5002.0  347.37  5008.2  356.44  5013.3  349.66  5022.2  347.37
  5032.6  348.08  5042.3  350.69  5047.5  354.46  5053.4  357.00  5063.8  353.50
  5081.7  353.82  5094.9  356.17  5105.3  356.22  5121.0  360.13  5155.2  361.56
  5194.5  368.04  5219.5  370.32  5268.0  373.14  5307.4  373.61  5343.9  375.45
#Mann=3,-1,0
  4612.2    0.05       0  4998.0    0.04       0  5002.0    0.05       0
Bank Sta=4998,5002
Exp/Cntr=0.3,0.1

Type RM Length L Ch R = 1,8778,435,435,435
BEGIN DESCRIPTION:
Clear Creek T 28 16.0
END DESCRIPTION:
XS GIS Cut Line= 3
      2742431.51      6793107.19      2742226.00      6793061.00
      2741679.05      6793094.28
#Sta/Elev= 30
  4785.0  378.98  4862.4  374.30  4879.7  372.44  4928.1  369.34  4954.6  362.82
  4964.9  357.84  4971.4  356.74  4976.5  351.82  4985.4  348.48  4993.1  346.68
  4998.0  346.68  4998.3  346.18  5002.0  346.68  5005.7  351.94  5010.0  353.40
  5015.7  355.34  5025.7  356.80  5055.7  358.54  5105.8  358.36  5155.9  360.70
  5180.6  360.15  5216.0  359.46  5266.1  359.86  5296.2  361.28  5404.3  362.74
  5426.4  363.71  5466.5  368.26  5486.5  372.92  5516.6  376.83  5543.6  378.19
#Mann=5,-1,0
  4785.0    0.05       0  4998.0    0.04       0  5002.0    0.05       0
  5010.0    0.12       0  5180.6    0.05       0
Bank Sta=4998,5002
Exp/Cntr=0.3,0.1

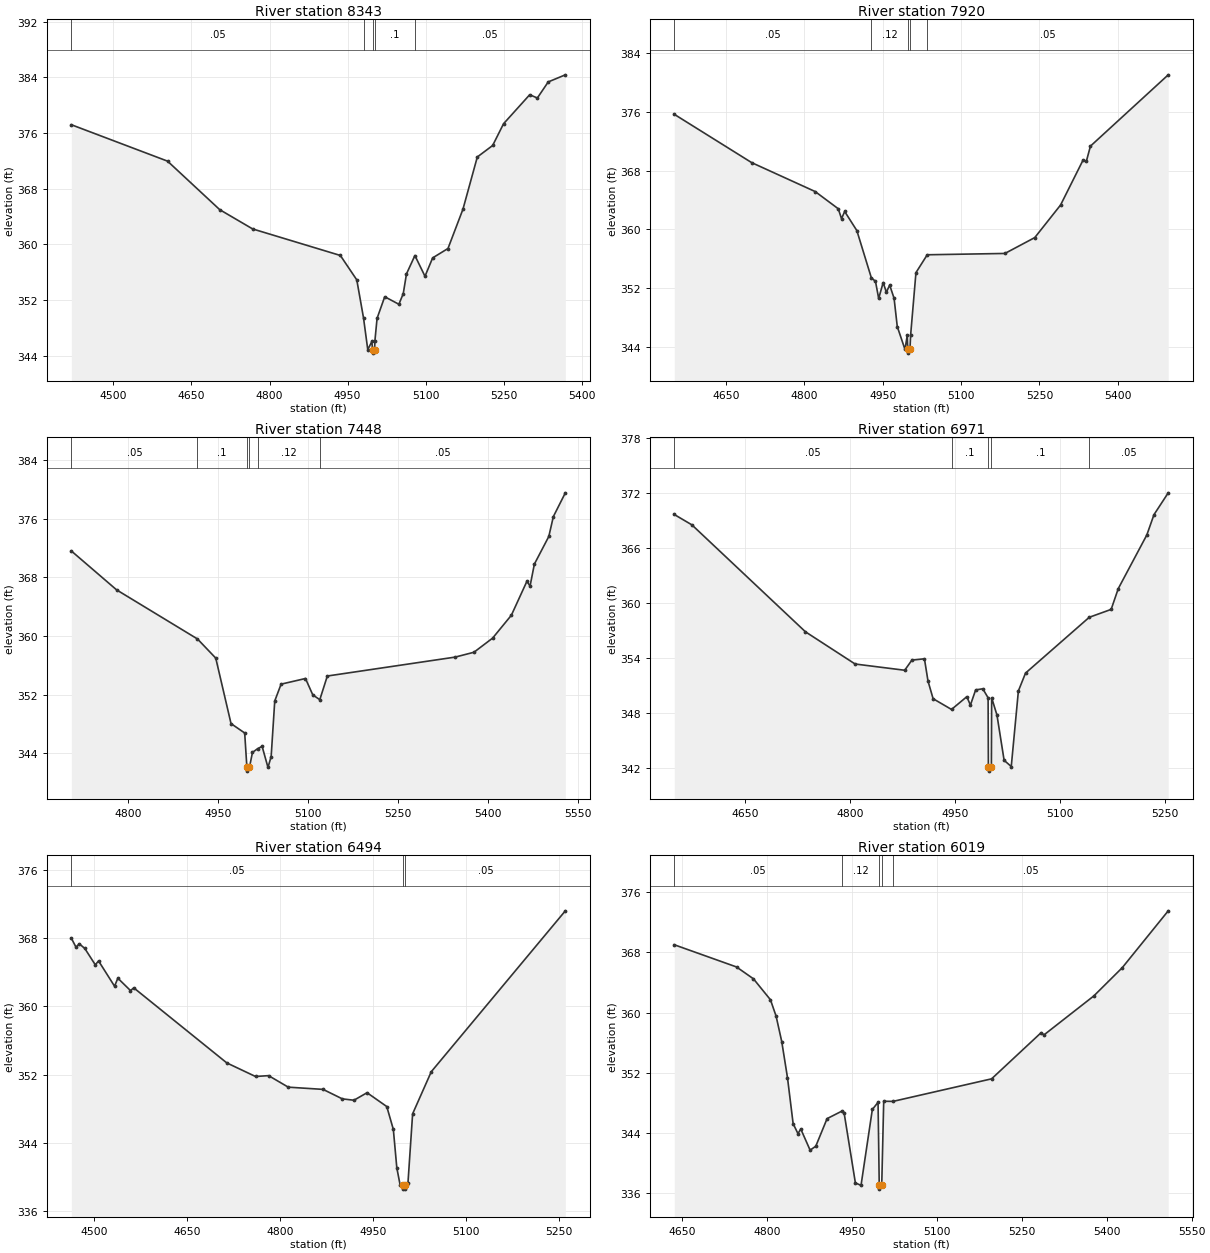
Type RM Length L Ch R = 1,8343,423,423,423
BEGIN DESCRIPTION:
Clear Creek T 28 15.0
END DESCRIPTION:
XS GIS Cut Line= 3
      2742576.60      6792944.39      2742026.00      6792761.00
      2741726.22      6792545.40
#Sta/Elev= 30
  4419.1  377.19  4604.0  371.96  4704.3  364.99  4767.6  362.22  4936.2  358.41
  4967.8  354.90  4980.7  349.45  4988.9  344.88  4996.8  346.06  4998.0  344.88
  4998.3  344.38  5002.1  344.88  5002.5  346.06  5006.8  349.38  5021.5  352.48
  5048.7  351.40  5057.1  352.92  5063.3  355.76  5079.5  358.40  5098.9  355.42
  5113.6  358.06  5143.1  359.41  5171.9  365.06  5199.5  372.56  5229.0  374.21
  5249.9  377.33  5300.2  381.50  5314.9  381.03  5335.8  383.34  5368.7  384.36
#Mann=5,-1,0
  4419.1    0.05       0  4980.7     0.1       0  4998.0    0.07       0
  5002.1     0.1       0  5079.5    0.05       0
Bank Sta=4998,5002.1
Exp/Cntr=0.3,0.1

Type RM Length L Ch R = 1,7920,472,472,472
BEGIN DESCRIPTION:
Clear Creek T 28 14.0
END DESCRIPTION:
XS GIS Cut Line= 3
      2742621.13      6792742.83      2742256.17      6792480.78
      2741875.98      6792160.99
#Sta/Elev= 30
  4550.7  375.65  4699.1  369.07  4820.6  365.14  4864.8  362.80  4871.0  361.45
  4877.1  362.43  4900.4  359.83  4928.1  353.42  4936.1  352.92  4942.2  350.60
  4950.8  352.76  4956.9  351.45  4963.3  352.41  4971.7  350.62  4977.8  346.78
  4992.6  343.66  4997.0  345.61  4997.9  343.66  4998.3  343.16  5002.1  343.66
  5003.4  345.61  5013.6  354.11  5035.2  356.54  5184.0  356.72  5241.2  358.88
  5290.6  363.31  5333.5  369.40  5340.1  369.29  5347.8  371.32  5496.8  381.02
#Mann=5,-1,0
  4550.7    0.05       0  4928.1    0.12       0  4997.9    0.07       0
  5002.1    0.12       0  5035.2    0.05       0
Bank Sta=4997.9,5002.1
Exp/Cntr=0.3,0.1

Type RM Length L Ch R = 1,7448,477,477,477
BEGIN DESCRIPTION:
Clear Creek T 28 13.0
END DESCRIPTION:
XS GIS Cut Line= 3
      2742761.04      6792242.21      2742476.00      6792211.00
      2741967.11      6792036.26
#Sta/Elev= 30
  4704.8  371.58  4780.3  366.28  4915.4  359.58  4945.9  356.97  4971.4  348.04
  4994.2  346.76  4997.9  342.06  4998.2  341.56  5002.1  342.06  5007.2  344.11
  5015.8  344.62  5023.3  344.94  5033.1  342.06  5038.4  343.55  5044.4  351.13
  5055.0  353.42  5095.7  354.19  5107.9  351.96  5119.6  351.30  5132.2  354.53
  5345.7  357.11  5377.0  357.77  5408.2  359.70  5439.5  362.82  5465.4  367.44
  5470.7  366.80  5477.9  369.79  5502.0  373.56  5509.6  376.27  5529.6  379.51
#Mann=6,-1,0
  4704.8    0.05       0  4915.4     0.1       0  4997.9    0.07       0
  5002.1     0.1       0  5015.8    0.12       0  5119.6    0.05       0
Bank Sta=4997.9,5002.1
Exp/Cntr=0.3,0.1

Type RM Length L Ch R = 1,6971,477,477,477
BEGIN DESCRIPTION:
Clear Creek T 28 12.0
END DESCRIPTION:
XS GIS Cut Line= 3
      2742920.90      6791835.60      2742476.00      6791761.00
      2742225.96      6791710.99
#Sta/Elev= 30
  4548.9  369.63  4574.1  368.50  4736.4  356.85  4807.4  353.34  4878.3  352.66
  4888.5  353.76  4906.5  353.91  4911.6  351.48  4918.9  349.56  4945.2  348.39
  4967.1  349.78  4972.2  348.86  4979.7  350.52  4989.9  350.64  4997.5  349.66
  4997.9  342.17  4998.2  341.67  5002.2  342.17  5002.6  349.66  5010.2  347.77
  5020.4  342.85  5030.6  342.17  5040.8  350.41  5051.0  352.35  5142.1  358.43
  5173.4  359.29  5183.6  361.56  5224.4  367.40  5234.6  369.61  5255.0  371.99
#Mann=5,-1,0
  4548.9    0.05       0  4945.2     0.1       0  4997.9    0.07       0
  5002.2     0.1       0  5142.1    0.05       0
Bank Sta=4997.9,5002.2
Exp/Cntr=0.3,0.1

Type RM Length L Ch R = 1,6494,475,475,475
BEGIN DESCRIPTION:
Clear Creek T 28 11.0
END DESCRIPTION:
XS GIS Cut Line= 3
      2742986.48      6791489.05      2742476.00      6791311.00
      2742219.72      6791304.52
#Sta/Elev= 30
  4463.2  367.99  4470.7  366.94  4476.0  367.34  4484.9  366.79  4501.8  364.88
  4507.1  365.33  4532.9  362.37  4538.2  363.31  4558.6  361.86  4563.9  362.18
  4714.0  353.39  4760.3  351.80  4781.4  351.90  4813.2  350.55  4869.3  350.29
  4900.4  349.18  4919.1  349.02  4940.3  349.90  4972.1  348.28  4982.7  345.60
  4988.3  341.10  4993.6  339.11  4997.8  339.11  4998.2  338.61  5001.8  338.61
  5002.2  339.11  5006.3  339.34  5013.8  347.43  5043.9  352.36  5260.2  371.20
#Mann=3,-1,0
  4463.2    0.05       0  4997.8    0.04       0  5002.2    0.05       0
Bank Sta=4997.8,5002.2
Exp/Cntr=0.3,0.1

Type RM Length L Ch R = 1,6019,438,438,438
BEGIN DESCRIPTION:
Clear Creek T 28 10.0
END DESCRIPTION:
XS GIS Cut Line= 3
      2743035.92      6790897.96      2742676.00      6790911.00
      2742164.96      6790955.13
#Sta/Elev= 30
  4635.5  369.01  4745.5  366.06  4775.5  364.48  4805.5  361.70  4815.5  359.52
  4825.5  356.13  4835.6  351.35  4845.6  345.23  4854.1  343.91  4859.1  344.52
  4875.6  341.71  4885.6  342.23  4905.6  345.90  4931.8  346.90  4935.6  346.71
  4955.6  337.36  4965.6  337.03  4985.6  347.12  4995.7  348.07  4997.8  337.03
  4998.2  336.53  5002.2  337.03  5005.7  348.21  5022.0  348.19  5196.4  351.19
  5284.0  357.33  5289.0  357.03  5377.1  362.21  5427.3  365.96  5508.6  373.52
#Mann=5,-1,0
  4635.5    0.05       0  4931.8    0.12       0  4997.8    0.07       0
  5002.2    0.12       0  5022.0    0.05       0
Bank Sta=4997.8,5002.2
Exp/Cntr=0.3,0.1

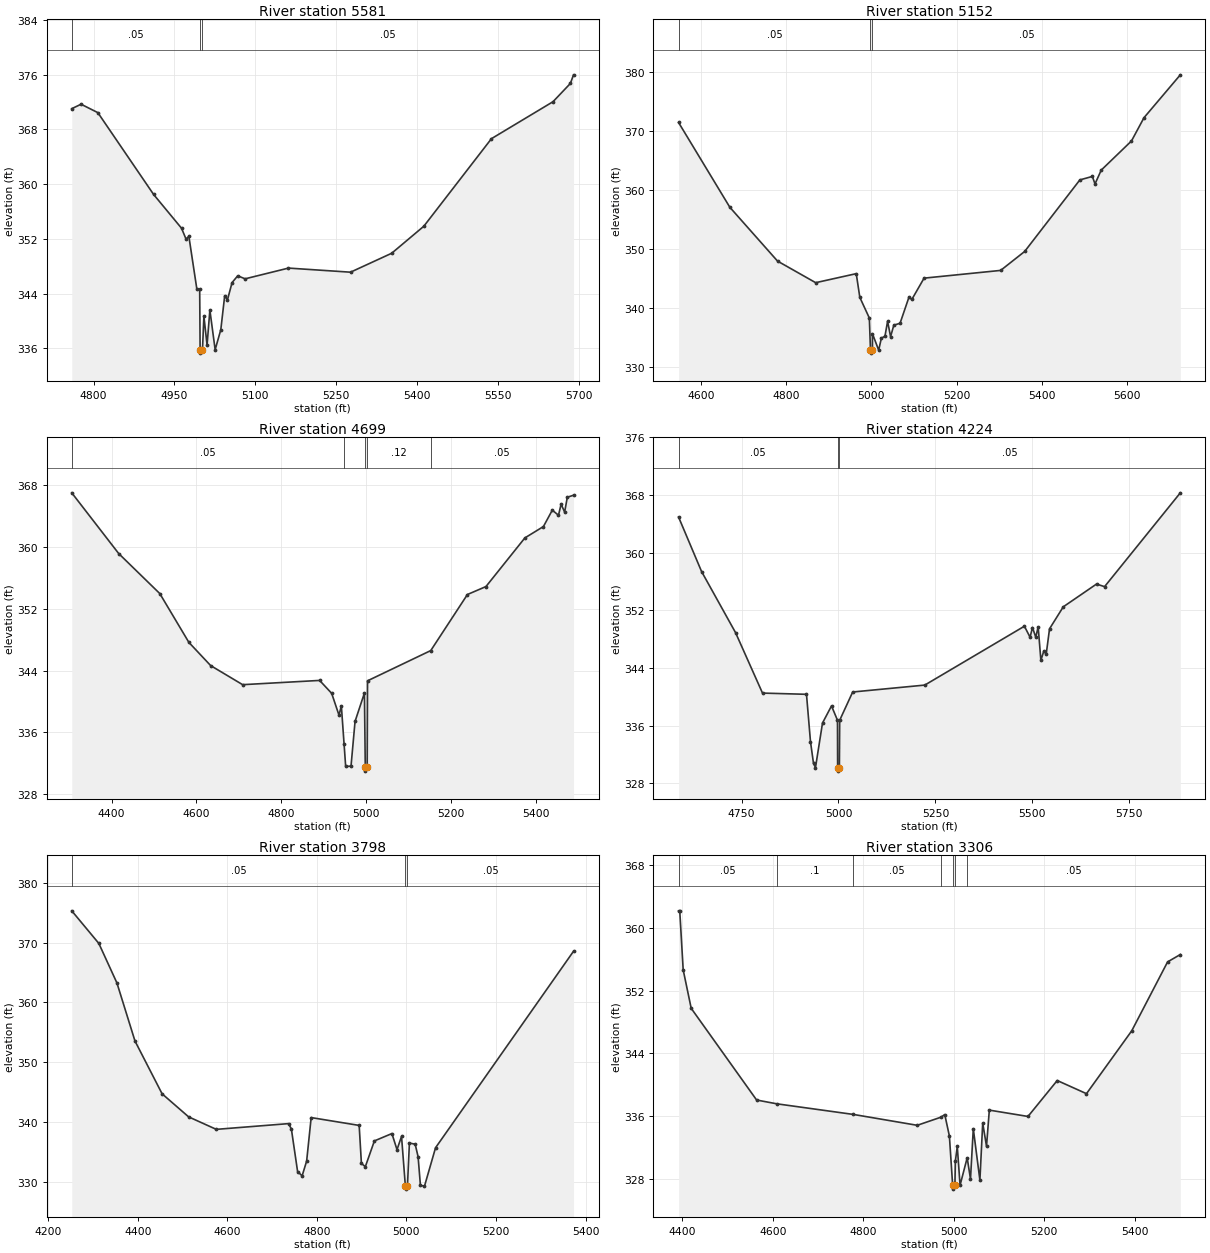
Type RM Length L Ch R = 1,5581,429,429,429
BEGIN DESCRIPTION:
Clear Creek T 28 9.0
END DESCRIPTION:
XS GIS Cut Line= 3
      2743002.74      6790621.80      2742776.00      6790561.00
      2742110.47      6790765.86
#Sta/Elev= 30
  4759.6  371.04  4776.9  371.69  4808.0  370.46  4911.5  358.49  4963.3  353.55
  4971.8  351.94  4976.9  352.38  4991.8  344.62  4997.0  344.62  4997.8  335.78
  4998.2  335.28  5002.2  335.78  5004.8  340.69  5010.7  336.46  5015.9  341.58
  5025.7  335.78  5036.2  338.71  5043.4  343.67  5048.6  343.09  5057.1  345.60
  5067.6  346.59  5081.3  346.15  5161.8  347.72  5276.9  347.12  5353.3  349.89
  5412.9  353.84  5538.4  366.65  5652.7  372.06  5684.9  374.73  5690.7  375.99
#Mann=3,-1,0
  4759.6    0.05       0  4997.8    0.04       0  5002.2    0.05       0
Bank Sta=4997.8,5002.2
Exp/Cntr=0.3,0.1

Type RM Length L Ch R = 1,5152,453,453,453
BEGIN DESCRIPTION:
Clear Creek T 28 8.0
END DESCRIPTION:
XS GIS Cut Line= 3
      2743026.00      6790011.00      2742626.00      6790211.00
      2742040.46      6790645.23
#Sta/Elev= 30
  4547.9  371.42  4668.1  357.05  4779.9  347.93  4869.3  344.27  4964.4  345.80
  4972.8  341.78  4995.1  338.28  4997.8  332.83  4998.2  332.33  5002.3  332.83
  5002.4  335.62  5017.0  332.83  5023.3  334.87  5031.7  335.19  5037.9  337.73
  5044.9  335.12  5052.5  337.07  5067.1  337.39  5088.0  341.82  5094.7  341.43
  5123.4  345.04  5302.9  346.35  5359.2  349.56  5488.6  361.69  5517.9  362.28
  5524.1  361.01  5538.7  363.35  5609.6  368.29  5638.9  372.23  5724.1  379.50
#Mann=3,-1,0
  4547.9    0.05       0  4997.8    0.04       0  5002.3    0.05       0
Bank Sta=4997.8,5002.3
Exp/Cntr=0.3,0.1

Type RM Length L Ch R = 1,4699,475,475,475
BEGIN DESCRIPTION:
Clear Creek T 28 7.0
END DESCRIPTION:
XS GIS Cut Line= 3
      2743050.78      6789718.97      2742426.00      6790011.00
      2742031.78      6790306.60
#Sta/Elev= 30
  4306.1  366.98  4416.7  359.13  4513.6  353.95  4582.1  347.64  4633.4  344.64
  4708.8  342.17  4890.2  342.72  4918.6  341.05  4935.9  338.22  4941.4  339.44
  4947.9  334.44  4951.6  331.59  4964.2  331.64  4973.7  337.42  4995.8  341.09
  4997.8  331.49  4998.2  330.99  5002.3  331.49  5003.1  342.67  5152.1  346.58
  5238.5  353.83  5282.2  354.86  5373.9  361.15  5417.6  362.62  5438.5  364.74
  5453.1  364.08  5459.3  365.51  5467.6  364.49  5473.9  366.41  5488.5  366.67
#Mann=5,-1,0
  4306.1    0.05       0  4947.9    0.12       0  4997.8    0.07       0
  5002.3    0.12       0  5152.1    0.05       0
Bank Sta=4997.8,5002.3
Exp/Cntr=0.3,0.1

Type RM Length L Ch R = 1,4224,426,426,426
BEGIN DESCRIPTION:
Clear Creek T 28 6.0
END DESCRIPTION:
XS GIS Cut Line= 3
      2742825.98      6789511.00      2742426.00      6789611.00
      2741716.63      6790133.97
#Sta/Elev= 30
  4587.7  364.95  4647.0  357.39  4734.6  348.91  4804.1  340.52  4917.5  340.35
  4927.8  333.78  4935.6  330.75  4940.7  330.19  4958.8  336.37  4982.0  338.74
  4997.4  336.75  4997.8  330.19  4998.2  329.69  5002.3  330.19  5003.1  336.75
  5036.6  340.67  5222.5  341.63  5479.3  349.80  5493.9  348.27  5500.1  349.62
  5508.6  348.28  5514.8  349.71  5521.8  345.07  5529.4  346.36  5535.6  345.95
  5544.1  349.44  5579.5  352.49  5665.2  355.65  5686.0  355.29  5881.3  368.31
#Mann=3,-1,0
  4587.7    0.05       0  4997.8    0.04       0  5002.3    0.05       0
Bank Sta=4997.8,5002.3
Exp/Cntr=0.3,0.1

Type RM Length L Ch R = 1,3798,492,492,492
BEGIN DESCRIPTION:
Clear Creek T 28 5.0
END DESCRIPTION:
XS GIS Cut Line= 3
      2742875.99      6789311.00      2742126.00      6789411.00
      2741776.03      6789510.99
#Sta/Elev= 30
  4252.6  375.30  4313.1  369.85  4353.5  363.24  4393.8  353.54  4454.4  344.71
  4513.6  340.86  4575.4  338.77  4736.8  339.73  4743.1  338.83  4757.0  331.71
  4767.1  331.00  4777.2  333.47  4787.3  340.74  4894.5  339.43  4899.5  333.07
  4908.3  332.54  4928.5  336.84  4967.6  338.07  4979.0  335.38  4989.1  337.59
  4997.7  329.28  4998.2  328.78  5002.3  329.28  5006.7  336.48  5019.6  336.29
  5026.1  334.19  5031.3  329.41  5040.4  329.28  5065.1  335.70  5373.2  368.54
#Mann=3,-1,0
  4252.6    0.05       0  4997.7    0.04       0  5002.3    0.05       0
Bank Sta=4997.7,5002.3
Exp/Cntr=0.3,0.1

Type RM Length L Ch R = 1,3306,463,463,463
BEGIN DESCRIPTION:
Clear Creek T 28 4.0
END DESCRIPTION:
XS GIS Cut Line= 3
      2742626.03      6789061.01      2742026.00      6788961.00
      2741726.00      6789360.99
#Sta/Elev= 30
  4392.1  362.20  4394.7  362.20  4402.3  354.66  4420.0  349.75  4564.5  338.04
  4608.5  337.56  4778.1  336.20  4919.3  334.81  4971.8  335.85  4980.1  336.18
  4990.3  333.44  4997.5  327.16  4998.2  326.66  5002.5  327.16  5003.5  330.22
  5007.7  332.11  5013.9  327.16  5029.6  330.66  5036.9  327.95  5043.1  334.38
  5057.7  327.81  5063.9  335.11  5072.3  332.13  5078.5  336.75  5163.9  335.94
  5228.5  340.53  5293.1  338.85  5393.1  346.88  5472.3  355.68  5500.4  356.62
#Mann=7,-1,0
  4392.1    0.05       0  4608.5     0.1       0  4778.1    0.05       0
  4971.8    0.12       0  4997.5    0.07       0  5002.5    0.12       0
  5029.6    0.05       0
Bank Sta=4997.5,5002.5
Exp/Cntr=0.3,0.1