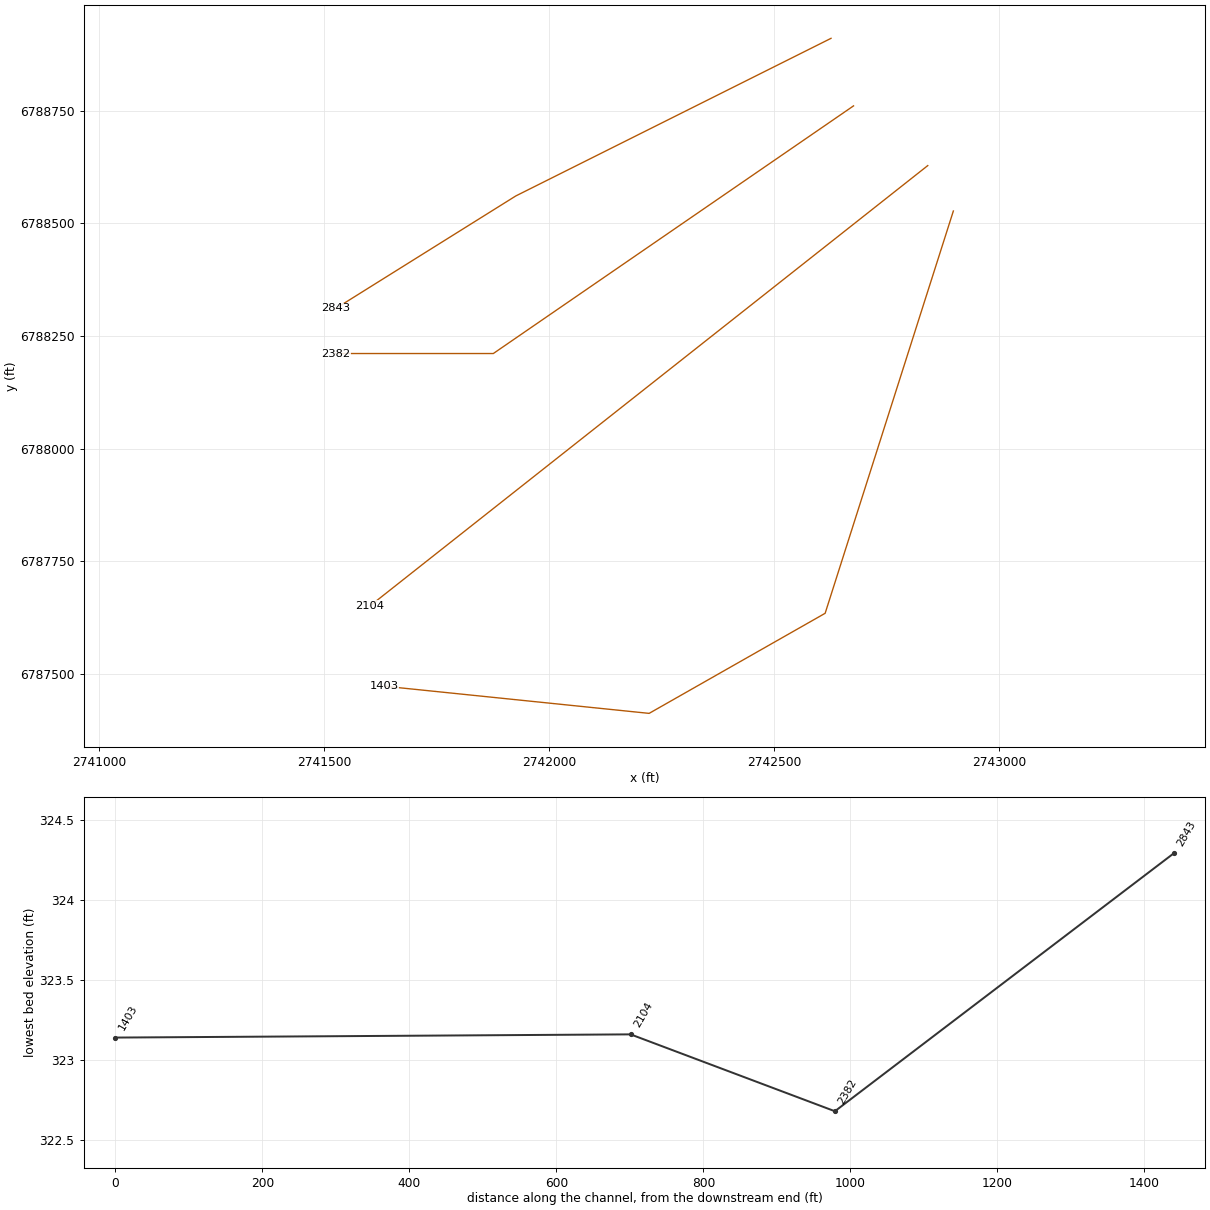
HEC-RAS study Clear Creek T 28.prj: Clear Creek T 28 Base Level Engineering

--- Clear Creek T 28.g01 (geometry) --- (continued)

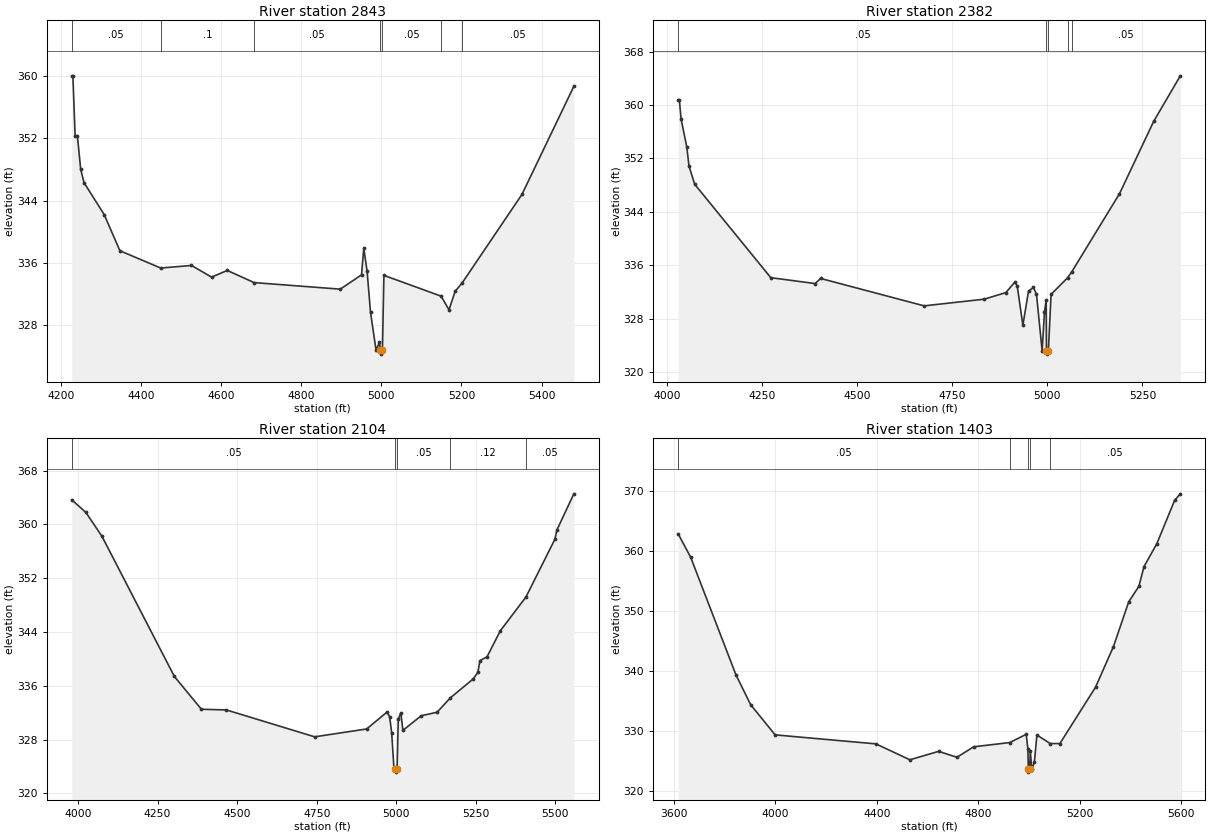
Type RM Length L Ch R = 1,2843,461,461,461
BEGIN DESCRIPTION:
Clear Creek T 28 3.0
END DESCRIPTION:
XS GIS Cut Line= 3
      2742625.98      6788910.99      2741926.00      6788561.00
      2741526.00      6788311.00
#Sta/Elev= 30
  4226.4  360.01  4229.2  360.01  4234.8  352.29  4240.4  352.34  4248.7  348.01
  4257.1  346.29  4307.4  342.20  4346.6  337.56  4448.6  335.34  4525.5  335.67
  4575.8  334.17  4614.9  335.03  4682.0  333.47  4897.2  332.63  4950.3  334.47
  4955.9  337.88  4964.3  334.90  4972.7  329.66  4986.6  324.79  4995.0  325.80
  4997.5  324.79  4998.2  324.29  5002.5  324.79  5006.2  334.40  5149.1  331.73
  5168.8  329.98  5184.1  332.35  5201.7  333.43  5351.0  344.78  5480.7  358.66
#Mann=7,-1,0
  4226.4    0.05       0  4448.6     0.1       0  4682.0    0.05       0
  4997.5    0.04       0  5002.5    0.05       0  5149.1    0.12       0
  5201.7    0.05       0
Bank Sta=4997.5,5002.5
Exp/Cntr=0.3,0.1

Type RM Length L Ch R = 1,2382,278,278,278
BEGIN DESCRIPTION:
Clear Creek T 28 2.0
END DESCRIPTION:
XS GIS Cut Line= 3
      2742676.01      6788761.01      2741876.00      6788211.00
      2741526.03      6788211.00
#Sta/Elev= 30
  4028.8  360.68  4031.8  360.68  4036.3  357.89  4051.1  353.76  4057.2  350.83
  4072.1  348.12  4272.3  334.13  4388.7  333.25  4403.6  334.01  4675.6  329.91
  4833.9  330.91  4890.7  331.90  4914.4  333.47  4920.5  332.91  4935.4  327.00
  4950.3  332.14  4963.2  332.66  4971.2  331.68  4986.1  323.18  4992.2  328.92
  4996.6  330.75  4997.5  323.18  4998.1  322.68  5002.5  323.18  5009.6  331.63
  5052.9  334.11  5064.4  335.04  5189.6  346.70  5279.6  357.55  5349.6  364.36
#Mann=5,-1,0
  4028.8    0.05       0  4997.5    0.04       0  5002.5    0.05       0
  5052.9    0.12       0  5064.4    0.05       0
Bank Sta=4997.5,5002.5
Exp/Cntr=0.3,0.1

Type RM Length L Ch R = 1,2104,701,701,701
BEGIN DESCRIPTION:
Mapping XS 37175cd9
END DESCRIPTION:
XS GIS Cut Line= 2
      2742840.81      6788628.36      2741602.31      6787650.67
#Sta/Elev= 30
  3980.2  363.65  4024.6  361.78  4075.0  358.24  4302.6  337.39  4387.6  332.51
  4466.1  332.41  4743.5  328.41  4907.0  329.58  4971.1  332.10  4979.2  331.39
  4985.5  329.05  4992.8  323.66  4997.5  323.66  4998.1  323.16  5002.6  323.66
  5006.4  331.07  5014.4  331.98  5020.8  329.37  5078.5  331.55  5128.2  332.06
  5170.3  334.22  5242.1  337.03  5256.5  338.01  5262.9  339.74  5285.4  340.32
  5327.0  344.18  5407.5  349.20  5498.6  357.80  5504.9  359.18  5558.1  364.55
#Mann=5,-1,0
  3980.2    0.05       0  4997.5    0.04       0  5002.6    0.05       0
  5170.3    0.12       0  5407.5    0.05       0
Bank Sta=4997.5,5002.6
Exp/Cntr=0.3,0.1

Type RM Length L Ch R = 1,1403,0,0,0
BEGIN DESCRIPTION:
Clear Creek T 28 1.0
END DESCRIPTION:
XS GIS Cut Line= 4
      2742897.70      6788527.59      2742612.93      6787634.08
      2742222.02      6787411.83      2741633.78      6787472.21
#Sta/Elev= 30
  3617.7  362.90  3666.6  359.03  3845.0  339.40  3903.0  334.41  3999.6  329.36
  4396.6  327.86  4530.7  325.20  4644.0  326.61  4716.1  325.62  4782.0  327.37
  4924.3  328.08  4989.1  329.45  4995.8  326.99  4997.5  323.64  4998.1  323.14
  5002.6  323.64  5005.2  326.70  5011.2  323.64  5021.3  324.78  5031.3  329.34
  5083.7  327.91  5121.8  327.91  5262.5  337.33  5332.9  344.10  5393.2  351.58
  5433.1  354.16  5453.5  357.47  5503.8  361.27  5574.2  368.53  5596.5  369.61
#Mann=5,-1,0
  3617.7    0.05       0  4924.3    0.12       0  4997.5    0.07       0
  5002.6    0.12       0  5083.7    0.05       0
Bank Sta=4997.5,5002.6
Exp/Cntr=0.3,0.1

Chan Stop Cuts=-1

--- Clear Creek T 28.g02 (geometry) ---

Geom Title=EX_06102017
Program Version=4.10

Chan Stop Cuts=-1
Use User Specified Reach Order=0
Composite Channel Slope=5