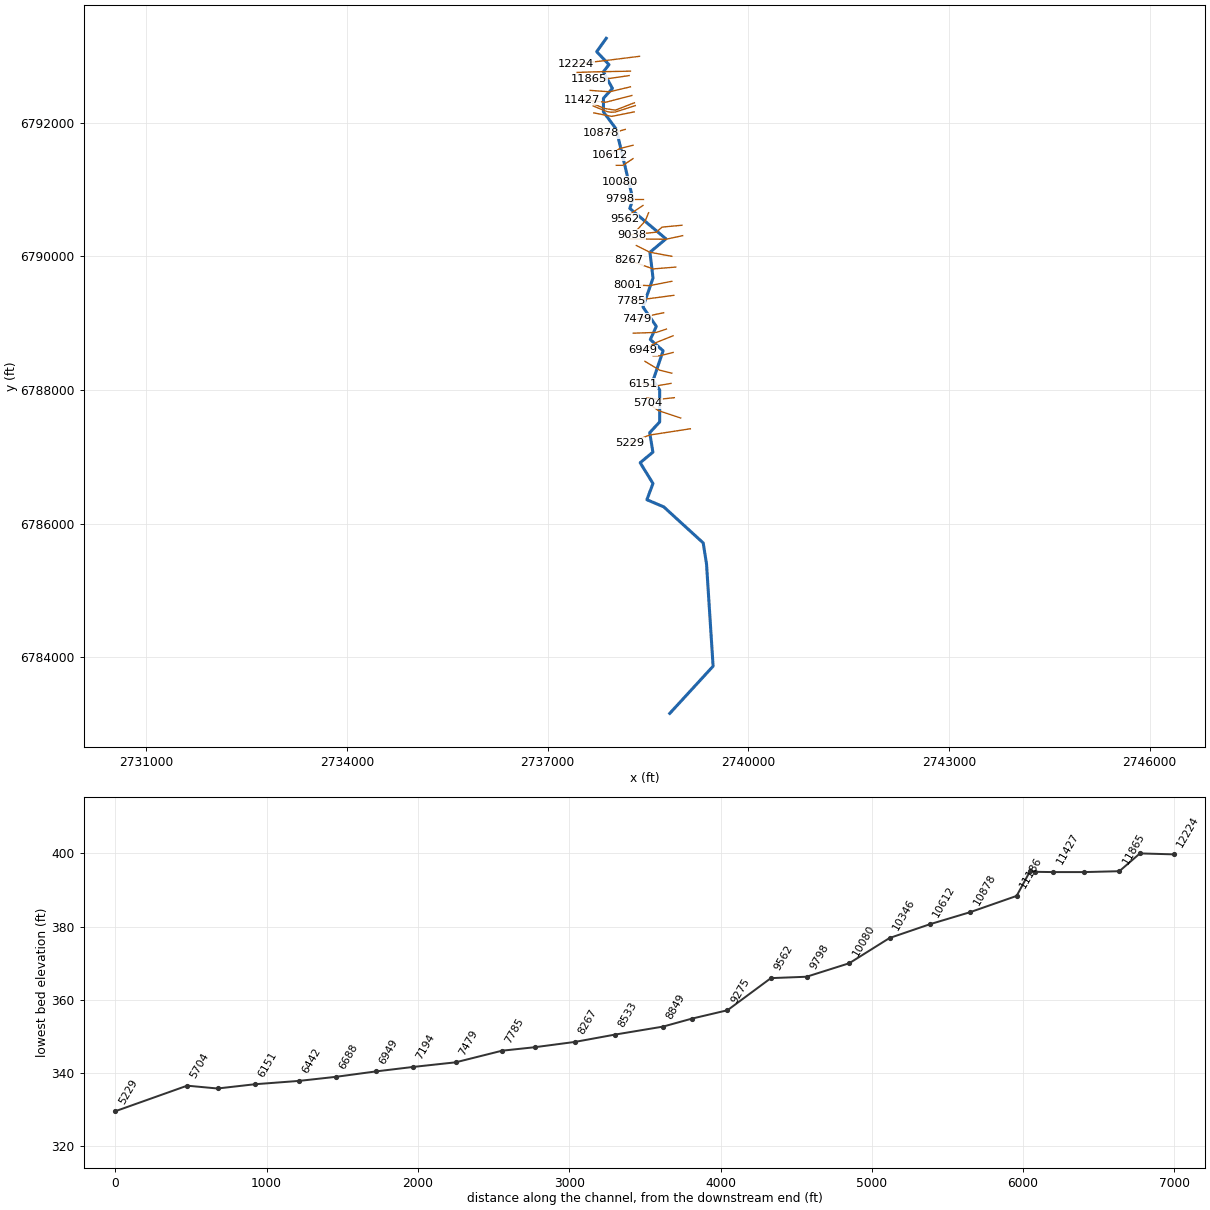
--- Clear Creek T 29.prj (project) ---

Proj Title=Clear Creek T 29 Base Level Engineering
Current Plan=p01
Default Exp/Contr=0.3,0.1
English Units
Geom File=g01
Flow File=f01
Plan File=p01
BEGIN DESCRIPTION:
Clear Creek T 29
END DESCRIPTION:

--- Clear Creek T 29.p01 (plan) ---

Plan Title=Multiple Run
Short Identifier=Multiple
Geom File=g01
Flow File=f01
Subcritical Flow
K Sum by GR= 0
Std Step Tol= 0.01
Critical Tol= 0.01
Num of Std Step Trials= 20
Max Error Tol= 0.3
Flow Tol Ratio= 0.001
Split Flow NTrial= 30
Split Flow Tol= 0.02
Split Flow Ratio= 0.02
Log Output Level= 0
Friction Slope Method= 1
Unsteady Friction Slope Method= 2
Unsteady Bridges Friction Slope Method= 1
Parabolic Critical Depth
Global Vel Dist=  1 , 1 , 1
Global Log Level= 0
CheckData=True
Encroach Param= -1, 0, 0, 0
BEGIN DESCRIPTION:
Multiple Run
END DESCRIPTION:

--- Clear Creek T 29.f01 (steady flow) ---

Flow Title=Multiple
Number of Profiles=7
Profile Names=10-year,25-year,50-year,1pct_min,100-year,1pct_plu,500-year
River Rch & RM= Clear Creek T 29,Reach-1,12224
     165     203     231     131     261     522     334
River Rch & RM= Clear Creek T 29,Reach-1,9038
     382     498     589     346     691    1379     951
River Rch & RM= Clear Creek T 29,Reach-1,5229
     634     853    1031     619    1234    2463    1767
River Rch & RM= Clear Creek T 29,Reach-1,2847
     867    1186    1448     877    1749    3490    2551
Boundary for River Rch & Prof#=Clear Creek T 29,Reach-1,1
Up Type=0
Dn Type=3
Dn Slope=0.005
Boundary for River Rch & Prof#=Clear Creek T 29,Reach-1,2
Up Type=0
Dn Type=3
Dn Slope=0.005
Boundary for River Rch & Prof#=Clear Creek T 29,Reach-1,3
Up Type=0
Dn Type=3
Dn Slope=0.005
Boundary for River Rch & Prof#=Clear Creek T 29,Reach-1,4
Up Type=0
Dn Type=3
Dn Slope=0.005
Boundary for River Rch & Prof#=Clear Creek T 29,Reach-1,5
Up Type=0
Dn Type=3
Dn Slope=0.005
Boundary for River Rch & Prof#=Clear Creek T 29,Reach-1,6
Up Type=0
Dn Type=3
Dn Slope=0.005
Boundary for River Rch & Prof#=Clear Creek T 29,Reach-1,7
Up Type=0
Dn Type=3
Dn Slope=0.005

--- Clear Creek T 29.g01 (geometry) ---

Geom Title=Existing Conditions

River Reach=Clear Creek T 29,Reach-1
Reach XY= 30
      2737876.00      6793261.00      2737733.28      6793061.06
      2737917.04      6792867.68      2737833.11      6792761.01
      2737968.69      6792510.90      2737833.98      6792364.33
      2737833.75      6792161.09      2738023.94      6791905.15
      2738275.07      6790851.15      2738227.74      6790716.63
      2738768.93      6790261.01      2738529.37      6790059.72
      2738575.48      6789676.22      2738425.64      6789240.79
      2738624.76      6788951.30      2738534.84      6788754.05
      2738726.59      6788586.00      2738575.63      6788142.59
      2738675.35      6788000.36      2738675.25      6787521.68
      2738526.00      6787361.00      2738573.37      6787069.48
      2738383.31      6786911.10      2738574.96      6786600.56
      2738483.59      6786357.65      2738736.12      6786250.65
      2739326.00      6785711.00      2739375.48      6785395.78
      2739473.94      6783866.85      2738826.00      6783161.00

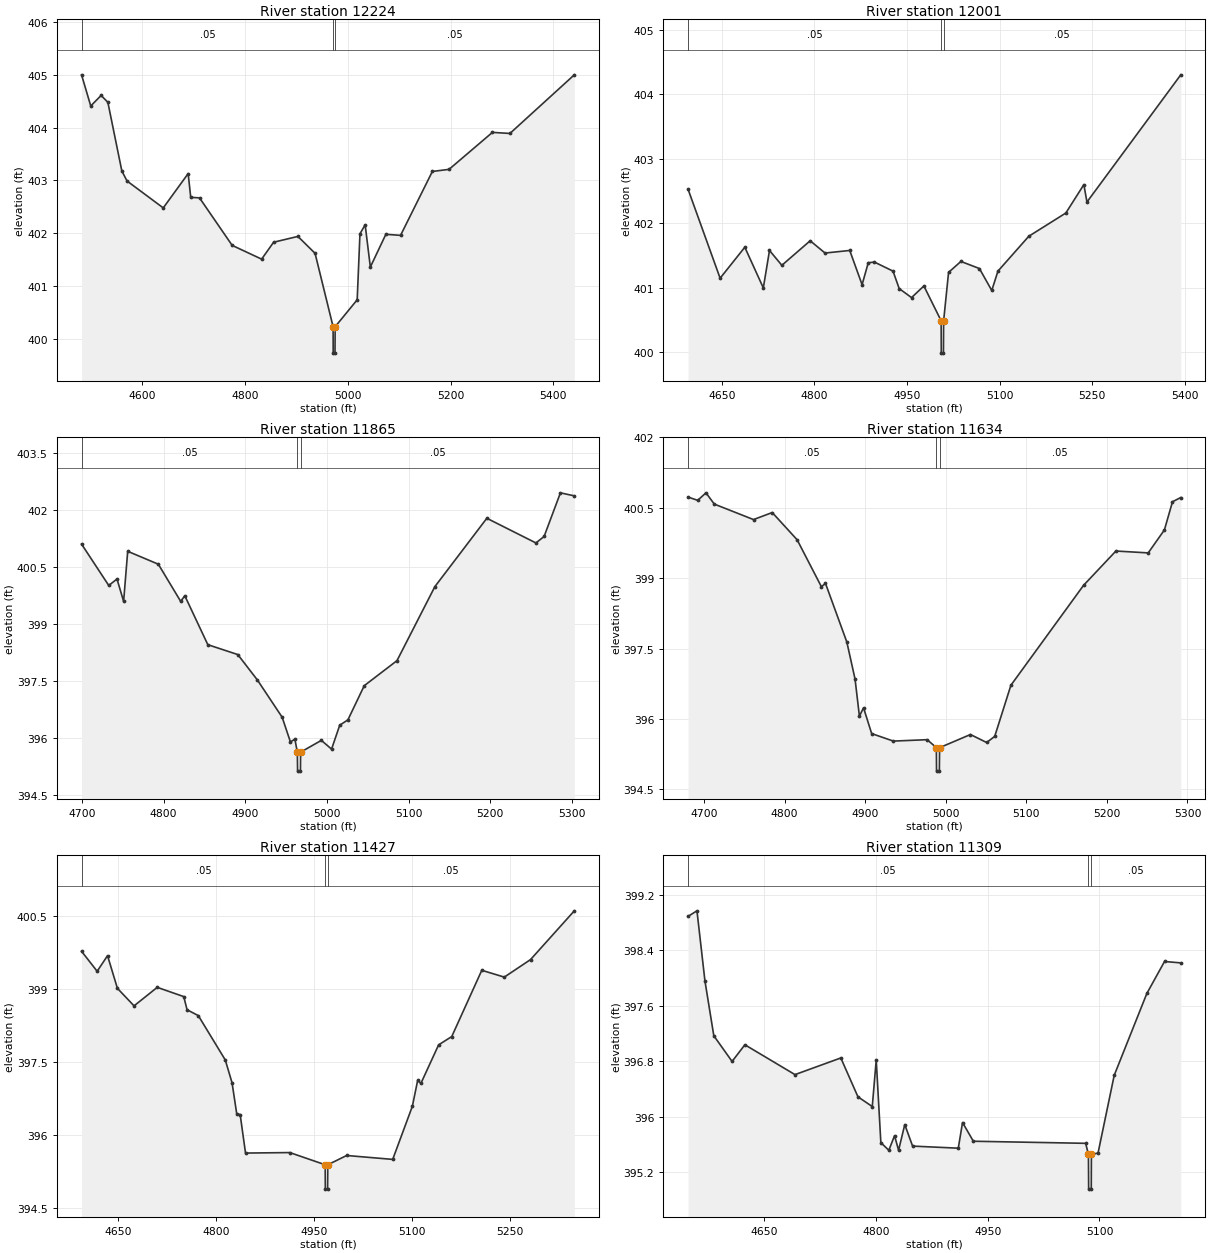
Type RM Length L Ch R = 1,12224,223,223,223
BEGIN DESCRIPTION:
2496
END DESCRIPTION:
XS GIS Cut Line= 3
      2738373.81      6792992.10      2737874.28      6792929.70
      2737421.52      6792878.05
#Sta/Elev= 30
  4481.8  405.00  4499.7  404.41  4519.9  404.61  4533.0  404.48  4560.2  403.18
  4570.3  402.99  4640.8  402.48  4689.3  403.13  4694.3  402.68  4711.4  402.67
  4775.0  401.77  4832.3  401.51  4855.6  401.83  4902.9  401.94  4936.3  401.62
  4971.4  400.23  4971.6  399.73  4975.1  399.73  4975.4  400.23  5018.3  400.74
  5023.7  401.99  5033.8  402.16  5043.9  401.36  5074.1  401.98  5102.7  401.96
  5164.6  403.17  5197.1  403.21  5281.5  403.91  5315.6  403.89  5440.9  405.00
#Mann=3,-1,0
  4481.8    0.05       0  4971.4    0.04       0  4975.4    0.05       0
Bank Sta=4971.4,4975.4
Exp/Cntr=0.3,0.1

Type RM Length L Ch R = 1,12001,136,136,136
BEGIN DESCRIPTION:
2495
END DESCRIPTION:
XS GIS Cut Line= 3
      2738237.99      6792769.84      2737692.24      6792759.31
      2737439.93      6792750.93
#Sta/Elev= 30
  4595.2  402.53  4647.2  401.15  4687.2  401.63  4717.2  401.00  4727.2  401.58
  4747.2  401.35  4793.1  401.73  4817.2  401.54  4857.2  401.58  4877.2  401.05
  4887.2  401.39  4897.2  401.40  4927.3  401.26  4937.3  400.99  4957.3  400.85
  4977.3  401.03  5005.3  400.49  5005.5  399.99  5009.0  399.99  5009.3  400.49
  5017.3  401.24  5037.3  401.41  5067.3  401.30  5087.3  400.96  5097.3  401.26
  5147.3  401.80  5207.3  402.16  5236.5  402.60  5241.5  402.33  5393.5  404.30
#Mann=3,-1,0
  4595.2    0.05       0  5005.3    0.05       0  5009.3    0.05       0
Bank Sta=5005.3,5009.3
Exp/Cntr=0.3,0.1

Type RM Length L Ch R = 1,11865,231,231,231
BEGIN DESCRIPTION:
1313
END DESCRIPTION:
XS GIS Cut Line= 3
      2738218.99      6792703.89      2737926.00      6792661.00
      2737619.01      6792649.85
#Sta/Elev= 30
  4699.6  401.11  4732.9  400.02  4743.0  400.19  4751.1  399.60  4756.1  400.92
  4793.6  400.58  4821.0  399.60  4826.0  399.75  4854.2  398.46  4890.9  398.20
  4914.9  397.53  4945.2  396.55  4955.3  395.90  4960.8  395.97  4963.8  395.63
  4964.1  395.13  4967.6  395.13  4967.8  395.63  4993.2  395.94  5005.7  395.71
  5015.7  396.34  5025.7  396.48  5045.7  397.38  5085.8  398.04  5132.2  399.99
  5195.8  401.79  5255.9  401.14  5265.9  401.31  5285.9  402.46  5302.9  402.38
#Mann=3,-1,0
  4699.6    0.05       0  4963.8    0.05       0  4967.8    0.05       0
Bank Sta=4963.8,4967.8
Exp/Cntr=0.3,0.1

Type RM Length L Ch R = 1,11634,207,207,207
BEGIN DESCRIPTION:
1312
END DESCRIPTION:
XS GIS Cut Line= 3
      2738237.66      6792535.48      2737926.00      6792461.00
      2737635.72      6792482.24
#Sta/Elev= 30
  4680.2  400.73  4692.2  400.66  4702.5  400.82  4712.8  400.58  4761.5  400.25
  4784.7  400.40  4815.6  399.82  4845.7  398.82  4850.8  398.89  4877.3  397.64
  4887.5  396.85  4892.9  396.06  4898.0  396.24  4908.1  395.69  4935.0  395.53
  4977.0  395.56  4988.4  395.39  4988.6  394.89  4992.1  394.89  4992.4  395.39
  5030.7  395.67  5050.8  395.50  5060.8  395.63  5080.9  396.72  5171.1  398.85
  5211.2  399.58  5251.3  399.54  5271.4  400.03  5281.4  400.63  5291.7  400.72
#Mann=3,-1,0
  4680.2    0.05       0  4988.4    0.04       0  4992.4    0.05       0
Bank Sta=4988.4,4992.4
Exp/Cntr=0.3,0.1

Type RM Length L Ch R = 1,11427,118,118,118
BEGIN DESCRIPTION:
1311
END DESCRIPTION:
XS GIS Cut Line= 3
      2738259.11      6792406.10      2737866.07      6792304.33
      2737519.37      6792340.72
#Sta/Elev= 30
  4594.0  399.77  4617.9  399.36  4633.8  399.68  4648.9  399.01  4674.4  398.65
  4709.9  399.03  4750.5  398.84  4755.6  398.57  4772.8  398.45  4814.1  397.54
  4824.5  397.07  4831.7  396.43  4836.9  396.42  4845.1  395.63  4912.9  395.64
  4967.1  395.39  4967.3  394.89  4970.8  394.89  4971.1  395.39  5000.0  395.58
  5070.5  395.50  5100.6  396.59  5108.7  397.12  5113.7  397.06  5140.8  397.85
  5160.9  398.02  5206.9  399.38  5241.4  399.24  5281.6  399.60  5348.6  400.60
#Mann=3,-1,0
  4594.0    0.05       0  4967.1    0.03       0  4971.1    0.05       0
Bank Sta=4967.1,4971.1
Exp/Cntr=0.3,0.1

Type RM Length L Ch R = 1,11309,35,35,35
BEGIN DESCRIPTION:
2365
END DESCRIPTION:
XS GIS Cut Line= 4
      2738297.19      6792296.94      2738011.45      6792186.26
      2737849.00      6792211.85      2737673.67      6792285.62
#Sta/Elev= 30
  4548.0  398.89  4560.0  398.97  4570.7  397.96  4582.6  397.17  4607.1  396.80
  4624.3  397.04  4691.5  396.61  4753.0  396.85  4776.0  396.29  4795.2  396.15
  4800.5  396.82  4806.7  395.63  4817.4  395.52  4825.1  395.73  4830.5  395.52
  4838.8  395.89  4849.3  395.58  4910.6  395.55  4916.3  395.92  4930.8  395.65
  5081.5  395.62  5085.2  395.46  5085.5  394.96  5089.0  394.96  5089.2  395.46
  5098.1  395.48  5119.8  396.60  5163.6  397.78  5187.3  398.24  5209.1  398.22
#Mann=3,-1,0
  4548.0    0.05       0  5085.2    0.04       0  5089.2    0.05       0
Bank Sta=5085.2,5089.2
Exp/Cntr=0.3,0.1

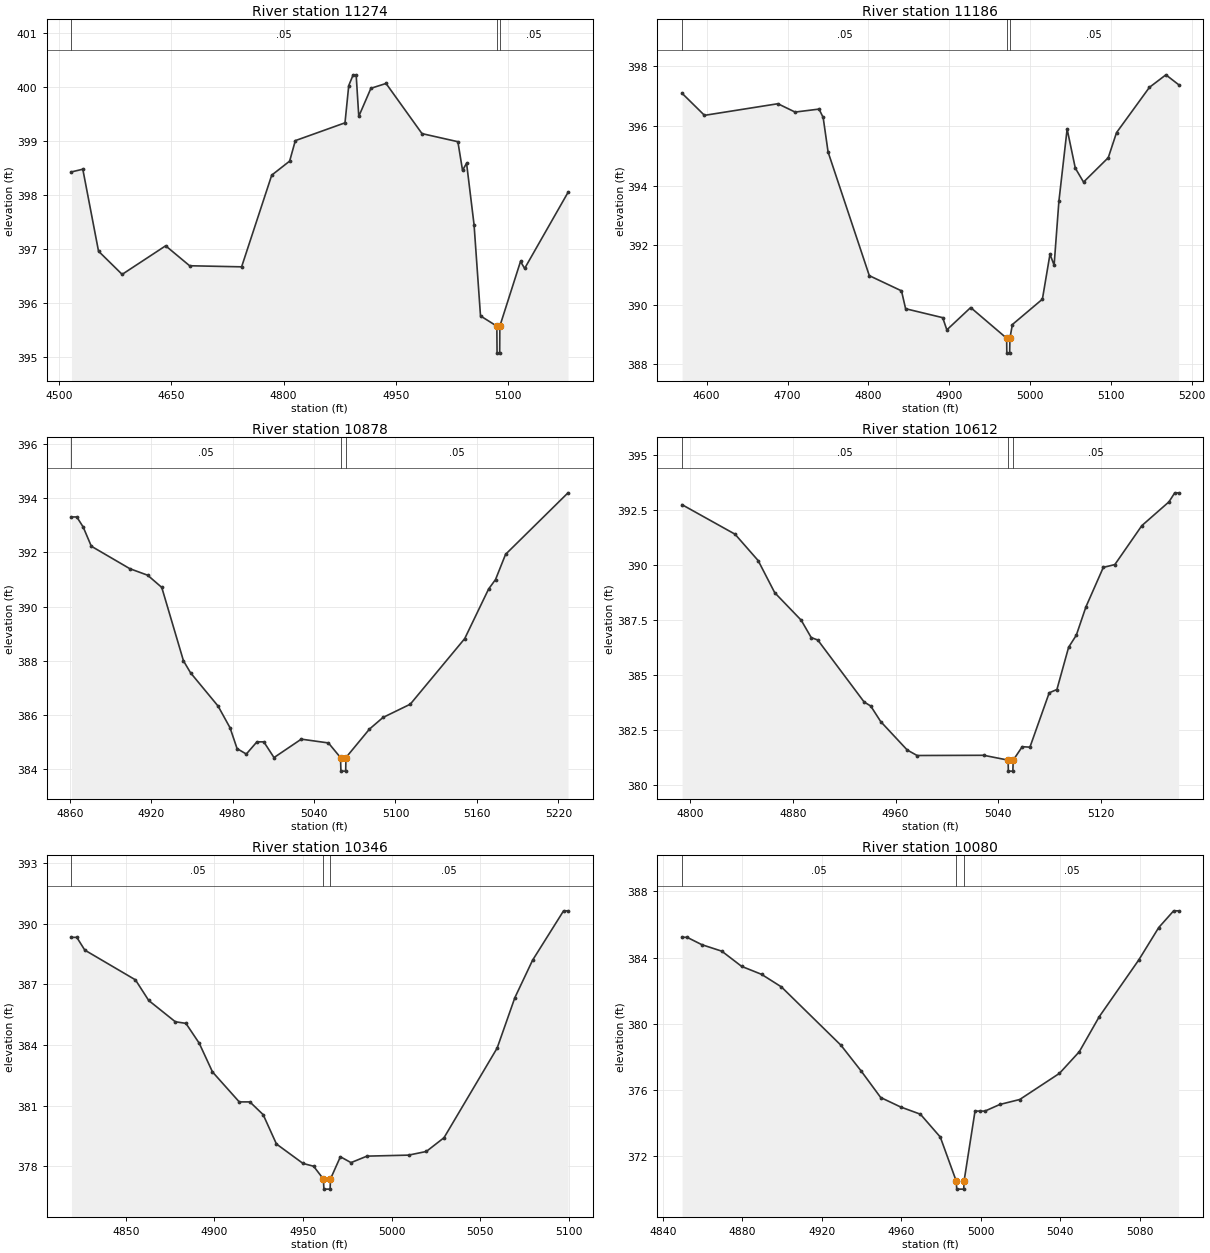
Type RM Length L Ch R = 1,11274,88,88,88
BEGIN DESCRIPTION:
1310
END DESCRIPTION:
XS GIS Cut Line= 6
      2738310.38      6792254.61      2738012.66      6792158.67
      2737948.00      6792155.40      2737900.78      6792161.21
      2737846.18      6792181.03      2737679.93      6792248.97
#Sta/Elev= 30
  4516.8  398.43  4531.9  398.48  4552.9  396.96  4584.4  396.53  4642.5  397.06
  4674.5  396.69  4743.9  396.67  4784.1  398.37  4808.0  398.63  4815.6  399.01
  4881.9  399.34  4886.9  400.03  4892.8  400.23  4896.8  400.23  4900.3  399.46
  4916.5  399.98  4936.7  400.07  4984.7  399.14  5032.6  398.99  5038.8  398.46
  5044.2  398.59  5054.2  397.45  5062.8  395.76  5084.6  395.57  5084.9  395.07
  5088.4  395.07  5088.6  395.57  5116.2  396.77  5121.7  396.64  5179.6  398.05
#Mann=3,-1,0
  4516.8    0.05       0  5084.6    0.04       0  5088.6    0.05       0
Bank Sta=5084.6,5088.6
Exp/Cntr=0.3,0.1

Type RM Length L Ch R = 1,11186,308,308,308
BEGIN DESCRIPTION:
2364
END DESCRIPTION:
XS GIS Cut Line= 3
      2738293.13      6792160.04      2737959.22      6792093.24
      2737690.61      6792145.66
#Sta/Elev= 30
  4569.6  397.10  4597.3  396.36  4688.1  396.75  4709.4  396.47  4739.0  396.57
  4744.1  396.29  4750.2  395.13  4801.2  390.98  4841.0  390.47  4846.1  389.87
  4892.0  389.57  4897.1  389.16  4926.6  389.91  4971.1  388.88  4971.3  388.38
  4974.8  388.38  4975.1  388.88  4978.2  389.34  5015.3  390.19  5024.7  391.70
  5029.8  391.33  5035.7  393.47  5045.9  395.90  5056.0  394.59  5066.2  394.12
  5096.8  394.94  5107.0  395.78  5147.7  397.30  5168.1  397.72  5183.8  397.39
#Mann=3,-1,0
  4569.6    0.05       0  4971.1    0.04       0  4975.1    0.05       0
Bank Sta=4971.1,4975.1
Exp/Cntr=0.3,0.1

Type RM Length L Ch R = 1,10878,266,266,266
BEGIN DESCRIPTION:
1309
END DESCRIPTION:
XS GIS Cut Line= 3
      2738160.12      6791898.07      2738026.00      6791861.00
      2737800.22      6791841.09
#Sta/Elev= 30
  4861.3  393.31  4865.2  393.31  4869.9  392.94  4875.9  392.23  4904.3  391.40
  4917.4  391.16  4927.8  390.71  4943.8  388.00  4949.0  387.56  4969.3  386.33
  4978.1  385.53  4983.3  384.76  4990.1  384.56  4997.9  385.01  5003.0  385.01
  5010.5  384.43  5030.6  385.11  5050.6  384.97  5059.5  384.43  5059.8  383.93
  5063.3  383.93  5063.5  384.43  5080.8  385.48  5090.8  385.91  5110.9  386.40
  5151.0  388.82  5168.6  390.65  5173.7  391.00  5181.1  391.93  5227.1  394.20
#Mann=3,-1,0
  4861.3    0.05       0  5059.5    0.04       0  5063.5    0.05       0
Bank Sta=5059.5,5063.5
Exp/Cntr=0.3,0.1

Type RM Length L Ch R = 1,10612,266,266,266
BEGIN DESCRIPTION:
1308
END DESCRIPTION:
XS GIS Cut Line= 3
      2738275.95      6791660.99      2738076.00      6791611.00
      2737925.99      6791510.99
#Sta/Elev= 30
  4793.9  392.75  4835.1  391.41  4853.1  390.21  4866.0  388.75  4886.6  387.50
  4894.4  386.71  4899.5  386.60  4935.6  383.78  4940.7  383.60  4948.5  382.89
  4969.1  381.60  4976.8  381.35  5028.6  381.36  5047.6  381.14  5047.8  380.64
  5051.3  380.64  5051.6  381.14  5058.6  381.75  5064.6  381.73  5079.6  384.20
  5085.6  384.35  5094.7  386.27  5100.7  386.82  5108.2  388.11  5121.7  389.90
  5130.7  390.03  5151.7  391.80  5172.8  392.88  5177.3  393.29  5180.3  393.29
#Mann=3,-1,0
  4793.9    0.05       0  5047.6    0.04       0  5051.6    0.05       0
Bank Sta=5047.6,5051.6
Exp/Cntr=0.3,0.1

Type RM Length L Ch R = 1,10346,266,266,266
BEGIN DESCRIPTION:
1307
END DESCRIPTION:
XS GIS Cut Line= 3
      2738276.02      6791461.01      2738126.00      6791361.00
      2738026.00      6791361.00
#Sta/Elev= 30
  4819.3  389.32  4822.3  389.32  4826.8  388.69  4855.4  387.22  4862.9  386.20
  4877.9  385.15  4883.9  385.07  4891.4  384.09  4898.9  382.67  4914.0  381.19
  4920.0  381.19  4927.5  380.56  4935.0  379.11  4950.0  378.15  4956.0  378.01
  4961.5  377.38  4961.8  376.88  4965.3  376.88  4965.5  377.38  4971.1  378.48
  4977.1  378.19  4986.1  378.51  5009.6  378.56  5019.6  378.74  5029.6  379.42
  5059.6  383.85  5069.6  386.34  5079.6  388.19  5097.1  390.63  5099.6  390.63
#Mann=3,-1,0
  4819.3    0.05       0  4961.5    0.04       0  4965.5    0.05       0
Bank Sta=4961.5,4965.5
Exp/Cntr=0.3,0.1

Type RM Length L Ch R = 1,10080,282,282,282
BEGIN DESCRIPTION:
1306
END DESCRIPTION:
XS GIS Cut Line= 3
      2738326.01      6791111.00      2738176.00      6791111.00
      2738076.01      6791111.00
#Sta/Elev= 29
  4849.6  385.23  4852.1  385.23  4859.6  384.78  4869.6  384.39  4879.6  383.47
  4889.6  382.99  4899.6  382.23  4929.6  378.70  4939.6  377.17  4949.6  375.54
  4959.6  374.97  4969.6  374.53  4979.6  373.15  4987.6  370.50  4987.9  370.00
  4991.4  370.00  4991.6  370.50  4997.1  374.72  4999.6  374.72  5002.1  374.72
  5009.6  375.12  5019.6  375.42  5039.6  377.00  5049.6  378.31  5059.6  380.42
  5079.6  383.87  5089.6  385.82  5097.1  386.83  5099.6  386.83
#Mann=3,-1,0
  4849.6    0.05       0  4987.6    0.04       0  4991.6    0.05       0
Bank Sta=4987.6,4991.6
Exp/Cntr=0.3,0.1

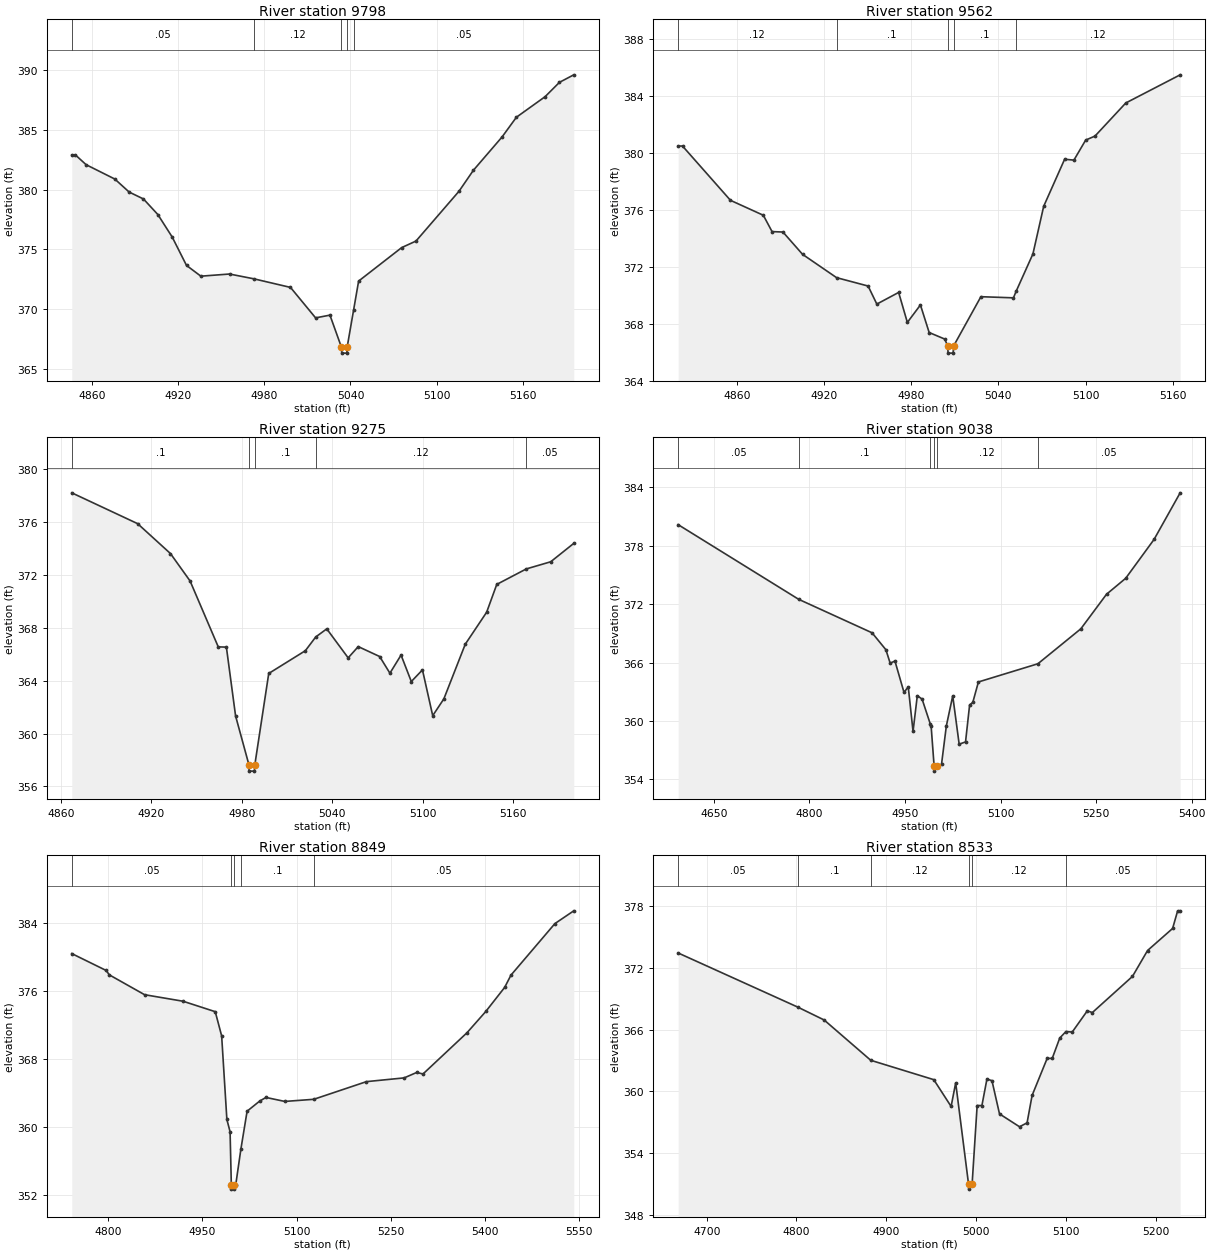
Type RM Length L Ch R = 1,9798,236,236,236
BEGIN DESCRIPTION:
1305
END DESCRIPTION:
XS GIS Cut Line= 3
      2738426.04      6790861.00      2738276.00      6790861.00
      2738076.04      6790861.00
#Sta/Elev= 30
  4845.7  382.90  4848.2  382.90  4855.7  382.08  4875.7  380.88  4885.7  379.79
  4895.7  379.21  4905.7  377.91  4915.7  376.03  4925.7  373.65  4935.7  372.75
  4955.7  372.93  4972.6  372.53  4998.2  371.81  5015.7  369.26  5025.7  369.49
  5033.7  366.81  5034.0  366.31  5037.5  366.31  5037.7  366.81  5042.2  369.92
  5045.7  372.34  5075.7  375.14  5085.7  375.69  5115.7  379.86  5125.7  381.61
  5145.7  384.40  5155.7  386.05  5175.7  387.77  5185.7  388.97  5195.7  389.60
#Mann=5,-1,0
  4845.7    0.05       0  4972.6    0.12       0  5033.7    0.07       0
  5037.7    0.12       0  5042.2    0.05       0
Bank Sta=5033.7,5037.7
Exp/Cntr=0.3,0.1

Type RM Length L Ch R = 1,9562,287,287,287
BEGIN DESCRIPTION:
1304
END DESCRIPTION:
XS GIS Cut Line= 3
      2738425.98      6790760.98      2738276.00      6790661.00
      2738146.77      6790558.17
#Sta/Elev= 30
  4819.7  380.50  4822.7  380.50  4855.7  376.68  4878.3  375.63  4884.3  374.48
  4891.8  374.45  4905.3  372.88  4928.7  371.24  4950.4  370.65  4956.4  369.38
  4971.4  370.20  4977.4  368.09  4986.4  369.32  4992.4  367.38  5003.1  366.92
  5005.2  366.43  5005.4  365.93  5008.9  365.93  5009.2  366.43  5028.0  369.90
  5050.4  369.82  5052.2  370.27  5063.8  372.91  5071.2  376.26  5085.6  379.57
  5092.0  379.51  5100.1  380.92  5106.5  381.20  5127.7  383.53  5165.1  385.51
#Mann=5,-1,0
  4819.7    0.12       0  4928.7     0.1       0  5005.2    0.07       0
  5009.2     0.1       0  5052.2    0.12       0
Bank Sta=5005.2,5009.2
Exp/Cntr=0.3,0.1

Type RM Length L Ch R = 1,9275,237,237,237
BEGIN DESCRIPTION:
1303
END DESCRIPTION:
XS GIS Cut Line= 3
      2738509.42      6790651.64      2738459.33      6790528.54
      2738324.55      6790380.51
#Sta/Elev= 30
  4867.1  378.19  4910.8  375.86  4932.6  373.60  4945.6  371.53  4964.3  366.55
  4969.7  366.53  4975.8  361.33  4984.6  357.66  4984.8  357.16  4988.3  357.16
  4988.6  357.66  4997.8  364.54  5022.1  366.26  5029.0  367.30  5036.3  367.91
  5050.5  365.72  5057.2  366.57  5071.4  365.82  5078.2  364.56  5085.6  365.93
  5092.4  363.93  5099.8  364.81  5106.6  361.35  5114.0  362.62  5128.2  366.75
  5142.4  369.17  5149.1  371.27  5168.7  372.44  5184.9  372.98  5200.2  374.37
#Mann=5,-1,0
  4867.1     0.1       0  4984.6    0.07       0  4988.6     0.1       0
  5029.0    0.12       0  5168.7    0.05       0
Bank Sta=4984.6,4988.6
Exp/Cntr=0.3,0.1

Type RM Length L Ch R = 1,9038,189,189,189
BEGIN DESCRIPTION:
1302
END DESCRIPTION:
XS GIS Cut Line= 4
      2739006.78      6790464.25      2738710.20      6790436.43
      2738626.00      6790361.00      2738250.99      6790321.63
#Sta/Elev= 30
  4594.0  380.17  4783.2  372.50  4898.4  369.06  4920.1  367.32  4926.8  365.94
  4934.3  366.16  4948.5  362.94  4955.2  363.50  4962.7  358.93  4969.4  362.60
  4976.9  362.25  4990.0  359.65  4991.1  359.47  4995.8  355.35  4996.1  354.85
  4999.8  355.35  5007.4  355.55  5015.0  359.50  5025.0  362.58  5035.1  357.62
  5045.1  357.85  5051.5  361.65  5056.5  361.91  5065.3  364.01  5158.7  365.88
  5226.1  369.47  5266.4  373.02  5296.5  374.66  5341.0  378.65  5382.0  383.44
#Mann=6,-1,0
  4594.0    0.05       0  4783.2     0.1       0  4990.0    0.12       0
  4995.8    0.07       0  4999.8    0.12       0  5158.7    0.05       0
Bank Sta=4995.8,4999.8
Exp/Cntr=0.3,0.1

Type RM Length L Ch R = 1,8849,316,316,316
BEGIN DESCRIPTION:
1301
END DESCRIPTION:
XS GIS Cut Line= 3
      2739019.26      6790308.68      2738767.05      6790254.34
      2738225.99      6790261.00
#Sta/Elev= 30
  4742.0  380.41  4796.5  378.43  4801.9  377.90  4857.9  375.57  4919.2  374.80
  4970.4  373.57  4980.6  370.72  4988.9  360.89  4994.0  359.44  4996.0  353.19
  4996.2  352.69  4999.7  352.69  5000.0  353.19  5003.0  353.19  5011.3  357.44
  5021.1  361.86  5041.1  363.05  5051.1  363.48  5081.1  363.01  5127.2  363.26
  5211.1  365.34  5271.1  365.78  5291.1  366.42  5301.1  366.24  5371.1  371.09
  5401.1  373.60  5431.1  376.43  5441.1  377.87  5511.1  383.94  5541.1  385.44
#Mann=5,-1,0
  4742.0    0.05       0  4996.0    0.04       0  5000.0    0.05       0
  5011.3     0.1       0  5127.2    0.05       0
Bank Sta=4996,5000
Exp/Cntr=0.3,0.1

Type RM Length L Ch R = 1,8533,266,266,266
BEGIN DESCRIPTION:
1300
END DESCRIPTION:
XS GIS Cut Line= 3
      2738855.94      6790000.00      2738526.00      6790061.00
      2738326.03      6790160.98
#Sta/Elev= 30
  4668.2  373.43  4801.4  368.18  4830.8  366.93  4882.7  363.02  4952.9  361.14
  4972.2  358.54  4977.3  360.83  4991.6  351.02  4991.8  350.52  4995.6  351.02
  5001.2  358.63  5006.5  358.63  5012.1  361.20  5017.7  361.04  5026.1  357.82
  5048.4  356.57  5056.8  356.95  5062.4  359.61  5079.2  363.21  5084.8  363.20
  5093.2  365.18  5100.1  365.81  5107.1  365.76  5123.9  367.82  5129.5  367.65
  5174.2  371.16  5191.0  373.67  5218.9  375.81  5224.5  377.52  5227.3  377.52
#Mann=6,-1,0
  4668.2    0.05       0  4801.4     0.1       0  4882.7    0.12       0
  4991.6    0.07       0  4995.6    0.12       0  5100.1    0.05       0
Bank Sta=4991.6,4995.6
Exp/Cntr=0.3,0.1

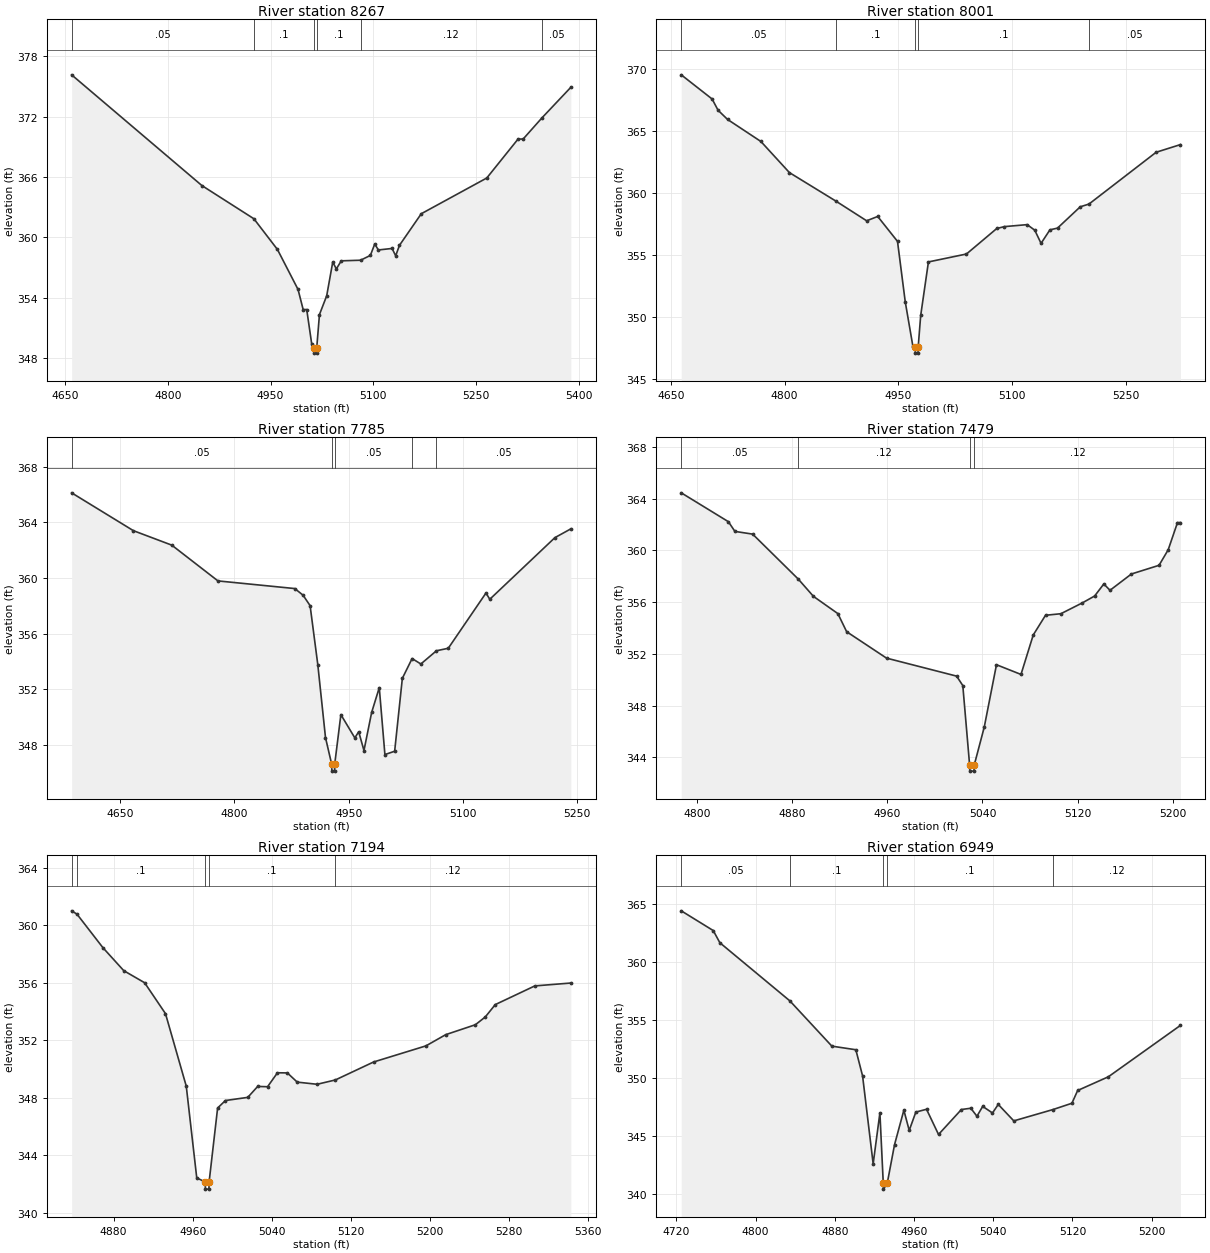
Type RM Length L Ch R = 1,8267,266,266,266
BEGIN DESCRIPTION:
1299
END DESCRIPTION:
XS GIS Cut Line= 3
      2738915.68      6789838.64      2738576.00      6789811.00
      2738210.48      6789942.90
#Sta/Elev= 30
  4659.3  376.16  4849.6  365.16  4925.6  361.86  4960.0  358.81  4990.1  354.84
  4997.6  352.84  5002.8  352.84  5010.1  349.42  5013.4  349.01  5013.7  348.51
  5017.2  348.51  5017.4  349.01  5021.4  352.34  5032.0  354.21  5040.8  357.55
  5046.1  356.88  5053.3  357.68  5081.5  357.74  5095.8  358.22  5102.2  359.35
  5107.5  358.76  5127.5  358.91  5132.8  358.18  5138.3  359.22  5170.2  362.36
  5265.9  365.91  5311.6  369.78  5319.0  369.78  5346.6  371.89  5388.7  374.92
#Mann=6,-1,0
  4659.3    0.05       0  4925.6     0.1       0  5013.4    0.07       0
  5017.4     0.1       0  5081.5    0.12       0  5346.6    0.05       0
Bank Sta=5013.4,5017.4
Exp/Cntr=0.3,0.1

Type RM Length L Ch R = 1,8001,216,216,216
BEGIN DESCRIPTION:
1298
END DESCRIPTION:
XS GIS Cut Line= 3
      2738855.97      6789625.94      2738526.00      6789561.00
      2738203.90      6789572.37
#Sta/Elev= 30
  4663.7  369.52  4704.4  367.57  4712.3  366.66  4724.8  365.92  4768.8  364.14
  4806.4  361.63  4867.7  359.33  4908.3  357.74  4922.9  358.09  4949.0  356.08
  4959.2  351.21  4969.2  347.65  4972.3  347.56  4972.6  347.06  4976.1  347.06
  4976.3  347.56  4979.6  350.10  4989.8  354.42  5040.0  355.06  5080.0  357.12
  5090.1  357.27  5120.1  357.43  5130.1  356.98  5138.4  355.92  5150.1  357.01
  5160.1  357.15  5190.1  358.87  5201.6  359.09  5290.2  363.27  5322.3  363.89
#Mann=5,-1,0
  4663.7    0.05       0  4867.7     0.1       0  4972.3    0.07       0
  4976.3     0.1       0  5201.6    0.05       0
Bank Sta=4972.3,4976.3
Exp/Cntr=0.3,0.1

Type RM Length L Ch R = 1,7785,306,306,306
BEGIN DESCRIPTION:
1297
END DESCRIPTION:
XS GIS Cut Line= 3
      2738886.37      6789415.78      2738476.33      6789360.86
      2738236.11      6789334.15
#Sta/Elev= 30
  4586.3  366.11  4667.4  363.39  4717.8  362.35  4778.4  359.78  4879.3  359.23
  4890.2  358.75  4899.4  358.00  4909.5  353.76  4919.6  348.52  4927.7  346.61
  4928.0  346.11  4931.5  346.11  4931.7  346.61  4939.8  350.17  4958.1  348.50
  4963.2  348.94  4970.1  347.59  4980.2  350.33  4990.2  352.11  4997.6  347.30
  5010.4  347.54  5020.5  352.78  5033.3  354.20  5044.8  353.81  5065.3  354.76
  5080.8  354.94  5130.3  358.91  5135.3  358.46  5220.8  362.89  5241.7  363.52
#Mann=5,-1,0
  4586.3    0.05       0  4927.7    0.04       0  4931.7    0.05       0
  5033.3    0.12       0  5065.3    0.05       0
Bank Sta=4927.7,4931.7
Exp/Cntr=0.3,0.1

Type RM Length L Ch R = 1,7479,285,285,285
BEGIN DESCRIPTION:
1296
END DESCRIPTION:
XS GIS Cut Line= 3
      2738734.69      6789155.47      2738526.00      6789111.00
      2738326.03      6789061.01
#Sta/Elev= 30
  4786.9  364.44  4826.5  362.21  4832.0  361.46  4846.9  361.25  4885.3  357.77
  4898.0  356.44  4918.5  355.11  4925.9  353.71  4959.4  351.67  5018.3  350.28
  5023.5  349.55  5029.2  343.44  5029.4  342.94  5032.9  342.94  5033.2  343.44
  5041.5  346.33  5051.8  351.16  5072.4  350.41  5082.7  353.46  5093.0  354.98
  5105.9  355.10  5124.0  355.94  5134.3  356.47  5142.0  357.40  5147.2  356.91
  5165.2  358.17  5188.4  358.84  5196.1  360.04  5203.9  362.14  5206.4  362.14
#Mann=4,-1,0
  4786.9    0.05       0  4885.3    0.12       0  5029.2    0.07       0
  5033.2    0.12       0
Bank Sta=5029.2,5033.2
Exp/Cntr=0.3,0.1

Type RM Length L Ch R = 1,7194,245,245,245
BEGIN DESCRIPTION:
1295
END DESCRIPTION:
XS GIS Cut Line= 3
      2738775.99      6788911.00      2738626.00      6788861.00
      2738279.60      6788849.39
#Sta/Elev= 30
  4837.6  361.01  4843.0  360.78  4869.2  358.45  4890.3  356.85  4911.4  356.01
  4932.5  353.86  4953.5  348.82  4964.1  342.44  4972.6  342.16  4972.9  341.66
  4976.4  341.66  4976.6  342.16  4985.2  347.30  4993.1  347.82  5015.7  348.04
  5025.7  348.80  5035.7  348.78  5045.7  349.75  5055.7  349.74  5065.7  349.10
  5085.8  348.95  5104.2  349.25  5142.9  350.50  5195.8  351.62  5215.8  352.40
  5245.8  353.09  5255.8  353.63  5265.9  354.49  5305.9  355.79  5342.3  355.99
#Mann=5,-1,0
  4837.6    0.05       0  4843.0     0.1       0  4972.6    0.07       0
  4976.6     0.1       0  5104.2    0.12       0
Bank Sta=4972.6,4976.6
Exp/Cntr=0.3,0.1

Type RM Length L Ch R = 1,6949,261,261,261
BEGIN DESCRIPTION:
1294
END DESCRIPTION:
XS GIS Cut Line= 3
      2738875.98      6788810.99      2738626.00      6788711.00
      2738423.13      6788592.66
#Sta/Elev= 30
  4725.0  364.42  4757.3  362.72  4764.0  361.67  4834.7  356.66  4877.1  352.76
  4901.3  352.45  4908.1  350.20  4918.8  342.62  4925.6  347.01  4929.0  340.94
  4929.2  340.44  4933.0  340.94  4940.4  344.28  4949.8  347.24  4955.2  345.50
  4961.9  347.08  4972.7  347.32  4984.8  345.15  5007.9  347.30  5017.4  347.41
  5023.6  346.72  5029.4  347.57  5039.3  347.00  5045.1  347.74  5060.8  346.32
  5100.5  347.30  5119.5  347.84  5125.3  348.94  5156.3  350.12  5229.1  354.55
#Mann=5,-1,0
  4725.0    0.05       0  4834.7     0.1       0  4929.0    0.07       0
  4933.0     0.1       0  5100.5    0.12       0
Bank Sta=4929,4933
Exp/Cntr=0.3,0.1

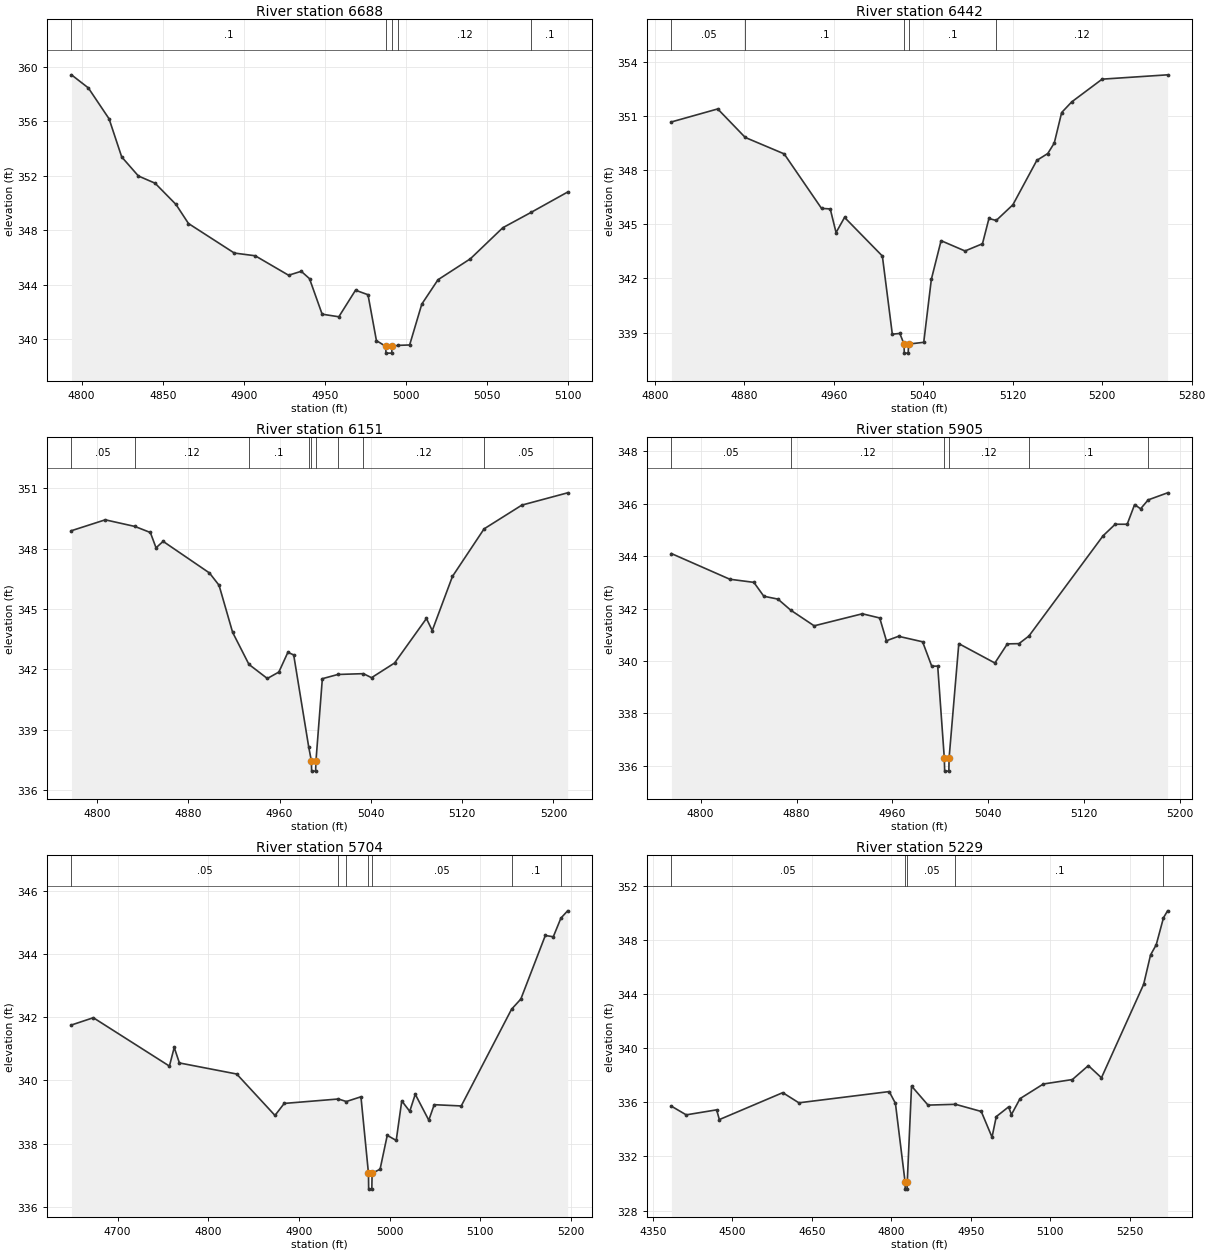
Type RM Length L Ch R = 1,6688,246,246,246
BEGIN DESCRIPTION:
1293
END DESCRIPTION:
XS GIS Cut Line= 3
      2738876.04      6788561.01      2738676.00      6788511.00
      2738576.00      6788511.00
#Sta/Elev= 30
  4793.7  359.42  4804.1  358.46  4816.9  356.19  4824.7  353.39  4835.0  351.99
  4845.3  351.46  4858.2  349.90  4865.9  348.50  4894.2  346.33  4907.1  346.13
  4927.7  344.70  4935.5  344.99  4940.6  344.45  4948.4  341.84  4958.7  341.65
  4969.0  343.60  4976.7  343.27  4981.9  339.90  4987.6  339.48  4987.8  338.98
  4991.3  338.98  4991.6  339.48  4995.4  339.55  5002.4  339.58  5009.9  342.58
  5019.9  344.37  5039.9  345.91  5059.9  348.19  5077.4  349.32  5099.9  350.81
#Mann=5,-1,0
  4793.7     0.1       0  4987.6    0.07       0  4991.6     0.1       0
  4995.4    0.12       0  5077.4     0.1       0
Bank Sta=4987.6,4991.6
Exp/Cntr=0.3,0.1

Type RM Length L Ch R = 1,6442,291,291,291
BEGIN DESCRIPTION:
1292
END DESCRIPTION:
XS GIS Cut Line= 3
      2738856.20      6788250.90      2738676.53      6788295.81
      2738454.73      6788428.40
#Sta/Elev= 30
  4814.8  350.67  4856.2  351.39  4880.8  349.81  4915.6  348.90  4949.0  345.88
  4956.8  345.85  4962.0  344.54  4969.6  345.38  5003.4  343.24  5012.3  338.91
  5019.0  338.95  5022.8  338.36  5023.0  337.86  5026.5  337.86  5026.8  338.36
  5040.4  338.46  5047.2  341.95  5055.9  344.09  5077.3  343.52  5092.9  343.92
  5098.7  345.32  5105.2  345.21  5120.1  346.08  5141.5  348.54  5151.3  348.92
  5157.1  349.50  5163.7  351.19  5172.7  351.78  5199.9  353.04  5258.4  353.28
#Mann=5,-1,0
  4814.8    0.05       0  4880.8     0.1       0  5022.8    0.07       0
  5026.8     0.1       0  5105.2    0.12       0
Bank Sta=5022.8,5026.8
Exp/Cntr=0.3,0.1

Type RM Length L Ch R = 1,6151,246,246,246
BEGIN DESCRIPTION:
1291
END DESCRIPTION:
XS GIS Cut Line= 3
      2738845.16      6788098.23      2738626.00      6788061.00
      2738416.49      6788095.92
#Sta/Elev= 30
  4777.7  348.89  4807.3  349.43  4833.3  349.10  4846.8  348.80  4851.8  348.04
  4858.0  348.36  4898.6  346.79  4907.0  346.18  4918.9  343.84  4933.2  342.25
  4949.3  341.55  4959.4  341.87  4967.3  342.85  4972.4  342.72  4985.5  338.17
  4987.9  337.45  4988.1  336.95  4991.6  336.95  4991.9  337.45  4997.5  341.54
  5011.1  341.75  5033.5  341.79  5040.6  341.59  5060.8  342.32  5088.7  344.53
  5093.8  343.93  5111.5  346.62  5139.2  348.98  5172.3  350.16  5212.4  350.77
#Mann=9,-1,0
  4777.7    0.05       0  4833.3    0.12       0  4933.2     0.1       0
  4985.5    0.12       0  4987.9    0.07       0  4991.9    0.12       0
  5011.1     0.1       0  5033.5    0.12       0  5139.2    0.05       0
Bank Sta=4987.9,4991.9
Exp/Cntr=0.3,0.1

Type RM Length L Ch R = 1,5905,201,201,201
BEGIN DESCRIPTION:
1290
END DESCRIPTION:
XS GIS Cut Line= 3
      2738894.40      6787884.66      2738676.00      6787861.00
      2738482.45      6787878.35
#Sta/Elev= 30
  4775.6  344.10  4824.3  343.12  4844.4  343.00  4852.7  342.47  4864.5  342.36
  4875.1  341.94  4894.7  341.34  4934.9  341.80  4949.4  341.64  4955.0  340.77
  4965.1  340.94  4985.2  340.73  4992.8  339.80  4997.8  339.80  5003.3  336.29
  5003.6  335.79  5007.1  335.79  5007.3  336.29  5015.4  340.66  5045.5  339.92
  5055.9  340.65  5065.6  340.66  5073.9  340.95  5135.8  344.78  5145.9  345.22
  5155.9  345.22  5162.1  345.97  5167.1  345.81  5173.4  346.15  5189.6  346.42
#Mann=6,-1,0
  4775.6    0.05       0  4875.1    0.12       0  5003.3    0.07       0
  5007.3    0.12       0  5073.9     0.1       0  5173.4    0.05       0
Bank Sta=5003.3,5007.3
Exp/Cntr=0.3,0.1

Type RM Length L Ch R = 1,5704,475,475,475
BEGIN DESCRIPTION:
1289
END DESCRIPTION:
XS GIS Cut Line= 3
      2738988.86      6787580.32      2738656.03      6787691.16
      2738494.29      6787802.39
#Sta/Elev= 30
  4649.2  341.75  4673.3  341.98  4757.2  340.45  4762.5  341.04  4768.2  340.55
  4831.4  340.20  4873.6  338.89  4883.8  339.27  4943.5  339.41  4952.3  339.33
  4968.4  339.48  4976.7  337.06  4976.9  336.56  4980.4  336.56  4980.7  337.06
  4989.5  337.19  4997.4  338.26  5007.3  338.10  5013.4  339.35  5022.2  339.02
  5028.3  339.56  5043.2  338.74  5049.2  339.23  5079.0  339.19  5134.5  342.25
  5144.7  342.57  5171.7  344.58  5180.5  344.54  5188.9  345.13  5196.3  345.36
#Mann=7,-1,0
  4649.2    0.05       0  4943.5    0.12       0  4952.3    0.05       0
  4976.7    0.03       0  4980.7    0.05       0  5134.5     0.1       0
  5188.9    0.05       0
Bank Sta=4976.7,4980.7
Exp/Cntr=0.3,0.1

Type RM Length L Ch R = 1,5229,230,230,230
BEGIN DESCRIPTION:
1288
END DESCRIPTION:
XS GIS Cut Line= 3
      2739133.55      6787419.32      2738525.97      6787325.37
      2738226.03      6787211.01
#Sta/Elev= 30
  4385.2  335.71  4413.1  335.07  4470.5  335.44  4475.6  334.72  4595.2  336.71
  4625.6  335.96  4796.0  336.79  4807.7  335.92  4826.0  330.08  4826.2  329.58
  4829.7  329.58  4830.0  330.08  4838.1  337.20  4869.2  335.79  4921.0  335.85
  4969.6  335.32  4989.9  333.42  4997.9  334.94  5021.2  335.66  5026.5  335.09
  5042.8  336.27  5086.7  337.35  5141.5  337.68  5171.6  338.71  5196.3  337.81
  5275.9  344.72  5288.9  346.89  5299.6  347.64  5313.3  349.64  5321.0  350.15
#Mann=5,-1,0
  4385.2    0.05       0  4826.0    0.07       0  4830.0    0.05       0
  4921.0     0.1       0  5313.3    0.12       0
Bank Sta=4826,4830
Exp/Cntr=0.3,0.1