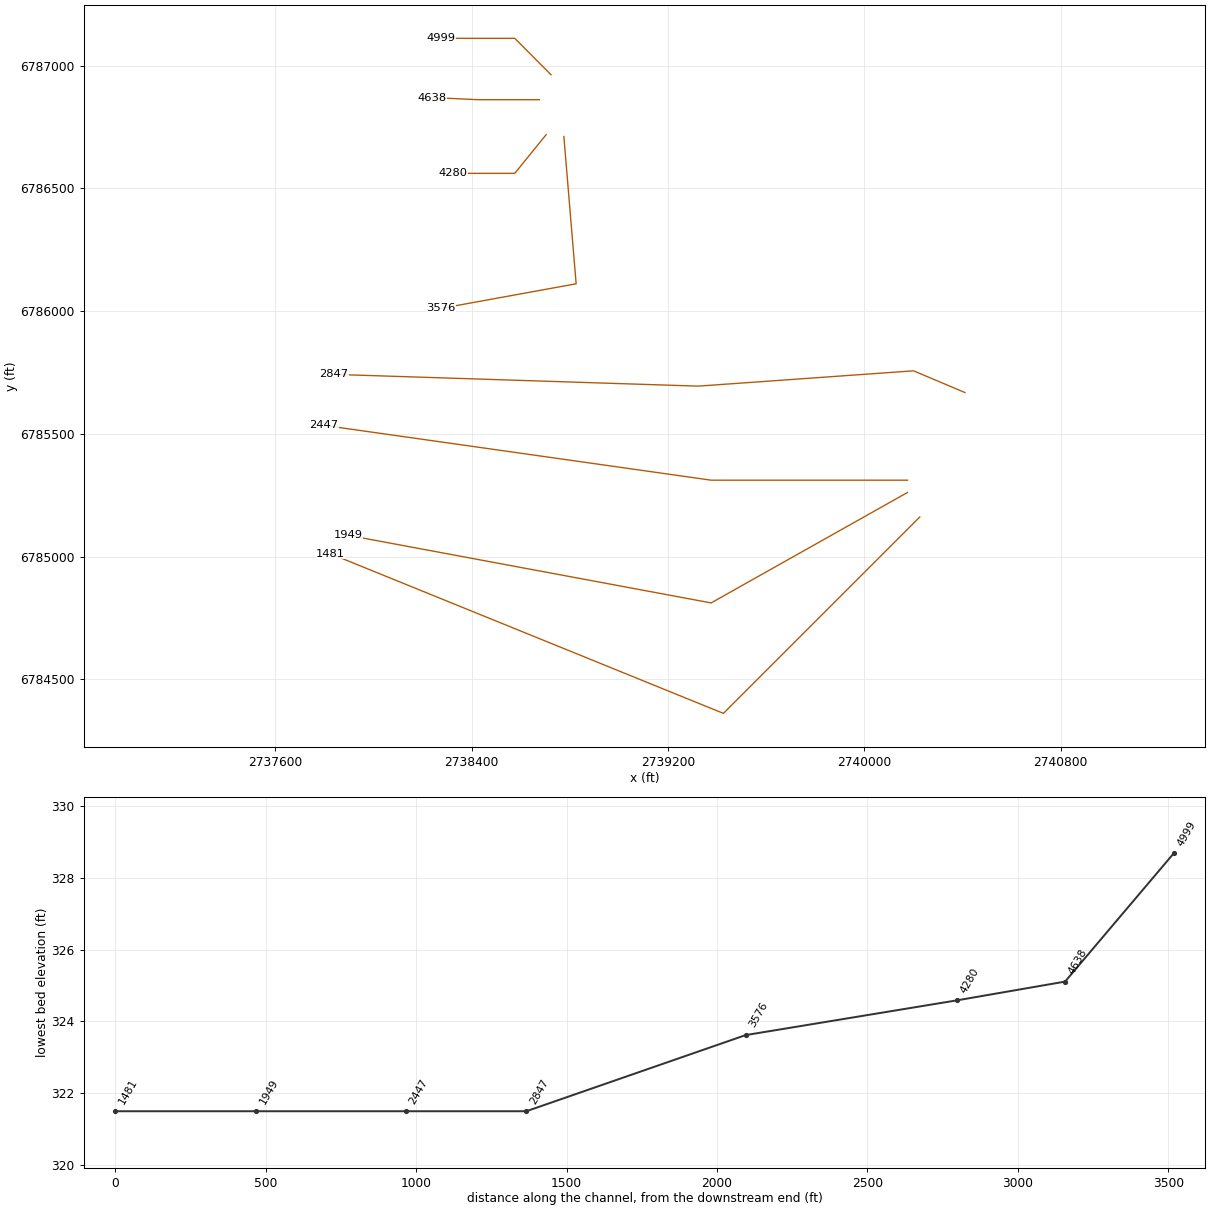
HEC-RAS study Clear Creek T 29.prj: Clear Creek T 29 Base Level Engineering

--- Clear Creek T 29.g01 (geometry) --- (continued)

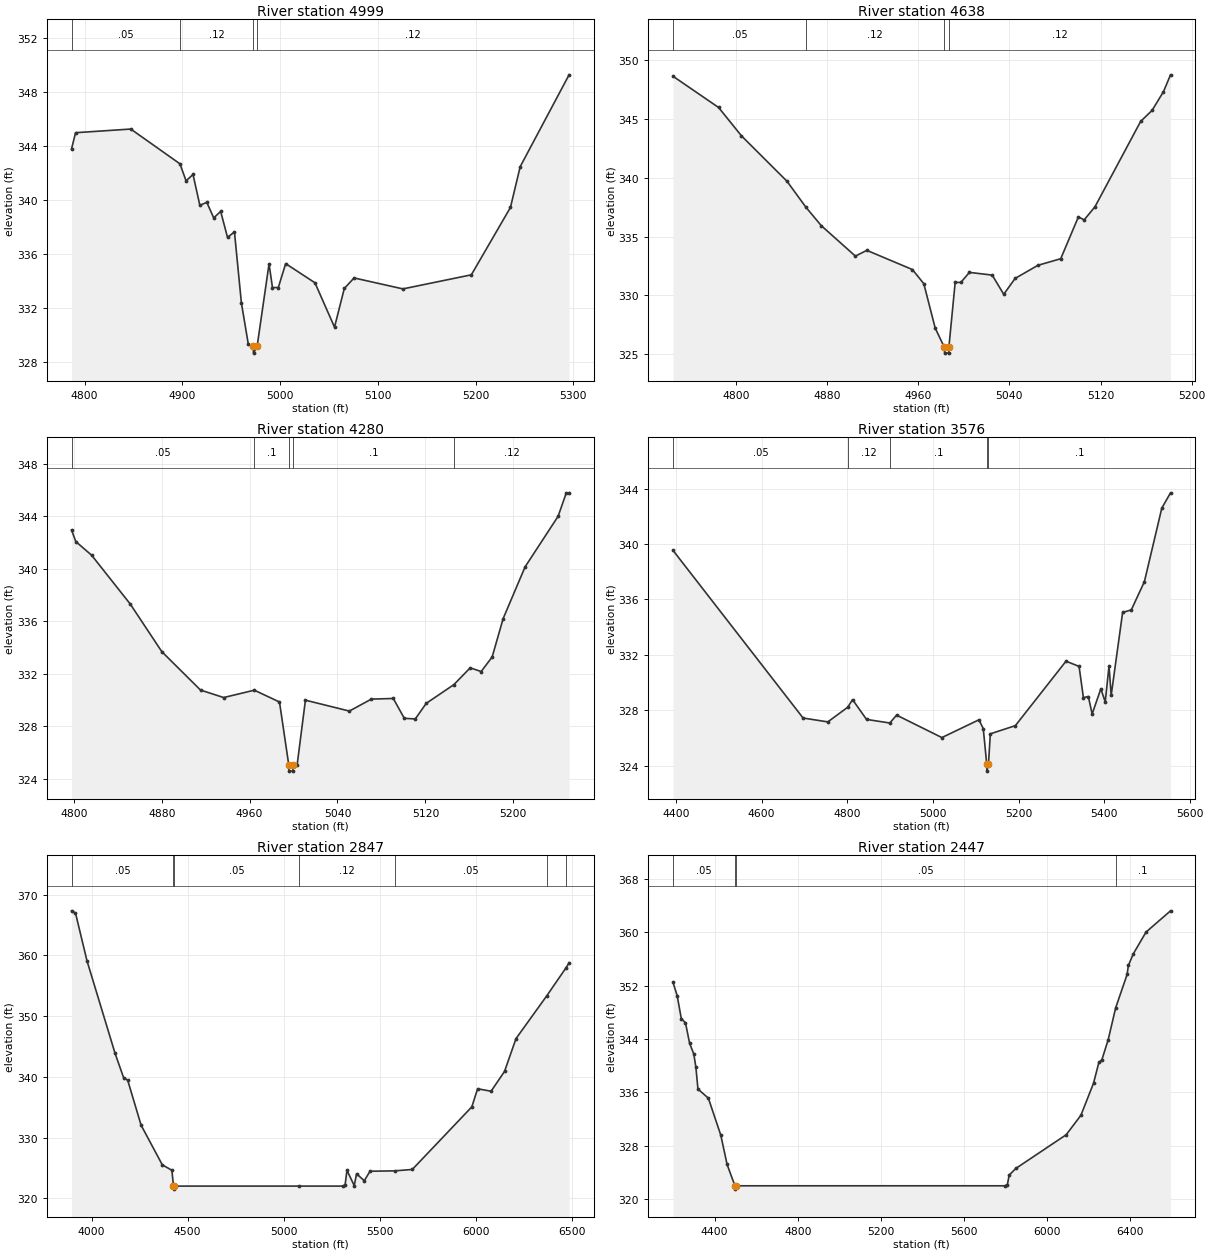
Type RM Length L Ch R = 1,4999,361,361,361
BEGIN DESCRIPTION:
1287
END DESCRIPTION:
XS GIS Cut Line= 3
      2738723.54      6786962.79      2738576.00      6787111.00
      2738276.03      6787111.00
#Sta/Elev= 30
  4786.6  343.78  4790.7  344.98  4847.2  345.25  4897.5  342.68  4903.8  341.42
  4910.9  341.89  4917.9  339.61  4925.0  339.83  4932.1  338.68  4939.2  339.16
  4946.2  337.24  4953.3  337.64  4960.4  332.40  4967.5  329.33  4972.5  329.18
  4972.8  328.68  4976.5  329.18  4988.7  335.28  4992.2  333.53  4998.2  333.53
  5005.7  335.30  5035.7  333.88  5055.7  330.60  5065.7  333.46  5075.7  334.24
  5125.7  333.43  5195.7  334.47  5235.7  339.45  5245.7  342.47  5295.7  349.26
#Mann=4,-1,0
  4786.6    0.05       0  4897.5    0.12       0  4972.5    0.07       0
  4976.5    0.12       0
Bank Sta=4972.5,4976.5
Exp/Cntr=0.3,0.1

Type RM Length L Ch R = 1,4638,358,358,358
BEGIN DESCRIPTION:
1286
END DESCRIPTION:
XS GIS Cut Line= 3
      2738676.01      6786861.00      2738426.00      6786861.00
      2738239.82      6786869.79
#Sta/Elev= 30
  4745.0  348.60  4785.0  345.95  4805.0  343.55  4845.0  339.69  4861.5  337.50
  4875.0  335.93  4905.0  333.34  4915.0  333.83  4955.0  332.20  4965.0  331.00
  4975.0  327.23  4983.0  325.61  4983.3  325.11  4986.8  325.11  4987.0  325.61
  4992.5  331.11  4997.5  331.11  5005.0  331.96  5025.0  331.73  5035.1  330.10
  5045.1  331.45  5065.1  332.56  5085.1  333.12  5100.6  336.67  5105.6  336.41
  5115.1  337.52  5155.2  344.77  5165.2  345.70  5175.2  347.29  5181.4  348.72
#Mann=4,-1,0
  4745.0    0.05       0  4861.5    0.12       0  4983.0    0.07       0
  4987.0    0.12       0
Bank Sta=4983,4987
Exp/Cntr=0.3,0.1

Type RM Length L Ch R = 1,4280,704,704,704
BEGIN DESCRIPTION:
1285
END DESCRIPTION:
XS GIS Cut Line= 3
      2738703.88      6786718.55      2738576.00      6786561.00
      2738326.02      6786561.00
#Sta/Elev= 30
  4797.9  342.94  4801.8  342.06  4816.2  341.02  4851.4  337.30  4880.1  333.68
  4915.3  330.76  4936.4  330.19  4964.3  330.75  4987.2  329.85  4995.6  325.09
  4995.8  324.59  4999.3  324.59  4999.6  325.09  5003.3  325.09  5010.8  329.99
  5050.8  329.16  5070.8  330.07  5090.8  330.12  5100.8  328.61  5110.8  328.56
  5120.8  329.75  5145.9  331.17  5160.8  332.45  5170.8  332.17  5180.8  333.28
  5190.8  336.20  5210.8  340.14  5240.8  343.98  5248.3  345.77  5250.8  345.77
#Mann=5,-1,0
  4797.9    0.05       0  4964.3     0.1       0  4995.6    0.07       0
  4999.6     0.1       0  5145.9    0.12       0
Bank Sta=4995.6,4999.6
Exp/Cntr=0.3,0.1

Type RM Length L Ch R = 1,3576,729,729,729
BEGIN DESCRIPTION:
1284
END DESCRIPTION:
XS GIS Cut Line= 3
      2738776.00      6786711.02      2738826.00      6786111.00
      2738276.02      6786011.00
#Sta/Elev= 30
  4393.2  339.54  4696.8  327.45  4754.5  327.17  4801.1  328.23  4812.2  328.78
  4844.8  327.35  4899.2  327.09  4915.0  327.66  5020.7  326.04  5107.1  327.32
  5117.3  326.69  5125.4  324.12  5125.7  323.62  5129.4  324.12  5133.8  326.31
  5192.2  326.90  5310.4  331.55  5340.9  331.17  5351.0  328.92  5362.5  329.00
  5371.4  327.74  5391.7  329.56  5401.9  328.61  5410.8  331.21  5415.8  329.08
  5442.5  335.06  5462.8  335.25  5493.3  337.28  5534.0  342.59  5554.3  343.69
#Mann=5,-1,0
  4393.2    0.05       0  4801.1    0.12       0  4899.2     0.1       0
  5125.4    0.07       0  5129.4     0.1       0
Bank Sta=5125.4,5129.4
Exp/Cntr=0.3,0.1

Type RM Length L Ch R = 1,2847,400,400,400
BEGIN DESCRIPTION:
2359
END DESCRIPTION:
XS GIS Cut Line= 4
      2740410.05      6785667.99      2740200.46      6785756.52
      2739323.41      6785694.12      2737839.97      6785742.00
#Sta/Elev= 30
  3895.8  367.36  3916.4  366.99  3976.2  359.13  4122.4  343.88  4167.9  339.78
  4187.9  339.48  4258.1  332.03  4368.4  325.51  4418.5  324.60  4426.6  322.00
  4426.8  321.50  4430.6  322.00  5082.8  322.00  5310.2  322.00  5320.2  322.15
  5330.2  324.60  5368.0  322.08  5380.2  324.03  5420.2  322.88  5450.2  324.45
  5578.3  324.51  5670.3  324.74  5980.5  335.06  6010.5  338.04  6080.6  337.63
  6150.6  340.89  6210.6  346.31  6371.0  353.37  6470.1  357.93  6486.8  358.78
#Mann=7,-1,0
  3895.8    0.05       0  4426.6    0.03       0  4430.6    0.05       0
  5082.8    0.12       0  5578.3    0.05       0  6371.0     0.1       0
  6470.1    0.05       0
Bank Sta=4426.6,4430.6
Exp/Cntr=0.3,0.1

Type RM Length L Ch R = 1,2447,498,498,498
BEGIN DESCRIPTION:
1283
END DESCRIPTION:
XS GIS Cut Line= 3
      2740175.99      6785311.00      2739376.00      6785311.00
      2737799.32      6785534.25
#Sta/Elev= 30
  4200.1  352.52  4220.1  350.54  4240.1  347.06  4260.1  346.46  4280.1  343.36
  4300.1  341.78  4310.1  339.80  4320.1  336.51  4370.1  335.15  4430.1  329.58
  4460.1  325.21  4497.9  322.00  4498.3  321.50  4502.2  322.00  5798.0  322.00
  5808.1  322.18  5816.7  323.61  5848.5  324.60  6090.9  329.66  6161.6  332.58
  6222.2  337.38  6247.9  340.50  6262.6  340.92  6292.9  343.93  6328.8  348.70
  6383.8  353.71  6389.9  355.06  6414.1  356.83  6474.7  360.06  6592.5  363.25
#Mann=4,-1,0
  4200.1    0.05       0  4497.9    0.03       0  4502.2    0.05       0
  6328.8     0.1       0
Bank Sta=4497.9,4502.2
Exp/Cntr=0.3,0.1

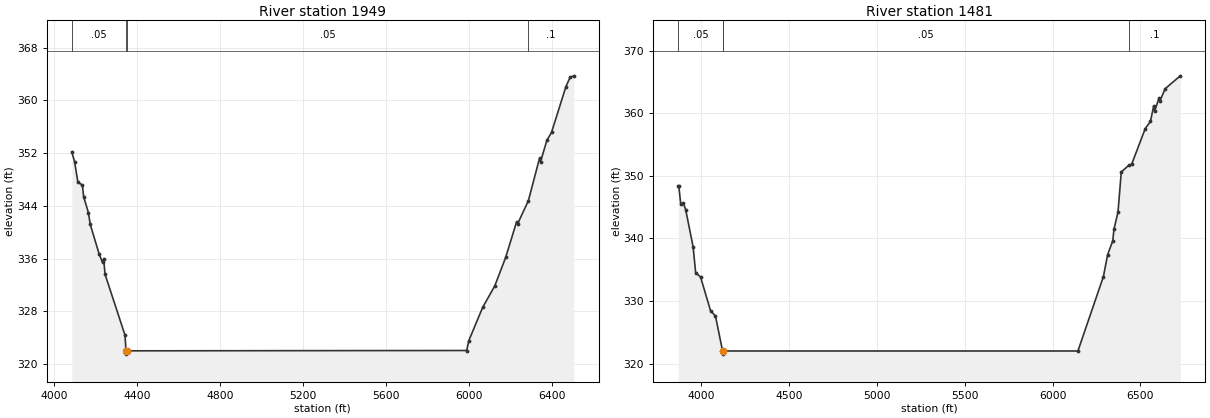
Type RM Length L Ch R = 1,1949,468,468,468
BEGIN DESCRIPTION:
1282
END DESCRIPTION:
XS GIS Cut Line= 3
      2740175.98      6785260.99      2739376.00      6784811.00
      2737898.07      6785086.28
#Sta/Elev= 30
  4086.3  352.20  4100.0  350.68  4115.9  347.58  4137.6  347.16  4143.6  345.38
  4166.6  342.96  4175.2  341.21  4218.5  336.67  4234.5  335.42  4240.2  335.88
  4246.9  333.60  4342.8  324.40  4348.0  322.00  4348.4  321.50  4352.3  322.00
  5990.8  322.05  6001.0  323.55  6068.1  328.61  6125.9  331.83  6178.7  336.17
  6231.4  341.57  6236.5  341.28  6288.3  344.79  6341.9  351.20  6347.0  350.71
  6377.4  353.93  6399.8  355.14  6468.9  362.05  6489.3  363.51  6507.5  363.73
#Mann=4,-1,0
  4086.3    0.05       0  4348.0    0.03       0  4352.3    0.05       0
  6288.3     0.1       0
Bank Sta=4348,4352.3
Exp/Cntr=0.3,0.1

Type RM Length L Ch R = 1,1481,0,0,0
BEGIN DESCRIPTION:
1281
END DESCRIPTION:
XS GIS Cut Line= 3
      2740225.99      6785160.99      2739426.00      6784361.00
      2737825.96      6785011.02
#Sta/Elev= 30
  3868.6  348.30  3872.1  348.30  3882.7  345.50  3896.9  345.66  3911.0  344.57
  3953.4  338.63  3967.6  334.54  3995.9  333.80  4052.4  328.45  4080.7  327.57
  4121.0  322.00  4121.4  321.50  4125.3  322.00  6144.1  322.00  6289.2  333.89
  6313.3  337.40  6342.7  339.62  6349.2  341.44  6372.2  344.18  6390.9  350.60
  6434.8  351.69  6449.8  351.82  6527.5  357.54  6557.0  358.67  6575.6  361.17
  6581.0  360.32  6605.1  362.36  6610.5  361.90  6640.6  363.90  6727.0  365.96
#Mann=4,-1,0
  3868.6    0.05       0  4121.0    0.03       0  4125.3    0.05       0
  6434.8     0.1       0
Bank Sta=4121,4125.3
Exp/Cntr=0.3,0.1

Chan Stop Cuts=-1