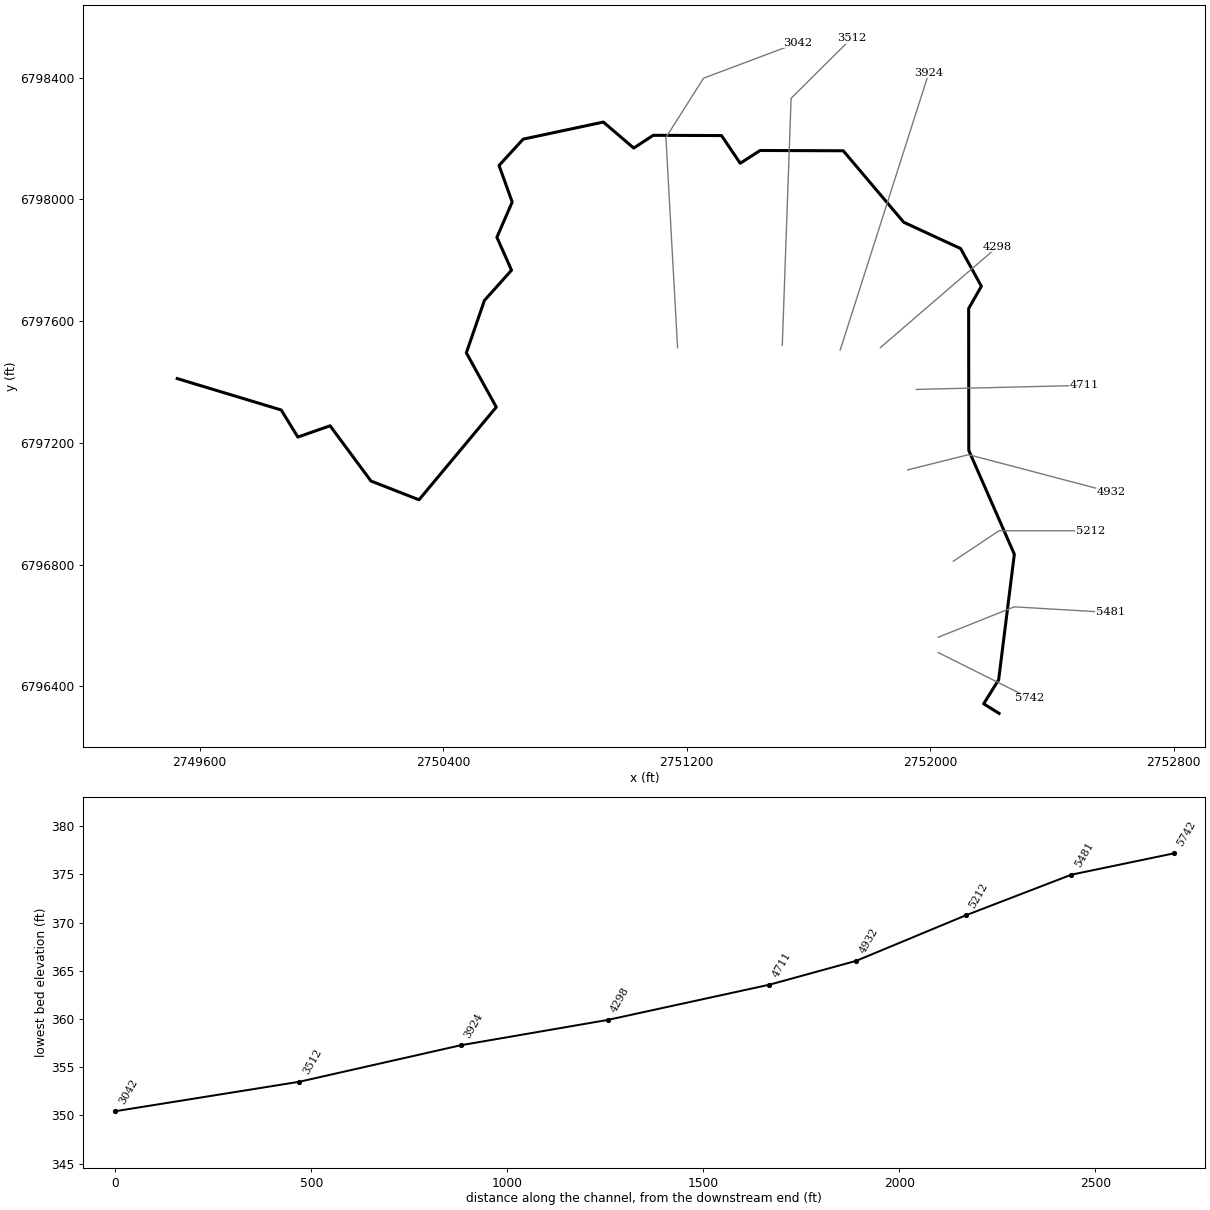
--- Clear Creek T 3.prj (project) ---

Proj Title=Clear Creek T 3 Base Level Engineering
Current Plan=p01
Default Exp/Contr=0.3,0.1
English Units
Geom File=g01
Flow File=f01
Plan File=p01
BEGIN DESCRIPTION:
Clear Creek T 3
END DESCRIPTION:

--- Clear Creek T 3.p01 (plan) ---

Plan Title=Multiple Run
Short Identifier=Multiple
Geom File=g01
Flow File=f01
Subcritical Flow
K Sum by GR= 0
Std Step Tol= 0.01
Critical Tol= 0.01
Num of Std Step Trials= 20
Max Error Tol= 0.3
Flow Tol Ratio= 0.001
Split Flow NTrial= 30
Split Flow Tol= 0.02
Split Flow Ratio= 0.02
Log Output Level= 0
Friction Slope Method= 1
Unsteady Friction Slope Method= 2
Unsteady Bridges Friction Slope Method= 1
Parabolic Critical Depth
Global Vel Dist=  1 , 1 , 1
Global Log Level= 0
CheckData=True
Encroach Param= -1, 0, 0, 0
BEGIN DESCRIPTION:
Multiple Run
END DESCRIPTION:

--- Clear Creek T 3.f01 (steady flow) ---

Flow Title=Multiple
Number of Profiles=7
Profile Names=10-year,25-year,50-year,1pct_min,100-year,1pct_plu,500-year
River Rch & RM= Clear Creek T 3,Reach-1,5742
     250     319     373     217     433     864     584
Boundary for River Rch & Prof#=Clear Creek T 3,Reach-1,1
Up Type=0
Dn Type=3
Dn Slope=0.005
Boundary for River Rch & Prof#=Clear Creek T 3,Reach-1,2
Up Type=0
Dn Type=3
Dn Slope=0.005
Boundary for River Rch & Prof#=Clear Creek T 3,Reach-1,3
Up Type=0
Dn Type=3
Dn Slope=0.005
Boundary for River Rch & Prof#=Clear Creek T 3,Reach-1,4
Up Type=0
Dn Type=3
Dn Slope=0.005
Boundary for River Rch & Prof#=Clear Creek T 3,Reach-1,5
Up Type=0
Dn Type=3
Dn Slope=0.005
Boundary for River Rch & Prof#=Clear Creek T 3,Reach-1,6
Up Type=0
Dn Type=3
Dn Slope=0.005
Boundary for River Rch & Prof#=Clear Creek T 3,Reach-1,7
Up Type=0
Dn Type=3
Dn Slope=0.005

--- Clear Creek T 3.g01 (geometry) ---

Geom Title=Existing Conditions

River Reach=Clear Creek T 3,Reach-1
Reach XY= 30
      2752226.00      6796311.00      2752175.57      6796342.44
      2752224.78      6796421.48      2752276.29      6796833.84
      2752126.67      6797174.91      2752126.18      6797641.02
      2752167.96      6797714.32      2752099.85      6797838.14
      2751912.79      6797924.62      2751714.17      6798159.38
      2751441.15      6798160.33      2751375.70      6798118.26
      2751314.17      6798209.34      2751089.86      6798210.17
      2751025.90      6798168.34      2750926.10      6798253.66
      2750662.62      6798197.63      2750583.31      6798111.11
      2750626.57      6797990.95      2750576.26      6797875.09
      2750624.36      6797767.03      2750535.32      6797667.66
      2750475.90      6797495.64      2750574.24      6797317.12
      2750320.37      6797012.73      2750162.43      6797074.47
      2750028.30      6797255.89      2749922.36      6797218.76
      2749867.66      6797307.79      2749526.00      6797411.00

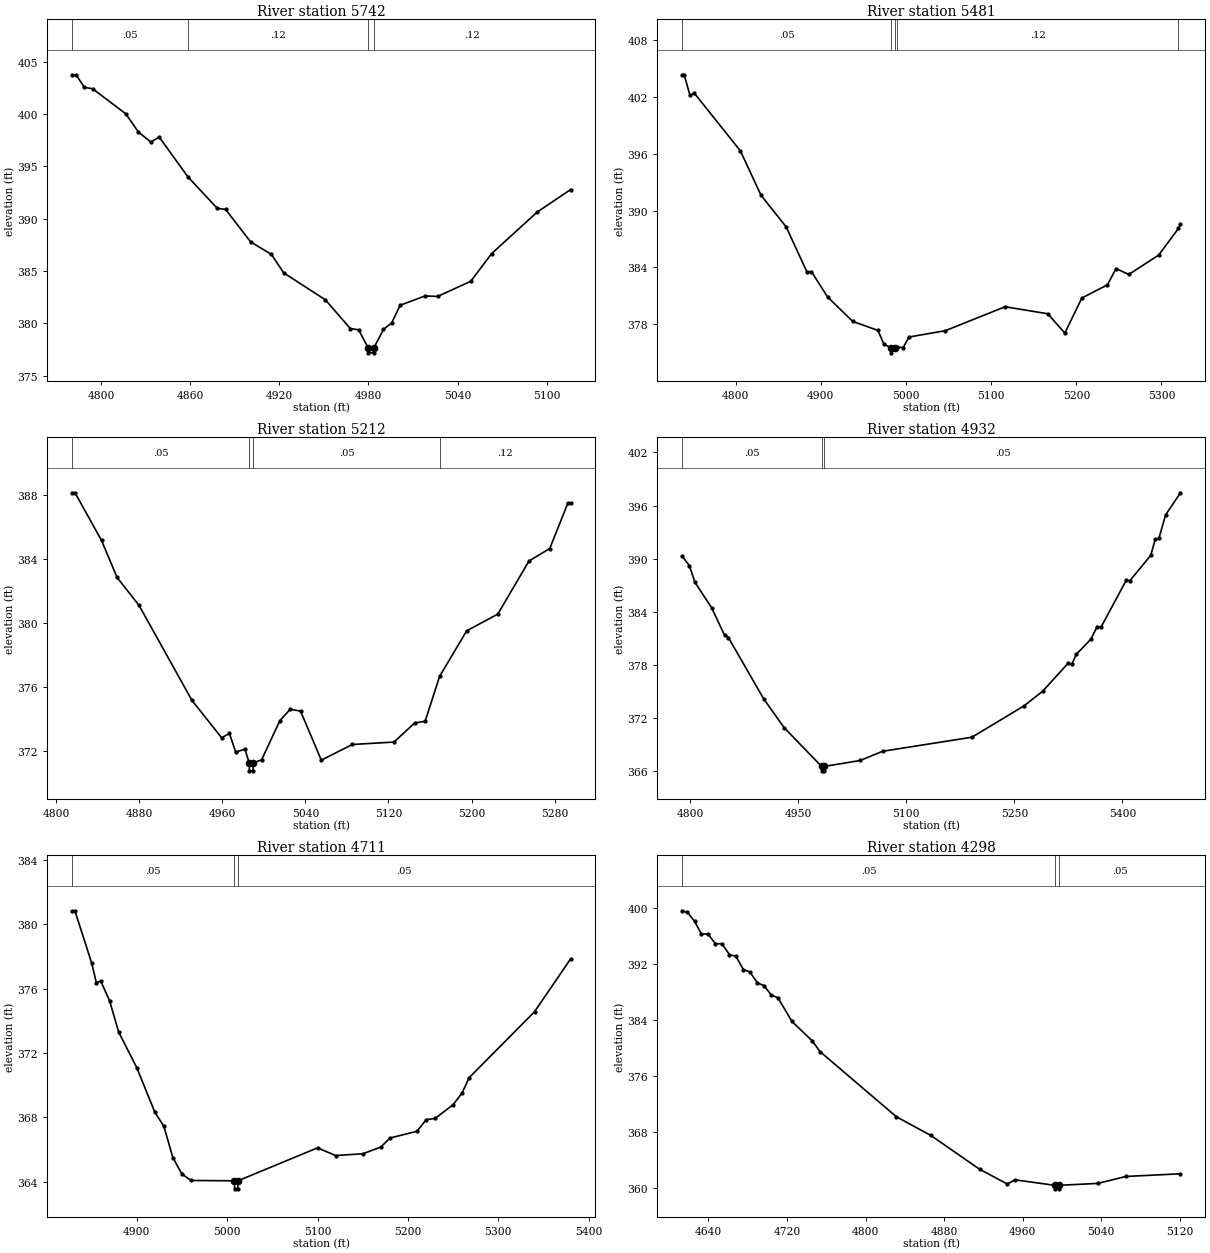
Type RM Length L Ch R = 1,5742,261,261,261
BEGIN DESCRIPTION:
Clear Creek T 3 5.0
END DESCRIPTION:
XS GIS Cut Line= 3
      2752026.00      6796511.00      2752226.00      6796411.00
      2752325.99      6796361.00
#Sta/Elev= 30
  4780.5  403.76  4783.3  403.76  4788.9  402.56  4794.5  402.42  4816.8  400.02
  4825.2  398.29  4833.6  397.33  4839.2  397.81  4858.6  393.99  4878.3  390.99
  4883.9  390.89  4900.7  387.79  4914.7  386.59  4923.0  384.82  4951.0  382.25
  4967.8  379.50  4973.4  379.38  4979.7  377.68  4980.0  377.18  4983.5  377.18
  4983.7  377.68  4990.1  379.42  4995.7  380.06  5001.3  381.73  5018.1  382.62
  5026.5  382.57  5048.8  384.02  5062.8  386.66  5093.5  390.64  5115.9  392.78
#Mann=4,-1,0
  4780.5    0.05       0  4858.6    0.12       0  4979.7    0.07       0
  4983.7    0.12       0
Bank Sta=4979.7,4983.7
Exp/Cntr=0.3,0.1

Type RM Length L Ch R = 1,5481,269,269,269
BEGIN DESCRIPTION:
Clear Creek T 3 4.0
END DESCRIPTION:
XS GIS Cut Line= 3
      2752025.99      6796561.00      2752276.00      6796661.00
      2752591.59      6796642.43
#Sta/Elev= 30
  4736.9  404.35  4739.6  404.35  4746.3  402.20  4751.7  402.38  4805.6  396.31
  4829.8  391.62  4859.4  388.27  4883.7  383.52  4889.0  383.56  4907.9  380.88
  4937.5  378.29  4967.1  377.34  4973.9  375.92  4982.6  375.47  4982.9  374.97
  4986.6  375.47  4989.0  375.58  4996.7  375.52  5003.5  376.64  5046.2  377.31
  5116.4  379.84  5166.4  379.10  5186.5  377.06  5206.5  380.76  5236.6  382.16
  5246.6  383.88  5261.6  383.25  5296.7  385.30  5319.9  388.11  5322.3  388.61
#Mann=5,-1,0
  4736.9    0.05       0  4982.6    0.07       0  4986.6    0.05       0
  4989.0    0.12       0  5319.9     0.1       0
Bank Sta=4982.6,4986.6
Exp/Cntr=0.3,0.1

Type RM Length L Ch R = 1,5212,280,280,280
BEGIN DESCRIPTION:
Clear Creek T 3 3.0
END DESCRIPTION:
XS GIS Cut Line= 3
      2752076.03      6796811.02      2752226.00      6796911.00
      2752525.96      6796911.00
#Sta/Elev= 30
  4815.1  388.16  4818.1  388.16  4843.6  385.18  4858.6  382.86  4879.7  381.12
  4930.7  375.17  4959.3  372.83  4966.8  373.10  4972.8  371.94  4981.8  372.11
  4985.8  371.26  4986.1  370.76  4989.6  370.76  4989.8  371.26  4997.8  371.45
  5015.3  373.89  5025.3  374.61  5035.3  374.50  5055.3  371.43  5085.3  372.41
  5125.3  372.56  5145.3  373.76  5155.3  373.86  5169.2  376.67  5195.3  379.52
  5225.3  380.57  5255.3  383.89  5275.3  384.67  5292.8  387.52  5295.3  387.52
#Mann=4,-1,0
  4815.1    0.05       0  4985.8    0.05       0  4989.8    0.05       0
  5169.2    0.12       0
Bank Sta=4985.8,4989.8
Exp/Cntr=0.3,0.1

Type RM Length L Ch R = 1,4932,221,221,221
BEGIN DESCRIPTION:
Clear Creek T 3 2.0
END DESCRIPTION:
XS GIS Cut Line= 3
      2751925.95      6797110.99      2752126.00      6797161.00
      2752595.90      6797037.34
#Sta/Elev= 30
  4788.4  390.32  4798.8  389.21  4806.5  387.33  4829.7  384.45  4847.7  381.33
  4852.9  381.09  4901.8  374.18  4930.2  370.92  4982.3  366.53  4982.5  366.03
  4986.0  366.03  4986.3  366.53  5036.0  367.20  5067.0  368.24  5191.1  369.83
  5263.5  373.38  5289.3  375.03  5324.5  378.18  5329.6  378.05  5335.8  379.18
  5356.5  380.94  5364.8  382.33  5370.0  382.23  5405.1  387.54  5410.3  387.51
  5439.2  390.37  5445.4  392.17  5450.6  392.31  5459.9  394.95  5480.5  397.44
#Mann=3,-1,0
  4788.4    0.05       0  4982.3    0.05       0  4986.3    0.05       0
Bank Sta=4982.3,4986.3
Exp/Cntr=0.3,0.1

Type RM Length L Ch R = 1,4711,413,413,413
BEGIN DESCRIPTION:
Mapping XS 7457619c
END DESCRIPTION:
XS GIS Cut Line= 2
      2751954.34      6797375.34      2752505.68      6797388.65
#Sta/Elev= 30
  4828.3  380.85  4831.6  380.85  4850.0  377.63  4855.3  376.39  4860.3  376.47
  4870.0  375.25  4880.0  373.31  4900.0  371.10  4920.0  368.33  4930.0  367.45
  4940.0  365.50  4950.0  364.48  4960.0  364.08  5008.0  364.06  5008.3  363.56
  5011.8  363.56  5012.0  364.06  5100.0  366.11  5120.0  365.63  5150.1  365.74
  5170.1  366.16  5180.1  366.72  5210.1  367.14  5220.1  367.86  5230.1  367.94
  5250.1  368.80  5260.1  369.54  5267.5  370.46  5340.1  374.58  5379.8  377.85
#Mann=3,-1,0
  4828.3    0.05       0  5008.0    0.05       0  5012.0    0.05       0
Bank Sta=5008,5012
Exp/Cntr=0.3,0.1

Type RM Length L Ch R = 1,4298,374,374,374
BEGIN DESCRIPTION:
Mapping XS 7381c49a
END DESCRIPTION:
XS GIS Cut Line= 2
      2751836.24      6797512.74      2752221.00      6797844.14
#Sta/Elev= 30
  4612.9  399.65  4618.5  399.43  4625.8  398.15  4632.8  396.33  4639.4  396.33
  4647.1  394.94  4653.7  394.93  4661.3  393.39  4667.9  393.14  4675.6  391.23
  4682.2  390.90  4689.8  389.35  4696.4  388.96  4704.1  387.59  4710.7  387.22
  4725.0  383.83  4745.8  381.03  4753.5  379.53  4831.4  370.20  4866.5  367.53
  4916.1  362.70  4944.4  360.59  4952.1  361.19  4992.8  360.40  4993.1  359.90
  4996.6  359.90  4996.8  360.40  5036.6  360.68  5065.1  361.67  5120.7  362.05
#Mann=3,-1,0
  4612.9    0.05       0  4992.8    0.05       0  4996.8    0.05       0
Bank Sta=4992.8,4996.8
Exp/Cntr=0.3,0.1

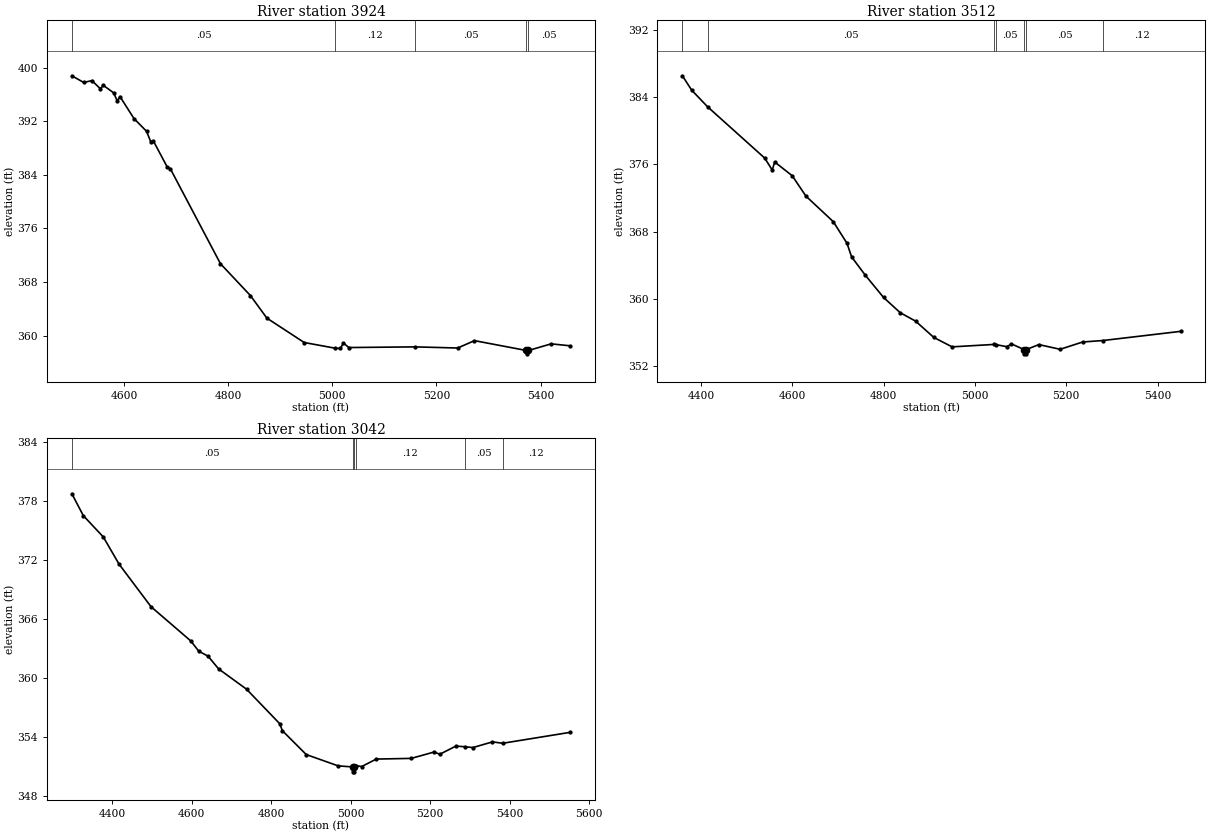
Type RM Length L Ch R = 1,3924,412,412,412
BEGIN DESCRIPTION:
Mapping XS 71b1bc3a
END DESCRIPTION:
XS GIS Cut Line= 2
      2751704.07      6797504.39      2751995.42      6798415.43
#Sta/Elev= 30
  4500.1  398.78  4522.8  397.78  4538.5  398.06  4555.0  396.83  4560.2  397.37
  4580.5  396.22  4587.1  395.02  4592.4  395.68  4619.3  392.40  4643.5  390.49
  4651.5  388.94  4656.7  389.03  4683.6  385.10  4688.9  384.94  4785.4  370.73
  4843.0  365.97  4874.5  362.61  4946.2  358.97  5005.8  358.12  5015.8  358.08
  5021.5  358.89  5032.0  358.22  5158.7  358.32  5240.9  358.15  5273.1  359.25
  5372.8  357.78  5373.1  357.28  5376.8  357.78  5420.4  358.77  5456.6  358.48
#Mann=5,-1,0
  4500.1    0.05       0  5005.8    0.12       0  5158.7    0.05       0
  5372.8    0.05       0  5376.8    0.05       0
Bank Sta=5372.8,5376.8
Exp/Cntr=0.3,0.1

Type RM Length L Ch R = 1,3512,470,470,470
BEGIN DESCRIPTION:
Mapping XS 2e3346c5
END DESCRIPTION:
XS GIS Cut Line= 3
      2751513.91      6797520.58      2751542.89      6798331.76
      2751741.13      6798528.78
#Sta/Elev= 30
  4359.1  386.54  4379.5  384.83  4414.4  382.85  4539.6  376.75  4556.1  375.32
  4561.2  376.30  4599.7  374.66  4629.7  372.24  4689.7  369.20  4719.8  366.62
  4729.8  365.01  4759.8  362.84  4799.8  360.19  4836.3  358.38  4869.9  357.38
  4909.9  355.44  4949.9  354.32  5042.5  354.61  5046.3  354.58  5070.0  354.34
  5080.0  354.67  5108.0  353.99  5108.3  353.49  5111.8  353.49  5112.0  353.99
  5140.0  354.59  5186.6  354.03  5236.1  354.90  5279.9  355.07  5450.3  356.16
#Mann=7,-1,0
  4359.1    0.12       0  4414.4    0.05       0  5042.5    0.12       0
  5046.3    0.05       0  5108.0    0.05       0  5112.0    0.05       0
  5279.9    0.12       0
Bank Sta=5108,5112
Exp/Cntr=0.3,0.1

Type RM Length L Ch R = 1,3042,0,0,0
BEGIN DESCRIPTION:
Clear Creek T 3 1.0
END DESCRIPTION:
XS GIS Cut Line= 4
      2751169.88      6797512.25      2751131.59      6798202.69
      2751255.27      6798397.90      2751564.98      6798514.14
#Sta/Elev= 30
  4298.3  378.75  4327.1  376.52  4377.2  374.36  4417.2  371.57  4497.4  367.25
  4597.5  363.76  4617.5  362.72  4640.9  362.21  4667.6  360.91  4737.7  358.85
  4821.3  355.33  4827.9  354.62  4888.0  352.19  4968.1  351.04  5004.5  350.93
  5004.7  350.43  5008.2  350.43  5008.5  350.93  5013.0  351.06  5027.6  350.97
  5064.1  351.73  5152.2  351.80  5209.9  352.45  5224.0  352.22  5264.4  353.05
  5286.7  352.99  5307.1  352.90  5356.5  353.48  5382.3  353.34  5551.7  354.45
#Mann=6,-1,0
  4298.3    0.05       0  5004.5    0.05       0  5008.5    0.05       0
  5013.0    0.12       0  5286.7    0.05       0  5382.3    0.12       0
Bank Sta=5004.5,5008.5
Exp/Cntr=0.3,0.1

Chan Stop Cuts=-1