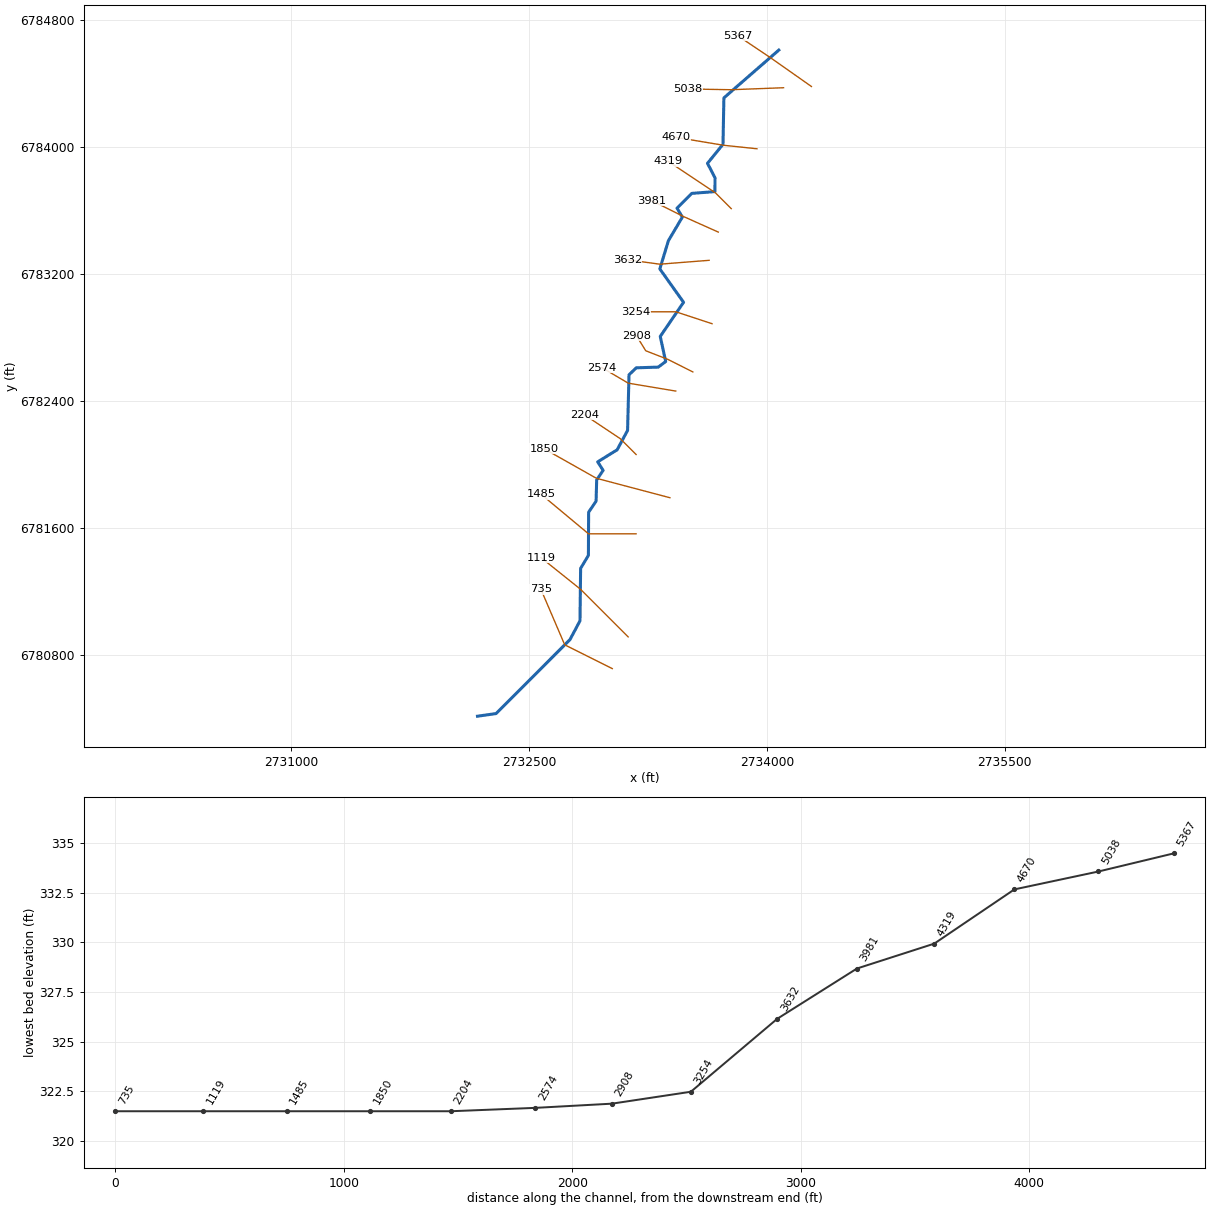
--- Clear Creek T 30.prj (project) ---

Proj Title=Clear Creek T 30 Base Level Engineering
Current Plan=p01
Default Exp/Contr=0.3,0.1
English Units
Geom File=g01
Flow File=f01
Plan File=p01
BEGIN DESCRIPTION:
Clear Creek T 30
END DESCRIPTION:

--- Clear Creek T 30.p01 (plan) ---

Plan Title=Multiple Run
Short Identifier=Multiple
Geom File=g01
Flow File=f01
Subcritical Flow
K Sum by GR= 0
Std Step Tol= 0.01
Critical Tol= 0.01
Num of Std Step Trials= 20
Max Error Tol= 0.3
Flow Tol Ratio= 0.001
Split Flow NTrial= 30
Split Flow Tol= 0.02
Split Flow Ratio= 0.02
Log Output Level= 0
Friction Slope Method= 1
Unsteady Friction Slope Method= 2
Unsteady Bridges Friction Slope Method= 1
Parabolic Critical Depth
Global Vel Dist=  1 , 1 , 1
Global Log Level= 0
CheckData=True
Encroach Param= -1, 0, 0, 0
BEGIN DESCRIPTION:
Multiple Run
END DESCRIPTION:

--- Clear Creek T 30.f01 (steady flow) ---

Flow Title=Multiple
Number of Profiles=7
Profile Names=10-year,25-year,50-year,1pct_min,100-year,1pct_plu,500-year
River Rch & RM= Clear Creek T 30,Reach-1,5367
     629     842    1014     606    1208    2411    1714
Boundary for River Rch & Prof#=Clear Creek T 30,Reach-1,1
Up Type=0
Dn Type=3
Dn Slope=0.005
Boundary for River Rch & Prof#=Clear Creek T 30,Reach-1,2
Up Type=0
Dn Type=3
Dn Slope=0.005
Boundary for River Rch & Prof#=Clear Creek T 30,Reach-1,3
Up Type=0
Dn Type=3
Dn Slope=0.005
Boundary for River Rch & Prof#=Clear Creek T 30,Reach-1,4
Up Type=0
Dn Type=3
Dn Slope=0.005
Boundary for River Rch & Prof#=Clear Creek T 30,Reach-1,5
Up Type=0
Dn Type=3
Dn Slope=0.005
Boundary for River Rch & Prof#=Clear Creek T 30,Reach-1,6
Up Type=0
Dn Type=3
Dn Slope=0.005
Boundary for River Rch & Prof#=Clear Creek T 30,Reach-1,7
Up Type=0
Dn Type=3
Dn Slope=0.005

--- Clear Creek T 30.g01 (geometry) ---

Geom Title=Existing Conditions

River Reach=Clear Creek T 30,Reach-1
Reach XY= 30
      2734076.00      6784611.00      2733729.54      6784309.54
      2733723.93      6784016.86      2733626.10      6783896.96
      2733673.73      6783805.35      2733673.02      6783718.66
      2733527.45      6783707.45      2733433.99      6783614.35
      2733467.75      6783557.77      2733379.83      6783409.42
      2733325.60      6783231.13      2733475.29      6783020.80
      2733328.26      6782805.44      2733362.65      6782647.19
      2733315.89      6782612.06      2733177.22      6782607.56
      2733131.34      6782563.74      2733122.25      6782212.55
      2733056.37      6782090.53      2732933.89      6782014.58
      2732968.19      6781961.11      2732927.39      6781900.56
      2732923.73      6781766.94      2732876.68      6781697.08
      2732875.32      6781424.92      2732826.21      6781342.73
      2732822.25      6781012.55      2732759.36      6780894.32
      2732292.76      6780427.43      2732176.00      6780411.00

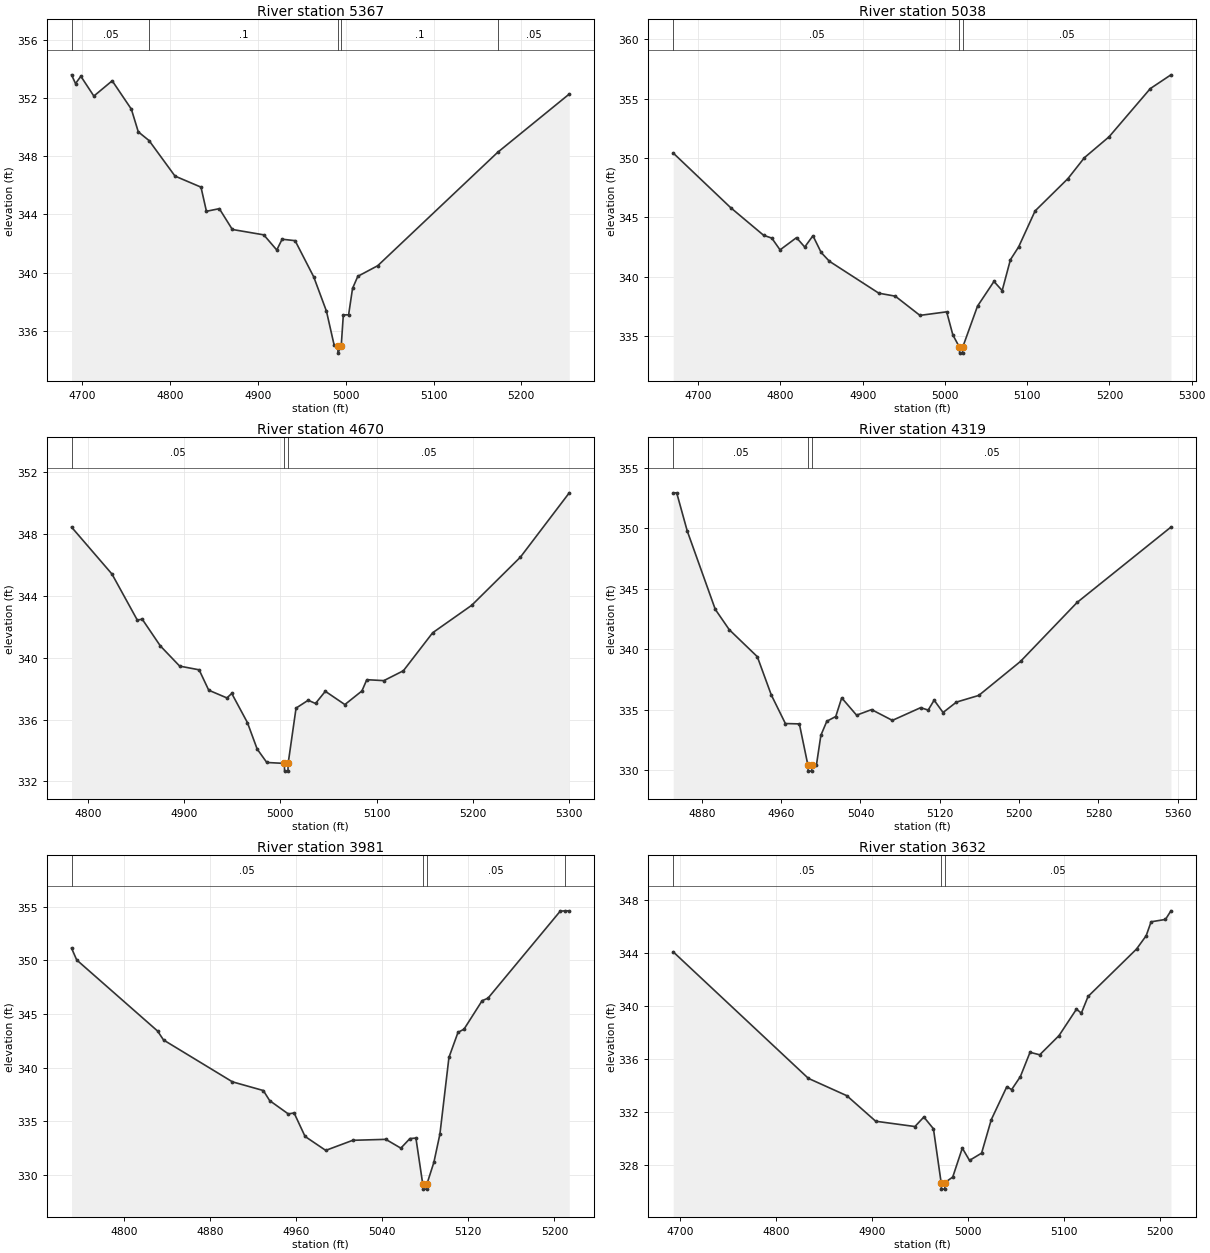
Type RM Length L Ch R = 1,5367,329,329,329
BEGIN DESCRIPTION:
Clear Creek T 30 14.0
END DESCRIPTION:
XS GIS Cut Line= 3
      2734281.68      6784381.29      2734026.00      6784561.00
      2733814.93      6784702.81
#Sta/Elev= 30
  4687.8  353.60  4692.3  353.00  4698.4  353.50  4713.2  352.14  4734.1  353.19
  4755.9  351.24  4763.8  349.68  4776.1  349.08  4805.6  346.64  4835.2  345.88
  4841.4  344.22  4856.1  344.40  4870.9  342.97  4906.7  342.60  4921.5  341.56
  4927.6  342.30  4942.4  342.20  4963.6  339.71  4978.1  337.35  4986.8  335.03
  4990.9  334.97  4991.2  334.47  4994.9  334.97  4997.3  337.10  5003.3  337.10
  5007.8  338.92  5013.8  339.75  5036.5  340.48  5173.0  348.27  5254.6  352.28
#Mann=5,-1,0
  4687.8    0.05       0  4776.1     0.1       0  4990.9    0.07       0
  4994.9     0.1       0  5173.0    0.05       0
Bank Sta=4990.9,4994.9
Exp/Cntr=0.3,0.1

Type RM Length L Ch R = 1,5038,368,368,368
BEGIN DESCRIPTION:
Clear Creek T 30 13.0
END DESCRIPTION:
XS GIS Cut Line= 3
      2734105.78      6784373.56      2733776.00      6784361.00
      2733500.86      6784365.79
#Sta/Elev= 30
  4669.6  350.42  4739.4  345.82  4779.5  343.49  4789.5  343.25  4799.5  342.26
  4819.5  343.29  4829.5  342.50  4839.5  343.45  4849.5  342.04  4859.5  341.30
  4919.6  338.61  4939.6  338.36  4969.6  336.74  5002.1  337.04  5009.6  335.10
  5017.6  334.06  5017.9  333.56  5021.4  333.56  5021.6  334.06  5039.6  337.52
  5059.6  339.60  5069.6  338.83  5079.6  341.43  5089.6  342.51  5109.6  345.54
  5149.6  348.27  5169.6  350.03  5199.6  351.79  5249.7  355.85  5274.8  357.01
#Mann=3,-1,0
  4669.6    0.05       0  5017.6    0.03       0  5021.6    0.05       0
Bank Sta=5017.6,5021.6
Exp/Cntr=0.3,0.1

Type RM Length L Ch R = 1,4670,351,351,351
BEGIN DESCRIPTION:
Clear Creek T 30 12.0
END DESCRIPTION:
XS GIS Cut Line= 3
      2733937.73      6783988.72      2733726.00      6784011.00
      2733426.04      6784060.99
#Sta/Elev= 30
  4783.1  348.46  4825.1  345.42  4851.4  342.44  4856.5  342.50  4875.3  340.77
  4895.4  339.46  4915.6  339.22  4925.6  337.90  4944.5  337.40  4949.5  337.69
  4965.8  335.80  4975.9  334.09  4985.9  333.22  5004.1  333.16  5004.4  332.66
  5007.9  332.66  5008.1  333.16  5016.3  336.74  5028.9  337.25  5036.5  337.04
  5046.7  337.83  5067.0  336.97  5084.7  337.85  5089.8  338.58  5107.5  338.52
  5127.8  339.16  5158.2  341.62  5198.8  343.40  5249.4  346.52  5300.1  350.68
#Mann=3,-1,0
  4783.1    0.05       0  5004.1    0.04       0  5008.1    0.05       0
Bank Sta=5004.1,5008.1
Exp/Cntr=0.3,0.1

Type RM Length L Ch R = 1,4319,338,338,338
BEGIN DESCRIPTION:
Clear Creek T 30 11.0
END DESCRIPTION:
XS GIS Cut Line= 3
      2733775.97      6783611.03      2733676.00      6783711.00
      2733376.03      6783910.98
#Sta/Elev= 30
  4851.2  352.91  4854.7  352.91  4865.3  349.77  4893.6  343.29  4907.7  341.61
  4936.0  339.38  4950.1  336.22  4964.3  333.86  4978.4  333.83  4987.0  330.43
  4987.3  329.93  4990.8  329.93  4991.0  330.43  4995.6  330.43  5000.1  332.89
  5006.1  334.05  5015.1  334.44  5021.1  335.98  5036.1  334.55  5051.2  335.01
  5072.2  334.12  5100.7  335.17  5108.3  334.97  5114.3  335.79  5123.3  334.77
  5136.8  335.63  5159.3  336.18  5201.4  338.99  5258.5  343.86  5353.1  350.08
#Mann=3,-1,0
  4851.2    0.05       0  4987.0    0.04       0  4991.0    0.05       0
Bank Sta=4987,4991
Exp/Cntr=0.3,0.1

Type RM Length L Ch R = 1,3981,349,349,349
BEGIN DESCRIPTION:
Clear Creek T 30 10.0
END DESCRIPTION:
XS GIS Cut Line= 3
      2733694.07      6783463.43      2733476.00      6783561.00
      2733276.01      6783660.99
#Sta/Elev= 30
  4751.3  351.14  4756.1  350.04  4831.2  343.42  4836.8  342.58  4900.8  338.68
  4929.5  337.87  4935.4  336.93  4952.7  335.69  4958.1  335.78  4968.3  333.59
  4987.5  332.29  5012.6  333.23  5043.3  333.32  5057.3  332.50  5065.7  333.39
  5071.3  333.44  5077.6  329.18  5077.9  328.68  5081.4  328.68  5081.6  329.18
  5088.0  331.18  5093.6  333.81  5102.0  340.96  5110.4  343.29  5116.0  343.59
  5132.8  346.24  5138.3  346.48  5205.4  354.59  5210.2  354.62  5213.8  354.62
#Mann=4,-1,0
  4751.3    0.05       0  5077.6    0.04       0  5081.6    0.05       0
  5210.2    0.12       0
Bank Sta=5077.6,5081.6
Exp/Cntr=0.3,0.1

Type RM Length L Ch R = 1,3632,378,378,378
BEGIN DESCRIPTION:
Clear Creek T 30 9.0
END DESCRIPTION:
XS GIS Cut Line= 3
      2733636.47      6783285.43      2733326.00      6783261.00
      2733120.39      6783288.77
#Sta/Elev= 30
  4693.0  344.08  4833.9  334.52  4874.0  333.21  4904.1  331.28  4945.0  330.88
  4954.3  331.60  4964.3  330.71  4972.3  326.65  4972.6  326.15  4976.1  326.15
  4976.3  326.65  4984.4  327.06  4994.4  329.25  5001.9  328.32  5014.5  328.87
  5024.6  331.40  5040.8  333.89  5045.8  333.67  5054.9  334.65  5065.0  336.49
  5075.1  336.30  5095.2  337.75  5113.4  339.75  5118.5  339.45  5125.5  340.71
  5176.0  344.29  5186.1  345.30  5191.2  346.35  5206.2  346.53  5211.9  347.18
#Mann=3,-1,0
  4693.0    0.05       0  4972.3    0.04       0  4976.3    0.05       0
Bank Sta=4972.3,4976.3
Exp/Cntr=0.3,0.1

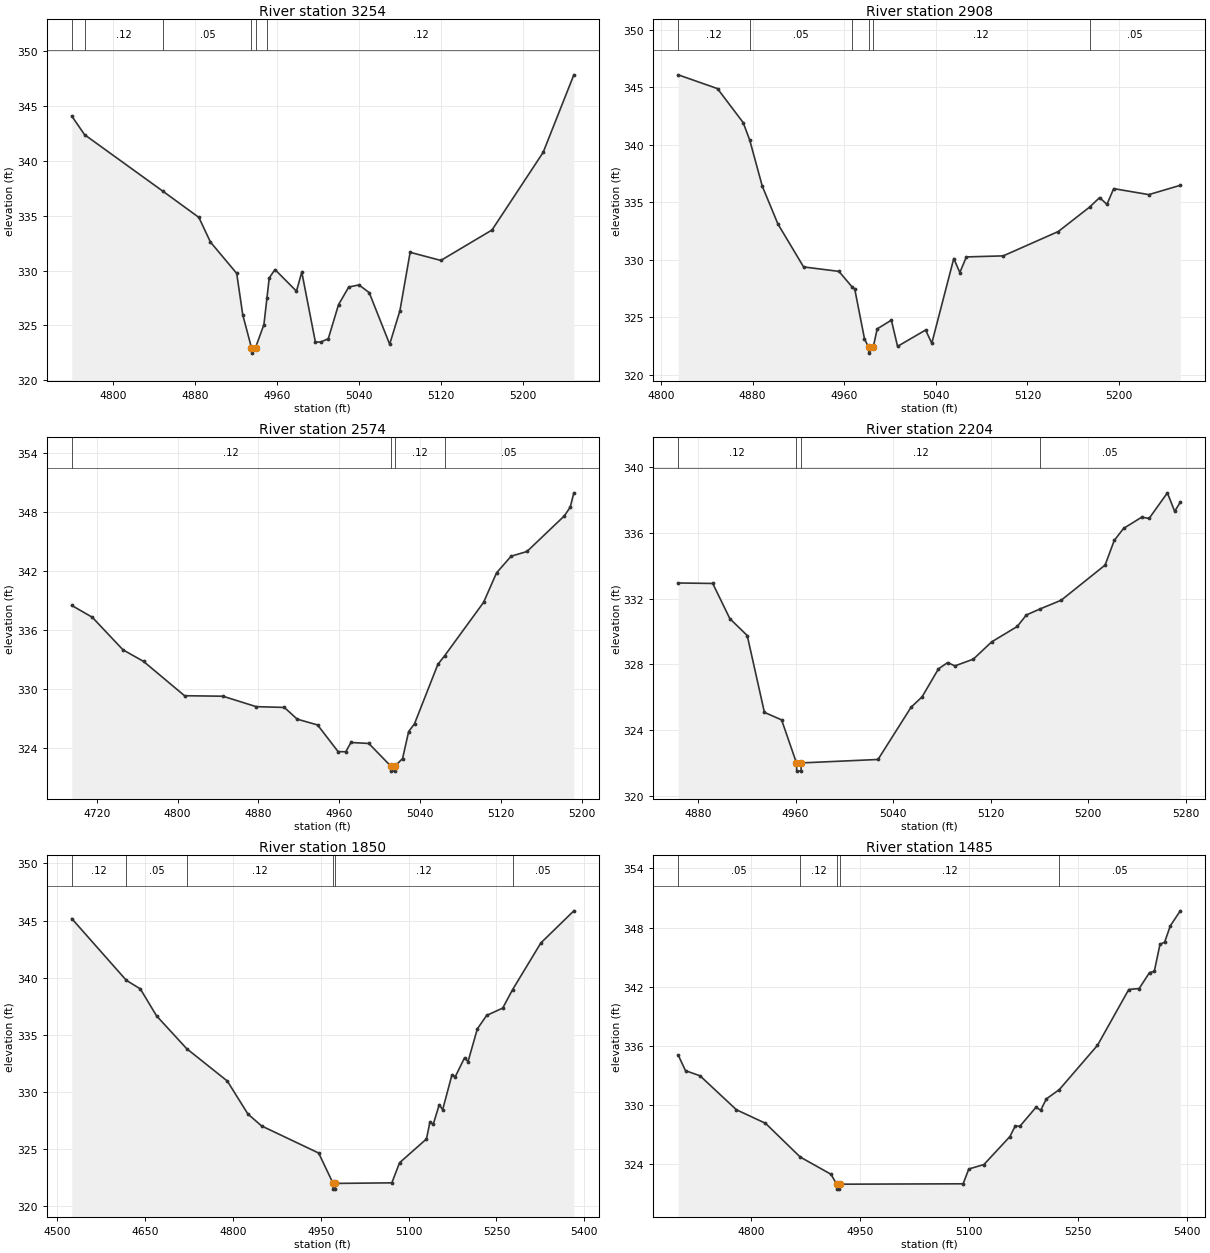
Type RM Length L Ch R = 1,3254,346,346,346
BEGIN DESCRIPTION:
Clear Creek T 30 8.0
END DESCRIPTION:
XS GIS Cut Line= 3
      2733654.70      6782885.82      2733426.00      6782961.00
      2733176.04      6782961.00
#Sta/Elev= 30
  4759.3  344.07  4771.8  342.37  4848.7  337.20  4883.5  334.84  4894.8  332.60
  4920.5  329.74  4926.4  325.97  4934.9  322.98  4935.1  322.48  4938.9  322.98
  4947.1  325.08  4950.1  327.53  4952.3  329.33  4957.9  330.09  4978.9  328.12
  4984.1  329.86  4997.4  323.49  5002.5  323.49  5010.0  323.79  5020.0  326.89
  5030.0  328.50  5040.0  328.69  5050.0  327.99  5070.0  323.29  5080.0  326.34
  5090.0  331.66  5120.0  330.92  5170.0  333.69  5220.0  340.76  5250.0  347.82
#Mann=6,-1,0
  4759.3    0.05       0  4771.8    0.12       0  4848.7    0.05       0
  4934.9    0.07       0  4938.9    0.05       0  4950.1    0.12       0
Bank Sta=4934.9,4938.9
Exp/Cntr=0.3,0.1

Type RM Length L Ch R = 1,2908,334,334,334
BEGIN DESCRIPTION:
Clear Creek T 30 7.0
END DESCRIPTION:
XS GIS Cut Line= 4
      2733533.81      6782581.64      2733376.00      6782661.00
      2733237.08      6782714.92      2733177.40      6782810.81
#Sta/Elev= 30
  4815.0  346.09  4849.3  344.89  4871.7  341.94  4877.4  340.43  4888.4  336.41
  4902.1  333.11  4924.5  329.38  4955.4  328.99  4966.7  327.66  4969.2  327.45
  4977.7  323.13  4981.3  322.38  4981.5  321.88  4985.3  322.38  4988.8  323.99
  5001.2  324.75  5006.6  322.47  5031.1  323.89  5036.5  322.74  5055.7  330.11
  5061.0  328.89  5066.7  330.25  5098.9  330.34  5147.0  332.46  5174.3  334.58
  5183.1  335.41  5189.5  334.82  5195.4  336.19  5226.1  335.67  5253.6  336.48
#Mann=6,-1,0
  4815.0    0.12       0  4877.4    0.05       0  4966.7    0.12       0
  4981.3    0.07       0  4985.3    0.12       0  5174.3    0.05       0
Bank Sta=4981.3,4985.3
Exp/Cntr=0.3,0.1

Type RM Length L Ch R = 1,2574,370,370,370
BEGIN DESCRIPTION:
Clear Creek T 30 6.0
END DESCRIPTION:
XS GIS Cut Line= 3
      2733426.04      6782460.99      2733126.00      6782511.00
      2732960.12      6782609.12
#Sta/Elev= 30
  4695.3  338.50  4715.6  337.30  4746.0  333.99  4766.3  332.82  4806.9  329.33
  4844.9  329.28  4877.8  328.22  4905.7  328.14  4918.4  326.95  4938.6  326.36
  4958.9  323.65  4966.5  323.64  4971.6  324.58  4989.3  324.48  5011.1  322.17
  5011.4  321.67  5014.9  321.67  5015.1  322.17  5022.7  322.95  5028.7  325.69
  5034.5  326.48  5057.6  332.51  5064.4  333.40  5102.9  338.82  5115.7  341.81
  5130.1  343.50  5145.8  343.98  5182.8  347.60  5188.6  348.48  5192.2  349.94
#Mann=4,-1,0
  4695.3    0.12       0  5011.1    0.07       0  5015.1    0.12       0
  5064.4    0.05       0
Bank Sta=5011.1,5015.1
Exp/Cntr=0.3,0.1

Type RM Length L Ch R = 1,2204,354,354,354
BEGIN DESCRIPTION:
Clear Creek T 30 5.0
END DESCRIPTION:
XS GIS Cut Line= 3
      2733175.99      6782061.01      2733076.00      6782161.00
      2732850.94      6782311.04
#Sta/Elev= 30
  4863.7  332.96  4892.0  332.93  4906.1  330.78  4920.3  329.76  4934.4  325.08
  4948.5  324.62  4960.7  322.00  4960.9  321.50  4964.4  321.50  4964.7  322.00
  5027.6  322.21  5054.7  325.39  5063.7  326.02  5077.2  327.73  5084.7  328.11
  5090.7  327.91  5105.8  328.32  5120.8  329.37  5141.8  330.31  5149.3  331.01
  5160.6  331.38  5177.9  331.91  5213.9  334.05  5221.4  335.55  5229.0  336.28
  5244.0  336.97  5250.0  336.89  5265.0  338.45  5271.0  337.32  5275.6  337.89
#Mann=4,-1,0
  4863.7    0.12       0  4960.7    0.07       0  4964.7    0.12       0
  5160.6    0.05       0
Bank Sta=4960.7,4964.7
Exp/Cntr=0.3,0.1

Type RM Length L Ch R = 1,1850,365,365,365
BEGIN DESCRIPTION:
Clear Creek T 30 4.0
END DESCRIPTION:
XS GIS Cut Line= 3
      2733389.12      6781788.54      2732926.00      6781911.00
      2732596.97      6782096.60
#Sta/Elev= 30
  4525.3  345.17  4618.4  339.77  4642.3  339.02  4670.0  336.66  4721.4  333.79
  4790.7  330.96  4825.8  328.08  4849.2  327.03  4946.6  324.66  4971.3  322.00
  4971.6  321.50  4975.1  321.50  4975.3  322.00  5071.5  322.05  5084.7  323.81
  5130.6  325.89  5136.5  327.37  5142.2  327.18  5152.4  328.89  5158.2  328.45
  5174.1  331.50  5179.8  331.34  5195.7  333.00  5201.5  332.65  5217.4  335.52
  5233.3  336.70  5260.7  337.34  5277.5  338.95  5325.8  343.04  5382.1  345.85
#Mann=6,-1,0
  4525.3    0.12       0  4618.4    0.05       0  4721.4    0.12       0
  4971.3    0.07       0  4975.3    0.12       0  5277.5    0.05       0
Bank Sta=4971.3,4975.3
Exp/Cntr=0.3,0.1

Type RM Length L Ch R = 1,1485,366,366,366
BEGIN DESCRIPTION:
Clear Creek T 30 3.0
END DESCRIPTION:
XS GIS Cut Line= 3
      2733175.99      6781561.00      2732876.00      6781561.00
      2732576.01      6781811.00
#Sta/Elev= 30
  4700.0  335.07  4710.0  333.50  4730.0  332.98  4780.0  329.54  4820.0  328.17
  4867.8  324.75  4910.0  323.01  4918.0  322.00  4918.2  321.50  4921.7  321.50
  4922.0  322.00  5091.8  322.04  5099.6  323.54  5120.4  323.99  5156.2  326.83
  5163.4  327.89  5169.9  327.87  5192.0  329.79  5198.5  329.50  5206.3  330.64
  5224.2  331.59  5276.6  336.07  5319.6  341.72  5333.9  341.82  5348.2  343.44
  5354.7  343.55  5362.5  346.28  5369.0  346.53  5376.8  348.18  5390.5  349.69
#Mann=5,-1,0
  4700.0    0.05       0  4867.8    0.12       0  4918.0    0.07       0
  4922.0    0.12       0  5224.2    0.05       0
Bank Sta=4918,4922
Exp/Cntr=0.3,0.1

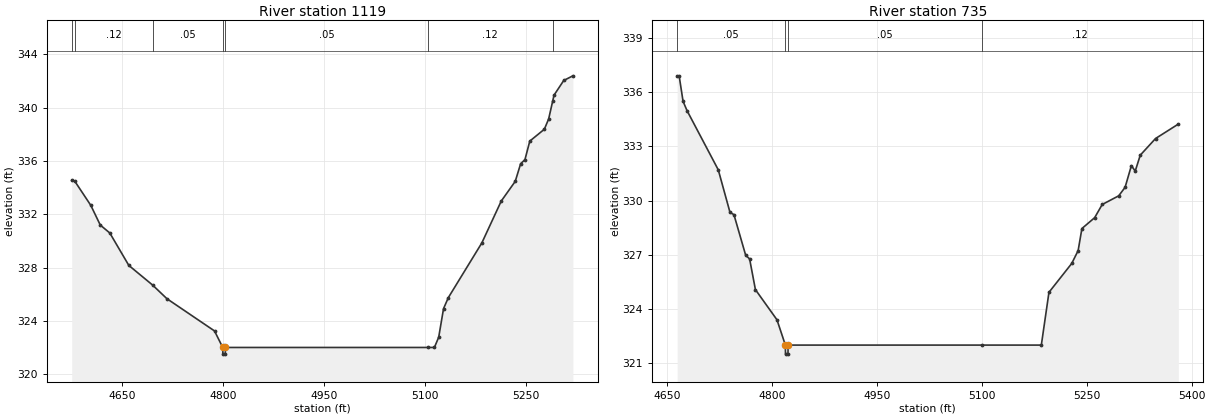
Type RM Length L Ch R = 1,1119,384,384,384
BEGIN DESCRIPTION:
Clear Creek T 30 2.0
END DESCRIPTION:
XS GIS Cut Line= 3
      2733126.00      6780911.00      2732826.00      6781211.00
      2732576.01      6781410.99
#Sta/Elev= 30
  4575.7  334.55  4580.5  334.46  4604.0  332.67  4618.1  331.19  4632.3  330.59
  4660.5  328.16  4695.7  326.69  4717.1  325.66  4787.8  323.24  4800.0  322.00
  4800.2  321.50  4803.7  321.50  4804.0  322.00  5104.4  322.00  5114.4  322.00
  5120.8  322.77  5128.0  324.92  5135.2  325.75  5184.9  329.85  5213.7  332.99
  5234.5  334.47  5242.5  335.79  5248.9  336.10  5256.1  337.49  5277.7  338.38
  5284.1  339.15  5290.0  340.47  5292.1  340.94  5306.5  342.04  5320.1  342.39
#Mann=7,-1,0
  4575.7    0.05       0  4580.5    0.12       0  4695.7    0.05       0
  4800.0    0.03       0  4804.0    0.05       0  5104.4    0.12       0
  5290.0    0.05       0
Bank Sta=4800,4804
Exp/Cntr=0.3,0.1

Type RM Length L Ch R = 1,735,0,0,0
BEGIN DESCRIPTION:
Clear Creek T 30 1.0
END DESCRIPTION:
XS GIS Cut Line= 3
      2733026.03      6780710.98      2732726.00      6780861.00
      2732576.01      6781210.97
#Sta/Elev= 30
  4664.8  336.90  4667.6  336.90  4673.2  335.49  4678.8  334.98  4723.5  331.70
  4740.3  329.34  4745.9  329.22  4762.7  326.97  4768.3  326.77  4776.6  325.07
  4807.4  323.40  4819.4  322.00  4819.6  321.50  4823.1  321.50  4823.4  322.00
  5100.5  322.00  5185.2  322.00  5196.1  324.92  5228.7  326.52  5237.8  327.23
  5243.2  328.45  5261.4  329.05  5272.2  329.78  5295.8  330.26  5304.9  330.73
  5313.9  331.93  5319.4  331.63  5326.6  332.51  5348.4  333.43  5381.0  334.23
#Mann=4,-1,0
  4664.8    0.05       0  4819.4    0.03       0  4823.4    0.05       0
  5100.5    0.12       0
Bank Sta=4819.4,4823.4
Exp/Cntr=0.3,0.1

Chan Stop Cuts=-1