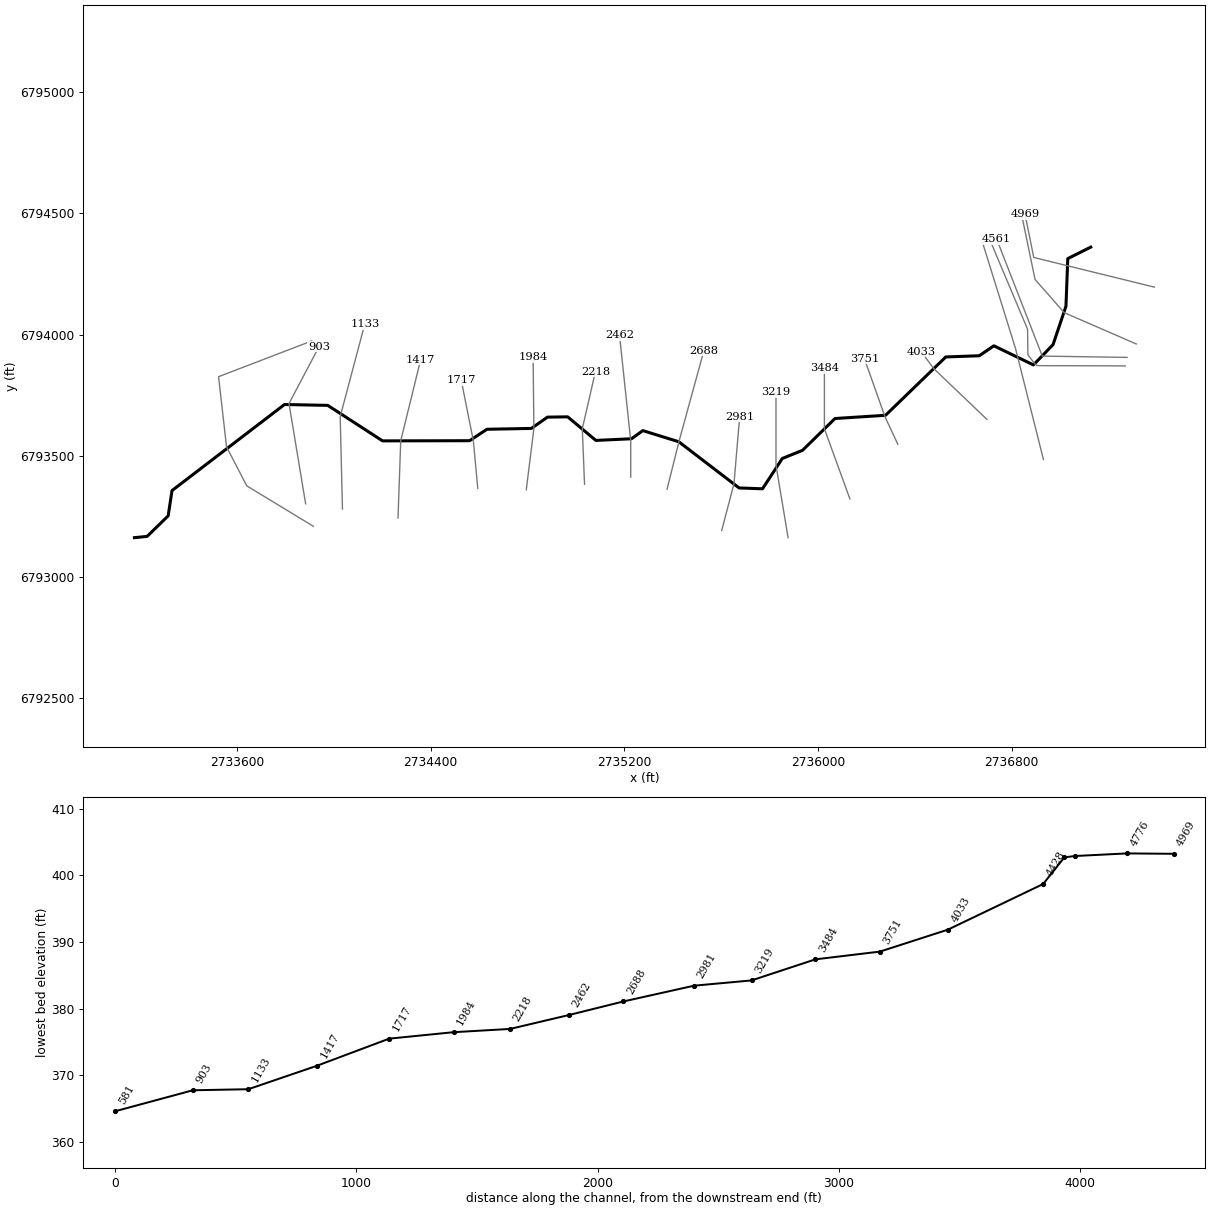
--- Clear Creek T 31.prj (project) ---

Proj Title=Clear Creek T 31 Base Level Engineering
Current Plan=p01
Default Exp/Contr=0.3,0.1
English Units
Geom File=g01
Flow File=f01
Plan File=p01
BEGIN DESCRIPTION:
Clear Creek T 31
END DESCRIPTION:

--- Clear Creek T 31.p01 (plan) ---

Plan Title=Multiple Run
Short Identifier=Multiple
Geom File=g01
Flow File=f01
Subcritical Flow
K Sum by GR= 0
Std Step Tol= 0.01
Critical Tol= 0.01
Num of Std Step Trials= 20
Max Error Tol= 0.3
Flow Tol Ratio= 0.001
Split Flow NTrial= 30
Split Flow Tol= 0.02
Split Flow Ratio= 0.02
Log Output Level= 0
Friction Slope Method= 1
Unsteady Friction Slope Method= 2
Unsteady Bridges Friction Slope Method= 1
Parabolic Critical Depth
Global Vel Dist=  1 , 1 , 1
Global Log Level= 0
CheckData=True
Encroach Param= -1, 0, 0, 0
BEGIN DESCRIPTION:
Multiple Run
END DESCRIPTION:

--- Clear Creek T 31.f01 (steady flow) ---

Flow Title=Multiple
Number of Profiles=7
Profile Names=10-year,25-year,50-year,1pct_min,100-year,1pct_plu,500-year
River Rch & RM= Clear Creek T 31,Reach-1,4969
     190     236     270     154     308     614     397
River Rch & RM= Clear Creek T 31,Reach-1,2462
     377     492     583     343     685    1367     944
Boundary for River Rch & Prof#=Clear Creek T 31,Reach-1,1
Up Type=0
Dn Type=3
Dn Slope=0.005
Boundary for River Rch & Prof#=Clear Creek T 31,Reach-1,2
Up Type=0
Dn Type=3
Dn Slope=0.005
Boundary for River Rch & Prof#=Clear Creek T 31,Reach-1,3
Up Type=0
Dn Type=3
Dn Slope=0.005
Boundary for River Rch & Prof#=Clear Creek T 31,Reach-1,4
Up Type=0
Dn Type=3
Dn Slope=0.005
Boundary for River Rch & Prof#=Clear Creek T 31,Reach-1,5
Up Type=0
Dn Type=3
Dn Slope=0.005
Boundary for River Rch & Prof#=Clear Creek T 31,Reach-1,6
Up Type=0
Dn Type=3
Dn Slope=0.005
Boundary for River Rch & Prof#=Clear Creek T 31,Reach-1,7
Up Type=0
Dn Type=3
Dn Slope=0.005

--- Clear Creek T 31.g01 (geometry) ---

Geom Title=Existing Conditions

River Reach=Clear Creek T 31,Reach-1
Reach XY= 30
      2737126.00      6794361.00      2737031.26      6794313.69
      2737023.74      6794116.94      2736970.48      6793958.54
      2736889.41      6793874.50      2736726.01      6793953.47
      2736665.56      6793912.40      2736527.47      6793907.46
      2736278.45      6793666.46      2736069.81      6793653.19
      2735935.66      6793521.79      2735852.17      6793488.13
      2735770.29      6793362.88      2735673.58      6793366.39
      2735424.41      6793557.18      2735275.90      6793603.22
      2735229.33      6793569.55      2735082.05      6793562.66
      2734965.52      6793660.06      2734881.98      6793658.84
      2734815.50      6793612.22      2734631.94      6793608.74
      2734560.78      6793561.52      2734200.91      6793560.79
      2733974.53      6793707.45      2733795.98      6793711.04
      2733331.26      6793355.53      2733315.49      6793251.23
      2733228.54      6793166.30      2733176.00      6793161.00

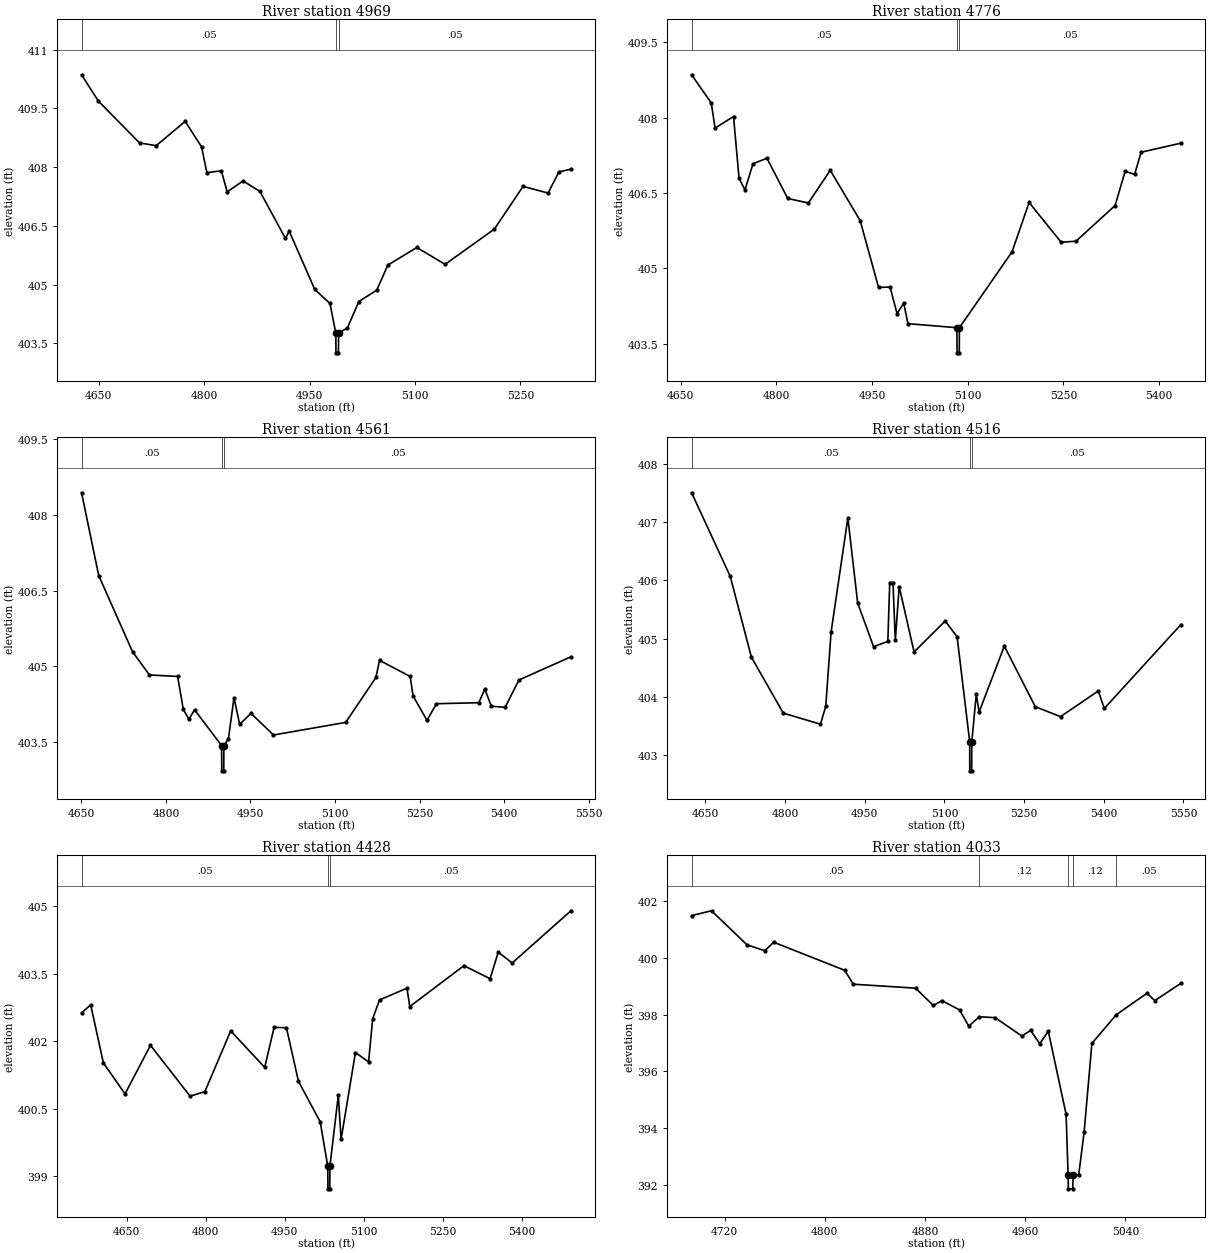
Type RM Length L Ch R = 1,4969,193,193,193
BEGIN DESCRIPTION:
2501
END DESCRIPTION:
XS GIS Cut Line= 3
      2737389.12      6794195.78      2736890.68      6794318.44
      2736854.55      6794497.73
#Sta/Elev= 30
  4625.7  410.36  4649.5  409.69  4708.2  408.62  4731.9  408.55  4773.1  409.17
  4796.4  408.52  4804.0  407.86  4824.6  407.91  4832.8  407.37  4855.5  407.65
  4879.5  407.38  4915.8  406.18  4921.0  406.37  4957.4  404.88  4979.1  404.52
  4987.4  403.76  4987.6  403.26  4991.1  403.26  4991.4  403.76  5004.0  403.90
  5020.2  404.57  5045.6  404.86  5061.4  405.50  5102.6  405.95  5142.9  405.52
  5213.0  406.42  5253.8  407.51  5289.4  407.34  5304.8  407.88  5321.9  407.95
#Mann=3,-1,0
  4625.7    0.05       0  4987.4    0.04       0  4991.4    0.05       0
Bank Sta=4987.4,4991.4
Exp/Cntr=0.3,0.1

Type RM Length L Ch R = 1,4776,215,215,215
BEGIN DESCRIPTION:
2500
END DESCRIPTION:
XS GIS Cut Line= 4
      2737314.22      6793961.06      2737016.74      6794090.37
      2736896.05      6794227.66      2736843.36      6794482.09
#Sta/Elev= 30
  4667.2  408.85  4698.0  408.29  4704.0  407.79  4732.9  408.02  4741.6  406.79
  4750.9  406.56  4763.4  407.08  4785.3  407.19  4817.9  406.39  4850.2  406.30
  4884.5  406.95  4931.4  405.95  4960.3  404.62  4978.3  404.63  4989.2  404.10
  4999.7  404.31  5006.3  403.90  5083.0  403.82  5083.3  403.32  5086.8  403.32
  5087.0  403.82  5169.5  405.33  5196.2  406.31  5246.4  405.52  5269.7  405.54
  5331.0  406.25  5346.7  406.93  5361.6  406.87  5371.8  407.31  5434.2  407.49
#Mann=3,-1,0
  4667.2    0.05       0  5083.0    0.05       0  5087.0    0.05       0
Bank Sta=5083,5087
Exp/Cntr=0.3,0.1

Type RM Length L Ch R = 1,4561,45,45,45
BEGIN DESCRIPTION:
1882
END DESCRIPTION:
XS GIS Cut Line= 3
      2737276.37      6793905.62      2736926.00      6793911.00
      2736738.06      6794393.26
#Sta/Elev= 30
  4650.4  408.44  4680.8  406.80  4740.8  405.29  4770.8  404.83  4820.8  404.80
  4830.8  404.15  4840.8  403.95  4850.8  404.14  4898.8  403.43  4899.1  402.93
  4902.6  402.93  4902.8  403.43  4910.8  403.56  4920.8  404.38  4930.8  403.85
  4950.8  404.07  4990.8  403.64  5118.9  403.89  5172.5  404.78  5178.9  405.12
  5233.2  404.80  5238.6  404.41  5263.1  403.93  5279.9  404.26  5355.0  404.28
  5365.7  404.55  5377.2  404.21  5401.7  404.19  5426.2  404.73  5518.4  405.19
#Mann=3,-1,0
  4650.4    0.05       0  4898.8    0.05       0  4902.8    0.05       0
Bank Sta=4898.8,4902.8
Exp/Cntr=0.3,0.1

Type RM Length L Ch R = 1,4516,88,88,88
BEGIN DESCRIPTION:
2357
END DESCRIPTION:
XS GIS Cut Line= 6
      2737268.61      6793870.48      2736906.33      6793871.64
      2736895.13      6793878.95      2736866.66      6793916.16
      2736865.07      6794022.20      2736712.53      6794383.99
#Sta/Elev= 30
  4624.0  407.50  4696.6  406.07  4736.6  404.68  4796.6  403.72  4866.6  403.53
  4876.6  403.84  4886.6  405.11  4918.2  407.07  4936.6  405.61  4966.6  404.86
  4993.4  404.95  4997.0  405.96  5003.1  405.96  5007.5  404.97  5014.8  405.89
  5042.8  404.77  5101.4  405.30  5123.8  405.03  5147.5  403.23  5147.7  402.73
  5151.2  402.73  5151.5  403.23  5159.9  404.04  5165.3  403.74  5212.7  404.87
  5271.0  403.83  5318.5  403.66  5389.6  404.10  5400.9  403.80  5545.2  405.24
#Mann=3,-1,0
  4624.0    0.05       0  5147.5    0.05       0  5151.5    0.05       0
Bank Sta=5147.5,5151.5
Exp/Cntr=0.3,0.1

Type RM Length L Ch R = 1,4428,395,395,395
BEGIN DESCRIPTION:
2358
END DESCRIPTION:
XS GIS Cut Line= 3
      2736930.62      6793484.23      2736815.48      6793942.01
      2736680.02      6794377.39
#Sta/Elev= 30
  4564.5  402.63  4581.8  402.81  4605.8  401.52  4646.9  400.83  4695.2  401.91
  4770.2  400.78  4798.3  400.88  4847.3  402.23  4911.8  401.42  4929.6  402.31
  4953.0  402.30  4975.8  401.11  5017.0  400.21  5031.4  399.22  5031.7  398.72
  5035.2  398.72  5035.4  399.22  5051.4  400.80  5056.6  399.82  5083.9  401.75
  5108.8  401.54  5116.5  402.50  5129.7  402.92  5181.6  403.18  5186.8  402.77
  5289.6  403.68  5339.2  403.39  5354.7  403.98  5381.1  403.74  5492.5  404.90
#Mann=3,-1,0
  4564.5    0.05       0  5031.4    0.05       0  5035.4    0.05       0
Bank Sta=5031.4,5035.4
Exp/Cntr=0.3,0.1

Type RM Length L Ch R = 1,4033,282,282,282
BEGIN DESCRIPTION:
1881
END DESCRIPTION:
XS GIS Cut Line= 3
      2736697.27      6793649.57      2736476.00      6793861.00
      2736426.29      6793929.53
#Sta/Elev= 30
  4693.7  401.50  4709.6  401.67  4737.9  400.47  4752.1  400.26  4759.3  400.56
  4815.9  399.57  4822.8  399.08  4872.5  398.94  4886.7  398.33  4893.6  398.50
  4907.7  398.17  4915.0  397.60  4923.4  397.93  4936.1  397.90  4957.4  397.25
  4964.4  397.45  4971.6  396.98  4978.5  397.42  4992.7  394.49  4994.3  392.36
  4994.5  391.86  4998.0  391.86  4998.3  392.36  5002.8  392.36  5007.1  393.86
  5013.3  396.99  5032.7  398.00  5057.3  398.76  5063.5  398.50  5084.4  399.11
#Mann=5,-1,0
  4693.7    0.05       0  4923.4    0.12       0  4994.3    0.07       0
  4998.3    0.12       0  5032.7    0.05       0
Bank Sta=4994.3,4998.3
Exp/Cntr=0.3,0.1

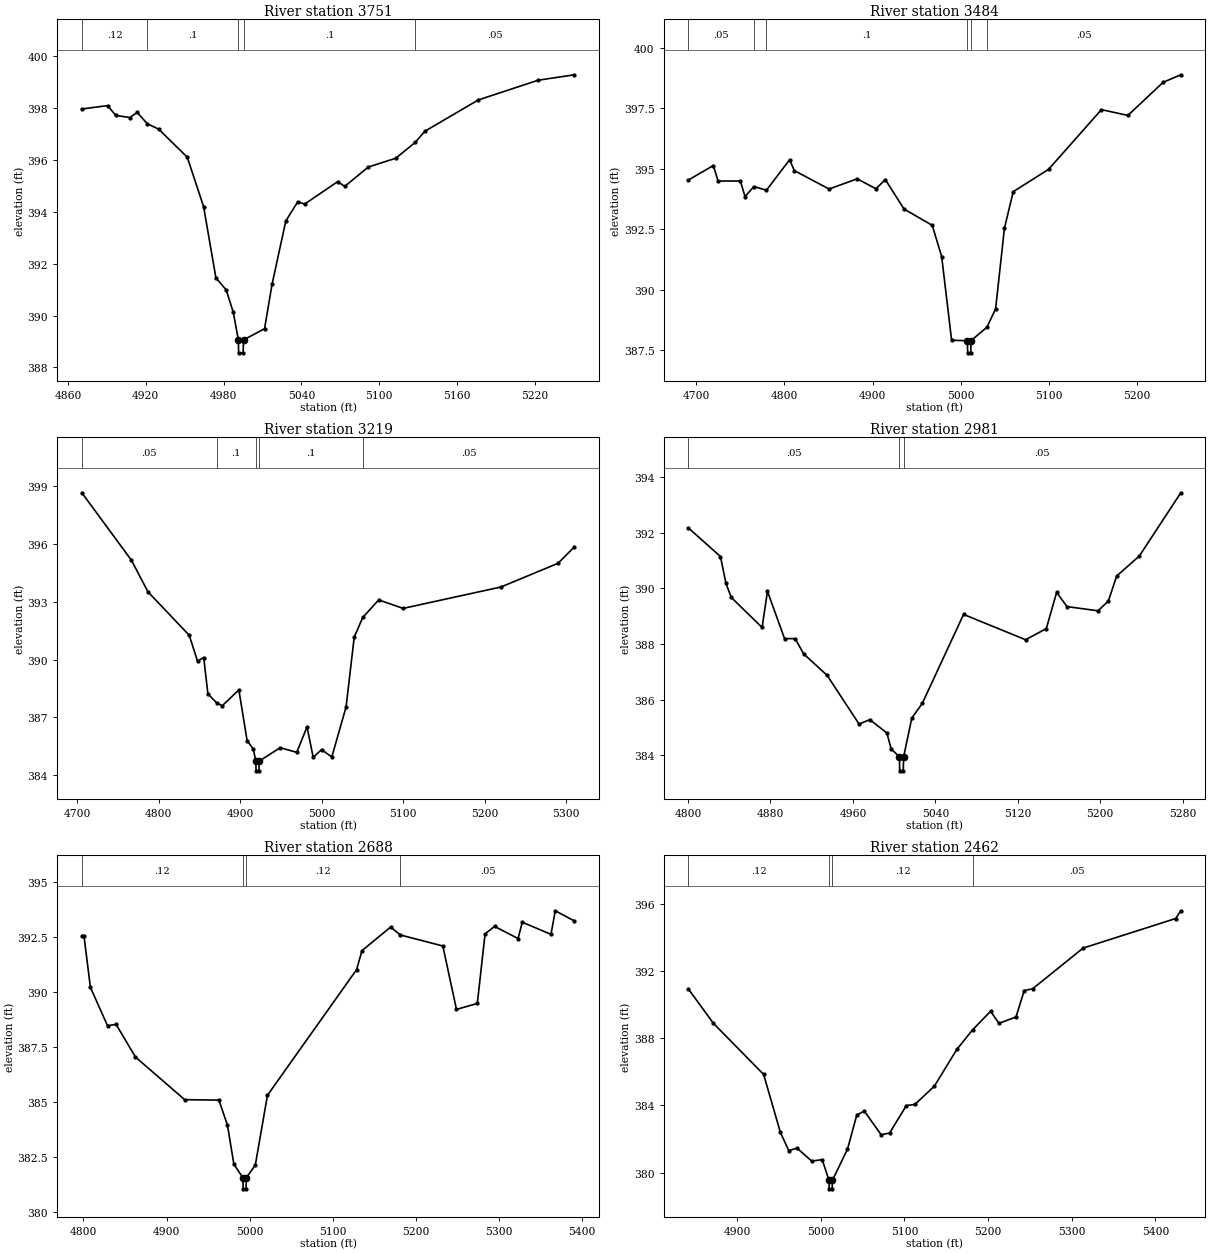
Type RM Length L Ch R = 1,3751,267,267,267
BEGIN DESCRIPTION:
1880
END DESCRIPTION:
XS GIS Cut Line= 3
      2736328.99      6793547.28      2736276.00      6793661.00
      2736191.15      6793900.78
#Sta/Elev= 30
  4870.7  397.97  4890.5  398.10  4896.9  397.72  4907.8  397.64  4913.3  397.84
  4921.2  397.40  4930.0  397.19  4952.0  396.11  4964.6  394.20  4974.1  391.45
  4982.0  390.99  4987.5  390.12  4991.4  389.06  4991.6  388.56  4995.1  388.56
  4995.4  389.06  5011.6  389.49  5017.4  391.21  5028.0  393.65  5037.2  394.39
  5042.5  394.30  5068.1  395.17  5073.4  394.98  5091.6  395.73  5112.8  396.07
  5127.8  396.68  5135.2  397.11  5176.5  398.32  5222.6  399.08  5250.5  399.29
#Mann=5,-1,0
  4870.7    0.12       0  4921.2     0.1       0  4991.4    0.07       0
  4995.4     0.1       0  5127.8    0.05       0
Bank Sta=4991.4,4995.4
Exp/Cntr=0.3,0.1

Type RM Length L Ch R = 1,3484,265,265,265
BEGIN DESCRIPTION:
1879
END DESCRIPTION:
XS GIS Cut Line= 3
      2736131.30      6793320.97      2736026.00      6793611.00
      2736026.00      6793860.95
#Sta/Elev= 30
  4691.1  394.54  4719.5  395.14  4724.8  394.50  4750.1  394.50  4755.4  393.86
  4765.5  394.27  4779.7  394.12  4806.0  395.38  4811.3  394.93  4850.7  394.17
  4882.6  394.59  4903.9  394.18  4914.5  394.56  4935.8  393.34  4967.7  392.67
  4978.4  391.38  4989.7  387.92  5007.6  387.90  5007.9  387.40  5011.4  387.40
  5011.6  387.90  5029.8  388.46  5039.6  389.22  5049.6  392.55  5059.6  394.06
  5099.6  394.98  5159.6  397.45  5189.6  397.21  5229.6  398.58  5249.6  398.89
#Mann=6,-1,0
  4691.1    0.05       0  4765.5    0.12       0  4779.7     0.1       0
  5007.6    0.07       0  5011.6     0.1       0  5029.8    0.05       0
Bank Sta=5007.6,5011.6
Exp/Cntr=0.3,0.1

Type RM Length L Ch R = 1,3219,238,238,238
BEGIN DESCRIPTION:
1878
END DESCRIPTION:
XS GIS Cut Line= 3
      2735876.00      6793161.03      2735826.00      6793461.00
      2735826.00      6793760.99
#Sta/Elev= 30
  4705.9  398.66  4766.7  395.16  4787.0  393.52  4837.7  391.26  4847.8  389.92
  4855.4  390.11  4860.5  388.23  4871.4  387.75  4878.2  387.61  4898.5  388.43
  4908.6  385.80  4916.2  385.36  4919.3  384.73  4919.6  384.23  4923.1  384.23
  4923.3  384.73  4949.2  385.43  4969.5  385.19  4982.1  386.51  4989.7  384.93
  4999.9  385.33  5012.5  384.95  5030.0  387.54  5040.0  391.17  5050.5  392.19
  5070.0  393.10  5100.0  392.66  5220.0  393.77  5290.0  395.00  5310.0  395.85
#Mann=5,-1,0
  4705.9    0.05       0  4871.4     0.1       0  4919.3    0.07       0
  4923.3     0.1       0  5050.5    0.05       0
Bank Sta=4919.3,4923.3
Exp/Cntr=0.3,0.1

Type RM Length L Ch R = 1,2981,293,293,293
BEGIN DESCRIPTION:
1877
END DESCRIPTION:
XS GIS Cut Line= 3
      2735601.79      6793190.68      2735652.48      6793383.84
      2735676.00      6793661.05
#Sta/Elev= 30
  4800.3  392.17  4831.5  391.14  4836.7  390.19  4842.0  389.67  4871.9  388.59
  4877.1  389.89  4893.7  388.19  4904.0  388.19  4912.3  387.64  4935.0  386.87
  4966.0  385.12  4976.4  385.28  4993.0  384.80  4997.1  384.23  5005.2  383.94
  5005.4  383.44  5008.9  383.44  5009.2  383.94  5017.2  385.34  5027.3  385.86
  5067.4  389.06  5127.6  388.15  5147.7  388.55  5157.7  389.85  5167.8  389.34
  5197.9  389.19  5207.9  389.54  5216.0  390.44  5238.0  391.16  5278.2  393.43
#Mann=3,-1,0
  4800.3    0.05       0  5005.2    0.04       0  5009.2    0.05       0
Bank Sta=5005.2,5009.2
Exp/Cntr=0.3,0.1

Type RM Length L Ch R = 1,2688,226,226,226
BEGIN DESCRIPTION:
1876
END DESCRIPTION:
XS GIS Cut Line= 3
      2735376.01      6793361.03      2735426.00      6793561.00
      2735528.32      6793933.58
#Sta/Elev= 30
  4798.1  392.57  4800.6  392.57  4808.4  390.22  4829.0  388.48  4839.3  388.54
  4862.5  387.06  4921.8  385.12  4963.0  385.10  4973.3  383.96  4981.0  382.19
  4991.9  381.57  4992.2  381.07  4995.7  381.07  4995.9  381.57  5006.8  382.15
  5021.4  385.32  5128.7  391.03  5135.1  391.89  5169.6  392.96  5181.4  392.60
  5232.4  392.10  5248.8  389.22  5273.9  389.49  5283.2  392.65  5294.6  392.99
  5322.9  392.44  5328.0  393.18  5362.5  392.63  5367.7  393.70  5390.6  393.24
#Mann=4,-1,0
  4798.1    0.12       0  4991.9    0.07       0  4995.9    0.12       0
  5181.4    0.05       0
Bank Sta=4991.9,4995.9
Exp/Cntr=0.3,0.1

Type RM Length L Ch R = 1,2462,244,244,244
BEGIN DESCRIPTION:
1875
END DESCRIPTION:
XS GIS Cut Line= 3
      2735226.00      6793411.01      2735226.00      6793561.00
      2735179.72      6793997.06
#Sta/Elev= 30
  4841.8  390.93  4871.8  388.88  4931.8  385.84  4951.8  382.39  4961.8  381.31
  4971.8  381.45  4989.3  380.68  5001.8  380.77  5009.9  379.53  5010.2  379.03
  5013.7  379.03  5013.9  379.53  5032.0  381.39  5043.1  383.42  5052.1  383.66
  5072.2  382.25  5082.3  382.35  5102.4  383.99  5112.5  384.05  5135.8  385.14
  5162.7  387.33  5181.6  388.50  5203.0  389.60  5213.0  388.88  5233.4  389.26
  5243.2  390.83  5253.3  390.94  5313.6  393.36  5424.2  395.12  5430.3  395.58
#Mann=4,-1,0
  4841.8    0.12       0  5009.9    0.07       0  5013.9    0.12       0
  5181.6    0.05       0
Bank Sta=5009.9,5013.9
Exp/Cntr=0.3,0.1

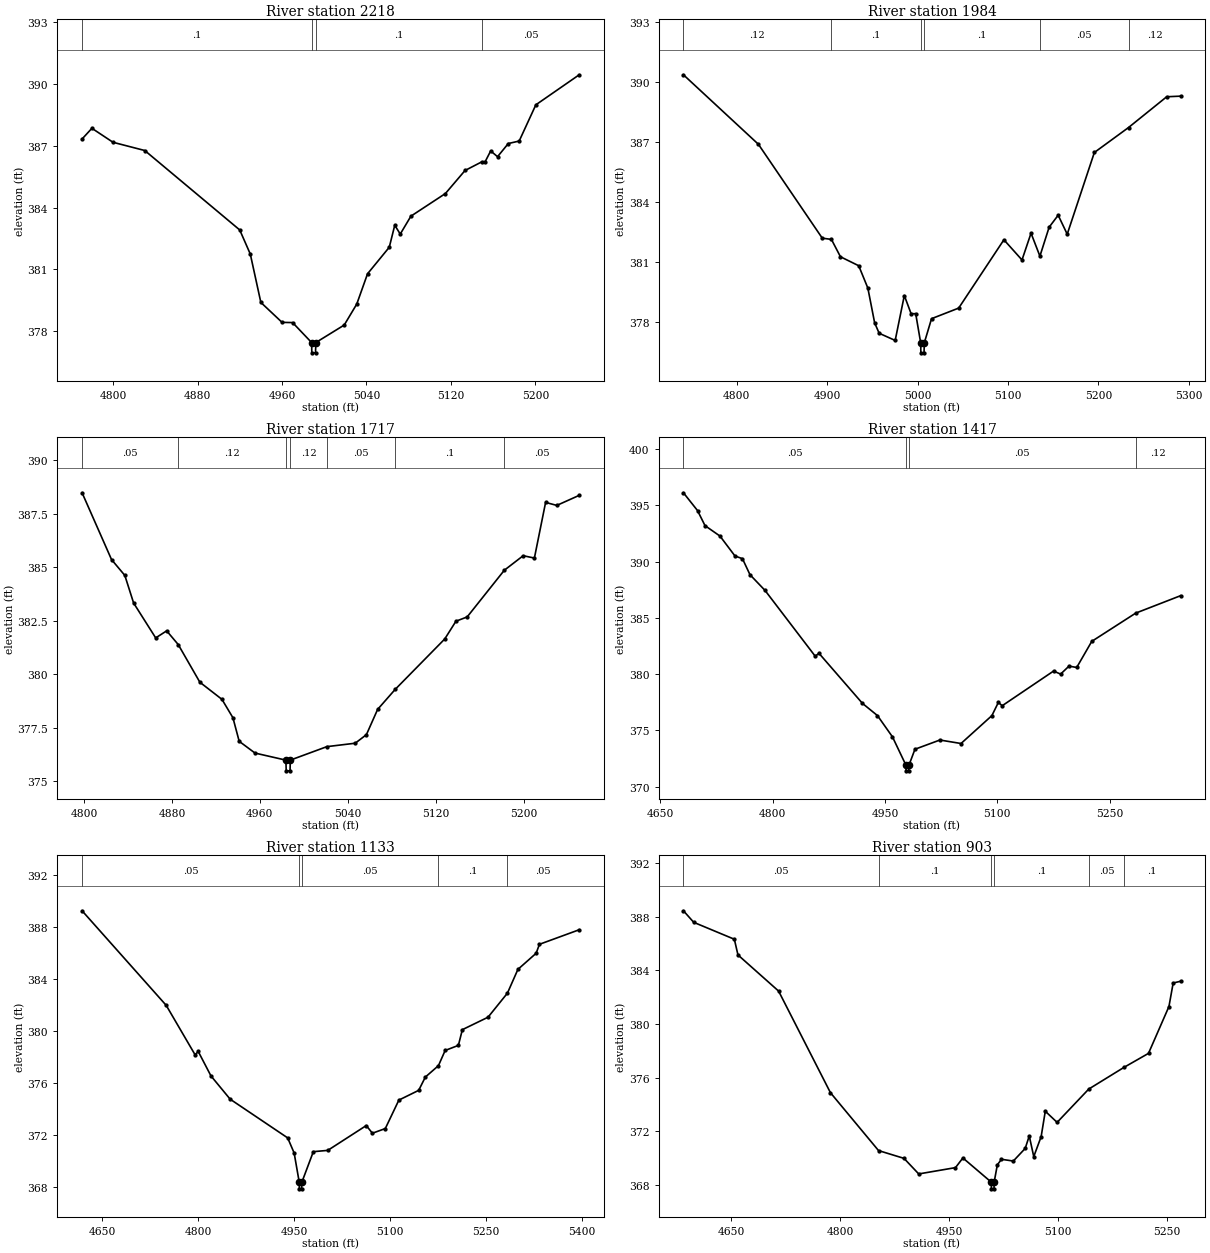
Type RM Length L Ch R = 1,2218,234,234,234
BEGIN DESCRIPTION:
1874
END DESCRIPTION:
XS GIS Cut Line= 3
      2735035.27      6793381.69      2735026.00      6793611.00
      2735080.11      6793846.46
#Sta/Elev= 30
  4770.5  387.33  4779.8  387.85  4799.8  387.17  4829.9  386.77  4919.9  382.91
  4929.9  381.74  4939.9  379.39  4960.0  378.42  4970.0  378.41  4988.0  377.44
  4988.2  376.94  4991.7  376.94  4992.0  377.44  5018.9  378.29  5030.8  379.31
  5041.0  380.78  5061.6  382.07  5066.8  383.14  5072.0  382.71  5082.1  383.58
  5114.8  384.68  5133.4  385.80  5149.3  386.22  5152.5  386.23  5157.7  386.75
  5164.2  386.47  5174.4  387.11  5184.7  387.23  5200.5  388.99  5241.6  390.45
#Mann=4,-1,0
  4770.5     0.1       0  4988.0    0.07       0  4992.0     0.1       0
  5149.3    0.05       0
Bank Sta=4988,4992
Exp/Cntr=0.3,0.1

Type RM Length L Ch R = 1,1984,267,267,267
BEGIN DESCRIPTION:
1873
END DESCRIPTION:
XS GIS Cut Line= 3
      2734794.54      6793358.70      2734826.00      6793611.00
      2734822.80      6793906.33
#Sta/Elev= 30
  4741.2  390.37  4824.1  386.89  4894.7  382.19  4904.8  382.13  4914.8  381.26
  4935.0  380.81  4945.1  379.69  4952.6  377.95  4957.6  377.43  4975.3  377.07
  4985.4  379.32  4992.9  378.41  4998.0  378.41  5003.5  376.95  5003.7  376.45
  5007.2  376.45  5007.5  376.95  5015.5  378.16  5045.5  378.69  5095.5  382.11
  5115.5  381.10  5125.5  382.44  5135.3  381.29  5145.5  382.74  5155.5  383.34
  5165.5  382.39  5195.5  386.48  5233.3  387.73  5275.5  389.27  5290.8  389.30
#Mann=6,-1,0
  4741.2    0.12       0  4904.8     0.1       0  5003.5    0.07       0
  5007.5     0.1       0  5135.3    0.05       0  5233.3    0.12       0
Bank Sta=5003.5,5007.5
Exp/Cntr=0.3,0.1

Type RM Length L Ch R = 1,1717,300,300,300
BEGIN DESCRIPTION:
1872
END DESCRIPTION:
XS GIS Cut Line= 3
      2734594.32      6793364.29      2734576.00      6793561.00
      2734526.00      6793810.98
#Sta/Elev= 30
  4798.2  388.47  4825.0  385.35  4837.1  384.61  4845.1  383.32  4865.2  381.69
  4875.2  382.02  4885.7  381.38  4905.4  379.62  4925.5  378.82  4935.5  377.96
  4941.2  376.86  4955.6  376.31  4983.7  375.98  4984.0  375.48  4987.5  375.48
  4987.7  375.98  5021.0  376.61  5046.8  376.77  5057.0  377.17  5067.2  378.35
  5083.1  379.28  5128.3  381.64  5138.5  382.47  5148.7  382.67  5182.5  384.85
  5199.7  385.53  5209.9  385.42  5220.1  388.02  5230.3  387.88  5250.7  388.35
#Mann=7,-1,0
  4798.2    0.05       0  4885.7    0.12       0  4983.7    0.07       0
  4987.7    0.12       0  5021.0    0.05       0  5083.1     0.1       0
  5182.5    0.05       0
Bank Sta=4983.7,4987.7
Exp/Cntr=0.3,0.1

Type RM Length L Ch R = 1,1417,284,284,284
BEGIN DESCRIPTION:
1871
END DESCRIPTION:
XS GIS Cut Line= 3
      2734264.70      6793242.21      2734276.00      6793561.00
      2734358.15      6793895.57
#Sta/Elev= 30
  4681.1  396.12  4699.9  394.54  4709.9  393.20  4729.9  392.27  4749.9  390.50
  4759.9  390.26  4769.9  388.84  4790.0  387.44  4857.0  381.59  4862.0  381.85
  4920.0  377.40  4940.1  376.31  4960.1  374.42  4978.1  371.90  4978.3  371.40
  4981.8  371.40  4982.1  371.90  4990.1  373.32  5023.4  374.14  5051.6  373.83
  5092.8  376.31  5101.4  377.48  5106.6  377.19  5175.1  380.27  5184.5  380.00
  5195.7  380.71  5206.0  380.59  5226.1  382.91  5284.7  385.42  5344.6  386.97
#Mann=4,-1,0
  4681.1    0.05       0  4978.1    0.04       0  4982.1    0.05       0
  5284.7    0.12       0
Bank Sta=4978.1,4982.1
Exp/Cntr=0.3,0.1

Type RM Length L Ch R = 1,1133,230,230,230
BEGIN DESCRIPTION:
1870
END DESCRIPTION:
XS GIS Cut Line= 3
      2734035.32      6793279.45      2734026.00      6793661.00
      2734127.65      6794043.66
#Sta/Elev= 30
  4618.3  389.28  4749.9  382.00  4795.0  378.20  4800.0  378.45  4819.9  376.57
  4849.9  374.78  4939.9  371.80  4950.0  370.64  4958.0  368.38  4958.2  367.88
  4961.7  367.88  4962.0  368.38  4980.0  370.74  5002.6  370.84  5062.8  372.75
  5072.4  372.16  5092.6  372.52  5113.8  374.71  5144.8  375.46  5155.2  376.48
  5175.7  377.36  5186.2  378.53  5206.9  378.92  5213.1  380.13  5253.3  381.09
  5283.6  382.94  5300.0  384.77  5328.5  386.01  5333.7  386.70  5395.9  387.82
#Mann=5,-1,0
  4618.3    0.05       0  4958.0    0.04       0  4962.0    0.05       0
  5175.7     0.1       0  5283.6    0.05       0
Bank Sta=4958,4962
Exp/Cntr=0.3,0.1

Type RM Length L Ch R = 1,903,322,322,322
BEGIN DESCRIPTION:
2346
END DESCRIPTION:
XS GIS Cut Line= 3
      2733883.17      6793300.99      2733814.55      6793715.04
      2733938.50      6793950.06
#Sta/Elev= 30
  4583.9  388.43  4598.1  387.57  4654.1  386.31  4659.1  385.14  4715.1  382.45
  4786.6  374.88  4852.9  370.57  4888.0  369.99  4908.3  368.83  4959.0  369.30
  4969.2  370.02  5008.3  368.22  5008.6  367.72  5012.1  367.72  5012.3  368.22
  5016.7  369.51  5022.4  369.92  5038.7  369.79  5055.1  370.73  5060.7  371.66
  5066.9  370.12  5077.1  371.61  5082.8  373.50  5099.1  372.67  5142.7  375.15
  5191.4  376.77  5225.1  377.81  5253.3  381.30  5259.1  383.05  5269.3  383.18
#Mann=6,-1,0
  4583.9    0.05       0  4852.9     0.1       0  5008.3    0.07       0
  5012.3     0.1       0  5142.7    0.05       0  5191.4     0.1       0
Bank Sta=5008.3,5012.3
Exp/Cntr=0.3,0.1

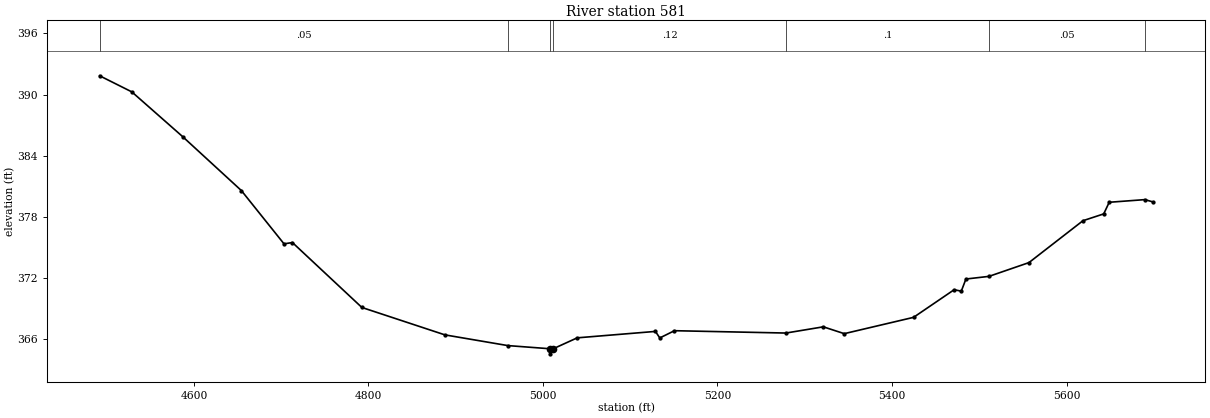
Type RM Length L Ch R = 1,581,0,0,0
BEGIN DESCRIPTION:
1869
END DESCRIPTION:
XS GIS Cut Line= 5
      2733914.80      6793208.24      2733640.14      6793374.96
      2733556.50      6793536.11      2733523.59      6793825.94
      2733908.49      6793973.56
#Sta/Elev= 30
  4492.0  391.85  4528.9  390.27  4587.0  385.89  4654.4  380.59  4703.3  375.36
  4712.9  375.49  4792.5  369.12  4887.7  366.43  4959.7  365.38  5007.8  365.07
  5008.1  364.57  5011.8  365.07  5039.3  366.14  5128.9  366.77  5133.9  366.13
  5150.7  366.84  5278.4  366.61  5321.3  367.22  5345.3  366.55  5424.7  368.15
  5471.2  370.86  5479.4  370.72  5484.7  371.91  5511.1  372.17  5556.9  373.52
  5618.8  377.63  5642.6  378.30  5648.9  379.44  5689.7  379.70  5698.8  379.48
#Mann=7,-1,0
  4492.0    0.05       0  4959.7    0.12       0  5007.8    0.07       0
  5011.8    0.12       0  5278.4     0.1       0  5511.1    0.05       0
  5689.7     0.1       0
Bank Sta=5007.8,5011.8
Exp/Cntr=0.3,0.1

Chan Stop Cuts=-1