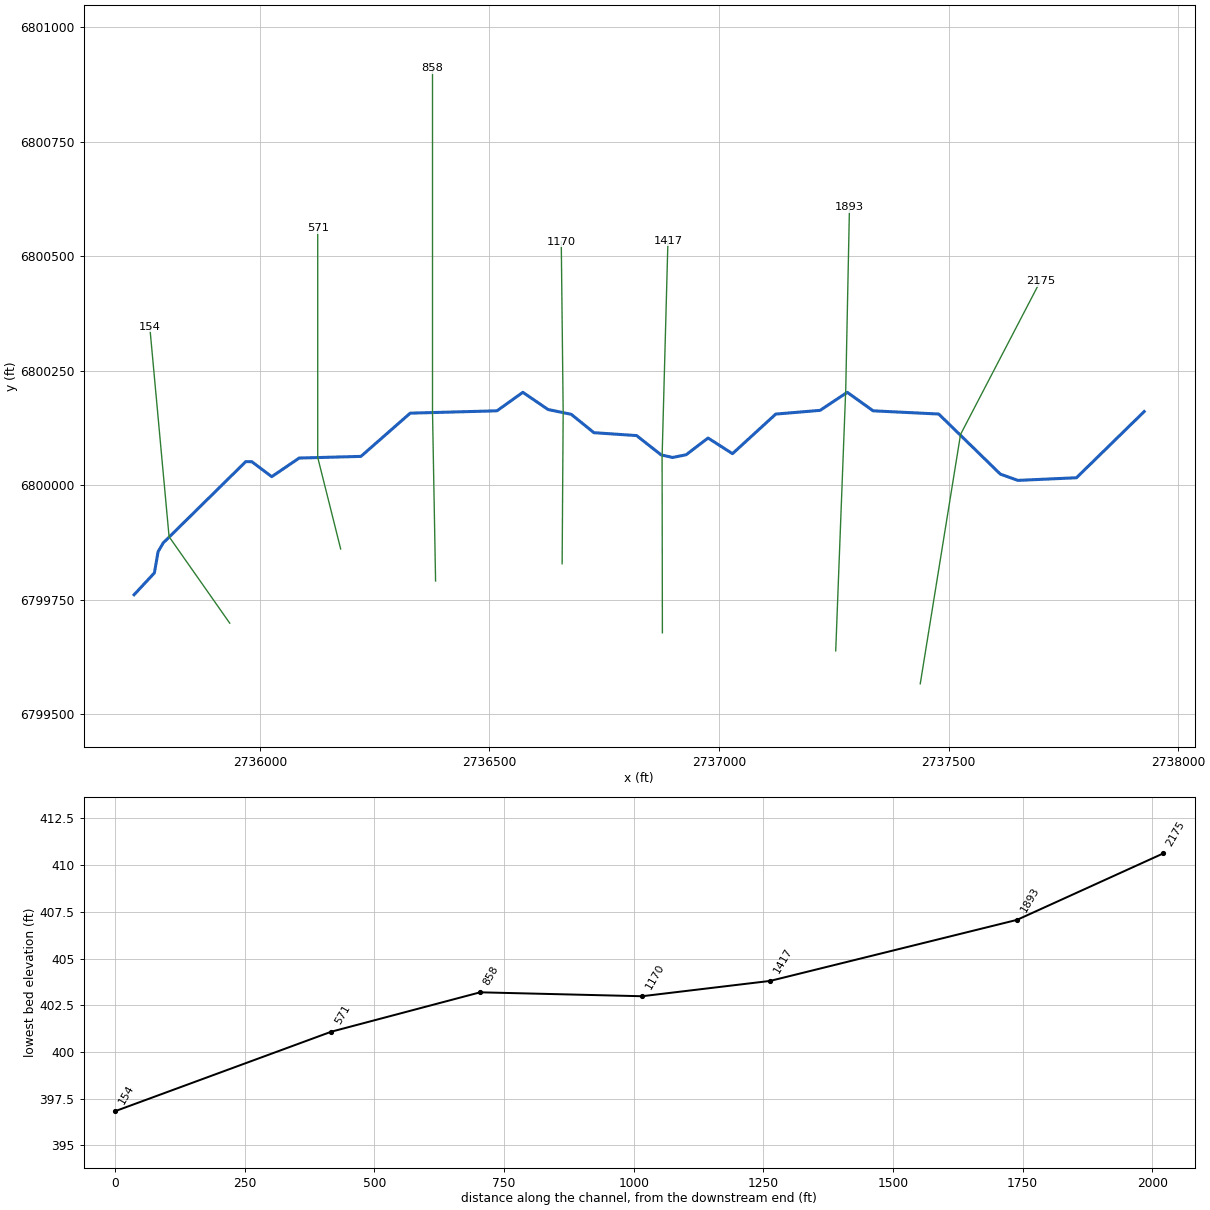
--- Clear Creek T 32.prj (project) ---

Proj Title=Clear Creek T 32 Base Level Engineering
Current Plan=p01
Default Exp/Contr=0.3,0.1
English Units
Geom File=g01
Flow File=f01
Plan File=p01
BEGIN DESCRIPTION:
Clear Creek T 32
END DESCRIPTION:

--- Clear Creek T 32.p01 (plan) ---

Plan Title=Multiple Run
Short Identifier=Multiple
Geom File=g01
Flow File=f01
Subcritical Flow
K Sum by GR= 0
Std Step Tol= 0.01
Critical Tol= 0.01
Num of Std Step Trials= 20
Max Error Tol= 0.3
Flow Tol Ratio= 0.001
Split Flow NTrial= 30
Split Flow Tol= 0.02
Split Flow Ratio= 0.02
Log Output Level= 0
Friction Slope Method= 1
Unsteady Friction Slope Method= 2
Unsteady Bridges Friction Slope Method= 1
Parabolic Critical Depth
Global Vel Dist=  1 , 1 , 1
Global Log Level= 0
CheckData=True
Encroach Param= -1, 0, 0, 0
BEGIN DESCRIPTION:
Multiple Run
END DESCRIPTION:

--- Clear Creek T 32.f01 (steady flow) ---

Flow Title=Multiple
Number of Profiles=7
Profile Names=10-year,25-year,50-year,1pct_min,100-year,1pct_plu,500-year
River Rch & RM= Clear Creek T 32,Reach-1,2175
     323     414     483     281     560    1117     750
Boundary for River Rch & Prof#=Clear Creek T 32,Reach-1,1
Up Type=0
Dn Type=3
Dn Slope=0.005
Boundary for River Rch & Prof#=Clear Creek T 32,Reach-1,2
Up Type=0
Dn Type=3
Dn Slope=0.005
Boundary for River Rch & Prof#=Clear Creek T 32,Reach-1,3
Up Type=0
Dn Type=3
Dn Slope=0.005
Boundary for River Rch & Prof#=Clear Creek T 32,Reach-1,4
Up Type=0
Dn Type=3
Dn Slope=0.005
Boundary for River Rch & Prof#=Clear Creek T 32,Reach-1,5
Up Type=0
Dn Type=3
Dn Slope=0.005
Boundary for River Rch & Prof#=Clear Creek T 32,Reach-1,6
Up Type=0
Dn Type=3
Dn Slope=0.005
Boundary for River Rch & Prof#=Clear Creek T 32,Reach-1,7
Up Type=0
Dn Type=3
Dn Slope=0.005

--- Clear Creek T 32.g01 (geometry) ---

Geom Title=Existing Conditions

River Reach=Clear Creek T 32,Reach-1
Reach XY= 30
      2737926.00      6800161.00      2737778.45      6800016.45
      2737650.89      6800010.68      2737612.68      6800024.37
      2737478.45      6800155.53      2737335.60      6800162.56
      2737279.30      6800202.92      2737220.10      6800163.56
      2737123.57      6800155.45      2737029.33      6800069.01
      2736976.09      6800103.16      2736928.30      6800066.63
      2736898.84      6800060.70      2736873.83      6800066.40
      2736820.44      6800108.51      2736727.58      6800114.83
      2736678.17      6800154.91      2736627.64      6800165.42
      2736572.71      6800202.94      2736516.41      6800162.55
      2736327.47      6800157.45      2736220.14      6800063.08
      2736085.59      6800059.45      2736025.90      6800018.81
      2735982.66      6800051.40      2735969.33      6800051.70
      2735789.57      6799874.23      2735778.34      6799855.03
      2735770.29      6799808.65      2735726.00      6799761.00

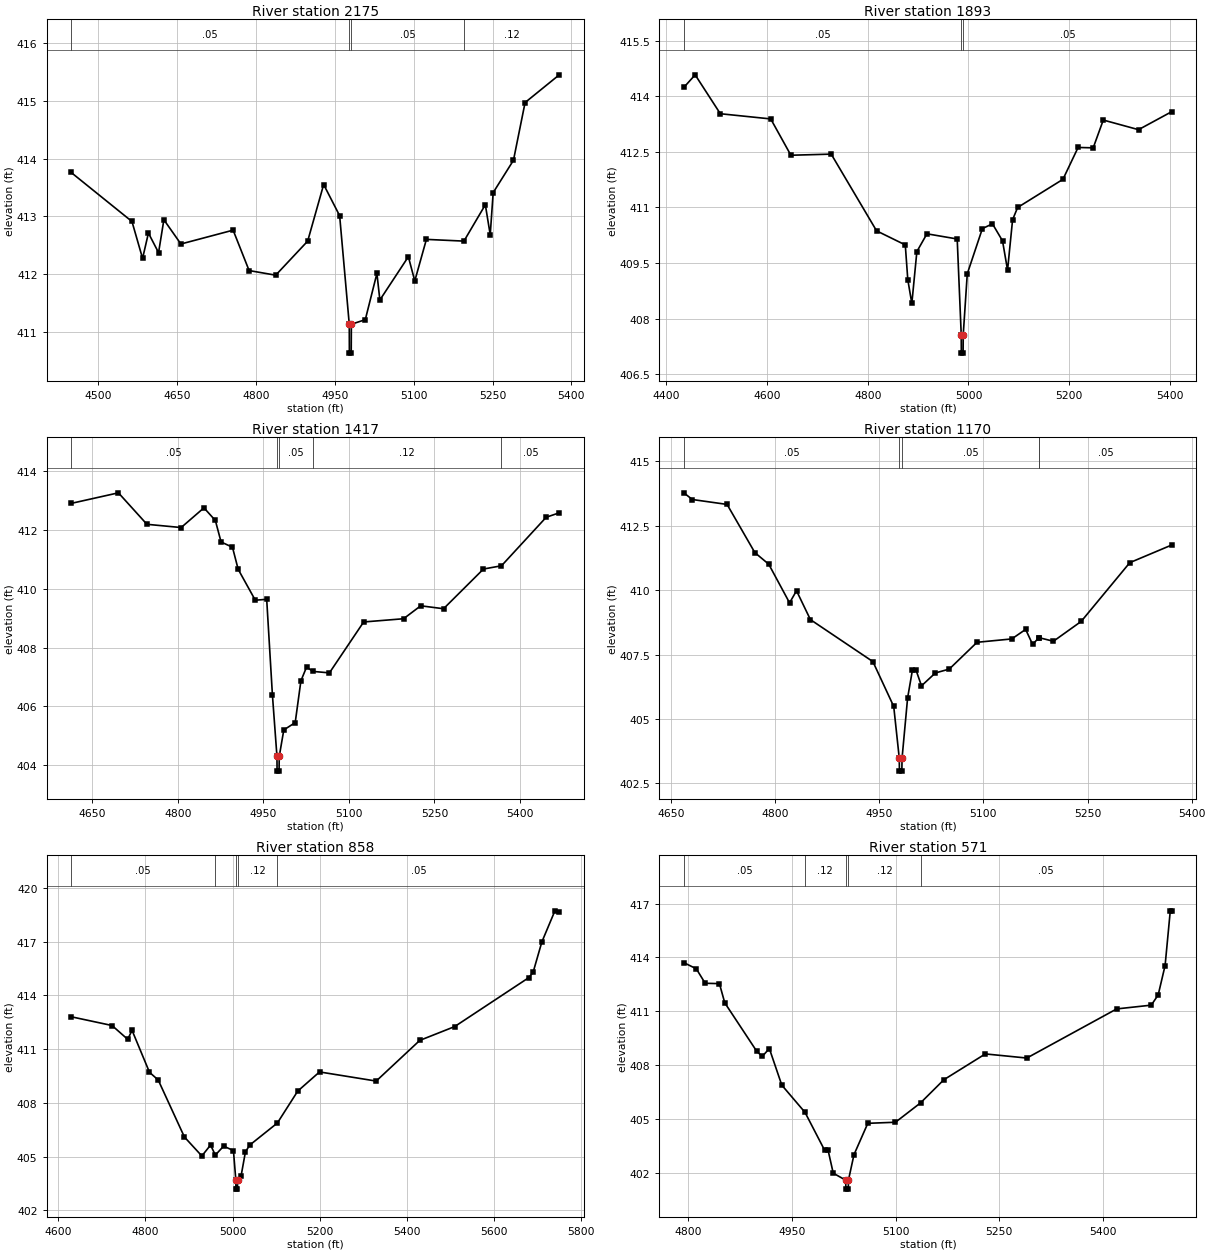
Type RM Length L Ch R = 1,2175,282,282,282
BEGIN DESCRIPTION:
Clear Creek T 32 7.0
END DESCRIPTION:
XS GIS Cut Line= 3
      2737438.25      6799566.72      2737526.00      6800111.00
      2737699.85      6800445.74
#Sta/Elev= 30
  4448.4  413.76  4564.2  412.91  4584.4  412.27  4595.5  412.71  4614.8  412.37
  4624.9  412.94  4657.3  412.52  4756.6  412.76  4787.0  412.06  4837.6  411.98
  4898.4  412.57  4928.8  413.55  4959.2  413.01  4977.5  411.13  4977.7  410.63
  4981.2  410.63  4981.5  411.13  5008.0  411.21  5030.1  412.01  5035.7  411.55
  5089.9  412.30  5102.1  411.88  5124.2  412.60  5195.6  412.57  5236.3  413.20
  5245.6  412.68  5251.2  413.41  5289.8  413.97  5311.9  414.97  5376.9  415.45
#Mann=4,-1,0
  4448.4    0.05       0  4977.5    0.04       0  4981.5    0.05       0
  5195.6    0.12       0
Bank Sta=4977.5,4981.5
Exp/Cntr=0.3,0.1

Type RM Length L Ch R = 1,1893,476,476,476
BEGIN DESCRIPTION:
Clear Creek T 32 6.0
END DESCRIPTION:
XS GIS Cut Line= 3
      2737254.14      6799638.51      2737276.00      6800211.00
      2737284.08      6800607.51
#Sta/Elev= 30
  4434.7  414.24  4457.2  414.58  4507.2  413.53  4607.3  413.39  4647.3  412.41
  4727.4  412.44  4817.5  410.37  4874.5  409.99  4879.5  409.05  4887.5  408.41
  4897.5  409.81  4917.5  410.29  4977.6  410.15  4985.6  407.57  4985.8  407.07
  4989.3  407.07  4989.6  407.57  4997.6  409.21  5027.6  410.43  5047.6  410.56
  5067.6  410.10  5077.6  409.31  5087.6  410.67  5097.6  411.00  5187.6  411.76
  5217.7  412.62  5247.7  412.61  5267.7  413.36  5337.7  413.10  5404.2  413.59
#Mann=3,-1,0
  4434.7    0.05       0  4985.6    0.04       0  4989.6    0.05       0
Bank Sta=4985.6,4989.6
Exp/Cntr=0.3,0.1

Type RM Length L Ch R = 1,1417,247,247,247
BEGIN DESCRIPTION:
Clear Creek T 32 5.0
END DESCRIPTION:
XS GIS Cut Line= 3
      2736876.65      6799678.03      2736876.00      6800061.00
      2736888.75      6800533.86
#Sta/Elev= 30
  4612.8  412.90  4695.8  413.26  4745.8  412.19  4805.8  412.08  4845.8  412.75
  4865.8  412.32  4875.8  411.59  4895.8  411.41  4905.8  410.66  4935.8  409.61
  4955.8  409.64  4965.8  406.40  4973.8  404.30  4974.0  403.80  4977.5  403.80
  4977.8  404.30  4985.8  405.20  5005.8  405.45  5015.8  406.87  5025.8  407.34
  5036.6  407.19  5065.8  407.14  5125.8  408.87  5195.8  408.98  5225.9  409.42
  5265.9  409.32  5335.9  410.67  5367.5  410.78  5445.9  412.43  5468.8  412.58
#Mann=5,-1,0
  4612.8    0.05       0  4973.8    0.04       0  4977.8    0.05       0
  5036.6    0.12       0  5367.5    0.05       0
Bank Sta=4973.8,4977.8
Exp/Cntr=0.3,0.1

Type RM Length L Ch R = 1,1170,312,312,312
BEGIN DESCRIPTION:
Clear Creek T 32 4.0
END DESCRIPTION:
XS GIS Cut Line= 3
      2736658.32      6799828.72      2736660.58      6800160.11
      2736656.39      6800531.79
#Sta/Elev= 30
  4668.6  413.78  4680.9  413.52  4730.9  413.33  4770.9  411.46  4790.9  411.01
  4820.9  409.51  4830.9  409.98  4850.9  408.86  4940.9  407.23  4970.9  405.49
  4978.9  403.48  4979.1  402.98  4982.6  402.98  4982.9  403.48  4990.9  405.82
  4997.9  406.91  5002.9  406.91  5010.9  406.29  5030.9  406.79  5050.9  406.94
  5090.9  407.98  5140.9  408.11  5160.9  408.48  5170.9  407.90  5179.8  408.15
  5180.1  408.16  5200.9  408.02  5240.9  408.79  5310.9  411.07  5371.7  411.76
#Mann=5,-1,0
  4668.6    0.05       0  4978.9    0.04       0  4982.9    0.05       0
  5179.8    0.12       0  5180.1    0.05       0
Bank Sta=4978.9,4982.9
Exp/Cntr=0.3,0.1

Type RM Length L Ch R = 1,858,287,287,287
BEGIN DESCRIPTION:
Clear Creek T 32 3.0
END DESCRIPTION:
XS GIS Cut Line= 3
      2736382.68      6799791.09      2736376.00      6800161.00
      2736376.00      6800911.03
#Sta/Elev= 30
  4629.6  412.81  4723.6  412.32  4759.5  411.55  4769.5  412.05  4809.5  409.71
  4829.5  409.28  4889.6  406.10  4929.6  405.04  4949.6  405.65  4960.6  405.09
  4979.6  405.59  5002.1  405.34  5007.6  403.69  5007.8  403.19  5011.3  403.19
  5011.6  403.69  5019.6  403.92  5029.6  405.27  5039.6  405.65  5102.9  406.88
  5149.6  408.66  5199.6  409.73  5329.6  409.22  5429.6  411.49  5509.6  412.26
  5679.6  414.99  5689.6  415.29  5709.6  416.98  5739.6  418.72  5749.6  418.63
#Mann=5,-1,0
  4629.6    0.05       0  4960.6    0.12       0  5007.6    0.07       0
  5011.6    0.12       0  5102.9    0.05       0
Bank Sta=5007.6,5011.6
Exp/Cntr=0.3,0.1

Type RM Length L Ch R = 1,571,417,417,417
BEGIN DESCRIPTION:
Clear Creek T 32 2.0
END DESCRIPTION:
XS GIS Cut Line= 3
      2736175.99      6799861.03      2736126.00      6800061.00
      2736126.00      6800560.97
#Sta/Elev= 30
  4793.6  413.71  4811.6  413.37  4824.5  412.56  4845.1  412.54  4852.8  411.47
  4899.2  408.76  4907.0  408.48  4917.3  408.92  4935.3  406.88  4968.9  405.36
  4997.1  403.26  5002.2  403.26  5009.7  401.97  5027.7  401.58  5028.0  401.08
  5031.5  401.08  5031.7  401.58  5039.7  403.00  5059.7  404.75  5099.7  404.81
  5136.0  405.89  5169.7  407.18  5229.7  408.62  5289.7  408.39  5419.7  411.13
  5469.7  411.34  5479.7  411.91  5489.7  413.55  5497.2  416.60  5499.7  416.60
#Mann=5,-1,0
  4793.6    0.05       0  4968.9    0.12       0  5027.7    0.07       0
  5031.7    0.12       0  5136.0    0.05       0
Bank Sta=5027.7,5031.7
Exp/Cntr=0.3,0.1

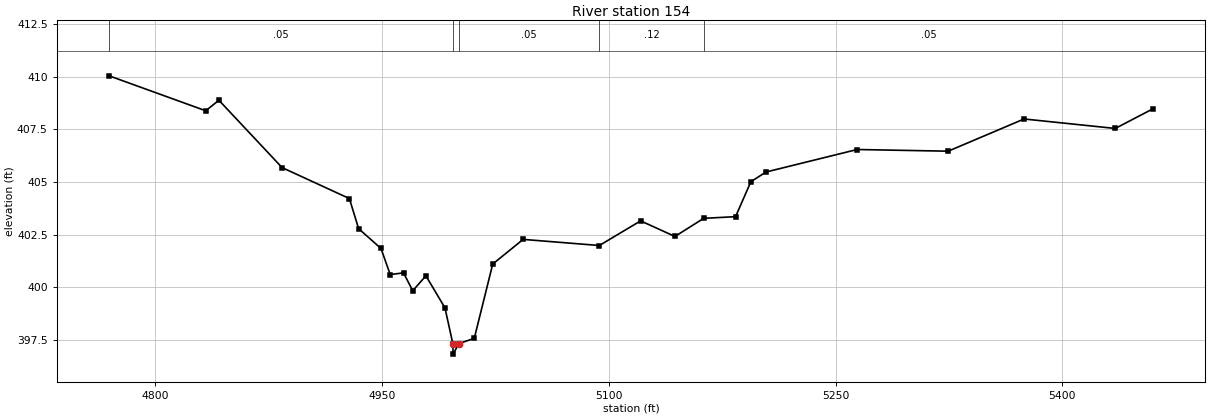
Type RM Length L Ch R = 1,154,0,0,0
BEGIN DESCRIPTION:
Clear Creek T 32 1.0
END DESCRIPTION:
XS GIS Cut Line= 3
      2735934.39      6799699.06      2735802.28      6799887.83
      2735760.24      6800346.00
#Sta/Elev= 30
  4769.6  410.04  4833.5  408.38  4842.2  408.88  4884.0  405.68  4928.5  404.21
  4934.6  402.78  4949.4  401.84  4955.5  400.60  4964.3  400.68  4970.4  399.83
  4979.1  400.54  4991.7  399.02  4996.9  397.32  4997.1  396.82  5000.9  397.32
  5011.1  397.57  5023.3  401.10  5043.4  402.27  5093.8  401.98  5121.1  403.15
  5143.8  402.41  5162.8  403.27  5183.9  403.35  5194.0  405.01  5204.0  405.47
  5264.3  406.54  5324.5  406.46  5374.7  407.99  5435.0  407.54  5460.1  408.48
#Mann=5,-1,0
  4769.6    0.05       0  4996.9    0.04       0  5000.9    0.05       0
  5093.8    0.12       0  5162.8    0.05       0
Bank Sta=4996.9,5000.9
Exp/Cntr=0.3,0.1

Chan Stop Cuts=-1