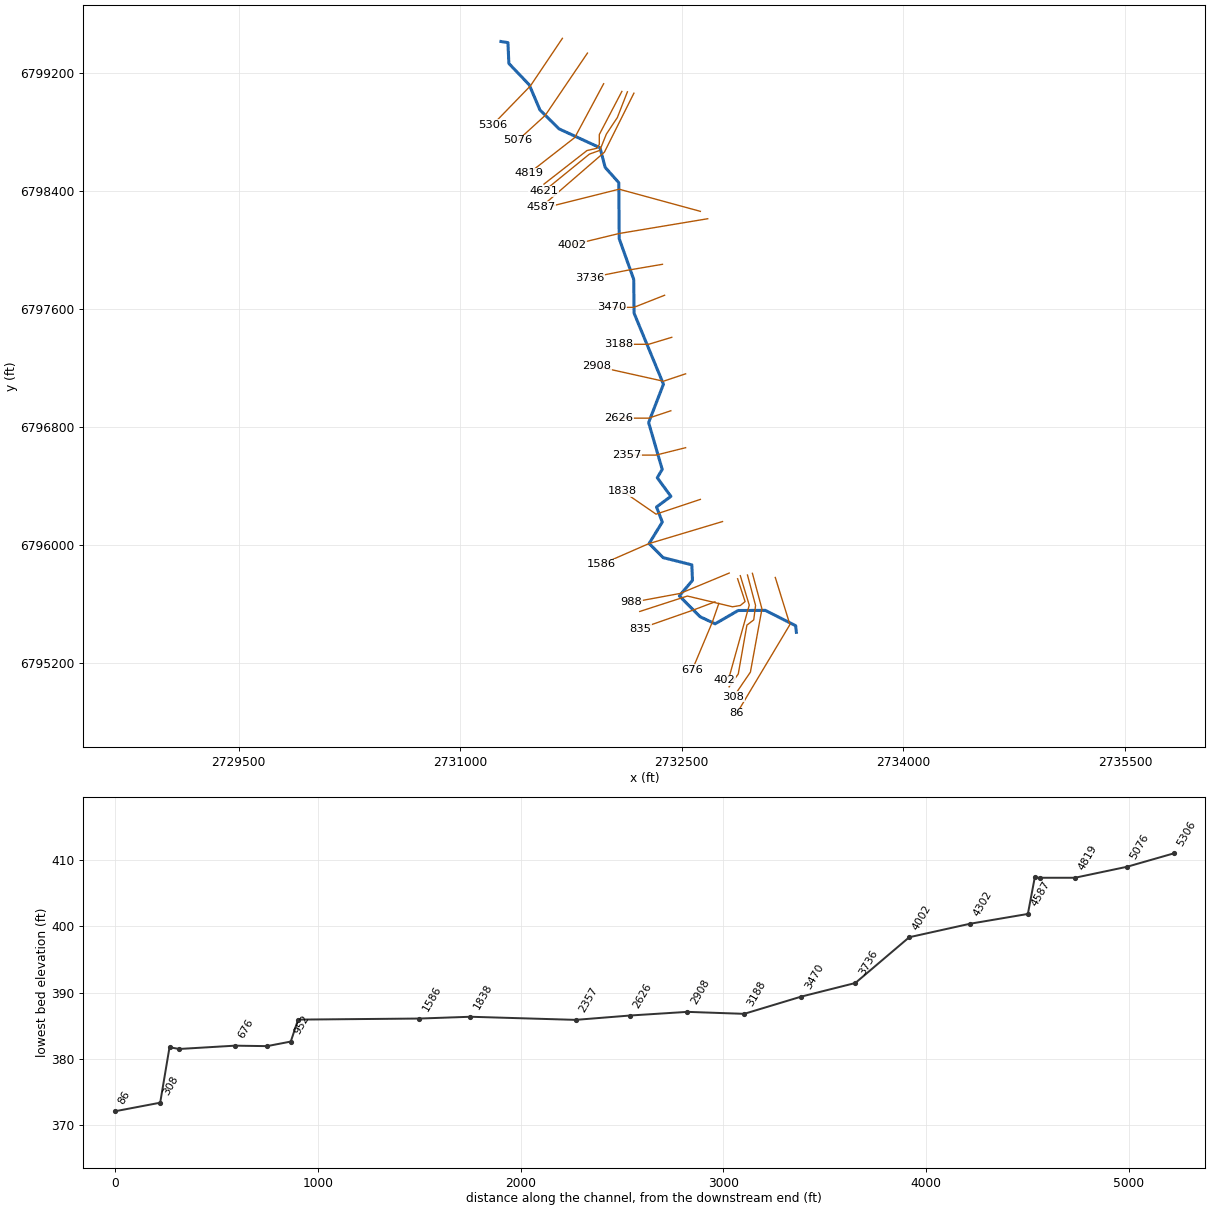
--- Clear Creek T 33.prj (project) ---

Proj Title=Clear Creek T 33 Base Level Engineering
Current Plan=p01
Default Exp/Contr=0.3,0.1
English Units
Geom File=g01
Flow File=f01
Plan File=p01
BEGIN DESCRIPTION:
Clear Creek T 33
END DESCRIPTION:

--- Clear Creek T 33.p01 (plan) ---

Plan Title=Multiple Run
Short Identifier=Multiple
Geom File=g01
Flow File=f01
Subcritical Flow
K Sum by GR= 0
Std Step Tol= 0.01
Critical Tol= 0.01
Num of Std Step Trials= 20
Max Error Tol= 0.3
Flow Tol Ratio= 0.001
Split Flow NTrial= 30
Split Flow Tol= 0.02
Split Flow Ratio= 0.02
Log Output Level= 0
Friction Slope Method= 1
Unsteady Friction Slope Method= 2
Unsteady Bridges Friction Slope Method= 1
Parabolic Critical Depth
Global Vel Dist=  1 , 1 , 1
Global Log Level= 0
CheckData=True
Encroach Param= -1, 0, 0, 0
BEGIN DESCRIPTION:
Multiple Run
END DESCRIPTION:

--- Clear Creek T 33.f01 (steady flow) ---

Flow Title=Multiple
Number of Profiles=7
Profile Names=10-year,25-year,50-year,1pct_min,100-year,1pct_plu,500-year
River Rch & RM= Clear Creek T 33,Reach-1,5306
     228     286     330     189     378     754     495
River Rch & RM= Clear Creek T 33,Reach-1,1586
     324     417     488     284     567    1131     763
Boundary for River Rch & Prof#=Clear Creek T 33,Reach-1,1
Up Type=0
Dn Type=3
Dn Slope=0.005
Boundary for River Rch & Prof#=Clear Creek T 33,Reach-1,2
Up Type=0
Dn Type=3
Dn Slope=0.005
Boundary for River Rch & Prof#=Clear Creek T 33,Reach-1,3
Up Type=0
Dn Type=3
Dn Slope=0.005
Boundary for River Rch & Prof#=Clear Creek T 33,Reach-1,4
Up Type=0
Dn Type=3
Dn Slope=0.005
Boundary for River Rch & Prof#=Clear Creek T 33,Reach-1,5
Up Type=0
Dn Type=3
Dn Slope=0.005
Boundary for River Rch & Prof#=Clear Creek T 33,Reach-1,6
Up Type=0
Dn Type=3
Dn Slope=0.005
Boundary for River Rch & Prof#=Clear Creek T 33,Reach-1,7
Up Type=0
Dn Type=3
Dn Slope=0.005

--- Clear Creek T 33.g01 (geometry) ---

Geom Title=Existing Conditions

River Reach=Clear Creek T 33,Reach-1
Reach XY= 30
      2731276.00      6799411.00      2731323.28      6799403.29
      2731329.54      6799262.47      2731467.86      6799117.06
      2731539.62      6798947.78      2731669.94      6798819.14
      2731946.57      6798691.42      2731981.54      6798558.58
      2732073.93      6798455.14      2732076.52      6798076.22
      2732174.78      6797800.50      2732177.20      6797571.50
      2732376.10      6797090.90      2732275.71      6796831.18
      2732367.71      6796514.21      2732334.01      6796457.67
      2732426.37      6796331.37      2732329.10      6796259.56
      2732368.30      6796157.59      2732279.27      6796012.34
      2732373.70      6795916.79      2732568.24      6795867.80
      2732572.52      6795762.50      2732483.60      6795657.66
      2732623.71      6795516.81      2732726.00      6795468.50
      2732881.93      6795558.76      2733065.50      6795559.80
      2733271.10      6795455.72      2733276.00      6795411.00

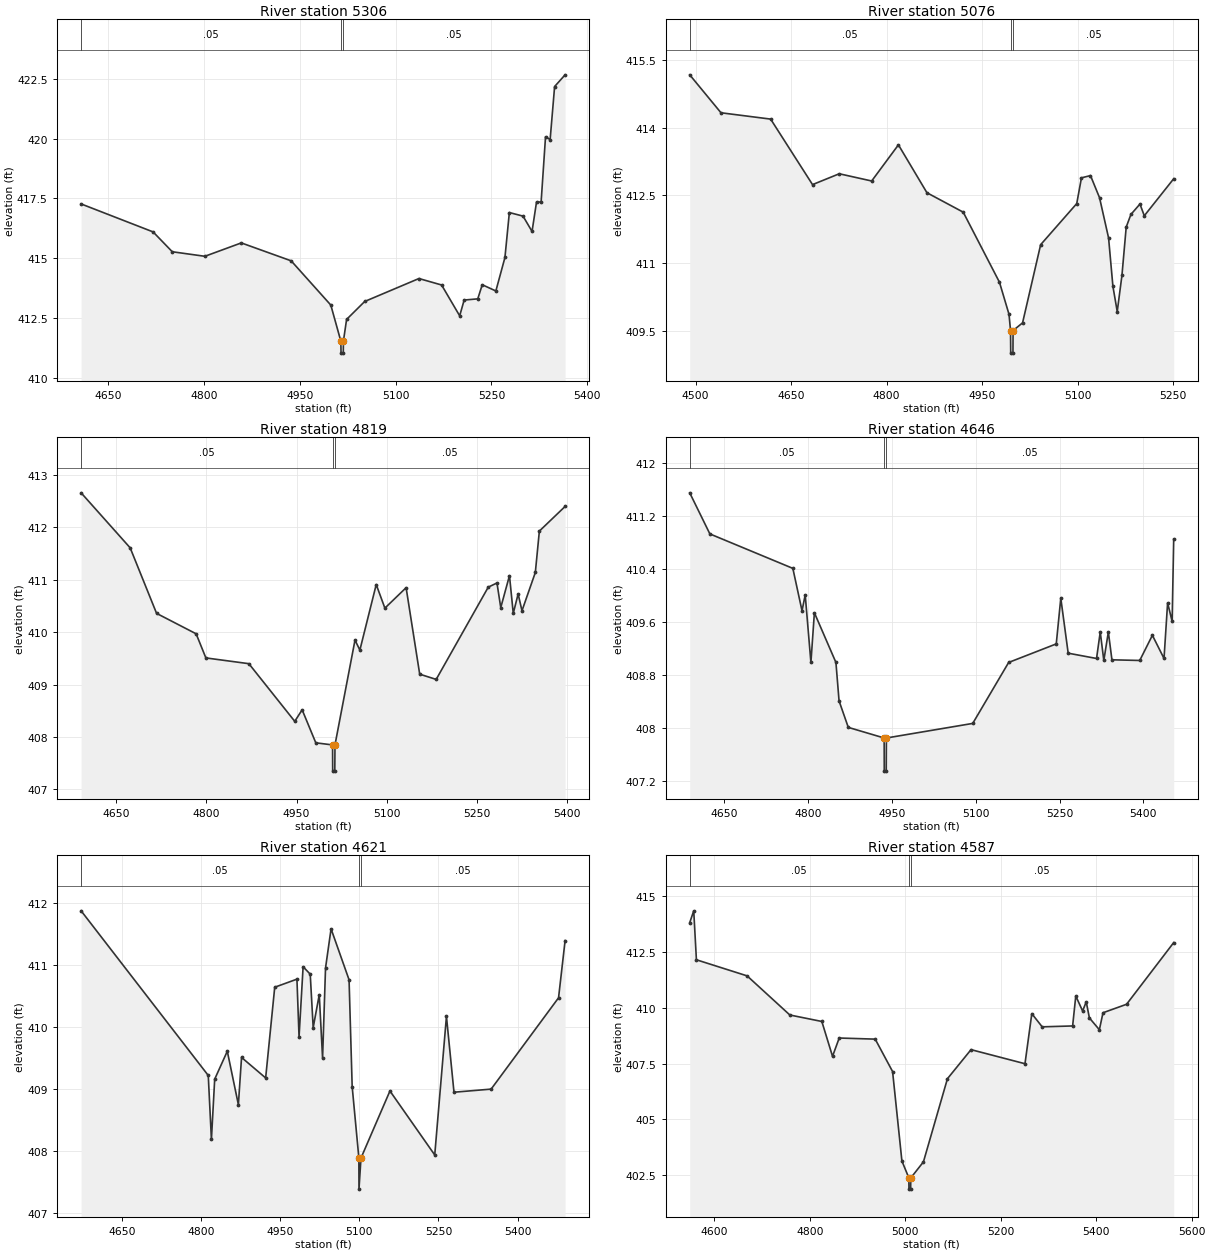
Type RM Length L Ch R = 1,5306,230,230,230
BEGIN DESCRIPTION:
Clear Creek T 33 17.0
END DESCRIPTION:
XS GIS Cut Line= 3
      2731691.90      6799432.29      2731476.00      6799111.00
      2731218.45      6798845.33
#Sta/Elev= 30
  4608.1  417.27  4720.7  416.10  4750.7  415.27  4801.7  415.08  4858.7  415.64
  4936.7  414.89  4998.7  413.04  5014.4  411.53  5014.7  411.03  5018.2  411.03
  5018.4  411.53  5023.4  412.44  5051.7  413.19  5136.6  414.15  5172.0  413.88
  5200.3  412.59  5207.3  413.25  5228.6  413.30  5235.6  413.89  5256.9  413.63
  5271.1  415.03  5278.0  416.91  5299.4  416.76  5313.5  416.12  5320.5  417.35
  5327.7  417.35  5334.6  420.08  5341.8  419.96  5348.8  422.18  5365.2  422.67
#Mann=3,-1,0
  4608.1    0.05       0  5014.4    0.04       0  5018.4    0.05       0
Bank Sta=5014.4,5018.4
Exp/Cntr=0.3,0.1

Type RM Length L Ch R = 1,5076,257,257,257
BEGIN DESCRIPTION:
Clear Creek T 33 16.0
END DESCRIPTION:
XS GIS Cut Line= 3
      2731861.53      6799332.31      2731576.00      6798911.00
      2731390.51      6798741.53
#Sta/Elev= 30
  4490.8  415.17  4539.9  414.33  4617.9  414.19  4683.7  412.74  4725.7  412.98
  4776.6  412.82  4818.6  413.62  4863.4  412.56  4920.4  412.13  4977.3  410.58
  4992.3  409.87  4994.7  409.51  4995.0  409.01  4998.5  409.01  4998.7  409.51
  5013.6  409.68  5042.0  411.41  5098.7  412.32  5106.1  412.89  5120.3  412.94
  5134.5  412.45  5148.7  411.56  5155.5  410.49  5162.3  409.93  5169.7  410.73
  5176.4  411.80  5183.8  412.08  5198.0  412.31  5204.8  412.05  5251.0  412.87
#Mann=3,-1,0
  4490.8    0.05       0  4994.7    0.04       0  4998.7    0.05       0
Bank Sta=4994.7,4998.7
Exp/Cntr=0.3,0.1

Type RM Length L Ch R = 1,4819,173,173,173
BEGIN DESCRIPTION:
Clear Creek T 33 15.0
END DESCRIPTION:
XS GIS Cut Line= 3
      2731971.21      6799124.90      2731776.00      6798761.00
      2731466.95      6798519.94
#Sta/Elev= 30
  4591.6  412.66  4673.2  411.61  4717.1  410.36  4782.9  409.97  4799.1  409.51
  4870.6  409.40  4946.9  408.30  4959.2  408.52  4981.9  407.89  5009.8  407.85
  5010.0  407.35  5013.5  407.35  5013.8  407.85  5047.1  409.85  5055.2  409.66
  5082.4  410.91  5096.8  410.46  5132.1  410.85  5154.7  409.20  5182.1  409.10
  5268.7  410.86  5283.2  410.94  5289.5  410.47  5304.0  411.08  5310.3  410.36
  5318.4  410.73  5324.8  410.41  5347.0  411.14  5353.7  411.93  5396.5  412.40
#Mann=3,-1,0
  4591.6    0.05       0  5009.8    0.05       0  5013.8    0.05       0
Bank Sta=5009.8,5013.8
Exp/Cntr=0.3,0.1

Type RM Length L Ch R = 1,4646,25,25,25
BEGIN DESCRIPTION:
Mapping XS 7bdb2f79
END DESCRIPTION:
XS GIS Cut Line= 6
      2732094.54      6799072.92      2731941.81      6798780.99
      2731941.91      6798714.32      2731924.88      6798687.94
      2731858.31      6798672.52      2731567.28      6798445.44
#Sta/Elev= 30
  4589.1  411.55  4625.1  410.93  4773.4  410.41  4789.8  409.77  4795.5  410.01
  4805.7  408.99  4811.9  409.74  4850.4  408.99  4856.0  408.41  4872.5  408.01
  4936.6  407.85  4936.8  407.35  4940.3  407.35  4940.6  407.85  5094.9  408.07
  5159.1  408.99  5244.2  409.27  5252.3  409.96  5265.5  409.13  5316.2  409.05
  5322.8  409.45  5329.2  409.02  5337.3  409.45  5343.7  409.03  5393.4  409.02
  5416.0  409.40  5436.8  409.05  5443.2  409.89  5451.3  409.61  5454.1  410.85
#Mann=3,-1,0
  4589.1    0.05       0  4936.6    0.05       0  4940.6    0.05       0
Bank Sta=4936.6,4940.6
Exp/Cntr=0.3,0.1

Type RM Length L Ch R = 1,4621,34,34,34
BEGIN DESCRIPTION:
Mapping XS 5e9bc8c9
END DESCRIPTION:
XS GIS Cut Line= 6
      2732132.12      6799070.35      2732064.13      6798896.43
      2731989.55      6798783.84      2731945.07      6798673.70
      2731875.05      6798648.67      2731564.39      6798395.75
#Sta/Elev= 30
  4572.8  411.87  4813.8  409.22  4819.8  408.19  4826.0  409.16  4849.9  409.61
  4870.9  408.75  4876.9  409.51  4922.6  409.18  4939.8  410.64  4981.9  410.77
  4985.9  409.84  4993.6  410.97  5007.1  410.85  5012.7  409.99  5024.2  410.52
  5030.5  409.50  5036.1  410.95  5046.6  411.58  5080.7  410.76  5086.6  409.04
  5099.3  407.89  5099.5  407.39  5103.3  407.89  5158.2  408.97  5243.1  407.94
  5265.3  410.17  5279.6  408.95  5350.0  409.00  5477.8  410.47  5490.2  411.39
#Mann=3,-1,0
  4572.8    0.05       0  5099.3    0.05       0  5103.3    0.05       0
Bank Sta=5099.3,5103.3
Exp/Cntr=0.3,0.1

Type RM Length L Ch R = 1,4587,285,285,285
BEGIN DESCRIPTION:
Clear Creek T 33 14.0
END DESCRIPTION:
XS GIS Cut Line= 3
      2732176.01      6799061.02      2731976.00      6798661.00
      2731547.74      6798290.22
#Sta/Elev= 30
  4548.7  413.80  4557.1  414.33  4562.7  412.14  4668.9  411.42  4758.4  409.67
  4825.4  409.38  4847.8  407.82  4861.8  408.64  4937.2  408.59  4973.6  407.14
  4993.1  403.14  5007.7  402.38  5007.9  401.88  5011.4  401.88  5011.7  402.38
  5038.2  403.10  5088.5  406.82  5137.9  408.12  5250.9  407.49  5265.2  409.73
  5286.9  409.14  5350.7  409.18  5357.3  410.52  5371.6  409.85  5379.2  410.26
  5385.8  409.54  5406.7  409.01  5414.3  409.77  5463.7  410.15  5562.4  412.91
#Mann=3,-1,0
  4548.7    0.05       0  5007.7    0.05       0  5011.7    0.05       0
Bank Sta=5007.7,5011.7
Exp/Cntr=0.3,0.1

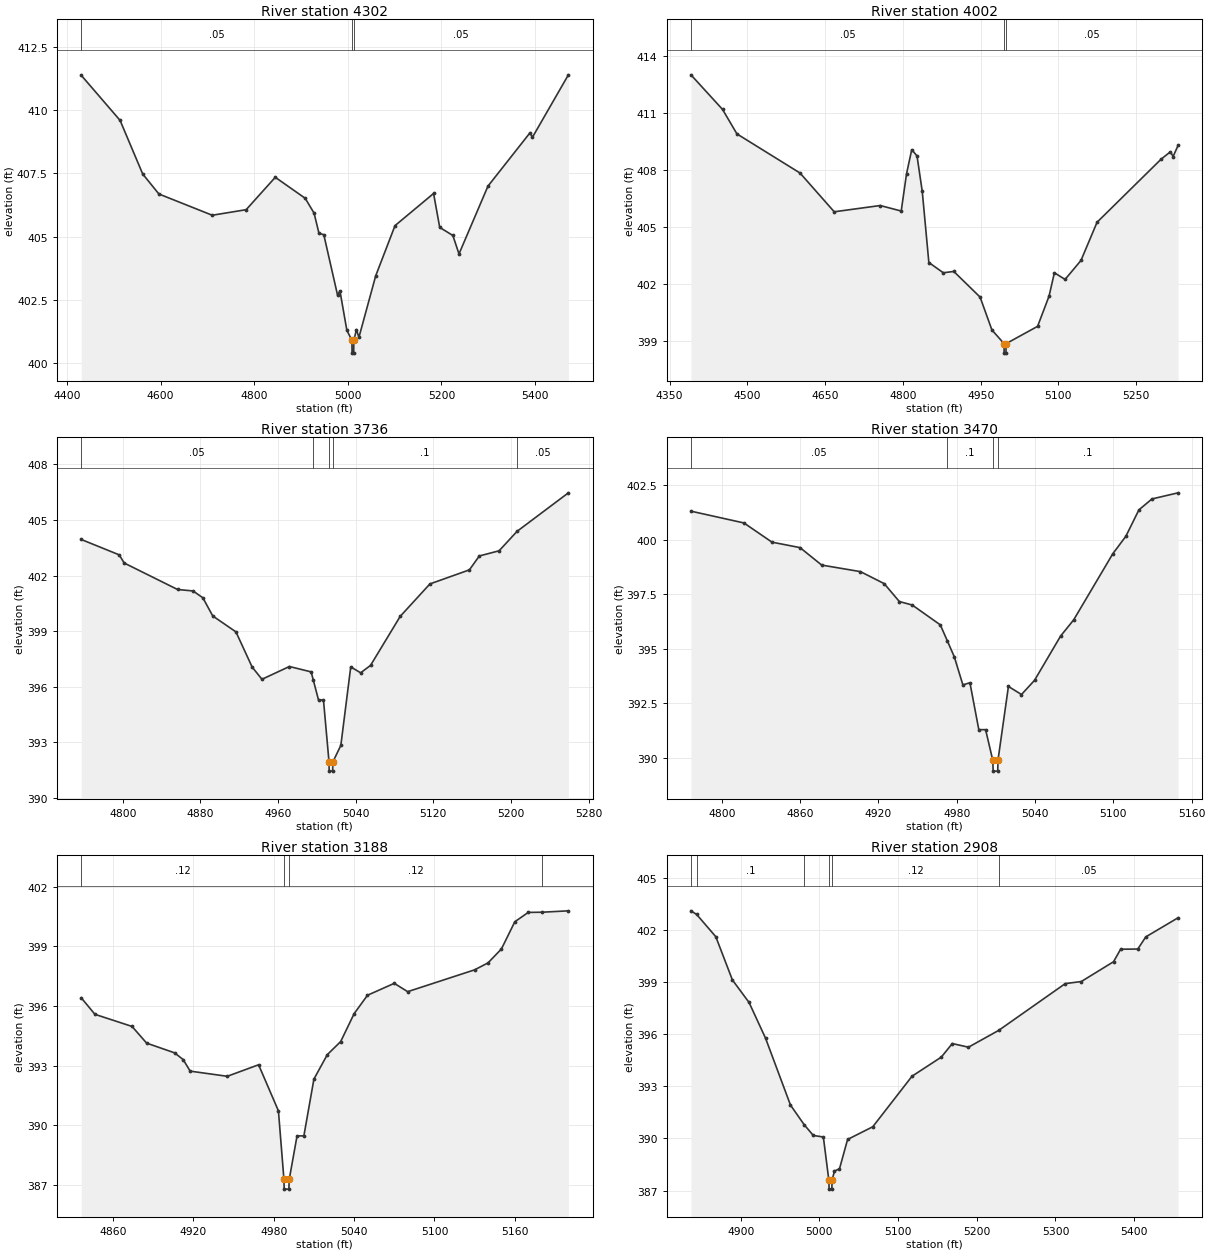
Type RM Length L Ch R = 1,4302,300,300,300
BEGIN DESCRIPTION:
Clear Creek T 33 13.0
END DESCRIPTION:
XS GIS Cut Line= 3
      2732626.02      6798260.99      2732076.00      6798411.00
      2731619.21      6798296.62
#Sta/Elev= 30
  4430.3  411.38  4513.2  409.60  4561.6  407.48  4596.2  406.69  4710.2  405.85
  4782.7  406.07  4844.9  407.35  4908.9  406.52  4927.9  405.93  4938.2  405.14
  4948.6  405.08  4978.0  402.69  4983.1  402.86  4997.8  401.31  5008.7  400.90
  5009.0  400.40  5012.5  400.40  5012.7  400.90  5018.4  401.33  5023.6  401.02
  5059.6  403.46  5100.8  405.44  5183.2  406.71  5196.3  405.37  5224.4  405.05
  5237.5  404.32  5299.4  407.00  5389.3  409.11  5394.4  408.93  5471.3  411.40
#Mann=3,-1,0
  4430.3    0.05       0  5008.7    0.04       0  5012.7    0.05       0
Bank Sta=5008.7,5012.7
Exp/Cntr=0.3,0.1

Type RM Length L Ch R = 1,4002,266,266,266
BEGIN DESCRIPTION:
Clear Creek T 33 12.0
END DESCRIPTION:
XS GIS Cut Line= 3
      2732676.03      6798211.01      2732076.00      6798111.00
      2731754.19      6798033.13
#Sta/Elev= 30
  4391.3  413.01  4452.2  411.19  4480.0  409.90  4601.7  407.84  4667.6  405.80
  4756.3  406.13  4796.8  405.84  4807.0  407.79  4817.1  409.07  4827.3  408.74
  4837.4  406.87  4850.1  403.13  4878.0  402.59  4898.2  402.66  4948.9  401.31
  4971.7  399.58  4995.1  398.86  4995.3  398.36  4998.8  398.36  4999.1  398.86
  5059.8  399.77  5081.9  401.36  5092.2  402.59  5112.8  402.24  5143.5  403.24
  5174.5  405.25  5298.0  408.57  5316.0  408.96  5321.1  408.71  5330.7  409.29
#Mann=3,-1,0
  4391.3    0.05       0  4995.1    0.04       0  4999.1    0.05       0
Bank Sta=4995.1,4999.1
Exp/Cntr=0.3,0.1

Type RM Length L Ch R = 1,3736,266,266,266
BEGIN DESCRIPTION:
Clear Creek T 33 11.0
END DESCRIPTION:
XS GIS Cut Line= 3
      2732369.56      6797902.57      2732126.00      6797861.00
      2731876.03      6797811.01
#Sta/Elev= 30
  4757.2  403.95  4796.3  403.12  4801.4  402.68  4856.4  401.25  4872.4  401.17
  4882.5  400.80  4892.7  399.82  4916.6  398.96  4933.3  397.06  4943.4  396.40
  4971.7  397.09  4994.1  396.80  4996.3  396.36  5001.7  395.28  5006.8  395.28
  5012.5  391.94  5012.7  391.44  5016.2  391.44  5016.5  391.94  5024.7  392.83
  5034.9  397.07  5045.1  396.75  5055.3  397.15  5085.9  399.80  5116.5  401.55
  5157.2  402.31  5167.4  403.06  5187.8  403.34  5206.3  404.39  5259.2  406.47
#Mann=5,-1,0
  4757.2    0.05       0  4996.3     0.1       0  5012.5    0.07       0
  5016.5     0.1       0  5206.3    0.05       0
Bank Sta=5012.5,5016.5
Exp/Cntr=0.3,0.1

Type RM Length L Ch R = 1,3470,282,282,282
BEGIN DESCRIPTION:
Clear Creek T 33 10.0
END DESCRIPTION:
XS GIS Cut Line= 3
      2732383.74      6797692.94      2732176.00      6797611.00
      2732026.02      6797611.00
#Sta/Elev= 30
  4776.3  401.30  4816.9  400.76  4838.4  399.88  4859.9  399.63  4876.5  398.83
  4906.2  398.53  4924.4  397.98  4936.0  397.16  4945.9  397.00  4967.4  396.09
  4972.7  395.37  4978.1  394.63  4984.7  393.34  4990.1  393.44  4996.9  391.29
  5002.1  391.29  5007.6  389.89  5007.9  389.39  5011.4  389.39  5011.6  389.89
  5019.6  393.27  5029.6  392.90  5039.6  393.55  5059.6  395.58  5069.6  396.32
  5099.6  399.35  5109.6  400.15  5119.6  401.36  5129.6  401.86  5149.6  402.14
#Mann=4,-1,0
  4776.3    0.05       0  4972.7     0.1       0  5007.6    0.07       0
  5011.6     0.1       0
Bank Sta=5007.6,5011.6
Exp/Cntr=0.3,0.1

Type RM Length L Ch R = 1,3188,280,280,280
BEGIN DESCRIPTION:
Clear Creek T 33 9.0
END DESCRIPTION:
XS GIS Cut Line= 3
      2732432.71      6797408.34      2732276.00      6797361.00
      2732076.00      6797361.00
#Sta/Elev= 30
  4836.3  396.41  4846.5  395.58  4874.2  394.97  4885.1  394.13  4906.0  393.64
  4912.4  393.30  4917.6  392.72  4945.3  392.46  4968.7  393.04  4983.5  390.72
  4987.6  387.28  4987.8  386.78  4991.3  386.78  4991.6  387.28  4997.4  389.46
  5002.5  389.46  5010.0  392.32  5020.0  393.55  5030.0  394.21  5040.0  395.61
  5050.0  396.54  5070.0  397.14  5080.0  396.72  5130.0  397.82  5140.0  398.17
  5150.0  398.87  5160.0  400.24  5170.0  400.71  5180.3  400.72  5200.0  400.79
#Mann=4,-1,0
  4836.3    0.12       0  4987.6    0.07       0  4991.6    0.12       0
  5180.3    0.05       0
Bank Sta=4987.6,4991.6
Exp/Cntr=0.3,0.1

Type RM Length L Ch R = 1,2908,282,282,282
BEGIN DESCRIPTION:
Clear Creek T 33 8.0
END DESCRIPTION:
XS GIS Cut Line= 3
      2732525.98      6797160.99      2732376.00      6797111.00
      2731925.97      6797211.01
#Sta/Elev= 30
  4836.7  403.10  4844.0  402.89  4868.3  401.61  4889.4  399.12  4910.5  397.83
  4931.5  395.77  4963.2  391.92  4980.6  390.79  4992.2  390.17  5005.0  390.08
  5012.0  387.58  5012.3  387.08  5015.8  387.08  5016.0  387.58  5019.1  388.12
  5025.5  388.25  5035.8  389.94  5067.8  390.67  5117.7  393.58  5154.9  394.68
  5168.9  395.46  5189.4  395.25  5227.9  396.22  5312.4  398.91  5332.8  399.03
  5373.8  400.17  5382.8  400.89  5404.6  400.90  5414.8  401.60  5455.8  402.70
#Mann=6,-1,0
  4836.7    0.05       0  4844.0     0.1       0  4980.6    0.12       0
  5012.0    0.07       0  5016.0    0.12       0  5227.9    0.05       0
Bank Sta=5012,5016
Exp/Cntr=0.3,0.1

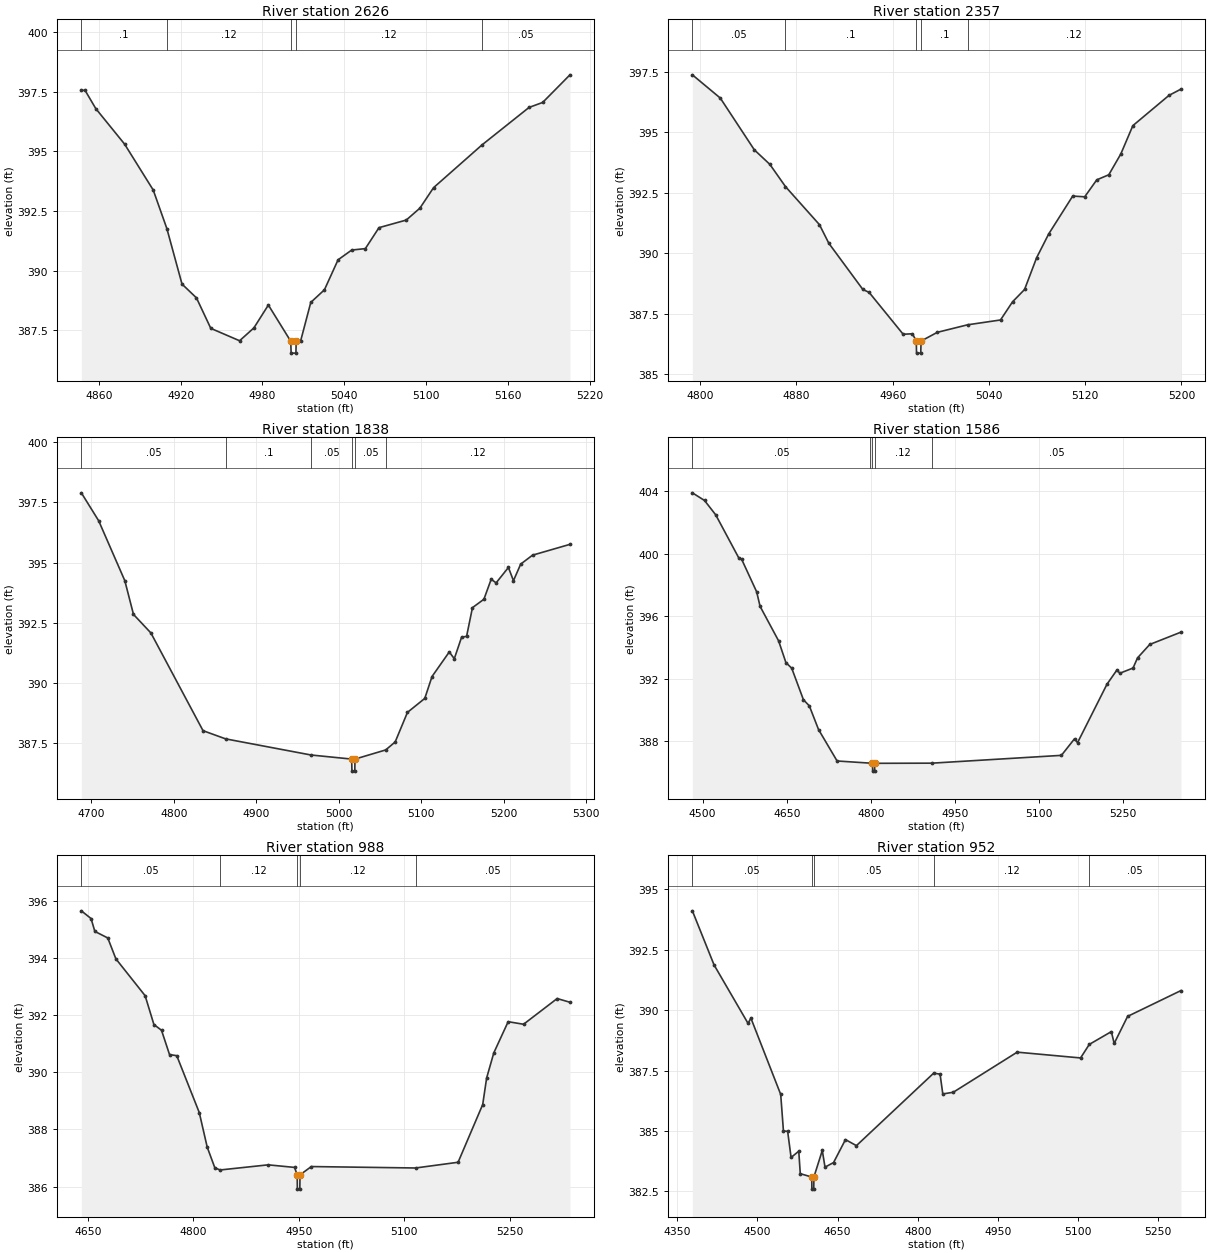
Type RM Length L Ch R = 1,2626,269,269,269
BEGIN DESCRIPTION:
Clear Creek T 33 7.0
END DESCRIPTION:
XS GIS Cut Line= 3
      2732426.04      6796911.01      2732276.00      6796861.00
      2732075.96      6796861.00
#Sta/Elev= 30
  4847.2  397.57  4849.9  397.57  4857.8  396.80  4878.9  395.31  4899.9  393.38
  4909.9  391.76  4921.0  389.43  4931.6  388.85  4942.1  387.57  4963.2  387.05
  4973.7  387.59  4984.3  388.55  5000.7  387.03  5001.0  386.53  5004.5  386.53
  5004.7  387.03  5007.9  387.03  5015.4  388.66  5025.4  389.19  5035.4  390.45
  5045.4  390.86  5055.4  390.92  5065.4  391.80  5085.4  392.12  5095.4  392.62
  5105.4  393.48  5141.0  395.28  5175.4  396.85  5185.4  397.06  5205.4  398.22
#Mann=5,-1,0
  4847.2     0.1       0  4909.9    0.12       0  5000.7    0.07       0
  5004.7    0.12       0  5141.0    0.05       0
Bank Sta=5000.7,5004.7
Exp/Cntr=0.3,0.1

Type RM Length L Ch R = 1,2357,519,519,519
BEGIN DESCRIPTION:
Clear Creek T 33 6.0
END DESCRIPTION:
XS GIS Cut Line= 3
      2732525.98      6796660.99      2732326.00      6796611.00
      2732126.03      6796611.00
#Sta/Elev= 30
  4793.5  397.37  4816.7  396.41  4845.0  394.27  4857.9  393.67  4870.9  392.75
  4899.1  391.18  4906.9  390.41  4935.2  388.50  4940.4  388.38  4968.7  386.65
  4976.4  386.67  4979.6  386.37  4979.8  385.87  4983.3  385.87  4983.6  386.37
  4997.1  386.73  5022.2  387.04  5049.6  387.24  5059.6  387.99  5069.6  388.50
  5079.6  389.81  5089.6  390.79  5109.6  392.36  5119.6  392.33  5129.6  393.03
  5139.6  393.24  5149.6  394.10  5159.6  395.27  5189.6  396.52  5199.6  396.78
#Mann=5,-1,0
  4793.5    0.05       0  4870.9     0.1       0  4979.6    0.07       0
  4983.6     0.1       0  5022.2    0.12       0
Bank Sta=4979.6,4983.6
Exp/Cntr=0.3,0.1

Type RM Length L Ch R = 1,1838,252,252,252
BEGIN DESCRIPTION:
Clear Creek T 33 5.0
END DESCRIPTION:
XS GIS Cut Line= 3
      2732625.96      6796310.99      2732326.00      6796211.00
      2732098.62      6796367.65
#Sta/Elev= 30
  4687.8  397.90  4708.8  396.74  4740.5  394.25  4751.0  392.85  4772.1  392.08
  4835.3  388.02  4862.7  387.68  4966.2  387.01  5015.5  386.84  5015.8  386.34
  5019.3  386.34  5019.5  386.84  5056.7  387.22  5068.2  387.55  5083.1  388.78
  5104.1  389.36  5112.9  390.27  5133.8  391.29  5139.9  391.01  5148.7  391.90
  5154.8  391.94  5161.9  393.13  5175.8  393.48  5184.6  394.31  5190.6  394.16
  5205.5  394.80  5211.6  394.25  5220.4  394.94  5234.7  395.31  5280.1  395.76
#Mann=6,-1,0
  4687.8    0.05       0  4862.7     0.1       0  4966.2    0.05       0
  5015.5    0.03       0  5019.5    0.05       0  5056.7    0.12       0
Bank Sta=5015.5,5019.5
Exp/Cntr=0.3,0.1

Type RM Length L Ch R = 1,1586,598,598,598
BEGIN DESCRIPTION:
Clear Creek T 33 4.0
END DESCRIPTION:
XS GIS Cut Line= 3
      2732775.97      6796160.99      2732276.00      6796011.00
      2731954.90      6795870.67
#Sta/Elev= 30
  4481.6  403.89  4503.3  403.40  4523.3  402.48  4564.2  399.74  4569.4  399.65
  4596.4  397.55  4602.5  396.62  4635.6  394.41  4648.6  393.02  4659.0  392.66
  4679.9  390.64  4690.4  390.25  4706.9  388.73  4740.0  386.72  4799.6  386.58
  4803.2  386.57  4803.5  386.07  4807.0  386.07  4807.2  386.57  4909.3  386.58
  5140.5  387.08  5163.9  388.14  5169.3  387.89  5221.8  391.63  5239.5  392.54
  5245.0  392.34  5268.4  392.67  5276.4  393.32  5298.2  394.18  5354.0  394.97
#Mann=5,-1,0
  4481.6    0.05       0  4799.6    0.12       0  4803.2    0.03       0
  4807.2    0.12       0  4909.3    0.05       0
Bank Sta=4803.2,4807.2
Exp/Cntr=0.3,0.1

Type RM Length L Ch R = 1,988,36,36,36
BEGIN DESCRIPTION:
Clear Creek T 33 3.0
END DESCRIPTION:
XS GIS Cut Line= 3
      2732821.31      6795812.28      2732489.44      6795674.32
      2732159.52      6795613.36
#Sta/Elev= 30
  4640.6  395.65  4654.4  395.38  4659.8  394.93  4678.2  394.70  4689.7  393.97
  4731.3  392.68  4743.8  391.67  4754.6  391.47  4766.0  390.62  4776.3  390.58
  4808.3  388.59  4819.6  387.38  4830.4  386.66  4837.8  386.58  4906.3  386.76
  4943.8  386.67  4947.6  386.41  4947.8  385.91  4951.3  385.91  4951.6  386.41
  4967.7  386.70  5115.9  386.65  5176.4  386.85  5211.4  388.87  5217.0  389.80
  5227.2  390.68  5247.6  391.77  5269.5  391.68  5317.3  392.58  5335.5  392.45
#Mann=5,-1,0
  4640.6    0.05       0  4837.8    0.12       0  4947.6    0.07       0
  4951.6    0.12       0  5115.9    0.05       0
Bank Sta=4947.6,4951.6
Exp/Cntr=0.3,0.1

Type RM Length L Ch R = 1,952,117,117,117
BEGIN DESCRIPTION:
Mapping XS b1d6cadd
END DESCRIPTION:
XS GIS Cut Line= 6
      2732878.12      6795773.84      2732928.86      6795619.13
      2732896.59      6795592.75      2732843.47      6795583.92
      2732538.13      6795656.68      2732215.45      6795552.10
#Sta/Elev= 30
  4378.2  394.11  4418.8  391.87  4482.4  389.45  4487.7  389.67  4543.5  386.51
  4548.6  385.00  4556.5  384.98  4562.9  383.90  4577.3  384.16  4580.1  383.23
  4601.6  383.09  4601.8  382.59  4605.3  382.59  4605.6  383.09  4621.3  384.19
  4626.4  383.50  4642.4  383.69  4664.7  384.64  4685.2  384.39  4829.7  387.39
  4841.7  387.35  4846.8  386.53  4866.4  386.60  4986.0  388.26  5104.6  388.02
  5120.9  388.58  5162.2  389.11  5167.5  388.62  5192.6  389.74  5292.5  390.81
#Mann=5,-1,0
  4378.2    0.05       0  4601.6    0.07       0  4605.6    0.05       0
  4829.7    0.12       0  5120.9    0.05       0
Bank Sta=4601.6,4605.6
Exp/Cntr=0.3,0.1

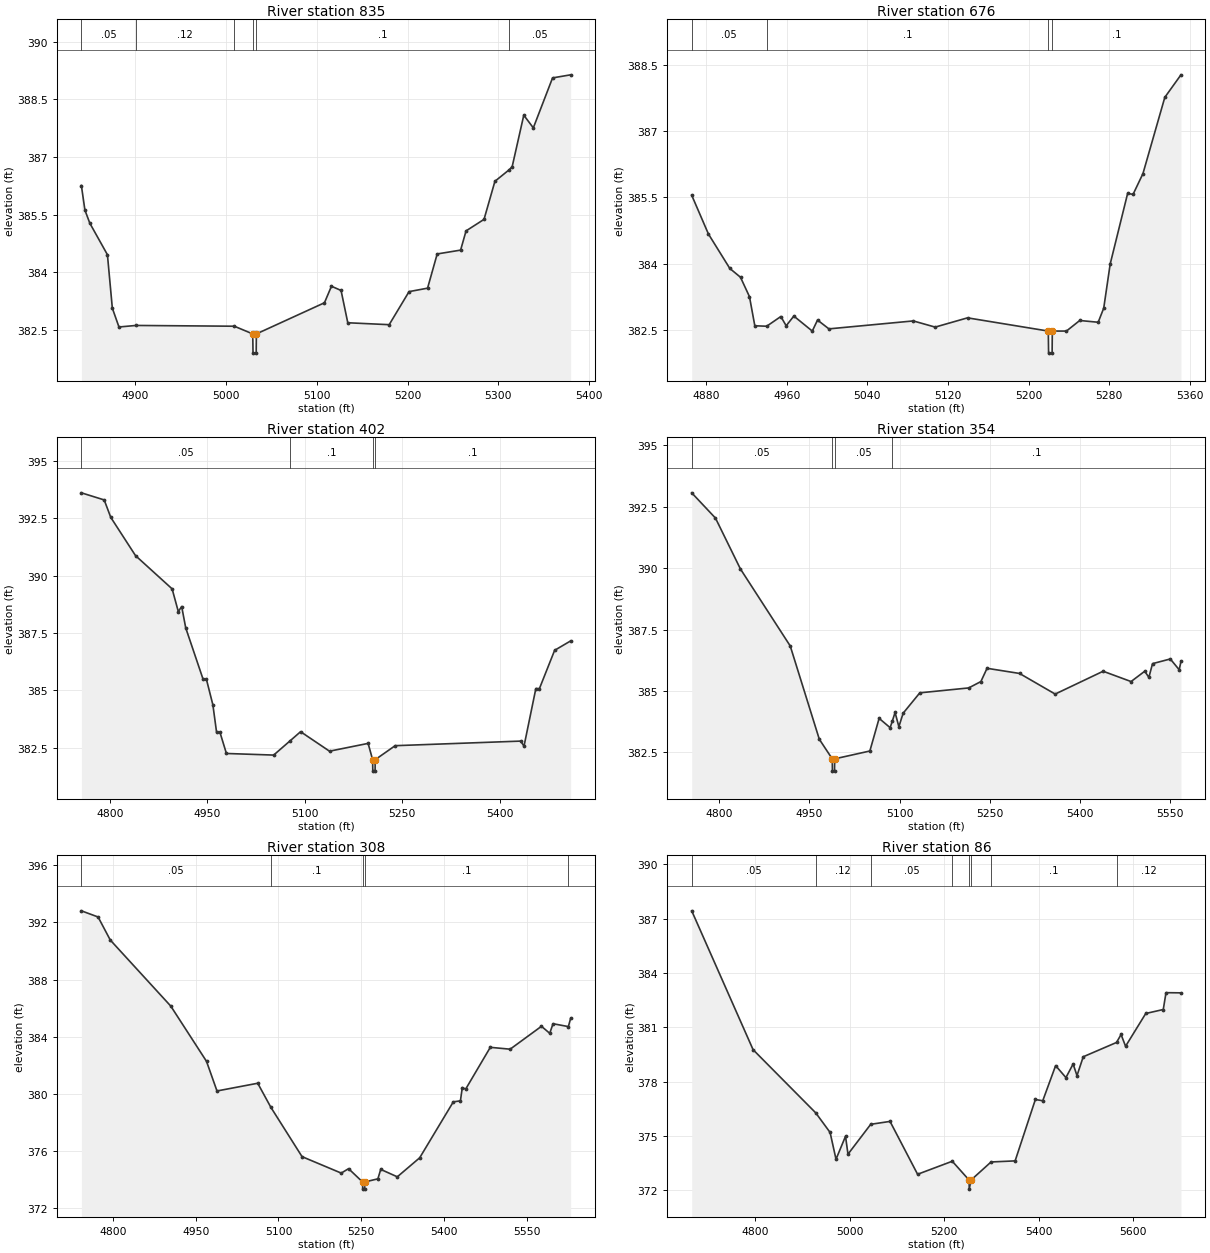
Type RM Length L Ch R = 1,835,159,159,159
BEGIN DESCRIPTION:
Clear Creek T 33 2.0
END DESCRIPTION:
XS GIS Cut Line= 3
      2732724.70      6795617.38      2732576.00      6795561.00
      2732217.24      6795435.85
#Sta/Elev= 30
  4840.7  386.26  4844.6  385.62  4850.0  385.28  4869.4  384.46  4874.8  383.07
  4882.1  382.58  4900.9  382.62  5009.2  382.60  5029.5  382.40  5029.8  381.90
  5033.3  381.90  5033.5  382.40  5108.5  383.21  5116.2  383.64  5126.8  383.53
  5134.2  382.69  5179.8  382.64  5201.7  383.50  5222.1  383.59  5232.7  384.48
  5258.5  384.58  5264.5  385.08  5284.3  385.38  5296.3  386.37  5312.0  386.67
  5315.3  386.75  5328.1  388.09  5338.6  387.76  5359.8  389.06  5379.7  389.14
#Mann=6,-1,0
  4840.7    0.05       0  4900.9    0.12       0  5009.2     0.1       0
  5029.5    0.07       0  5033.5     0.1       0  5312.0    0.05       0
Bank Sta=5029.5,5033.5
Exp/Cntr=0.3,0.1

Type RM Length L Ch R = 1,676,274,274,274
BEGIN DESCRIPTION:
Mapping XS 8ae5d7de
END DESCRIPTION:
XS GIS Cut Line= 3
      2732750.97      6795606.70      2732707.15      6795480.42
      2732570.93      6795156.24
#Sta/Elev= 30
  4865.8  385.55  4882.4  384.67  4903.6  383.89  4914.2  383.69  4923.1  383.25
  4928.4  382.59  4940.2  382.58  4954.2  382.80  4959.5  382.59  4967.1  382.81
  4985.4  382.47  4990.6  382.72  5001.9  382.52  5085.6  382.70  5107.3  382.56
  5139.4  382.77  5219.5  382.47  5219.8  381.97  5223.3  381.97  5223.5  382.47
  5237.5  382.47  5250.7  382.71  5269.0  382.67  5274.5  382.99  5280.9  383.99
  5298.2  385.59  5303.6  385.57  5313.4  386.04  5335.1  387.77  5351.1  388.28
#Mann=4,-1,0
  4865.8    0.05       0  4940.2     0.1       0  5219.5    0.07       0
  5223.5     0.1       0
Bank Sta=5219.5,5223.5
Exp/Cntr=0.3,0.1

Type RM Length L Ch R = 1,402,48,48,48
BEGIN DESCRIPTION:
Mapping XS e0972838
END DESCRIPTION:
XS GIS Cut Line= 4
      2732896.41      6795794.56      2732957.01      6795595.11
      2732824.04      6795119.20      2732786.91      6795085.70
#Sta/Elev= 30
  4756.4  393.61  4791.5  393.30  4801.6  392.54  4839.7  390.87  4896.0  389.42
  4905.5  388.43  4910.7  388.65  4916.9  387.72  4943.6  385.48  4948.8  385.47
  4958.7  384.36  4964.4  383.16  4969.6  383.16  4979.5  382.24  5052.2  382.17
  5077.4  382.79  5093.6  383.19  5138.1  382.34  5197.5  382.68  5204.4  381.97
  5204.7  381.47  5208.2  381.47  5208.4  381.97  5239.1  382.58  5432.1  382.78
  5437.3  382.56  5455.5  385.07  5461.0  385.07  5484.4  386.74  5509.0  387.15
#Mann=4,-1,0
  4756.4    0.05       0  5077.4     0.1       0  5204.4    0.04       0
  5208.4     0.1       0
Bank Sta=5204.4,5208.4
Exp/Cntr=0.3,0.1

Type RM Length L Ch R = 1,354,46,46,46
BEGIN DESCRIPTION:
Mapping XS 8270d66c
END DESCRIPTION:
XS GIS Cut Line= 6
      2732944.84      6795799.18      2732999.73      6795592.65
      2732987.31      6795495.38      2732941.07      6795459.66
      2732882.65      6795129.24      2732820.52      6795041.91
#Sta/Elev= 30
  4754.6  393.07  4794.1  392.04  4835.5  389.97  4918.3  386.83  4966.6  383.03
  4988.1  382.23  4988.4  381.73  4991.9  381.73  4992.1  382.23  5050.6  382.55
  5066.0  383.88  5084.3  383.50  5087.8  383.76  5092.5  384.12  5098.8  383.54
  5105.9  384.09  5133.6  384.92  5214.8  385.12  5235.1  385.38  5245.3  385.92
  5299.3  385.71  5358.5  384.87  5438.2  385.80  5484.6  385.38  5507.3  385.80
  5514.2  385.55  5520.3  386.11  5549.8  386.30  5564.6  385.86  5567.5  386.20
#Mann=4,-1,0
  4754.6    0.05       0  4988.1    0.04       0  4992.1    0.05       0
  5087.8     0.1       0
Bank Sta=4988.1,4992.1
Exp/Cntr=0.3,0.1

Type RM Length L Ch R = 1,308,222,222,222
BEGIN DESCRIPTION:
Mapping XS 1dbc9dbe
END DESCRIPTION:
XS GIS Cut Line= 4
      2732978.43      6795810.31      2733042.94      6795569.43
      2732964.75      6795141.56      2732850.30      6794973.68
#Sta/Elev= 30
  4742.5  392.80  4772.8  392.37  4794.9  390.76  4904.7  386.14  4969.5  382.28
  4988.5  380.21  5062.4  380.75  5086.2  379.07  5142.8  375.62  5213.9  374.47
  5227.2  374.78  5252.6  373.85  5252.8  373.35  5256.3  373.35  5256.6  373.85
  5280.4  374.07  5285.5  374.73  5315.6  374.21  5356.2  375.54  5417.2  379.45
  5430.1  379.52  5433.5  380.45  5439.6  380.34  5484.3  383.26  5520.3  383.13
  5577.1  384.73  5592.1  384.24  5598.1  384.91  5625.9  384.71  5630.0  385.28
#Mann=5,-1,0
  4742.5    0.05       0  5086.2     0.1       0  5252.6    0.04       0
  5256.6     0.1       0  5625.9    0.12       0
Bank Sta=5252.6,5256.6
Exp/Cntr=0.3,0.1

Type RM Length L Ch R = 1,86,0,0,0
BEGIN DESCRIPTION:
Clear Creek T 33 1.0
END DESCRIPTION:
XS GIS Cut Line= 3
      2733133.24      6795782.38      2733232.30      6795463.51
      2732872.76      6794862.32
#Sta/Elev= 30
  4666.1  387.43  4795.9  379.76  4928.4  376.27  4958.7  375.19  4971.2  373.71
  4991.3  374.98  4996.5  373.99  5044.6  375.64  5085.4  375.80  5143.7  372.88
  5217.0  373.60  5252.6  372.56  5252.9  372.06  5256.6  372.56  5299.0  373.56
  5349.9  373.62  5392.7  377.01  5408.3  376.94  5435.5  378.88  5457.3  378.22
  5472.5  378.97  5480.7  378.33  5493.9  379.37  5564.3  380.16  5573.9  380.60
  5583.4  379.95  5626.1  381.76  5663.1  381.98  5668.9  382.91  5700.5  382.90
#Mann=8,-1,0
  4666.1    0.05       0  4928.4    0.12       0  5044.6    0.05       0
  5217.0    0.12       0  5252.6    0.07       0  5256.6    0.12       0
  5299.0     0.1       0  5564.3    0.12       0
Bank Sta=5252.6,5256.6
Exp/Cntr=0.3,0.1

Chan Stop Cuts=-1