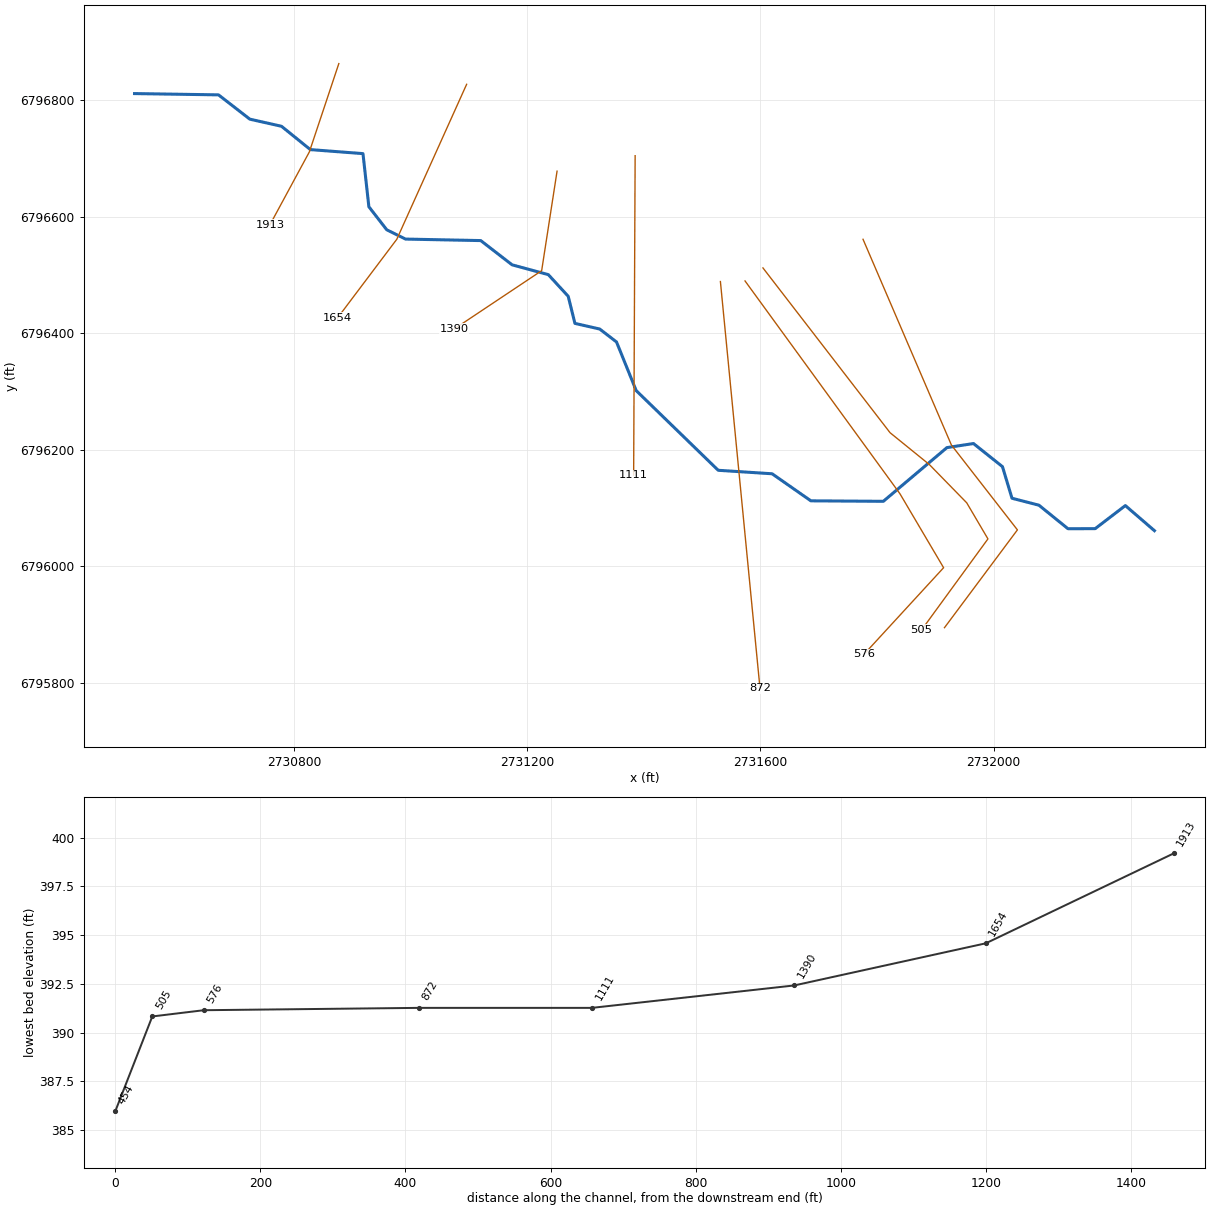
--- Clear Creek T 34.prj (project) ---

Proj Title=Clear Creek T 34 Base Level Engineering
Current Plan=p01
Default Exp/Contr=0.3,0.1
English Units
Geom File=g01
Flow File=f01
Plan File=p01
BEGIN DESCRIPTION:
Clear Creek T 34
END DESCRIPTION:

--- Clear Creek T 34.p01 (plan) ---

Plan Title=Multiple Run
Short Identifier=Multiple
Geom File=g01
Flow File=f01
Subcritical Flow
K Sum by GR= 0
Std Step Tol= 0.01
Critical Tol= 0.01
Num of Std Step Trials= 20
Max Error Tol= 0.3
Flow Tol Ratio= 0.001
Split Flow NTrial= 30
Split Flow Tol= 0.02
Split Flow Ratio= 0.02
Log Output Level= 0
Friction Slope Method= 1
Unsteady Friction Slope Method= 2
Unsteady Bridges Friction Slope Method= 1
Parabolic Critical Depth
Global Vel Dist=  1 , 1 , 1
Global Log Level= 0
CheckData=True
Encroach Param= -1, 0, 0, 0
BEGIN DESCRIPTION:
Multiple Run
END DESCRIPTION:

--- Clear Creek T 34.f01 (steady flow) ---

Flow Title=Multiple
Number of Profiles=7
Profile Names=10-year,25-year,50-year,1pct_min,100-year,1pct_plu,500-year
River Rch & RM= Clear Creek T 34,Reach-1,1913
     159     195     222     126     251     500     319
Boundary for River Rch & Prof#=Clear Creek T 34,Reach-1,1
Up Type=0
Dn Type=3
Dn Slope=0.005
Boundary for River Rch & Prof#=Clear Creek T 34,Reach-1,2
Up Type=0
Dn Type=3
Dn Slope=0.005
Boundary for River Rch & Prof#=Clear Creek T 34,Reach-1,3
Up Type=0
Dn Type=3
Dn Slope=0.005
Boundary for River Rch & Prof#=Clear Creek T 34,Reach-1,4
Up Type=0
Dn Type=3
Dn Slope=0.005
Boundary for River Rch & Prof#=Clear Creek T 34,Reach-1,5
Up Type=0
Dn Type=3
Dn Slope=0.005
Boundary for River Rch & Prof#=Clear Creek T 34,Reach-1,6
Up Type=0
Dn Type=3
Dn Slope=0.005
Boundary for River Rch & Prof#=Clear Creek T 34,Reach-1,7
Up Type=0
Dn Type=3
Dn Slope=0.005

--- Clear Creek T 34.g01 (geometry) ---

Geom Title=Existing Conditions

River Reach=Clear Creek T 34,Reach-1
Reach XY= 30
      2730526.00      6796811.00      2730670.09      6796808.80
      2730723.82      6796767.11      2730778.19      6796754.89
      2730827.66      6796714.86      2730917.99      6796707.97
      2730928.11      6796616.78      2730958.79      6796577.25
      2730991.03      6796561.34      2731120.07      6796558.75
      2731173.85      6796517.15      2731235.98      6796500.32
      2731270.11      6796463.21      2731281.66      6796416.66
      2731324.21      6796406.97      2731353.02      6796384.79
      2731386.78      6796301.34      2731527.50      6796164.61
      2731620.02      6796158.64      2731686.51      6796112.20
      2731810.83      6796111.37      2731919.98      6796203.53
      2731965.50      6796210.50      2732015.24      6796170.85
      2732031.62      6796116.62      2732077.86      6796104.69
      2732127.70      6796064.35      2732174.37      6796064.46
      2732226.12      6796104.05      2732276.00      6796061.00

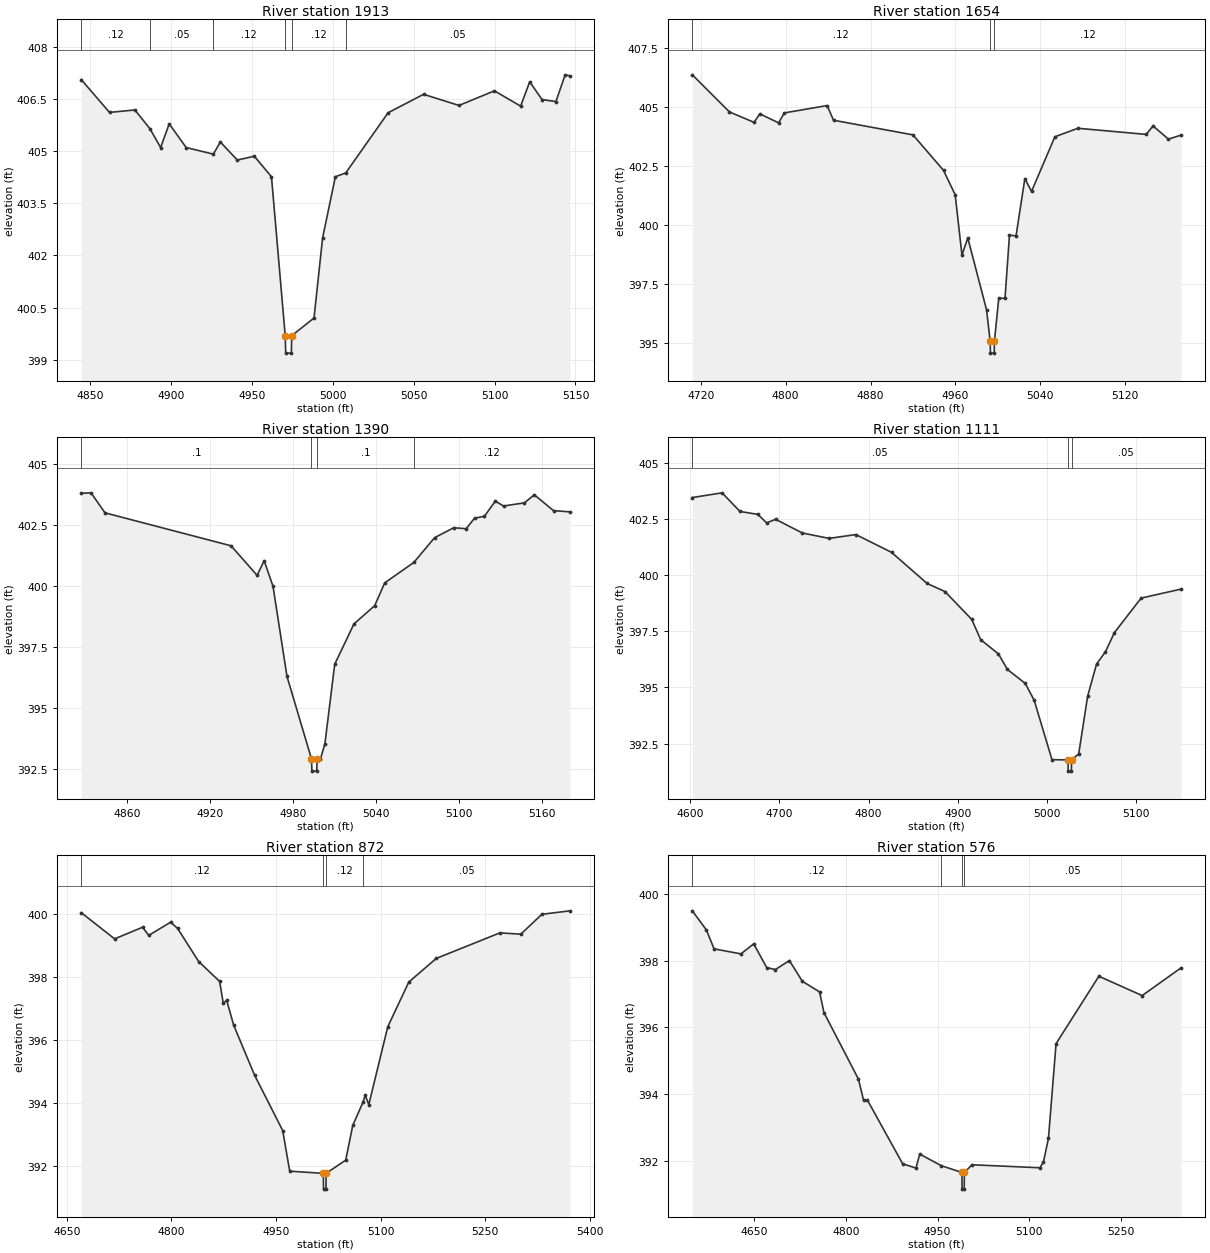
Type RM Length L Ch R = 1,1913,259,259,259
BEGIN DESCRIPTION:
Clear Creek T 34 5.0
END DESCRIPTION:
XS GIS Cut Line= 3
      2730876.54      6796862.43      2730826.00      6796711.00
      2730758.30      6796585.77
#Sta/Elev= 30
  4844.6  407.05  4862.0  406.11  4877.7  406.18  4887.0  405.64  4893.6  405.10
  4898.9  405.78  4909.4  405.10  4926.2  404.91  4930.5  405.26  4941.0  404.74
  4951.5  404.85  4962.1  404.26  4970.6  399.69  4970.9  399.19  4974.4  399.19
  4974.6  399.69  4988.4  400.20  4993.7  402.50  5001.6  404.26  5008.0  404.37
  5034.2  406.10  5056.1  406.63  5078.0  406.31  5099.9  406.73  5116.1  406.29
  5121.7  406.99  5129.3  406.48  5137.9  406.42  5143.6  407.19  5146.6  407.16
#Mann=6,-1,0
  4844.6    0.12       0  4887.0    0.05       0  4926.2    0.12       0
  4970.6    0.07       0  4974.6    0.12       0  5008.0    0.05       0
Bank Sta=4970.6,4974.6
Exp/Cntr=0.3,0.1

Type RM Length L Ch R = 1,1654,264,264,264
BEGIN DESCRIPTION:
Clear Creek T 34 4.0
END DESCRIPTION:
XS GIS Cut Line= 3
      2731095.84      6796826.92      2730976.00      6796561.00
      2730874.30      6796426.00
#Sta/Elev= 30
  4712.0  406.35  4747.0  404.78  4770.2  404.34  4775.6  404.70  4793.3  404.32
  4798.8  404.74  4839.1  405.05  4845.1  404.43  4920.0  403.81  4948.8  402.31
  4959.8  401.28  4966.2  398.73  4971.7  399.45  4989.4  396.41  4992.8  395.08
  4993.1  394.58  4996.6  394.58  4996.8  395.08  5000.9  396.90  5006.8  396.90
  5011.0  399.57  5017.2  399.54  5025.5  401.96  5031.8  401.42  5053.8  403.73
  5075.5  404.09  5140.0  403.83  5146.3  404.19  5160.9  403.63  5172.7  403.80
#Mann=3,-1,0
  4712.0    0.12       0  4992.8    0.07       0  4996.8    0.12       0
Bank Sta=4992.8,4996.8
Exp/Cntr=0.3,0.1

Type RM Length L Ch R = 1,1390,279,279,279
BEGIN DESCRIPTION:
Clear Creek T 34 3.0
END DESCRIPTION:
XS GIS Cut Line= 3
      2731251.00      6796677.88      2731224.57      6796507.12
      2731074.55      6796407.10
#Sta/Elev= 30
  4827.2  403.80  4834.2  403.82  4844.3  403.00  4935.4  401.65  4954.2  400.44
  4959.3  401.04  4965.7  399.99  4975.8  396.30  4993.5  392.92  4993.8  392.42
  4997.3  392.42  4997.5  392.92  5000.0  392.92  5003.2  393.54  5010.3  396.80
  5024.2  398.45  5039.2  399.20  5046.4  400.13  5067.5  400.97  5082.4  401.98
  5096.3  402.39  5105.3  402.35  5111.3  402.78  5118.5  402.86  5126.3  403.48
  5132.3  403.28  5147.4  403.41  5154.5  403.74  5168.4  403.09  5180.3  403.04
#Mann=4,-1,0
  4827.2     0.1       0  4993.5    0.07       0  4997.5     0.1       0
  5067.5    0.12       0
Bank Sta=4993.5,4997.5
Exp/Cntr=0.3,0.1

Type RM Length L Ch R = 1,1111,239,239,239
BEGIN DESCRIPTION:
Mapping XS 26d330d7
END DESCRIPTION:
XS GIS Cut Line= 2
      2731384.98      6796704.38      2731382.41      6796156.28
#Sta/Elev= 30
  4602.3  403.46  4635.7  403.67  4655.7  402.84  4675.7  402.71  4685.7  402.33
  4695.7  402.49  4725.7  401.88  4755.7  401.64  4785.7  401.81  4825.7  401.02
  4865.7  399.63  4885.7  399.27  4915.7  398.03  4925.7  397.13  4945.7  396.49
  4955.7  395.80  4975.7  395.18  4985.7  394.43  5005.7  391.78  5023.7  391.77
  5023.9  391.27  5027.4  391.27  5027.7  391.77  5035.7  392.04  5045.7  394.61
  5055.7  396.04  5065.7  396.59  5075.7  397.44  5105.7  398.98  5150.4  399.38
#Mann=3,-1,0
  4602.3    0.05       0  5023.7    0.05       0  5027.7    0.05       0
Bank Sta=5023.7,5027.7
Exp/Cntr=0.3,0.1

Type RM Length L Ch R = 1,872,296,296,296
BEGIN DESCRIPTION:
Mapping XS 6e4df955
END DESCRIPTION:
XS GIS Cut Line= 2
      2731531.28      6796488.47      2731599.17      6795790.86
#Sta/Elev= 30
  4670.8  400.04  4718.5  399.21  4758.7  399.58  4767.4  399.32  4798.9  399.74
  4808.9  399.54  4839.1  398.49  4869.2  397.86  4874.3  397.17  4879.3  397.26
  4889.3  396.47  4919.4  394.88  4959.6  393.13  4969.7  391.84  5017.9  391.77
  5018.2  391.27  5021.7  391.27  5021.9  391.77  5050.0  392.19  5060.1  393.29
  5074.6  394.02  5078.0  394.25  5083.1  393.95  5110.3  396.42  5140.5  397.84
  5179.9  398.59  5271.1  399.40  5301.2  399.36  5331.4  399.99  5371.7  400.10
#Mann=4,-1,0
  4670.8    0.12       0  5017.9    0.07       0  5021.9    0.12       0
  5074.6    0.05       0
Bank Sta=5017.9,5021.9
Exp/Cntr=0.3,0.1

Type RM Length L Ch R = 1,576,71,71,71
BEGIN DESCRIPTION:
Clear Creek T 34 2.0
END DESCRIPTION:
XS GIS Cut Line= 4
      2731573.53      6796489.51      2731839.31      6796124.40
      2731914.27      6795997.45      2731777.99      6795849.20
#Sta/Elev= 30
  4548.4  399.49  4571.3  398.92  4584.0  398.35  4628.0  398.20  4648.9  398.50
  4670.2  397.79  4684.4  397.73  4707.4  398.00  4728.5  397.38  4756.8  397.06
  4764.0  396.44  4820.4  394.45  4828.9  393.81  4835.1  393.82  4892.9  391.91
  4914.7  391.78  4920.9  392.20  4956.5  391.85  4990.0  391.65  4990.2  391.15
  4993.7  391.15  4994.0  391.65  5006.5  391.88  5117.8  391.79  5123.6  391.97
  5131.7  392.67  5144.2  395.51  5214.3  397.53  5285.2  396.95  5348.8  397.78
#Mann=4,-1,0
  4548.4    0.12       0  4956.5    0.05       0  4990.0    0.03       0
  4994.0    0.05       0
Bank Sta=4990,4994
Exp/Cntr=0.3,0.1

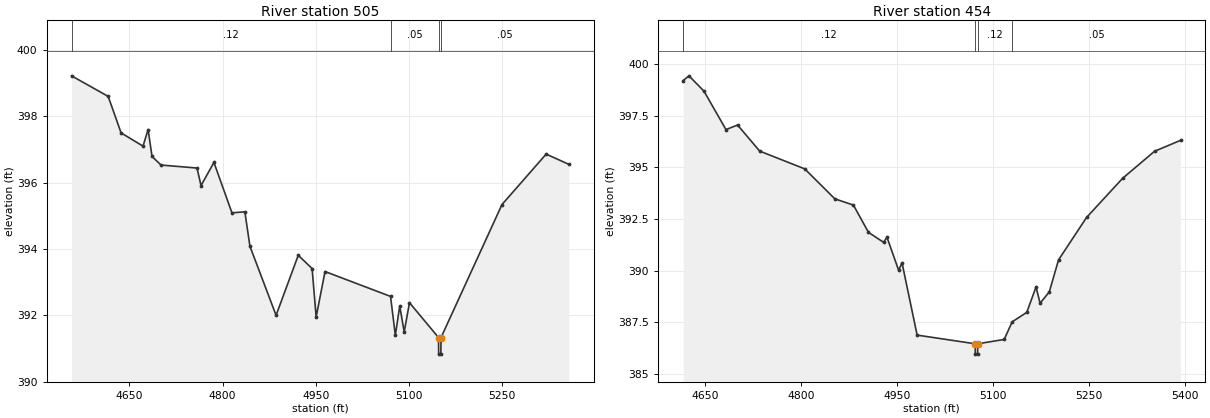
Type RM Length L Ch R = 1,505,51,51,51
BEGIN DESCRIPTION:
Mapping XS 2f2ac301
END DESCRIPTION:
XS GIS Cut Line= 6
      2731604.29      6796511.85      2731822.40      6796229.09
      2731889.88      6796174.39      2731953.94      6796108.79
      2731990.34      6796046.87      2731876.34      6795890.51
#Sta/Elev= 30
  4556.7  399.22  4615.7  398.60  4636.5  397.50  4671.8  397.10  4680.0  397.60
  4686.3  396.79  4700.8  396.53  4758.8  396.44  4765.2  395.91  4786.0  396.61
  4815.0  395.09  4835.8  395.12  4844.0  394.08  4886.1  392.00  4921.8  393.81
  4944.1  393.41  4950.6  391.95  4964.9  393.32  5070.4  392.57  5078.1  391.40
  5085.2  392.28  5092.4  391.50  5100.9  392.38  5147.7  391.33  5147.9  390.83
  5151.4  390.83  5151.7  391.33  5249.9  395.34  5321.0  396.86  5357.7  396.55
#Mann=4,-1,0
  4556.7    0.12       0  5070.4    0.05       0  5147.7    0.07       0
  5151.7    0.05       0
Bank Sta=5147.7,5151.7
Exp/Cntr=0.3,0.1

Type RM Length L Ch R = 1,454,0,0,0
BEGIN DESCRIPTION:
Clear Creek T 34 1.0
END DESCRIPTION:
XS GIS Cut Line= 4
      2731776.00      6796561.00      2731927.68      6796207.90
      2732040.91      6796062.35      2731915.79      6795894.58
#Sta/Elev= 30
  4615.7  399.20  4624.8  399.43  4648.3  398.69  4682.7  396.83  4700.9  397.05
  4735.4  395.79  4805.9  394.93  4853.0  393.48  4882.0  393.18  4905.6  391.86
  4929.1  391.38  4934.6  391.62  4952.7  390.03  4958.1  390.38  4981.7  386.89
  5072.5  386.47  5072.7  385.97  5076.2  385.97  5076.5  386.47  5117.9  386.68
  5130.3  387.53  5153.2  387.99  5167.7  389.22  5174.0  388.43  5188.4  388.98
  5202.9  390.53  5246.7  392.58  5303.0  394.47  5353.0  395.78  5393.7  396.31
#Mann=4,-1,0
  4615.7    0.12       0  5072.5    0.07       0  5076.5    0.12       0
  5130.3    0.05       0
Bank Sta=5072.5,5076.5
Exp/Cntr=0.3,0.1

Chan Stop Cuts=-1