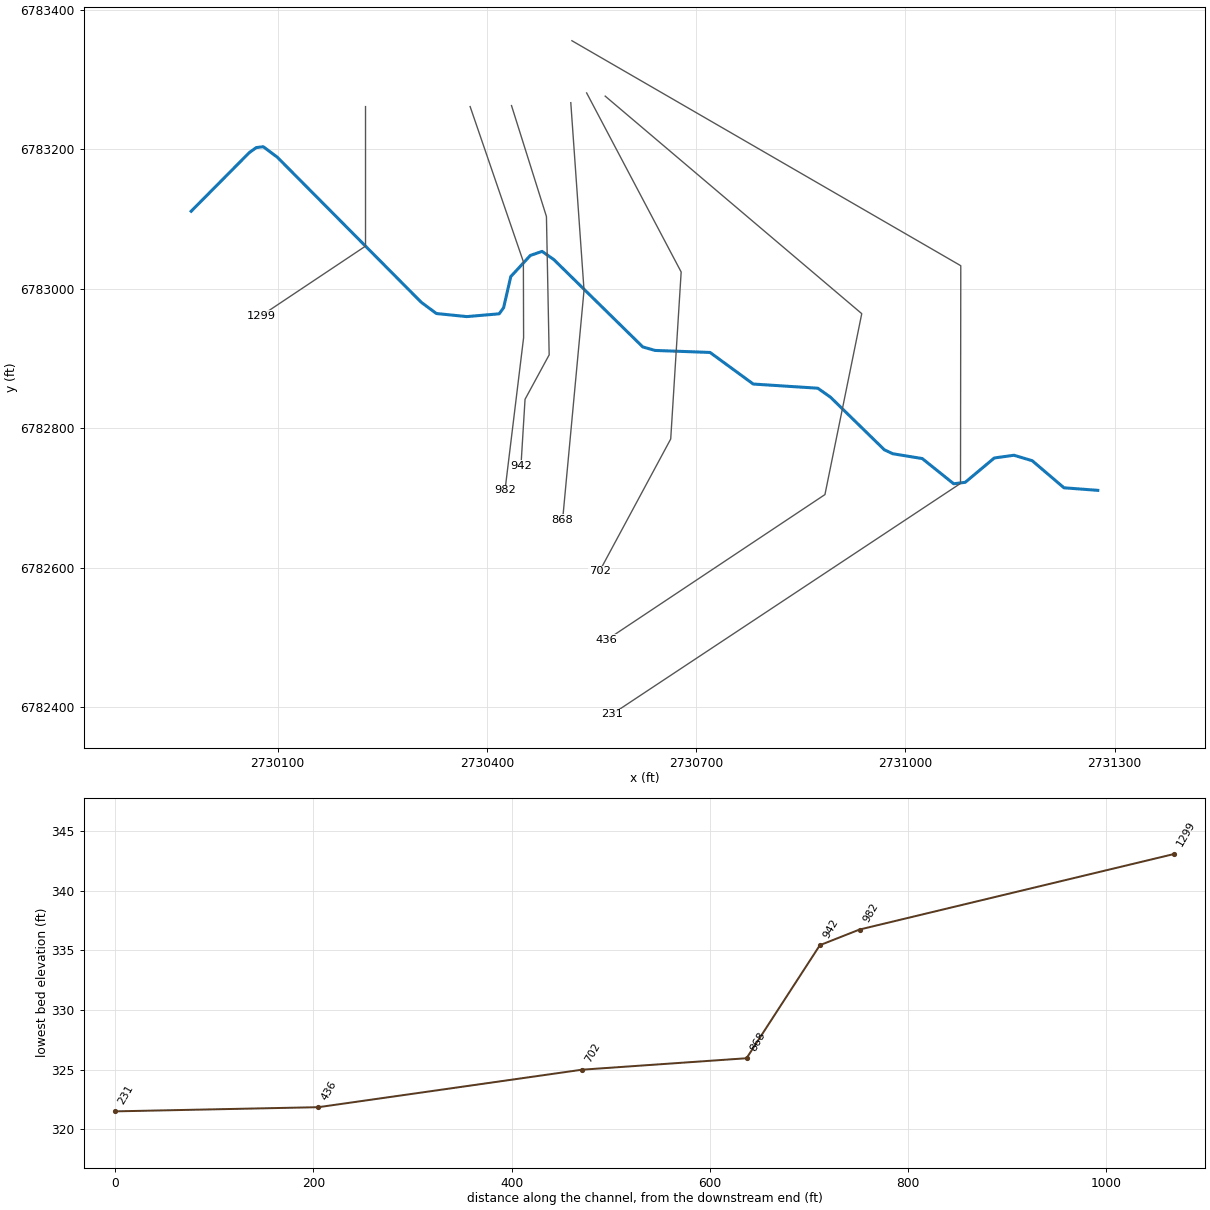
--- Clear Creek T 35.prj (project) ---

Proj Title=Clear Creek T 35 Base Level Engineering
Current Plan=p01
Default Exp/Contr=0.3,0.1
English Units
Geom File=g01
Flow File=f01
Plan File=p01
BEGIN DESCRIPTION:
Clear Creek T 35
END DESCRIPTION:

--- Clear Creek T 35.p01 (plan) ---

Plan Title=Multiple Run
Short Identifier=Multiple
Geom File=g01
Flow File=f01
Subcritical Flow
K Sum by GR= 0
Std Step Tol= 0.01
Critical Tol= 0.01
Num of Std Step Trials= 20
Max Error Tol= 0.3
Flow Tol Ratio= 0.001
Split Flow NTrial= 30
Split Flow Tol= 0.02
Split Flow Ratio= 0.02
Log Output Level= 0
Friction Slope Method= 1
Unsteady Friction Slope Method= 2
Unsteady Bridges Friction Slope Method= 1
Parabolic Critical Depth
Global Vel Dist=  1 , 1 , 1
Global Log Level= 0
CheckData=True
Encroach Param= -1, 0, 0, 0
BEGIN DESCRIPTION:
Multiple Run
END DESCRIPTION:

--- Clear Creek T 35.f01 (steady flow) ---

Flow Title=Multiple
Number of Profiles=7
Profile Names=10-year,25-year,50-year,1pct_min,100-year,1pct_plu,500-year
River Rch & RM= Clear Creek T 35,Reach-1,1299
     262     336     395     232     462     922     629
Boundary for River Rch & Prof#=Clear Creek T 35,Reach-1,1
Up Type=0
Dn Type=3
Dn Slope=0.005
Boundary for River Rch & Prof#=Clear Creek T 35,Reach-1,2
Up Type=0
Dn Type=3
Dn Slope=0.005
Boundary for River Rch & Prof#=Clear Creek T 35,Reach-1,3
Up Type=0
Dn Type=3
Dn Slope=0.005
Boundary for River Rch & Prof#=Clear Creek T 35,Reach-1,4
Up Type=0
Dn Type=3
Dn Slope=0.005
Boundary for River Rch & Prof#=Clear Creek T 35,Reach-1,5
Up Type=0
Dn Type=3
Dn Slope=0.005
Boundary for River Rch & Prof#=Clear Creek T 35,Reach-1,6
Up Type=0
Dn Type=3
Dn Slope=0.005
Boundary for River Rch & Prof#=Clear Creek T 35,Reach-1,7
Up Type=0
Dn Type=3
Dn Slope=0.005

--- Clear Creek T 35.g01 (geometry) ---

Geom Title=Existing Conditions

River Reach=Clear Creek T 35,Reach-1
Reach XY= 30
      2729976.00      6783111.00      2730059.33      6783195.01
      2730069.33      6783202.20      2730079.33      6783203.49
      2730099.33      6783188.61      2730305.87      6782980.57
      2730327.57      6782964.43      2730371.29      6782960.00
      2730417.66      6782964.02      2730424.00      6782972.74
      2730434.30      6783017.36      2730462.35      6783047.66
      2730479.16      6783053.46      2730495.93      6783041.81
      2730623.57      6782916.52      2730641.22      6782911.52
      2730720.02      6782908.64      2730781.98      6782863.36
      2730874.50      6782857.38      2730892.74      6782844.51
      2730969.96      6782769.14      2730982.05      6782763.47
      2731024.35      6782756.55      2731069.39      6782720.43
      2731085.92      6782722.51      2731127.63      6782757.41
      2731155.79      6782761.30      2731182.00      6782753.46
      2731227.49      6782714.69      2731276.00      6782711.00

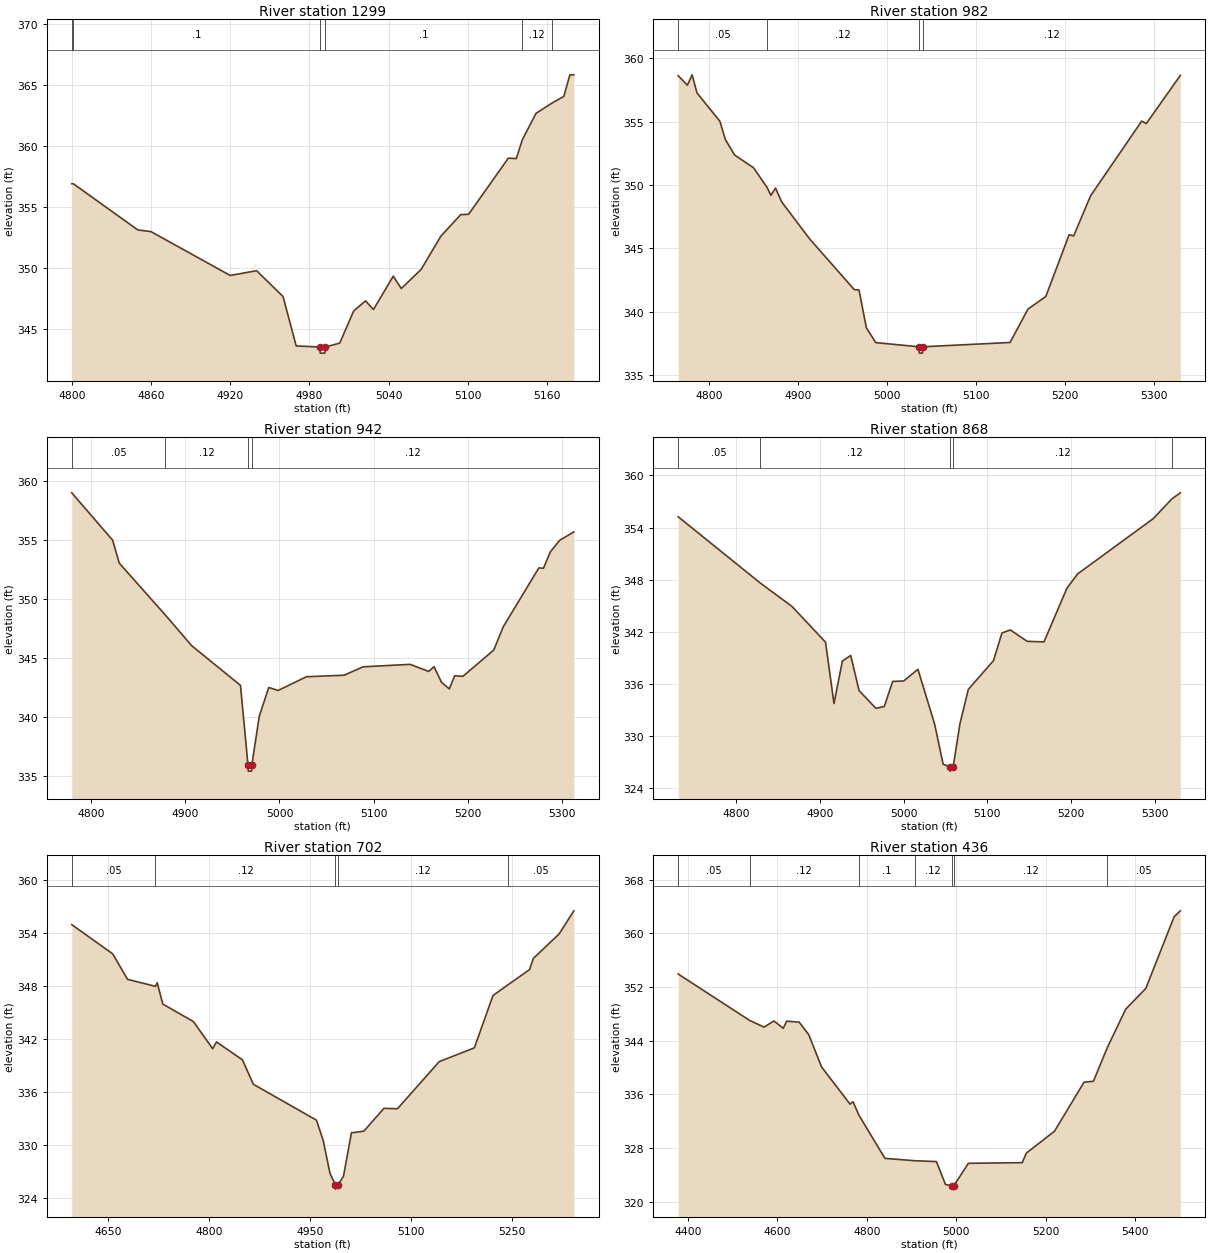
Type RM Length L Ch R = 1,1299,317,317,317
BEGIN DESCRIPTION:
Clear Creek T 35 4.0
END DESCRIPTION:
XS GIS Cut Line= 3
      2730226.00      6783260.98      2730226.00      6783061.00
      2730075.97      6782960.98
#Sta/Elev= 30
  4800.0  356.92  4801.2  356.92  4850.0  353.14  4860.0  353.00  4920.0  349.41
  4940.0  349.80  4960.0  347.69  4970.0  343.64  4988.0  343.55  4988.2  343.05
  4991.7  343.05  4992.0  343.55  5003.0  343.87  5013.5  346.50  5022.5  347.33
  5028.5  346.62  5043.5  349.35  5049.6  348.34  5064.6  349.90  5079.6  352.63
  5094.6  354.39  5100.6  354.42  5130.7  359.02  5136.7  358.98  5141.3  360.53
  5151.7  362.69  5163.8  363.53  5172.7  364.07  5177.3  365.84  5180.3  365.84
#Mann=6,-1,0
  4800.0    0.05       0  4801.2     0.1       0  4988.0    0.07       0
  4992.0     0.1       0  5141.3    0.12       0  5163.8    0.05       0
Bank Sta=4988,4992
Exp/Cntr=0.3,0.1

Type RM Length L Ch R = 1,982,40,40,40
BEGIN DESCRIPTION:
Clear Creek T 35 3.0
END DESCRIPTION:
XS GIS Cut Line= 4
      2730376.00      6783261.00      2730452.35      6783038.64
      2730452.67      6782929.76      2730425.99      6782710.96
#Sta/Elev= 30
  4764.9  358.62  4775.2  357.87  4780.5  358.69  4786.0  357.26  4811.8  355.02
  4817.8  353.59  4828.3  352.36  4849.5  351.36  4865.1  349.77  4869.0  349.18
  4874.3  349.75  4881.2  348.66  4912.9  345.72  4962.8  341.74  4968.1  341.71
  4976.4  338.73  4986.9  337.56  5035.6  337.23  5035.9  336.73  5039.4  336.73
  5039.6  337.23  5137.9  337.57  5158.0  340.20  5178.1  341.20  5204.3  346.07
  5209.4  345.98  5228.5  349.15  5285.9  355.04  5291.0  354.84  5329.3  358.64
#Mann=4,-1,0
  4764.9    0.05       0  4865.1    0.12       0  5035.6    0.07       0
  5039.6    0.12       0
Bank Sta=5035.6,5039.6
Exp/Cntr=0.3,0.1

Type RM Length L Ch R = 1,942,74,74,74
BEGIN DESCRIPTION:
Mapping XS 40c74201
END DESCRIPTION:
XS GIS Cut Line= 5
      2730435.33      6783262.43      2730485.42      6783103.41
      2730489.34      6782905.21      2730454.74      6782841.49
      2730448.89      6782746.13
#Sta/Elev= 30
  4779.5  358.98  4822.9  354.97  4829.9  353.03  4879.0  348.62  4906.8  346.04
  4958.6  342.68  4966.6  335.92  4966.9  335.42  4970.4  335.42  4970.6  335.92
  4978.6  340.08  4988.6  342.50  4998.6  342.25  5028.6  343.41  5068.7  343.54
  5088.7  344.25  5138.7  344.46  5158.4  343.86  5164.1  344.26  5172.0  342.94
  5180.3  342.38  5186.0  343.49  5194.8  343.45  5227.5  345.67  5237.5  347.63
  5275.3  352.62  5280.3  352.60  5287.6  353.99  5297.6  354.97  5312.5  355.67
#Mann=4,-1,0
  4779.5    0.05       0  4879.0    0.12       0  4966.6    0.07       0
  4970.6    0.12       0
Bank Sta=4966.6,4970.6
Exp/Cntr=0.3,0.1

Type RM Length L Ch R = 1,868,166,166,166
BEGIN DESCRIPTION:
Clear Creek T 35 2.0
END DESCRIPTION:
XS GIS Cut Line= 3
      2730520.34      6783266.61      2730539.32      6782997.88
      2730508.62      6782668.81
#Sta/Elev= 30
  4730.6  355.24  4828.4  347.63  4866.6  344.91  4906.6  340.80  4916.7  333.73
  4926.7  338.62  4936.7  339.27  4946.7  335.22  4966.8  333.18  4976.8  333.39
  4986.8  336.28  5000.0  336.33  5017.0  337.68  5037.0  331.35  5047.1  326.75
  5055.1  326.45  5055.4  325.95  5059.1  326.45  5067.2  331.41  5077.2  335.36
  5107.3  338.68  5117.4  341.86  5127.4  342.21  5147.5  340.90  5167.6  340.83
  5195.0  347.01  5207.8  348.66  5298.2  355.03  5320.4  357.30  5330.5  358.00
#Mann=5,-1,0
  4730.6    0.05       0  4828.4    0.12       0  5055.1    0.07       0
  5059.1    0.12       0  5320.4    0.05       0
Bank Sta=5055.1,5059.1
Exp/Cntr=0.3,0.1

Type RM Length L Ch R = 1,702,266,266,266
BEGIN DESCRIPTION:
Mapping XS 693bfcec
END DESCRIPTION:
XS GIS Cut Line= 4
      2730543.06      6783280.57      2730678.60      6783023.95
      2730663.62      6782784.61      2730561.51      6782594.98
#Sta/Elev= 30
  4596.5  354.91  4657.3  351.60  4679.3  348.72  4720.7  347.93  4723.3  348.34
  4731.7  345.92  4777.0  343.95  4805.7  340.87  4811.4  341.64  4849.8  339.62
  4866.1  336.85  4959.8  332.79  4969.8  330.49  4979.9  326.76  4987.9  325.49
  4988.1  324.99  4991.9  325.49  4999.9  326.45  5011.7  331.36  5030.0  331.54
  5060.0  334.13  5080.0  334.08  5142.0  339.41  5194.2  340.97  5221.8  346.88
  5243.9  348.09  5276.1  349.82  5281.8  351.09  5320.0  353.85  5341.9  356.47
#Mann=5,-1,0
  4596.5    0.05       0  4720.7    0.12       0  4987.9    0.07       0
  4991.9    0.12       0  5243.9    0.05       0
Bank Sta=4987.9,4991.9
Exp/Cntr=0.3,0.1

Type RM Length L Ch R = 1,436,205,205,205
BEGIN DESCRIPTION:
Mapping XS f010be1e
END DESCRIPTION:
XS GIS Cut Line= 4
      2730569.68      6783275.96      2730937.55      6782964.22
      2730884.77      6782704.95      2730571.79      6782496.72
#Sta/Elev= 30
  4378.5  353.94  4537.9  347.03  4570.4  346.02  4592.5  346.94  4613.3  345.85
  4621.0  346.91  4648.9  346.76  4670.5  344.88  4699.0  340.08  4762.7  334.53
  4769.3  334.89  4782.3  332.91  4840.7  326.44  4906.9  326.09  4955.8  325.96
  4976.2  322.53  4990.7  322.35  4990.9  321.85  4994.7  322.35  5027.3  325.70
  5147.8  325.80  5156.7  327.21  5219.9  330.49  5285.9  337.80  5306.9  337.94
  5338.0  342.97  5379.1  348.70  5424.1  351.80  5487.3  362.48  5501.2  363.37
#Mann=7,-1,0
  4378.5    0.05       0  4537.9    0.12       0  4782.3     0.1       0
  4906.9    0.12       0  4990.7    0.07       0  4994.7    0.12       0
  5338.0    0.05       0
Bank Sta=4990.7,4994.7
Exp/Cntr=0.3,0.1

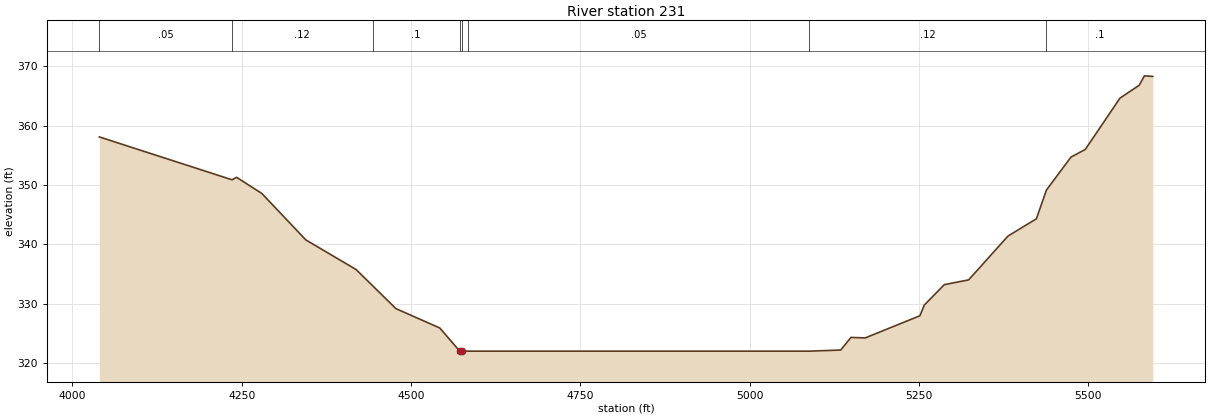
Type RM Length L Ch R = 1,231,0,0,0
BEGIN DESCRIPTION:
Clear Creek T 35 1.0
END DESCRIPTION:
XS GIS Cut Line= 4
      2730521.96      6783355.37      2731079.55      6783032.93
      2731079.15      6782720.92      2730579.33      6782390.10
#Sta/Elev= 30
  4039.7  358.12  4235.7  350.89  4242.4  351.31  4279.7  348.58  4344.7  340.75
  4418.9  335.76  4443.3  333.02  4477.7  329.17  4542.4  325.91  4571.9  322.00
  4572.1  321.50  4575.9  322.00  4583.5  322.00  5087.7  322.00  5134.5  322.19
  5149.6  324.32  5170.6  324.23  5251.4  327.97  5257.9  329.78  5287.4  333.21
  5323.4  334.02  5381.3  341.39  5423.4  344.32  5438.2  349.16  5474.5  354.72
  5495.6  356.01  5546.8  364.66  5575.2  366.83  5582.9  368.42  5595.2  368.32
#Mann=8,-1,0
  4039.7    0.05       0  4235.7    0.12       0  4443.3     0.1       0
  4571.9    0.03       0  4575.9     0.1       0  4583.5    0.05       0
  5087.7    0.12       0  5438.2     0.1       0
Bank Sta=4571.9,4575.9
Exp/Cntr=0.3,0.1

Chan Stop Cuts=-1