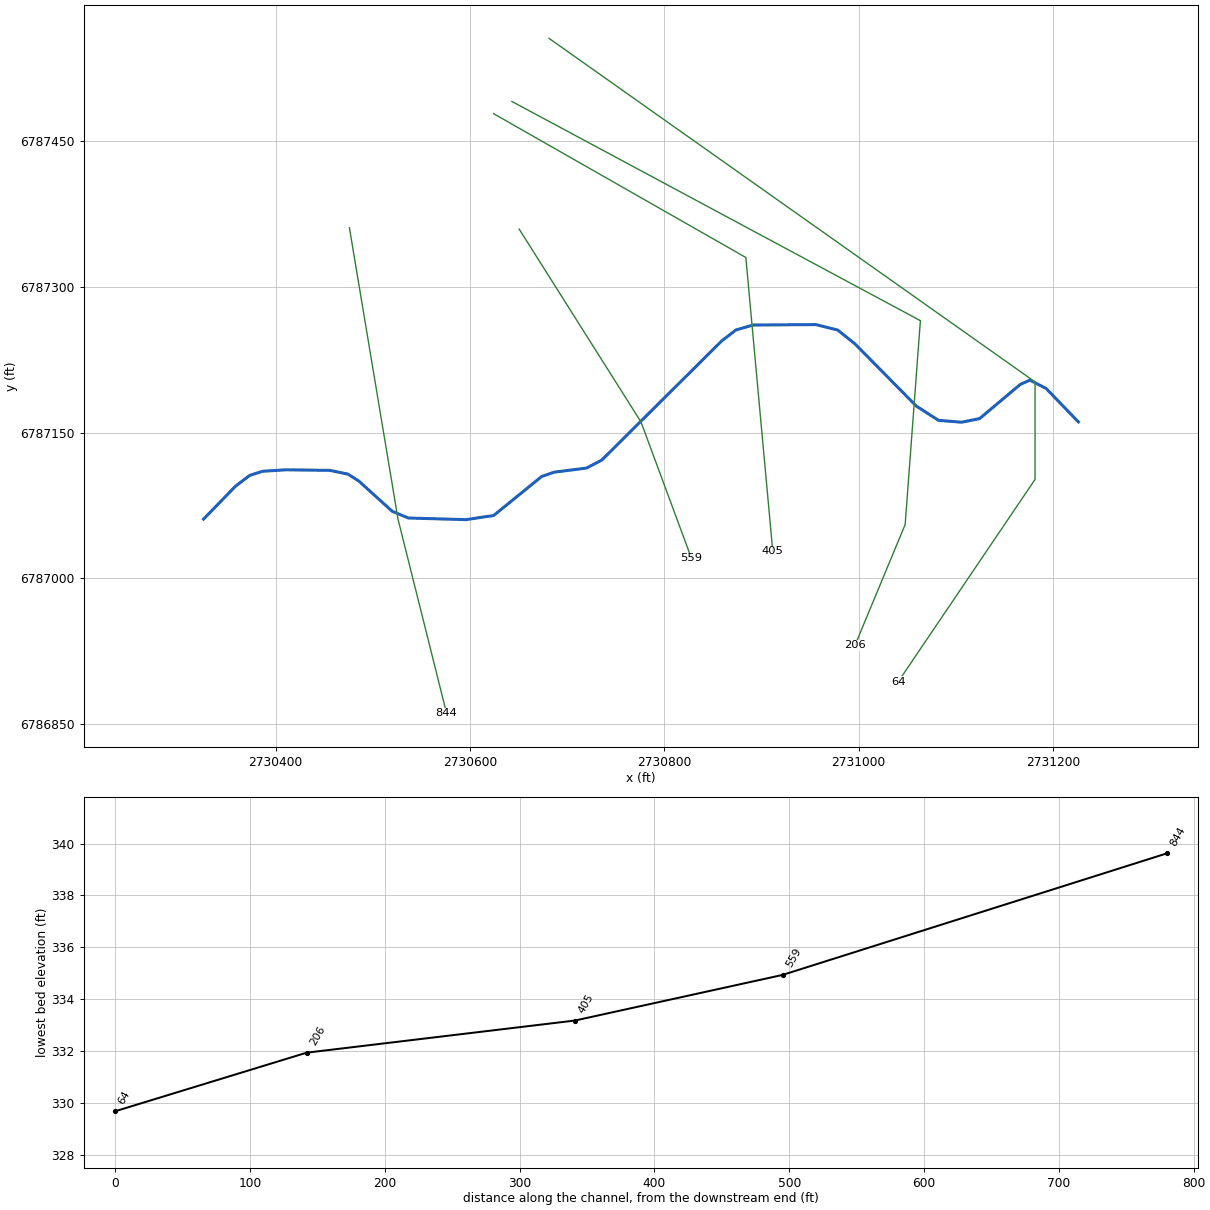
--- Clear Creek T 36.prj (project) ---

Proj Title=Clear Creek T 36 Base Level Engineering
Current Plan=p01
Default Exp/Contr=0.3,0.1
English Units
Geom File=g01
Flow File=f01
Plan File=p01
BEGIN DESCRIPTION:
Clear Creek T 36
END DESCRIPTION:

--- Clear Creek T 36.p01 (plan) ---

Plan Title=Multiple Run
Short Identifier=Multiple
Geom File=g01
Flow File=f01
Subcritical Flow
K Sum by GR= 0
Std Step Tol= 0.01
Critical Tol= 0.01
Num of Std Step Trials= 20
Max Error Tol= 0.3
Flow Tol Ratio= 0.001
Split Flow NTrial= 30
Split Flow Tol= 0.02
Split Flow Ratio= 0.02
Log Output Level= 0
Friction Slope Method= 1
Unsteady Friction Slope Method= 2
Unsteady Bridges Friction Slope Method= 1
Parabolic Critical Depth
Global Vel Dist=  1 , 1 , 1
Global Log Level= 0
CheckData=True
Encroach Param= -1, 0, 0, 0
BEGIN DESCRIPTION:
Multiple Run
END DESCRIPTION:

--- Clear Creek T 36.f01 (steady flow) ---

Flow Title=Multiple
Number of Profiles=7
Profile Names=10-year,25-year,50-year,1pct_min,100-year,1pct_plu,500-year
River Rch & RM= Clear Creek T 36,Reach-1,844
     262     337     396     232     463     923     630
Boundary for River Rch & Prof#=Clear Creek T 36,Reach-1,1
Up Type=0
Dn Type=3
Dn Slope=0.005
Boundary for River Rch & Prof#=Clear Creek T 36,Reach-1,2
Up Type=0
Dn Type=3
Dn Slope=0.005
Boundary for River Rch & Prof#=Clear Creek T 36,Reach-1,3
Up Type=0
Dn Type=3
Dn Slope=0.005
Boundary for River Rch & Prof#=Clear Creek T 36,Reach-1,4
Up Type=0
Dn Type=3
Dn Slope=0.005
Boundary for River Rch & Prof#=Clear Creek T 36,Reach-1,5
Up Type=0
Dn Type=3
Dn Slope=0.005
Boundary for River Rch & Prof#=Clear Creek T 36,Reach-1,6
Up Type=0
Dn Type=3
Dn Slope=0.005
Boundary for River Rch & Prof#=Clear Creek T 36,Reach-1,7
Up Type=0
Dn Type=3
Dn Slope=0.005

--- Clear Creek T 36.g01 (geometry) ---

Geom Title=Existing Conditions

River Reach=Clear Creek T 36,Reach-1
Reach XY= 30
      2730326.00      6787061.00      2730358.95      6787094.96
      2730373.45      6787105.95      2730386.46      6787110.18
      2730410.96      6787111.73      2730455.92      6787111.11
      2730474.41      6787107.30      2730485.64      6787100.18
      2730519.96      6787069.09      2730536.55      6787062.10
      2730596.05      6787060.40      2730624.42      6787064.67
      2730673.83      6787104.85      2730686.71      6787109.28
      2730719.97      6787113.50      2730735.68      6787121.76
      2730859.25      6787244.60      2730873.57      6787255.60
      2730891.22      6787260.76      2730955.94      6787261.21
      2730978.42      6787255.59      2730996.14      6787241.37
      2731059.34      6787177.26      2731082.05      6787162.65
      2731105.83      6787160.69      2731124.37      6787164.43
      2731166.17      6787199.56      2731176.12      6787204.05
      2731192.83      6787195.44      2731226.00      6787161.00

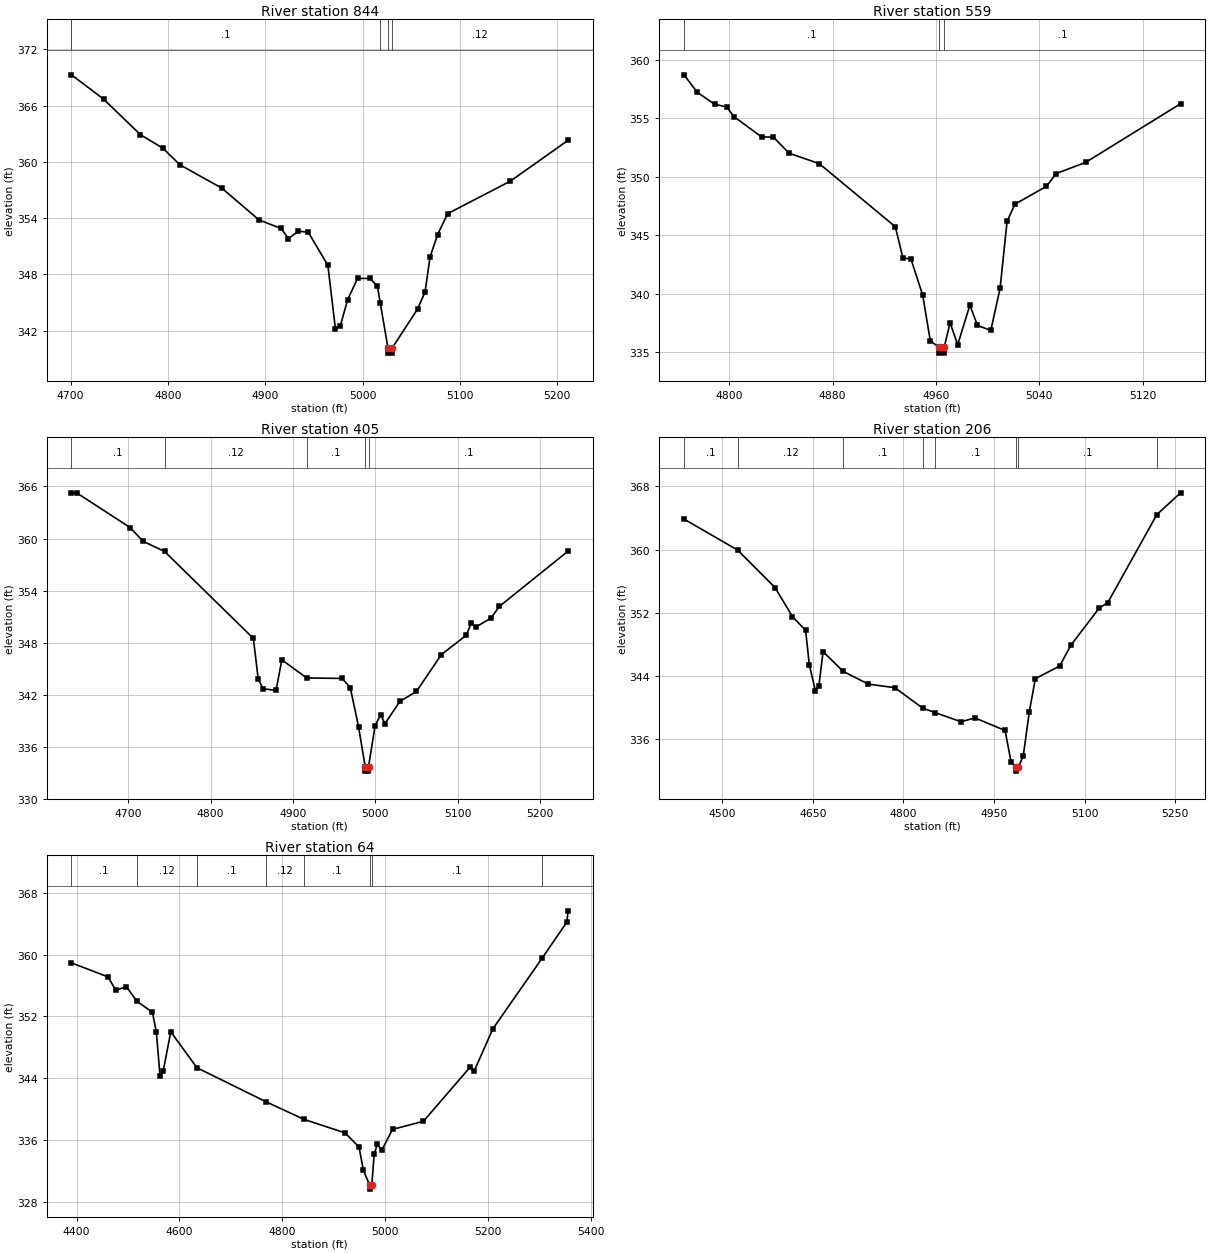
Type RM Length L Ch R = 1,844,285,285,285
BEGIN DESCRIPTION:
Clear Creek T 36 3.0
END DESCRIPTION:
XS GIS Cut Line= 3
      2730476.01      6787360.96      2730526.00      6787061.00
      2730576.01      6786860.96
#Sta/Elev= 30
  4700.9  369.27  4733.8  366.69  4771.8  362.89  4794.6  361.47  4812.4  359.68
  4855.5  357.19  4893.5  353.82  4916.3  352.90  4923.9  351.82  4934.0  352.61
  4944.2  352.51  4964.4  348.97  4972.1  342.23  4977.1  342.49  4984.7  345.32
  4994.9  347.58  5007.6  347.58  5015.3  346.75  5018.2  344.99  5026.2  340.12
  5026.4  339.62  5029.9  339.62  5030.2  340.12  5056.5  344.31  5064.3  346.14
  5069.4  349.87  5077.2  352.25  5087.5  354.48  5151.9  357.94  5211.2  362.29
#Mann=4,-1,0
  4700.9     0.1       0  5018.2    0.12       0  5026.2    0.07       0
  5030.2    0.12       0
Bank Sta=5026.2,5030.2
Exp/Cntr=0.3,0.1

Type RM Length L Ch R = 1,559,154,154,154
BEGIN DESCRIPTION:
Clear Creek T 36 2.0
END DESCRIPTION:
XS GIS Cut Line= 3
      2730650.68      6787359.50      2730776.00      6787161.00
      2730827.87      6787020.73
#Sta/Elev= 30
  4765.0  358.73  4775.1  357.25  4788.6  356.21  4797.9  355.99  4803.8  355.14
  4825.0  353.42  4834.2  353.40  4846.2  352.03  4869.7  351.13  4928.5  345.74
  4934.4  343.07  4940.6  342.98  4949.7  339.89  4955.6  335.98  4962.3  335.43
  4962.5  334.93  4966.0  334.93  4966.3  335.43  4970.9  337.52  4976.8  335.65
  4986.2  339.03  4992.1  337.30  5002.4  336.87  5009.6  340.47  5015.0  346.20
  5021.1  347.67  5045.4  349.19  5053.1  350.29  5075.8  351.24  5149.3  356.26
#Mann=3,-1,0
  4765.0     0.1       0  4962.3    0.07       0  4966.3     0.1       0
Bank Sta=4962.3,4966.3
Exp/Cntr=0.3,0.1

Type RM Length L Ch R = 1,405,199,199,199
BEGIN DESCRIPTION:
Mapping XS 4503624b
END DESCRIPTION:
XS GIS Cut Line= 3
      2730624.32      6787478.38      2730883.87      6787330.32
      2730911.58      6787027.90
#Sta/Elev= 30
  4631.2  365.24  4637.4  365.27  4702.3  361.27  4718.1  359.68  4744.1  358.51
  4851.9  348.48  4857.8  343.77  4863.6  342.68  4879.4  342.47  4886.4  346.01
  4916.6  343.92  4959.5  343.86  4969.5  342.80  4979.5  338.30  4987.6  333.67
  4987.8  333.17  4991.3  333.17  4991.6  333.67  4999.6  338.41  5006.4  339.70
  5011.4  338.63  5029.7  341.21  5049.8  342.36  5080.0  346.61  5110.1  348.83
  5116.4  350.25  5121.5  349.77  5140.2  350.82  5150.3  352.16  5233.7  358.54
#Mann=5,-1,0
  4631.2     0.1       0  4744.1    0.12       0  4916.6     0.1       0
  4987.6    0.07       0  4991.6     0.1       0
Bank Sta=4987.6,4991.6
Exp/Cntr=0.3,0.1

Type RM Length L Ch R = 1,206,142,142,142
BEGIN DESCRIPTION:
Mapping XS bb547c67
END DESCRIPTION:
XS GIS Cut Line= 4
      2730643.23      6787490.90      2731063.45      6787265.26
      2731047.78      6787055.35      2730996.25      6786931.18
#Sta/Elev= 30
  4437.0  363.86  4525.8  359.93  4587.7  355.18  4616.3  351.52  4638.2  349.76
  4644.4  345.37  4654.4  342.13  4660.1  342.68  4667.1  347.07  4700.4  344.57
  4742.1  342.95  4786.0  342.50  4831.8  339.92  4853.1  339.33  4895.5  338.19
  4918.6  338.67  4968.4  337.08  4978.4  333.06  4986.4  332.43  4986.7  331.93
  4990.4  332.43  4998.5  333.87  5008.5  339.45  5018.5  343.65  5058.6  345.24
  5077.4  347.89  5124.1  352.58  5138.4  353.28  5219.6  364.43  5258.9  367.19
#Mann=8,-1,0
  4437.0     0.1       0  4525.8    0.12       0  4700.4     0.1       0
  4831.8    0.12       0  4853.1     0.1       0  4986.4    0.07       0
  4990.4     0.1       0  5219.6    0.12       0
Bank Sta=4986.4,4990.4
Exp/Cntr=0.3,0.1

Type RM Length L Ch R = 1,64,0,0,0
BEGIN DESCRIPTION:
Clear Creek T 36 1.0
END DESCRIPTION:
XS GIS Cut Line= 4
      2730681.37      6787555.91      2731181.41      6787202.19
      2731181.41      6787101.80      2731040.44      6786893.27
#Sta/Elev= 30
  4390.2  358.93  4461.3  357.11  4476.1  355.40  4497.0  355.85  4517.1  353.97
  4547.4  352.54  4555.1  349.98  4562.2  344.29  4568.3  344.92  4583.1  350.02
  4633.9  345.37  4768.6  340.95  4842.0  338.69  4921.7  336.94  4948.7  335.12
  4957.3  332.09  4969.6  330.17  4969.8  329.67  4973.6  330.17  4978.2  334.23
  4984.4  335.46  4993.0  334.70  5013.9  337.40  5073.9  338.44  5164.4  345.43
  5172.8  344.99  5208.8  350.40  5304.7  359.56  5352.7  364.22  5354.8  365.66
#Mann=8,-1,0
  4390.2     0.1       0  4517.1    0.12       0  4633.9     0.1       0
  4768.6    0.12       0  4842.0     0.1       0  4969.6    0.07       0
  4973.6     0.1       0  5304.7    0.12       0
Bank Sta=4969.6,4973.6
Exp/Cntr=0.3,0.1

Chan Stop Cuts=-1