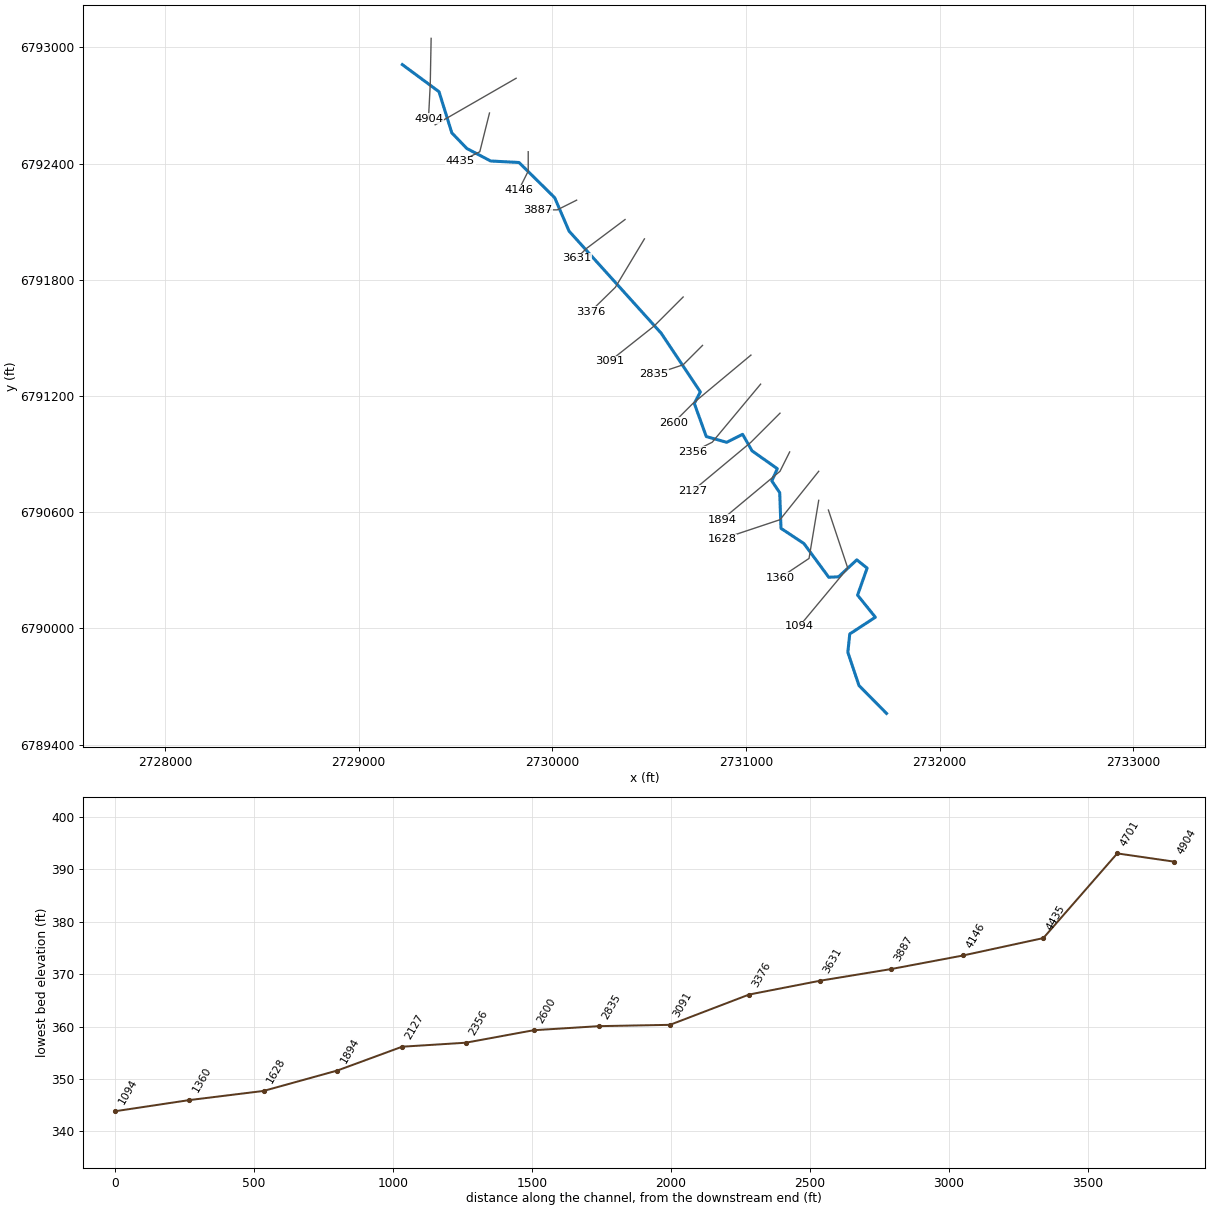
--- Clear Creek T 37.prj (project) ---

Proj Title=Clear Creek T 37 Base Level Engineering
Current Plan=p01
Default Exp/Contr=0.3,0.1
English Units
Geom File=g01
Flow File=f01
Plan File=p01
BEGIN DESCRIPTION:
Clear Creek T 37
END DESCRIPTION:

--- Clear Creek T 37.p01 (plan) ---

Plan Title=Multiple Run
Short Identifier=Multiple
Geom File=g01
Flow File=f01
Subcritical Flow
K Sum by GR= 0
Std Step Tol= 0.01
Critical Tol= 0.01
Num of Std Step Trials= 20
Max Error Tol= 0.3
Flow Tol Ratio= 0.001
Split Flow NTrial= 30
Split Flow Tol= 0.02
Split Flow Ratio= 0.02
Log Output Level= 0
Friction Slope Method= 1
Unsteady Friction Slope Method= 2
Unsteady Bridges Friction Slope Method= 1
Parabolic Critical Depth
Global Vel Dist=  1 , 1 , 1
Global Log Level= 0
CheckData=True
Encroach Param= -1, 0, 0, 0
BEGIN DESCRIPTION:
Multiple Run
END DESCRIPTION:

--- Clear Creek T 37.f01 (steady flow) ---

Flow Title=Multiple
Number of Profiles=7
Profile Names=10-year,25-year,50-year,1pct_min,100-year,1pct_plu,500-year
River Rch & RM= Clear Creek T 37,Reach-1,4904
     289     372     436     255     508    1013     688
Boundary for River Rch & Prof#=Clear Creek T 37,Reach-1,1
Up Type=0
Dn Type=3
Dn Slope=0.005
Boundary for River Rch & Prof#=Clear Creek T 37,Reach-1,2
Up Type=0
Dn Type=3
Dn Slope=0.005
Boundary for River Rch & Prof#=Clear Creek T 37,Reach-1,3
Up Type=0
Dn Type=3
Dn Slope=0.005
Boundary for River Rch & Prof#=Clear Creek T 37,Reach-1,4
Up Type=0
Dn Type=3
Dn Slope=0.005
Boundary for River Rch & Prof#=Clear Creek T 37,Reach-1,5
Up Type=0
Dn Type=3
Dn Slope=0.005
Boundary for River Rch & Prof#=Clear Creek T 37,Reach-1,6
Up Type=0
Dn Type=3
Dn Slope=0.005
Boundary for River Rch & Prof#=Clear Creek T 37,Reach-1,7
Up Type=0
Dn Type=3
Dn Slope=0.005

--- Clear Creek T 37.g01 (geometry) ---

Geom Title=Existing Conditions

River Reach=Clear Creek T 37,Reach-1
Reach XY= 30
      2729226.00      6792911.00      2729415.37      6792771.00
      2729481.52      6792558.56      2729559.29      6792477.63
      2729681.93      6792413.25      2729828.45      6792405.53
      2730012.38      6792224.21      2730086.76      6792051.32
      2730562.37      6791524.21      2730764.74      6791220.99
      2730733.80      6791161.10      2730795.43      6790990.34
      2730901.03      6790960.68      2730983.00      6791001.94
      2731031.62      6790916.68      2731162.36      6790824.36
      2731133.81      6790761.10      2731174.62      6790700.56
      2731181.18      6790516.44      2731299.72      6790437.88
      2731427.64      6790264.09      2731478.29      6790266.08
      2731572.67      6790353.73      2731626.00      6790311.00
      2731576.58      6790171.61      2731668.50      6790057.42
      2731536.31      6789971.10      2731526.37      6789876.28
      2731583.86      6789704.83      2731726.00      6789561.00

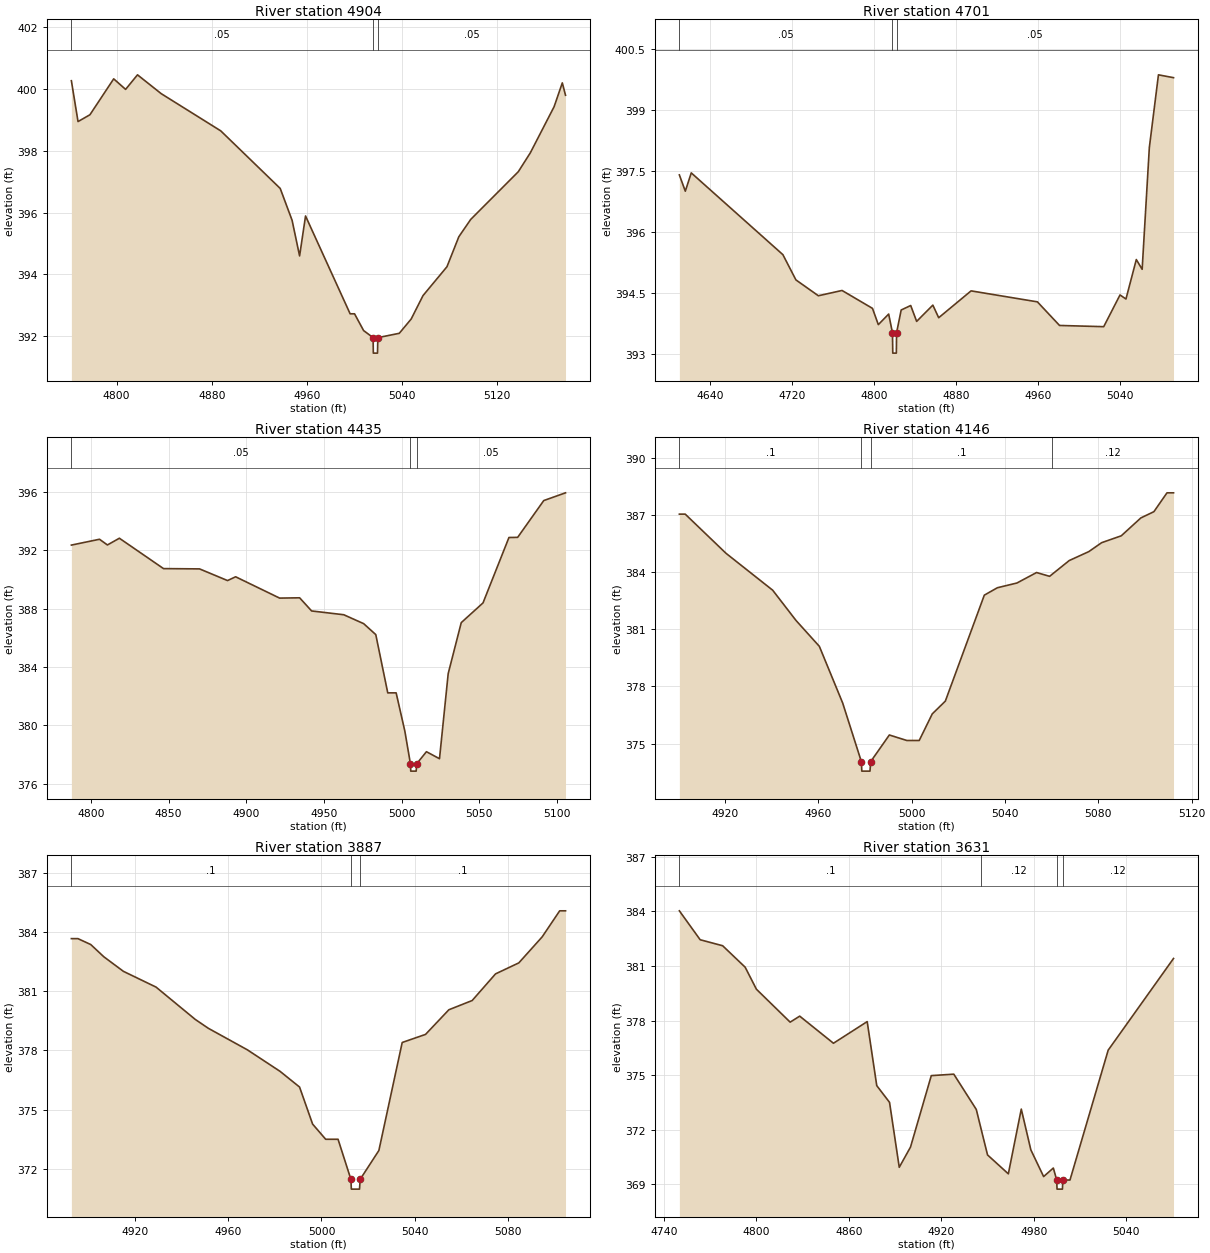
Type RM Length L Ch R = 1,4904,203,203,203
BEGIN DESCRIPTION:
Clear Creek T 37 16.0
END DESCRIPTION:
XS GIS Cut Line= 3
      2729374.71      6793046.61      2729370.14      6792808.56
      2729360.96      6792631.39
#Sta/Elev= 30
  4761.9  400.26  4767.5  398.94  4777.5  399.16  4797.5  400.32  4807.5  399.98
  4817.5  400.45  4837.5  399.84  4887.5  398.64  4937.5  396.78  4947.5  395.75
  4953.8  394.60  4958.8  395.89  4996.3  392.73  5000.0  392.73  5007.6  392.19
  5015.6  391.96  5015.8  391.46  5019.3  391.46  5019.6  391.96  5037.6  392.10
  5047.6  392.56  5057.6  393.32  5077.7  394.25  5087.7  395.22  5097.7  395.78
  5137.7  397.32  5147.8  397.93  5167.8  399.42  5174.7  400.19  5177.4  399.79
#Mann=3,-1,0
  4761.9    0.05       0  5015.6    0.05       0  5019.6    0.05       0
Bank Sta=5015.6,5019.6
Exp/Cntr=0.3,0.1

Type RM Length L Ch R = 1,4701,266,266,266
BEGIN DESCRIPTION:
Clear Creek T 37 15.0
END DESCRIPTION:
XS GIS Cut Line= 3
      2729813.53      6792840.38      2729475.35      6792645.73
      2729395.48      6792600.27
#Sta/Elev= 30
  4609.8  397.40  4615.6  397.00  4621.4  397.45  4710.8  395.44  4723.5  394.82
  4745.4  394.43  4768.5  394.56  4798.2  394.12  4803.9  393.72  4814.0  393.98
  4817.7  393.52  4818.0  393.02  4821.5  393.02  4821.7  393.52  4826.2  394.08
  4835.5  394.19  4841.3  393.80  4857.1  394.20  4862.8  393.89  4894.4  394.55
  4959.1  394.28  4980.7  393.70  5023.8  393.67  5039.7  394.45  5045.5  394.35
  5055.6  395.32  5061.3  395.08  5068.3  398.07  5077.2  399.86  5091.9  399.79
#Mann=3,-1,0
  4609.8    0.05       0  4817.7    0.05       0  4821.7    0.05       0
Bank Sta=4817.7,4821.7
Exp/Cntr=0.3,0.1

Type RM Length L Ch R = 1,4435,289,289,289
BEGIN DESCRIPTION:
Clear Creek T 37 14.0
END DESCRIPTION:
XS GIS Cut Line= 3
      2729676.01      6792661.02      2729626.00      6792461.00
      2729525.98      6792410.99
#Sta/Elev= 30
  4787.4  392.35  4805.5  392.75  4810.6  392.36  4818.3  392.82  4846.7  390.74
  4869.9  390.72  4887.9  389.92  4893.1  390.18  4921.4  388.72  4934.3  388.74
  4942.0  387.84  4962.7  387.58  4975.5  386.97  4983.3  386.22  4991.0  382.23
  4996.4  382.23  5002.0  379.61  5005.6  377.37  5005.8  376.87  5009.3  376.87
  5009.6  377.37  5015.9  378.20  5024.3  377.72  5029.9  383.55  5038.3  387.04
  5052.3  388.39  5069.0  392.87  5074.6  392.88  5091.4  395.40  5105.4  395.93
#Mann=3,-1,0
  4787.4    0.05       0  5005.6    0.04       0  5009.6    0.05       0
Bank Sta=5005.6,5009.6
Exp/Cntr=0.3,0.1

Type RM Length L Ch R = 1,4146,259,259,259
BEGIN DESCRIPTION:
Clear Creek T 37 13.0
END DESCRIPTION:
XS GIS Cut Line= 3
      2729876.00      6792460.99      2729876.00      6792361.00
      2729826.00      6792260.99
#Sta/Elev= 30
  4900.4  387.06  4902.9  387.06  4920.4  385.00  4940.4  383.06  4950.4  381.47
  4960.4  380.11  4970.4  377.13  4978.4  374.05  4978.6  373.55  4982.1  373.55
  4982.4  374.05  4990.4  375.45  4997.9  375.16  5003.2  375.16  5008.8  376.56
  5014.4  377.23  5031.1  382.80  5036.7  383.19  5045.1  383.44  5053.5  383.99
  5059.1  383.79  5060.1  383.89  5067.5  384.62  5075.9  385.09  5081.4  385.56
  5089.8  385.92  5098.2  386.86  5103.8  387.19  5109.4  388.18  5112.2  388.18
#Mann=4,-1,0
  4900.4     0.1       0  4978.4    0.07       0  4982.4     0.1       0
  5060.1    0.12       0
Bank Sta=4978.4,4982.4
Exp/Cntr=0.3,0.1

Type RM Length L Ch R = 1,3887,256,256,256
BEGIN DESCRIPTION:
Clear Creek T 37 12.0
END DESCRIPTION:
XS GIS Cut Line= 3
      2730125.97      6792210.98      2730026.00      6792161.00
      2729925.97      6792161.00
#Sta/Elev= 28
  4892.8  383.67  4895.6  383.67  4901.1  383.37  4906.7  382.75  4915.1  382.01
  4929.1  381.21  4945.9  379.57  4951.5  379.12  4968.2  378.03  4982.2  376.94
  4990.6  376.14  4996.2  374.26  5001.8  373.49  5007.1  373.49  5012.6  371.46
  5012.8  370.96  5016.3  370.96  5016.6  371.46  5024.6  372.92  5034.6  378.40
  5044.6  378.81  5054.6  380.06  5064.6  380.53  5074.6  381.88  5084.6  382.44
  5094.6  383.76  5102.1  385.08  5104.6  385.08
#Mann=3,-1,0
  4892.8     0.1       0  5012.6    0.07       0  5016.6     0.1       0
Bank Sta=5012.6,5016.6
Exp/Cntr=0.3,0.1

Type RM Length L Ch R = 1,3631,255,255,255
BEGIN DESCRIPTION:
Clear Creek T 37 11.0
END DESCRIPTION:
XS GIS Cut Line= 3
      2730375.98      6792110.99      2730176.00      6791961.00
      2730125.99      6791910.99
#Sta/Elev= 30
  4750.0  384.03  4763.5  382.44  4778.1  382.11  4792.7  380.93  4800.0  379.72
  4821.9  377.91  4828.1  378.24  4850.0  376.75  4871.9  377.94  4878.1  374.42
  4886.4  373.50  4892.7  369.93  4900.0  371.04  4913.5  374.97  4928.1  375.05
  4942.7  373.11  4945.9  372.01  4950.0  370.61  4963.5  369.57  4971.9  373.13
  4978.1  370.89  4986.4  369.42  4992.7  369.89  4994.9  369.23  4995.1  368.73
  4998.6  368.73  4998.9  369.23  5003.5  369.23  5028.3  376.37  5070.7  381.41
#Mann=4,-1,0
  4750.0     0.1       0  4945.9    0.12       0  4994.9    0.07       0
  4998.9    0.12       0
Bank Sta=4994.9,4998.9
Exp/Cntr=0.3,0.1

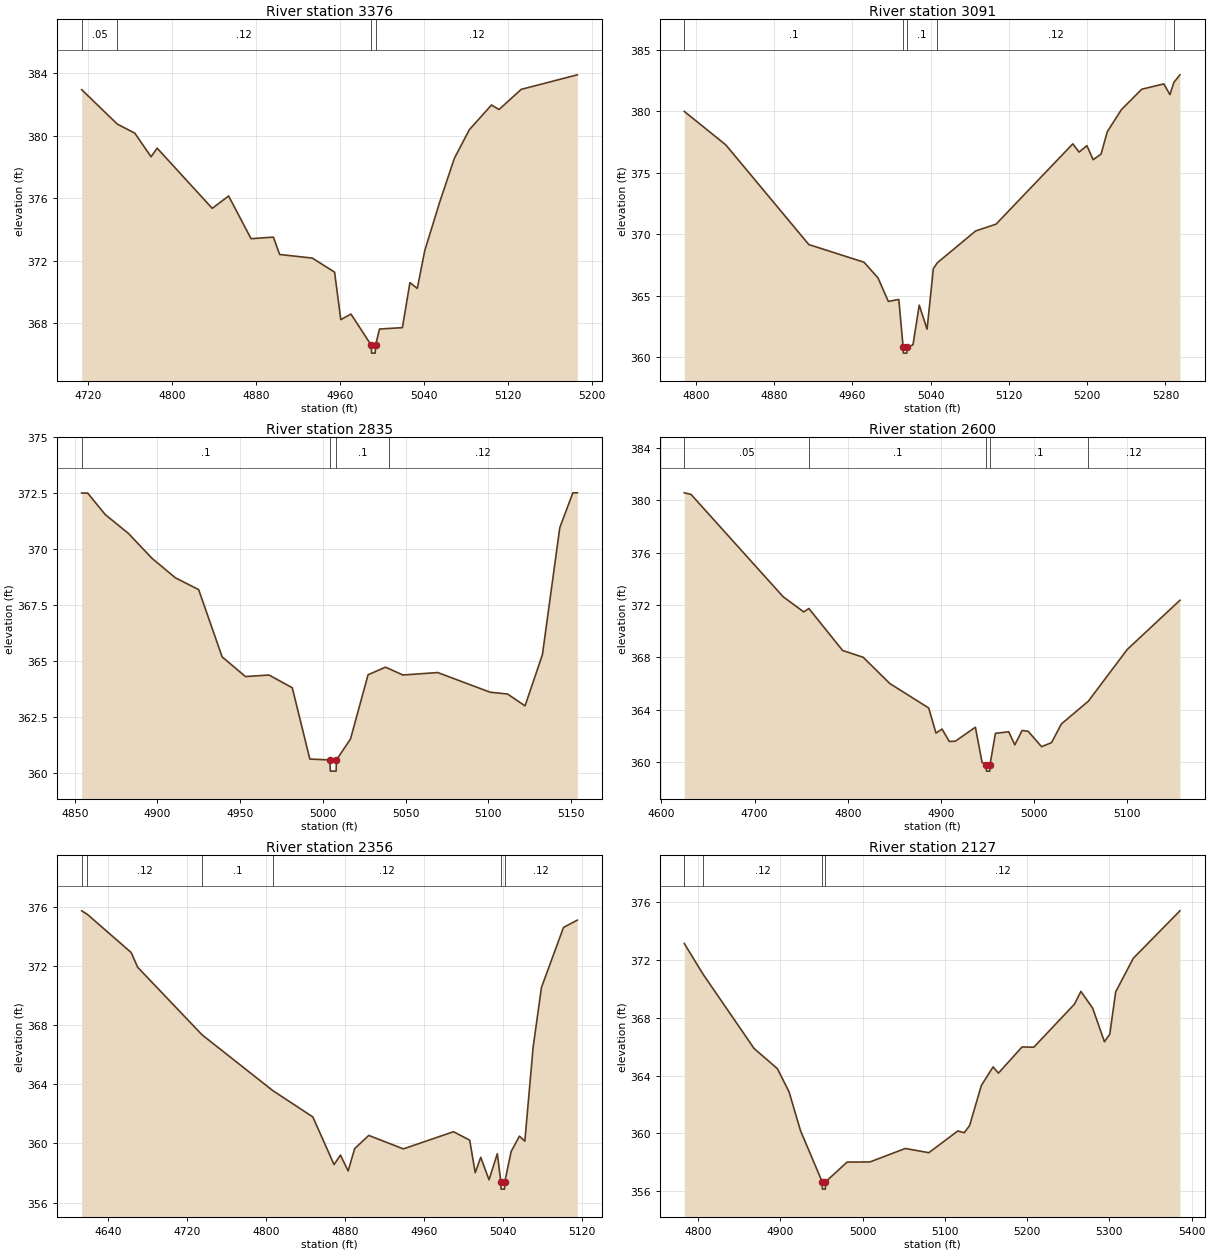
Type RM Length L Ch R = 1,3376,285,285,285
BEGIN DESCRIPTION:
Clear Creek T 37 10.0
END DESCRIPTION:
XS GIS Cut Line= 3
      2730476.02      6792011.03      2730326.00      6791761.00
      2730196.80      6791634.64
#Sta/Elev= 30
  4714.1  382.95  4748.0  380.75  4764.7  380.17  4780.2  378.66  4786.0  379.21
  4838.5  375.36  4854.1  376.15  4875.5  373.42  4896.8  373.52  4902.7  372.41
  4933.8  372.18  4955.1  371.28  4961.0  368.24  4970.7  368.60  4990.1  366.60
  4990.3  366.10  4993.8  366.10  4994.1  366.60  4997.9  367.64  5019.7  367.73
  5026.9  370.61  5033.9  370.24  5041.0  372.65  5055.2  375.75  5069.3  378.57
  5083.5  380.39  5104.6  381.97  5111.8  381.68  5132.9  382.97  5186.4  383.90
#Mann=4,-1,0
  4714.1    0.05       0  4748.0    0.12       0  4990.1    0.07       0
  4994.1    0.12       0
Bank Sta=4990.1,4994.1
Exp/Cntr=0.3,0.1

Type RM Length L Ch R = 1,3091,256,256,256
BEGIN DESCRIPTION:
Clear Creek T 37 9.0
END DESCRIPTION:
XS GIS Cut Line= 3
      2730676.00      6791711.00      2730526.00      6791561.00
      2730295.17      6791378.00
#Sta/Elev= 30
  4788.1  380.00  4830.5  377.28  4915.4  369.16  4971.9  367.72  4986.1  366.45
  4996.7  364.53  5007.4  364.69  5011.8  360.82  5012.1  360.32  5015.6  360.32
  5015.8  360.82  5021.9  360.99  5028.3  364.23  5036.3  362.27  5042.7  367.19
  5046.7  367.67  5086.0  370.27  5106.8  370.82  5185.3  377.36  5191.7  376.69
  5199.7  377.21  5206.1  376.07  5214.2  376.53  5220.5  378.34  5235.0  380.15
  5255.8  381.81  5278.3  382.24  5284.6  381.37  5288.6  382.36  5294.8  382.98
#Mann=5,-1,0
  4788.1     0.1       0  5011.8    0.07       0  5015.8     0.1       0
  5046.7    0.12       0  5288.6    0.05       0
Bank Sta=5011.8,5015.8
Exp/Cntr=0.3,0.1

Type RM Length L Ch R = 1,2835,235,235,235
BEGIN DESCRIPTION:
Clear Creek T 37 8.0
END DESCRIPTION:
XS GIS Cut Line= 3
      2730776.03      6791461.03      2730676.00      6791361.00
      2730525.97      6791310.99
#Sta/Elev= 29
  4854.2  372.51  4857.8  372.51  4868.4  371.55  4882.5  370.70  4896.7  369.59
  4910.8  368.72  4924.9  368.19  4939.1  365.18  4953.2  364.30  4967.4  364.37
  4981.5  363.80  4992.1  360.61  5004.2  360.57  5004.5  360.07  5008.0  360.07
  5008.2  360.57  5016.7  361.51  5027.3  364.38  5037.8  364.72  5040.0  364.65
  5048.4  364.37  5069.4  364.48  5101.1  363.60  5111.6  363.52  5122.2  362.99
  5132.7  365.28  5143.2  370.96  5151.1  372.52  5153.8  372.52
#Mann=4,-1,0
  4854.2     0.1       0  5004.2    0.07       0  5008.2     0.1       0
  5040.0    0.12       0
Bank Sta=5004.2,5008.2
Exp/Cntr=0.3,0.1

Type RM Length L Ch R = 1,2600,244,244,244
BEGIN DESCRIPTION:
Clear Creek T 37 7.0
END DESCRIPTION:
XS GIS Cut Line= 3
      2731026.00      6791411.00      2730726.00      6791161.00
      2730626.03      6791061.03
#Sta/Elev= 30
  4624.6  380.58  4631.8  380.46  4730.7  372.63  4752.8  371.47  4758.3  371.73
  4794.5  368.52  4816.6  368.00  4845.2  365.99  4886.9  364.12  4894.7  362.20
  4901.2  362.51  4909.0  361.56  4915.5  361.58  4937.0  362.65  4944.2  359.95
  4948.7  359.79  4948.9  359.29  4952.4  359.29  4952.7  359.79  4958.5  362.18
  4972.8  362.30  4979.3  361.30  4987.1  362.40  4993.6  362.34  5008.0  361.16
  5018.7  361.47  5029.3  362.90  5058.2  364.64  5100.0  368.60  5156.5  372.36
#Mann=5,-1,0
  4624.6    0.05       0  4758.3     0.1       0  4948.7    0.07       0
  4952.7     0.1       0  5058.2    0.12       0
Bank Sta=4948.7,4952.7
Exp/Cntr=0.3,0.1

Type RM Length L Ch R = 1,2356,229,229,229
BEGIN DESCRIPTION:
Clear Creek T 37 6.0
END DESCRIPTION:
XS GIS Cut Line= 3
      2731076.02      6791261.03      2730826.00      6790961.00
      2730725.96      6790910.98
#Sta/Elev= 30
  4613.3  375.72  4618.9  375.49  4663.5  372.90  4670.0  371.91  4735.3  367.34
  4807.0  363.57  4847.6  361.79  4869.1  358.57  4875.6  359.21  4883.4  358.14
  4890.0  359.65  4904.3  360.54  4939.4  359.63  4990.2  360.79  5006.6  360.22
  5012.2  358.02  5017.8  359.06  5026.2  357.54  5034.6  359.30  5038.2  357.41
  5038.4  356.91  5041.9  356.91  5042.2  357.41  5048.6  359.45  5057.0  360.49
  5062.5  360.15  5070.9  366.50  5079.3  370.53  5101.7  374.60  5115.7  375.09
#Mann=6,-1,0
  4613.3    0.05       0  4618.9    0.12       0  4735.3     0.1       0
  4807.0    0.12       0  5038.2    0.07       0  5042.2    0.12       0
Bank Sta=5038.2,5042.2
Exp/Cntr=0.3,0.1

Type RM Length L Ch R = 1,2127,233,233,233
BEGIN DESCRIPTION:
Clear Creek T 37 5.0
END DESCRIPTION:
XS GIS Cut Line= 3
      2731176.02      6791111.02      2731026.00      6790961.00
      2730725.98      6790710.98
#Sta/Elev= 30
  4783.1  373.13  4805.7  371.03  4868.0  365.87  4896.3  364.48  4910.4  362.89
  4924.5  360.18  4950.8  356.65  4951.1  356.15  4954.6  356.15  4954.8  356.65
  4981.1  358.02  5008.9  358.03  5051.9  358.96  5080.5  358.67  5115.7  360.17
  5123.5  360.05  5130.0  360.54  5144.3  363.31  5158.6  364.60  5165.1  364.17
  5193.8  365.98  5208.1  365.96  5257.6  368.94  5265.4  369.82  5279.7  368.66
  5294.0  366.34  5300.5  366.86  5307.7  369.79  5329.1  372.11  5385.8  375.39
#Mann=4,-1,0
  4783.1    0.05       0  4805.7    0.12       0  4950.8    0.07       0
  4954.8    0.12       0
Bank Sta=4950.8,4954.8
Exp/Cntr=0.3,0.1

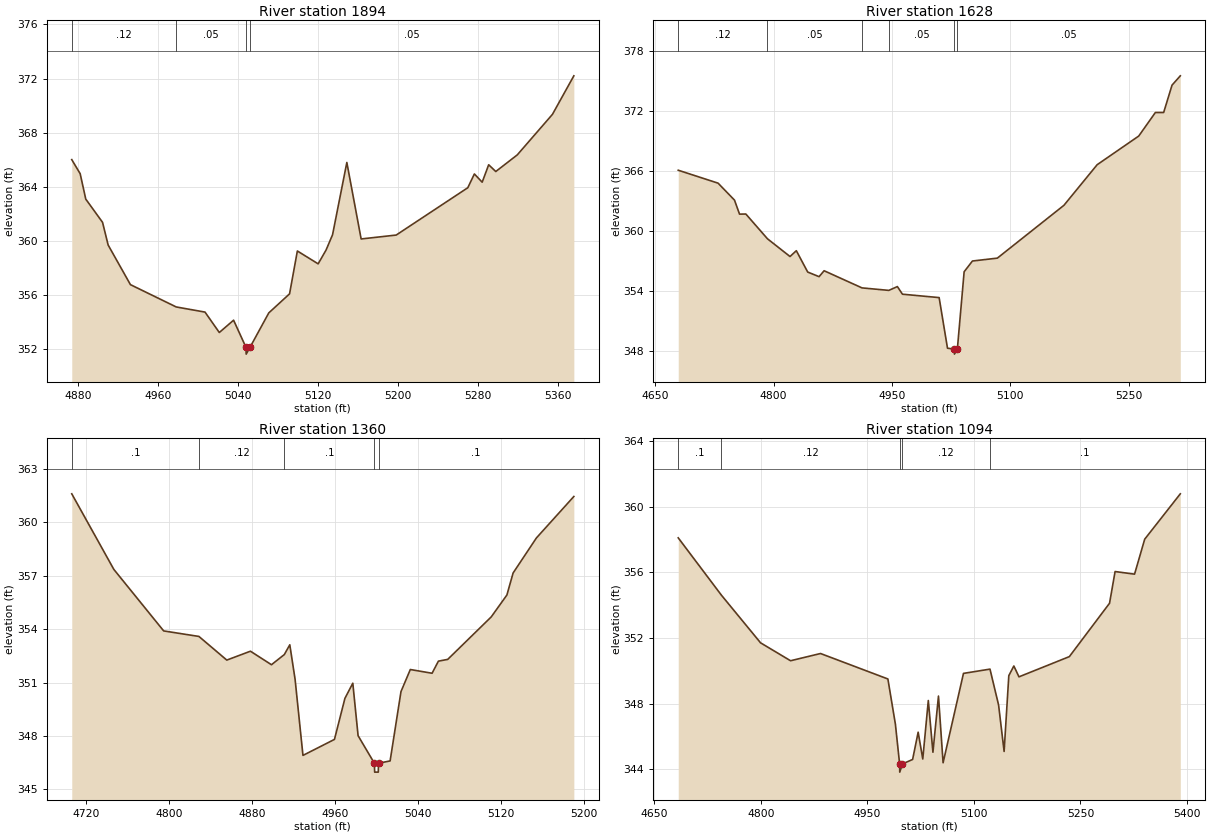
Type RM Length L Ch R = 1,1894,266,266,266
BEGIN DESCRIPTION:
Clear Creek T 37 4.0
END DESCRIPTION:
XS GIS Cut Line= 3
      2731226.01      6790911.02      2731176.00      6790811.00
      2730876.03      6790561.02
#Sta/Elev= 30
  4873.4  366.00  4881.8  364.96  4887.4  363.08  4904.2  361.36  4909.8  359.68
  4932.1  356.75  4977.9  355.10  5006.7  354.72  5021.0  353.21  5035.3  354.12
  5047.7  352.11  5047.9  351.61  5051.7  352.11  5070.5  354.66  5091.3  356.07
  5099.1  359.24  5119.9  358.29  5127.8  359.31  5134.3  360.44  5148.6  365.79
  5162.9  360.13  5198.0  360.42  5269.6  363.92  5276.2  364.94  5284.0  364.33
  5290.5  365.62  5297.6  365.12  5319.1  366.35  5354.3  369.35  5375.7  372.20
#Mann=4,-1,0
  4873.4    0.12       0  4977.9    0.05       0  5047.7    0.04       0
  5051.7    0.05       0
Bank Sta=5047.7,5051.7
Exp/Cntr=0.3,0.1

Type RM Length L Ch R = 1,1628,268,268,268
BEGIN DESCRIPTION:
Clear Creek T 37 3.0
END DESCRIPTION:
XS GIS Cut Line= 3
      2731376.03      6790811.03      2731176.00      6790561.00
      2730876.03      6790461.01
#Sta/Elev= 30
  4679.2  366.06  4729.7  364.77  4750.5  363.08  4756.9  361.68  4764.9  361.69
  4792.3  359.22  4820.9  357.45  4828.9  358.03  4843.3  355.90  4857.7  355.44
  4864.1  356.03  4912.1  354.32  4946.1  354.07  4957.0  354.45  4963.4  353.69
  5009.9  353.35  5020.5  348.30  5029.0  348.21  5029.3  347.71  5033.0  348.21
  5041.6  355.93  5052.1  357.00  5083.7  357.29  5168.1  362.56  5210.2  366.61
  5262.9  369.47  5284.0  371.82  5294.5  371.82  5305.1  374.55  5315.6  375.48
#Mann=6,-1,0
  4679.2    0.12       0  4792.3    0.05       0  4912.1    0.12       0
  4946.1    0.05       0  5029.0    0.05       0  5033.0    0.05       0
Bank Sta=5029,5033
Exp/Cntr=0.3,0.1

Type RM Length L Ch R = 1,1360,266,266,266
BEGIN DESCRIPTION:
Clear Creek T 37 2.0
END DESCRIPTION:
XS GIS Cut Line= 3
      2731376.01      6790661.04      2731326.00      6790361.00
      2731175.96      6790260.98
#Sta/Elev= 30
  4706.0  361.61  4746.6  357.36  4794.7  353.90  4828.7  353.59  4855.6  352.26
  4878.4  352.76  4898.7  352.00  4911.1  352.57  4916.4  353.12  4921.5  351.18
  4929.1  346.90  4959.5  347.80  4969.6  350.11  4977.2  350.96  4982.3  348.01
  4998.0  346.46  4998.3  345.96  5001.8  345.96  5002.0  346.46  5013.2  346.59
  5023.7  350.49  5032.7  351.73  5053.7  351.52  5059.8  352.20  5068.8  352.30
  5110.8  354.69  5125.9  355.92  5131.9  357.16  5154.4  359.13  5190.5  361.46
#Mann=5,-1,0
  4706.0     0.1       0  4828.7    0.12       0  4911.1     0.1       0
  4998.0    0.07       0  5002.0     0.1       0
Bank Sta=4998,5002
Exp/Cntr=0.3,0.1

Type RM Length L Ch R = 1,1094,0,0,0
BEGIN DESCRIPTION:
Clear Creek T 37 1.0
END DESCRIPTION:
XS GIS Cut Line= 3
      2731426.01      6790610.98      2731526.00      6790311.00
      2731276.01      6790011.01
#Sta/Elev= 30
  4683.8  358.10  4744.6  354.61  4799.7  351.71  4841.9  350.62  4884.1  351.06
  4978.9  349.51  4989.5  346.75  4995.4  344.34  4995.6  343.84  4999.4  344.34
  5013.7  344.61  5021.5  346.27  5028.0  344.64  5035.8  348.20  5042.3  345.05
  5050.1  348.47  5056.6  344.41  5085.3  349.85  5122.6  350.11  5134.7  347.93
  5142.5  345.10  5149.1  349.71  5156.2  350.30  5163.4  349.64  5234.3  350.87
  5290.9  354.12  5298.7  356.05  5326.1  355.89  5340.4  358.02  5390.5  360.78
#Mann=5,-1,0
  4683.8     0.1       0  4744.6    0.12       0  4995.4    0.07       0
  4999.4    0.12       0  5122.6     0.1       0
Bank Sta=4995.4,4999.4
Exp/Cntr=0.3,0.1

Chan Stop Cuts=-1