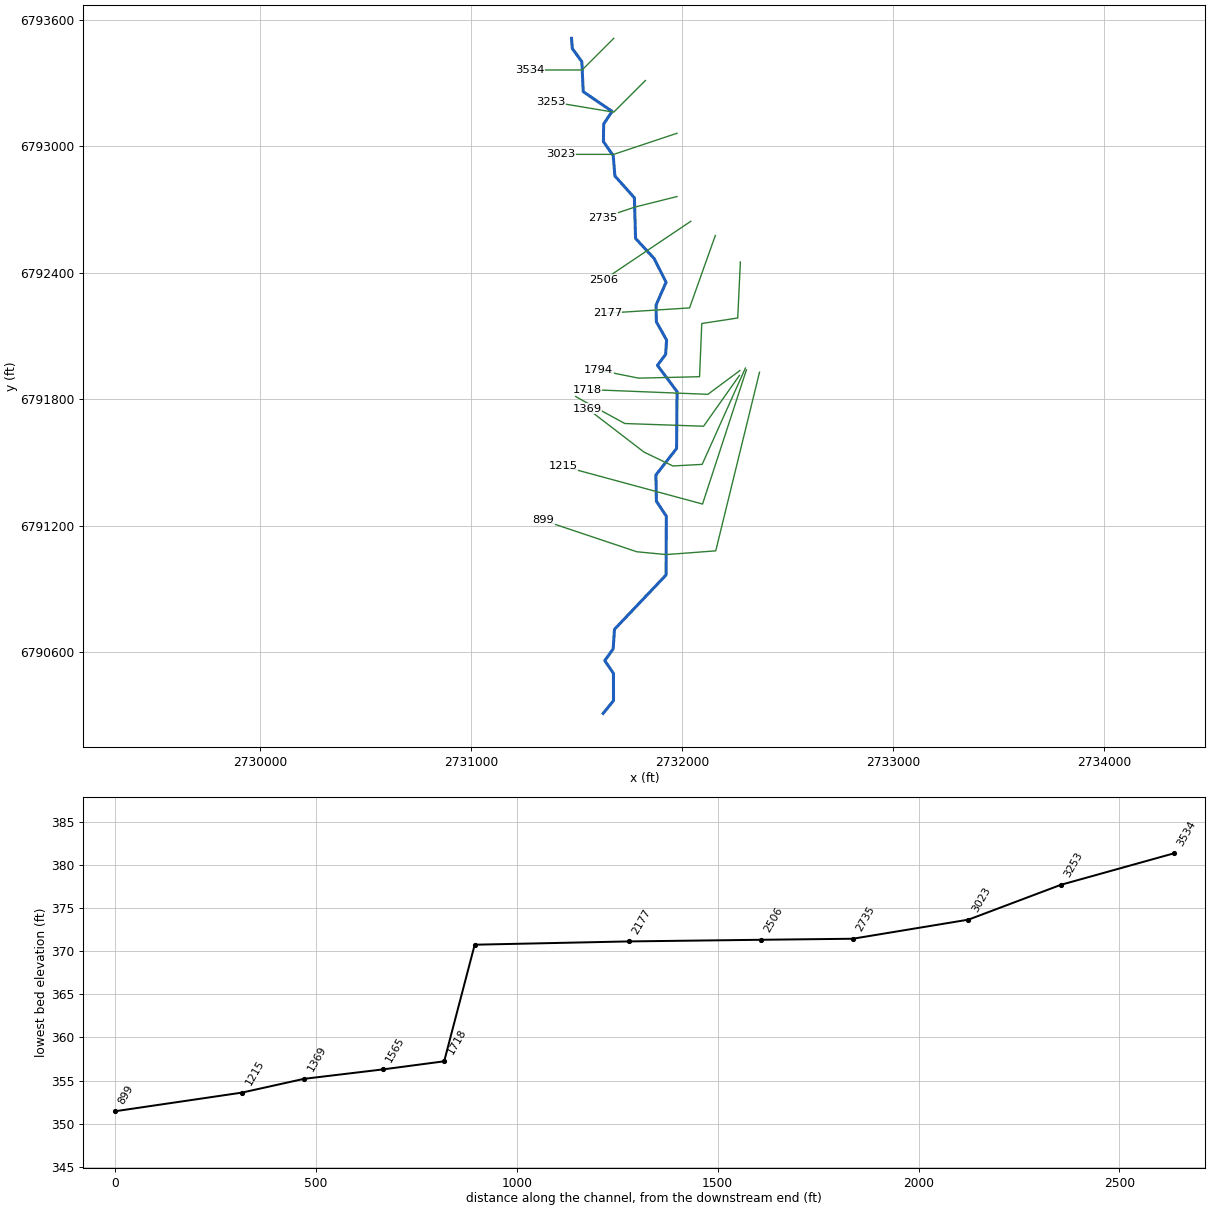
--- Clear Creek T 38.prj (project) ---

Proj Title=Clear Creek T 38 Base Level Engineering
Current Plan=p01
Default Exp/Contr=0.3,0.1
English Units
Geom File=g01
Flow File=f01
Plan File=p01
BEGIN DESCRIPTION:
Clear Creek T 38
END DESCRIPTION:

--- Clear Creek T 38.p01 (plan) ---

Plan Title=Multiple Run
Short Identifier=Multiple
Geom File=g01
Flow File=f01
Subcritical Flow
K Sum by GR= 0
Std Step Tol= 0.01
Critical Tol= 0.01
Num of Std Step Trials= 20
Max Error Tol= 0.3
Flow Tol Ratio= 0.001
Split Flow NTrial= 30
Split Flow Tol= 0.02
Split Flow Ratio= 0.02
Log Output Level= 0
Friction Slope Method= 1
Unsteady Friction Slope Method= 2
Unsteady Bridges Friction Slope Method= 1
Parabolic Critical Depth
Global Vel Dist=  1 , 1 , 1
Global Log Level= 0
CheckData=True
Encroach Param= -1, 0, 0, 0
BEGIN DESCRIPTION:
Multiple Run
END DESCRIPTION:

--- Clear Creek T 38.f01 (steady flow) ---

Flow Title=Multiple
Number of Profiles=7
Profile Names=10-year,25-year,50-year,1pct_min,100-year,1pct_plu,500-year
River Rch & RM= Clear Creek T 38,Reach-1,3534
     186     231     264     151     302     602     391
Boundary for River Rch & Prof#=Clear Creek T 38,Reach-1,1
Up Type=0
Dn Type=3
Dn Slope=0.005
Boundary for River Rch & Prof#=Clear Creek T 38,Reach-1,2
Up Type=0
Dn Type=3
Dn Slope=0.005
Boundary for River Rch & Prof#=Clear Creek T 38,Reach-1,3
Up Type=0
Dn Type=3
Dn Slope=0.005
Boundary for River Rch & Prof#=Clear Creek T 38,Reach-1,4
Up Type=0
Dn Type=3
Dn Slope=0.005
Boundary for River Rch & Prof#=Clear Creek T 38,Reach-1,5
Up Type=0
Dn Type=3
Dn Slope=0.005
Boundary for River Rch & Prof#=Clear Creek T 38,Reach-1,6
Up Type=0
Dn Type=3
Dn Slope=0.005
Boundary for River Rch & Prof#=Clear Creek T 38,Reach-1,7
Up Type=0
Dn Type=3
Dn Slope=0.005

--- Clear Creek T 38.g01 (geometry) ---

Geom Title=Existing Conditions

River Reach=Clear Creek T 38,Reach-1
Reach XY= 30
      2731476.00      6793511.00      2731479.65      6793462.51
      2731524.87      6793400.53      2731531.37      6793258.30
      2731668.30      6793164.67      2731628.38      6793105.12
      2731627.11      6793021.55      2731673.64      6792955.02
      2731681.54      6792858.58      2731773.93      6792755.14
      2731779.55      6792562.47      2731867.84      6792467.05
      2731924.20      6792354.89      2731876.40      6792245.73
      2731878.17      6792166.97      2731926.58      6792081.04
      2731922.05      6792012.50      2731883.33      6791960.90
      2731976.29      6791836.12      2731973.93      6791566.86
      2731875.94      6791441.01      2731878.25      6791316.94
      2731925.48      6791245.78      2731923.94      6790966.85
      2731679.61      6790709.50      2731673.44      6790616.90
      2731633.56      6790561.00      2731674.63      6790500.56
      2731675.05      6790371.41      2731626.00      6790311.00

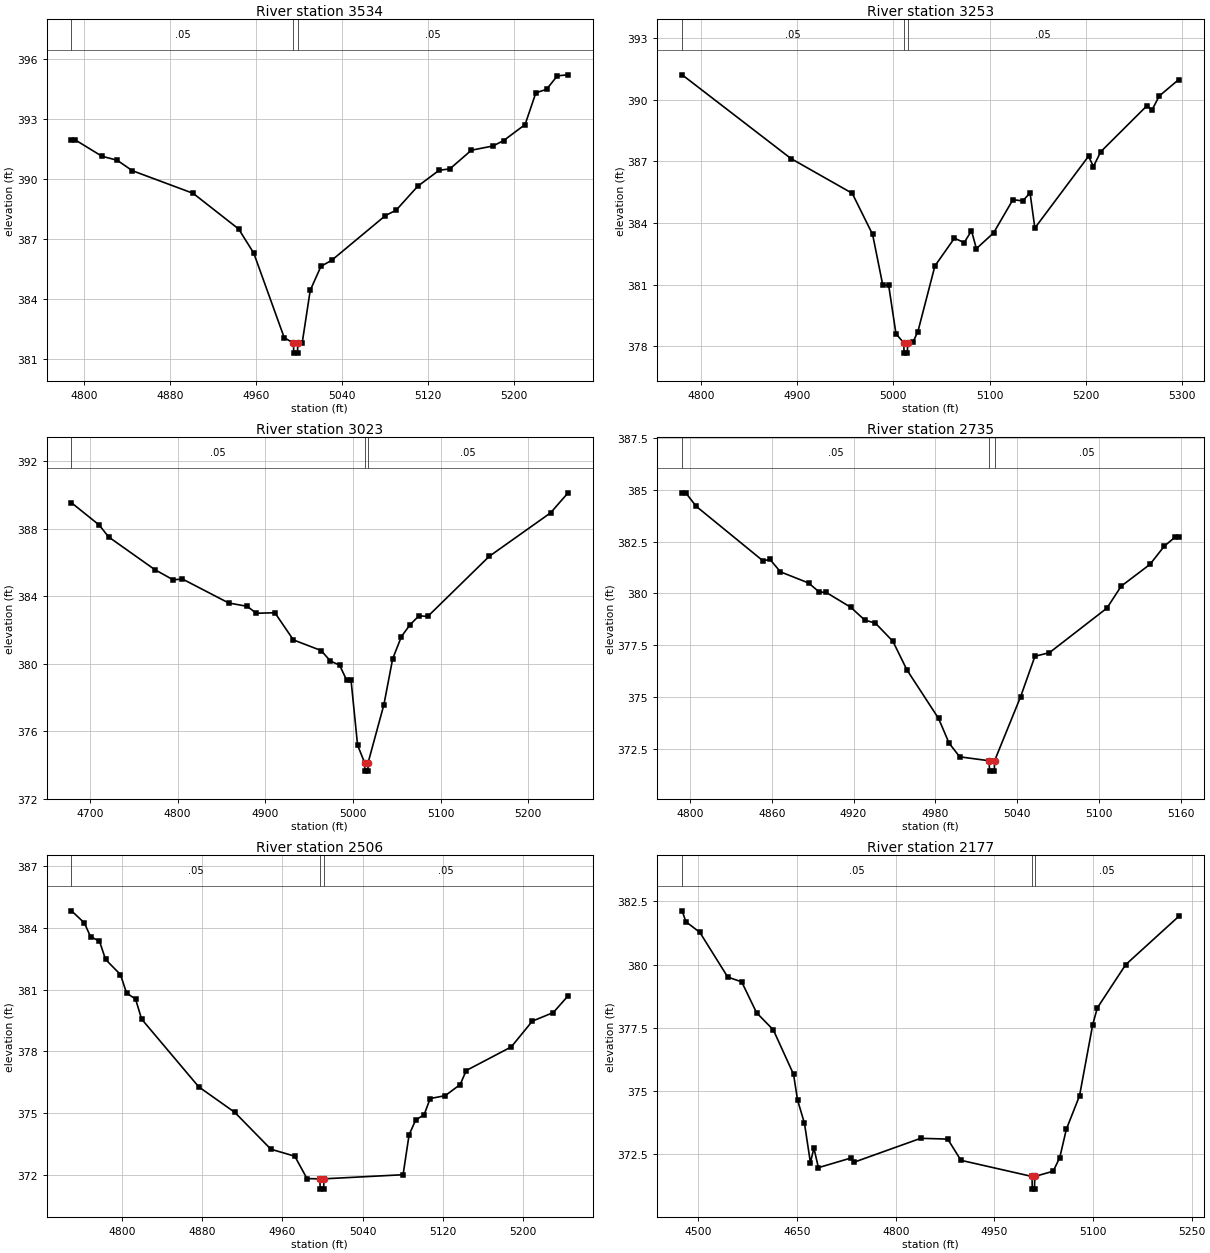
Type RM Length L Ch R = 1,3534,281,281,281
BEGIN DESCRIPTION:
2191
END DESCRIPTION:
XS GIS Cut Line= 3
      2731676.02      6793511.02      2731526.00      6793361.00
      2731275.97      6793361.00
#Sta/Elev= 30
  4788.3  391.94  4791.9  391.94  4816.6  391.13  4830.8  390.93  4844.9  390.41
  4901.5  389.28  4943.9  387.50  4958.0  386.29  4986.3  382.08  4994.9  381.81
  4995.2  381.31  4998.7  381.31  4998.9  381.81  5003.0  381.81  5010.5  384.44
  5020.5  385.64  5030.5  385.94  5080.5  388.17  5090.5  388.44  5110.5  389.63
  5130.5  390.43  5140.5  390.50  5160.5  391.43  5180.5  391.64  5190.5  391.91
  5210.5  392.71  5220.5  394.29  5230.5  394.47  5240.5  395.14  5250.5  395.19
#Mann=3,-1,0
  4788.3    0.05       0  4994.9    0.04       0  4998.9    0.05       0
Bank Sta=4994.9,4998.9
Exp/Cntr=0.3,0.1

Type RM Length L Ch R = 1,3253,230,230,230
BEGIN DESCRIPTION:
2190
END DESCRIPTION:
XS GIS Cut Line= 3
      2731826.01      6793311.01      2731676.00      6793161.00
      2731375.98      6793211.00
#Sta/Elev= 30
  4780.4  391.20  4893.5  387.13  4957.2  385.44  4978.4  383.44  4989.0  380.97
  4995.1  380.97  5002.7  378.61  5010.8  378.17  5011.1  377.67  5014.6  377.67
  5014.8  378.17  5020.4  378.21  5025.5  378.72  5043.2  381.91  5063.5  383.26
  5073.6  383.04  5081.2  383.62  5086.3  382.75  5104.1  383.51  5124.3  385.13
  5134.5  385.07  5142.1  385.46  5147.1  383.75  5202.9  387.24  5208.0  386.74
  5215.6  387.46  5263.7  389.70  5268.8  389.48  5276.4  390.17  5296.7  390.97
#Mann=3,-1,0
  4780.4    0.05       0  5010.8    0.04       0  5014.8    0.05       0
Bank Sta=5010.8,5014.8
Exp/Cntr=0.3,0.1

Type RM Length L Ch R = 1,3023,288,288,288
BEGIN DESCRIPTION:
2189
END DESCRIPTION:
XS GIS Cut Line= 3
      2731976.01      6793061.00      2731676.00      6792961.00
      2731426.04      6792961.00
#Sta/Elev= 30
  4679.1  389.55  4710.7  388.23  4721.3  387.53  4774.0  385.59  4795.1  384.98
  4805.6  385.03  4858.3  383.61  4879.4  383.41  4889.9  383.00  4911.0  383.03
  4932.1  381.42  4963.7  380.79  4974.3  380.17  4984.8  379.92  4992.7  379.05
  4997.8  379.05  5005.3  375.18  5013.3  374.14  5013.6  373.64  5017.1  373.64
  5017.3  374.14  5035.3  377.58  5045.3  380.30  5055.3  381.62  5065.3  382.33
  5075.3  382.85  5085.3  382.81  5155.3  386.37  5225.3  388.95  5245.3  390.14
#Mann=3,-1,0
  4679.1    0.05       0  5013.3    0.04       0  5017.3    0.05       0
Bank Sta=5013.3,5017.3
Exp/Cntr=0.3,0.1

Type RM Length L Ch R = 1,2735,229,229,229
BEGIN DESCRIPTION:
2188
END DESCRIPTION:
XS GIS Cut Line= 3
      2731975.99      6792761.00      2731776.00      6792711.00
      2731625.96      6792660.99
#Sta/Elev= 30
  4794.3  384.85  4796.9  384.85  4804.6  384.20  4853.6  381.57  4858.7  381.64
  4866.4  381.04  4887.1  380.50  4894.8  380.07  4899.9  380.05  4918.0  379.33
  4928.3  378.71  4936.0  378.57  4948.9  377.69  4959.2  376.31  4982.4  373.97
  4990.1  372.78  4997.9  372.12  5019.5  371.93  5019.8  371.43  5023.3  371.43
  5023.5  371.93  5042.6  375.02  5053.1  376.97  5063.7  377.14  5105.9  379.29
  5116.4  380.35  5137.5  381.40  5148.0  382.28  5155.9  382.71  5158.6  382.71
#Mann=3,-1,0
  4794.3    0.05       0  5019.5    0.04       0  5023.5    0.05       0
Bank Sta=5019.5,5023.5
Exp/Cntr=0.3,0.1

Type RM Length L Ch R = 1,2506,329,329,329
BEGIN DESCRIPTION:
2257
END DESCRIPTION:
XS GIS Cut Line= 2
      2732041.20      6792643.58      2731629.71      6792367.18
#Sta/Elev= 30
  4749.5  384.83  4762.4  384.24  4768.5  383.57  4777.4  383.36  4783.5  382.47
  4798.4  381.73  4804.5  380.83  4813.4  380.55  4819.5  379.57  4876.5  376.28
  4912.5  375.04  4948.5  373.25  4972.4  372.91  4984.6  371.82  4997.5  371.81
  4997.7  371.31  5001.2  371.31  5001.5  371.81  5080.5  372.01  5086.5  373.95
  5093.1  374.67  5101.5  374.92  5107.5  375.71  5122.5  375.85  5137.5  376.39
  5143.5  377.07  5188.5  378.22  5209.5  379.47  5230.5  379.89  5245.2  380.70
#Mann=3,-1,0
  4749.5    0.05       0  4997.5    0.04       0  5001.5    0.05       0
Bank Sta=4997.5,5001.5
Exp/Cntr=0.3,0.1

Type RM Length L Ch R = 1,2177,383,383,383
BEGIN DESCRIPTION:
2256
END DESCRIPTION:
XS GIS Cut Line= 3
      2732157.60      6792576.25      2732035.45      6792233.04
      2731645.44      6792208.28
#Sta/Elev= 30
  4475.2  382.13  4480.8  381.70  4502.0  381.28  4544.5  379.51  4565.7  379.32
  4588.3  378.10  4613.8  377.42  4644.6  375.66  4650.6  374.65  4661.2  373.72
  4670.2  372.17  4675.5  372.74  4682.4  371.97  4731.8  372.35  4737.1  372.19
  4837.9  373.13  4879.0  373.10  4899.1  372.26  5007.3  371.62  5007.5  371.12
  5011.0  371.12  5011.3  371.62  5039.4  371.83  5049.4  372.37  5059.4  373.49
  5079.4  374.81  5099.5  377.63  5106.5  378.29  5149.6  380.00  5230.3  381.91
#Mann=3,-1,0
  4475.2    0.05       0  5007.3    0.04       0  5011.3    0.05       0
Bank Sta=5007.3,5011.3
Exp/Cntr=0.3,0.1

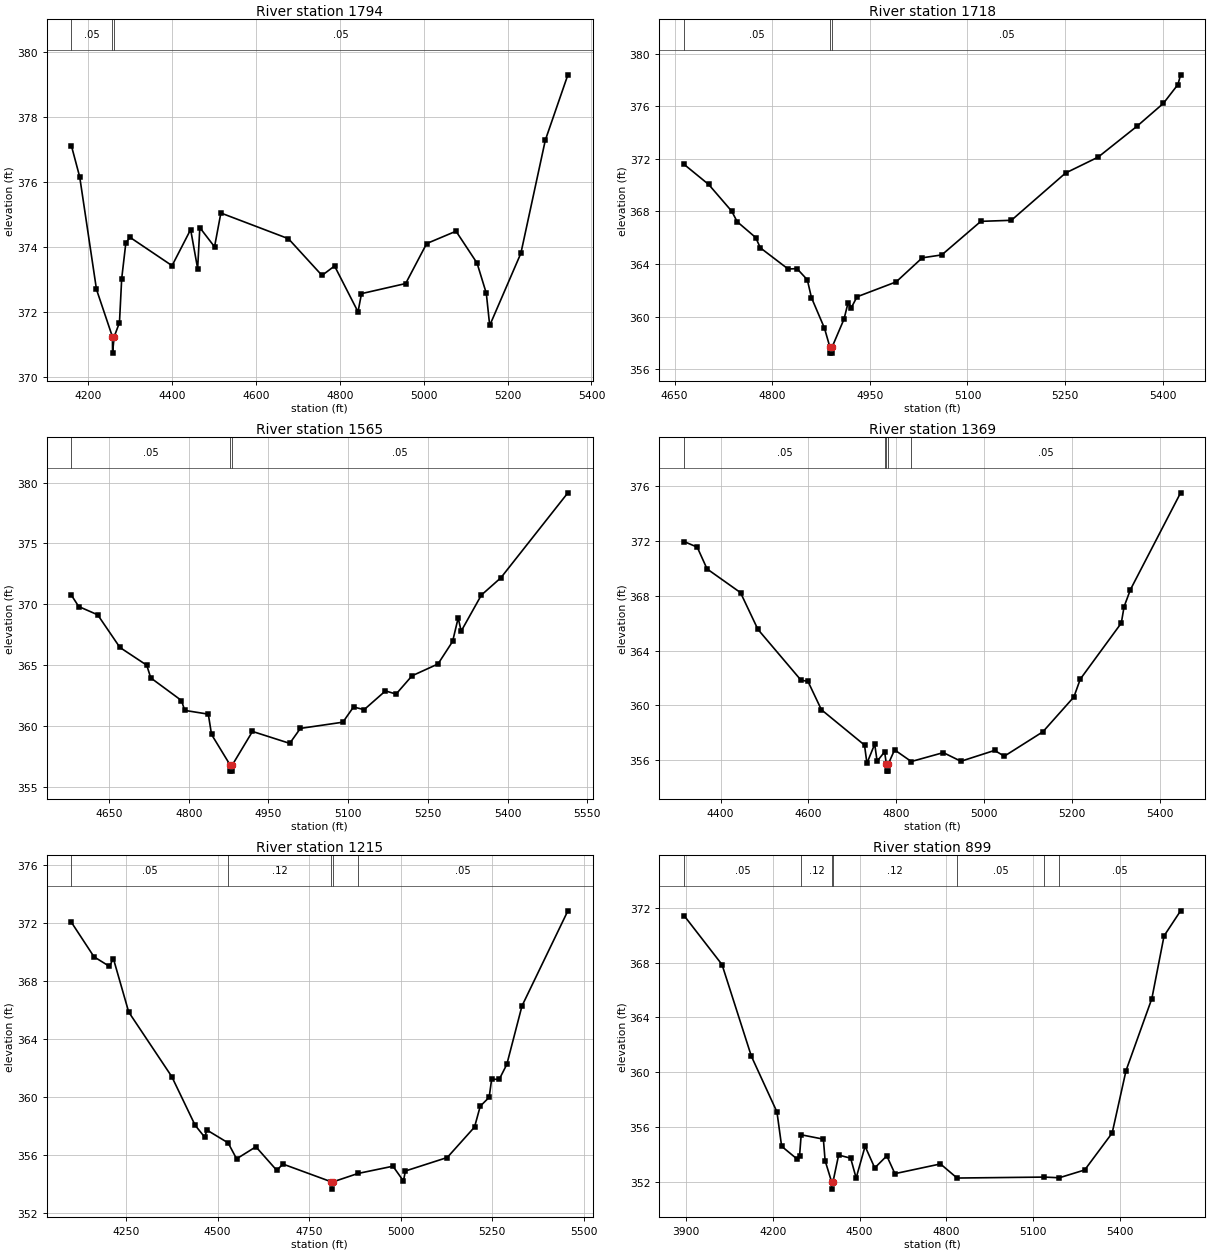
Type RM Length L Ch R = 1,1794,76,76,76
BEGIN DESCRIPTION:
2345
END DESCRIPTION:
XS GIS Cut Line= 6
      2732276.38      6792450.58      2732263.86      6792185.27
      2732093.44      6792159.18      2732082.82      6791906.96
      2731793.87      6791900.16      2731603.22      6791938.53
#Sta/Elev= 30
  4160.2  377.11  4179.8  376.16  4219.8  372.70  4257.9  371.24  4258.1  370.74
  4261.9  371.24  4274.6  371.68  4279.9  373.03  4289.9  374.14  4299.9  374.30
  4400.0  373.43  4444.3  374.54  4461.0  373.34  4466.2  374.60  4501.3  374.01
  4516.4  375.05  4677.4  374.26  4757.5  373.13  4787.5  373.42  4843.4  372.01
  4851.7  372.57  4957.0  372.88  5007.1  374.11  5077.1  374.49  5127.2  373.51
  5149.3  372.58  5157.4  371.59  5231.7  373.81  5290.0  377.29  5343.8  379.30
#Mann=3,-1,0
  4160.2    0.05       0  4257.9    0.04       0  4261.9    0.05       0
Bank Sta=4257.9,4261.9
Exp/Cntr=0.3,0.1

Type RM Length L Ch R = 1,1718,153,153,153
BEGIN DESCRIPTION:
2344
END DESCRIPTION:
XS GIS Cut Line= 3
      2732274.17      6791936.17      2732122.30      6791823.46
      2731549.48      6791846.26
#Sta/Elev= 30
  4664.9  371.57  4702.5  370.05  4737.9  368.02  4746.3  367.22  4774.7  366.02
  4781.8  365.24  4824.5  363.63  4838.1  363.66  4854.0  362.81  4860.3  361.46
  4880.3  359.14  4888.4  357.74  4888.6  357.24  4892.1  357.24  4892.4  357.74
  4910.4  359.83  4916.6  361.07  4921.6  360.70  4930.4  361.52  4990.4  362.65
  5030.5  364.48  5060.5  364.70  5120.5  367.25  5167.4  367.33  5250.6  370.92
  5300.7  372.13  5360.7  374.49  5400.8  376.21  5423.2  377.64  5427.3  378.38
#Mann=3,-1,0
  4664.9    0.05       0  4888.4    0.04       0  4892.4    0.05       0
Bank Sta=4888.4,4892.4
Exp/Cntr=0.3,0.1

Type RM Length L Ch R = 1,1565,196,196,196
BEGIN DESCRIPTION:
2507
END DESCRIPTION:
XS GIS Cut Line= 5
      2732271.79      6791912.86      2732102.01      6791672.25
      2731728.86      6791684.99      2731547.41      6791783.99
      2731495.56      6791812.89
#Sta/Elev= 30
  4579.5  370.74  4593.1  369.82  4628.8  369.14  4670.6  366.46  4721.1  365.00
  4728.6  363.96  4786.4  362.10  4792.5  361.29  4836.9  360.98  4843.0  359.31
  4878.0  356.80  4878.2  356.30  4881.7  356.30  4882.0  356.80  4920.0  359.56
  4990.1  358.58  5010.1  359.81  5090.1  360.32  5110.1  361.57  5130.1  361.35
  5170.2  362.89  5190.2  362.63  5220.2  364.13  5269.0  365.10  5296.5  366.95
  5307.0  368.88  5312.7  367.80  5350.6  370.76  5387.3  372.18  5513.4  379.16
#Mann=3,-1,0
  4579.5    0.05       0  4878.0    0.04       0  4882.0    0.05       0
Bank Sta=4878,4882
Exp/Cntr=0.3,0.1

Type RM Length L Ch R = 1,1369,154,154,154
BEGIN DESCRIPTION:
2506
END DESCRIPTION:
XS GIS Cut Line= 5
      2732300.23      6791947.98      2732095.30      6791491.38
      2731956.57      6791483.82      2731819.77      6791549.44
      2731550.96      6791755.93
#Sta/Elev= 30
  4317.1  371.95  4346.7  371.55  4369.1  369.96  4445.3  368.23  4484.9  365.55
  4583.1  361.84  4598.8  361.76  4629.4  359.69  4727.6  357.11  4733.1  355.78
  4750.8  357.18  4756.3  355.93  4773.4  356.62  4777.4  355.71  4777.7  355.21
  4781.2  355.21  4781.4  355.71  4796.1  356.76  4834.1  355.91  4907.0  356.56
  4947.1  355.93  5023.7  356.72  5045.9  356.30  5133.7  358.08  5204.3  360.62
  5218.8  361.92  5312.2  366.01  5318.5  367.20  5333.0  368.45  5447.2  375.51
#Mann=5,-1,0
  4317.1    0.05       0  4773.4    0.12       0  4777.4    0.04       0
  4781.4    0.12       0  4834.1    0.05       0
Bank Sta=4777.4,4781.4
Exp/Cntr=0.3,0.1

Type RM Length L Ch R = 1,1215,316,316,316
BEGIN DESCRIPTION:
2343
END DESCRIPTION:
XS GIS Cut Line= 3
      2732304.95      6791939.44      2732097.02      6791303.33
      2731435.10      6791482.60
#Sta/Elev= 30
  4101.3  372.01  4162.8  369.64  4204.9  368.98  4215.6  369.52  4257.5  365.83
  4375.0  361.38  4438.7  358.03  4465.3  357.19  4470.6  357.70  4528.8  356.81
  4552.0  355.71  4604.7  356.54  4661.8  354.91  4678.3  355.35  4811.0  354.12
  4811.3  353.62  4815.0  354.12  4883.4  354.70  4978.8  355.20  5007.5  354.18
  5012.7  354.87  5127.0  355.80  5201.5  357.90  5217.1  359.34  5241.4  359.95
  5248.2  361.20  5268.9  361.19  5289.6  362.22  5331.0  366.25  5456.3  372.81
#Mann=5,-1,0
  4101.3    0.05       0  4528.8    0.12       0  4811.0    0.04       0
  4815.0    0.12       0  4883.4    0.05       0
Bank Sta=4811,4815
Exp/Cntr=0.3,0.1

Type RM Length L Ch R = 1,899,0,0,0
BEGIN DESCRIPTION:
2187
END DESCRIPTION:
XS GIS Cut Line= 5
      2732367.03      6791927.97      2732159.62      6791081.40
      2731924.94      6791063.82      2731785.48      6791077.10
      2731341.88      6791225.82
#Sta/Elev= 30
  3894.2  371.43  4024.9  367.86  4126.2  361.17  4214.6  357.10  4230.8  354.59
  4282.3  353.69  4292.6  353.85  4298.3  355.43  4375.0  355.11  4381.0  353.54
  4403.9  351.96  4404.1  351.46  4407.9  351.96  4427.7  353.95  4469.3  353.72
  4488.2  352.27  4519.1  354.59  4552.5  353.01  4594.1  353.89  4622.1  352.59
  4779.5  353.30  4836.9  352.27  5138.4  352.34  5190.0  352.29  5277.8  352.86
  5372.7  355.56  5420.6  360.12  5509.8  365.38  5552.0  369.96  5609.1  371.79
#Mann=7,-1,0
  3894.2    0.05       0  4298.3    0.12       0  4403.9    0.04       0
  4407.9    0.12       0  4836.9    0.05       0  5138.4    0.12       0
  5190.0    0.05       0
Bank Sta=4403.9,4407.9
Exp/Cntr=0.3,0.1

Chan Stop Cuts=-1