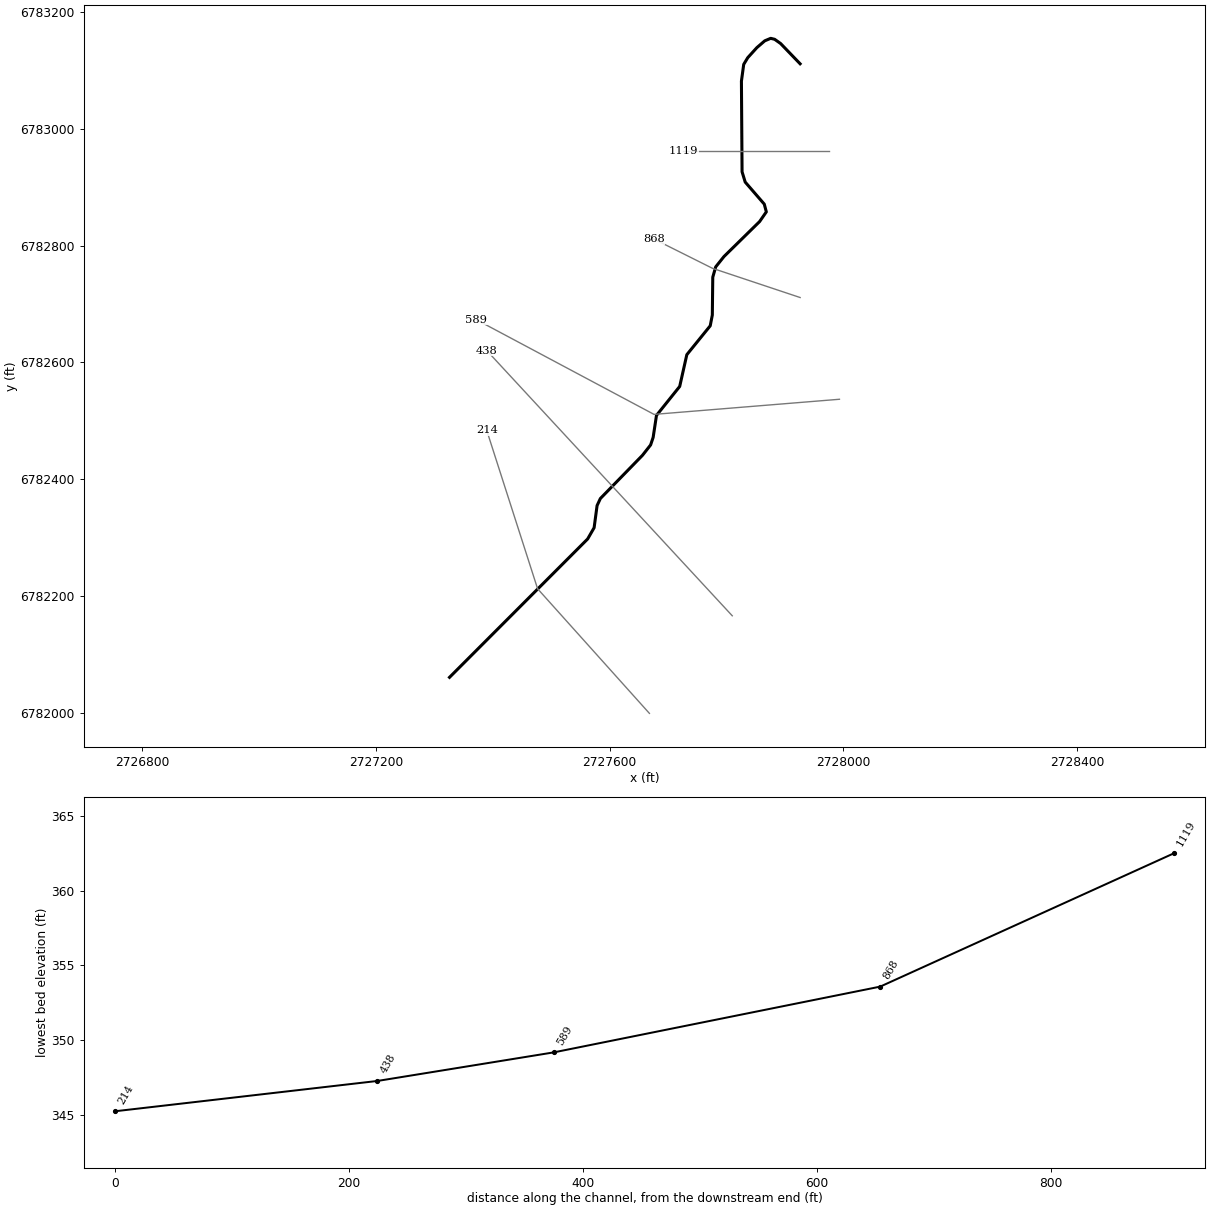
--- Clear Creek T 39.prj (project) ---

Proj Title=Clear Creek T 39 Base Level Engineering
Current Plan=p01
Default Exp/Contr=0.3,0.1
English Units
Geom File=g01
Flow File=f01
Plan File=p01
BEGIN DESCRIPTION:
Clear Creek T 39
END DESCRIPTION:

--- Clear Creek T 39.p01 (plan) ---

Plan Title=Multiple Run
Short Identifier=Multiple
Geom File=g01
Flow File=f01
Subcritical Flow
K Sum by GR= 0
Std Step Tol= 0.01
Critical Tol= 0.01
Num of Std Step Trials= 20
Max Error Tol= 0.3
Flow Tol Ratio= 0.001
Split Flow NTrial= 30
Split Flow Tol= 0.02
Split Flow Ratio= 0.02
Log Output Level= 0
Friction Slope Method= 1
Unsteady Friction Slope Method= 2
Unsteady Bridges Friction Slope Method= 1
Parabolic Critical Depth
Global Vel Dist=  1 , 1 , 1
Global Log Level= 0
CheckData=True
Encroach Param= -1, 0, 0, 0
BEGIN DESCRIPTION:
Multiple Run
END DESCRIPTION:

--- Clear Creek T 39.f01 (steady flow) ---

Flow Title=Multiple
Number of Profiles=7
Profile Names=10-year,25-year,50-year,1pct_min,100-year,1pct_plu,500-year
River Rch & RM= Clear Creek T 39,Reach-1,1119
     219     277     320     185     369     737     489
Boundary for River Rch & Prof#=Clear Creek T 39,Reach-1,1
Up Type=0
Dn Type=3
Dn Slope=0.005
Boundary for River Rch & Prof#=Clear Creek T 39,Reach-1,2
Up Type=0
Dn Type=3
Dn Slope=0.005
Boundary for River Rch & Prof#=Clear Creek T 39,Reach-1,3
Up Type=0
Dn Type=3
Dn Slope=0.005
Boundary for River Rch & Prof#=Clear Creek T 39,Reach-1,4
Up Type=0
Dn Type=3
Dn Slope=0.005
Boundary for River Rch & Prof#=Clear Creek T 39,Reach-1,5
Up Type=0
Dn Type=3
Dn Slope=0.005
Boundary for River Rch & Prof#=Clear Creek T 39,Reach-1,6
Up Type=0
Dn Type=3
Dn Slope=0.005
Boundary for River Rch & Prof#=Clear Creek T 39,Reach-1,7
Up Type=0
Dn Type=3
Dn Slope=0.005

--- Clear Creek T 39.g01 (geometry) ---

Geom Title=Existing Conditions

River Reach=Clear Creek T 39,Reach-1
Reach XY= 30
      2727926.00      6783111.00      2727892.62      6783145.67
      2727882.42      6783152.91      2727875.67      6783154.56
      2727865.52      6783150.31      2727852.05      6783138.71
      2727836.39      6783121.47      2727829.48      6783109.97
      2727825.56      6783081.31      2727826.66      6782926.16
      2727832.03      6782908.55      2727864.66      6782870.85
      2727868.19      6782857.59      2727856.67      6782840.98
      2727795.71      6782781.15      2727781.55      6782763.43
      2727776.53      6782745.78      2727775.76      6782681.10
      2727772.17      6782662.59      2727732.12      6782613.18
      2727719.92      6782558.80      2727680.19      6782509.26
      2727674.49      6782471.63      2727670.15      6782458.71
      2727656.18      6782440.93      2727584.18      6782367.04
      2727578.54      6782354.95      2727573.47      6782317.05
      2727562.37      6782297.79      2727326.00      6782061.00

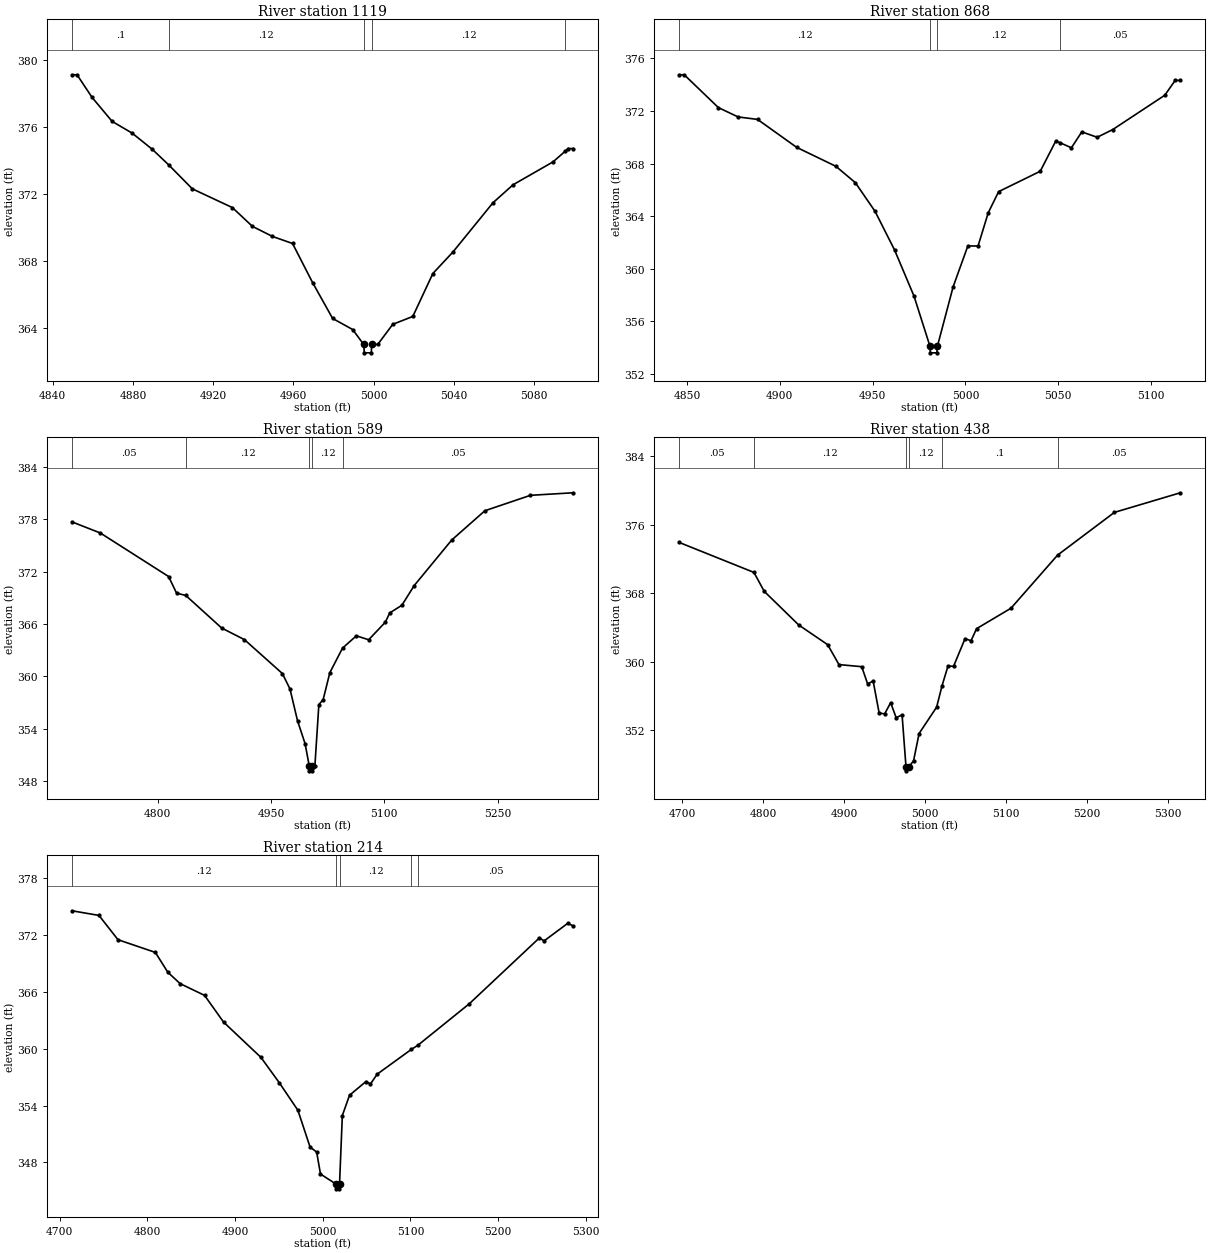
Type RM Length L Ch R = 1,1119,251,251,251
BEGIN DESCRIPTION:
Clear Creek T 39 4.0
END DESCRIPTION:
XS GIS Cut Line= 3
      2727976.03      6782961.00      2727826.00      6782961.00
      2727726.03      6782961.00
#Sta/Elev= 30
  4849.6  379.10  4852.1  379.10  4859.6  377.75  4869.6  376.32  4879.6  375.62
  4889.6  374.66  4897.8  373.73  4909.6  372.30  4929.6  371.18  4939.6  370.06
  4949.6  369.46  4959.6  369.04  4969.6  366.71  4979.6  364.57  4989.6  363.91
  4995.1  363.02  4995.4  362.52  4998.9  362.52  4999.1  363.02  5002.1  363.02
  5009.6  364.22  5019.6  364.69  5029.6  367.25  5039.6  368.53  5059.6  371.47
  5069.6  372.54  5089.6  373.91  5095.7  374.55  5097.1  374.70  5099.6  374.70
#Mann=5,-1,0
  4849.6     0.1       0  4897.8    0.12       0  4995.1    0.07       0
  4999.1    0.12       0  5095.7    0.05       0
Bank Sta=4995.1,4999.1
Exp/Cntr=0.3,0.1

Type RM Length L Ch R = 1,868,279,279,279
BEGIN DESCRIPTION:
Clear Creek T 39 3.0
END DESCRIPTION:
XS GIS Cut Line= 3
      2727926.04      6782710.99      2727776.00      6782761.00
      2727675.97      6782811.02
#Sta/Elev= 30
  4845.8  374.76  4848.5  374.76  4866.9  372.26  4877.5  371.55  4888.0  371.36
  4909.1  369.23  4930.2  367.79  4940.7  366.54  4951.3  364.36  4961.8  361.42
  4972.3  357.90  4980.9  354.08  4981.1  353.58  4984.6  353.58  4984.9  354.08
  4993.4  358.62  5001.3  361.72  5006.8  361.72  5012.3  364.25  5017.9  365.86
  5040.3  367.41  5048.7  369.72  5050.7  369.60  5057.1  369.20  5062.7  370.41
  5071.0  370.00  5079.4  370.59  5107.4  373.20  5113.0  374.33  5115.8  374.33
#Mann=4,-1,0
  4845.8    0.12       0  4980.9    0.07       0  4984.9    0.12       0
  5050.7    0.05       0
Bank Sta=4980.9,4984.9
Exp/Cntr=0.3,0.1

Type RM Length L Ch R = 1,589,151,151,151
BEGIN DESCRIPTION:
Clear Creek T 39 2.0
END DESCRIPTION:
XS GIS Cut Line= 3
      2727993.31      6782536.89      2727676.00      6782511.00
      2727371.95      6782673.04
#Sta/Elev= 30
  4686.9  377.71  4724.3  376.44  4814.6  371.45  4825.2  369.54  4837.3  369.28
  4884.9  365.54  4915.0  364.21  4965.1  360.33  4975.2  358.56  4985.2  354.90
  4995.2  352.28  5000.8  349.67  5001.0  349.17  5004.5  349.17  5004.8  349.67
  5008.1  349.67  5013.4  356.77  5019.1  357.34  5027.9  360.42  5044.7  363.24
  5063.0  364.65  5079.3  364.20  5101.3  366.21  5107.2  367.28  5123.2  368.15
  5139.5  370.41  5189.1  375.63  5233.0  378.99  5293.3  380.76  5349.8  381.05
#Mann=5,-1,0
  4686.9    0.05       0  4837.3    0.12       0  5000.8    0.07       0
  5004.8    0.12       0  5044.7    0.05       0
Bank Sta=5000.8,5004.8
Exp/Cntr=0.3,0.1

Type RM Length L Ch R = 1,438,224,224,224
BEGIN DESCRIPTION:
Mapping XS 50ae23e1
END DESCRIPTION:
XS GIS Cut Line= 2
      2727809.86      6782166.35      2727389.81      6782620.20
#Sta/Elev= 30
  4696.5  373.92  4788.7  370.42  4801.4  368.21  4844.0  364.28  4879.7  361.98
  4893.6  359.66  4921.7  359.41  4929.0  357.40  4935.8  357.74  4943.2  354.00
  4950.0  353.90  4957.4  355.21  4964.2  353.45  4971.5  353.79  4976.3  347.75
  4976.6  347.25  4980.3  347.75  4985.7  348.44  4992.5  351.61  5014.1  354.68
  5020.8  357.18  5028.2  359.50  5035.0  359.45  5049.2  362.69  5056.6  362.44
  5063.4  363.85  5105.9  366.24  5163.4  372.44  5233.5  377.43  5314.9  379.72
#Mann=6,-1,0
  4696.5    0.05       0  4788.7    0.12       0  4976.3    0.07       0
  4980.3    0.12       0  5020.8     0.1       0  5163.4    0.05       0
Bank Sta=4976.3,4980.3
Exp/Cntr=0.3,0.1

Type RM Length L Ch R = 1,214,0,0,0
BEGIN DESCRIPTION:
Clear Creek T 39 1.0
END DESCRIPTION:
XS GIS Cut Line= 3
      2727668.10      6781999.33      2727476.75      6782212.57
      2727389.64      6782483.82
#Sta/Elev= 30
  4714.1  374.54  4744.8  374.05  4766.5  371.49  4809.1  370.15  4823.3  368.06
  4837.3  366.86  4865.2  365.62  4886.9  362.80  4929.5  359.08  4950.4  356.41
  4971.6  353.51  4985.5  349.63  4993.0  349.10  4997.4  346.78  5015.1  345.72
  5015.3  345.22  5018.8  345.22  5019.1  345.72  5022.3  352.95  5030.5  355.09
  5049.2  356.53  5054.4  356.28  5062.0  357.31  5101.1  359.93  5108.3  360.35
  5167.0  364.73  5247.1  371.69  5252.3  371.36  5279.2  373.21  5285.5  372.95
#Mann=5,-1,0
  4714.1    0.12       0  5015.1    0.07       0  5019.1    0.12       0
  5101.1     0.1       0  5108.3    0.05       0
Bank Sta=5015.1,5019.1
Exp/Cntr=0.3,0.1

Chan Stop Cuts=-1