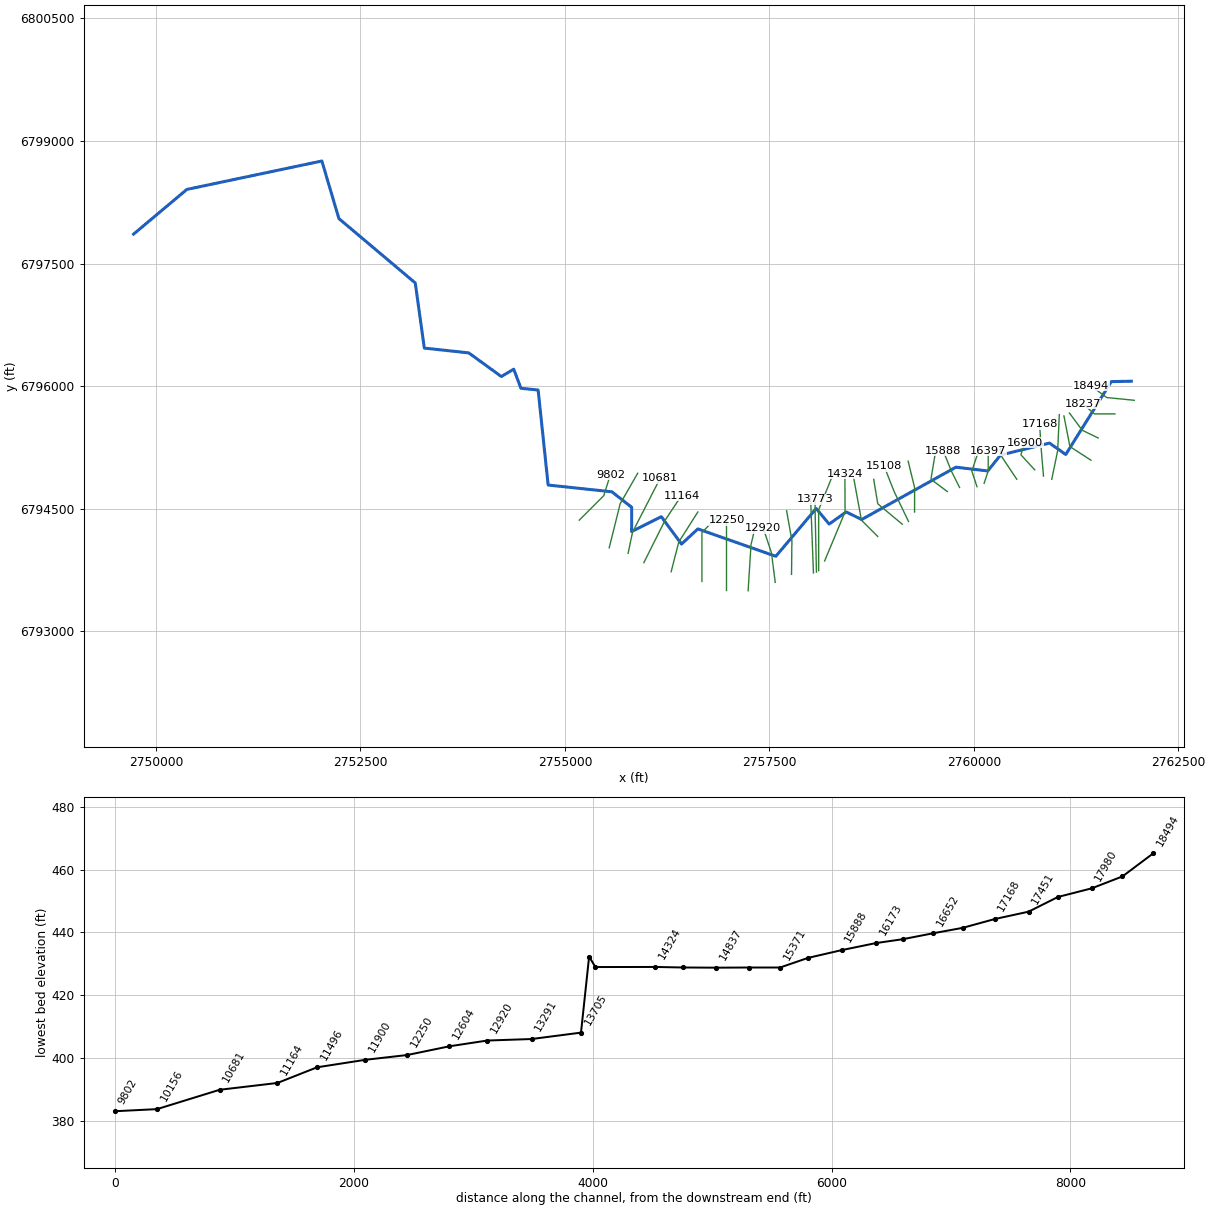
--- Clear Creek T 4.prj (project) ---

Proj Title=Clear Creek T 4 Base Level Engineering
Current Plan=p01
Default Exp/Contr=0.3,0.1
English Units
Geom File=g01
Flow File=f01
Plan File=p01
Y Axis Title=Elevation
X Axis Title(PF)=Main Channel Distance
X Axis Title(XS)=Station
BEGIN DESCRIPTION:
Clear Creek T 4
END DESCRIPTION:
DSS Export Rating Curves= 0
DSS Export Rating Curve Sorted= 0
DSS Export Volume Flow Curves= 0
DXF OffsetX= 0
DXF OffsetY= 0
DXF ScaleX= 1
DXF ScaleY= 10

--- Clear Creek T 4.p01 (plan) ---

Plan Title=Multiple Run
Program Version=4.10
Short Identifier=Multiple
Geom File=g01
Flow File=f01
Subcritical Flow
K Sum by GR= 0
Std Step Tol= 0.01
Critical Tol= 0.01
Num of Std Step Trials= 20
Max Error Tol= 0.3
Flow Tol Ratio= 0.001
Split Flow NTrial= 30
Split Flow Tol= 0.02
Split Flow Ratio= 0.02
Log Output Level= 0
Friction Slope Method= 1
Unsteady Friction Slope Method= 2
Unsteady Bridges Friction Slope Method= 1
Parabolic Critical Depth
Global Vel Dist= 1 , 1 , 1
Global Log Level= 0
CheckData=True
Encroach Param=-1 ,0,0, 0
BEGIN DESCRIPTION:
Multiple Run
END DESCRIPTION:
Computation Interval=1HOUR
Output Interval=1HOUR
Run HTab= 0
Run UNet= 0
Run PostProcess= 0
Run WQNet= 0
UNET Theta= 1
UNET Theta Warmup= 1
UNET ZTol= 0.02
UNET ZSATol= 0.05
UNET MxIter= 20
UNET MaxInSteps= 0
UNET DtIC= 0
UNET DtMin= 0
UNET MaxCRTS= 20
UNET WFStab= 2
UNET SFStab= 1
UNET WFX= 1
UNET SFX= 1
UNET DSS MLevel= 4
UNET DZMax Abort= 100
UNET Convert EG Bridges= 0
UNET Use Existing IB Tables=-1
UNET Froude Reduction=False
UNET Froude Limit= 1
UNET Froude Power= 10
UNET Time Slicing=0,0, 5
UNET Junction Losses=0
Instantaneous Interval=1HOUR
Write IC File= 0
Write IC File at Sim End=0
Echo Input=False
Echo Parameters=False
Echo Output=False
Write Detailed= 0
WQ AD Non Conservative
WQ ULTIMATE=-1
WQ Max Comp Step=1HOUR
WQ Output Interval=15MIN
WQ Output Selected Increments= 0
WQ Output face flow=0
WQ Output face velocity=0
WQ Output face area=0
WQ Output face dispersion=0
WQ Output cell volume=0
WQ Output cell surface area=0
WQ Output cell continuity=0
WQ Output cumulative cell continuity=0
WQ Output face conc=0
WQ Output face dconc_dx=0
WQ Output face courant=0
WQ Output face peclet=0
WQ Output face adv mass=0
WQ Output face disp mass=0
WQ Output cell mass=0
WQ Output cell source sink temp=0
WQ Output cell source sink nsm=0
WQ Output MaxMinRange=-1
WQ Daily Max Min Mean=-1
WQ Daily Range=0
WQ Daily Time=0
WQ Create Restart=0
WQ Fixed Restart=0
WQ System Summary=0
WQ Use Fixed Temperature=0
Sorting and Armoring Iterations= 10
XS Update Threshold= 0.02
Hydraulics Update Threshold= 0.02
Energy Slope Method= 1
Volume Change Method= 0
XS Weighting Method= 0
Number of US Weighted Cross Sections= 1
Number of DS Weighted Cross Sections= 1
Upstream XS Weight=0.25
Main XS Weight=0.5
Downstream XS Weight=0.25
Number of DS XS's Weighted with US Boundary= 1
Upstream Boundary Weight= 1
Weight of XSs Associated with US Boundary= 0
Number of US XS's Weighted with DS Boundary= 1
Downstream Boundary Weight= 0.5
Weight of XSs Associated with DS Boundary= 0.5
Sediment Output Level= 4
Mass or Volume Output= 0
Output Increment Type= 1
Profile and TS Output Increment= 10
XS Output Flag= 0
XS Output Increment= 10
Disregard all LS=0
Disregard all Conn=0
Disregard all Breaches=0
Disregard all Pumps=0

--- Clear Creek T 4.f01 (steady flow) ---

Flow Title=Multiple
Number of Profiles=7
Profile Names=10-year,25-year,50-year,1pct_min,100-year,1pct_plu,500-year
River Rch & RM= Clear Creek T 4,Reach-1,18494
     185     231     267     154     307     613     406
River Rch & RM= Clear Creek T 4,Reach-1,15605
     267     341     399     233     464     927     629
River Rch & RM= Clear Creek T 4,Reach-1,13825
     416     549     656     390     778    1553    1097
River Rch & RM= Clear Creek T 4,Reach-1,11164
     558     749     905     544    1085    2165    1562
River Rch & RM= Clear Creek T 4,Reach-1,8669
     641     866    1049     631    1259    2513    1820
Boundary for River Rch & Prof#=Clear Creek T 4,Reach-1,1
Up Type=0
Dn Type=3
Dn Slope=0.005
Boundary for River Rch & Prof#=Clear Creek T 4,Reach-1,2
Up Type=0
Dn Type=3
Dn Slope=0.005
Boundary for River Rch & Prof#=Clear Creek T 4,Reach-1,3
Up Type=0
Dn Type=3
Dn Slope=0.005
Boundary for River Rch & Prof#=Clear Creek T 4,Reach-1,4
Up Type=0
Dn Type=3
Dn Slope=0.005
Boundary for River Rch & Prof#=Clear Creek T 4,Reach-1,5
Up Type=0
Dn Type=3
Dn Slope=0.005
Boundary for River Rch & Prof#=Clear Creek T 4,Reach-1,6
Up Type=0
Dn Type=3
Dn Slope=0.005
Boundary for River Rch & Prof#=Clear Creek T 4,Reach-1,7
Up Type=0
Dn Type=3
Dn Slope=0.005

--- Clear Creek T 4.g01 (geometry) ---

Geom Title=Existing Conditions

River Reach=Clear Creek T 4,Reach-1
Reach XY= 30
      2761926.00      6796061.00      2761681.01      6796056.00
      2761124.65      6795164.34      2760926.01      6795303.93
      2760327.45      6795157.47      2760170.70      6794963.00
      2759781.45      6795008.83      2758629.41      6794368.77
      2758439.91      6794460.96      2758231.30      6794313.00
      2758072.66      6794503.42      2757579.35      6793918.58
      2756626.08      6794253.70      2756425.97      6794067.88
      2756179.41      6794403.23      2755815.88      6794221.05
      2755816.84      6794518.00      2755574.82      6794707.84
      2754795.41      6794790.33      2754673.00      6795953.05
      2754462.62      6795974.37      2754374.63      6796207.99
      2754222.67      6796118.61      2753824.75      6796407.56
      2753281.18      6796466.41      2753170.48      6797263.44
      2752236.52      6798051.21      2752028.44      6798755.61
      2750377.63      6798407.87      2749726.00      6797861.00

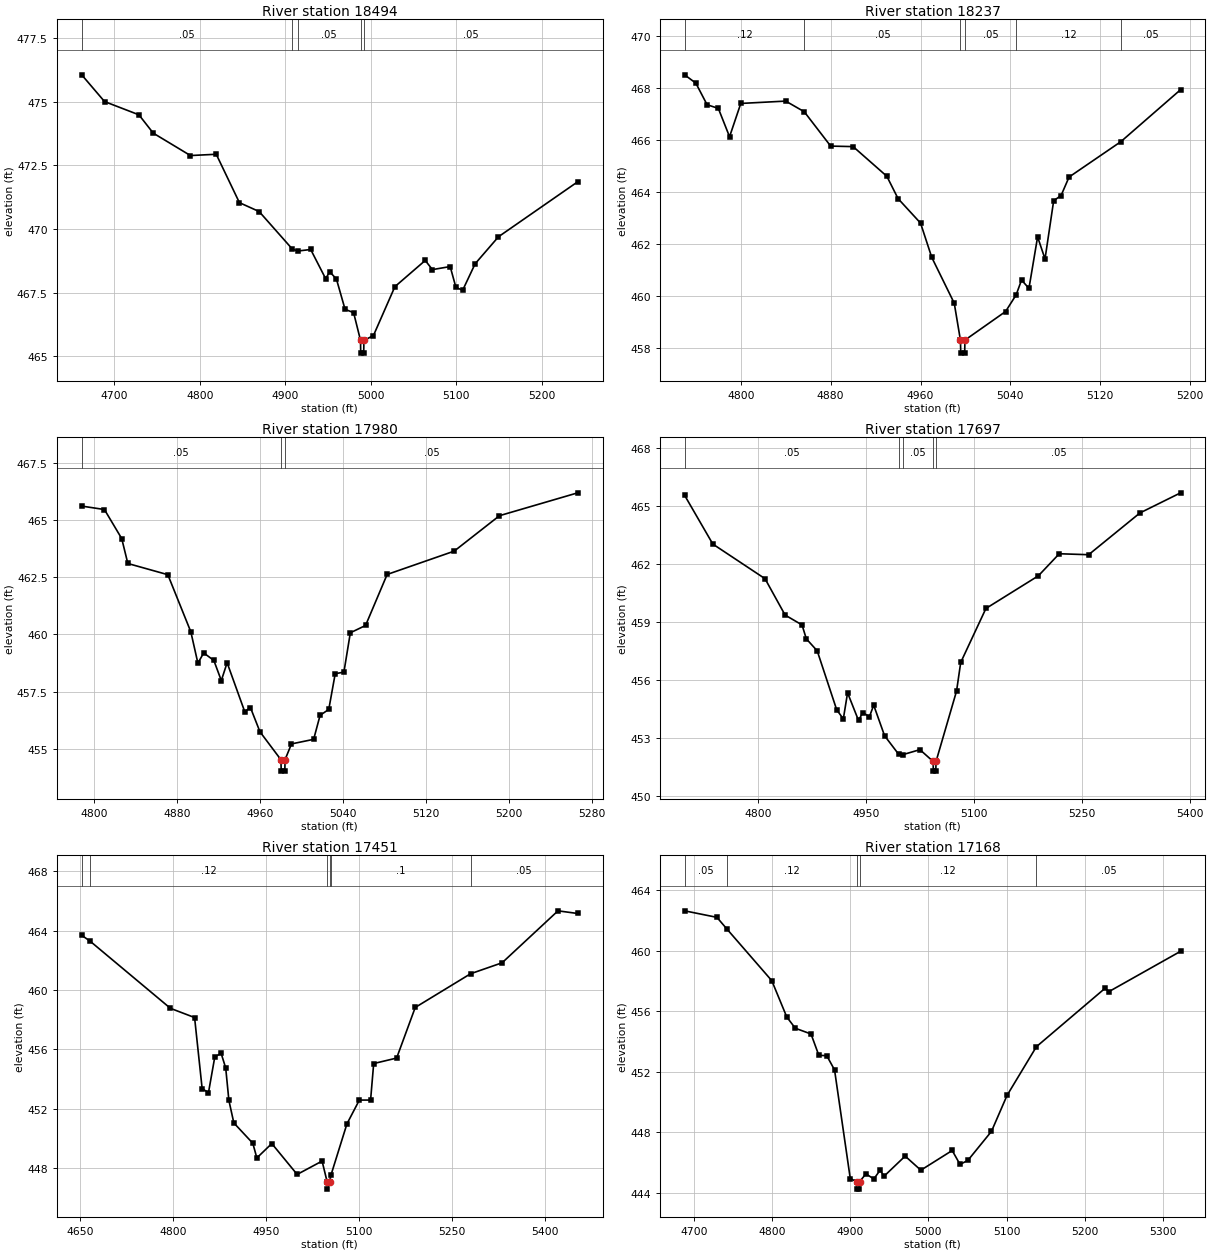
Type RM Length L Ch R = 1,18494,257,257,257
BEGIN DESCRIPTION:
Clear Creek T 4 43.0
END DESCRIPTION:
XS GIS Cut Line= 3
      2761962.58      6795827.56      2761626.00      6795861.00
      2761431.51      6796005.10
#Sta/Elev= 30
  4661.8  476.06  4688.5  475.01  4728.7  474.49  4745.5  473.77  4789.0  472.89
  4819.2  472.94  4846.3  471.04  4869.4  470.69  4908.4  469.21  4914.7  469.14
  4929.7  469.20  4947.1  468.06  4952.1  468.32  4959.8  468.04  4969.9  466.85
  4979.9  466.72  4988.0  465.63  4988.2  465.13  4991.7  465.13  4992.0  465.63
  5003.1  465.82  5028.2  467.74  5063.7  468.77  5072.1  468.41  5092.9  468.53
  5099.6  467.71  5107.5  467.60  5122.1  468.64  5149.4  469.70  5242.1  471.86
#Mann=5,-1,0
  4661.8    0.05       0  4908.4    0.12       0  4914.7    0.05       0
  4988.0    0.04       0  4992.0    0.05       0
Bank Sta=4988,4992
Exp/Cntr=0.3,0.1

Type RM Length L Ch R = 1,18237,257,257,257
BEGIN DESCRIPTION:
Clear Creek T 4 42.0
END DESCRIPTION:
XS GIS Cut Line= 3
      2761726.01      6795661.00      2761476.00      6795661.00
      2761330.57      6795785.58
#Sta/Elev= 30
  4750.0  468.51  4760.0  468.19  4770.0  467.36  4780.0  467.22  4790.0  466.13
  4800.0  467.41  4840.0  467.50  4856.5  467.09  4880.0  465.77  4900.0  465.75
  4930.0  464.61  4940.0  463.75  4960.0  462.81  4970.0  461.49  4990.0  459.73
  4995.5  458.31  4995.8  457.81  4999.3  457.81  4999.5  458.31  5035.7  459.41
  5045.1  460.05  5049.9  460.62  5056.5  460.30  5064.2  462.28  5070.8  461.43
  5078.5  463.67  5085.1  463.87  5092.2  464.58  5138.3  465.94  5191.5  467.94
#Mann=6,-1,0
  4750.0    0.12       0  4856.5    0.05       0  4995.5    0.04       0
  4999.5    0.05       0  5045.1    0.12       0  5138.3    0.05       0
Bank Sta=4995.5,4999.5
Exp/Cntr=0.3,0.1

Type RM Length L Ch R = 1,17980,283,283,283
BEGIN DESCRIPTION:
Clear Creek T 4 41.0
END DESCRIPTION:
XS GIS Cut Line= 3
      2761520.74      6795366.47      2761326.00      6795461.00
      2761170.00      6795671.66
#Sta/Elev= 30
  4787.7  465.61  4809.6  465.46  4826.3  464.19  4832.2  463.10  4870.8  462.61
  4893.0  460.11  4899.8  458.74  4905.4  459.19  4915.2  458.86  4922.4  457.98
  4928.0  458.76  4945.0  456.62  4950.5  456.80  4959.7  455.74  4979.9  454.52
  4980.2  454.02  4983.7  454.02  4983.9  454.52  4990.1  455.21  5011.5  455.41
  5017.7  456.46  5026.1  456.72  5032.3  458.28  5040.7  458.35  5046.9  460.07
  5061.6  460.39  5082.4  462.62  5147.1  463.64  5190.8  465.19  5266.3  466.19
#Mann=3,-1,0
  4787.7    0.05       0  4979.9    0.04       0  4983.9    0.05       0
Bank Sta=4979.9,4983.9
Exp/Cntr=0.3,0.1

Type RM Length L Ch R = 1,17697,246,246,246
BEGIN DESCRIPTION:
Clear Creek T 4 40.0
END DESCRIPTION:
XS GIS Cut Line= 3
      2761433.15      6795094.21      2761176.00      6795261.00
      2761102.24      6795636.41
#Sta/Elev= 30
  4697.8  465.53  4737.0  463.01  4809.5  461.22  4837.4  459.34  4860.9  458.83
  4866.9  458.11  4882.0  457.49  4909.1  454.44  4918.3  453.97  4924.2  455.32
  4939.4  453.89  4945.3  454.30  4954.5  454.08  4960.5  454.68  4975.6  453.10
  4995.0  452.15  5000.8  452.12  5024.7  452.38  5043.1  451.77  5043.3  451.27
  5046.8  451.27  5047.1  451.77  5075.6  455.41  5081.4  456.89  5116.4  459.68
  5189.3  461.37  5218.3  462.51  5259.1  462.46  5330.4  464.62  5386.9  465.66
#Mann=5,-1,0
  4697.8    0.05       0  4995.0     0.1       0  5000.8    0.05       0
  5043.1    0.07       0  5047.1    0.05       0
Bank Sta=5043.1,5047.1
Exp/Cntr=0.3,0.1

Type RM Length L Ch R = 1,17451,283,283,283
BEGIN DESCRIPTION:
Clear Creek T 4 39.0
END DESCRIPTION:
XS GIS Cut Line= 3
      2760953.40      6794860.83      2761026.00      6795211.00
      2761045.86      6795652.74
#Sta/Elev= 30
  4652.4  463.69  4665.8  463.30  4795.5  458.77  4834.4  458.15  4846.6  453.36
  4856.8  453.09  4867.0  455.50  4877.2  455.74  4884.6  454.75  4889.7  452.57
  4897.7  451.05  4928.3  449.68  4934.8  448.69  4958.9  449.66  4999.8  447.58
  5040.0  448.48  5048.1  447.09  5048.3  446.59  5052.1  447.09  5054.5  447.56
  5080.1  450.99  5100.1  452.59  5118.2  452.59  5123.2  455.05  5160.2  455.42
  5190.2  458.83  5279.4  461.10  5330.3  461.84  5420.4  465.34  5452.2  465.16
#Mann=6,-1,0
  4652.4    0.05       0  4665.8    0.12       0  5048.1    0.07       0
  5052.1    0.12       0  5054.5     0.1       0  5279.4    0.05       0
Bank Sta=5048.1,5052.1
Exp/Cntr=0.3,0.1

Type RM Length L Ch R = 1,17168,268,268,268
BEGIN DESCRIPTION:
Clear Creek T 4 38.0
END DESCRIPTION:
XS GIS Cut Line= 3
      2760852.40      6794899.87      2760826.00      6795211.00
      2760804.59      6795532.54
#Sta/Elev= 30
  4688.1  462.62  4729.4  462.19  4742.7  461.39  4799.6  458.01  4818.8  455.61
  4829.7  454.87  4849.8  454.49  4859.8  453.08  4869.9  453.06  4879.9  452.12
  4900.0  444.95  4908.0  444.75  4908.3  444.25  4911.8  444.25  4912.0  444.75
  4920.1  445.26  4930.1  444.92  4938.2  445.50  4943.2  445.10  4970.2  446.43
  4990.3  445.50  5030.4  446.80  5040.4  445.88  5050.5  446.15  5080.6  448.06
  5100.6  450.44  5138.1  453.65  5226.0  457.51  5231.0  457.29  5322.6  459.95
#Mann=5,-1,0
  4688.1    0.05       0  4742.7    0.12       0  4908.0    0.07       0
  4912.0    0.12       0  5138.1    0.05       0
Bank Sta=4908,4912
Exp/Cntr=0.3,0.1

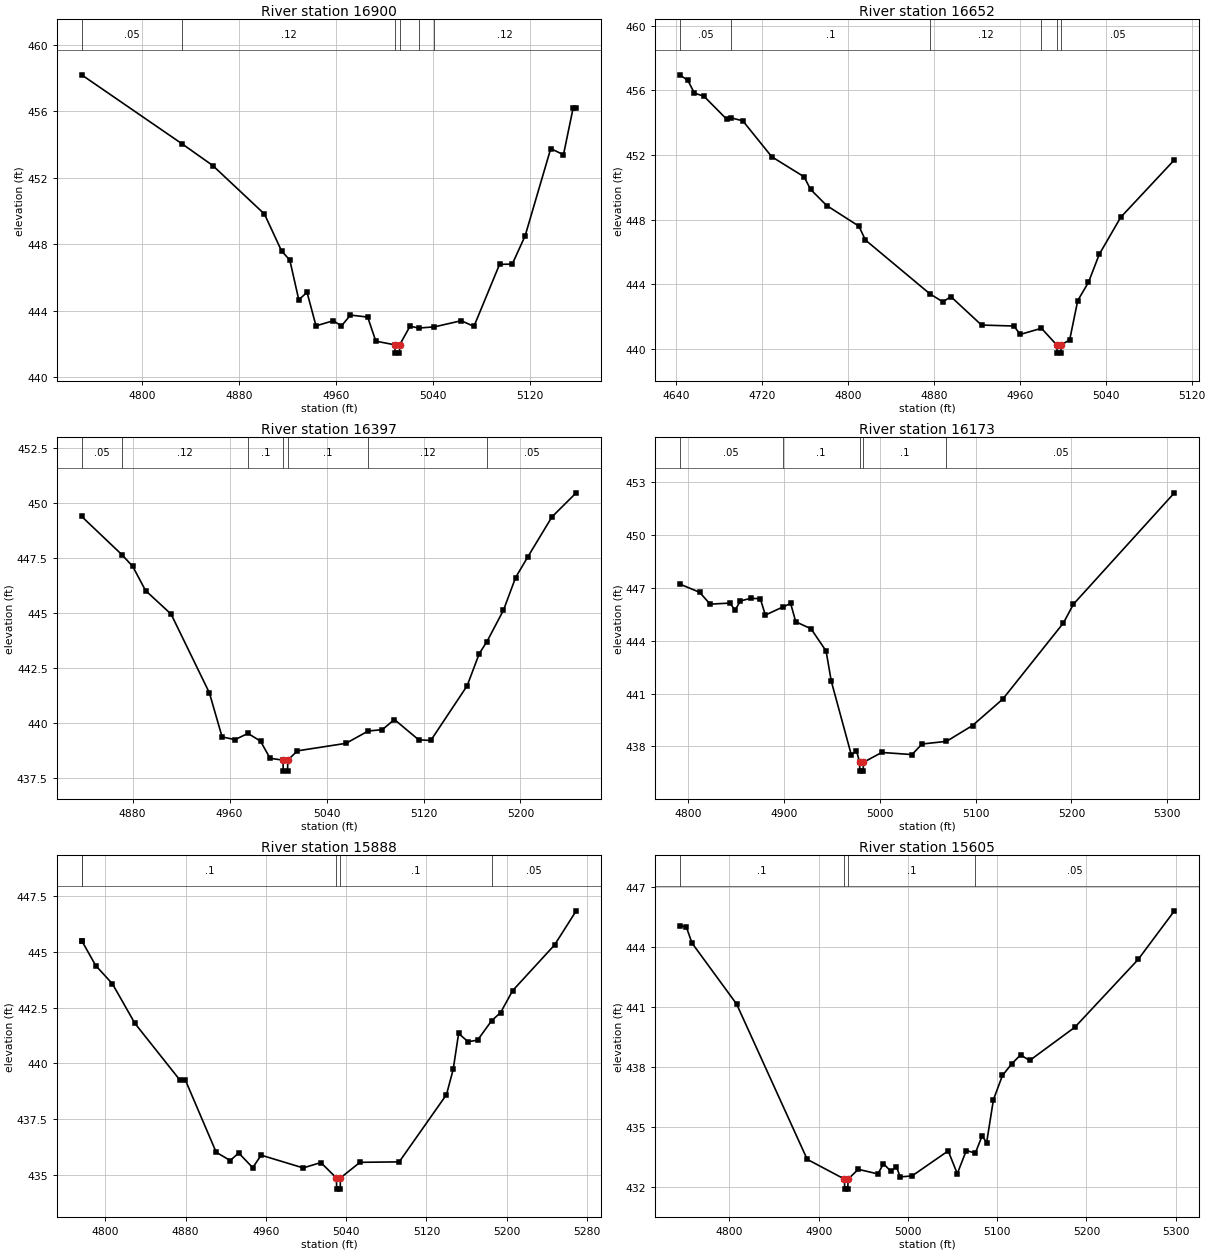
Type RM Length L Ch R = 1,16900,248,248,248
BEGIN DESCRIPTION:
Clear Creek T 4 37.0
END DESCRIPTION:
XS GIS Cut Line= 3
      2760744.59      6794976.91      2760576.00      6795161.00
      2760625.99      6795310.97
#Sta/Elev= 30
  4750.4  458.20  4833.3  454.04  4858.5  452.74  4901.1  449.82  4915.2  447.60
  4922.0  447.05  4929.4  444.66  4936.2  445.11  4943.6  443.09  4957.8  443.40
  4964.6  443.09  4972.0  443.74  4986.2  443.62  4992.9  442.17  5008.6  441.95
  5008.8  441.45  5012.3  441.45  5012.6  441.95  5021.1  443.07  5028.3  442.96
  5041.2  443.03  5063.3  443.40  5073.8  443.06  5094.9  446.79  5105.4  446.81
  5116.0  448.51  5137.1  453.76  5147.6  453.39  5155.5  456.18  5158.1  456.18
#Mann=6,-1,0
  4750.4    0.05       0  4833.3    0.12       0  5008.6    0.07       0
  5012.6    0.12       0  5028.3     0.1       0  5041.2    0.12       0
Bank Sta=5008.6,5012.6
Exp/Cntr=0.3,0.1

Type RM Length L Ch R = 1,16652,255,255,255
BEGIN DESCRIPTION:
Clear Creek T 4 36.0
END DESCRIPTION:
XS GIS Cut Line= 3
      2760525.99      6794861.01      2760326.00      6795161.00
      2760326.00      6795260.95
#Sta/Elev= 30
  4643.4  456.97  4650.9  456.62  4656.9  455.84  4665.9  455.64  4687.0  454.22
  4691.2  454.30  4702.0  454.12  4729.0  451.89  4759.1  450.65  4765.1  449.87
  4780.1  448.87  4810.1  447.59  4816.2  446.73  4876.3  443.39  4888.3  442.90
  4895.8  443.22  4924.3  441.46  4954.4  441.40  4960.4  440.88  4980.1  441.26
  4994.4  440.22  4994.7  439.72  4998.2  439.72  4998.4  440.22  5006.4  440.55
  5013.9  442.98  5023.9  444.11  5033.9  445.84  5053.9  448.14  5103.9  451.70
#Mann=6,-1,0
  4643.4    0.05       0  4691.2     0.1       0  4876.3    0.12       0
  4980.1    0.05       0  4994.4    0.04       0  4998.4    0.05       0
Bank Sta=4994.4,4998.4
Exp/Cntr=0.3,0.1

Type RM Length L Ch R = 1,16397,224,224,224
BEGIN DESCRIPTION:
Clear Creek T 4 35.0
END DESCRIPTION:
XS GIS Cut Line= 3
      2760126.00      6794811.01      2760176.00      6794961.00
      2760176.00      6795211.00
#Sta/Elev= 30
  4837.9  449.38  4871.2  447.64  4880.1  447.11  4890.6  446.02  4911.7  444.95
  4943.3  441.38  4953.8  439.38  4964.4  439.26  4975.2  439.54  4985.5  439.19
  4993.4  438.41  5004.0  438.33  5004.3  437.83  5007.8  437.83  5008.0  438.33
  5016.0  438.75  5056.0  439.09  5074.4  439.65  5086.0  439.71  5096.0  440.17
  5116.0  439.25  5126.0  439.22  5156.0  441.70  5166.0  443.16  5172.3  443.70
  5186.0  445.13  5196.0  446.61  5206.0  447.54  5226.0  449.36  5246.0  450.45
#Mann=7,-1,0
  4837.9    0.05       0  4871.2    0.12       0  4975.2     0.1       0
  5004.0    0.07       0  5008.0     0.1       0  5074.4    0.12       0
  5172.3    0.05       0
Bank Sta=5004,5008
Exp/Cntr=0.3,0.1

Type RM Length L Ch R = 1,16173,285,285,285
BEGIN DESCRIPTION:
Clear Creek T 4 34.0
END DESCRIPTION:
XS GIS Cut Line= 3
      2760039.01      6794770.96      2759976.00      6794961.00
      2760075.99      6795260.96
#Sta/Elev= 30
  4791.1  447.22  4811.8  446.75  4822.7  446.08  4843.4  446.14  4848.7  445.74
  4854.4  446.26  4864.9  446.41  4875.1  446.39  4880.4  445.46  4898.3  445.91
  4906.8  446.12  4912.1  445.08  4928.1  444.68  4943.8  443.42  4949.2  441.71
  4970.2  437.51  4975.5  437.77  4978.8  437.10  4979.0  436.60  4982.5  436.60
  4982.8  437.10  5001.9  437.66  5033.5  437.54  5044.0  438.14  5069.5  438.29
  5096.7  439.19  5128.3  440.69  5191.6  445.01  5202.1  446.08  5307.5  452.40
#Mann=5,-1,0
  4791.1    0.05       0  4898.3     0.1       0  4978.8    0.07       0
  4982.8     0.1       0  5069.5    0.05       0
Bank Sta=4978.8,4982.8
Exp/Cntr=0.3,0.1

Type RM Length L Ch R = 1,15888,283,283,283
BEGIN DESCRIPTION:
Clear Creek T 4 33.0
END DESCRIPTION:
XS GIS Cut Line= 3
      2759825.99      6794761.01      2759726.00      6794961.00
      2759625.98      6795211.05
#Sta/Elev= 30
  4776.4  445.46  4776.9  445.46  4790.4  444.38  4807.1  443.56  4829.5  441.79
  4874.2  439.26  4879.8  439.25  4910.5  436.02  4924.5  435.65  4932.9  435.99
  4946.9  435.33  4955.3  435.89  4997.2  435.32  5014.8  435.56  5030.3  434.87
  5030.6  434.37  5034.1  434.37  5034.3  434.87  5053.8  435.57  5092.9  435.59
  5140.0  438.60  5146.7  439.73  5152.1  441.34  5161.5  440.97  5171.0  441.04
  5185.0  441.91  5193.9  442.27  5206.0  443.26  5247.7  445.30  5269.3  446.83
#Mann=5,-1,0
  4776.4    0.05       0  4776.9     0.1       0  5030.3    0.07       0
  5034.3     0.1       0  5185.0    0.05       0
Bank Sta=5030.3,5034.3
Exp/Cntr=0.3,0.1

Type RM Length L Ch R = 1,15605,234,234,234
BEGIN DESCRIPTION:
Clear Creek T 4 32.0
END DESCRIPTION:
XS GIS Cut Line= 3
      2759676.02      6794710.98      2759476.00      6794861.00
      2759526.01      6795161.03
#Sta/Elev= 30
  4744.4  445.06  4751.7  444.99  4758.0  444.19  4808.0  441.14  4887.1  433.38
  4928.9  432.39  4929.1  431.89  4932.6  431.89  4932.9  432.39  4944.4  432.88
  4966.3  432.65  4972.6  433.16  4980.9  432.78  4987.1  433.01  4991.3  432.50
  5004.6  432.55  5045.1  433.80  5055.3  432.66  5065.4  433.82  5075.5  433.69
  5083.1  434.55  5088.2  434.22  5095.8  436.36  5105.9  437.57  5116.1  438.14
  5126.2  438.60  5136.4  438.32  5187.0  439.98  5258.0  443.37  5298.6  445.80
#Mann=4,-1,0
  4744.4     0.1       0  4928.9    0.07       0  4932.9     0.1       0
  5075.5    0.05       0
Bank Sta=4928.9,4932.9
Exp/Cntr=0.3,0.1

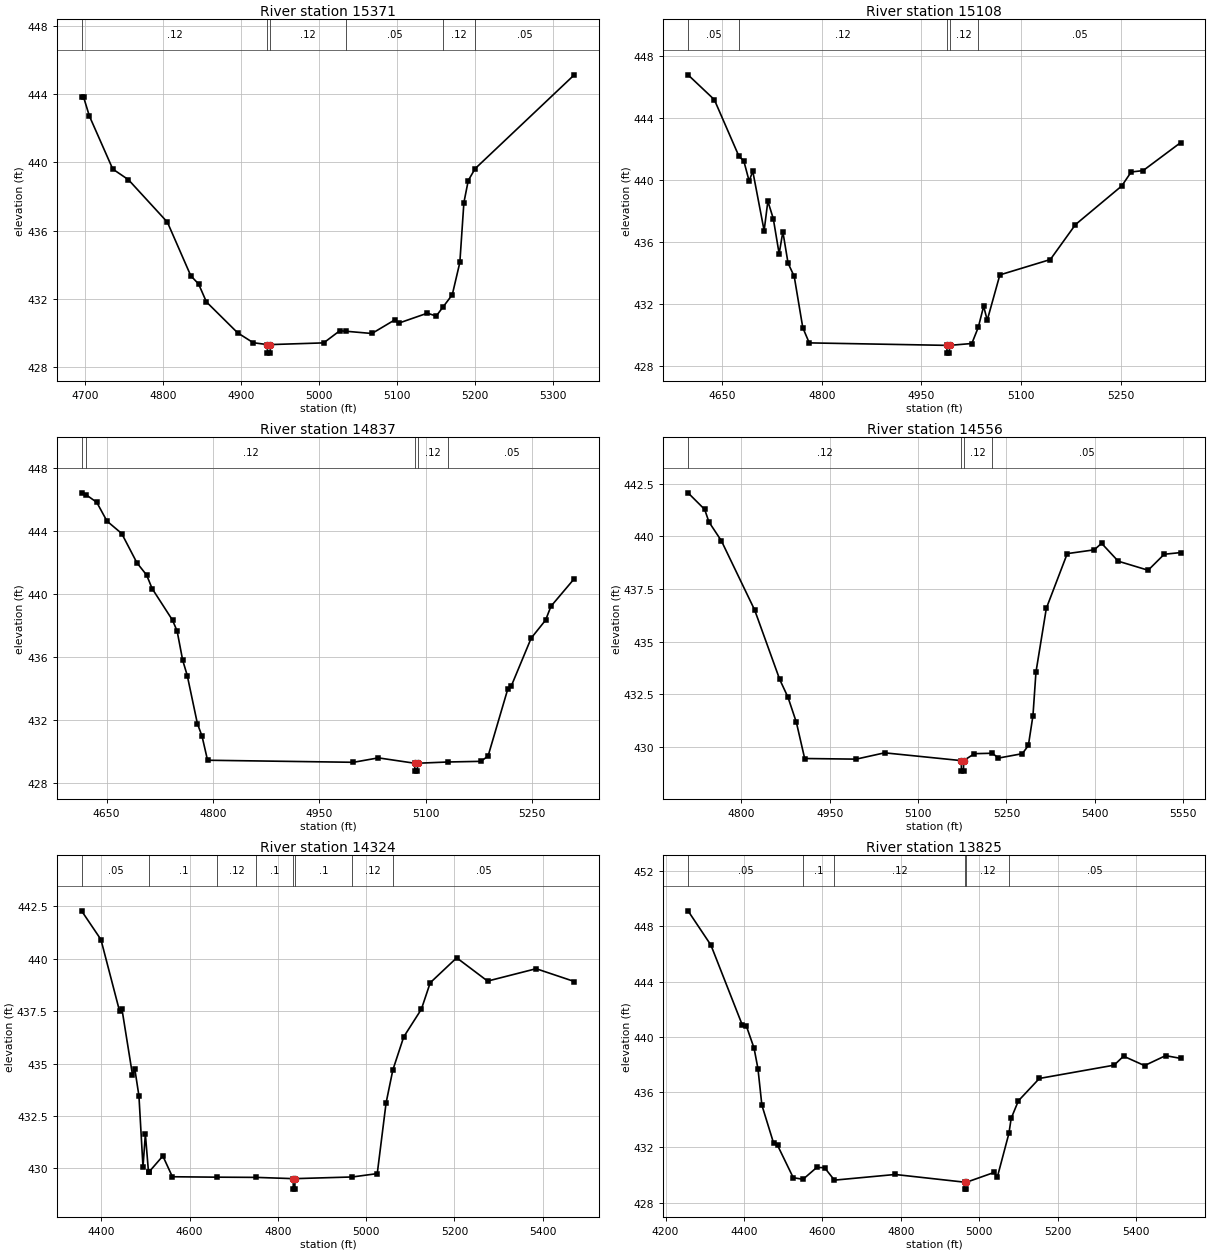
Type RM Length L Ch R = 1,15371,263,263,263
BEGIN DESCRIPTION:
Clear Creek T 4 31.0
END DESCRIPTION:
XS GIS Cut Line= 3
      2759276.00      6794460.96      2759276.00      6794761.00
      2759197.24      6795082.97
#Sta/Elev= 30
  4695.8  443.84  4698.3  443.84  4705.8  442.72  4735.8  439.61  4755.8  438.99
  4805.8  436.50  4835.8  433.36  4845.8  432.88  4855.8  431.83  4895.8  430.02
  4915.8  429.44  4933.8  429.33  4934.1  428.83  4937.6  428.83  4937.8  429.33
  5006.1  429.43  5026.7  430.14  5035.1  430.11  5067.9  429.98  5097.3  430.78
  5102.5  430.59  5139.0  431.17  5150.3  431.00  5158.7  431.51  5170.9  432.25
  5180.6  434.14  5185.8  437.65  5191.4  438.94  5200.1  439.63  5327.3  445.13
#Mann=6,-1,0
  4695.8    0.12       0  4933.8    0.07       0  4937.8    0.12       0
  5035.1    0.05       0  5158.7    0.12       0  5200.1    0.05       0
Bank Sta=4933.8,4937.8
Exp/Cntr=0.3,0.1

Type RM Length L Ch R = 1,15108,271,271,271
BEGIN DESCRIPTION:
Clear Creek T 4 30.0
END DESCRIPTION:
XS GIS Cut Line= 3
      2759201.95      6794345.33      2759026.00      6794711.00
      2758902.99      6795023.78
#Sta/Elev= 30
  4598.7  446.76  4638.3  445.16  4675.4  441.51  4682.7  441.21  4690.7  439.92
  4696.2  440.55  4713.3  436.72  4718.9  438.62  4727.1  437.49  4735.9  435.23
  4741.5  436.65  4749.3  434.63  4758.6  433.77  4771.5  430.47  4781.2  429.49
  4988.4  429.33  4988.7  428.83  4992.2  428.83  4992.4  429.33  5026.0  429.45
  5035.7  430.49  5043.8  431.85  5049.2  430.95  5068.2  433.87  5144.2  434.86
  5182.0  437.11  5251.7  439.60  5265.9  440.50  5283.9  440.59  5340.6  442.40
#Mann=5,-1,0
  4598.7    0.05       0  4675.4    0.12       0  4988.4    0.07       0
  4992.4    0.12       0  5035.7    0.05       0
Bank Sta=4988.4,4992.4
Exp/Cntr=0.3,0.1

Type RM Length L Ch R = 1,14837,281,281,281
BEGIN DESCRIPTION:
Clear Creek T 4 29.0
END DESCRIPTION:
XS GIS Cut Line= 3
      2759125.97      6794311.03      2758826.00      6794561.00
      2758776.00      6794860.99
#Sta/Elev= 30
  4614.6  446.42  4621.2  446.29  4636.0  445.82  4650.4  444.63  4671.2  443.84
  4692.7  441.98  4706.3  441.21  4714.1  440.35  4742.8  438.35  4749.3  437.66
  4757.1  435.82  4763.6  434.84  4777.9  431.79  4784.4  431.00  4792.2  429.47
  4997.9  429.34  5033.0  429.62  5084.2  429.28  5084.4  428.78  5087.9  428.78
  5088.2  429.28  5131.8  429.36  5177.4  429.40  5187.6  429.73  5215.4  433.98
  5220.5  434.19  5248.4  437.21  5268.7  438.35  5276.3  439.23  5309.2  440.98
#Mann=5,-1,0
  4614.6    0.05       0  4621.2    0.12       0  5084.2    0.07       0
  5088.2    0.12       0  5131.8    0.05       0
Bank Sta=5084.2,5088.2
Exp/Cntr=0.3,0.1

Type RM Length L Ch R = 1,14556,232,232,232
BEGIN DESCRIPTION:
Clear Creek T 4 28.0
END DESCRIPTION:
XS GIS Cut Line= 3
      2758826.00      6794161.00      2758626.00      6794361.00
      2758526.29      6794905.50
#Sta/Elev= 30
  4709.5  442.07  4737.8  441.28  4744.9  440.69  4766.1  439.79  4822.6  436.50
  4865.1  433.20  4879.2  432.35  4893.4  431.16  4907.5  429.44  4994.9  429.41
  5043.2  429.71  5173.3  429.34  5173.6  428.84  5177.1  428.84  5177.3  429.34
  5195.7  429.67  5226.1  429.69  5236.3  429.46  5277.0  429.67  5287.2  430.06
  5295.0  431.48  5300.1  433.55  5317.7  436.58  5353.2  439.18  5399.0  439.36
  5411.5  439.67  5439.7  438.82  5490.5  438.39  5517.8  439.15  5545.9  439.23
#Mann=4,-1,0
  4709.5    0.12       0  5173.3    0.07       0  5177.3    0.12       0
  5226.1    0.05       0
Bank Sta=5173.3,5177.3
Exp/Cntr=0.3,0.1

Type RM Length L Ch R = 1,14324,499,499,499
BEGIN DESCRIPTION:
Clear Creek T 4 27.0
END DESCRIPTION:
XS GIS Cut Line= 3
      2758176.00      6793861.01      2758426.00      6794461.00
      2758424.21      6794927.51
#Sta/Elev= 30
  4355.1  442.28  4399.0  440.91  4441.2  437.50  4446.6  437.60  4470.5  434.46
  4475.9  434.72  4485.1  433.46  4494.3  430.07  4499.7  431.63  4506.8  429.82
  4508.8  429.85  4539.3  430.59  4560.9  429.60  4662.3  429.58  4750.2  429.57
  4834.6  429.51  4834.9  429.01  4838.4  429.01  4838.6  429.51  4968.7  429.59
  5025.1  429.75  5045.1  433.12  5060.4  434.69  5085.1  436.27  5125.1  437.59
  5145.1  438.85  5205.1  440.04  5275.1  438.93  5385.1  439.52  5471.6  438.91
#Mann=8,-1,0
  4355.1    0.05       0  4508.8     0.1       0  4662.3    0.12       0
  4750.2     0.1       0  4834.6    0.07       0  4838.6     0.1       0
  4968.7    0.12       0  5060.4    0.05       0
Bank Sta=4834.6,4838.6
Exp/Cntr=0.3,0.1

Type RM Length L Ch R = 1,13825,52,52,52
BEGIN DESCRIPTION:
Clear Creek T 4 26.0
END DESCRIPTION:
XS GIS Cut Line= 3
      2758103.18      6793742.56      2758102.73      6794485.36
      2758295.38      6794962.21
#Sta/Elev= 30
  4257.2  449.12  4315.6  446.64  4395.6  440.86  4405.6  440.82  4425.6  439.19
  4435.6  437.70  4445.6  435.06  4475.6  432.30  4485.6  432.15  4525.6  429.81
  4550.6  429.69  4585.6  430.55  4605.6  430.53  4630.7  429.63  4785.6  430.04
  4963.6  429.48  4963.9  428.98  4967.4  428.98  4967.6  429.48  5038.4  430.19
  5046.3  429.85  5075.9  433.02  5081.6  434.10  5100.0  435.37  5153.6  436.99
  5344.1  437.95  5368.3  438.60  5421.9  437.92  5475.6  438.64  5514.3  438.44
#Mann=6,-1,0
  4257.2    0.05       0  4550.6     0.1       0  4630.7    0.12       0
  4963.6    0.07       0  4967.6    0.12       0  5075.9    0.05       0
Bank Sta=4963.6,4967.6
Exp/Cntr=0.3,0.1

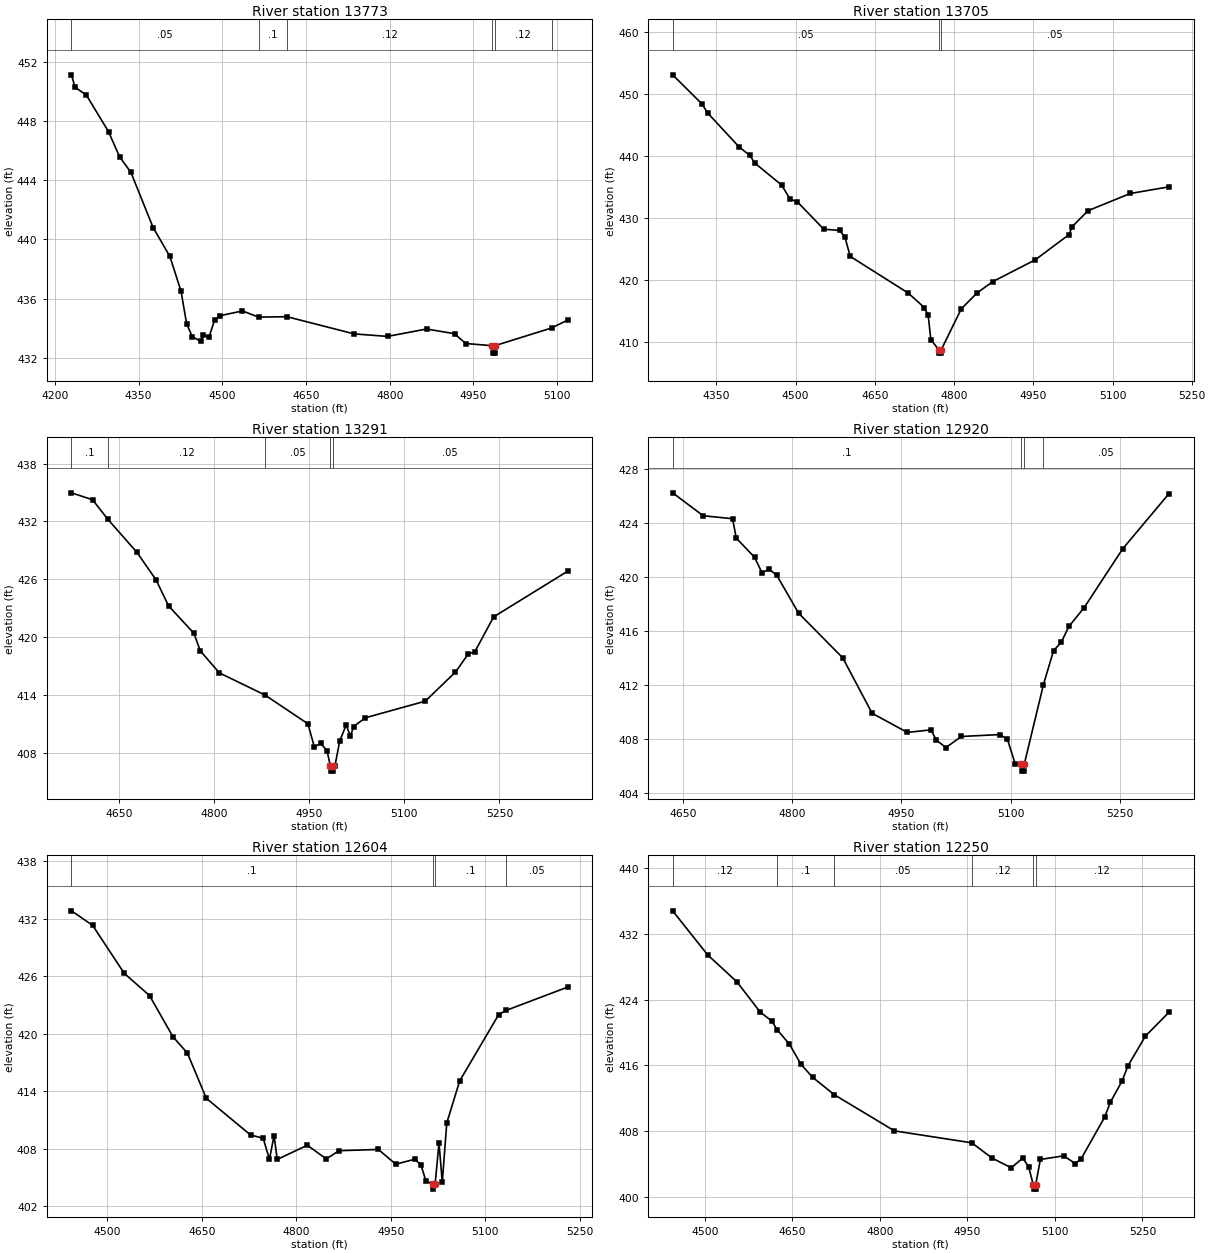
Type RM Length L Ch R = 1,13773,68,68,68
BEGIN DESCRIPTION:
Clear Creek T 4 25.0
END DESCRIPTION:
XS GIS Cut Line= 3
      2758076.04      6793724.60      2758059.30      6794494.82
      2758061.13      6794613.61
#Sta/Elev= 30
  4229.6  451.12  4236.0  450.27  4256.0  449.77  4296.0  447.28  4316.0  445.57
  4336.0  444.54  4376.0  440.80  4406.0  438.85  4426.0  436.50  4436.0  434.30
  4446.0  433.44  4461.2  433.11  4466.2  433.55  4476.1  433.39  4486.1  434.56
  4496.1  434.85  4536.1  435.17  4565.2  434.75  4615.9  434.78  4736.1  433.62
  4796.1  433.45  4866.1  433.95  4916.2  433.63  4936.2  432.97  4984.2  432.82
  4984.4  432.32  4987.9  432.32  4988.2  432.82  5090.2  434.02  5118.8  434.55
#Mann=6,-1,0
  4229.6    0.05       0  4565.2     0.1       0  4615.9    0.12       0
  4984.2    0.07       0  4988.2    0.12       0  5090.2    0.05       0
Bank Sta=4984.2,4988.2
Exp/Cntr=0.3,0.1

Type RM Length L Ch R = 1,13705,414,414,414
BEGIN DESCRIPTION:
Mapping XS 369acfed
END DESCRIPTION:
XS GIS Cut Line= 2
      2758039.49      6793714.99      2758003.78      6794653.71
#Sta/Elev= 30
  4267.1  453.15  4323.1  448.40  4333.2  446.99  4393.2  441.46  4413.2  440.12
  4423.2  438.83  4473.3  435.33  4489.3  433.07  4503.3  432.59  4553.3  428.17
  4583.3  427.97  4593.3  426.89  4603.4  423.77  4713.4  417.83  4743.5  415.50
  4751.0  414.22  4756.0  410.30  4771.5  408.62  4771.7  408.12  4775.2  408.12
  4775.5  408.62  4813.5  415.27  4843.5  417.86  4873.5  419.70  4953.6  423.21
  5017.6  427.29  5023.7  428.59  5053.7  431.17  5133.7  433.95  5206.5  435.02
#Mann=3,-1,0
  4267.1    0.05       0  4771.5    0.03       0  4775.5    0.05       0
Bank Sta=4771.5,4775.5
Exp/Cntr=0.3,0.1

Type RM Length L Ch R = 1,13291,371,371,371
BEGIN DESCRIPTION:
Clear Creek T 4 24.0
END DESCRIPTION:
XS GIS Cut Line= 3
      2757771.40      6793697.65      2757776.00      6794111.00
      2757711.41      6794475.24
#Sta/Elev= 30
  4574.3  434.96  4607.6  434.24  4631.9  432.20  4677.7  428.78  4707.7  425.94
  4727.7  423.22  4767.7  420.38  4777.7  418.56  4807.7  416.28  4879.7  413.98
  4947.7  410.99  4957.7  408.60  4967.7  408.95  4977.7  408.22  4983.2  406.58
  4983.4  406.08  4986.9  406.08  4987.2  406.58  4990.2  406.58  4997.8  409.20
  5008.0  410.87  5014.7  409.71  5019.8  410.71  5038.5  411.62  5132.9  413.34
  5180.6  416.36  5200.9  418.25  5211.1  418.46  5240.9  422.09  5357.6  426.82
#Mann=5,-1,0
  4574.3     0.1       0  4631.9    0.12       0  4879.7    0.05       0
  4983.2    0.04       0  4987.2    0.05       0
Bank Sta=4983.2,4987.2
Exp/Cntr=0.3,0.1

Type RM Length L Ch R = 1,12920,316,316,316
BEGIN DESCRIPTION:
Clear Creek T 4 23.0
END DESCRIPTION:
XS GIS Cut Line= 3
      2757572.03      6793599.46      2757526.00      6793961.00
      2757425.99      6794261.02
#Sta/Elev= 30
  4636.1  426.24  4678.0  424.54  4718.3  424.32  4723.4  422.88  4748.5  421.46
  4758.6  420.32  4768.7  420.56  4778.8  420.14  4809.0  417.31  4869.5  414.00
  4909.8  409.89  4958.1  408.47  4990.5  408.66  4998.0  407.89  5011.1  407.35
  5032.2  408.17  5084.9  408.31  5095.4  407.97  5106.0  406.16  5114.5  406.10
  5114.8  405.60  5118.3  405.60  5118.5  406.10  5144.9  412.02  5158.7  414.53
  5169.2  415.15  5179.8  416.33  5200.8  417.73  5253.5  422.08  5316.8  426.16
#Mann=4,-1,0
  4636.1     0.1       0  5114.5    0.07       0  5118.5     0.1       0
  5144.9    0.05       0
Bank Sta=5114.5,5118.5
Exp/Cntr=0.3,0.1

Type RM Length L Ch R = 1,12604,354,354,354
BEGIN DESCRIPTION:
Clear Creek T 4 22.0
END DESCRIPTION:
XS GIS Cut Line= 3
      2757240.84      6793497.49      2757276.00      6794061.00
      2757327.43      6794277.47
#Sta/Elev= 30
  4443.3  432.81  4476.9  431.29  4527.0  426.29  4567.1  423.97  4604.3  419.67
  4627.2  417.97  4657.2  413.25  4727.4  409.42  4747.4  409.08  4757.4  406.88
  4764.7  409.36  4769.8  406.87  4817.5  408.35  4847.6  406.92  4867.6  407.78
  4930.2  407.91  4957.8  406.37  4987.9  406.89  4997.9  406.29  5005.4  404.67
  5016.2  404.27  5016.4  403.77  5020.2  404.27  5026.4  408.61  5031.6  404.47
  5038.7  410.67  5059.3  415.07  5121.1  421.98  5133.3  422.43  5230.4  424.85
#Mann=4,-1,0
  4443.3     0.1       0  5016.2    0.07       0  5020.2     0.1       0
  5133.3    0.05       0
Bank Sta=5016.2,5020.2
Exp/Cntr=0.3,0.1

Type RM Length L Ch R = 1,12250,350,350,350
BEGIN DESCRIPTION:
Clear Creek T 4 21.0
END DESCRIPTION:
XS GIS Cut Line= 3
      2756976.00      6793510.98      2756976.00      6794061.00
      2756976.00      6794360.98
#Sta/Elev= 30
  4445.0  434.77  4505.0  429.42  4555.0  426.16  4595.0  422.48  4615.0  421.38
  4624.2  420.32  4645.0  418.60  4665.0  416.13  4685.0  414.55  4722.2  412.44
  4825.0  408.06  4957.6  406.61  4992.5  404.75  5025.0  403.58  5045.0  404.76
  5055.0  403.69  5063.0  401.49  5063.3  400.99  5066.8  400.99  5067.0  401.49
  5075.0  404.59  5115.0  405.03  5135.0  404.09  5145.0  404.69  5185.0  409.70
  5195.0  411.55  5215.0  414.10  5225.0  415.94  5255.0  419.56  5295.0  422.43
#Mann=6,-1,0
  4445.0    0.12       0  4624.2     0.1       0  4722.2    0.05       0
  4957.6    0.12       0  5063.0    0.07       0  5067.0    0.12       0
Bank Sta=5063,5067
Exp/Cntr=0.3,0.1

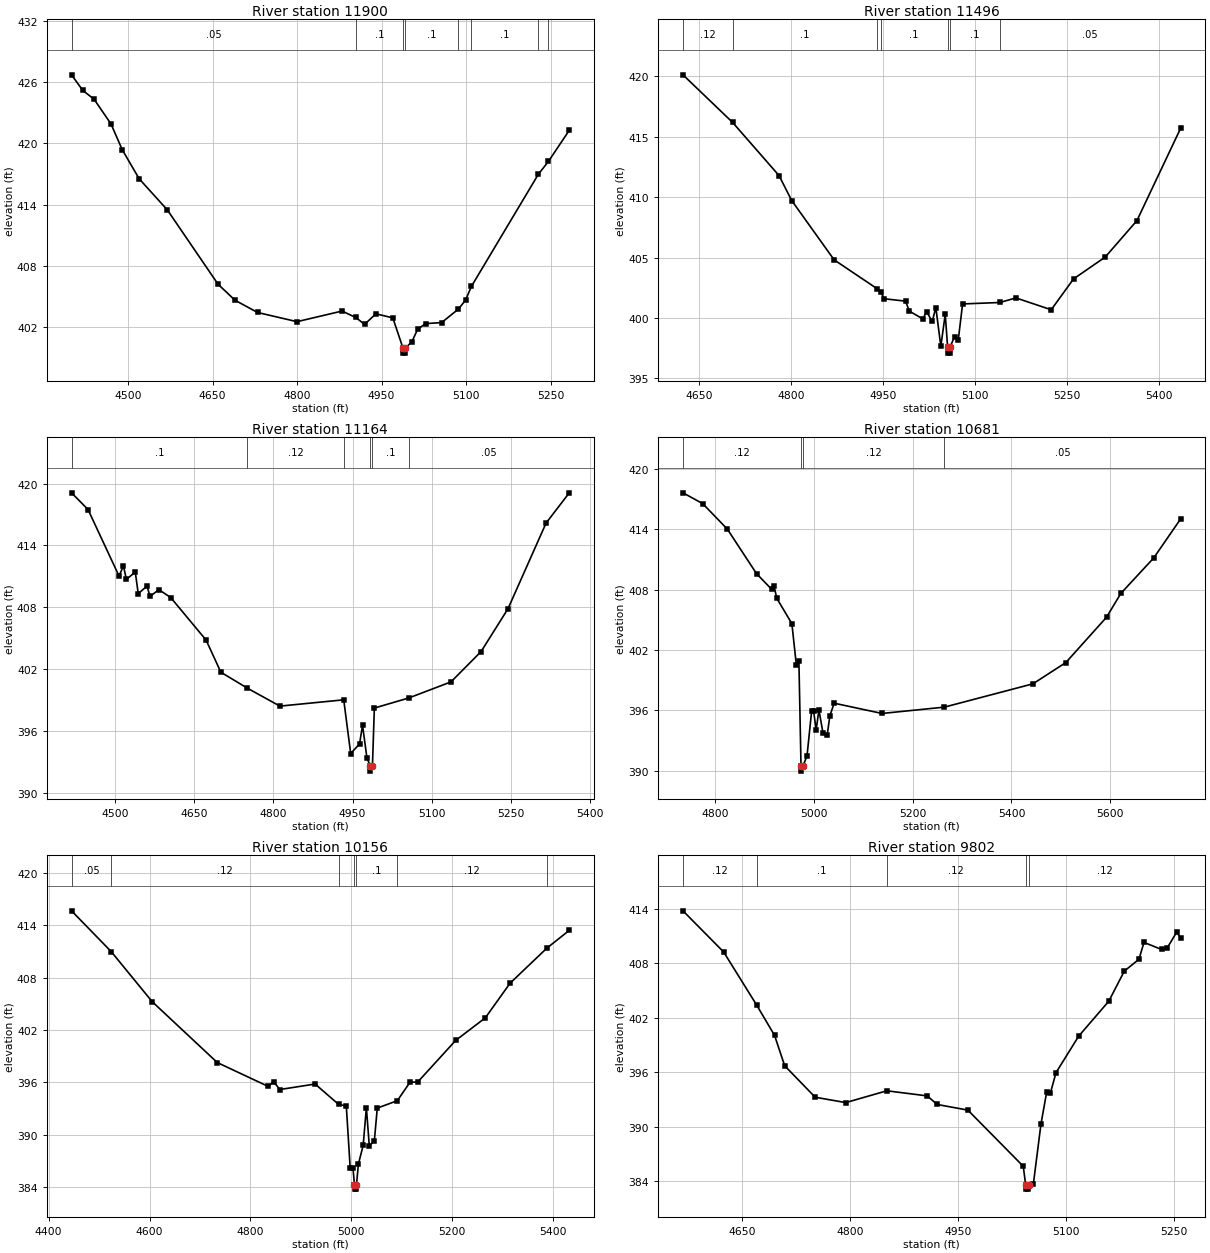
Type RM Length L Ch R = 1,11900,404,404,404
BEGIN DESCRIPTION:
Clear Creek T 4 20.0
END DESCRIPTION:
XS GIS Cut Line= 3
      2756676.00      6793611.00      2756676.00      6794211.00
      2756875.97      6794410.97
#Sta/Elev= 30
  4399.9  426.72  4419.9  425.19  4439.9  424.33  4469.9  421.91  4489.9  419.38
  4519.9  416.54  4569.9  413.49  4659.9  406.21  4689.9  404.65  4729.9  403.45
  4799.9  402.55  4879.9  403.59  4904.0  402.96  4919.9  402.29  4939.9  403.32
  4969.9  402.92  4987.9  399.97  4988.2  399.47  4991.7  399.47  4991.9  399.97
  5003.4  400.55  5014.0  401.81  5028.2  402.36  5056.5  402.46  5086.4  403.79
  5098.9  404.66  5109.3  406.00  5228.3  417.00  5246.0  418.24  5282.7  421.27
#Mann=8,-1,0
  4399.9    0.05       0  4904.0     0.1       0  4987.9    0.07       0
  4991.9     0.1       0  5086.4    0.05       0  5109.3     0.1       0
  5228.3    0.12       0  5246.0    0.05       0
Bank Sta=4987.9,4991.9
Exp/Cntr=0.3,0.1

Type RM Length L Ch R = 1,11496,332,332,332
BEGIN DESCRIPTION:
Clear Creek T 4 19.0
END DESCRIPTION:
XS GIS Cut Line= 3
      2756299.49      6793729.19      2756392.49      6794093.31
      2756626.01      6794461.02
#Sta/Elev= 30
  4624.2  420.12  4705.2  416.18  4780.9  411.78  4801.5  409.72  4870.7  404.81
  4941.1  402.41  4946.4  402.18  4952.4  401.59  4987.3  401.39  4993.2  400.57
  5015.5  399.92  5021.4  400.53  5030.7  399.71  5036.6  400.86  5044.7  397.66
  5051.9  400.30  5055.8  397.59  5056.1  397.09  5059.6  397.09  5059.8  397.59
  5067.1  398.46  5073.1  398.16  5080.2  401.16  5141.1  401.28  5167.1  401.66
  5224.7  400.68  5261.1  403.23  5312.8  405.04  5364.4  408.05  5435.6  415.68
#Mann=7,-1,0
  4624.2    0.12       0  4705.2     0.1       0  4941.1    0.12       0
  4946.4     0.1       0  5055.8    0.07       0  5059.8     0.1       0
  5141.1    0.05       0
Bank Sta=5055.8,5059.8
Exp/Cntr=0.3,0.1

Type RM Length L Ch R = 1,11164,483,483,483
BEGIN DESCRIPTION:
Clear Creek T 4 18.0
END DESCRIPTION:
XS GIS Cut Line= 3
      2755965.76      6793840.59      2756226.00      6794361.00
      2756426.00      6794661.00
#Sta/Elev= 30
  4417.8  419.11  4449.0  417.49  4507.7  411.04  4516.1  412.01  4521.7  410.71
  4538.5  411.42  4544.1  409.33  4560.8  410.06  4566.4  409.06  4583.2  409.71
  4605.6  408.95  4672.6  404.82  4700.6  401.70  4750.8  400.15  4812.4  398.41
  4933.3  399.02  4946.5  393.81  4963.3  394.74  4968.9  396.55  4977.3  393.37
  4983.7  392.60  4983.9  392.10  4987.7  392.60  4991.3  398.22  5056.5  399.20
  5136.4  400.76  5193.4  403.70  5244.5  407.87  5316.6  416.18  5360.2  419.09
#Mann=6,-1,0
  4417.8     0.1       0  4750.8    0.12       0  4933.3     0.1       0
  4983.7    0.07       0  4987.7     0.1       0  5056.5    0.05       0
Bank Sta=4983.7,4987.7
Exp/Cntr=0.3,0.1

Type RM Length L Ch R = 1,10681,525,525,525
BEGIN DESCRIPTION:
Clear Creek T 4 17.0
END DESCRIPTION:
XS GIS Cut Line= 3
      2755773.19      6793955.45      2755827.36      6794214.04
      2756165.78      6794874.14
#Sta/Elev= 30
  4735.8  417.64  4775.6  416.57  4825.5  414.03  4884.5  409.60  4915.1  408.04
  4920.2  408.32  4925.4  407.15  4956.0  404.62  4965.1  400.48  4970.2  400.89
  4974.5  390.44  4974.7  389.94  4978.5  390.44  4986.7  391.49  4995.9  395.89
  5000.0  395.89  5005.1  394.04  5010.7  396.03  5019.1  393.69  5027.3  393.50
  5032.9  395.46  5041.5  396.70  5138.3  395.68  5264.3  396.31  5443.4  398.63
  5510.0  400.75  5592.2  405.26  5621.0  407.62  5687.6  411.16  5741.8  415.03
#Mann=4,-1,0
  4735.8    0.12       0  4974.5    0.07       0  4978.5    0.12       0
  5264.3    0.05       0
Bank Sta=4974.5,4978.5
Exp/Cntr=0.3,0.1

Type RM Length L Ch R = 1,10156,354,354,354
BEGIN DESCRIPTION:
Clear Creek T 4 16.0
END DESCRIPTION:
XS GIS Cut Line= 3
      2755542.05      6794022.59      2755676.00      6794561.00
      2755890.68      6794935.05
#Sta/Elev= 30
  4445.5  415.66  4524.1  410.99  4605.2  405.26  4734.3  398.28  4835.4  395.54
  4845.8  396.10  4858.3  395.19  4928.2  395.82  4974.9  393.48  4990.0  393.31
  4997.7  386.22  5003.2  386.22  5006.2  384.28  5006.5  383.78  5010.0  383.78
  5010.2  384.28  5014.0  386.66  5023.4  388.78  5029.8  393.11  5035.6  388.72
  5045.6  389.33  5051.4  393.06  5091.1  393.91  5116.1  396.01  5131.9  396.07
  5206.7  400.81  5265.5  403.40  5314.6  407.37  5387.2  411.37  5431.6  413.41
#Mann=7,-1,0
  4445.5    0.05       0  4524.1    0.12       0  4974.9     0.1       0
  5006.2    0.07       0  5010.2     0.1       0  5091.1    0.12       0
  5387.2    0.05       0
Bank Sta=5006.2,5010.2
Exp/Cntr=0.3,0.1

Type RM Length L Ch R = 1,9802,318,318,318
BEGIN DESCRIPTION:
Clear Creek T 4 15.0
END DESCRIPTION:
XS GIS Cut Line= 3
      2755176.00      6794361.00      2755476.00      6794661.00
      2755555.59      6794916.22
#Sta/Elev= 30
  4567.4  413.79  4624.0  409.25  4669.7  403.42  4694.7  400.06  4708.8  396.71
  4751.2  393.24  4793.7  392.65  4850.8  393.95  4906.8  393.39  4920.9  392.44
  4963.4  391.82  5040.4  385.63  5043.7  383.61  5043.9  383.11  5047.4  383.11
  5047.7  383.61  5054.5  383.71  5065.0  390.28  5072.9  393.79  5078.2  393.72
  5085.9  395.95  5117.4  399.97  5159.3  403.83  5180.9  407.15  5201.2  408.45
  5208.2  410.31  5232.6  409.53  5240.7  409.73  5253.5  411.42  5259.0  410.84
#Mann=5,-1,0
  4567.4    0.12       0  4669.7     0.1       0  4850.8    0.12       0
  5043.7    0.07       0  5047.7    0.12       0
Bank Sta=5043.7,5047.7
Exp/Cntr=0.3,0.1