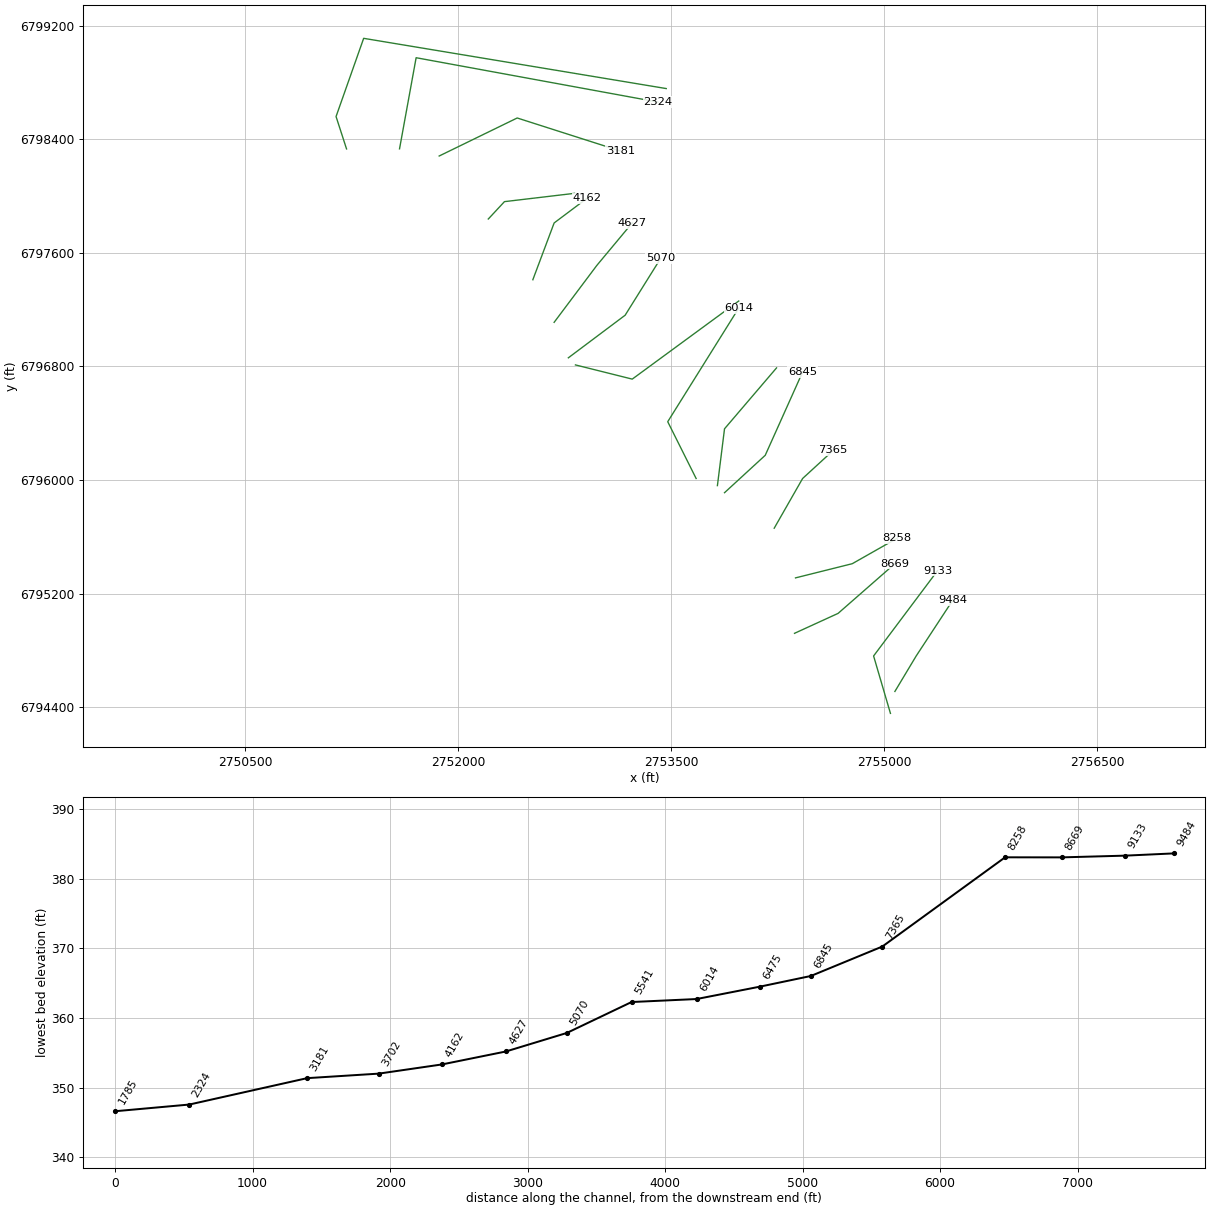
HEC-RAS study Clear Creek T 4.prj: Clear Creek T 4 Base Level Engineering

--- Clear Creek T 4.g01 (geometry) --- (continued)

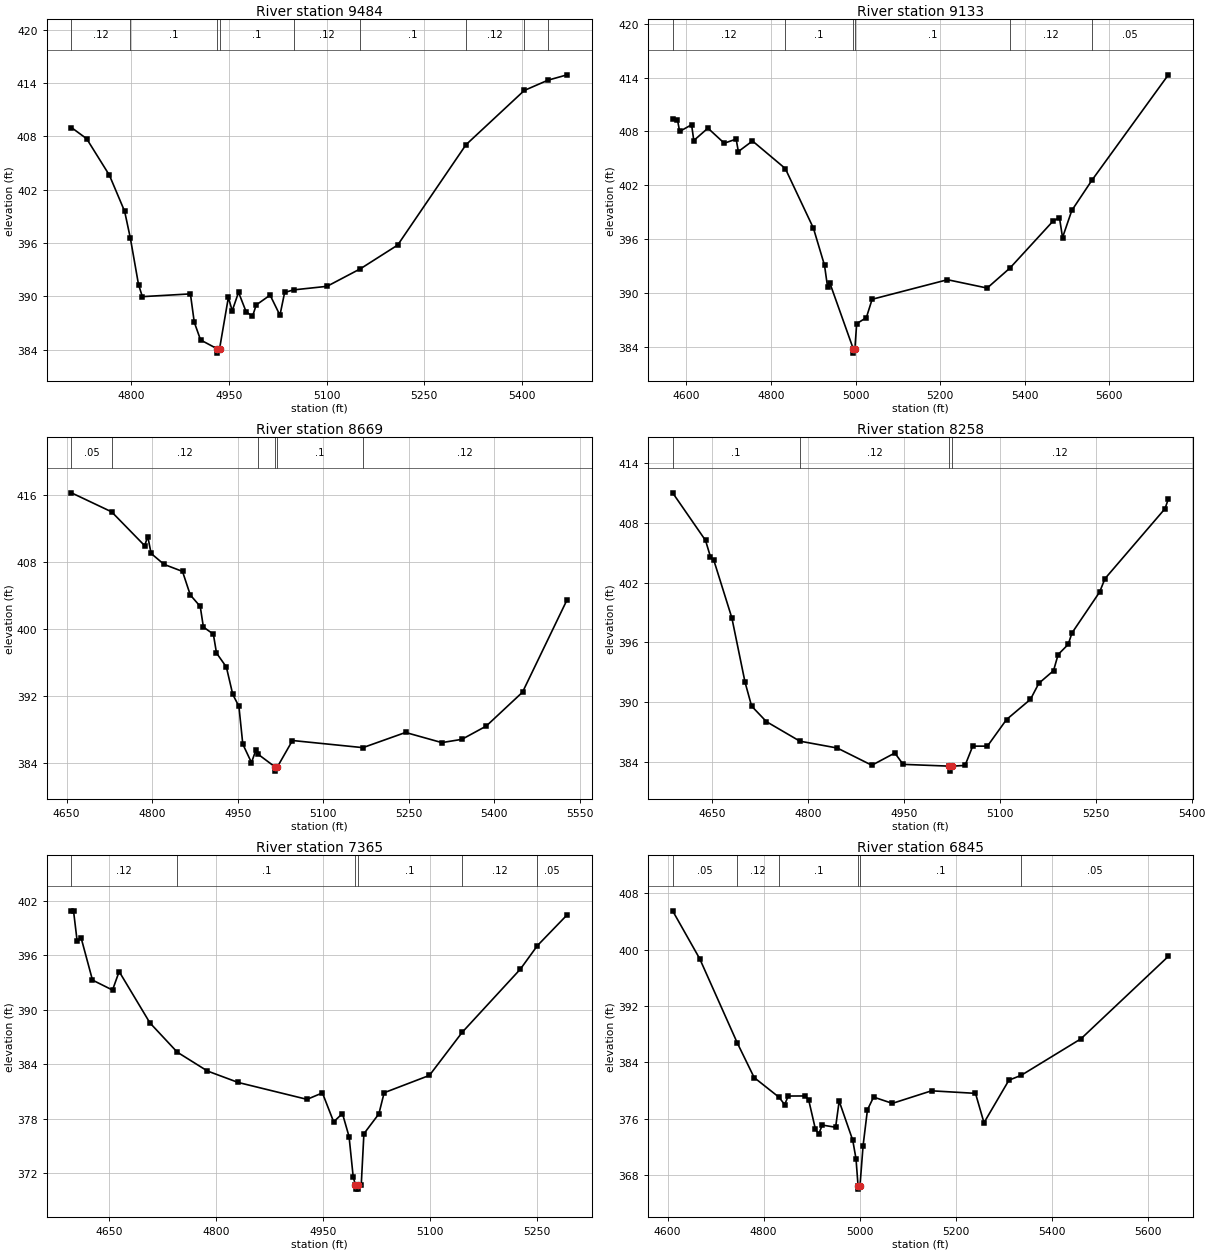
Type RM Length L Ch R = 1,9484,351,351,351
BEGIN DESCRIPTION:
Clear Creek T 4 14.0
END DESCRIPTION:
XS GIS Cut Line= 3
      2755075.99      6794510.99      2755226.00      6794761.00
      2755483.71      6795153.73
#Sta/Elev= 30
  4708.3  408.98  4731.6  407.73  4766.6  403.62  4790.0  399.56  4798.8  396.53
  4811.3  391.33  4817.2  389.97  4891.0  390.28  4896.9  387.10  4906.6  385.10
  4931.8  384.12  4932.0  383.62  4935.8  384.12  4949.3  389.89  4955.2  388.38
  4964.9  390.46  4976.5  388.28  4986.3  387.75  4992.1  389.04  5013.4  390.14
  5028.5  387.88  5035.7  390.44  5049.4  390.73  5100.8  391.13  5152.2  393.11
  5209.3  395.77  5314.2  407.05  5403.7  413.15  5440.2  414.31  5469.6  414.91
#Mann=9,-1,0
  4708.3    0.12       0  4798.8     0.1       0  4931.8    0.07       0
  4935.8     0.1       0  5049.4    0.12       0  5152.2     0.1       0
  5314.2    0.12       0  5403.7    0.05       0  5440.2    0.12       0
Bank Sta=4931.8,4935.8
Exp/Cntr=0.3,0.1

Type RM Length L Ch R = 1,9133,464,464,464
BEGIN DESCRIPTION:
Clear Creek T 4 13.0
END DESCRIPTION:
XS GIS Cut Line= 3
      2755044.67      6794356.67      2754926.00      6794761.00
      2755376.01      6795361.01
#Sta/Elev= 30
  4567.8  409.40  4579.2  409.30  4584.4  408.00  4612.6  408.75  4617.8  406.99
  4651.2  408.37  4689.8  406.69  4717.9  407.15  4723.1  405.76  4756.5  406.94
  4834.0  403.87  4900.5  397.22  4926.7  393.09  4933.9  390.68  4939.1  391.14
  4994.5  383.80  4994.7  383.30  4998.5  383.80  5002.7  386.58  5025.6  387.26
  5039.2  389.30  5217.3  391.48  5311.1  390.55  5365.1  392.79  5467.3  398.04
  5481.9  398.39  5489.2  396.18  5511.1  399.20  5558.7  402.57  5739.2  414.31
#Mann=6,-1,0
  4567.8    0.12       0  4834.0     0.1       0  4994.5    0.07       0
  4998.5     0.1       0  5365.1    0.12       0  5558.7    0.05       0
Bank Sta=4994.5,4998.5
Exp/Cntr=0.3,0.1

Type RM Length L Ch R = 1,8669,411,411,411
BEGIN DESCRIPTION:
Clear Creek T 4 12.0
END DESCRIPTION:
XS GIS Cut Line= 3
      2754368.99      6794920.52      2754676.00      6795061.00
      2755075.98      6795410.98
#Sta/Elev= 30
  4658.6  416.23  4729.1  413.96  4786.9  409.93  4792.4  411.02  4798.3  409.00
  4820.9  407.70  4853.3  406.86  4866.9  404.06  4884.4  402.68  4889.9  400.23
  4907.4  399.38  4912.9  397.13  4930.2  395.46  4941.4  392.20  4952.2  390.77
  4959.0  386.27  4974.2  384.07  4982.0  385.56  4986.1  385.05  5015.6  383.55
  5015.8  383.05  5019.6  383.55  5046.1  386.70  5169.6  385.85  5244.4  387.66
  5308.0  386.45  5343.1  386.84  5385.8  388.42  5449.4  392.46  5527.7  403.50
#Mann=6,-1,0
  4658.6    0.05       0  4729.1    0.12       0  4986.1     0.1       0
  5015.6    0.07       0  5019.6     0.1       0  5169.6    0.12       0
Bank Sta=5015.6,5019.6
Exp/Cntr=0.3,0.1

Type RM Length L Ch R = 1,8258,893,893,893
BEGIN DESCRIPTION:
Clear Creek T 4 11.0
END DESCRIPTION:
XS GIS Cut Line= 3
      2754376.04      6795311.01      2754776.00      6795411.00
      2755092.31      6795590.38
#Sta/Elev= 30
  4587.6  411.01  4639.1  406.23  4646.8  404.58  4652.0  404.25  4680.3  398.45
  4700.9  392.00  4711.2  389.59  4734.4  388.03  4786.7  386.07  4845.3  385.38
  4899.4  383.65  4935.4  384.88  4948.3  383.74  5020.8  383.56  5021.1  383.06
  5024.9  383.56  5045.3  383.63  5057.3  385.57  5080.3  385.57  5110.2  388.24
  5147.7  390.27  5160.8  391.88  5183.8  393.15  5191.0  394.77  5206.8  395.79
  5212.6  396.93  5255.9  401.04  5264.3  402.39  5358.3  409.42  5363.5  410.40
#Mann=4,-1,0
  4587.6     0.1       0  4786.7    0.12       0  5020.8    0.07       0
  5024.9    0.12       0
Bank Sta=5020.8,5024.9
Exp/Cntr=0.3,0.1

Type RM Length L Ch R = 1,7365,520,520,520
BEGIN DESCRIPTION:
Clear Creek T 4 10.0
END DESCRIPTION:
XS GIS Cut Line= 3
      2754226.00      6795661.00      2754426.00      6796011.00
      2754641.34      6796208.50
#Sta/Elev= 30
  4597.5  400.91  4600.4  400.91  4605.4  397.63  4611.2  397.89  4627.0  393.28
  4655.1  392.18  4664.4  394.22  4707.6  388.56  4745.9  385.34  4788.3  383.26
  4831.4  382.00  4927.9  380.14  4949.5  380.85  4965.3  377.66  4977.6  378.58
  4986.9  376.03  4992.7  371.59  4995.7  370.75  4996.0  370.25  4999.5  370.25
  4999.8  370.75  5004.0  370.75  5007.7  376.35  5028.7  378.54  5036.1  380.87
  5099.6  382.78  5145.6  387.53  5227.2  394.49  5251.1  397.08  5292.8  400.47
#Mann=6,-1,0
  4597.5    0.12       0  4745.9     0.1       0  4995.7    0.07       0
  4999.8     0.1       0  5145.6    0.12       0  5251.1    0.05       0
Bank Sta=4995.7,4999.8
Exp/Cntr=0.3,0.1

Type RM Length L Ch R = 1,6845,370,370,370
BEGIN DESCRIPTION:
Clear Creek T 4 9.0
END DESCRIPTION:
XS GIS Cut Line= 3
      2753876.03      6795911.03      2754162.81      6796174.44
      2754426.00      6796761.00
#Sta/Elev= 30
  4610.6  405.51  4667.0  398.71  4745.2  386.77  4780.4  381.85  4832.1  379.06
  4843.9  378.01  4851.3  379.23  4886.5  379.24  4893.9  378.68  4908.0  374.51
  4914.8  373.85  4922.2  375.11  4950.0  374.80  4957.4  378.51  4985.7  372.95
  4992.5  370.31  4996.7  366.52  4997.0  366.02  5000.8  366.52  5007.2  372.18
  5016.3  377.28  5029.1  379.08  5068.2  378.19  5149.7  379.97  5241.3  379.61
  5259.0  375.44  5310.9  381.48  5336.5  382.17  5460.9  387.35  5642.9  399.05
#Mann=6,-1,0
  4610.6    0.05       0  4745.2    0.12       0  4832.1     0.1       0
  4996.7    0.07       0  5000.8     0.1       0  5336.5    0.05       0
Bank Sta=4996.7,5000.8
Exp/Cntr=0.3,0.1

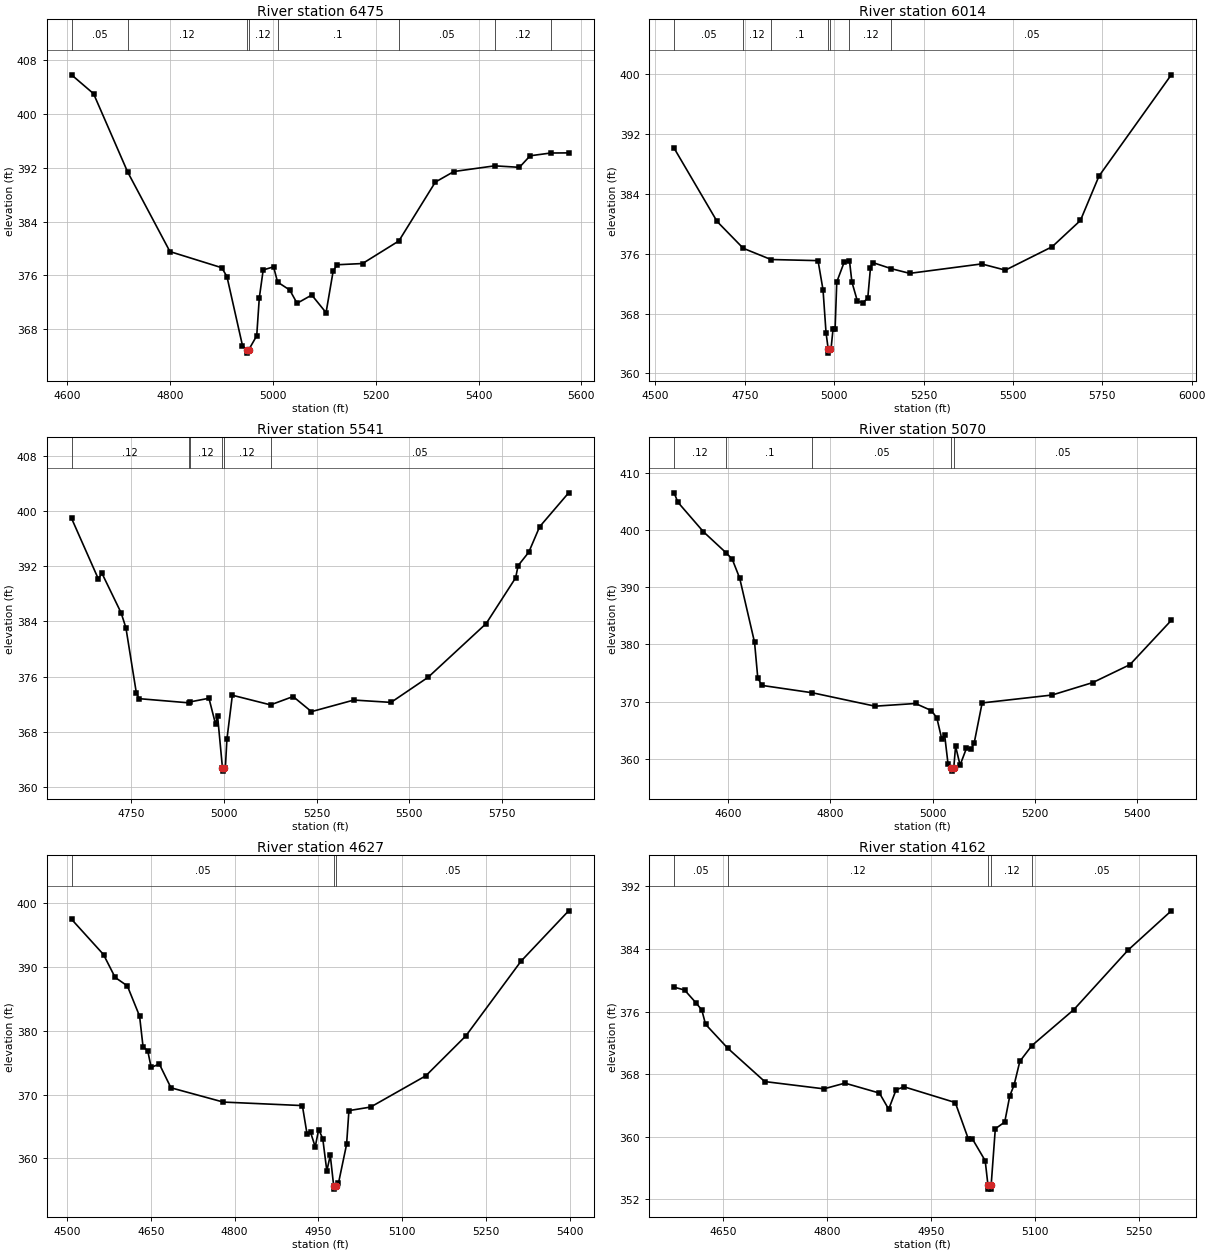
Type RM Length L Ch R = 1,6475,461,461,461
BEGIN DESCRIPTION:
Clear Creek T 4 8.0
END DESCRIPTION:
XS GIS Cut Line= 3
      2753826.00      6795960.97      2753876.00      6796361.00
      2754242.30      6796789.93
#Sta/Elev= 30
  4608.2  405.74  4651.1  402.94  4717.4  391.34  4799.7  379.54  4900.5  377.15
  4910.6  375.83  4940.8  365.60  4948.7  364.99  4949.1  364.49  4953.0  364.99
  4968.5  367.06  4973.5  372.66  4981.1  376.82  5001.3  377.28  5009.1  375.02
  5032.8  373.84  5047.0  371.88  5075.6  373.10  5103.4  370.49  5117.3  376.68
  5125.0  377.59  5174.4  377.77  5245.1  381.12  5316.0  389.84  5352.2  391.41
  5431.4  392.25  5479.6  392.03  5500.4  393.74  5540.4  394.15  5575.4  394.17
#Mann=8,-1,0
  4608.2    0.05       0  4717.4    0.12       0  4948.7    0.07       0
  4953.0    0.12       0  5009.1     0.1       0  5245.1    0.05       0
  5431.4    0.12       0  5540.4    0.05       0
Bank Sta=4948.7,4953
Exp/Cntr=0.3,0.1

Type RM Length L Ch R = 1,6014,473,473,473
BEGIN DESCRIPTION:
Clear Creek T 4 7.0
END DESCRIPTION:
XS GIS Cut Line= 3
      2753676.01      6796010.98      2753476.00      6796411.00
      2753975.98      6797210.97
#Sta/Elev= 30
  4552.4  390.09  4672.6  380.30  4745.7  376.72  4823.2  375.22  4954.9  375.07
  4968.9  371.16  4977.3  365.43  4983.5  363.21  4983.9  362.71  4987.8  363.21
  4991.2  363.24  4996.8  365.89  5002.6  365.89  5007.3  372.22  5028.5  374.92
  5042.9  375.03  5049.7  372.21  5065.1  369.64  5080.4  369.46  5094.0  370.05
  5101.6  374.11  5107.5  374.82  5160.2  373.99  5211.3  373.37  5412.4  374.63
  5479.0  373.80  5609.9  376.93  5688.9  380.44  5740.8  386.37  5943.0  399.90
#Mann=7,-1,0
  4552.4    0.05       0  4745.7    0.12       0  4823.2     0.1       0
  4983.5    0.07       0  4987.8     0.1       0  5042.9    0.12       0
  5160.2    0.05       0
Bank Sta=4983.5,4987.8
Exp/Cntr=0.3,0.1

Type RM Length L Ch R = 1,5541,471,471,471
BEGIN DESCRIPTION:
Clear Creek T 4 6.0
END DESCRIPTION:
XS GIS Cut Line= 3
      2752826.01      6796811.00      2753226.00      6796711.00
      2753976.04      6797261.03
#Sta/Elev= 30
  4588.1  398.96  4660.2  390.20  4670.5  390.95  4722.1  385.23  4735.0  383.06
  4763.3  373.57  4771.0  372.79  4904.0  372.19  4907.1  372.31  4959.2  372.85
  4977.2  369.06  4982.4  370.33  4995.6  362.78  4996.0  362.28  5000.0  362.78
  5003.5  362.78  5007.7  366.90  5022.4  373.29  5125.5  371.89  5186.4  373.10
  5236.0  370.91  5350.4  372.59  5450.8  372.25  5551.1  375.90  5707.8  383.69
  5787.3  390.32  5794.0  392.09  5822.8  394.04  5852.1  397.73  5930.5  402.65
#Mann=6,-1,0
  4588.1    0.12       0  4904.0    0.05       0  4907.1    0.12       0
  4995.6    0.07       0  5000.0    0.12       0  5125.5    0.05       0
Bank Sta=4995.6,5000
Exp/Cntr=0.3,0.1

Type RM Length L Ch R = 1,5070,443,443,443
BEGIN DESCRIPTION:
Clear Creek T 4 5.0
END DESCRIPTION:
XS GIS Cut Line= 3
      2752776.04      6796861.03      2753176.00      6797161.00
      2753426.03      6797561.04
#Sta/Elev= 30
  4494.7  406.48  4501.9  404.85  4551.9  399.68  4596.6  395.97  4608.2  394.89
  4622.8  391.57  4651.9  380.34  4658.2  374.11  4666.5  372.82  4765.1  371.53
  4887.4  369.19  4966.5  369.66  4997.6  368.42  5008.2  367.15  5017.6  363.52
  5023.5  364.10  5030.0  359.14  5036.6  358.34  5037.1  357.84  5041.2  358.34
  5044.8  362.19  5053.6  358.89  5066.0  361.82  5075.4  361.70  5081.3  362.82
  5096.7  369.76  5233.4  371.14  5313.0  373.32  5385.6  376.45  5466.4  384.19
#Mann=5,-1,0
  4494.7    0.12       0  4596.6     0.1       0  4765.1    0.05       0
  5036.6    0.05       0  5041.2    0.05       0
Bank Sta=5036.6,5041.2
Exp/Cntr=0.3,0.1

Type RM Length L Ch R = 1,4627,465,465,465
BEGIN DESCRIPTION:
Clear Creek T 4 4.0
END DESCRIPTION:
XS GIS Cut Line= 3
      2752676.00      6797111.00      2752976.00      6797511.00
      2753226.00      6797810.99
#Sta/Elev= 30
  4507.8  397.53  4565.1  391.99  4585.9  388.40  4607.8  387.07  4629.7  382.33
  4635.9  377.53  4644.3  376.88  4650.5  374.28  4665.1  374.81  4685.9  371.08
  4779.7  368.84  4921.3  368.29  4929.7  363.82  4935.9  364.11  4944.3  361.82
  4950.5  364.53  4957.8  363.12  4965.1  358.04  4971.3  360.48  4977.4  355.68
  4977.9  355.18  4982.0  355.68  4985.9  356.08  5000.5  362.20  5004.7  367.50
  5043.6  368.06  5142.5  372.97  5214.1  379.22  5313.0  390.95  5398.3  398.85
#Mann=3,-1,0
  4507.8    0.05       0  4977.4    0.05       0  4982.0    0.05       0
Bank Sta=4977.4,4982
Exp/Cntr=0.3,0.1

Type RM Length L Ch R = 1,4162,460,460,460
BEGIN DESCRIPTION:
Clear Creek T 4 3.0
END DESCRIPTION:
XS GIS Cut Line= 3
      2752526.02      6797411.04      2752676.00      6797811.00
      2752908.37      6797985.25
#Sta/Elev= 30
  4578.9  379.12  4594.0  378.75  4610.9  377.07  4618.9  376.19  4624.2  374.38
  4656.4  371.31  4709.7  367.06  4795.1  366.13  4825.4  366.86  4875.2  365.59
  4888.6  363.53  4899.3  366.01  4910.8  366.39  4984.7  364.38  5003.4  359.77
  5009.2  359.77  5027.9  356.95  5031.9  353.82  5032.3  353.32  5036.0  353.32
  5036.5  353.82  5042.5  361.03  5056.1  361.89  5063.4  365.23  5069.6  366.62
  5077.9  369.64  5095.2  371.65  5156.0  376.26  5234.2  383.86  5296.5  388.87
#Mann=5,-1,0
  4578.9    0.05       0  4656.4    0.12       0  5031.9    0.07       0
  5036.5    0.12       0  5095.2    0.05       0
Bank Sta=5031.9,5036.5
Exp/Cntr=0.3,0.1

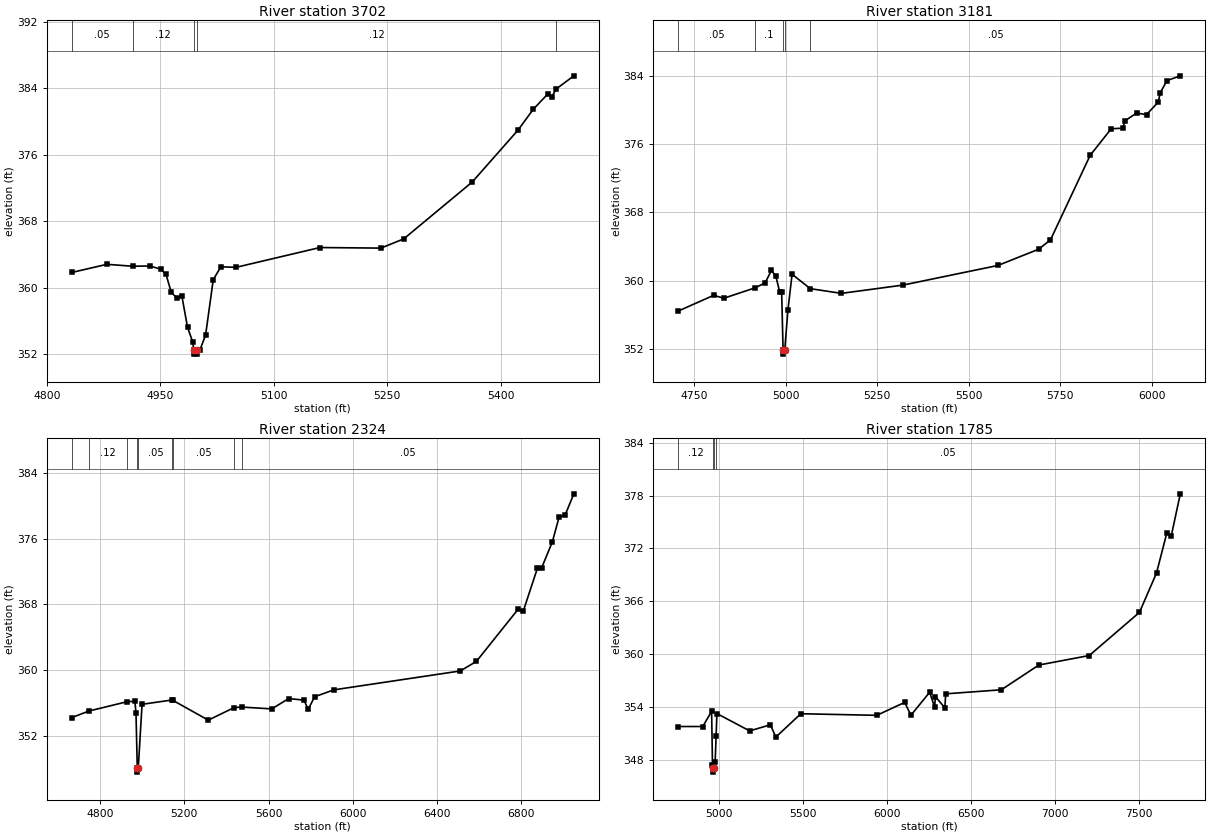
Type RM Length L Ch R = 1,3702,521,521,521
BEGIN DESCRIPTION:
Clear Creek T 4 2.0
END DESCRIPTION:
XS GIS Cut Line= 3
      2752212.36      6797838.79      2752326.00      6797961.00
      2752819.27      6798019.48
#Sta/Elev= 30
  4832.9  361.82  4879.3  362.80  4913.4  362.57  4936.0  362.60  4950.2  362.23
  4957.5  361.59  4964.4  359.42  4971.7  358.77  4978.5  358.95  4985.9  355.23
  4992.7  353.47  4994.1  352.50  4994.5  352.00  4998.2  352.00  4998.7  352.50
  5002.3  352.50  5009.8  354.30  5019.9  360.96  5030.0  362.50  5050.1  362.44
  5160.9  364.82  5241.5  364.75  5271.7  365.86  5362.3  372.71  5422.7  378.94
  5442.9  381.45  5462.5  383.33  5467.5  382.95  5473.2  383.89  5496.5  385.47
#Mann=5,-1,0
  4832.9    0.05       0  4913.4    0.12       0  4994.1    0.07       0
  4998.7    0.12       0  5473.2    0.05       0
Bank Sta=4994.1,4998.7
Exp/Cntr=0.3,0.1

Type RM Length L Ch R = 1,3181,857,857,857
BEGIN DESCRIPTION:
Mapping XS 8f738c96
END DESCRIPTION:
XS GIS Cut Line= 3
      2751866.28      6798282.44      2752415.81      6798550.26
      2753140.71      6798318.41
#Sta/Elev= 30
  4706.1  356.41  4802.9  358.26  4831.0  357.92  4916.8  359.15  4943.7  359.73
  4960.7  361.18  4972.8  360.52  4983.2  358.70  4988.8  358.61  4992.7  351.85
  4993.2  351.35  4997.3  351.85  5005.8  356.49  5017.3  360.73  5067.2  359.04
  5152.1  358.49  5320.2  359.46  5580.1  361.77  5691.4  363.68  5723.6  364.77
  5832.1  374.71  5889.6  377.83  5921.8  377.90  5927.1  378.76  5959.2  379.68
  5986.1  379.49  6018.3  380.97  6023.5  382.05  6042.1  383.49  6078.5  384.05
#Mann=5,-1,0
  4706.1    0.05       0  4916.8     0.1       0  4992.7    0.07       0
  4997.3     0.1       0  5067.2    0.05       0
Bank Sta=4992.7,4997.3
Exp/Cntr=0.3,0.1

Type RM Length L Ch R = 1,2324,539,539,539
BEGIN DESCRIPTION:
Mapping XS eb87e6cb
END DESCRIPTION:
XS GIS Cut Line= 3
      2751586.99      6798332.83      2751703.89      6798974.69
      2753406.09      6798662.51
#Sta/Elev= 30
  4665.9  354.20  4747.1  355.00  4929.1  356.14  4965.6  356.18  4970.7  354.74
  4976.8  348.06  4977.3  347.56  4981.5  348.06  4999.5  355.82  5143.5  356.35
  5145.7  356.30  5313.9  353.89  5437.1  355.43  5474.5  355.48  5615.3  355.26
  5695.3  356.52  5767.8  356.33  5788.1  355.21  5818.6  356.74  5910.1  357.58
  6510.0  359.88  6586.2  361.04  6784.5  367.40  6808.9  367.17  6876.0  372.39
  6896.3  372.45  6947.1  375.62  6978.4  378.57  7008.1  378.90  7048.9  381.45
#Mann=9,-1,0
  4665.9    0.05       0  4747.1    0.12       0  4929.1    0.05       0
  4976.8    0.04       0  4981.5    0.05       0  5143.5    0.12       0
  5145.7    0.05       0  5437.1    0.12       0  5474.5    0.05       0
Bank Sta=4976.8,4981.5
Exp/Cntr=0.3,0.1

Type RM Length L Ch R = 1,1785,0,0,0
BEGIN DESCRIPTION:
Clear Creek T 4 1.0
END DESCRIPTION:
XS GIS Cut Line= 4
      2751213.75      6798332.30      2751139.90      6798560.34
      2751334.32      6799111.24      2753465.55      6798757.47
#Sta/Elev= 30
  4760.3  351.78  4906.1  351.78  4958.7  353.50  4963.9  347.38  4966.8  347.10
  4967.3  346.60  4971.5  347.10  4979.7  347.70  4985.3  350.66  4990.2  353.25
  5184.9  351.28  5308.7  351.98  5340.0  350.57  5488.9  353.23  5940.7  353.05
  6106.4  354.52  6143.4  353.06  6254.9  355.67  6284.1  353.99  6289.2  355.17
  6345.1  353.90  6350.1  355.49  6680.7  355.95  6903.7  358.76  7203.4  359.84
  7501.8  364.74  7603.1  369.21  7664.0  373.72  7690.9  373.43  7744.6  378.20
#Mann=4,-1,0
  4760.3    0.12       0  4966.8    0.04       0  4971.5    0.12       0
  4985.3    0.05       0
Bank Sta=4966.8,4971.5
Exp/Cntr=0.3,0.1

Chan Stop Cuts=-1