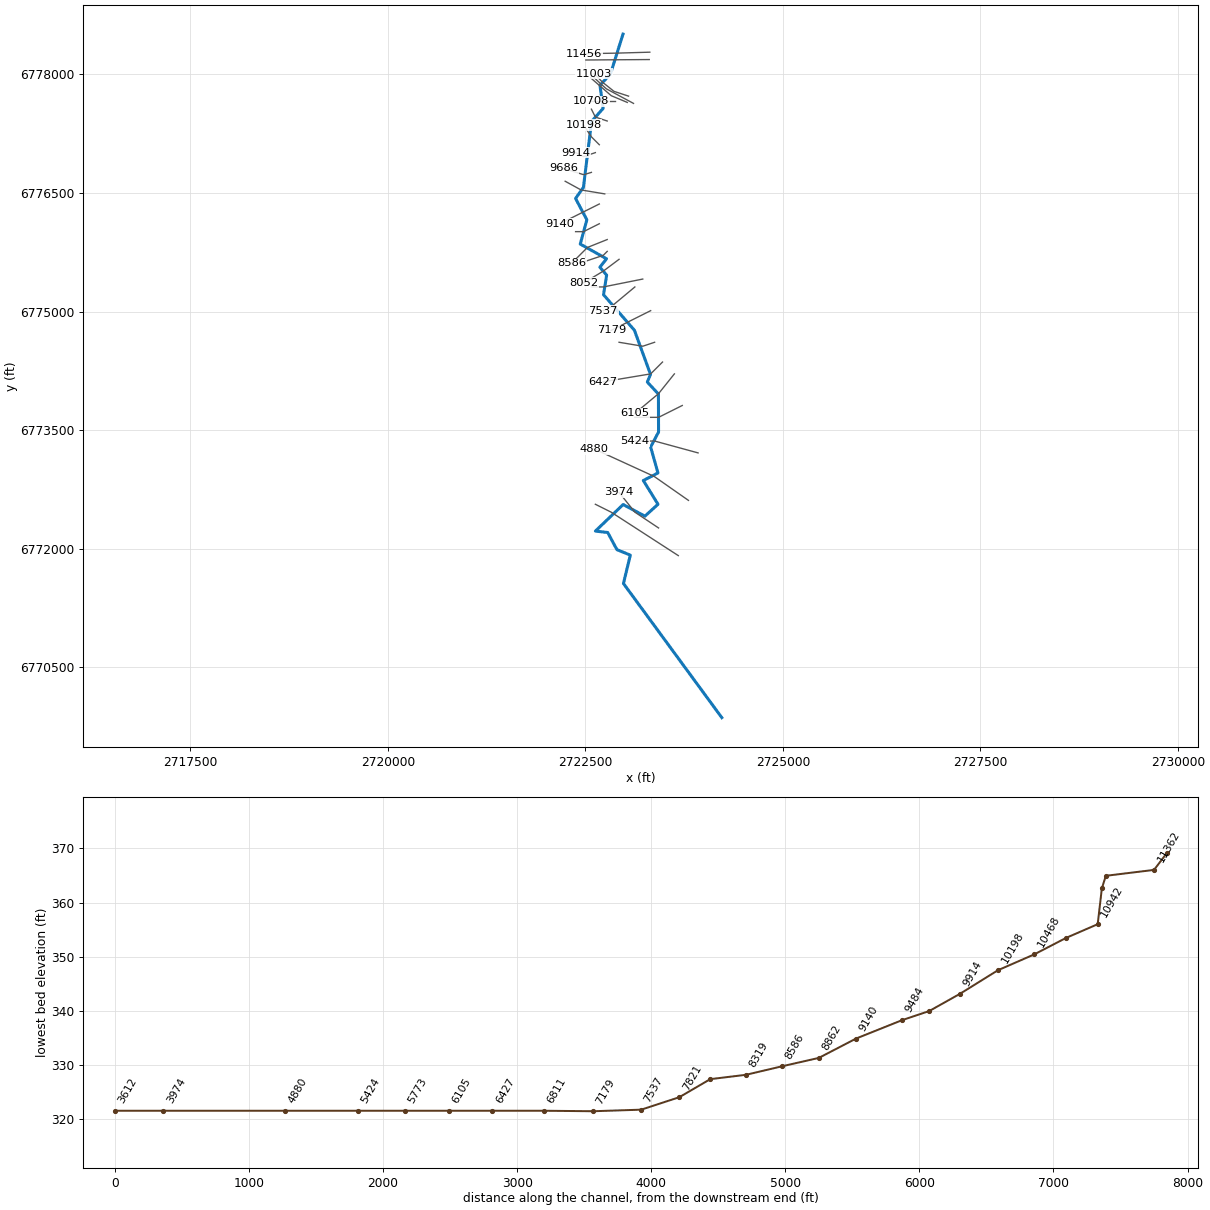
--- Clear Creek T 40.prj (project) ---

Proj Title=Clear Creek T 40 Base Level Engineering
Current Plan=p01
Default Exp/Contr=0.3,0.1
English Units
Geom File=g01
Flow File=f01
Plan File=p01
BEGIN DESCRIPTION:
Clear Creek T 40
END DESCRIPTION:

--- Clear Creek T 40.p01 (plan) ---

Plan Title=Multiple Run
Short Identifier=Multiple
Geom File=g01
Flow File=f01
Subcritical Flow
K Sum by GR= 0
Std Step Tol= 0.01
Critical Tol= 0.01
Num of Std Step Trials= 20
Max Error Tol= 0.3
Flow Tol Ratio= 0.001
Split Flow NTrial= 30
Split Flow Tol= 0.02
Split Flow Ratio= 0.02
Log Output Level= 0
Friction Slope Method= 1
Unsteady Friction Slope Method= 2
Unsteady Bridges Friction Slope Method= 1
Parabolic Critical Depth
Global Vel Dist=  1 , 1 , 1
Global Log Level= 0
CheckData=True
Encroach Param= -1, 0, 0, 0
BEGIN DESCRIPTION:
Multiple Run
END DESCRIPTION:

--- Clear Creek T 40.f01 (steady flow) ---

Flow Title=Multiple
Number of Profiles=7
Profile Names=10-year,25-year,50-year,1pct_min,100-year,1pct_plu,500-year
River Rch & RM= Clear Creek T 40,Reach-1,11456
      95     113     125      69     138     276     168
River Rch & RM= Clear Creek T 40,Reach-1,9914
     538     712     852     505    1008    2011    1410
Boundary for River Rch & Prof#=Clear Creek T 40,Reach-1,1
Up Type=0
Dn Type=3
Dn Slope=0.005
Boundary for River Rch & Prof#=Clear Creek T 40,Reach-1,2
Up Type=0
Dn Type=3
Dn Slope=0.005
Boundary for River Rch & Prof#=Clear Creek T 40,Reach-1,3
Up Type=0
Dn Type=3
Dn Slope=0.005
Boundary for River Rch & Prof#=Clear Creek T 40,Reach-1,4
Up Type=0
Dn Type=3
Dn Slope=0.005
Boundary for River Rch & Prof#=Clear Creek T 40,Reach-1,5
Up Type=0
Dn Type=3
Dn Slope=0.005
Boundary for River Rch & Prof#=Clear Creek T 40,Reach-1,6
Up Type=0
Dn Type=3
Dn Slope=0.005
Boundary for River Rch & Prof#=Clear Creek T 40,Reach-1,7
Up Type=0
Dn Type=3
Dn Slope=0.005

--- Clear Creek T 40.g01 (geometry) ---

Geom Title=Existing Conditions

River Reach=Clear Creek T 40,Reach-1
Reach XY= 30
      2722976.00      6778511.00      2722816.70      6778004.33
      2722683.82      6777864.41      2722725.06      6777571.48
      2722578.17      6777405.56      2722474.79      6776570.59
      2722375.53      6776431.16      2722518.44      6776161.00
      2722435.01      6775853.98      2722767.03      6775667.70
      2722683.12      6775561.00      2722768.66      6775461.10
      2722729.75      6775212.55      2723120.15      6774763.29
      2723324.14      6774204.86      2723283.82      6774107.59
      2723424.26      6773955.37      2723425.77      6773475.10
      2723325.68      6773285.97      2723418.35      6772957.31
      2723233.19      6772861.33      2723418.92      6772560.99
      2723253.23      6772410.51      2722977.73      6772557.69
      2722626.54      6772221.31      2722782.33      6772203.62
      2722899.01      6771986.64      2723068.54      6771917.08
      2722981.40      6771558.57      2724226.00      6769861.00

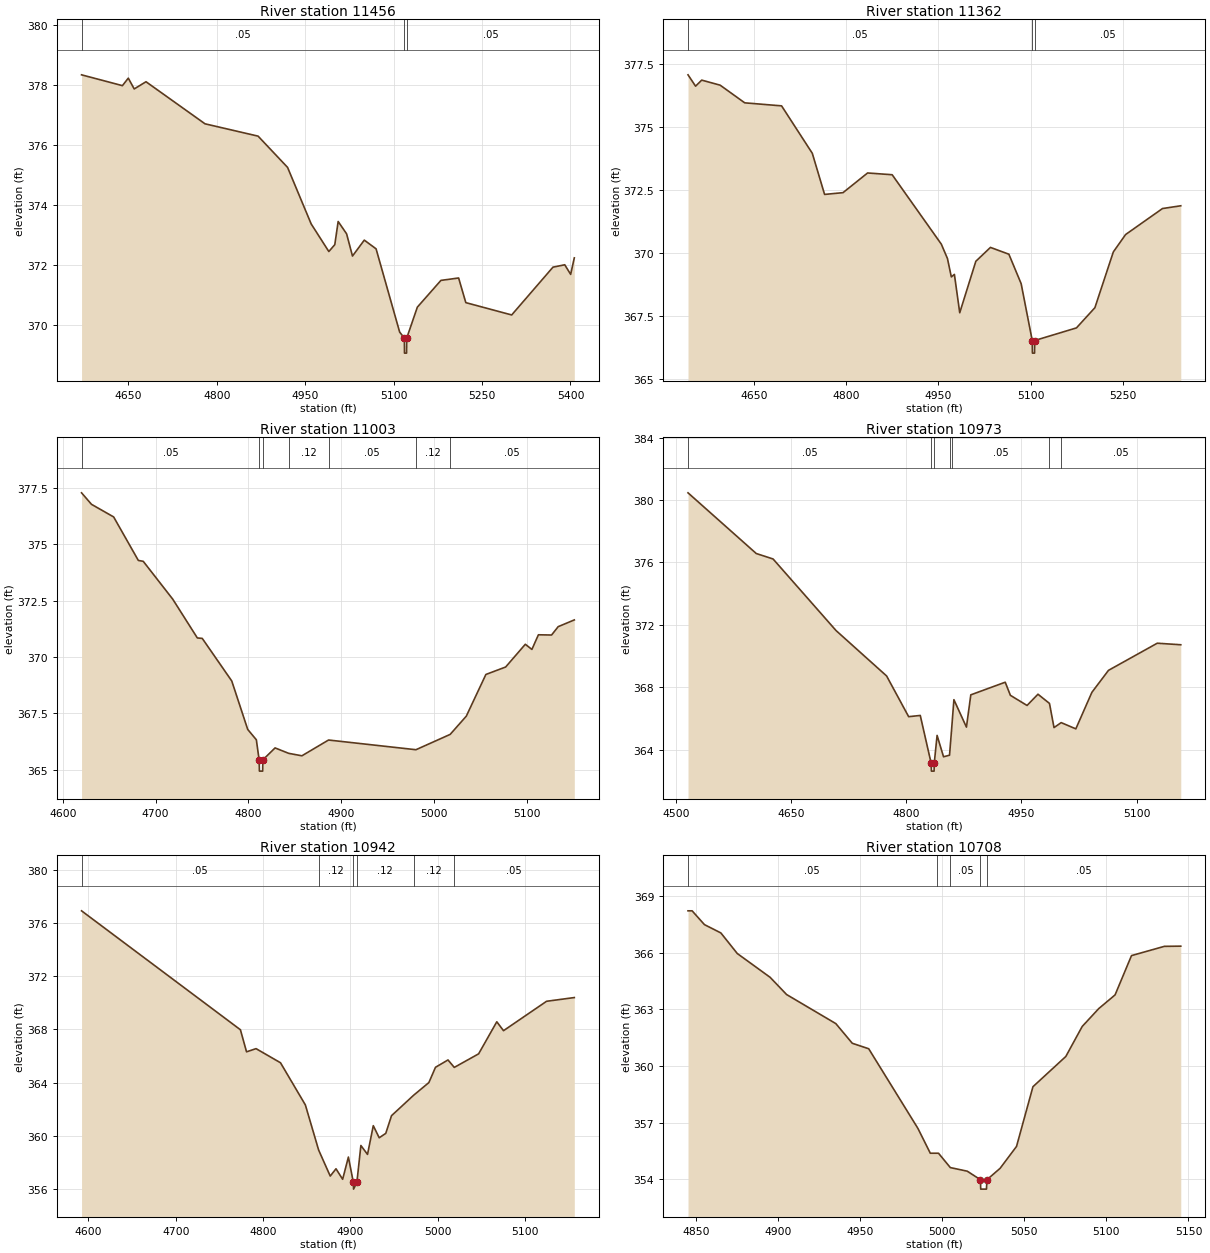
Type RM Length L Ch R = 1,11456,94,94,94
BEGIN DESCRIPTION:
Clear Creek T 40 25.0
END DESCRIPTION:
XS GIS Cut Line= 3
      2723315.28      6778282.13      2722879.48      6778269.74
      2722479.81      6778262.72
#Sta/Elev= 30
  4570.8  378.34  4640.1  377.98  4650.1  378.23  4660.1  377.87  4680.1  378.11
  4780.2  376.71  4870.2  376.30  4920.2  375.26  4960.2  373.38  4990.2  372.46
  5000.3  372.69  5006.0  373.46  5020.3  373.05  5030.3  372.31  5050.3  372.84
  5070.3  372.55  5110.3  369.78  5118.3  369.58  5118.5  369.08  5122.0  369.08
  5122.3  369.58  5140.3  370.61  5180.3  371.50  5210.3  371.58  5222.5  370.76
  5300.3  370.35  5370.3  371.94  5390.3  372.02  5400.3  371.70  5406.5  372.25
#Mann=3,-1,0
  4570.8    0.05       0  5118.3    0.05       0  5122.3    0.05       0
Bank Sta=5118.3,5122.3
Exp/Cntr=0.3,0.1

Type RM Length L Ch R = 1,11362,359,359,359
BEGIN DESCRIPTION:
Clear Creek T 40 24.0
END DESCRIPTION:
XS GIS Cut Line= 3
      2723308.30      6778188.89      2722838.55      6778185.73
      2722506.22      6778183.24
#Sta/Elev= 30
  4542.5  377.06  4554.8  376.61  4564.8  376.85  4594.8  376.65  4634.8  375.95
  4694.8  375.83  4744.8  373.95  4764.8  372.32  4794.8  372.39  4834.8  373.17
  4874.8  373.10  4954.8  370.35  4964.8  369.78  4971.1  369.05  4976.1  369.15
  4984.8  367.63  5011.0  369.67  5034.8  370.22  5064.8  369.95  5084.8  368.78
  5102.8  366.53  5103.1  366.03  5106.6  366.03  5106.8  366.53  5174.8  367.03
  5204.8  367.83  5234.8  370.04  5254.8  370.73  5314.8  371.76  5344.6  371.87
#Mann=3,-1,0
  4542.5    0.05       0  5102.8    0.05       0  5106.8    0.05       0
Bank Sta=5102.8,5106.8
Exp/Cntr=0.3,0.1

Type RM Length L Ch R = 1,11003,30,30,30
BEGIN DESCRIPTION:
Mapping XS 935f5909
END DESCRIPTION:
XS GIS Cut Line= 4
      2723046.16      6777725.93      2722861.52      6777786.58
      2722717.56      6777901.43      2722610.56      6778010.21
#Sta/Elev= 30
  4620.2  377.29  4630.9  376.78  4654.8  376.22  4681.4  374.29  4686.7  374.25
  4718.5  372.57  4745.0  370.85  4750.3  370.83  4782.1  368.94  4799.3  366.79
  4808.6  366.33  4811.6  365.44  4811.9  364.94  4815.4  364.94  4815.6  365.44
  4828.8  365.97  4843.4  365.73  4857.7  365.62  4886.4  366.32  4980.6  365.89
  5017.5  366.57  5034.9  367.38  5056.0  369.23  5077.3  369.56  5098.5  370.57
  5105.6  370.34  5112.6  370.99  5126.8  370.98  5133.9  371.35  5151.3  371.65
#Mann=7,-1,0
  4620.2    0.05       0  4811.6    0.07       0  4815.6    0.05       0
  4843.4    0.12       0  4886.4    0.05       0  4980.6    0.12       0
  5017.5    0.05       0
Bank Sta=4811.6,4815.6
Exp/Cntr=0.3,0.1

Type RM Length L Ch R = 1,10973,31,31,31
BEGIN DESCRIPTION:
Clear Creek T 40 23.0
END DESCRIPTION:
XS GIS Cut Line= 4
      2723109.00      6777633.89      2722765.85      6777818.12
      2722695.30      6777881.03      2722579.84      6777988.00
#Sta/Elev= 30
  4516.0  380.46  4604.8  376.57  4626.7  376.22  4708.7  371.63  4774.5  368.72
  4803.2  366.11  4818.3  366.19  4832.5  363.12  4832.8  362.62  4836.3  362.62
  4836.5  363.12  4840.2  364.91  4848.6  363.54  4856.4  363.64  4859.7  365.67
  4862.1  367.20  4878.4  365.44  4884.1  367.51  4928.9  368.32  4935.6  367.48
  4957.3  366.83  4971.5  367.55  4986.5  366.96  4992.4  365.41  5001.7  365.73
  5020.8  365.33  5041.7  367.67  5063.3  369.08  5126.8  370.82  5157.4  370.72
#Mann=7,-1,0
  4516.0    0.05       0  4832.5    0.07       0  4836.5    0.05       0
  4856.4    0.12       0  4859.7    0.05       0  4986.5    0.12       0
  5001.7    0.05       0
Bank Sta=4832.5,4836.5
Exp/Cntr=0.3,0.1

Type RM Length L Ch R = 1,10942,234,234,234
BEGIN DESCRIPTION:
Mapping XS 00cd4207
END DESCRIPTION:
XS GIS Cut Line= 3
      2723030.38      6777646.32      2722827.48      6777731.23
      2722567.06      6777956.84
#Sta/Elev= 30
  4592.1  376.91  4774.1  367.97  4781.1  366.31  4792.0  366.55  4820.0  365.49
  4848.5  362.32  4863.7  358.93  4877.0  356.97  4883.6  357.52  4891.2  356.73
  4897.8  358.40  4903.5  356.49  4903.7  355.99  4907.5  356.49  4912.1  359.27
  4919.7  358.60  4926.3  360.76  4933.1  359.85  4940.6  360.18  4947.2  361.51
  4972.4  363.04  4990.0  364.00  4997.6  365.15  5011.9  365.70  5019.1  365.14
  5047.0  366.16  5067.8  368.57  5075.5  367.90  5124.8  370.11  5156.6  370.39
#Mann=6,-1,0
  4592.1    0.05       0  4863.7    0.12       0  4903.5    0.07       0
  4907.5    0.12       0  4972.4    0.12       0  5019.1    0.05       0
Bank Sta=4903.5,4907.5
Exp/Cntr=0.3,0.1

Type RM Length L Ch R = 1,10708,240,240,240
BEGIN DESCRIPTION:
Clear Creek T 40 22.0
END DESCRIPTION:
XS GIS Cut Line= 3
      2722875.99      6777661.00      2722726.00      6777661.00
      2722575.99      6777661.00
#Sta/Elev= 30
  4845.3  368.21  4847.8  368.21  4855.3  367.48  4865.3  367.04  4875.3  365.95
  4895.3  364.69  4905.3  363.78  4935.3  362.24  4945.3  361.20  4955.3  360.91
  4985.3  356.69  4992.8  355.38  4996.6  355.38  4997.8  355.38  5005.0  354.62
  5015.3  354.43  5023.3  353.98  5023.5  353.48  5027.0  353.48  5027.3  353.98
  5035.3  354.58  5045.3  355.74  5055.3  358.90  5075.3  360.50  5085.3  362.09
  5095.3  363.03  5105.3  363.76  5115.3  365.84  5135.3  366.33  5145.3  366.34
#Mann=5,-1,0
  4845.3    0.05       0  4996.6    0.12       0  5005.0    0.05       0
  5023.3    0.07       0  5027.3    0.05       0
Bank Sta=5023.3,5027.3
Exp/Cntr=0.3,0.1

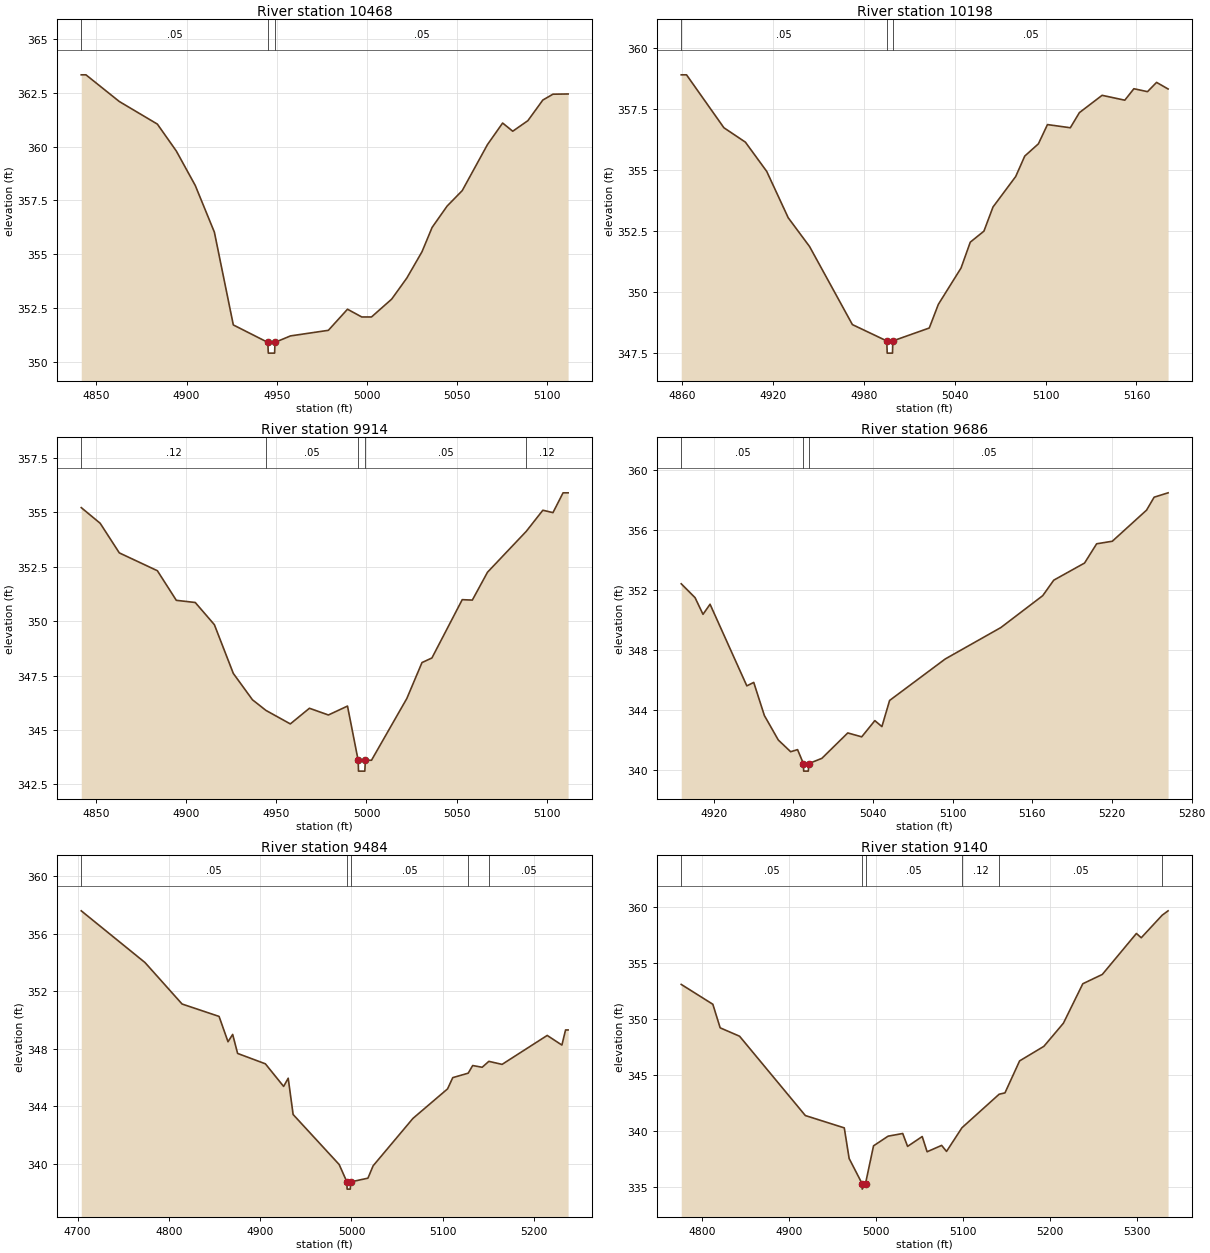
Type RM Length L Ch R = 1,10468,270,270,270
BEGIN DESCRIPTION:
Clear Creek T 40 21.0
END DESCRIPTION:
XS GIS Cut Line= 3
      2722776.00      6777411.00      2722626.00      6777461.00
      2722576.01      6777560.98
#Sta/Elev= 30
  4841.6  363.33  4844.2  363.33  4862.7  362.09  4883.8  361.04  4894.3  359.79
  4904.8  358.19  4915.4  356.02  4925.9  351.71  4945.0  350.90  4945.3  350.40
  4948.8  350.40  4949.0  350.90  4957.6  351.20  4978.6  351.46  4989.2  352.44
  4997.1  352.08  5002.5  352.08  5013.7  352.91  5022.1  353.89  5030.5  355.11
  5036.1  356.24  5044.4  357.23  5052.8  357.95  5066.8  360.09  5075.2  361.09
  5080.8  360.71  5089.2  361.20  5097.5  362.16  5103.1  362.43  5111.5  362.44
#Mann=3,-1,0
  4841.6    0.05       0  4945.0    0.04       0  4949.0    0.05       0
Bank Sta=4945,4949
Exp/Cntr=0.3,0.1

Type RM Length L Ch R = 1,10198,284,284,284
BEGIN DESCRIPTION:
Clear Creek T 40 20.0
END DESCRIPTION:
XS GIS Cut Line= 3
      2722675.97      6777111.03      2722576.00      6777211.00
      2722475.97      6777361.04
#Sta/Elev= 30
  4859.2  358.89  4862.7  358.89  4887.4  356.72  4901.6  356.13  4915.7  354.93
  4929.9  353.03  4944.0  351.85  4972.3  348.65  4995.0  347.98  4995.3  347.48
  4998.8  347.48  4999.0  347.98  5023.1  348.51  5029.1  349.48  5044.1  350.97
  5050.2  352.03  5059.2  352.48  5065.2  353.47  5080.2  354.72  5086.2  355.56
  5095.2  356.06  5101.2  356.85  5116.3  356.72  5122.3  357.34  5137.3  358.05
  5152.3  357.85  5158.3  358.32  5167.3  358.20  5173.3  358.58  5180.9  358.31
#Mann=3,-1,0
  4859.2    0.05       0  4995.0    0.04       0  4999.0    0.05       0
Bank Sta=4995,4999
Exp/Cntr=0.3,0.1

Type RM Length L Ch R = 1,9914,228,228,228
BEGIN DESCRIPTION:
Clear Creek T 40 19.0
END DESCRIPTION:
XS GIS Cut Line= 3
      2722625.99      6777011.00      2722476.00      6776961.00
      2722376.01      6777011.00
#Sta/Elev= 30
  4841.9  355.22  4852.4  354.50  4863.0  353.14  4884.1  352.32  4894.6  350.96
  4905.1  350.86  4915.7  349.84  4926.2  347.60  4936.8  346.39  4944.3  345.90
  4957.8  345.28  4968.4  346.00  4978.9  345.69  4989.5  346.10  4995.4  343.61
  4995.6  343.11  4999.1  343.11  4999.4  343.61  5002.8  343.61  5022.4  346.45
  5030.8  348.10  5036.3  348.31  5053.1  350.99  5058.7  350.97  5067.1  352.25
  5088.6  354.13  5097.8  355.10  5103.4  354.99  5109.0  355.90  5111.8  355.90
#Mann=5,-1,0
  4841.9    0.12       0  4944.3    0.05       0  4995.4    0.03       0
  4999.4    0.05       0  5088.6    0.12       0
Bank Sta=4995.4,4999.4
Exp/Cntr=0.3,0.1

Type RM Length L Ch R = 1,9686,202,202,202
BEGIN DESCRIPTION:
Clear Creek T 40 18.0
END DESCRIPTION:
XS GIS Cut Line= 3
      2722575.96      6776760.99      2722478.12      6776731.46
      2722225.97      6776811.01
#Sta/Elev= 30
  4895.6  352.40  4906.0  351.48  4912.0  350.37  4917.3  351.04  4945.0  345.61
  4950.2  345.84  4958.2  343.64  4968.7  342.01  4978.0  341.23  4983.2  341.37
  4987.6  340.44  4987.8  339.94  4991.3  339.94  4991.6  340.44  5001.5  340.79
  5021.0  342.48  5031.5  342.22  5041.4  343.30  5046.7  342.90  5052.5  344.64
  5094.4  347.40  5136.3  349.49  5167.8  351.61  5176.1  352.64  5199.3  353.78
  5208.4  355.06  5220.2  355.23  5246.0  357.30  5251.7  358.16  5262.2  358.45
#Mann=3,-1,0
  4895.6    0.05       0  4987.6    0.03       0  4991.6    0.05       0
Bank Sta=4987.6,4991.6
Exp/Cntr=0.3,0.1

Type RM Length L Ch R = 1,9484,344,344,344
BEGIN DESCRIPTION:
Clear Creek T 40 17.0
END DESCRIPTION:
XS GIS Cut Line= 3
      2722744.87      6776488.79      2722444.85      6776538.80
      2722244.02      6776648.72
#Sta/Elev= 30
  4704.1  357.58  4773.9  353.99  4814.5  351.11  4855.0  350.25  4864.8  348.49
  4869.9  349.00  4875.3  347.68  4905.7  346.96  4925.7  345.39  4930.7  345.96
  4936.1  343.44  4986.5  339.97  4995.0  338.76  4995.2  338.26  4998.7  338.26
  4999.0  338.76  5018.0  339.02  5023.7  339.88  5067.3  343.17  5105.2  345.22
  5110.9  346.00  5127.8  346.31  5132.7  346.84  5143.1  346.72  5150.4  347.13
  5164.9  346.92  5214.3  348.93  5230.4  348.26  5234.4  349.31  5237.2  349.31
#Mann=5,-1,0
  4704.1    0.05       0  4995.0    0.05       0  4999.0    0.05       0
  5127.8    0.12       0  5150.4    0.05       0
Bank Sta=4995,4999
Exp/Cntr=0.3,0.1

Type RM Length L Ch R = 1,9140,278,278,278
BEGIN DESCRIPTION:
Clear Creek T 40 16.0
END DESCRIPTION:
XS GIS Cut Line= 3
      2722675.96      6776360.98      2722476.00      6776261.00
      2722175.98      6776110.99
#Sta/Elev= 30
  4776.5  353.10  4812.8  351.33  4821.2  349.23  4843.5  348.48  4919.0  341.41
  4963.7  340.31  4969.3  337.58  4984.1  335.35  4984.3  334.85  4988.1  335.35
  4997.3  338.71  5014.0  339.57  5030.8  339.81  5036.4  338.66  5053.2  339.54
  5058.8  338.18  5075.5  338.75  5081.1  338.21  5098.8  340.32  5141.5  343.31
  5148.2  343.43  5165.0  346.28  5192.9  347.58  5215.3  349.64  5237.6  353.16
  5260.0  353.99  5299.1  357.64  5304.7  357.26  5328.7  359.27  5335.5  359.66
#Mann=6,-1,0
  4776.5    0.05       0  4984.1    0.03       0  4988.1    0.05       0
  5098.8    0.12       0  5141.5    0.05       0  5328.7    0.12       0
Bank Sta=4984.1,4988.1
Exp/Cntr=0.3,0.1

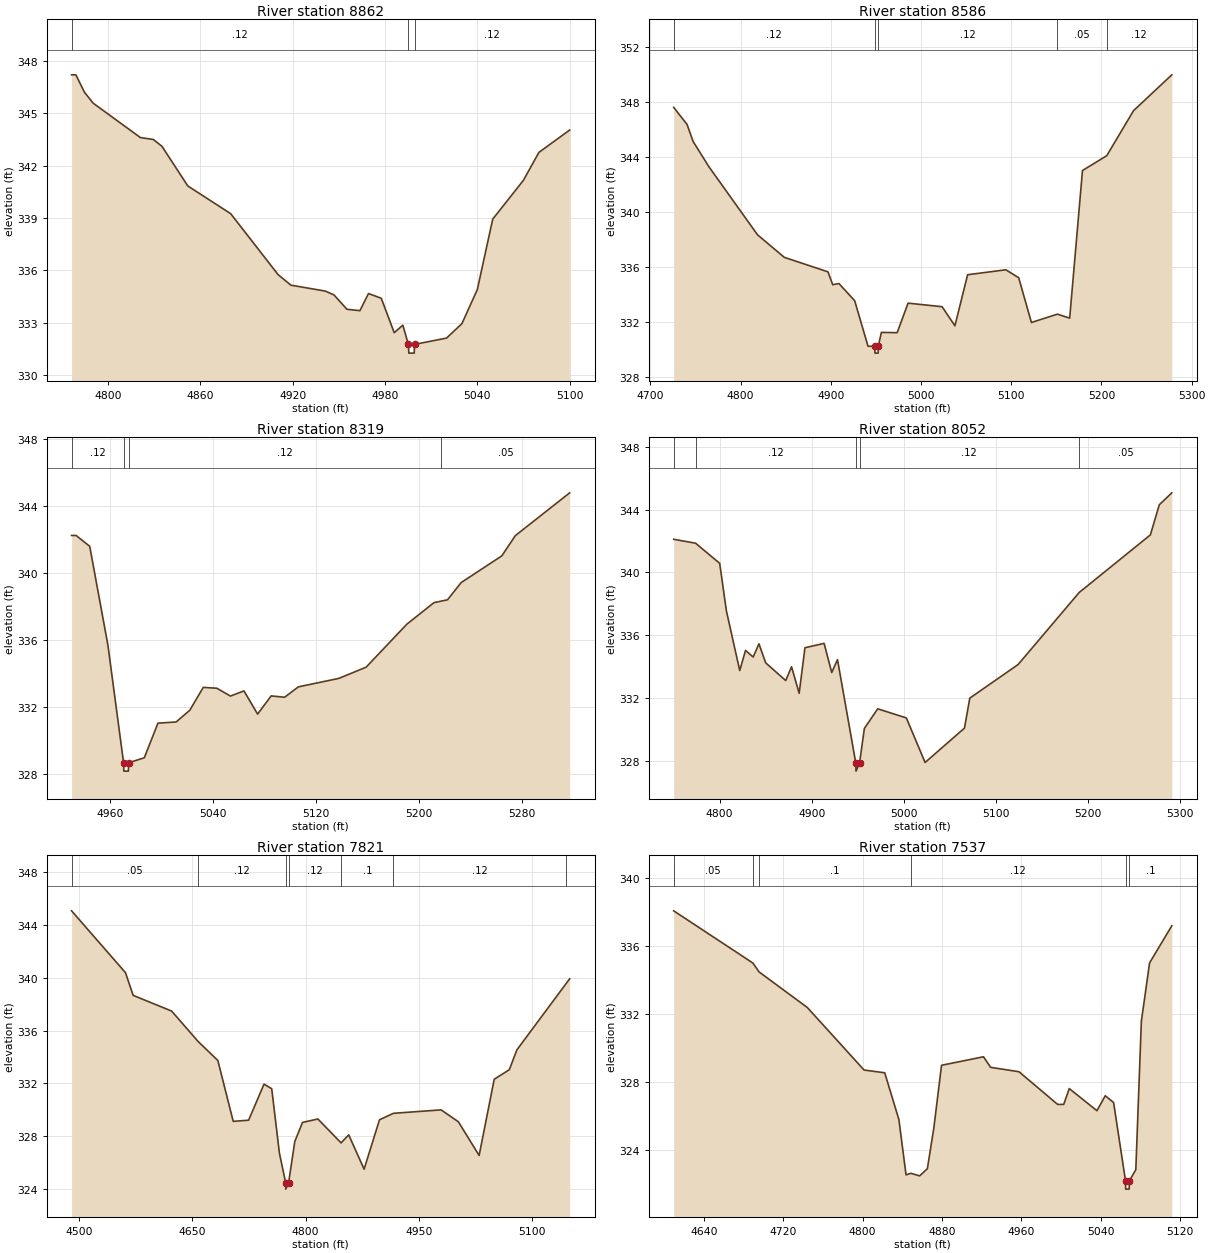
Type RM Length L Ch R = 1,8862,276,276,276
BEGIN DESCRIPTION:
Clear Creek T 40 15.0
END DESCRIPTION:
XS GIS Cut Line= 3
      2722675.99      6776111.00      2722476.00      6776011.00
      2722376.00      6776011.00
#Sta/Elev= 30
  4776.4  347.20  4779.2  347.20  4784.8  346.20  4790.4  345.58  4821.1  343.61
  4829.5  343.50  4835.1  343.11  4851.9  340.84  4879.8  339.25  4910.6  335.76
  4918.9  335.16  4941.3  334.82  4946.9  334.60  4955.3  333.78  4963.7  333.70
  4969.3  334.68  4977.6  334.41  4986.0  332.44  4991.6  332.87  4995.2  331.77
  4995.5  331.27  4999.0  331.27  4999.2  331.77  5020.0  332.13  5030.0  332.96
  5040.0  334.91  5050.0  338.94  5070.0  341.17  5080.0  342.76  5100.0  344.04
#Mann=3,-1,0
  4776.4    0.12       0  4995.2    0.07       0  4999.2    0.12       0
Bank Sta=4995.2,4999.2
Exp/Cntr=0.3,0.1

Type RM Length L Ch R = 1,8586,267,267,267
BEGIN DESCRIPTION:
Clear Creek T 40 14.0
END DESCRIPTION:
XS GIS Cut Line= 3
      2722775.99      6775910.99      2722526.00      6775811.00
      2722325.99      6775610.99
#Sta/Elev= 30
  4725.9  347.61  4740.7  346.37  4747.4  345.13  4764.9  343.29  4818.8  338.33
  4848.4  336.69  4896.9  335.63  4902.2  334.69  4909.0  334.78  4926.5  333.53
  4941.3  330.21  4948.7  330.21  4949.0  329.71  4952.5  329.71  4952.7  330.21
  4956.1  331.22  4973.6  331.20  4985.7  333.35  5023.4  333.09  5037.6  331.70
  5051.7  335.42  5094.1  335.78  5108.3  335.20  5122.4  331.94  5151.2  332.55
  5164.8  332.26  5179.0  343.01  5205.9  344.09  5235.6  347.37  5278.0  349.98
#Mann=5,-1,0
  4725.9    0.12       0  4948.7    0.07       0  4952.7    0.12       0
  5151.2    0.05       0  5205.9    0.12       0
Bank Sta=4948.7,4952.7
Exp/Cntr=0.3,0.1

Type RM Length L Ch R = 1,8319,267,267,267
BEGIN DESCRIPTION:
Clear Creek T 40 13.0
END DESCRIPTION:
XS GIS Cut Line= 3
      2722775.98      6775760.98      2722726.00      6775711.00
      2722426.00      6775611.00
#Sta/Elev= 30
  4930.0  342.25  4933.5  342.25  4944.1  341.60  4958.2  335.70  4970.4  328.65
  4970.6  328.15  4974.1  328.15  4974.4  328.65  4986.5  328.95  4997.1  331.02
  5011.2  331.09  5021.8  331.79  5032.3  333.16  5042.8  333.11  5053.4  332.64
  5063.9  332.95  5074.5  331.56  5085.0  332.65  5095.5  332.57  5106.1  333.19
  5137.7  333.70  5158.8  334.37  5190.4  336.94  5211.5  338.23  5217.1  338.32
  5222.0  338.40  5232.6  339.43  5264.2  341.03  5274.7  342.24  5316.9  344.80
#Mann=4,-1,0
  4930.0    0.12       0  4970.4    0.07       0  4974.4    0.12       0
  5217.1    0.05       0
Bank Sta=4970.4,4974.4
Exp/Cntr=0.3,0.1

Type RM Length L Ch R = 1,8052,231,231,231
BEGIN DESCRIPTION:
Clear Creek T 40 12.0
END DESCRIPTION:
XS GIS Cut Line= 3
      2722925.98      6775660.98      2722726.00      6775511.00
      2722476.02      6775361.01
#Sta/Elev= 30
  4750.0  342.11  4773.8  341.86  4800.0  340.58  4807.3  337.55  4821.8  333.75
  4828.1  335.03  4836.4  334.61  4842.7  335.45  4850.0  334.24  4871.8  333.11
  4878.1  333.99  4886.4  332.30  4892.7  335.20  4913.5  335.48  4921.8  333.62
  4928.1  334.44  4948.0  327.84  4948.2  327.34  4952.0  327.84  4957.3  330.06
  4971.8  331.31  5002.9  330.73  5023.3  327.89  5066.1  330.08  5071.9  331.99
  5124.4  334.13  5190.8  338.72  5268.2  342.39  5277.9  344.31  5291.5  345.07
#Mann=5,-1,0
  4750.0    0.05       0  4773.8    0.12       0  4948.0    0.07       0
  4952.0    0.12       0  5190.8    0.05       0
Bank Sta=4948,4952
Exp/Cntr=0.3,0.1

Type RM Length L Ch R = 1,7821,284,284,284
BEGIN DESCRIPTION:
Clear Creek T 40 11.0
END DESCRIPTION:
XS GIS Cut Line= 3
      2723226.05      6775411.01      2722726.00      6775311.00
      2722575.95      6775311.00
#Sta/Elev= 30
  4489.9  345.07  4561.3  340.39  4571.5  338.67  4622.5  337.48  4657.4  335.19
  4683.7  333.74  4704.1  329.13  4724.5  329.22  4744.9  331.95  4755.1  331.60
  4765.3  326.72  4773.5  324.50  4773.7  324.00  4777.5  324.50  4785.7  327.61
  4795.9  329.05  4816.3  329.31  4847.0  327.50  4857.1  328.11  4877.5  325.51
  4897.9  329.25  4916.4  329.74  4979.5  330.00  5002.4  329.10  5029.9  326.55
  5049.9  332.32  5069.9  333.04  5079.9  334.54  5145.0  339.55  5149.9  339.92
#Mann=7,-1,0
  4489.9    0.05       0  4657.4    0.12       0  4773.5    0.07       0
  4777.5    0.12       0  4847.0     0.1       0  4916.4    0.12       0
  5145.0    0.05       0
Bank Sta=4773.5,4777.5
Exp/Cntr=0.3,0.1

Type RM Length L Ch R = 1,7537,358,358,358
BEGIN DESCRIPTION:
Clear Creek T 40 10.0
END DESCRIPTION:
XS GIS Cut Line= 3
      2723125.99      6775310.99      2722826.00      6775061.00
      2722726.00      6775011.00
#Sta/Elev= 30
  4609.5  338.06  4689.4  334.99  4695.6  334.47  4744.2  332.38  4801.5  328.70
  4822.3  328.54  4836.6  325.79  4843.8  322.54  4848.7  322.63  4857.5  322.48
  4865.3  322.90  4871.8  325.28  4879.6  328.98  4921.9  329.48  4929.1  328.86
  4957.7  328.60  4996.7  326.68  5002.8  326.68  5008.4  327.61  5036.3  326.31
  5044.7  327.19  5053.1  326.79  5065.1  322.20  5065.3  321.70  5068.8  321.70
  5069.1  322.20  5075.5  322.84  5081.1  331.57  5089.4  335.00  5111.8  337.18
#Mann=6,-1,0
  4609.5    0.05       0  4689.4    0.12       0  4695.6     0.1       0
  4848.7    0.12       0  5065.1    0.07       0  5069.1     0.1       0
Bank Sta=5065.1,5069.1
Exp/Cntr=0.3,0.1

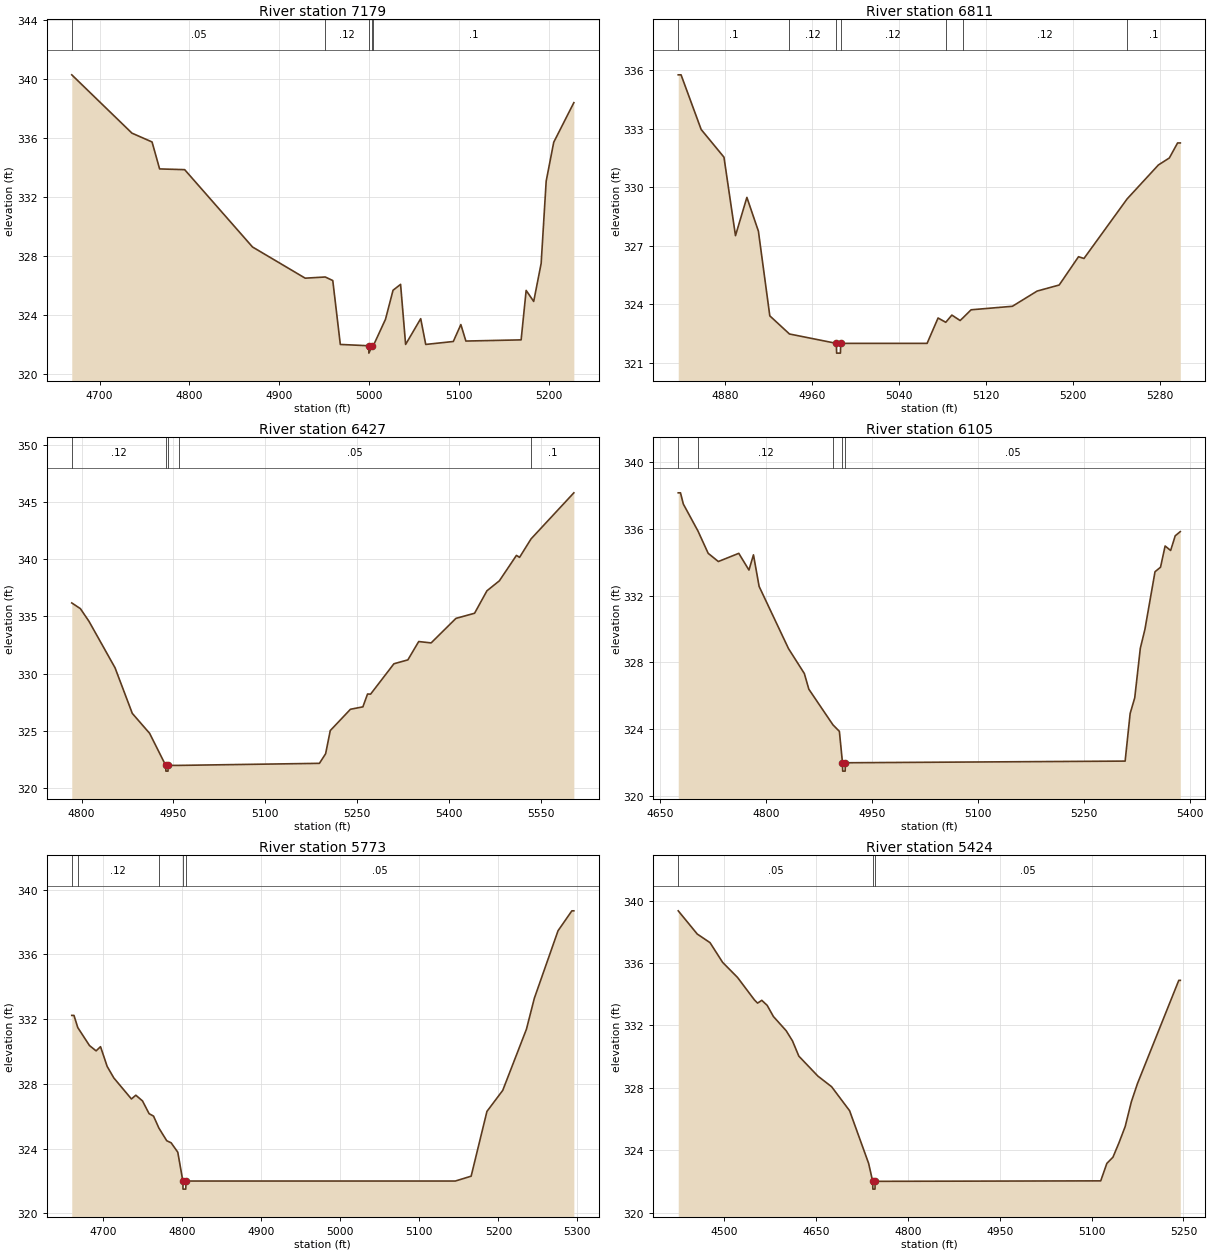
Type RM Length L Ch R = 1,7179,368,368,368
BEGIN DESCRIPTION:
Clear Creek T 40 9.0
END DESCRIPTION:
XS GIS Cut Line= 3
      2723325.96      6775010.98      2723026.00      6774861.00
      2722825.98      6774760.99
#Sta/Elev= 30
  4669.0  340.31  4736.0  336.35  4758.4  335.75  4766.8  333.92  4794.7  333.87
  4870.2  328.62  4928.9  326.50  4951.2  326.58  4959.6  326.34  4968.0  322.00
  4999.6  321.91  4999.8  321.41  5003.6  321.91  5004.7  321.91  5018.3  323.71
  5026.7  325.68  5035.1  326.08  5040.7  322.00  5057.5  323.75  5063.1  322.00
  5093.8  322.20  5102.2  323.35  5107.8  322.23  5169.3  322.31  5174.9  325.67
  5183.3  324.92  5191.6  327.50  5197.2  333.09  5205.6  335.73  5228.0  338.42
#Mann=5,-1,0
  4669.0    0.05       0  4951.2    0.12       0  4999.6    0.07       0
  5003.6    0.12       0  5004.7     0.1       0
Bank Sta=4999.6,5003.6
Exp/Cntr=0.3,0.1

Type RM Length L Ch R = 1,6811,384,384,384
BEGIN DESCRIPTION:
Clear Creek T 40 8.0
END DESCRIPTION:
XS GIS Cut Line= 3
      2723375.99      6774611.00      2723226.00      6774561.00
      2722926.04      6774610.99
#Sta/Elev= 30
  4836.8  335.76  4839.4  335.76  4857.9  332.96  4878.9  331.54  4889.5  327.52
  4900.0  329.48  4910.6  327.75  4921.1  323.41  4939.2  322.48  4982.4  322.00
  4982.6  321.50  4986.1  321.50  4986.4  322.00  5065.9  322.00  5076.0  323.30
  5083.1  323.08  5088.7  323.45  5096.3  323.17  5099.3  323.33  5106.4  323.72
  5144.4  323.90  5167.2  324.68  5187.5  324.99  5205.3  326.44  5210.3  326.35
  5250.0  329.40  5278.8  331.14  5288.9  331.50  5296.5  332.27  5299.0  332.27
#Mann=7,-1,0
  4836.8     0.1       0  4939.2    0.12       0  4982.4    0.07       0
  4986.4    0.12       0  5083.1     0.1       0  5099.3    0.12       0
  5250.0     0.1       0
Bank Sta=4982.4,4986.4
Exp/Cntr=0.3,0.1

Type RM Length L Ch R = 1,6427,322,322,322
BEGIN DESCRIPTION:
Clear Creek T 40 7.0
END DESCRIPTION:
XS GIS Cut Line= 3
      2723475.97      6774360.97      2723326.00      6774211.00
      2722725.96      6774110.99
#Sta/Elev= 30
  4783.9  336.18  4798.0  335.68  4812.1  334.57  4854.6  330.52  4882.8  326.54
  4911.1  324.80  4937.4  322.00  4937.7  321.50  4941.2  321.50  4941.4  322.00
  4958.6  322.00  5188.6  322.18  5198.7  323.02  5206.3  325.04  5239.3  326.90
  5259.6  327.11  5267.2  328.23  5272.2  328.22  5310.3  330.87  5333.1  331.21
  5350.8  332.81  5371.1  332.69  5411.6  334.83  5442.1  335.28  5462.3  337.24
  5482.6  338.11  5510.5  340.33  5515.6  340.16  5534.4  341.77  5604.3  345.79
#Mann=5,-1,0
  4783.9    0.12       0  4937.4    0.03       0  4941.4    0.12       0
  4958.6    0.05       0  5534.4     0.1       0
Bank Sta=4937.4,4941.4
Exp/Cntr=0.3,0.1

Type RM Length L Ch R = 1,6105,332,332,332
BEGIN DESCRIPTION:
Clear Creek T 40 6.0
END DESCRIPTION:
XS GIS Cut Line= 3
      2723626.01      6774211.01      2723426.00      6773961.00
      2723125.98      6773710.99
#Sta/Elev= 30
  4676.1  338.15  4679.3  338.15  4683.3  337.48  4704.1  335.86  4718.5  334.53
  4732.9  334.04  4761.8  334.53  4776.2  333.53  4782.6  334.44  4790.6  332.55
  4832.2  328.83  4854.6  327.34  4861.0  326.40  4895.1  324.27  4904.2  323.88
  4908.6  322.00  4908.9  321.50  4912.4  321.50  4912.6  322.00  5308.7  322.10
  5315.8  324.95  5322.3  325.89  5330.2  328.85  5336.7  329.98  5351.0  333.43
  5358.8  333.70  5365.3  334.97  5373.1  334.70  5379.6  335.58  5386.8  335.83
#Mann=5,-1,0
  4676.1     0.1       0  4704.1    0.12       0  4895.1    0.05       0
  4908.6    0.03       0  4912.6    0.05       0
Bank Sta=4908.6,4912.6
Exp/Cntr=0.3,0.1

Type RM Length L Ch R = 1,5773,349,349,349
BEGIN DESCRIPTION:
Clear Creek T 40 5.0
END DESCRIPTION:
XS GIS Cut Line= 3
      2723726.04      6773811.02      2723426.00      6773661.00
      2723125.96      6773661.00
#Sta/Elev= 30
  4660.0  332.23  4662.8  332.23  4667.6  331.48  4682.4  330.37  4690.8  330.04
  4696.4  330.30  4704.8  329.08  4713.2  328.37  4735.5  327.07  4741.1  327.30
  4749.5  326.95  4757.9  326.16  4763.5  326.01  4770.3  325.27  4780.2  324.49
  4785.8  324.36  4794.2  323.78  4800.6  322.00  4800.8  321.50  4804.3  321.50
  4804.6  322.00  5145.5  322.00  5165.5  322.30  5185.5  326.30  5205.5  327.60
  5235.5  331.38  5245.5  333.29  5275.5  337.46  5293.0  338.69  5295.5  338.69
#Mann=5,-1,0
  4660.0    0.05       0  4667.6    0.12       0  4770.3    0.05       0
  4800.6    0.03       0  4804.6    0.05       0
Bank Sta=4800.6,4804.6
Exp/Cntr=0.3,0.1

Type RM Length L Ch R = 1,5424,544,544,544
BEGIN DESCRIPTION:
Clear Creek T 40 4.0
END DESCRIPTION:
XS GIS Cut Line= 3
      2723926.04      6773210.99      2723376.00      6773361.00
      2723126.03      6773361.00
#Sta/Elev= 30
  4424.8  339.35  4455.9  337.86  4476.7  337.31  4497.4  336.04  4521.6  335.08
  4549.2  333.64  4554.4  333.43  4561.3  333.61  4570.0  333.29  4580.3  332.57
  4601.1  331.66  4611.4  331.01  4621.8  330.03  4652.9  328.75  4675.3  328.07
  4704.7  326.53  4735.8  323.15  4742.4  322.00  4742.7  321.50  4746.2  321.50
  4746.4  322.00  5114.9  322.03  5124.9  323.15  5134.9  323.55  5144.9  324.49
  5154.9  325.52  5164.9  327.10  5174.9  328.27  5242.4  334.89  5244.9  334.89
#Mann=3,-1,0
  4424.8    0.05       0  4742.4    0.03       0  4746.4    0.05       0
Bank Sta=4742.4,4746.4
Exp/Cntr=0.3,0.1

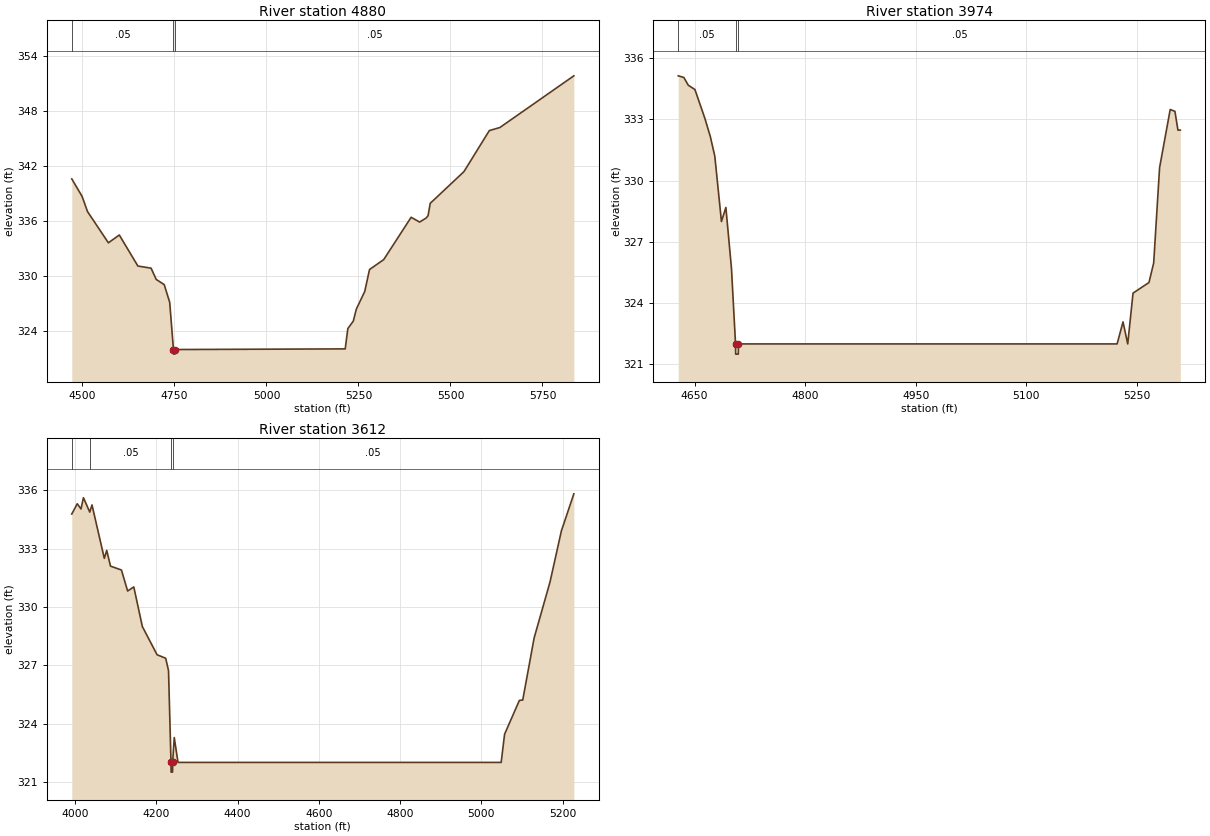
Type RM Length L Ch R = 1,4880,906,906,906
BEGIN DESCRIPTION:
Clear Creek T 40 3.0
END DESCRIPTION:
XS GIS Cut Line= 3
      2723804.11      6772610.12      2723370.50      6772913.15
      2722611.30      6773261.25
#Sta/Elev= 30
  4471.0  340.58  4499.0  338.68  4513.8  337.02  4570.5  333.62  4600.1  334.47
  4650.7  331.09  4686.5  330.86  4700.5  329.63  4722.2  329.07  4737.1  327.14
  4747.3  322.00  4747.5  321.50  4751.0  321.50  4751.3  322.00  5214.0  322.07
  5221.1  324.28  5236.0  325.10  5244.1  326.39  5267.1  328.33  5280.0  330.71
  5318.6  331.79  5393.1  336.40  5416.1  335.88  5433.6  336.31  5439.1  336.57
  5445.0  337.92  5536.6  341.37  5605.6  345.84  5634.1  346.17  5835.2  351.80
#Mann=3,-1,0
  4471.0    0.05       0  4747.3    0.05       0  4751.3    0.05       0
Bank Sta=4747.3,4751.3
Exp/Cntr=0.3,0.1

Type RM Length L Ch R = 1,3974,362,362,362
BEGIN DESCRIPTION:
Clear Creek T 40 2.0
END DESCRIPTION:
XS GIS Cut Line= 3
      2723426.03      6772260.98      2723126.00      6772461.00
      2722925.97      6772711.04
#Sta/Elev= 25
  4627.9  335.14  4635.5  335.06  4641.5  334.68  4650.5  334.47  4664.0  333.06
  4671.5  332.15  4677.5  331.20  4686.5  328.00  4692.5  328.69  4700.1  325.70
  4705.6  322.00  4705.8  321.50  4709.3  321.50  4709.6  322.00  5223.0  322.00
  5231.0  323.08  5237.4  322.00  5244.6  324.49  5266.2  325.01  5272.6  325.97
  5280.6  330.64  5295.0  333.49  5301.4  333.40  5305.5  332.48  5308.7  332.48
#Mann=3,-1,0
  4627.9    0.05       0  4705.6    0.03       0  4709.6    0.05       0
Bank Sta=4705.6,4709.6
Exp/Cntr=0.3,0.1

Type RM Length L Ch R = 1,3612,0,0,0
BEGIN DESCRIPTION:
Clear Creek T 40 1.0
END DESCRIPTION:
XS GIS Cut Line= 3
      2723675.99      6771911.01      2722826.00      6772461.00
      2722626.01      6772560.99
#Sta/Elev= 30
  3991.9  334.78  4005.4  335.31  4014.6  335.04  4020.6  335.62  4036.2  334.88
  4041.7  335.25  4072.0  332.50  4078.0  332.91  4087.2  332.10  4114.2  331.90
  4129.4  330.82  4144.6  331.03  4165.7  328.99  4201.9  327.54  4223.1  327.36
  4230.1  326.72  4236.2  322.00  4236.5  321.50  4240.0  321.50  4240.2  322.00
  4244.2  323.28  4253.4  322.00  5049.0  322.00  5057.4  323.45  5093.8  325.19
  5102.1  325.21  5130.1  328.40  5169.2  331.28  5197.2  333.91  5227.9  335.82
#Mann=4,-1,0
  3991.9    0.12       0  4036.2    0.05       0  4236.2    0.03       0
  4240.2    0.05       0
Bank Sta=4236.2,4240.2
Exp/Cntr=0.3,0.1

Chan Stop Cuts=-1