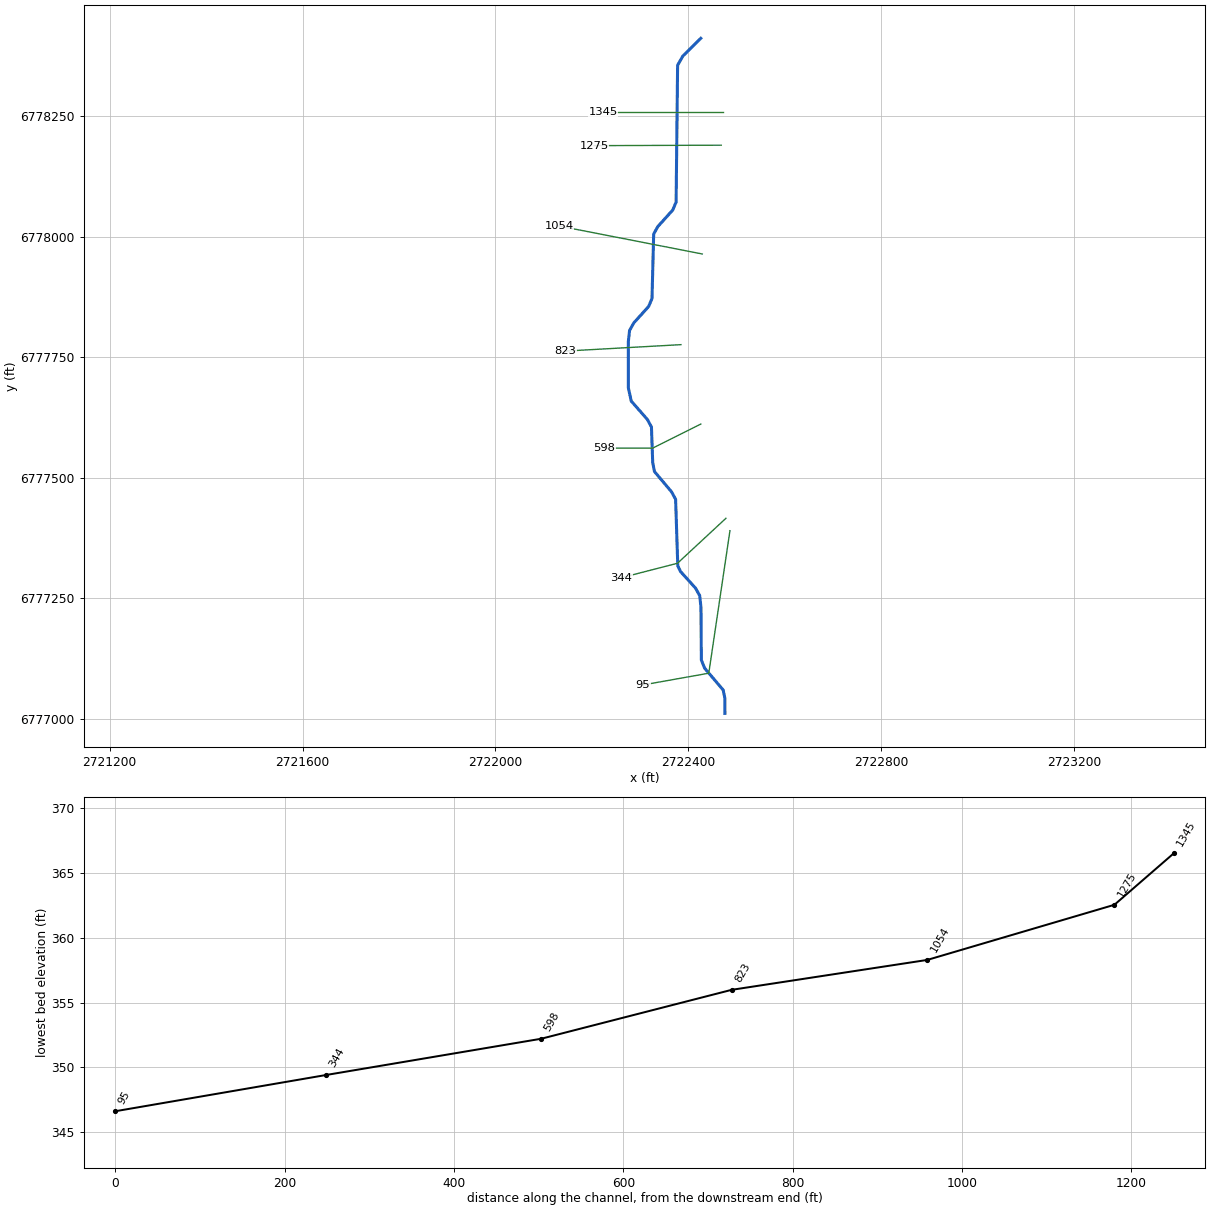
--- Clear Creek T 41.prj (project) ---

Proj Title=Clear Creek T 41 Base Level Engineering
Current Plan=p01
Default Exp/Contr=0.3,0.1
English Units
Geom File=g01
Flow File=f01
Plan File=p01
BEGIN DESCRIPTION:
Clear Creek T 41
END DESCRIPTION:

--- Clear Creek T 41.p01 (plan) ---

Plan Title=Multiple Run
Short Identifier=Multiple
Geom File=g01
Flow File=f01
Subcritical Flow
K Sum by GR= 0
Std Step Tol= 0.01
Critical Tol= 0.01
Num of Std Step Trials= 20
Max Error Tol= 0.3
Flow Tol Ratio= 0.001
Split Flow NTrial= 30
Split Flow Tol= 0.02
Split Flow Ratio= 0.02
Log Output Level= 0
Friction Slope Method= 1
Unsteady Friction Slope Method= 2
Unsteady Bridges Friction Slope Method= 1
Parabolic Critical Depth
Global Vel Dist=  1 , 1 , 1
Global Log Level= 0
CheckData=True
Encroach Param= -1, 0, 0, 0
BEGIN DESCRIPTION:
Multiple Run
END DESCRIPTION:

--- Clear Creek T 41.f01 (steady flow) ---

Flow Title=Multiple
Number of Profiles=7
Profile Names=10-year,25-year,50-year,1pct_min,100-year,1pct_plu,500-year
River Rch & RM= Clear Creek T 41,Reach-1,1345
      93     110     121      67     134     268     163
Boundary for River Rch & Prof#=Clear Creek T 41,Reach-1,1
Up Type=0
Dn Type=3
Dn Slope=0.005
Boundary for River Rch & Prof#=Clear Creek T 41,Reach-1,2
Up Type=0
Dn Type=3
Dn Slope=0.005
Boundary for River Rch & Prof#=Clear Creek T 41,Reach-1,3
Up Type=0
Dn Type=3
Dn Slope=0.005
Boundary for River Rch & Prof#=Clear Creek T 41,Reach-1,4
Up Type=0
Dn Type=3
Dn Slope=0.005
Boundary for River Rch & Prof#=Clear Creek T 41,Reach-1,5
Up Type=0
Dn Type=3
Dn Slope=0.005
Boundary for River Rch & Prof#=Clear Creek T 41,Reach-1,6
Up Type=0
Dn Type=3
Dn Slope=0.005
Boundary for River Rch & Prof#=Clear Creek T 41,Reach-1,7
Up Type=0
Dn Type=3
Dn Slope=0.005

--- Clear Creek T 41.g01 (geometry) ---

Geom Title=Existing Conditions

River Reach=Clear Creek T 41,Reach-1
Reach XY= 30
      2722426.00      6778411.00      2722388.92      6778374.51
      2722377.89      6778355.22      2722374.78      6778071.50
      2722367.86      6778054.94      2722336.86      6778020.64
      2722328.27      6778005.06      2722324.77      6777871.51
      2722317.85      6777854.95      2722286.85      6777820.65
      2722278.25      6777805.06      2722275.61      6777781.13
      2722275.77      6777685.93      2722281.74      6777658.67
      2722315.10      6777620.63      2722323.64      6777605.02
      2722326.24      6777531.10      2722329.86      6777512.60
      2722365.15      6777470.65      2722373.73      6777455.06
      2722378.27      6777316.94      2722384.15      6777304.95
      2722415.14      6777270.65      2722423.73      6777255.06
      2722426.33      6777231.13      2722427.13      6777121.47
      2722433.90      6777104.84      2722472.35      6777059.49
      2722475.88      6777042.80      2722476.00      6777011.00

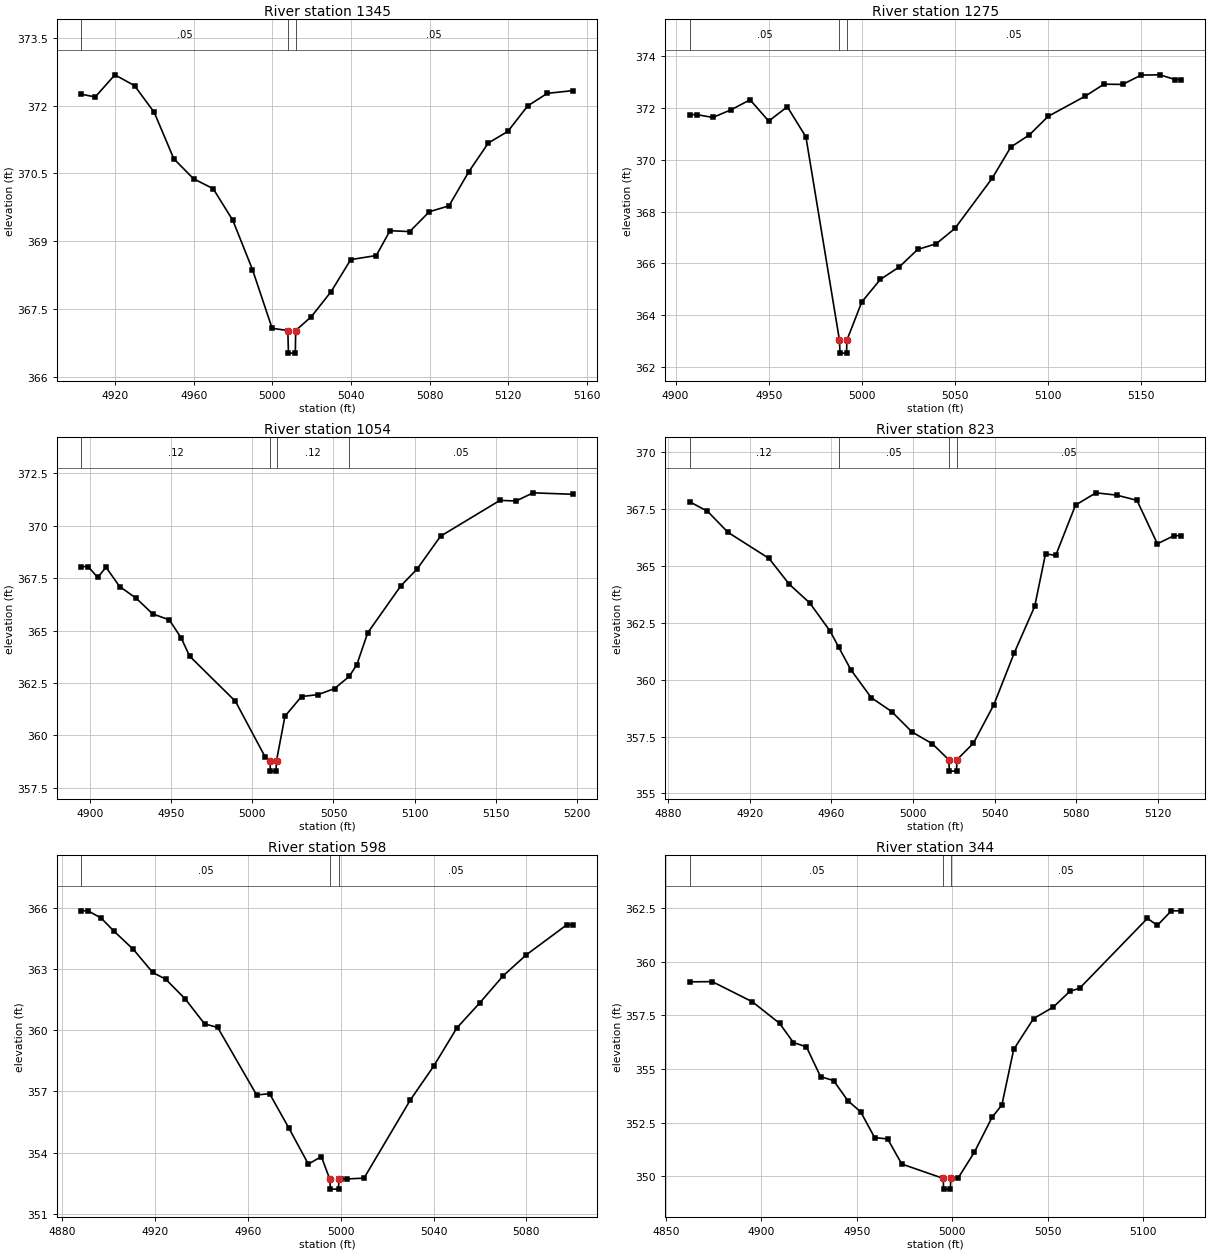
Type RM Length L Ch R = 1,1345,70,70,70
BEGIN DESCRIPTION:
Clear Creek T 41 3.0
END DESCRIPTION:
XS GIS Cut Line= 3
      2722473.03      6778258.89      2722323.01      6778258.89
      2722223.03      6778258.89
#Sta/Elev= 29
  4902.9  372.25  4909.9  372.19  4919.9  372.68  4929.9  372.44  4939.9  371.85
  4949.9  370.82  4959.9  370.38  4969.9  370.16  4979.9  369.46  4989.9  368.37
  4999.9  367.07  5007.9  367.02  5008.2  366.52  5011.7  366.52  5011.9  367.02
  5019.9  367.33  5029.9  367.88  5039.9  368.59  5052.9  368.68  5059.9  369.23
  5069.9  369.21  5079.9  369.65  5089.9  369.78  5099.9  370.53  5109.9  371.17
  5119.9  371.43  5129.9  371.99  5139.9  372.27  5152.9  372.33
#Mann=3,-1,0
  4902.9    0.05       0  5007.9    0.05       0  5011.9    0.05       0
Bank Sta=5007.9,5011.9
Exp/Cntr=0.3,0.1

Type RM Length L Ch R = 1,1275,221,221,221
BEGIN DESCRIPTION:
Mapping XS 83650674
END DESCRIPTION:
XS GIS Cut Line= 2
      2722468.54      6778189.38      2722204.74      6778188.45
#Sta/Elev= 29
  4907.5  371.73  4911.3  371.73  4920.0  371.62  4930.0  371.92  4940.0  372.30
  4950.0  371.48  4960.0  372.03  4970.0  370.87  4988.0  363.05  4988.3  362.55
  4991.8  362.55  4992.0  363.05  5000.0  364.52  5010.0  365.39  5020.0  365.86
  5030.0  366.54  5040.0  366.76  5050.0  367.35  5070.0  369.28  5080.0  370.48
  5090.0  370.95  5100.0  371.66  5120.0  372.44  5130.0  372.90  5140.0  372.89
  5150.0  373.25  5160.0  373.26  5168.2  373.08  5171.3  373.08
#Mann=3,-1,0
  4907.5    0.05       0  4988.0    0.05       0  4992.0    0.05       0
Bank Sta=4988,4992
Exp/Cntr=0.3,0.1

Type RM Length L Ch R = 1,1054,231,231,231
BEGIN DESCRIPTION:
Mapping XS 28d74c16
END DESCRIPTION:
XS GIS Cut Line= 2
      2722429.11      6777963.76      2722131.92      6778021.80
#Sta/Elev= 30
  4894.7  368.05  4898.8  368.05  4904.7  367.53  4909.8  368.02  4918.2  367.10
  4928.4  366.54  4938.6  365.79  4948.8  365.51  4956.2  364.64  4961.3  363.78
  4989.6  361.62  5007.8  358.98  5010.9  358.79  5011.1  358.29  5014.6  358.29
  5014.9  358.79  5020.1  360.91  5030.3  361.85  5040.5  361.94  5050.7  362.23
  5059.7  362.81  5064.4  363.37  5071.1  364.89  5091.5  367.13  5101.6  367.94
  5116.0  369.50  5152.6  371.21  5162.5  371.18  5173.0  371.57  5197.5  371.50
#Mann=4,-1,0
  4894.7    0.12       0  5010.9    0.07       0  5014.9    0.12       0
  5059.7    0.05       0
Bank Sta=5010.9,5014.9
Exp/Cntr=0.3,0.1

Type RM Length L Ch R = 1,823,225,225,225
BEGIN DESCRIPTION:
Mapping XS 404fdb54
END DESCRIPTION:
XS GIS Cut Line= 2
      2722384.84      6777775.71      2722144.51      6777762.33
#Sta/Elev= 30
  4890.5  367.82  4899.3  367.40  4909.4  366.47  4929.4  365.33  4939.4  364.19
  4949.4  363.37  4959.4  362.13  4963.5  361.44  4969.5  360.44  4979.5  359.21
  4989.5  358.60  4999.5  357.70  5009.5  357.18  5017.5  356.48  5017.8  355.98
  5021.3  355.98  5021.5  356.48  5029.6  357.21  5039.6  358.90  5049.6  361.18
  5059.6  363.22  5064.9  365.53  5069.9  365.46  5079.6  367.67  5089.6  368.21
  5099.7  368.11  5109.7  367.88  5119.7  365.97  5127.9  366.33  5131.2  366.33
#Mann=4,-1,0
  4890.5    0.12       0  4963.5    0.05       0  5017.5    0.04       0
  5021.5    0.05       0
Bank Sta=5017.5,5021.5
Exp/Cntr=0.3,0.1

Type RM Length L Ch R = 1,598,254,254,254
BEGIN DESCRIPTION:
Clear Creek T 41 2.0
END DESCRIPTION:
XS GIS Cut Line= 3
      2722426.00      6777611.00      2722326.00      6777561.00
      2722226.00      6777561.00
#Sta/Elev= 30
  4888.2  365.88  4891.0  365.88  4896.6  365.53  4902.2  364.88  4910.6  363.98
  4918.9  362.85  4924.5  362.52  4932.9  361.55  4941.3  360.32  4946.9  360.15
  4963.7  356.83  4969.3  356.89  4977.6  355.20  4986.0  353.43  4991.6  353.80
  4995.2  352.70  4995.5  352.20  4999.0  352.20  4999.2  352.70  5000.0  352.70
  5002.5  352.70  5010.0  352.74  5030.0  356.59  5040.0  358.24  5050.0  360.12
  5060.0  361.37  5070.0  362.69  5080.0  363.72  5097.5  365.20  5100.0  365.20
#Mann=3,-1,0
  4888.2    0.05       0  4995.2    0.04       0  4999.2    0.05       0
Bank Sta=4995.2,4999.2
Exp/Cntr=0.3,0.1

Type RM Length L Ch R = 1,344,249,249,249
BEGIN DESCRIPTION:
Mapping XS 13406856
END DESCRIPTION:
XS GIS Cut Line= 3
      2722478.11      6777415.59      2722377.60      6777322.33
      2722261.31      6777292.36
#Sta/Elev= 30
  4862.4  359.06  4874.3  359.07  4895.3  358.13  4909.5  357.13  4916.8  356.23
  4923.6  356.03  4931.0  354.64  4937.8  354.46  4945.2  353.53  4952.0  353.00
  4959.3  351.80  4966.1  351.74  4973.5  350.57  4995.2  349.90  4995.4  349.40
  4998.9  349.40  4999.2  349.90  5002.9  349.90  5011.5  351.12  5020.8  352.75
  5025.9  353.32  5032.1  355.91  5042.5  357.35  5052.8  357.88  5061.5  358.62
  5066.6  358.76  5102.1  362.02  5107.3  361.69  5114.6  362.37  5119.6  362.37
#Mann=3,-1,0
  4862.4    0.05       0  4995.2    0.04       0  4999.2    0.05       0
Bank Sta=4995.2,4999.2
Exp/Cntr=0.3,0.1

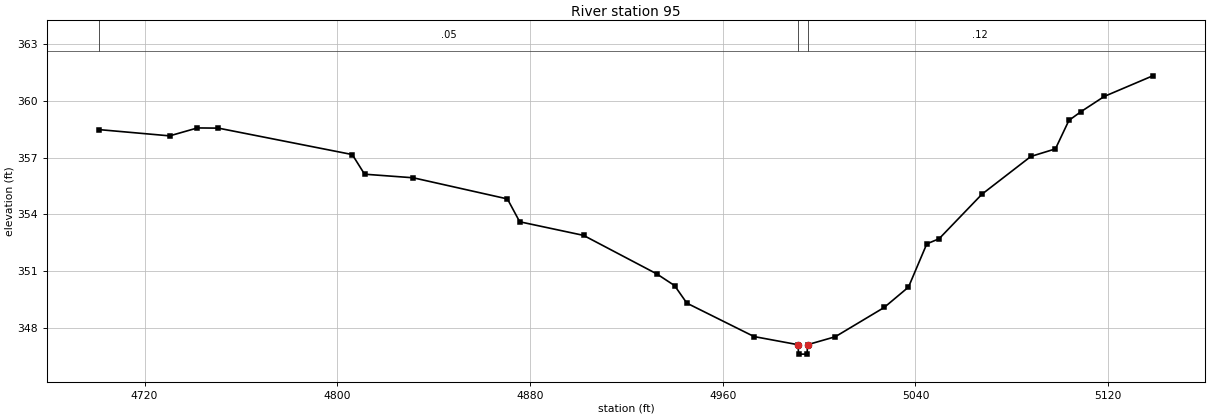
Type RM Length L Ch R = 1,95,0,0,0
BEGIN DESCRIPTION:
Clear Creek T 41 1.0
END DESCRIPTION:
XS GIS Cut Line= 3
      2722486.44      6777389.85      2722442.55      6777094.29
      2722306.20      6777070.00
#Sta/Elev= 30
  4701.2  358.49  4730.4  358.16  4741.9  358.58  4750.6  358.57  4806.2  357.17
  4811.3  356.13  4831.5  355.94  4870.6  354.82  4875.7  353.61  4902.2  352.89
  4932.6  350.85  4940.0  350.23  4945.1  349.30  4973.0  347.53  4991.2  347.10
  4991.5  346.60  4995.0  346.60  4995.2  347.10  5006.7  347.52  5027.0  349.07
  5037.1  350.15  5044.7  352.44  5049.8  352.71  5067.6  355.07  5087.9  357.07
  5098.1  357.47  5103.7  358.98  5108.8  359.45  5118.4  360.25  5138.5  361.34
#Mann=3,-1,0
  4701.2    0.05       0  4991.2    0.07       0  4995.2    0.12       0
Bank Sta=4991.2,4995.2
Exp/Cntr=0.3,0.1

Chan Stop Cuts=-1