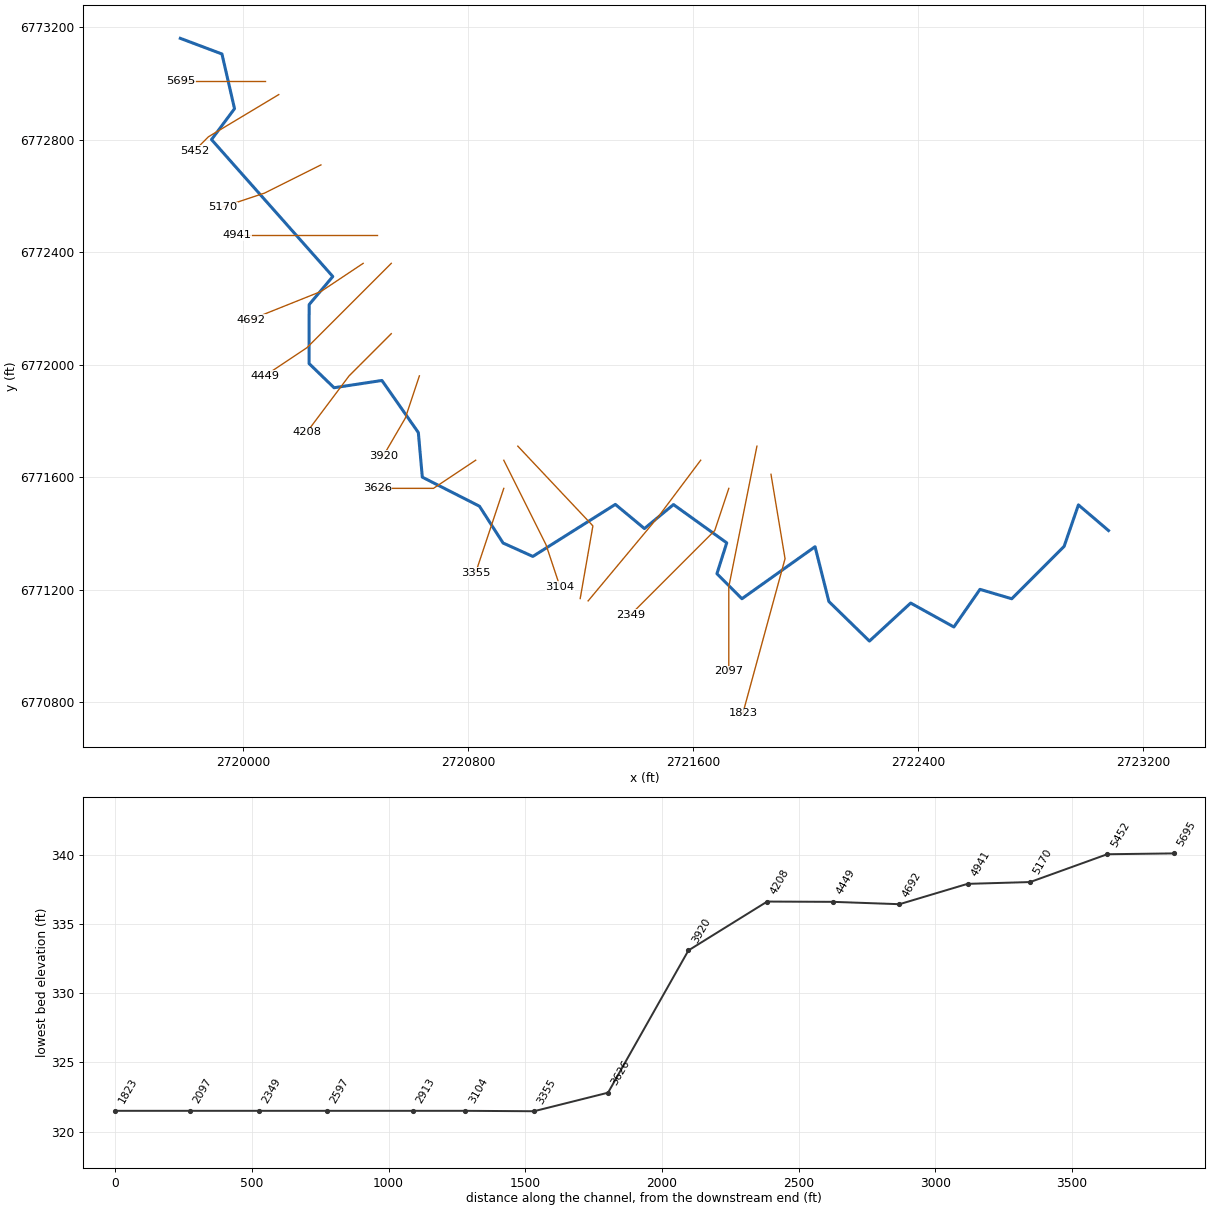
--- Clear Creek T 42.prj (project) ---

Proj Title=Clear Creek T 42 Base Level Engineering
Current Plan=p01
Default Exp/Contr=0.3,0.1
English Units
Geom File=g01
Flow File=f01
Plan File=p01
BEGIN DESCRIPTION:
Clear Creek T 42
END DESCRIPTION:

--- Clear Creek T 42.p01 (plan) ---

Plan Title=Multiple Run
Short Identifier=Multiple
Geom File=g01
Flow File=f01
Subcritical Flow
K Sum by GR= 0
Std Step Tol= 0.01
Critical Tol= 0.01
Num of Std Step Trials= 20
Max Error Tol= 0.3
Flow Tol Ratio= 0.001
Split Flow NTrial= 30
Split Flow Tol= 0.02
Split Flow Ratio= 0.02
Log Output Level= 0
Friction Slope Method= 1
Unsteady Friction Slope Method= 2
Unsteady Bridges Friction Slope Method= 1
Parabolic Critical Depth
Global Vel Dist=  1 , 1 , 1
Global Log Level= 0
CheckData=True
Encroach Param= -1, 0, 0, 0
BEGIN DESCRIPTION:
Multiple Run
END DESCRIPTION:

--- Clear Creek T 42.f01 (steady flow) ---

Flow Title=Multiple
Number of Profiles=7
Profile Names=10-year,25-year,50-year,1pct_min,100-year,1pct_plu,500-year
River Rch & RM= Clear Creek T 42,Reach-1,5695
     181     223     254     145     289     577     371
River Rch & RM= Clear Creek T 42,Reach-1,2597
     288     367     427     247     492     982     654
Boundary for River Rch & Prof#=Clear Creek T 42,Reach-1,1
Up Type=0
Dn Type=3
Dn Slope=0.005
Boundary for River Rch & Prof#=Clear Creek T 42,Reach-1,2
Up Type=0
Dn Type=3
Dn Slope=0.005
Boundary for River Rch & Prof#=Clear Creek T 42,Reach-1,3
Up Type=0
Dn Type=3
Dn Slope=0.005
Boundary for River Rch & Prof#=Clear Creek T 42,Reach-1,4
Up Type=0
Dn Type=3
Dn Slope=0.005
Boundary for River Rch & Prof#=Clear Creek T 42,Reach-1,5
Up Type=0
Dn Type=3
Dn Slope=0.005
Boundary for River Rch & Prof#=Clear Creek T 42,Reach-1,6
Up Type=0
Dn Type=3
Dn Slope=0.005
Boundary for River Rch & Prof#=Clear Creek T 42,Reach-1,7
Up Type=0
Dn Type=3
Dn Slope=0.005

--- Clear Creek T 42.g01 (geometry) ---

Geom Title=Existing Conditions

River Reach=Clear Creek T 42,Reach-1
Reach XY= 30
      2719776.00      6773161.00      2719924.03      6773105.35
      2719968.66      6772910.90      2719886.96      6772801.00
      2720318.15      6772314.23      2720234.02      6772214.34
      2720233.76      6772004.79      2720322.57      6771918.79
      2720492.79      6771944.61      2720622.24      6771759.44
      2720636.35      6771600.88      2720839.56      6771497.52
      2720923.46      6771366.70      2721029.29      6771319.05
      2721322.67      6771504.03      2721426.00      6771418.11
      2721529.33      6771503.38      2721718.62      6771367.33
      2721683.82      6771257.56      2721772.64      6771168.59
      2722032.67      6771353.54      2722081.81      6771158.71
      2722226.00      6771018.07      2722372.59      6771153.23
      2722526.30      6771068.20      2722618.99      6771201.96
      2722732.05      6771168.50      2722918.14      6771354.83
      2722969.00      6771502.24      2723076.00      6771411.00

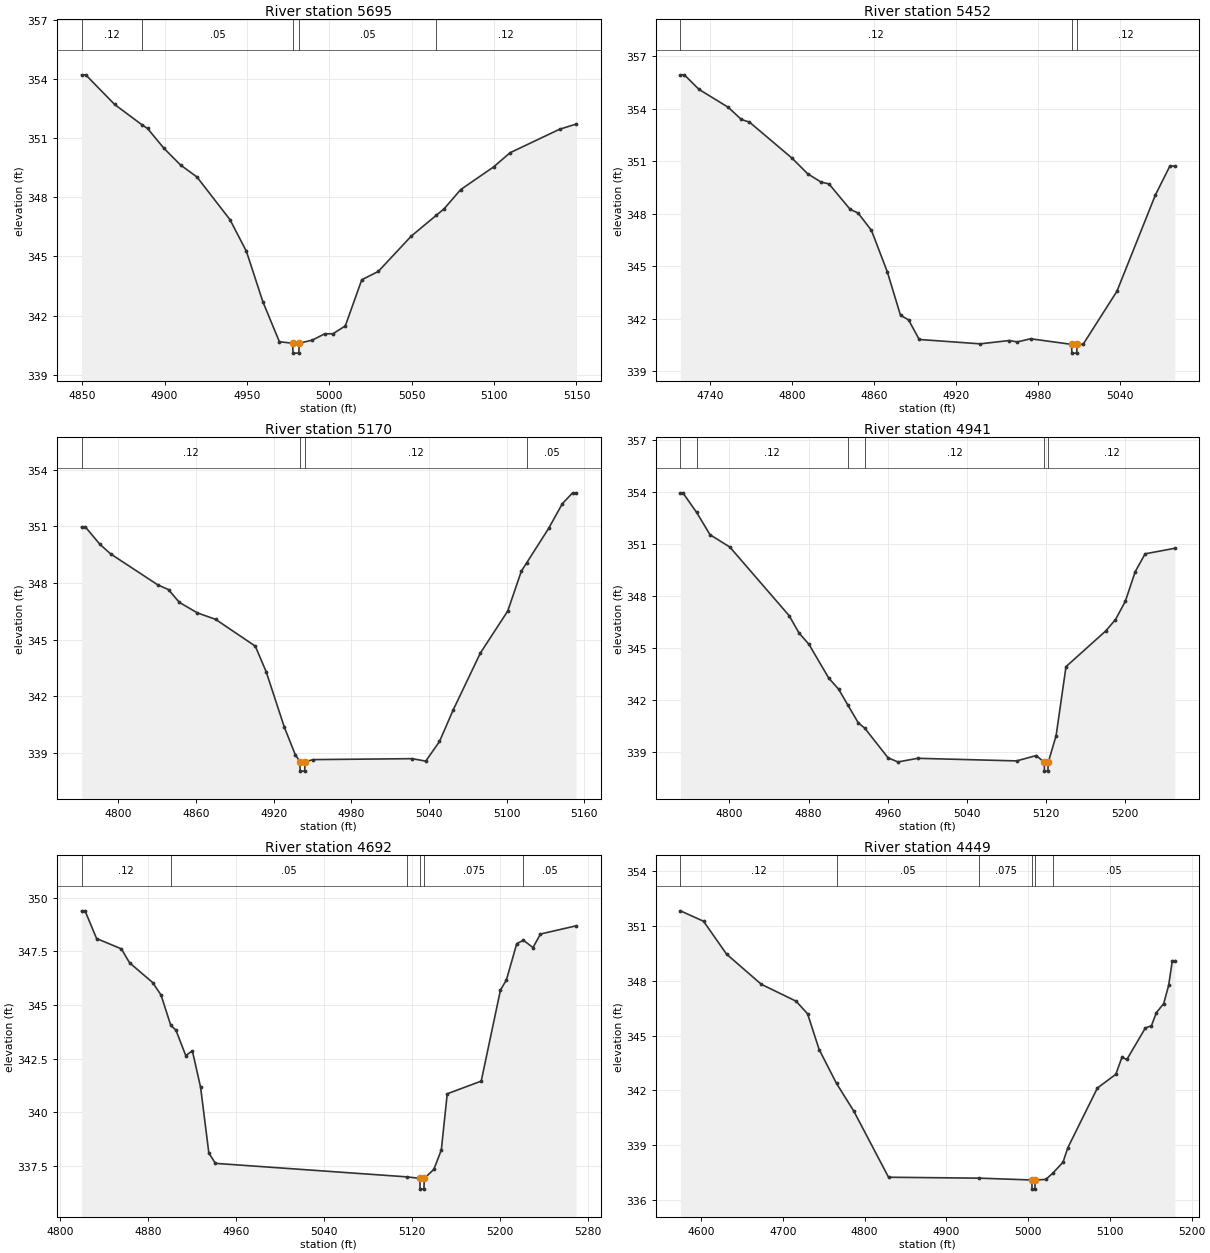
Type RM Length L Ch R = 1,5695,243,243,243
BEGIN DESCRIPTION:
Clear Creek T 42 18.0
END DESCRIPTION:
XS GIS Cut Line= 3
      2720076.04      6773011.00      2719926.00      6773011.00
      2719776.04      6773011.00
#Sta/Elev= 30
  4849.7  354.21  4852.2  354.21  4869.7  352.71  4886.4  351.67  4889.7  351.49
  4899.7  350.48  4909.7  349.64  4919.7  349.03  4939.7  346.87  4949.7  345.26
  4959.7  342.70  4969.7  340.68  4977.7  340.60  4978.0  340.10  4981.5  340.10
  4981.7  340.60  4989.7  340.76  4997.2  341.08  5002.2  341.08  5009.7  341.48
  5019.7  343.82  5029.7  344.24  5049.7  346.03  5064.8  347.08  5069.7  347.42
  5079.7  348.39  5099.7  349.54  5109.7  350.26  5139.7  351.45  5149.7  351.71
#Mann=5,-1,0
  4849.7    0.12       0  4886.4    0.05       0  4977.7    0.03       0
  4981.7    0.05       0  5064.8    0.12       0
Bank Sta=4977.7,4981.7
Exp/Cntr=0.3,0.1

Type RM Length L Ch R = 1,5452,282,282,282
BEGIN DESCRIPTION:
Clear Creek T 42 17.0
END DESCRIPTION:
XS GIS Cut Line= 3
      2720126.02      6772961.01      2719876.00      6772811.00
      2719825.99      6772760.99
#Sta/Elev= 30
  4718.1  355.93  4721.0  355.93  4731.7  355.10  4753.1  354.08  4762.8  353.38
  4768.7  353.23  4799.8  351.18  4811.4  350.28  4821.1  349.81  4827.0  349.70
  4842.5  348.25  4848.3  348.04  4858.1  347.05  4869.7  344.69  4879.4  342.20
  4885.3  341.94  4893.1  340.82  4937.8  340.57  4959.1  340.76  4965.0  340.68
  4974.7  340.86  5004.8  340.54  5005.0  340.04  5008.5  340.04  5008.8  340.54
  5013.2  340.54  5038.0  343.57  5066.2  349.07  5076.8  350.72  5080.4  350.72
#Mann=3,-1,0
  4718.1    0.12       0  5004.8    0.07       0  5008.8    0.12       0
Bank Sta=5004.8,5008.8
Exp/Cntr=0.3,0.1

Type RM Length L Ch R = 1,5170,229,229,229
BEGIN DESCRIPTION:
Clear Creek T 42 16.0
END DESCRIPTION:
XS GIS Cut Line= 3
      2720275.98      6772710.99      2720076.00      6772611.00
      2719925.99      6772561.00
#Sta/Elev= 30
  4771.8  350.97  4774.6  350.97  4785.7  350.06  4794.1  349.54  4830.5  347.90
  4838.9  347.64  4847.2  346.97  4861.2  346.41  4875.2  346.07  4905.9  344.65
  4914.3  343.29  4928.3  340.36  4936.7  338.91  4940.3  338.53  4940.5  338.03
  4944.0  338.03  4944.3  338.53  4950.7  338.64  5027.0  338.69  5037.5  338.56
  5048.1  339.60  5058.6  341.26  5079.7  344.29  5100.8  346.51  5111.3  348.62
  5115.4  349.06  5132.4  350.89  5143.0  352.20  5150.9  352.77  5153.5  352.77
#Mann=4,-1,0
  4771.8    0.12       0  4940.3    0.07       0  4944.3    0.12       0
  5115.4    0.05       0
Bank Sta=4940.3,4944.3
Exp/Cntr=0.3,0.1

Type RM Length L Ch R = 1,4941,249,249,249
BEGIN DESCRIPTION:
Clear Creek T 42 15.0
END DESCRIPTION:
XS GIS Cut Line= 3
      2720475.97      6772461.00      2720226.00      6772461.00
      2719975.97      6772461.00
#Sta/Elev= 30
  4750.4  353.96  4752.9  353.96  4766.8  352.83  4780.4  351.54  4800.4  350.83
  4860.4  346.87  4870.4  345.87  4880.4  345.22  4900.4  343.27  4910.4  342.63
  4920.0  341.69  4930.4  340.68  4936.7  340.39  4960.4  338.67  4970.4  338.43
  4990.4  338.64  5090.4  338.49  5110.4  338.80  5118.4  338.40  5118.6  337.90
  5122.1  337.90  5122.4  338.40  5130.4  339.95  5140.4  343.93  5180.4  345.98
  5190.4  346.64  5200.4  347.70  5210.4  349.41  5220.4  350.44  5250.4  350.76
#Mann=6,-1,0
  4750.4    0.05       0  4766.8    0.12       0  4920.0    0.05       0
  4936.7    0.12       0  5118.4    0.07       0  5122.4    0.12       0
Bank Sta=5118.4,5122.4
Exp/Cntr=0.3,0.1

Type RM Length L Ch R = 1,4692,243,243,243
BEGIN DESCRIPTION:
Clear Creek T 42 14.0
END DESCRIPTION:
XS GIS Cut Line= 3
      2720426.04      6772361.03      2720276.00      6772261.00
      2720025.98      6772160.99
#Sta/Elev= 30
  4819.7  349.39  4822.8  349.39  4833.3  348.10  4855.8  347.62  4863.3  346.97
  4884.3  346.05  4891.9  345.47  4900.8  344.05  4905.4  343.84  4914.4  342.65
  4920.4  342.87  4927.9  341.17  4935.4  338.11  4941.4  337.63  5115.8  337.00
  5127.3  336.93  5127.5  336.43  5131.0  336.43  5131.3  336.93  5140.0  337.35
  5146.8  338.25  5152.2  340.87  5183.1  341.46  5200.6  345.70  5206.0  346.17
  5215.4  347.86  5221.4  348.02  5230.2  347.68  5237.0  348.31  5269.3  348.69
#Mann=6,-1,0
  4819.7    0.12       0  4900.8    0.05       0  5115.8   0.075       0
  5127.3    0.03       0  5131.3   0.075       0  5221.4    0.05       0
Bank Sta=5127.3,5131.3
Exp/Cntr=0.3,0.1

Type RM Length L Ch R = 1,4449,241,241,241
BEGIN DESCRIPTION:
Clear Creek T 42 13.0
END DESCRIPTION:
XS GIS Cut Line= 3
      2720525.98      6772360.98      2720226.00      6772061.00
      2720076.01      6771961.01
#Sta/Elev= 30
  4574.8  351.82  4603.1  351.25  4631.3  349.45  4673.8  347.80  4716.2  346.88
  4730.3  346.19  4744.5  344.23  4765.7  342.38  4786.9  340.86  4829.3  337.25
  4940.5  337.20  5004.5  337.10  5004.8  336.60  5008.3  336.60  5008.5  337.10
  5021.6  337.13  5030.3  337.48  5042.6  338.07  5048.6  338.87  5084.7  342.13
  5107.2  342.88  5114.7  343.81  5120.7  343.69  5143.3  345.41  5150.8  345.54
  5156.8  346.25  5165.8  346.75  5171.8  347.74  5176.3  349.09  5179.3  349.09
#Mann=6,-1,0
  4574.8    0.12       0  4765.7    0.05       0  4940.5   0.075       0
  5004.5    0.07       0  5008.5   0.075       0  5030.3    0.05       0
Bank Sta=5004.5,5008.5
Exp/Cntr=0.3,0.1

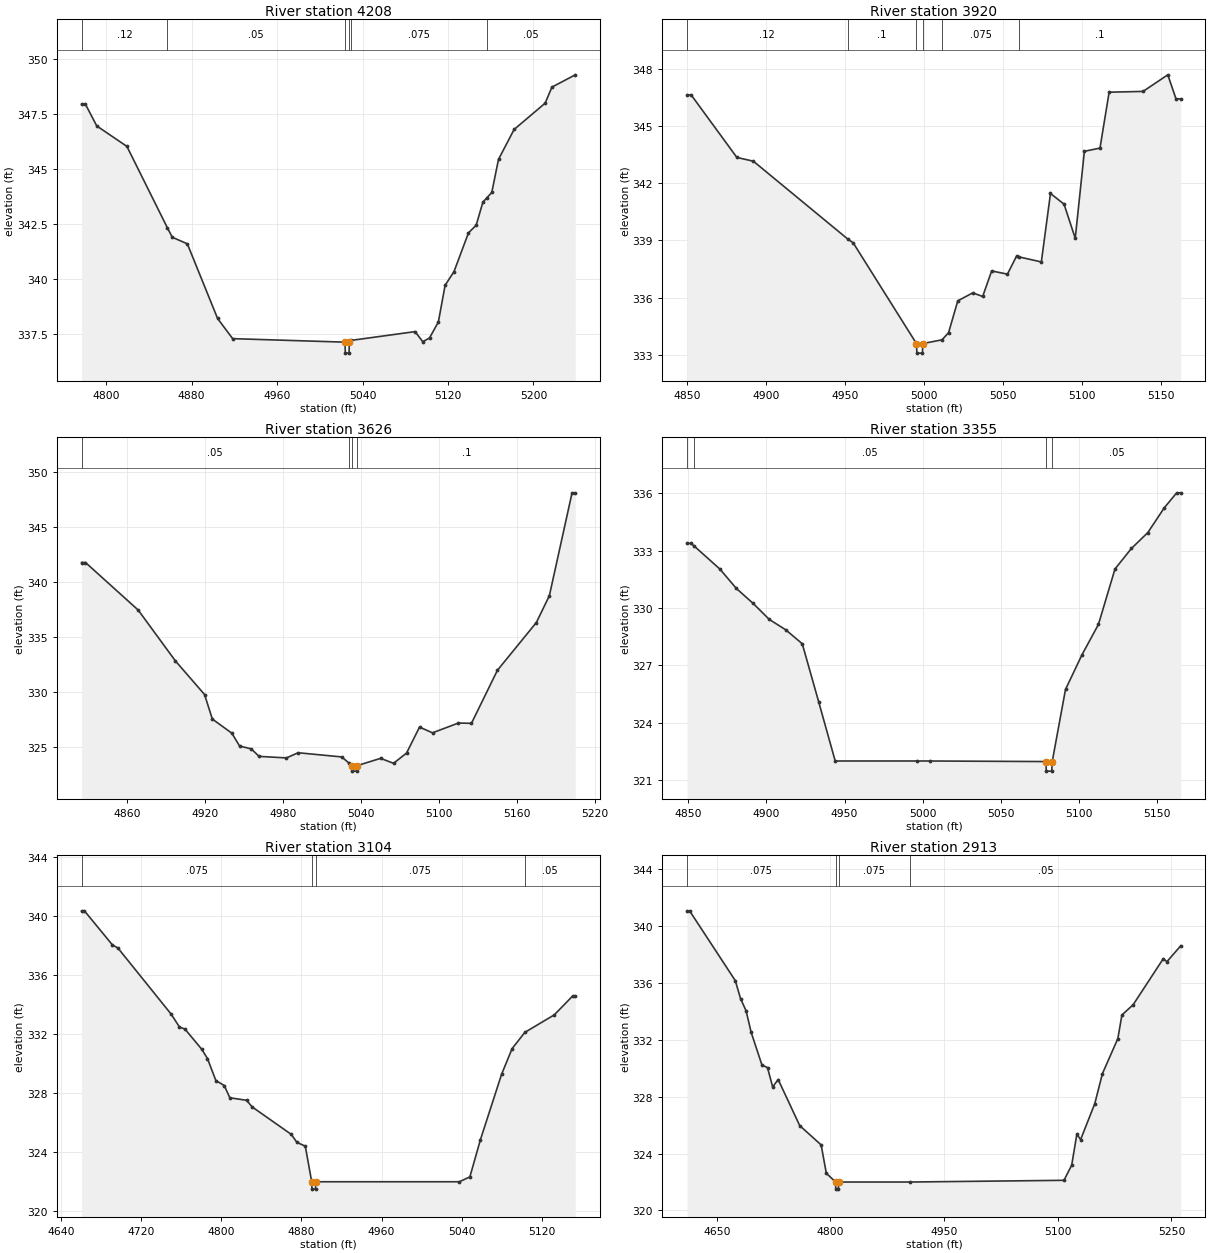
Type RM Length L Ch R = 1,4208,288,288,288
BEGIN DESCRIPTION:
Clear Creek T 42 12.0
END DESCRIPTION:
XS GIS Cut Line= 3
      2720526.01      6772111.01      2720376.00      6771961.00
      2720225.97      6771760.96
#Sta/Elev= 30
  4777.0  347.96  4780.6  347.96  4791.2  346.97  4819.4  346.04  4857.2  342.34
  4861.9  341.90  4876.0  341.60  4904.3  338.20  4918.4  337.28  5023.6  337.12
  5023.9  336.62  5027.4  336.62  5027.6  337.12  5029.3  337.20  5089.2  337.60
  5096.4  337.14  5102.7  337.31  5111.0  338.04  5117.3  339.71  5125.6  340.33
  5139.2  342.10  5146.4  342.45  5152.7  343.50  5156.3  343.69  5161.0  343.94
  5167.3  345.45  5181.9  346.81  5211.0  348.01  5217.3  348.74  5239.2  349.30
#Mann=6,-1,0
  4777.0    0.12       0  4857.2    0.05       0  5023.6    0.03       0
  5027.6    0.05       0  5029.3   0.075       0  5156.3    0.05       0
Bank Sta=5023.6,5027.6
Exp/Cntr=0.3,0.1

Type RM Length L Ch R = 1,3920,294,294,294
BEGIN DESCRIPTION:
Clear Creek T 42 11.0
END DESCRIPTION:
XS GIS Cut Line= 3
      2720625.99      6771960.97      2720576.00      6771811.00
      2720498.00      6771677.04
#Sta/Elev= 30
  4849.7  346.63  4852.3  346.63  4881.3  343.35  4891.8  343.15  4951.5  339.08
  4955.1  338.87  4995.2  333.59  4995.5  333.09  4999.0  333.09  4999.2  333.59
  5011.5  333.79  5015.6  334.17  5021.4  335.83  5030.9  336.25  5037.2  336.06
  5042.9  337.40  5052.9  337.23  5058.7  338.18  5060.5  338.13  5074.4  337.87
  5080.2  341.46  5088.8  340.90  5095.9  339.11  5101.7  343.67  5111.6  343.84
  5117.4  346.77  5138.9  346.81  5154.6  347.68  5159.8  346.42  5162.8  346.42
#Mann=6,-1,0
  4849.7    0.12       0  4951.5     0.1       0  4995.2    0.07       0
  4999.2     0.1       0  5011.5   0.075       0  5060.5     0.1       0
Bank Sta=4995.2,4999.2
Exp/Cntr=0.3,0.1

Type RM Length L Ch R = 1,3626,271,271,271
BEGIN DESCRIPTION:
Clear Creek T 42 10.0
END DESCRIPTION:
XS GIS Cut Line= 3
      2720826.03      6771661.02      2720676.00      6771561.00
      2720476.02      6771561.00
#Sta/Elev= 30
  4824.9  341.76  4827.9  341.76  4868.5  337.44  4897.1  332.83  4919.6  329.77
  4925.6  327.54  4940.6  326.26  4946.6  325.09  4955.6  324.83  4961.6  324.15
  4982.7  324.01  4991.7  324.48  5025.2  324.10  5030.5  323.58  5033.2  323.31
  5033.5  322.81  5037.0  322.81  5037.2  323.31  5055.2  323.97  5065.2  323.52
  5075.2  324.45  5085.2  326.81  5095.2  326.29  5115.2  327.18  5125.2  327.15
  5145.2  331.97  5175.2  336.31  5185.2  338.74  5202.7  348.09  5205.2  348.09
#Mann=4,-1,0
  4824.9    0.05       0  5030.5     0.1       0  5033.2    0.03       0
  5037.2     0.1       0
Bank Sta=5033.2,5037.2
Exp/Cntr=0.3,0.1

Type RM Length L Ch R = 1,3355,251,251,251
BEGIN DESCRIPTION:
Clear Creek T 42 9.0
END DESCRIPTION:
XS GIS Cut Line= 3
      2720926.00      6771560.99      2720876.00      6771411.00
      2720826.01      6771261.02
#Sta/Elev= 26
  4849.1  333.38  4851.7  333.38  4853.5  333.25  4870.2  332.03  4880.7  331.02
  4891.3  330.25  4901.8  329.40  4912.3  328.86  4922.9  328.13  4933.4  325.10
  4944.0  322.00  4996.7  322.00  5004.6  322.00  5079.0  321.97  5079.2  321.47
  5082.7  321.47  5083.0  321.97  5091.5  325.74  5102.1  327.56  5112.6  329.14
  5123.2  332.04  5133.7  333.11  5144.2  333.94  5154.8  335.24  5162.7  336.02
  5165.3  336.02
#Mann=4,-1,0
  4849.1   0.075       0  4853.5    0.05       0  5079.0    0.05       0
  5083.0    0.05       0
Bank Sta=5079,5083
Exp/Cntr=0.3,0.1

Type RM Length L Ch R = 1,3104,191,191,191
BEGIN DESCRIPTION:
Clear Creek T 42 8.0
END DESCRIPTION:
XS GIS Cut Line= 3
      2720925.99      6771661.01      2721076.00      6771361.00
      2721125.99      6771211.04
#Sta/Elev= 30
  4660.2  340.36  4663.0  340.36  4691.0  338.05  4696.5  337.84  4749.7  333.36
  4758.0  332.49  4763.6  332.34  4780.4  330.97  4786.0  330.35  4794.4  328.86
  4802.8  328.52  4808.4  327.69  4825.1  327.52  4830.7  327.07  4869.8  325.21
  4875.4  324.67  4883.8  324.41  4890.2  322.00  4890.5  321.50  4894.0  321.50
  4894.2  322.00  5037.8  322.00  5048.3  322.33  5058.9  324.86  5080.0  329.28
  5090.5  331.02  5103.2  332.12  5132.7  333.31  5151.1  334.59  5153.7  334.59
#Mann=4,-1,0
  4660.2   0.075       0  4890.2    0.07       0  4894.2   0.075       0
  5103.2    0.05       0
Bank Sta=4890.2,4894.2
Exp/Cntr=0.3,0.1

Type RM Length L Ch R = 1,2913,316,316,316
BEGIN DESCRIPTION:
Clear Creek T 42 7.0
END DESCRIPTION:
XS GIS Cut Line= 3
      2720976.02      6771710.97      2721242.84      6771427.63
      2721197.68      6771169.24
#Sta/Elev= 30
  4610.8  341.08  4614.2  341.08  4674.5  336.17  4681.4  334.91  4688.7  334.05
  4695.5  332.52  4709.7  330.23  4717.0  330.05  4723.8  328.69  4731.1  329.21
  4759.5  325.97  4787.8  324.61  4794.6  322.62  4806.8  322.00  4807.1  321.50
  4810.6  321.50  4810.8  322.00  4905.1  322.00  5108.2  322.12  5118.4  323.18
  5125.2  325.36  5130.2  324.99  5148.8  327.50  5159.0  329.63  5179.3  332.09
  5184.7  333.75  5199.6  334.48  5239.1  337.70  5244.2  337.51  5262.3  338.62
#Mann=4,-1,0
  4610.8   0.075       0  4806.8    0.03       0  4810.8   0.075       0
  4905.1    0.05       0
Bank Sta=4806.8,4810.8
Exp/Cntr=0.3,0.1

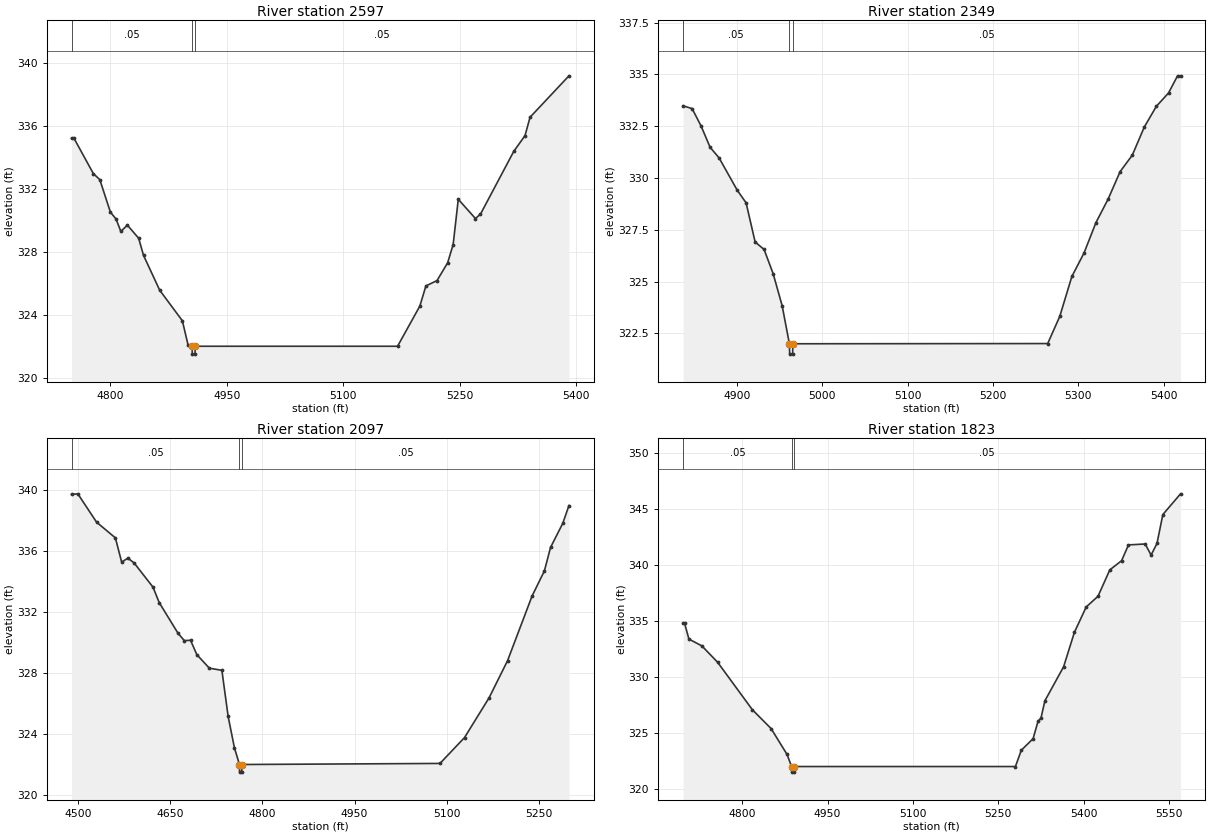
Type RM Length L Ch R = 1,2597,248,248,248
BEGIN DESCRIPTION:
Clear Creek T 42 6.0
END DESCRIPTION:
XS GIS Cut Line= 3
      2721625.99      6771660.98      2721476.00      6771461.00
      2721225.99      6771160.99
#Sta/Elev= 30
  4750.1  335.21  4753.2  335.21  4778.2  332.96  4786.5  332.58  4800.1  330.52
  4807.4  330.08  4813.6  329.29  4822.0  329.69  4836.5  328.86  4842.8  327.77
  4863.6  325.56  4892.8  323.62  4900.1  322.09  4905.4  322.00  4905.6  321.50
  4909.1  321.50  4909.4  322.00  5169.9  322.00  5198.6  324.55  5206.4  325.83
  5220.7  326.17  5234.4  327.30  5241.5  328.46  5248.1  331.33  5270.2  330.11
  5276.7  330.39  5319.6  334.38  5334.0  335.37  5340.5  336.54  5390.6  339.17
#Mann=3,-1,0
  4750.1    0.05       0  4905.4    0.03       0  4909.4    0.05       0
Bank Sta=4905.4,4909.4
Exp/Cntr=0.3,0.1

Type RM Length L Ch R = 1,2349,252,252,252
BEGIN DESCRIPTION:
Clear Creek T 42 5.0
END DESCRIPTION:
XS GIS Cut Line= 3
      2721725.99      6771560.96      2721676.00      6771411.00
      2721376.02      6771111.02
#Sta/Elev= 28
  4837.3  333.48  4847.8  333.35  4858.3  332.51  4868.9  331.48  4879.4  330.97
  4900.5  329.42  4911.0  328.80  4921.6  326.91  4932.1  326.55  4942.7  325.38
  4953.2  323.84  4961.7  322.00  4962.0  321.50  4965.5  321.50  4965.7  322.00
  5264.1  322.01  5278.2  323.32  5292.4  325.25  5306.5  326.37  5320.6  327.85
  5334.8  328.98  5348.9  330.31  5363.1  331.10  5377.2  332.46  5391.3  333.46
  5405.5  334.10  5416.1  334.93  5419.6  334.93
#Mann=3,-1,0
  4837.3    0.05       0  4961.7    0.03       0  4965.7    0.05       0
Bank Sta=4961.7,4965.7
Exp/Cntr=0.3,0.1

Type RM Length L Ch R = 1,2097,274,274,274
BEGIN DESCRIPTION:
Clear Creek T 42 4.0
END DESCRIPTION:
XS GIS Cut Line= 3
      2721826.00      6771711.02      2721726.00      6771211.00
      2721726.00      6770911.02
#Sta/Elev= 30
  4489.1  339.72  4499.3  339.76  4529.9  337.90  4560.5  336.87  4570.7  335.28
  4580.9  335.54  4591.1  335.22  4621.7  333.64  4631.9  332.62  4662.5  330.61
  4672.7  330.13  4682.9  330.15  4693.1  329.21  4713.5  328.32  4733.9  328.18
  4744.1  325.15  4754.3  323.10  4762.5  322.00  4762.7  321.50  4766.2  321.50
  4766.5  322.00  5089.0  322.07  5129.0  323.77  5169.0  326.38  5199.0  328.81
  5239.0  333.06  5259.0  334.70  5269.0  336.24  5289.0  337.83  5299.0  338.99
#Mann=3,-1,0
  4489.1    0.05       0  4762.5    0.03       0  4766.5    0.05       0
Bank Sta=4762.5,4766.5
Exp/Cntr=0.3,0.1

Type RM Length L Ch R = 1,1823,0,0,0
BEGIN DESCRIPTION:
Clear Creek T 42 3.0
END DESCRIPTION:
XS GIS Cut Line= 3
      2721876.00      6771611.02      2721926.00      6771311.00
      2721776.01      6770761.04
#Sta/Elev= 30
  4696.2  334.78  4698.8  334.78  4706.4  333.38  4729.2  332.77  4757.0  331.30
  4817.9  327.07  4850.8  325.39  4878.7  323.09  4886.8  322.00  4887.1  321.50
  4890.6  321.50  4890.8  322.00  5280.2  322.00  5290.6  323.46  5311.3  324.49
  5319.9  326.04  5325.1  326.32  5332.0  327.87  5364.9  330.91  5383.9  333.99
  5404.6  336.25  5425.3  337.20  5446.1  339.56  5466.8  340.38  5478.9  341.79
  5508.3  341.87  5518.6  340.88  5529.0  341.92  5539.3  344.50  5570.4  346.35
#Mann=3,-1,0
  4696.2    0.05       0  4886.8    0.03       0  4890.8    0.05       0
Bank Sta=4886.8,4890.8
Exp/Cntr=0.3,0.1

Chan Stop Cuts=-1