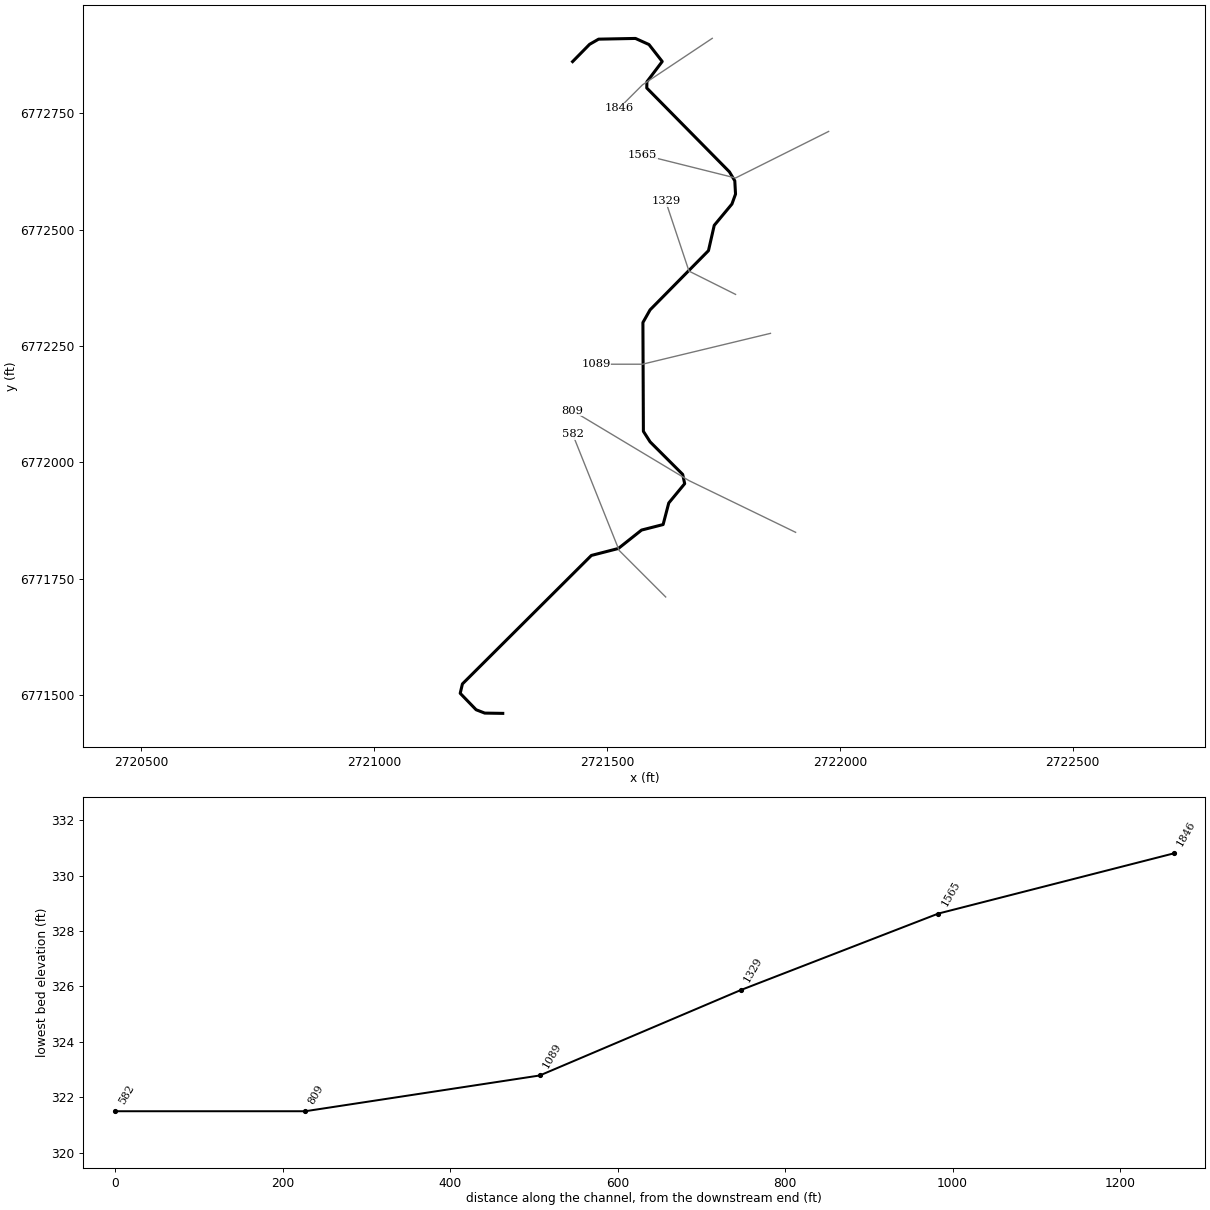
--- Clear Creek T 43.prj (project) ---

Proj Title=Clear Creek T 43 Base Level Engineering
Current Plan=p01
Default Exp/Contr=0.3,0.1
English Units
Geom File=g01
Flow File=f01
Plan File=p01
BEGIN DESCRIPTION:
Clear Creek T 43
END DESCRIPTION:

--- Clear Creek T 43.p01 (plan) ---

Plan Title=Multiple Run
Short Identifier=Multiple
Geom File=g01
Flow File=f01
Subcritical Flow
K Sum by GR= 0
Std Step Tol= 0.01
Critical Tol= 0.01
Num of Std Step Trials= 20
Max Error Tol= 0.3
Flow Tol Ratio= 0.001
Split Flow NTrial= 30
Split Flow Tol= 0.02
Split Flow Ratio= 0.02
Log Output Level= 0
Friction Slope Method= 1
Unsteady Friction Slope Method= 2
Unsteady Bridges Friction Slope Method= 1
Parabolic Critical Depth
Global Vel Dist=  1 , 1 , 1
Global Log Level= 0
CheckData=True
Encroach Param= -1, 0, 0, 0
BEGIN DESCRIPTION:
Multiple Run
END DESCRIPTION:

--- Clear Creek T 43.f01 (steady flow) ---

Flow Title=Multiple
Number of Profiles=7
Profile Names=10-year,25-year,50-year,1pct_min,100-year,1pct_plu,500-year
River Rch & RM= Clear Creek T 43,Reach-1,1846
     172     212     243     139     277     552     357
Boundary for River Rch & Prof#=Clear Creek T 43,Reach-1,1
Up Type=0
Dn Type=3
Dn Slope=0.005
Boundary for River Rch & Prof#=Clear Creek T 43,Reach-1,2
Up Type=0
Dn Type=3
Dn Slope=0.005
Boundary for River Rch & Prof#=Clear Creek T 43,Reach-1,3
Up Type=0
Dn Type=3
Dn Slope=0.005
Boundary for River Rch & Prof#=Clear Creek T 43,Reach-1,4
Up Type=0
Dn Type=3
Dn Slope=0.005
Boundary for River Rch & Prof#=Clear Creek T 43,Reach-1,5
Up Type=0
Dn Type=3
Dn Slope=0.005
Boundary for River Rch & Prof#=Clear Creek T 43,Reach-1,6
Up Type=0
Dn Type=3
Dn Slope=0.005
Boundary for River Rch & Prof#=Clear Creek T 43,Reach-1,7
Up Type=0
Dn Type=3
Dn Slope=0.005

--- Clear Creek T 43.g01 (geometry) ---

Geom Title=Existing Conditions

River Reach=Clear Creek T 43,Reach-1
Reach XY= 30
      2721426.00      6772861.00      2721462.52      6772898.13
      2721481.85      6772909.23      2721561.08      6772910.77
      2721590.10      6772897.66      2721618.54      6772861.25
      2721585.62      6772817.69      2721585.31      6772804.34
      2721762.88      6772624.21      2721774.39      6772604.96
      2721775.99      6772576.41      2721768.26      6772555.07
      2721730.25      6772509.26      2721717.86      6772454.94
      2721592.43      6772327.76      2721577.05      6772300.57
      2721578.07      6772066.85      2721592.50      6772044.24
      2721662.46      6771974.35      2721666.77      6771954.40
      2721632.57      6771912.95      2721620.45      6771866.59
      2721574.15      6771854.76      2721524.29      6771815.18
      2721466.32      6771800.23      2721189.34      6771524.25
      2721184.59      6771504.12      2721218.81      6771468.76
      2721237.34      6771461.59      2721276.00      6771461.00

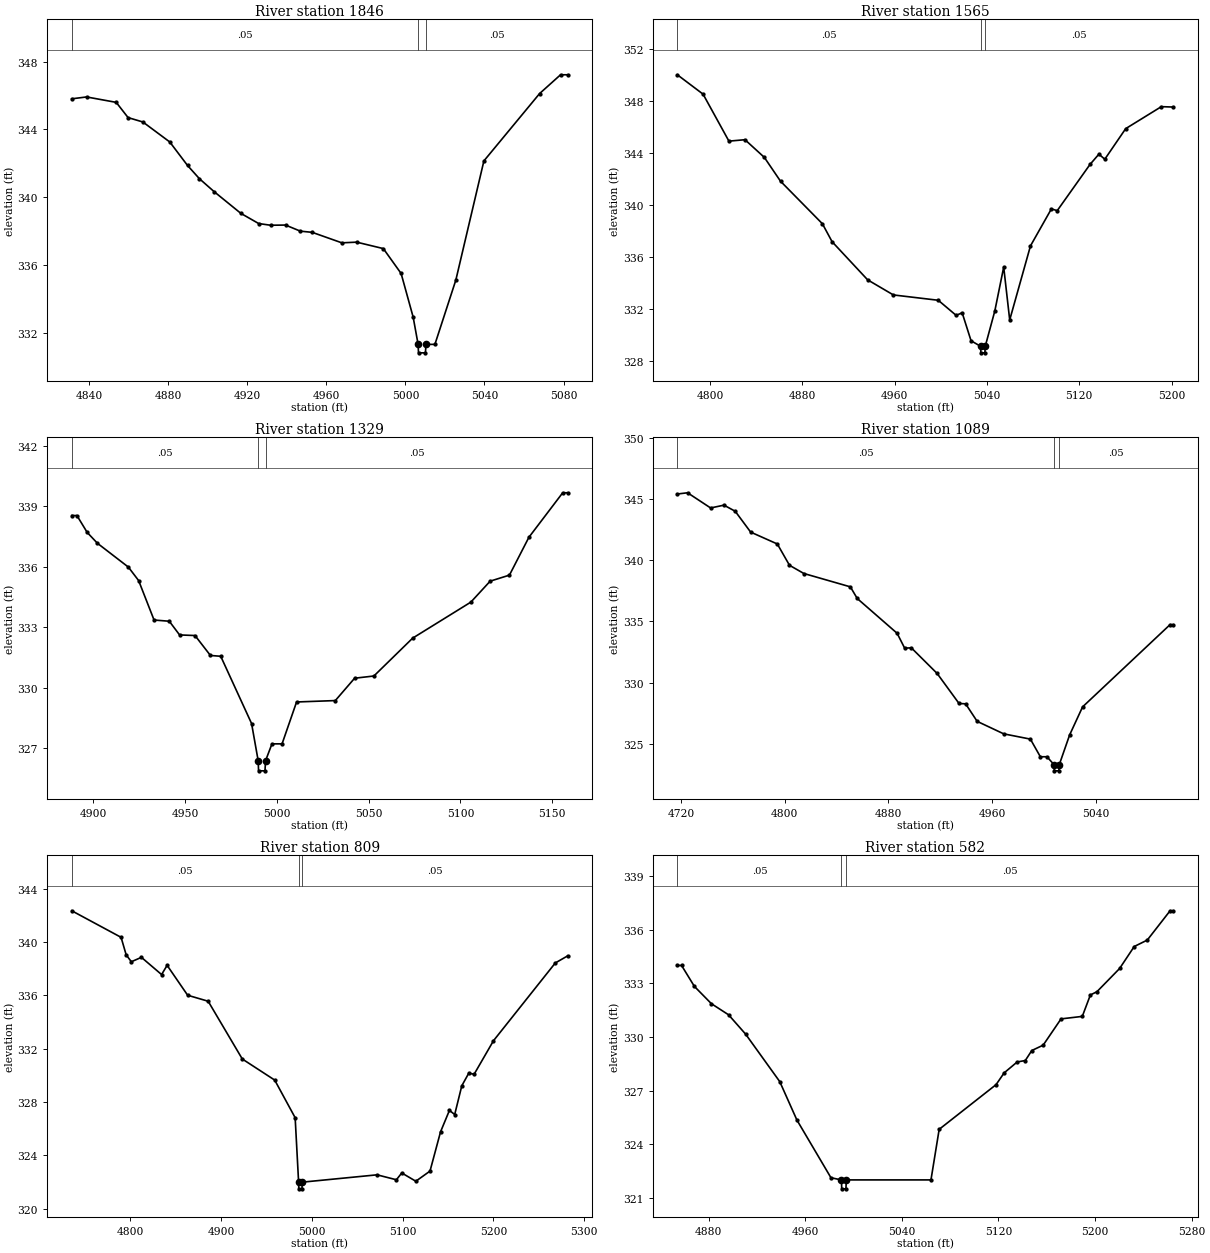
Type RM Length L Ch R = 1,1846,281,281,281
BEGIN DESCRIPTION:
Clear Creek T 43 6.0
END DESCRIPTION:
XS GIS Cut Line= 3
      2721725.99      6772910.99      2721576.00      6772811.00
      2721525.98      6772760.98
#Sta/Elev= 30
  4831.1  345.81  4838.6  345.92  4853.6  345.60  4859.6  344.70  4867.1  344.44
  4880.7  343.26  4889.7  341.87  4895.7  341.09  4903.2  340.32  4916.7  339.04
  4925.7  338.44  4931.7  338.34  4939.3  338.35  4946.8  337.99  4952.8  337.92
  4967.8  337.30  4975.3  337.34  4988.8  336.96  4997.8  335.49  5003.9  332.91
  5006.4  331.30  5006.6  330.80  5010.1  330.80  5010.4  331.30  5014.9  331.30
  5025.5  335.10  5039.7  342.14  5067.9  346.12  5078.5  347.23  5082.1  347.23
#Mann=3,-1,0
  4831.1    0.05       0  5006.4    0.03       0  5010.4    0.05       0
Bank Sta=5006.4,5010.4
Exp/Cntr=0.3,0.1

Type RM Length L Ch R = 1,1565,236,236,236
BEGIN DESCRIPTION:
Clear Creek T 43 5.0
END DESCRIPTION:
XS GIS Cut Line= 3
      2721975.96      6772710.98      2721776.00      6772611.00
      2721576.01      6772661.00
#Sta/Elev= 30
  4771.8  350.00  4794.1  348.51  4816.5  344.90  4830.4  345.01  4847.2  343.65
  4861.2  341.82  4897.5  338.55  4905.9  337.17  4936.7  334.24  4959.0  333.08
  4997.9  332.67  5013.4  331.51  5018.6  331.71  5026.3  329.56  5034.6  329.13
  5034.8  328.63  5038.3  328.63  5038.6  329.13  5046.9  331.85  5054.6  335.22
  5059.8  331.16  5077.8  336.85  5095.9  339.69  5101.0  339.56  5129.4  343.11
  5137.1  343.90  5142.2  343.51  5160.3  345.86  5191.2  347.55  5201.5  347.52
#Mann=3,-1,0
  4771.8    0.05       0  5034.6    0.03       0  5038.6    0.05       0
Bank Sta=5034.6,5038.6
Exp/Cntr=0.3,0.1

Type RM Length L Ch R = 1,1329,240,240,240
BEGIN DESCRIPTION:
Clear Creek T 43 4.0
END DESCRIPTION:
XS GIS Cut Line= 3
      2721776.03      6772360.98      2721676.00      6772411.00
      2721625.99      6772561.04
#Sta/Elev= 30
  4888.4  338.55  4891.2  338.55  4896.8  337.71  4902.4  337.17  4919.2  335.99
  4924.8  335.32  4933.2  333.36  4941.5  333.30  4947.1  332.62  4955.5  332.59
  4963.9  331.60  4969.5  331.56  4986.3  328.22  4989.9  326.37  4990.1  325.87
  4993.6  325.87  4993.9  326.37  4997.4  327.21  5002.9  327.21  5010.8  329.29
  5031.9  329.36  5042.4  330.47  5052.9  330.58  5074.0  332.46  5105.7  334.25
  5116.2  335.29  5126.7  335.59  5137.3  337.47  5155.7  339.68  5158.4  339.68
#Mann=3,-1,0
  4888.4    0.05       0  4989.9    0.03       0  4993.9    0.05       0
Bank Sta=4989.9,4993.9
Exp/Cntr=0.3,0.1

Type RM Length L Ch R = 1,1089,280,280,280
BEGIN DESCRIPTION:
Clear Creek T 43 3.0
END DESCRIPTION:
XS GIS Cut Line= 3
      2721851.02      6772277.28      2721576.00      6772211.00
      2721476.00      6772211.00
#Sta/Elev= 30
  4717.0  345.39  4724.9  345.49  4742.7  344.25  4753.0  344.48  4761.7  343.98
  4773.6  342.28  4794.2  341.31  4803.6  339.57  4814.7  338.90  4850.6  337.81
  4855.9  336.86  4886.7  334.02  4892.5  332.81  4897.7  332.83  4917.6  330.74
  4934.5  328.29  4939.6  328.26  4948.5  326.83  4969.0  325.81  4989.6  325.38
  4997.3  323.94  5002.4  323.94  5007.9  323.29  5008.1  322.79  5011.6  322.79
  5011.9  323.29  5019.9  325.72  5029.9  328.01  5097.4  334.72  5099.9  334.72
#Mann=3,-1,0
  4717.0    0.05       0  5007.9    0.03       0  5011.9    0.05       0
Bank Sta=5007.9,5011.9
Exp/Cntr=0.3,0.1

Type RM Length L Ch R = 1,809,227,227,227
BEGIN DESCRIPTION:
Clear Creek T 43 2.0
END DESCRIPTION:
XS GIS Cut Line= 3
      2721905.02      6771849.92      2721676.00      6771961.00
      2721425.98      6772111.01
#Sta/Elev= 30
  4735.6  342.34  4789.9  340.35  4795.5  339.04  4801.2  338.52  4812.3  338.85
  4834.5  337.56  4840.6  338.25  4863.2  336.01  4885.8  335.56  4923.4  331.23
  4959.1  329.65  4981.6  326.83  4985.4  322.00  4985.6  321.50  4989.1  321.50
  4989.4  322.00  5071.8  322.55  5093.1  322.18  5099.0  322.69  5114.5  322.07
  5130.1  322.83  5141.7  325.77  5151.5  327.38  5157.3  327.07  5165.1  329.22
  5172.8  330.17  5178.7  330.09  5200.0  332.60  5268.1  338.43  5281.7  338.96
#Mann=3,-1,0
  4735.6    0.05       0  4985.4    0.03       0  4989.4    0.05       0
Bank Sta=4985.4,4989.4
Exp/Cntr=0.3,0.1

Type RM Length L Ch R = 1,582,0,0,0
BEGIN DESCRIPTION:
Clear Creek T 43 1.0
END DESCRIPTION:
XS GIS Cut Line= 3
      2721625.97      6771711.03      2721526.00      6771811.00
      2721426.02      6772060.96
#Sta/Elev= 30
  4854.1  334.00  4857.6  334.00  4868.2  332.83  4882.3  331.86  4896.5  331.24
  4910.6  330.16  4938.9  327.50  4953.1  325.35  4981.3  322.12  4990.0  322.00
  4990.2  321.50  4993.7  321.50  4994.0  322.00  5064.1  322.00  5070.9  324.83
  5118.0  327.33  5124.7  327.99  5135.5  328.60  5142.2  328.68  5147.6  329.24
  5157.0  329.54  5171.8  331.01  5189.4  331.15  5196.1  332.35  5201.5  332.53
  5220.3  333.83  5232.4  335.06  5243.2  335.42  5262.1  337.06  5264.7  337.06
#Mann=3,-1,0
  4854.1    0.05       0  4990.0    0.05       0  4994.0    0.05       0
Bank Sta=4990,4994
Exp/Cntr=0.3,0.1

Chan Stop Cuts=-1