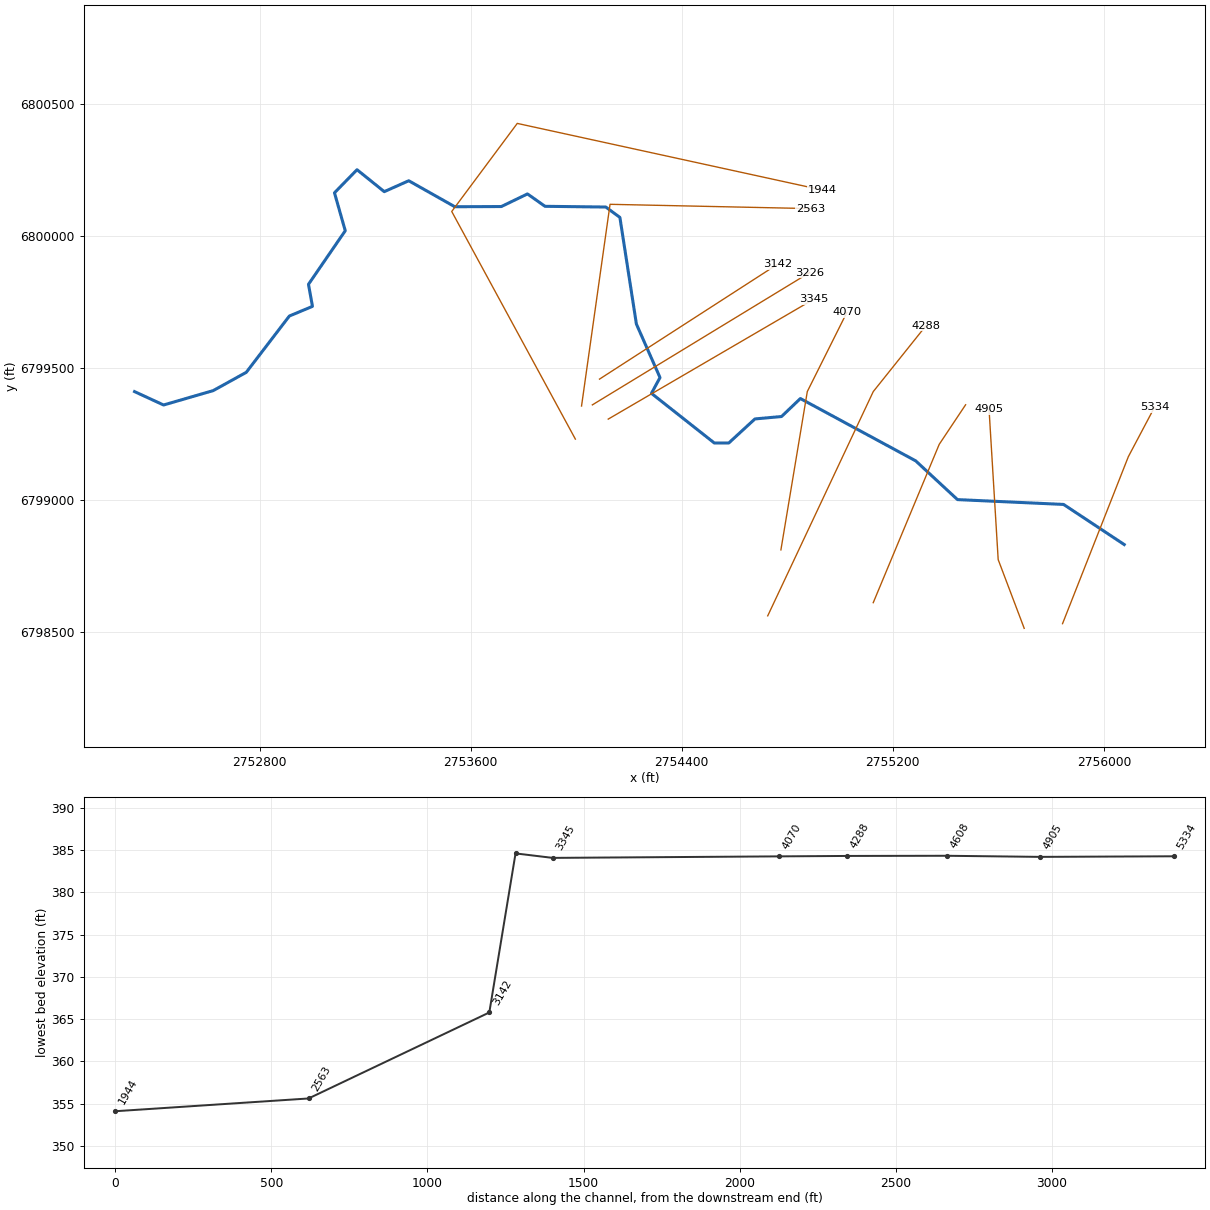
--- Clear Creek T 5.prj (project) ---

Proj Title=Clear Creek T 5 Base Level Engineering
Current Plan=p01
Default Exp/Contr=0.3,0.1
English Units
Geom File=g01
Flow File=f01
Plan File=p01
BEGIN DESCRIPTION:
Clear Creek T 5
END DESCRIPTION:

--- Clear Creek T 5.p01 (plan) ---

Plan Title=Multiple Run
Short Identifier=Multiple
Geom File=g01
Flow File=f01
Subcritical Flow
K Sum by GR= 0
Std Step Tol= 0.01
Critical Tol= 0.01
Num of Std Step Trials= 20
Max Error Tol= 0.3
Flow Tol Ratio= 0.001
Split Flow NTrial= 30
Split Flow Tol= 0.02
Split Flow Ratio= 0.02
Log Output Level= 0
Friction Slope Method= 1
Unsteady Friction Slope Method= 2
Unsteady Bridges Friction Slope Method= 1
Parabolic Critical Depth
Global Vel Dist=  1 , 1 , 1
Global Log Level= 0
CheckData=True
Encroach Param= -1, 0, 0, 0
BEGIN DESCRIPTION:
Multiple Run
END DESCRIPTION:

--- Clear Creek T 5.f01 (steady flow) ---

Flow Title=Multiple
Number of Profiles=7
Profile Names=10-year,25-year,50-year,1pct_min,100-year,1pct_plu,500-year
River Rch & RM= Clear Creek T 5,Reach-1,5334
     496     665     803     482     963    1921    1385
Boundary for River Rch & Prof#=Clear Creek T 5,Reach-1,1
Up Type=0
Dn Type=3
Dn Slope=0.005
Boundary for River Rch & Prof#=Clear Creek T 5,Reach-1,2
Up Type=0
Dn Type=3
Dn Slope=0.005
Boundary for River Rch & Prof#=Clear Creek T 5,Reach-1,3
Up Type=0
Dn Type=3
Dn Slope=0.005
Boundary for River Rch & Prof#=Clear Creek T 5,Reach-1,4
Up Type=0
Dn Type=3
Dn Slope=0.005
Boundary for River Rch & Prof#=Clear Creek T 5,Reach-1,5
Up Type=0
Dn Type=3
Dn Slope=0.005
Boundary for River Rch & Prof#=Clear Creek T 5,Reach-1,6
Up Type=0
Dn Type=3
Dn Slope=0.005
Boundary for River Rch & Prof#=Clear Creek T 5,Reach-1,7
Up Type=0
Dn Type=3
Dn Slope=0.005

--- Clear Creek T 5.g01 (geometry) ---

Geom Title=Existing Conditions

River Reach=Clear Creek T 5,Reach-1
Reach XY= 30
      2756077.20      6798831.27      2755847.37      6798983.33
      2755445.25      6799001.60      2755286.96      6799148.39
      2754849.76      6799384.65      2754778.43      6799316.52
      2754677.50      6799307.37      2754578.28      6799216.08
      2754523.72      6799216.08      2754285.29      6799404.31
      2754317.71      6799464.22      2754228.26      6799666.94
      2754165.68      6800071.18      2754112.29      6800110.53
      2753881.93      6800113.29      2753815.31      6800160.23
      2753716.35      6800112.40      2753539.91      6800111.67
      2753365.30      6800210.20      2753272.59      6800168.85
      2753169.30      6800252.03      2753083.80      6800164.45
      2753124.75      6800020.70      2752985.32      6799817.65
      2753000.36      6799734.02      2752912.79      6799697.38
      2752749.52      6799483.99      2752624.42      6799414.82
      2752436.09      6799360.22      2752326.00      6799411.00

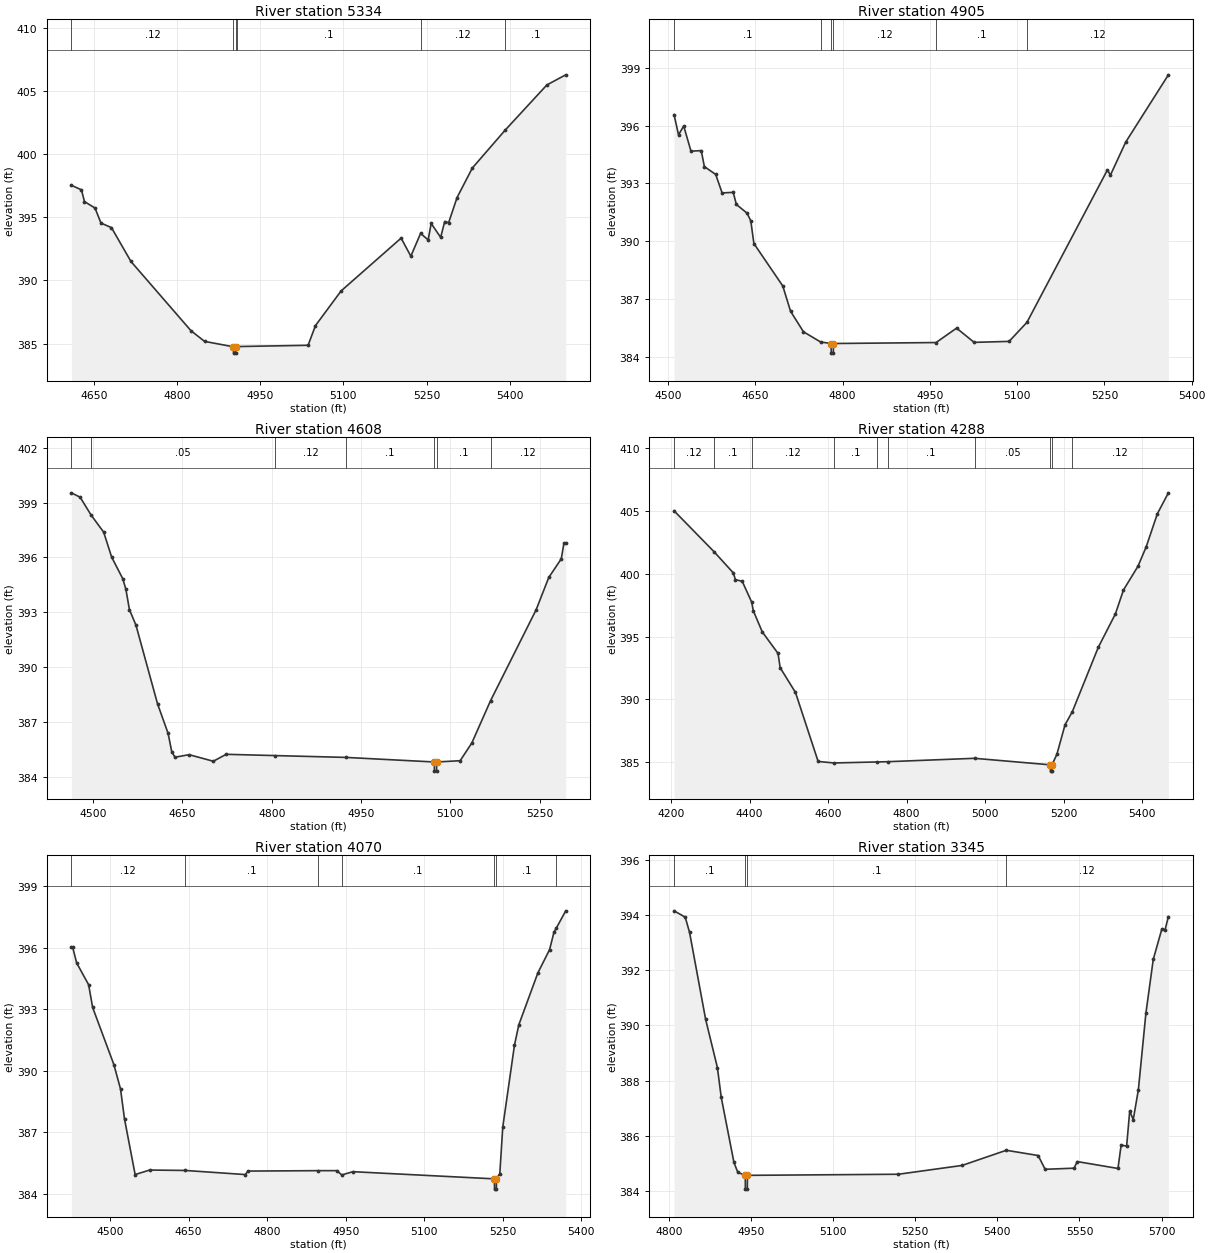
Type RM Length L Ch R = 1,5334,429,429,429
BEGIN DESCRIPTION:
2488
END DESCRIPTION:
XS GIS Cut Line= 3
      2755843.45      6798531.31      2756092.92      6799164.44
      2756191.73      6799351.09
#Sta/Elev= 30
  4609.4  397.53  4627.6  397.17  4633.0  396.24  4652.0  395.73  4662.8  394.54
  4681.7  394.18  4716.9  391.50  4825.2  386.02  4849.6  385.18  4901.7  384.75
  4902.0  384.25  4905.5  384.25  4905.7  384.75  4908.8  384.77  5036.4  384.87
  5049.7  386.43  5095.9  389.17  5204.2  393.35  5221.7  391.92  5239.3  393.72
  5253.0  393.21  5258.4  394.51  5275.5  393.41  5282.8  394.66  5289.9  394.57
  5305.1  396.56  5332.7  398.90  5391.8  401.89  5467.1  405.47  5501.1  406.27
#Mann=6,-1,0
  4609.4    0.12       0  4901.7    0.07       0  4905.7    0.12       0
  4908.8     0.1       0  5239.3    0.12       0  5391.8     0.1       0
Bank Sta=4901.7,4905.7
Exp/Cntr=0.3,0.1

Type RM Length L Ch R = 1,4905,297,297,297
BEGIN DESCRIPTION:
2487
END DESCRIPTION:
XS GIS Cut Line= 3
      2755698.11      6798513.77      2755599.54      6798774.15
      2755564.88      6799344.28
#Sta/Elev= 30
  4510.4  396.58  4518.1  395.53  4527.0  395.99  4539.5  394.68  4557.1  394.71
  4562.5  393.88  4582.0  393.47  4593.0  392.51  4612.1  392.54  4617.5  391.91
  4635.8  391.46  4642.3  391.06  4647.6  389.88  4697.3  387.67  4710.6  386.36
  4732.8  385.29  4762.2  384.76  4780.4  384.68  4780.6  384.18  4784.1  384.18
  4784.4  384.68  4960.7  384.73  4996.0  385.48  5026.1  384.74  5086.2  384.79
  5116.9  385.78  5255.3  393.71  5260.3  393.43  5286.6  395.15  5360.0  398.65
#Mann=6,-1,0
  4510.4     0.1       0  4762.2    0.12       0  4780.4    0.07       0
  4784.4    0.12       0  4960.7     0.1       0  5116.9    0.12       0
Bank Sta=4780.4,4784.4
Exp/Cntr=0.3,0.1

Type RM Length L Ch R = 1,4608,320,320,320
BEGIN DESCRIPTION:
1586
END DESCRIPTION:
XS GIS Cut Line= 3
      2755125.98      6798610.96      2755376.00      6799211.00
      2755475.99      6799360.99
#Sta/Elev= 30
  4463.4  399.53  4478.1  399.29  4496.2  398.33  4517.6  397.38  4531.1  396.01
  4549.6  394.84  4555.0  394.25  4560.9  393.14  4571.8  392.30  4608.1  387.99
  4625.9  386.37  4631.9  385.38  4637.3  385.07  4661.1  385.21  4701.8  384.85
  4723.4  385.23  4805.7  385.16  4924.8  385.06  5073.0  384.81  5073.2  384.31
  5076.7  384.31  5077.0  384.81  5116.4  384.88  5136.0  385.85  5167.4  388.16
  5244.1  393.14  5265.2  394.90  5286.2  395.92  5290.7  396.77  5293.7  396.77
#Mann=7,-1,0
  4463.4     0.1       0  4496.2    0.05       0  4805.7    0.12       0
  4924.8     0.1       0  5073.0    0.07       0  5077.0     0.1       0
  5167.4    0.12       0
Bank Sta=5073,5077
Exp/Cntr=0.3,0.1

Type RM Length L Ch R = 1,4288,218,218,218
BEGIN DESCRIPTION:
1585
END DESCRIPTION:
XS GIS Cut Line= 3
      2754726.01      6798561.03      2755126.00      6799411.00
      2755325.98      6799660.97
#Sta/Elev= 30
  4207.3  405.01  4309.0  401.76  4358.2  400.07  4363.7  399.53  4381.0  399.40
  4405.1  397.74  4409.3  397.05  4432.1  395.37  4472.2  393.66  4477.7  392.52
  4516.7  390.55  4574.4  385.06  4614.4  384.94  4723.8  385.02  4751.5  385.04
  4972.8  385.31  5166.3  384.79  5166.5  384.29  5170.0  384.29  5170.3  384.79
  5182.7  385.63  5203.5  387.98  5221.9  389.01  5288.3  394.15  5331.6  396.79
  5352.4  398.71  5389.2  400.59  5410.0  402.12  5438.8  404.78  5466.8  406.44
#Mann=10,-1,0
  4207.3    0.12       0  4309.0     0.1       0  4405.1    0.12       0
  4614.4     0.1       0  4723.8    0.12       0  4751.5     0.1       0
  4972.8    0.05       0  5166.3    0.05       0  5170.3    0.05       0
  5221.9    0.12       0
Bank Sta=5166.3,5170.3
Exp/Cntr=0.3,0.1

Type RM Length L Ch R = 1,4070,725,725,725
BEGIN DESCRIPTION:
1584
END DESCRIPTION:
XS GIS Cut Line= 3
      2754776.00      6798811.00      2754876.00      6799411.00
      2755026.01      6799711.01
#Sta/Elev= 30
  4426.4  396.02  4428.9  396.02  4436.5  395.26  4459.3  394.20  4467.0  393.09
  4507.5  390.31  4520.2  389.12  4527.8  387.66  4548.1  384.95  4575.9  385.17
  4643.6  385.15  4758.4  384.95  4763.5  385.12  4897.8  385.14  4933.3  385.14
  4942.6  384.93  4963.7  385.09  5233.9  384.74  5234.2  384.24  5237.7  384.24
  5237.9  384.74  5244.3  385.00  5249.9  387.26  5272.3  391.26  5280.6  392.25
  5317.0  394.78  5339.3  395.91  5347.7  396.76  5352.4  396.97  5370.1  397.80
#Mann=7,-1,0
  4426.4    0.12       0  4643.6     0.1       0  4897.8    0.12       0
  4942.6     0.1       0  5233.9    0.07       0  5237.9     0.1       0
  5352.4    0.12       0
Bank Sta=5233.9,5237.9
Exp/Cntr=0.3,0.1

Type RM Length L Ch R = 1,3345,119,119,119
BEGIN DESCRIPTION:
2409
END DESCRIPTION:
XS GIS Cut Line= 2
      2754121.54      6799306.75      2754901.48      6799761.83
#Sta/Elev= 30
  4809.4  394.16  4829.8  393.93  4837.7  393.38  4867.1  390.22  4888.6  388.47
  4895.6  387.39  4918.8  385.03  4925.8  384.67  4939.5  384.56  4939.7  384.06
  4943.2  384.06  4943.5  384.56  5219.3  384.60  5335.6  384.92  5416.3  385.47
  5474.5  385.28  5487.2  384.78  5540.1  384.82  5545.9  385.06  5620.3  384.81
  5626.1  385.66  5636.1  385.62  5641.8  386.90  5648.2  386.58  5657.6  387.67
  5671.3  390.44  5684.8  392.40  5700.6  393.51  5706.3  393.47  5712.4  393.95
#Mann=4,-1,0
  4809.4     0.1       0  4939.5    0.07       0  4943.5     0.1       0
  5416.3    0.12       0
Bank Sta=4939.5,4943.5
Exp/Cntr=0.3,0.1

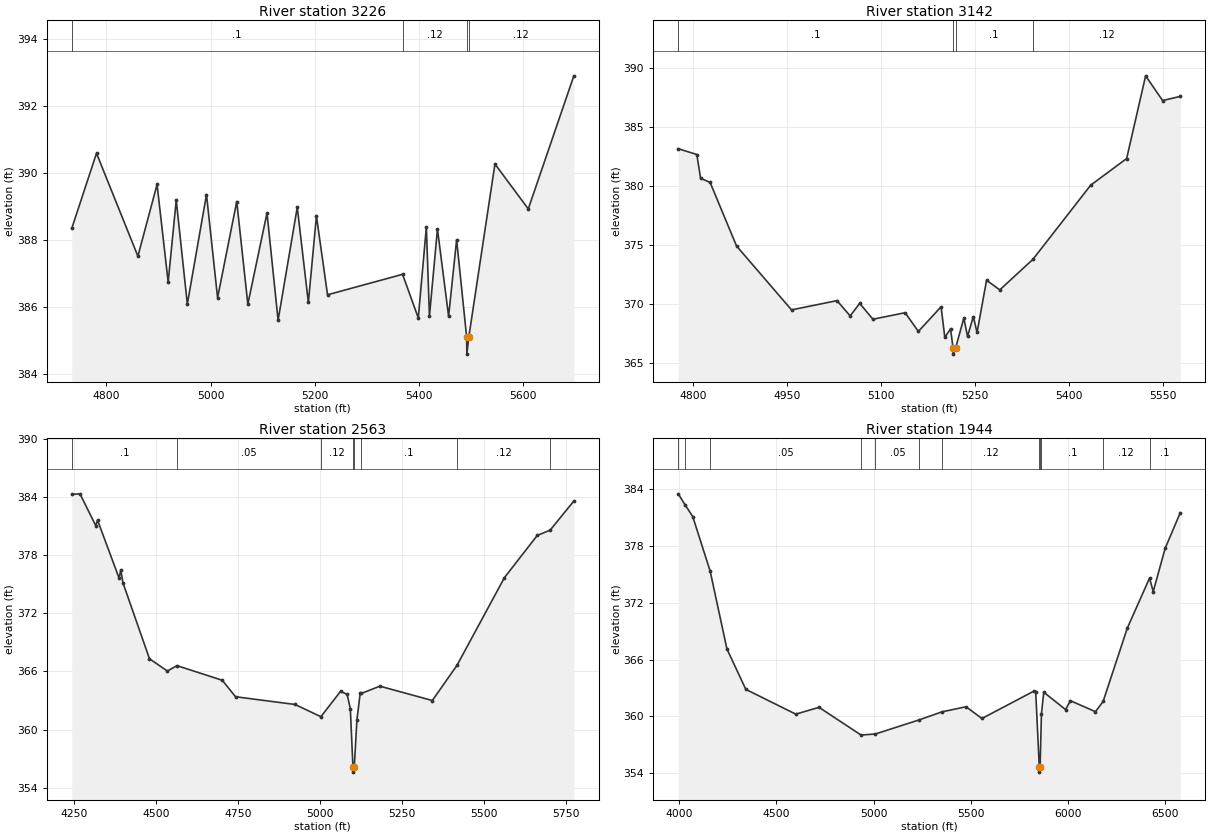
Type RM Length L Ch R = 1,3226,84,84,84
BEGIN DESCRIPTION:
2408
END DESCRIPTION:
XS GIS Cut Line= 2
      2754061.35      6799360.69      2754884.80      6799862.12
#Sta/Elev= 30
  4733.6  388.34  4781.1  390.58  4860.6  387.51  4897.4  389.65  4918.7  386.74
  4934.2  389.18  4955.5  386.08  4992.3  389.35  5013.6  386.27  5050.4  389.14
  5071.7  386.08  5108.5  388.80  5129.8  385.60  5166.6  388.97  5187.9  386.13
  5203.4  388.71  5224.7  386.36  5368.8  386.97  5399.0  385.67  5414.5  388.38
  5420.4  385.72  5435.8  388.32  5457.2  385.72  5472.6  388.00  5491.9  385.09
  5492.2  384.59  5495.9  385.09  5546.2  390.26  5610.2  388.92  5697.7  392.89
#Mann=4,-1,0
  4733.6     0.1       0  5368.8    0.12       0  5491.9    0.07       0
  5495.9    0.12       0
Bank Sta=5491.9,5495.9
Exp/Cntr=0.3,0.1

Type RM Length L Ch R = 1,3142,579,579,579
BEGIN DESCRIPTION:
2407
END DESCRIPTION:
XS GIS Cut Line= 2
      2754088.42      6799458.33      2754762.17      6799893.01
#Sta/Elev= 30
  4776.6  383.14  4806.3  382.65  4812.3  380.64  4827.5  380.29  4869.7  374.92
  4957.5  369.52  5030.1  370.30  5051.2  369.01  5066.4  370.07  5087.5  368.73
  5138.9  369.28  5160.1  367.70  5196.4  369.78  5202.3  367.20  5211.5  367.92
  5215.5  366.28  5215.7  365.78  5219.5  366.28  5232.7  368.83  5238.6  367.27
  5247.8  368.95  5253.8  367.61  5269.0  372.02  5290.1  371.21  5343.0  373.79
  5435.3  380.06  5492.7  382.31  5523.0  389.30  5550.1  387.21  5578.4  387.56
#Mann=4,-1,0
  4776.6     0.1       0  5215.5    0.07       0  5219.5     0.1       0
  5343.0    0.12       0
Bank Sta=5215.5,5219.5
Exp/Cntr=0.3,0.1

Type RM Length L Ch R = 1,2563,619,619,619
BEGIN DESCRIPTION:
2406
END DESCRIPTION:
XS GIS Cut Line= 3
      2754020.32      6799356.27      2754128.31      6800120.87
      2754887.75      6800104.63
#Sta/Elev= 30
  4242.0  384.27  4267.0  384.33  4315.4  381.03  4320.5  381.62  4386.5  375.62
  4391.5  376.48  4398.3  375.13  4479.1  367.31  4533.7  366.04  4562.9  366.60
  4701.2  365.09  4741.6  363.39  4923.4  362.59  5002.0  361.33  5061.9  363.94
  5081.9  363.65  5091.9  362.16  5099.9  356.11  5100.1  355.61  5103.9  356.11
  5111.9  360.98  5121.9  363.73  5125.6  363.73  5181.9  364.48  5342.0  363.00
  5417.1  366.62  5562.0  375.68  5662.0  380.03  5701.7  380.59  5773.8  383.59
#Mann=8,-1,0
  4242.0     0.1       0  4562.9    0.05       0  5002.0    0.12       0
  5099.9    0.05       0  5103.9    0.12       0  5125.6     0.1       0
  5417.1    0.12       0  5701.7     0.1       0
Bank Sta=5099.9,5103.9
Exp/Cntr=0.3,0.1

Type RM Length L Ch R = 1,1944,0,0,0
BEGIN DESCRIPTION:
1583
END DESCRIPTION:
XS GIS Cut Line= 4
      2753996.86      6799231.01      2753528.29      6800093.70
      2753776.69      6800427.55      2754932.01      6800175.23
#Sta/Elev= 30
  3996.1  383.52  4030.9  382.37  4070.6  381.12  4160.0  375.36  4246.4  367.12
  4343.4  362.85  4600.0  360.23  4719.7  360.95  4935.7  358.02  5009.0  358.13
  5235.3  359.63  5351.1  360.47  5475.1  361.01  5557.0  359.77  5825.6  362.68
  5833.4  362.56  5851.8  354.60  5852.1  354.10  5855.8  354.60  5862.8  360.26
  5874.7  362.55  5986.9  360.71  6011.5  361.65  6140.4  360.49  6179.7  361.57
  6304.2  369.33  6418.4  374.61  6437.3  373.19  6498.7  377.76  6576.5  381.53
#Mann=12,-1,0
  3996.1     0.1       0  4030.9    0.12       0  4160.0    0.05       0
  4935.7    0.12       0  5009.0    0.05       0  5235.3     0.1       0
  5351.1    0.12       0  5851.8    0.07       0  5855.8    0.12       0
  5862.8     0.1       0  6179.7    0.12       0  6418.4     0.1       0
Bank Sta=5851.8,5855.8
Exp/Cntr=0.3,0.1

Chan Stop Cuts=-1