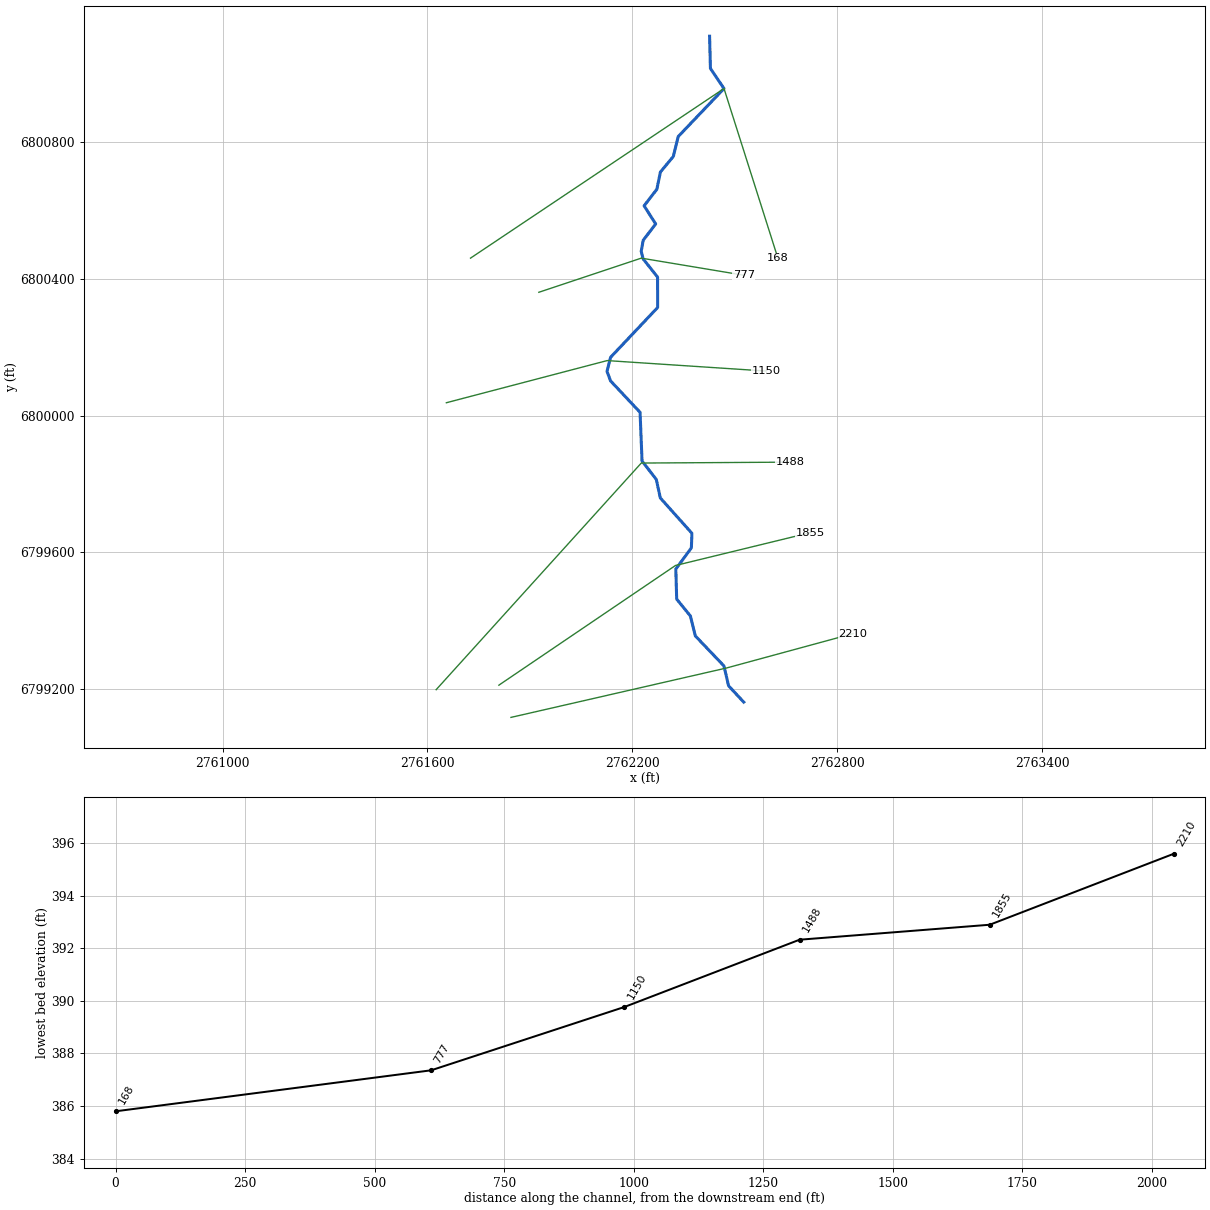
--- Clear Creek T 6.prj (project) ---

Proj Title=Clear Creek T 6 Base Level Engineering
Current Plan=p01
Default Exp/Contr=0.3,0.1
English Units
Geom File=g01
Flow File=f01
Plan File=p01
BEGIN DESCRIPTION:
Clear Creek T 6
END DESCRIPTION:

--- Clear Creek T 6.p01 (plan) ---

Plan Title=Multiple Run
Short Identifier=Multiple
Geom File=g01
Flow File=f01
Subcritical Flow
K Sum by GR= 0
Std Step Tol= 0.01
Critical Tol= 0.01
Num of Std Step Trials= 20
Max Error Tol= 0.3
Flow Tol Ratio= 0.001
Split Flow NTrial= 30
Split Flow Tol= 0.02
Split Flow Ratio= 0.02
Log Output Level= 0
Friction Slope Method= 1
Unsteady Friction Slope Method= 2
Unsteady Bridges Friction Slope Method= 1
Parabolic Critical Depth
Global Vel Dist=  1 , 1 , 1
Global Log Level= 0
CheckData=True
Encroach Param= -1, 0, 0, 0
BEGIN DESCRIPTION:
Multiple Run
END DESCRIPTION:

--- Clear Creek T 6.f01 (steady flow) ---

Flow Title=Multiple
Number of Profiles=7
Profile Names=10-year,25-year,50-year,1pct_min,100-year,1pct_plu,500-year
River Rch & RM= Clear Creek T 6,Reach-1,2210
     478     641     774     465     928    1852    1337
Boundary for River Rch & Prof#=Clear Creek T 6,Reach-1,1
Up Type=0
Dn Type=3
Dn Slope=0.005
Boundary for River Rch & Prof#=Clear Creek T 6,Reach-1,2
Up Type=0
Dn Type=3
Dn Slope=0.005
Boundary for River Rch & Prof#=Clear Creek T 6,Reach-1,3
Up Type=0
Dn Type=3
Dn Slope=0.005
Boundary for River Rch & Prof#=Clear Creek T 6,Reach-1,4
Up Type=0
Dn Type=3
Dn Slope=0.005
Boundary for River Rch & Prof#=Clear Creek T 6,Reach-1,5
Up Type=0
Dn Type=3
Dn Slope=0.005
Boundary for River Rch & Prof#=Clear Creek T 6,Reach-1,6
Up Type=0
Dn Type=3
Dn Slope=0.005
Boundary for River Rch & Prof#=Clear Creek T 6,Reach-1,7
Up Type=0
Dn Type=3
Dn Slope=0.005

--- Clear Creek T 6.g01 (geometry) ---

Geom Title=Existing Conditions

River Reach=Clear Creek T 6,Reach-1
Reach XY= 30
      2762526.00      6799161.00      2762481.70      6799208.65
      2762467.93      6799267.08      2762384.16      6799354.95
      2762369.85      6799413.17      2762329.67      6799462.58
      2762327.12      6799550.46      2762372.66      6799612.75
      2762374.26      6799655.37      2762281.85      6799758.71
      2762269.86      6799813.17      2762228.25      6799866.93
      2762222.44      6800009.53      2762136.20      6800101.33
      2762125.63      6800129.41      2762136.17      6800170.68
      2762273.92      6800316.48      2762273.69      6800405.44
      2762231.40      6800458.83      2762225.79      6800481.21
      2762231.63      6800513.30      2762268.17      6800561.08
      2762234.24      6800614.23      2762271.59      6800662.63
      2762282.05      6800713.19      2762319.89      6800758.81
      2762334.14      6800817.06      2762468.24      6800957.59
      2762428.47      6801016.36      2762426.00      6801111.00

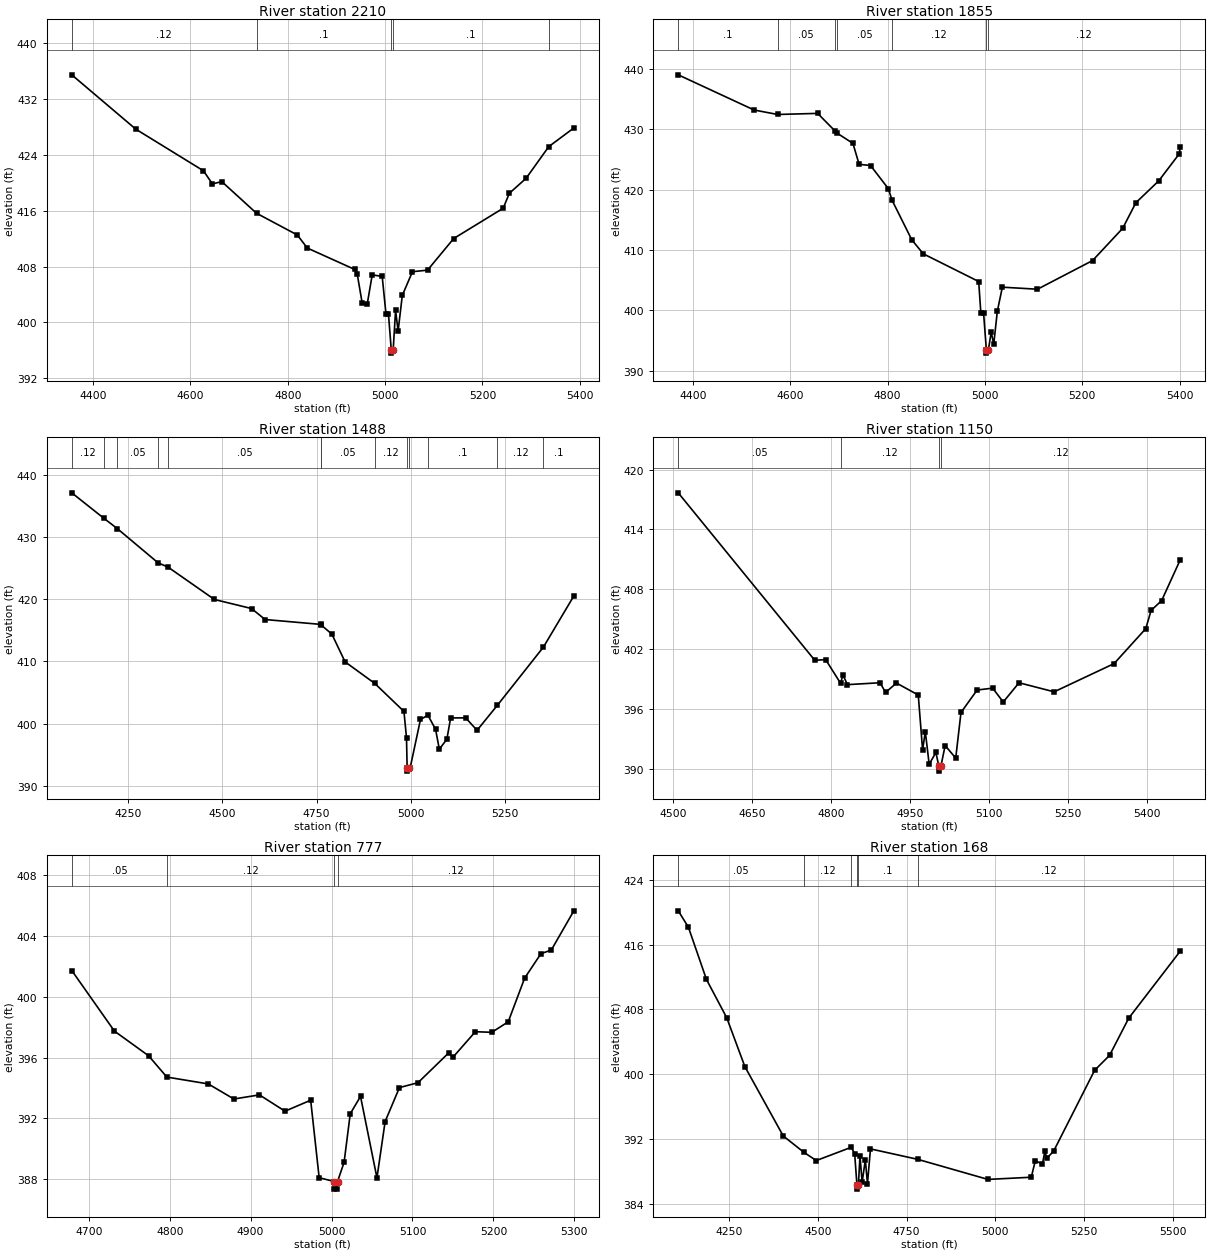
Type RM Length L Ch R = 1,2210,355,355,355
BEGIN DESCRIPTION:
Clear Creek T 6 6.0
END DESCRIPTION:
XS GIS Cut Line= 3
      2761844.44      6799116.26      2762476.00      6799261.00
      2762846.04      6799361.56
#Sta/Elev= 30
  4356.3  435.45  4487.8  427.67  4626.8  421.71  4645.2  419.83  4664.5  420.16
  4735.8  415.63  4819.6  412.52  4840.1  410.65  4937.3  407.59  4942.7  406.93
  4952.9  402.76  4963.2  402.60  4973.5  406.81  4994.0  406.58  5001.7  401.25
  5006.8  401.25  5012.6  396.10  5012.9  395.60  5016.6  396.10  5021.5  401.71
  5026.7  398.76  5035.3  403.86  5056.1  407.26  5087.1  407.48  5140.9  412.01
  5242.6  416.35  5255.1  418.48  5289.7  420.64  5336.2  425.17  5387.7  427.84
#Mann=5,-1,0
  4356.3    0.12       0  4735.8     0.1       0  5012.6    0.07       0
  5016.6     0.1       0  5336.2    0.05       0
Bank Sta=5012.6,5016.6
Exp/Cntr=0.3,0.1

Type RM Length L Ch R = 1,1855,367,367,367
BEGIN DESCRIPTION:
Clear Creek T 6 5.0
END DESCRIPTION:
XS GIS Cut Line= 3
      2761808.98      6799210.61      2762326.00      6799561.00
      2762721.08      6799657.23
#Sta/Elev= 30
  4370.1  439.02  4525.9  433.19  4574.2  432.45  4656.4  432.63  4691.8  429.74
  4696.5  429.35  4728.9  427.66  4741.6  424.19  4765.1  423.99  4801.4  420.18
  4809.5  418.20  4849.7  411.69  4873.3  409.36  4987.2  404.77  4991.6  399.57
  4997.2  399.57  5003.0  393.40  5003.2  392.90  5007.0  393.40  5012.9  396.38
  5018.1  394.37  5025.5  399.86  5035.8  403.83  5107.9  403.49  5221.1  408.24
  5282.9  413.58  5310.1  417.83  5356.9  421.44  5398.7  425.88  5401.3  427.02
#Mann=7,-1,0
  4370.1     0.1       0  4574.2    0.05       0  4691.8     0.1       0
  4696.5    0.05       0  4809.5    0.12       0  5003.0    0.07       0
  5007.0    0.12       0
Bank Sta=5003,5007
Exp/Cntr=0.3,0.1

Type RM Length L Ch R = 1,1488,338,338,338
BEGIN DESCRIPTION:
Clear Creek T 6 4.0
END DESCRIPTION:
XS GIS Cut Line= 3
      2761625.42      6799197.46      2762226.00      6799861.00
      2762662.82      6799863.67
#Sta/Elev= 30
  4100.5  437.16  4185.6  433.06  4221.2  431.40  4329.3  425.89  4356.2  425.18
  4478.8  419.98  4577.4  418.52  4613.3  416.75  4760.5  415.97  4761.1  415.92
  4790.4  414.40  4825.5  409.93  4904.2  406.46  4981.6  401.95  4988.4  397.71
  4990.1  392.83  4990.4  392.33  4994.1  392.83  4998.0  392.83  5025.5  400.65
  5045.2  401.34  5065.5  399.06  5075.5  395.86  5095.5  397.47  5105.5  400.90
  5145.5  400.91  5175.5  398.90  5229.5  402.94  5351.7  412.32  5432.3  420.55
#Mann=13,-1,0
  4100.5    0.12       0  4185.6     0.1       0  4221.2    0.05       0
  4329.3     0.1       0  4356.2    0.05       0  4760.5    0.12       0
  4761.1    0.05       0  4904.2    0.12       0  4990.1    0.07       0
  4994.1    0.12       0  5045.2     0.1       0  5229.5    0.12       0
  5351.7     0.1       0
Bank Sta=4990.1,4994.1
Exp/Cntr=0.3,0.1

Type RM Length L Ch R = 1,1150,373,373,373
BEGIN DESCRIPTION:
Clear Creek T 6 3.0
END DESCRIPTION:
XS GIS Cut Line= 3
      2761655.31      6800037.60      2762126.00      6800161.00
      2762591.40      6800130.37
#Sta/Elev= 30
  4509.6  417.67  4768.8  400.88  4789.4  400.95  4817.7  398.58  4822.2  399.40
  4830.8  398.44  4892.6  398.63  4903.2  397.66  4923.8  398.60  4965.2  397.40
  4973.4  391.90  4978.6  393.72  4985.9  390.46  4998.7  391.64  5004.2  390.27
  5004.5  389.77  5008.2  390.27  5016.2  392.33  5036.3  391.08  5046.3  395.65
  5076.9  397.90  5106.4  398.09  5126.5  396.70  5156.5  398.63  5223.1  397.72
  5336.9  400.55  5397.1  404.06  5407.1  405.88  5427.1  406.86  5462.6  410.97
#Mann=4,-1,0
  4509.6    0.05       0  4817.7    0.12       0  5004.2    0.07       0
  5008.2    0.12       0
Bank Sta=5004.2,5008.2
Exp/Cntr=0.3,0.1

Type RM Length L Ch R = 1,777,609,609,609
BEGIN DESCRIPTION:
Clear Creek T 6 2.0
END DESCRIPTION:
XS GIS Cut Line= 3
      2761925.99      6800361.00      2762226.00      6800461.00
      2762526.02      6800411.00
#Sta/Elev= 30
  4679.0  401.72  4731.7  397.74  4773.9  396.12  4796.5  394.72  4847.7  394.27
  4879.3  393.28  4910.9  393.55  4942.5  392.48  4974.2  393.20  4984.7  388.11
  5003.4  387.86  5003.6  387.36  5007.1  387.36  5007.4  387.86  5015.5  389.12
  5023.1  392.31  5035.8  393.45  5056.1  388.10  5066.2  391.80  5083.9  394.03
  5106.8  394.35  5144.8  396.31  5149.8  396.01  5177.7  397.70  5198.0  397.66
  5218.3  398.35  5238.6  401.22  5258.8  402.83  5271.5  403.06  5299.4  405.64
#Mann=4,-1,0
  4679.0    0.05       0  4796.5    0.12       0  5003.4    0.07       0
  5007.4    0.12       0
Bank Sta=5003.4,5007.4
Exp/Cntr=0.3,0.1

Type RM Length L Ch R = 1,168,0,0,0
BEGIN DESCRIPTION:
Clear Creek T 6 1.0
END DESCRIPTION:
XS GIS Cut Line= 3
      2761726.03      6800461.02      2762468.24      6800957.59
      2762625.99      6800461.04
#Sta/Elev= 30
  4107.0  420.18  4135.5  418.17  4186.5  411.70  4243.6  406.97  4294.6  400.94
  4402.7  392.37  4460.8  390.35  4495.8  389.33  4594.4  390.97  4603.9  390.17
  4610.3  386.30  4610.5  385.80  4614.3  386.30  4618.9  389.89  4624.9  386.65
  4633.9  389.42  4639.9  386.47  4648.4  390.77  4781.5  389.48  4979.2  387.00
  5101.3  387.27  5112.6  389.31  5132.8  388.89  5139.6  390.52  5144.9  389.60
  5164.3  390.50  5279.7  400.48  5321.7  402.32  5375.9  406.93  5521.0  415.21
#Mann=6,-1,0
  4107.0    0.05       0  4460.8    0.12       0  4594.4     0.1       0
  4610.3    0.07       0  4614.3     0.1       0  4781.5    0.12       0
Bank Sta=4610.3,4614.3
Exp/Cntr=0.3,0.1

Chan Stop Cuts=-1