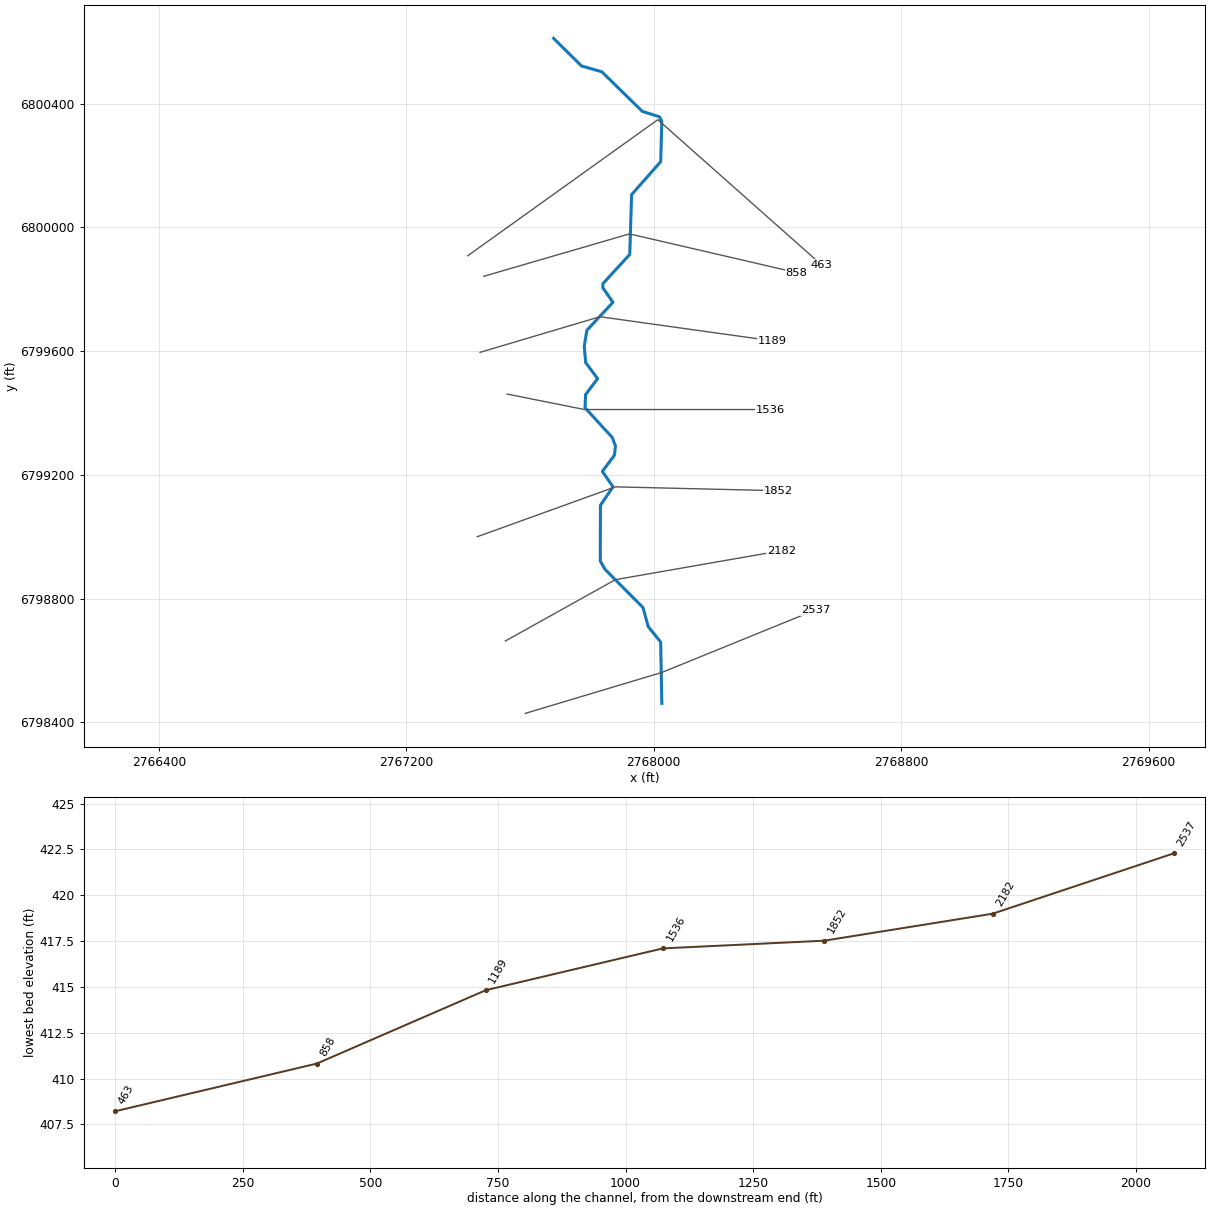
--- Clear Creek T 7.prj (project) ---

Proj Title=Clear Creek T 7 Base Level Engineering
Current Plan=p01
Default Exp/Contr=0.3,0.1
English Units
Geom File=g01
Flow File=f01
Plan File=p01
BEGIN DESCRIPTION:
Clear Creek T 7
END DESCRIPTION:

--- Clear Creek T 7.p01 (plan) ---

Plan Title=Multiple Run
Short Identifier=Multiple
Geom File=g01
Flow File=f01
Subcritical Flow
K Sum by GR= 0
Std Step Tol= 0.01
Critical Tol= 0.01
Num of Std Step Trials= 20
Max Error Tol= 0.3
Flow Tol Ratio= 0.001
Split Flow NTrial= 30
Split Flow Tol= 0.02
Split Flow Ratio= 0.02
Log Output Level= 0
Friction Slope Method= 1
Unsteady Friction Slope Method= 2
Unsteady Bridges Friction Slope Method= 1
Parabolic Critical Depth
Global Vel Dist=  1 , 1 , 1
Global Log Level= 0
CheckData=True
Encroach Param= -1, 0, 0, 0
BEGIN DESCRIPTION:
Multiple Run
END DESCRIPTION:

--- Clear Creek T 7.f01 (steady flow) ---

Flow Title=Multiple
Number of Profiles=7
Profile Names=10-year,25-year,50-year,1pct_min,100-year,1pct_plu,500-year
River Rch & RM= Clear Creek T 7,Reach-1,2537
     619     849    1041     636    1268    2530    1886
Boundary for River Rch & Prof#=Clear Creek T 7,Reach-1,1
Up Type=0
Dn Type=3
Dn Slope=0.005
Boundary for River Rch & Prof#=Clear Creek T 7,Reach-1,2
Up Type=0
Dn Type=3
Dn Slope=0.005
Boundary for River Rch & Prof#=Clear Creek T 7,Reach-1,3
Up Type=0
Dn Type=3
Dn Slope=0.005
Boundary for River Rch & Prof#=Clear Creek T 7,Reach-1,4
Up Type=0
Dn Type=3
Dn Slope=0.005
Boundary for River Rch & Prof#=Clear Creek T 7,Reach-1,5
Up Type=0
Dn Type=3
Dn Slope=0.005
Boundary for River Rch & Prof#=Clear Creek T 7,Reach-1,6
Up Type=0
Dn Type=3
Dn Slope=0.005
Boundary for River Rch & Prof#=Clear Creek T 7,Reach-1,7
Up Type=0
Dn Type=3
Dn Slope=0.005

--- Clear Creek T 7.g01 (geometry) ---

Geom Title=Existing Conditions

River Reach=Clear Creek T 7,Reach-1
Reach XY= 30
      2768026.00      6798461.00      2768022.26      6798659.45
      2767982.14      6798708.83      2767965.24      6798770.68
      2767842.43      6798894.24      2767827.05      6798921.43
      2767827.54      6799101.41      2767868.21      6799161.10
      2767833.83      6799210.92      2767872.44      6799262.65
      2767876.23      6799292.59      2767865.77      6799320.67
      2767777.78      6799416.64      2767779.57      6799459.35
      2767818.40      6799510.99      2767779.93      6799562.50
      2767775.18      6799615.58      2767783.80      6799667.17
      2767867.98      6799757.67      2767835.62      6799804.33
      2767835.32      6799817.66      2767922.44      6799912.46
      2767928.18      6800105.55      2768022.46      6800212.48
      2768025.78      6800342.42      2768018.20      6800357.45
      2767963.05      6800374.74      2767832.05      6800502.85
      2767766.30      6800521.72      2767676.00      6800611.00

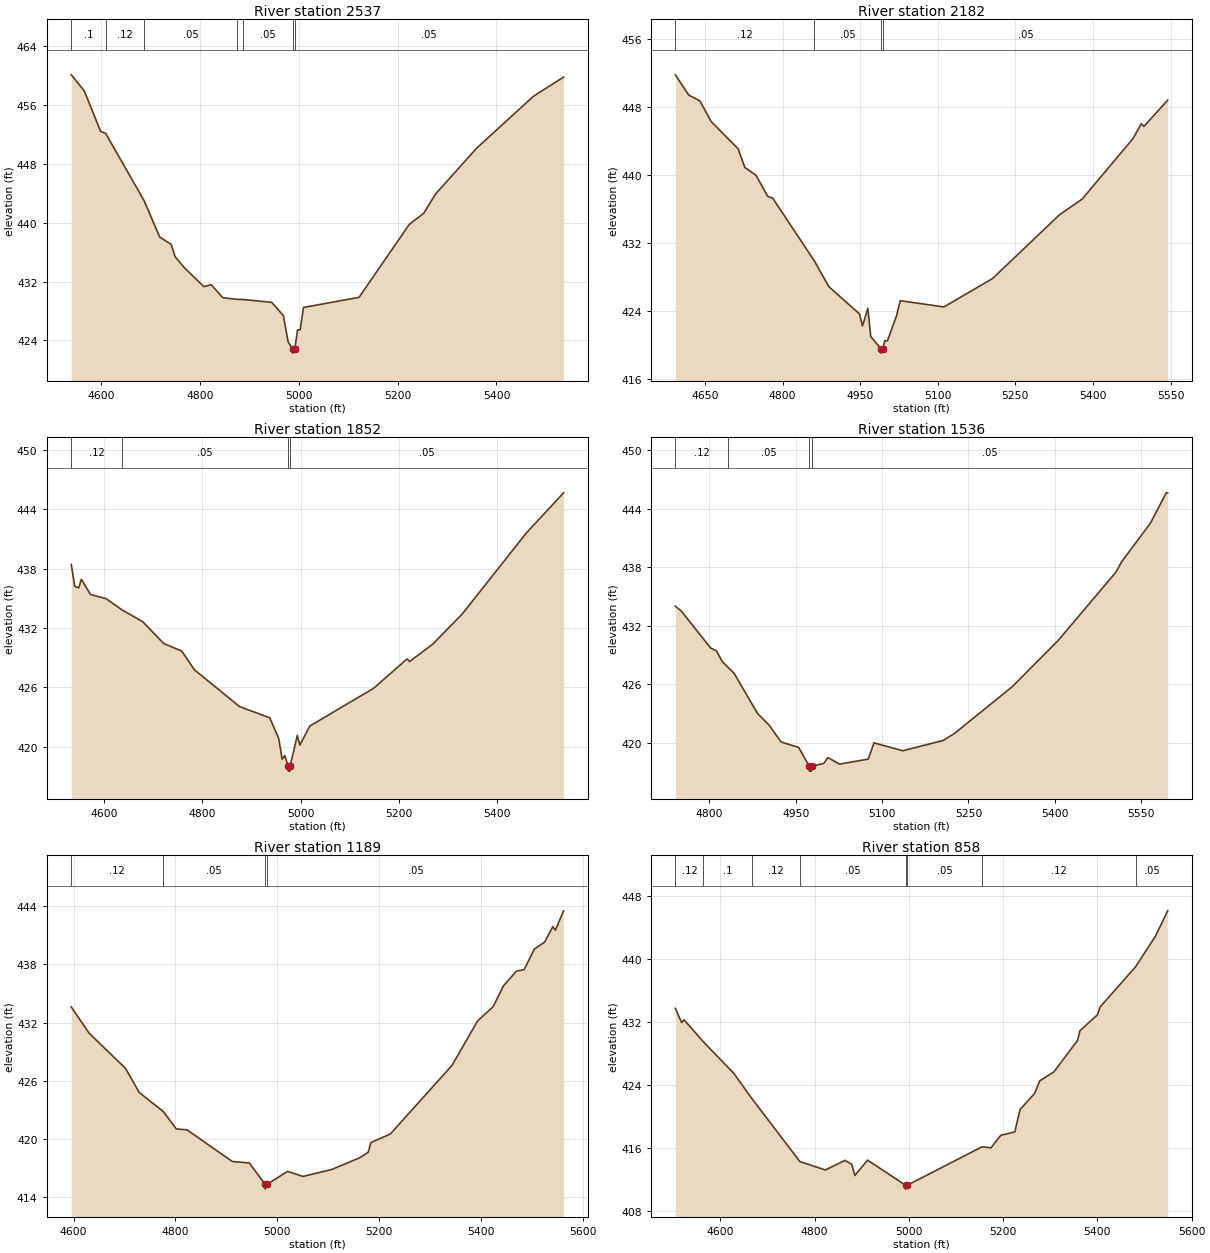
Type RM Length L Ch R = 1,2537,355,355,355
BEGIN DESCRIPTION:
Clear Creek T 7 6.0
END DESCRIPTION:
XS GIS Cut Line= 3
      2767584.71      6798428.71      2768026.00      6798561.00
      2768522.38      6798762.99
#Sta/Elev= 30
  4539.2  460.11  4565.6  457.92  4598.7  452.40  4608.7  452.16  4686.6  443.01
  4718.0  438.08  4741.4  437.06  4749.3  435.39  4769.3  433.81  4807.6  431.32
  4822.4  431.58  4845.9  429.82  4874.9  429.59  4887.5  429.57  4945.1  429.18
  4968.6  427.37  4978.1  423.83  4987.5  422.78  4987.7  422.28  4991.5  422.78
  4997.3  425.44  5002.6  425.44  5009.2  428.49  5121.7  429.86  5223.3  439.76
  5252.8  441.30  5276.8  443.92  5359.8  450.14  5474.9  457.20  5535.8  459.80
#Mann=7,-1,0
  4539.2     0.1       0  4608.7    0.12       0  4686.6    0.05       0
  4874.9     0.1       0  4887.5    0.05       0  4987.5    0.05       0
  4991.5    0.05       0
Bank Sta=4987.5,4991.5
Exp/Cntr=0.3,0.1

Type RM Length L Ch R = 1,2182,330,330,330
BEGIN DESCRIPTION:
Clear Creek T 7 5.0
END DESCRIPTION:
XS GIS Cut Line= 3
      2767520.09      6798662.64      2767876.00      6798861.00
      2768412.13      6798954.63
#Sta/Elev= 30
  4592.8  451.78  4618.5  449.40  4640.2  448.71  4661.9  446.28  4714.1  443.07
  4727.1  440.87  4748.8  439.94  4771.3  437.46  4780.8  437.26  4861.5  429.85
  4889.4  426.83  4948.8  423.60  4954.5  422.18  4964.8  424.26  4970.5  420.94
  4990.3  419.49  4990.5  418.99  4994.3  419.49  4997.4  420.44  5002.8  420.44
  5020.6  423.44  5027.5  425.17  5111.9  424.43  5206.0  427.78  5335.2  435.28
  5379.5  437.16  5477.4  444.27  5493.5  446.02  5498.5  445.70  5544.5  448.79
#Mann=4,-1,0
  4592.8    0.12       0  4861.5    0.05       0  4990.3    0.05       0
  4994.3    0.05       0
Bank Sta=4990.3,4994.3
Exp/Cntr=0.3,0.1

Type RM Length L Ch R = 1,1852,316,316,316
BEGIN DESCRIPTION:
Clear Creek T 7 4.0
END DESCRIPTION:
XS GIS Cut Line= 3
      2767429.42      6798999.85      2767876.00      6799161.00
      2768401.79      6799148.53
#Sta/Elev= 30
  4534.0  438.43  4541.0  436.22  4549.2  436.07  4554.5  436.93  4572.9  435.40
  4604.8  434.97  4637.6  433.82  4679.2  432.64  4721.7  430.44  4758.6  429.67
  4784.0  427.79  4876.0  424.05  4937.4  422.92  4955.6  420.83  4962.7  418.73
  4968.1  419.08  4974.9  418.02  4975.1  417.52  4978.6  417.52  4978.9  418.02
  4993.4  421.14  4998.7  420.16  5018.8  422.08  5148.8  425.91  5216.7  428.88
  5221.7  428.61  5268.8  430.37  5328.9  433.43  5458.9  441.61  5534.7  445.68
#Mann=4,-1,0
  4534.0    0.12       0  4637.6    0.05       0  4974.9    0.04       0
  4978.9    0.05       0
Bank Sta=4974.9,4978.9
Exp/Cntr=0.3,0.1

Type RM Length L Ch R = 1,1536,347,347,347
BEGIN DESCRIPTION:
Clear Creek T 7 3.0
END DESCRIPTION:
XS GIS Cut Line= 3
      2767526.04      6799460.99      2767776.00      6799411.00
      2768375.99      6799411.00
#Sta/Elev= 30
  4741.1  434.00  4751.3  433.51  4802.2  429.73  4812.4  429.42  4822.6  428.32
  4833.0  427.71  4843.0  427.13  4883.8  423.01  4904.2  421.79  4924.6  420.09
  4955.2  419.53  4973.6  417.60  4973.9  417.10  4977.4  417.10  4977.6  417.60
  4998.5  417.88  5006.0  418.49  5026.0  417.82  5076.0  418.33  5086.0  420.00
  5136.0  419.19  5206.0  420.24  5226.0  420.97  5326.0  425.75  5406.0  430.50
  5506.0  437.48  5516.0  438.55  5566.0  442.51  5593.5  445.62  5596.0  445.62
#Mann=4,-1,0
  4741.1    0.12       0  4833.0    0.05       0  4973.6    0.04       0
  4977.6    0.05       0
Bank Sta=4973.6,4977.6
Exp/Cntr=0.3,0.1

Type RM Length L Ch R = 1,1189,331,331,331
BEGIN DESCRIPTION:
Clear Creek T 7 2.0
END DESCRIPTION:
XS GIS Cut Line= 3
      2767438.24      6799595.81      2767826.00      6799711.00
      2768382.89      6799633.24
#Sta/Elev= 30
  4595.4  433.61  4630.4  430.91  4702.0  427.27  4728.7  424.80  4776.0  422.83
  4801.6  421.03  4822.6  420.94  4911.7  417.67  4944.9  417.52  4976.1  415.32
  4976.3  414.82  4980.1  415.32  5020.1  416.65  5050.4  416.13  5107.1  416.85
  5161.5  418.05  5178.6  418.63  5183.7  419.62  5222.0  420.51  5343.2  427.59
  5393.1  432.15  5424.0  433.65  5444.2  435.80  5469.7  437.31  5484.6  437.45
  5504.8  439.58  5525.0  440.31  5541.2  441.90  5546.2  441.54  5562.2  443.53
#Mann=4,-1,0
  4595.4    0.12       0  4776.0    0.05       0  4976.1    0.04       0
  4980.1    0.05       0
Bank Sta=4976.1,4980.1
Exp/Cntr=0.3,0.1

Type RM Length L Ch R = 1,858,395,395,395
BEGIN DESCRIPTION:
Mapping XS c95389ab
END DESCRIPTION:
XS GIS Cut Line= 3
      2767450.38      6799841.70      2767921.42      6799978.86
      2768461.18      6799853.68
#Sta/Elev= 30
  4504.4  433.75  4517.6  431.94  4522.8  432.30  4563.8  429.51  4628.6  425.49
  4666.1  422.36  4768.5  414.32  4822.7  413.25  4864.4  414.47  4878.7  413.96
  4885.2  412.55  4912.2  414.50  4992.8  411.32  4993.0  410.82  4996.8  411.32
  5155.1  416.19  5174.2  416.06  5194.8  417.64  5224.7  418.08  5235.8  420.91
  5266.6  422.95  5277.6  424.56  5307.7  425.69  5357.8  429.68  5362.9  430.91
  5400.1  432.93  5405.6  433.92  5481.0  439.02  5523.2  442.91  5549.1  446.12
#Mann=8,-1,0
  4504.4    0.12       0  4563.8     0.1       0  4666.1    0.12       0
  4768.5    0.05       0  4992.8    0.05       0  4996.8    0.05       0
  5155.1    0.12       0  5481.0    0.05       0
Bank Sta=4992.8,4996.8
Exp/Cntr=0.3,0.1

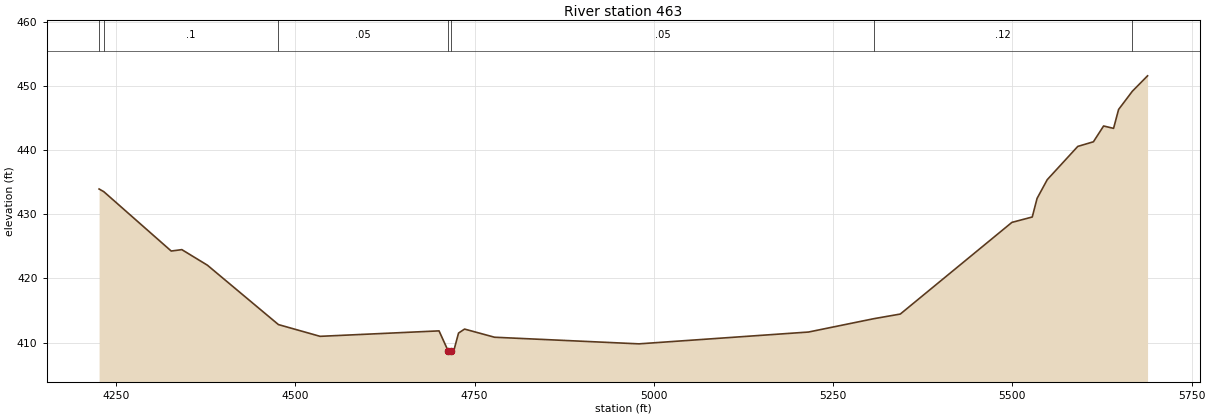
Type RM Length L Ch R = 1,463,0,0,0
BEGIN DESCRIPTION:
Clear Creek T 7 1.0
END DESCRIPTION:
XS GIS Cut Line= 3
      2767398.38      6799907.98      2768013.05      6800348.02
      2768541.49      6799879.46
#Sta/Elev= 30
  4226.3  433.93  4232.9  433.51  4326.9  424.27  4341.7  424.49  4377.3  422.07
  4476.4  412.82  4534.5  410.99  4700.4  411.84  4713.1  408.72  4713.4  408.22
  4717.1  408.72  4721.3  408.88  4727.6  411.50  4736.0  412.12  4777.8  410.85
  4979.2  409.82  5215.7  411.66  5306.9  413.74  5343.7  414.46  5499.3  428.73
  5527.7  429.57  5534.4  432.46  5548.6  435.38  5591.2  440.56  5613.0  441.28
  5627.2  443.74  5641.1  443.37  5648.1  446.31  5667.3  449.15  5688.5  451.55
#Mann=7,-1,0
  4226.3    0.12       0  4232.9     0.1       0  4476.4    0.05       0
  4713.1    0.05       0  4717.1    0.05       0  5306.9    0.12       0
  5667.3    0.05       0
Bank Sta=4713.1,4717.1
Exp/Cntr=0.3,0.1

Chan Stop Cuts=-1