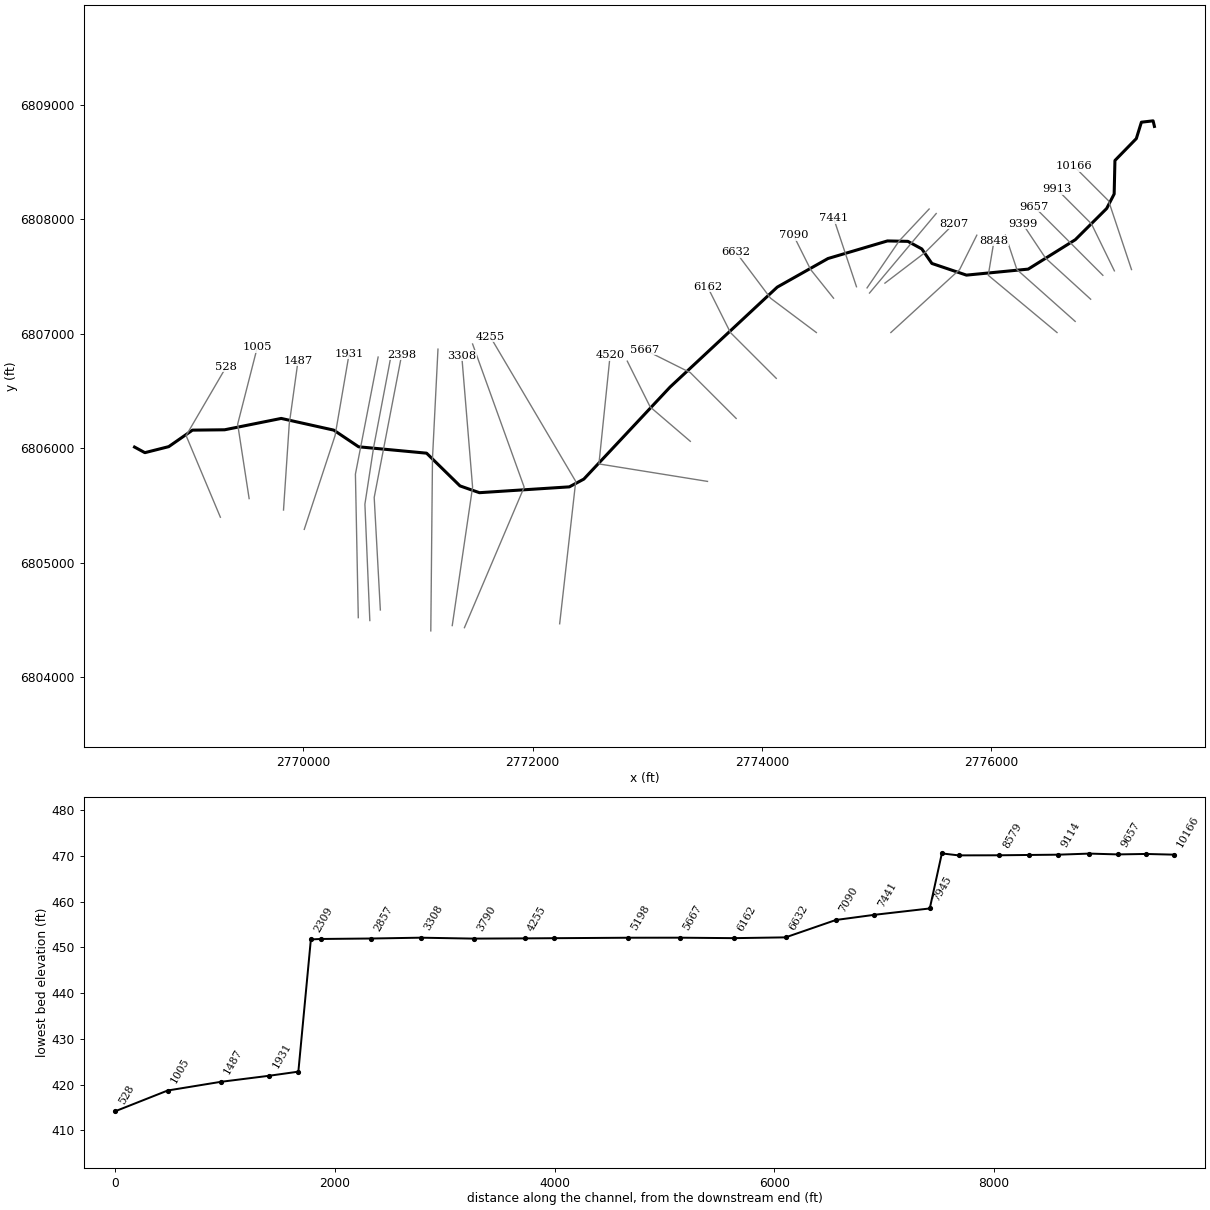
--- Clear Creek T 8.prj (project) ---

Proj Title=Clear Creek T 8 Base Level Engineering
Current Plan=p01
Default Exp/Contr=0.3,0.1
English Units
Geom File=g01
Flow File=f01
Plan File=p01
BEGIN DESCRIPTION:
Clear Creek T 8
END DESCRIPTION:

--- Clear Creek T 8.p01 (plan) ---

Plan Title=Multiple Run
Short Identifier=Multiple
Geom File=g01
Flow File=f01
Subcritical Flow
K Sum by GR= 0
Std Step Tol= 0.01
Critical Tol= 0.01
Num of Std Step Trials= 20
Max Error Tol= 0.3
Flow Tol Ratio= 0.001
Split Flow NTrial= 30
Split Flow Tol= 0.02
Split Flow Ratio= 0.02
Log Output Level= 0
Friction Slope Method= 1
Unsteady Friction Slope Method= 2
Unsteady Bridges Friction Slope Method= 1
Parabolic Critical Depth
Global Vel Dist=  1 , 1 , 1
Global Log Level= 0
CheckData=True
Encroach Param= -1, 0, 0, 0
BEGIN DESCRIPTION:
Multiple Run
END DESCRIPTION:

--- Clear Creek T 8.f01 (steady flow) ---

Flow Title=Multiple
Number of Profiles=7
Profile Names=10-year,25-year,50-year,1pct_min,100-year,1pct_plu,500-year
River Rch & RM= Clear Creek T 8,Reach-1,10166
     318     415     492     291     580    1158     808
River Rch & RM= Clear Creek T 8,Reach-1,8207
     655     895    1094     666    1328    2650    1960
River Rch & RM= Clear Creek T 8,Reach-1,6632
     774    1063    1303     794    1584    3160    2346
River Rch & RM= Clear Creek T 8,Reach-1,4255
    1094    1528    1895    1166    2327    4642    3518
Boundary for River Rch & Prof#=Clear Creek T 8,Reach-1,1
Up Type=0
Dn Type=3
Dn Slope=0.005
Boundary for River Rch & Prof#=Clear Creek T 8,Reach-1,2
Up Type=0
Dn Type=3
Dn Slope=0.005
Boundary for River Rch & Prof#=Clear Creek T 8,Reach-1,3
Up Type=0
Dn Type=3
Dn Slope=0.005
Boundary for River Rch & Prof#=Clear Creek T 8,Reach-1,4
Up Type=0
Dn Type=3
Dn Slope=0.005
Boundary for River Rch & Prof#=Clear Creek T 8,Reach-1,5
Up Type=0
Dn Type=3
Dn Slope=0.005
Boundary for River Rch & Prof#=Clear Creek T 8,Reach-1,6
Up Type=0
Dn Type=3
Dn Slope=0.005
Boundary for River Rch & Prof#=Clear Creek T 8,Reach-1,7
Up Type=0
Dn Type=3
Dn Slope=0.005

--- Clear Creek T 8.g01 (geometry) ---

Geom Title=Existing Conditions

River Reach=Clear Creek T 8,Reach-1
Reach XY= 30
      2777426.00      6808811.00      2777414.49      6808859.74
      2777312.29      6808847.85      2777268.14      6808704.83
      2777081.46      6808513.45      2777074.64      6808220.65
      2777009.36      6808094.32      2776735.68      6807821.78
      2776324.44      6807564.76      2775785.66      6807512.38
      2775484.05      6807614.32      2775396.13      6807741.23
      2775274.45      6807807.25      2775096.03      6807810.93
      2774577.50      6807657.38      2774134.48      6807407.49
      2773199.18      6806534.70      2772446.92      6805731.14
      2772320.48      6805663.34      2771535.66      6805612.38
      2771366.21      6805671.52      2771074.54      6805957.46
      2770481.45      6806013.18      2770264.67      6806158.70
      2769805.97      6806260.93      2769312.08      6806161.68
      2769031.52      6806158.65      2768824.53      6806014.55
      2768616.21      6805961.85      2768526.00      6806011.00

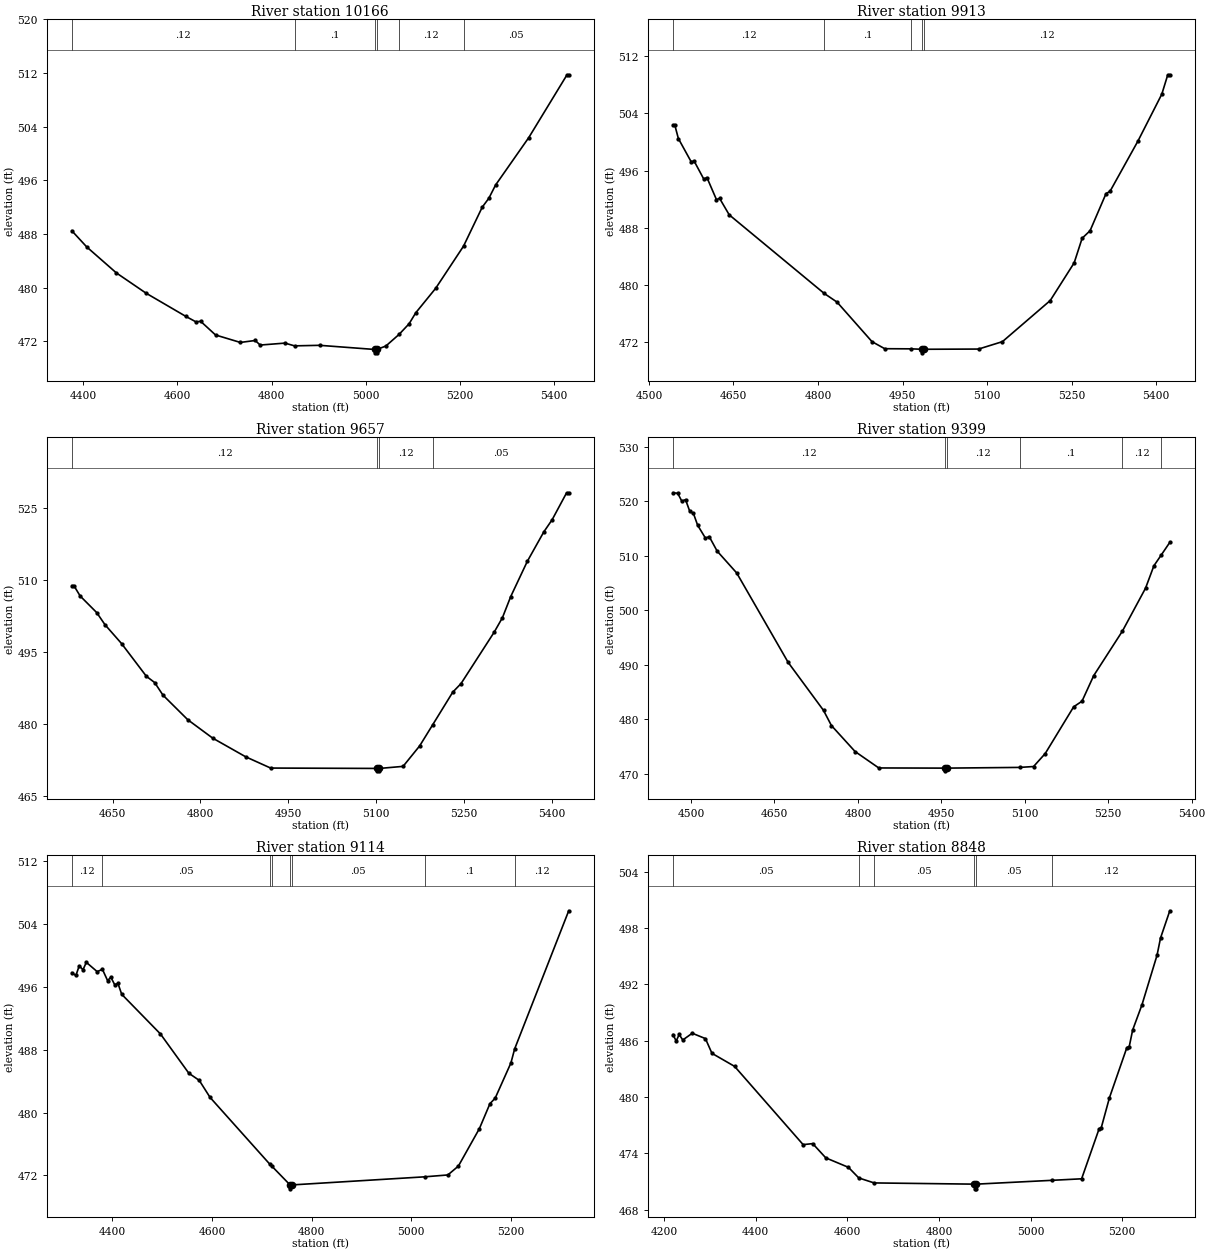
Type RM Length L Ch R = 1,10166,253,253,253
BEGIN DESCRIPTION:
Clear Creek T 8 25.0
END DESCRIPTION:
XS GIS Cut Line= 3
      2777226.01      6807560.97      2777026.00      6808161.00
      2776725.97      6808461.03
#Sta/Elev= 30
  4375.3  488.48  4407.0  486.07  4470.2  482.19  4533.4  479.17  4617.8  475.72
  4638.9  474.92  4649.4  474.98  4681.0  472.95  4733.7  471.84  4765.3  472.13
  4775.9  471.45  4828.6  471.74  4848.9  471.33  4902.4  471.41  5019.9  470.79
  5020.2  470.29  5023.7  470.29  5023.9  470.79  5043.1  471.30  5071.2  473.03
  5092.6  474.62  5106.8  476.26  5149.2  479.91  5208.4  486.19  5248.2  492.00
  5262.3  493.33  5276.5  495.29  5347.2  502.37  5428.5  511.72  5432.1  511.72
#Mann=6,-1,0
  4375.3    0.12       0  4848.9     0.1       0  5019.9    0.07       0
  5023.9     0.1       0  5071.2    0.12       0  5208.4    0.05       0
Bank Sta=5019.9,5023.9
Exp/Cntr=0.3,0.1

Type RM Length L Ch R = 1,9913,256,256,256
BEGIN DESCRIPTION:
Clear Creek T 8 24.0
END DESCRIPTION:
XS GIS Cut Line= 3
      2777076.51      6807549.78      2776876.00      6807961.00
      2776575.98      6808261.02
#Sta/Elev= 30
  4542.5  502.32  4546.0  502.32  4552.2  500.48  4574.8  497.24  4580.3  497.30
  4597.3  494.80  4602.9  495.01  4619.8  491.92  4625.4  492.09  4642.4  489.79
  4810.8  478.78  4833.8  477.55  4895.8  472.01  4918.4  471.02  4965.4  471.00
  4984.0  470.94  4984.2  470.44  4988.0  470.94  5084.9  470.97  5127.3  472.01
  5212.1  477.77  5254.6  483.06  5268.7  486.50  5282.8  487.56  5311.1  492.76
  5318.2  493.08  5367.7  500.12  5410.1  506.70  5420.7  509.42  5424.3  509.42
#Mann=5,-1,0
  4542.5    0.12       0  4810.8     0.1       0  4965.4    0.12       0
  4984.0    0.07       0  4988.0    0.12       0
Bank Sta=4984,4988
Exp/Cntr=0.3,0.1

Type RM Length L Ch R = 1,9657,258,258,258
BEGIN DESCRIPTION:
Clear Creek T 8 23.0
END DESCRIPTION:
XS GIS Cut Line= 3
      2776976.03      6807510.97      2776676.00      6807811.00
      2776375.98      6808111.02
#Sta/Elev= 30
  4580.5  508.91  4584.1  508.91  4594.7  506.77  4623.0  503.31  4637.1  500.79
  4665.4  496.86  4707.8  490.04  4722.0  488.73  4736.1  486.12  4778.5  480.99
  4821.0  477.16  4877.5  473.26  4920.0  470.92  5101.8  470.84  5102.1  470.34
  5105.6  470.34  5105.8  470.84  5146.2  471.27  5174.5  475.53  5196.7  479.92
  5231.1  486.74  5245.2  488.52  5301.8  499.23  5315.9  502.25  5330.1  506.66
  5358.4  513.99  5386.6  520.13  5400.8  522.66  5425.5  528.27  5429.1  528.27
#Mann=4,-1,0
  4580.5    0.12       0  5101.8    0.07       0  5105.8    0.12       0
  5196.7    0.05       0
Bank Sta=5101.8,5105.8
Exp/Cntr=0.3,0.1

Type RM Length L Ch R = 1,9399,285,285,285
BEGIN DESCRIPTION:
Clear Creek T 8 22.0
END DESCRIPTION:
XS GIS Cut Line= 3
      2776869.43      6807302.15      2776476.00      6807661.00
      2776275.98      6807961.04
#Sta/Elev= 30
  4467.5  521.59  4476.1  521.50  4483.5  520.05  4490.2  520.33  4497.7  518.21
  4504.4  517.80  4511.9  515.64  4526.0  513.26  4532.8  513.54  4547.0  510.88
  4582.1  506.87  4674.7  490.43  4738.2  481.62  4752.4  478.84  4794.9  474.07
  4837.5  471.05  4955.8  471.02  4956.0  470.52  4959.8  471.02  5090.5  471.15
  5115.7  471.31  5136.7  473.70  5187.8  482.28  5202.8  483.31  5223.8  488.00
  5275.5  496.20  5317.0  504.07  5332.0  508.18  5344.8  510.10  5360.6  512.48
#Mann=6,-1,0
  4467.5    0.12       0  4955.8    0.07       0  4959.8    0.12       0
  5090.5     0.1       0  5275.5    0.12       0  5344.8    0.05       0
Bank Sta=4955.8,4959.8
Exp/Cntr=0.3,0.1

Type RM Length L Ch R = 1,9114,266,266,266
BEGIN DESCRIPTION:
Clear Creek T 8 21.0
END DESCRIPTION:
XS GIS Cut Line= 3
      2776734.54      6807108.29      2776226.00      6807561.00
      2776125.99      6807861.02
#Sta/Elev= 30
  4318.8  497.81  4327.0  497.47  4333.7  498.70  4341.2  498.19  4347.9  499.14
  4369.6  497.96  4380.2  498.25  4390.5  496.82  4397.2  497.24  4404.7  496.30
  4411.4  496.45  4418.9  495.07  4496.7  490.01  4553.6  485.01  4574.5  484.10
  4596.2  481.93  4715.8  473.44  4720.0  473.18  4756.7  470.78  4756.9  470.28
  4760.7  470.78  5026.6  471.81  5073.4  472.05  5094.5  473.18  5136.7  477.96
  5157.8  481.13  5168.3  481.83  5199.9  486.32  5207.4  488.11  5315.9  505.71
#Mann=8,-1,0
  4318.8    0.12       0  4380.2    0.05       0  4715.8    0.12       0
  4720.0    0.05       0  4756.7    0.03       0  4760.7    0.05       0
  5026.6     0.1       0  5207.4    0.12       0
Bank Sta=4756.7,4760.7
Exp/Cntr=0.3,0.1

Type RM Length L Ch R = 1,8848,269,269,269
BEGIN DESCRIPTION:
Clear Creek T 8 20.0
END DESCRIPTION:
XS GIS Cut Line= 3
      2776576.01      6807010.99      2775976.00      6807511.00
      2776026.00      6807811.02
#Sta/Elev= 30
  4219.0  486.66  4226.2  485.97  4232.7  486.67  4240.5  486.08  4261.3  486.80
  4290.0  486.23  4304.3  484.66  4353.7  483.27  4503.4  474.93  4524.3  475.04
  4552.9  473.52  4602.4  472.51  4625.0  471.38  4658.5  470.85  4877.6  470.72
  4877.9  470.22  4881.4  470.22  4881.6  470.72  5047.8  471.13  5111.6  471.29
  5149.6  476.59  5154.6  476.75  5172.4  479.93  5210.4  485.27  5215.5  485.36
  5223.1  487.15  5243.4  489.83  5276.3  495.11  5283.9  496.94  5304.2  499.85
#Mann=6,-1,0
  4219.0    0.05       0  4625.0    0.12       0  4658.5    0.05       0
  4877.6    0.03       0  4881.6    0.05       0  5047.8    0.12       0
Bank Sta=4877.6,4881.6
Exp/Cntr=0.3,0.1

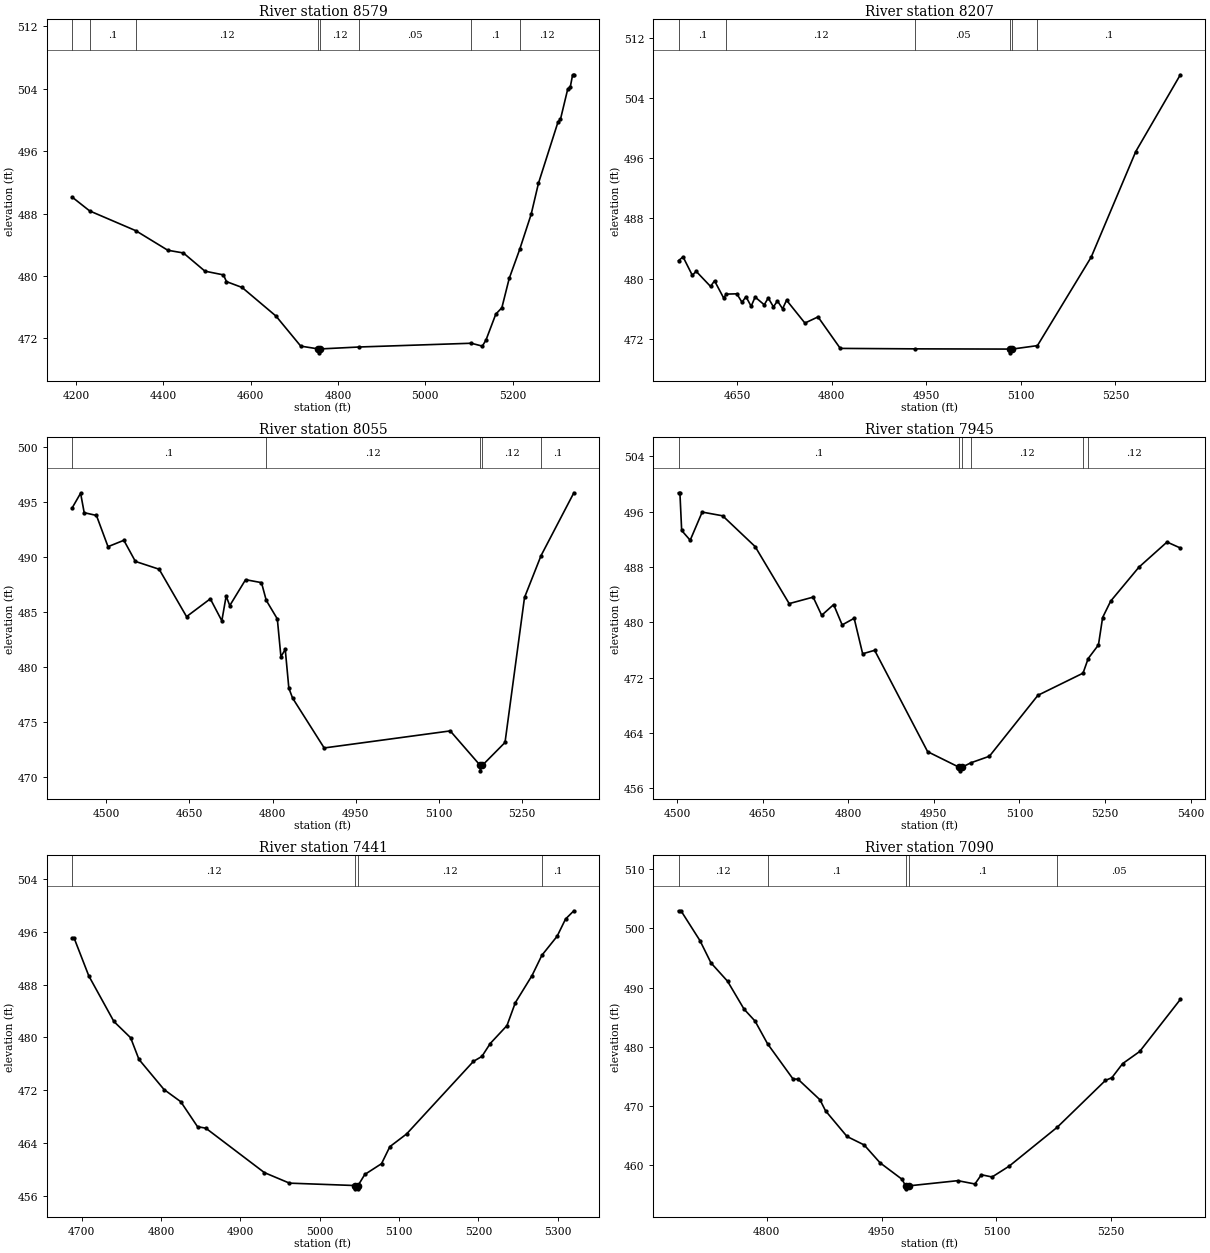
Type RM Length L Ch R = 1,8579,372,372,372
BEGIN DESCRIPTION:
Clear Creek T 8 19.0
END DESCRIPTION:
XS GIS Cut Line= 3
      2775126.01      6807011.01      2775726.00      6807561.00
      2775875.98      6807860.96
#Sta/Elev= 30
  4190.8  490.12  4231.1  488.34  4336.6  485.81  4410.0  483.30  4445.8  482.95
  4495.1  480.62  4537.6  480.14  4544.4  479.28  4580.2  478.53  4657.9  474.86
  4714.6  471.01  4755.2  470.65  4755.4  470.15  4759.2  470.65  4848.9  470.90
  5105.3  471.38  5130.5  471.01  5138.9  471.80  5161.3  475.11  5175.2  475.93
  5192.0  479.68  5216.1  483.42  5242.3  487.91  5259.1  491.90  5303.8  499.74
  5309.4  500.08  5326.2  503.99  5331.8  504.20  5337.3  505.79  5340.1  505.79
#Mann=8,-1,0
  4190.8    0.12       0  4231.1     0.1       0  4336.6    0.12       0
  4755.2    0.03       0  4759.2    0.12       0  4848.9    0.05       0
  5105.3     0.1       0  5216.1    0.12       0
Bank Sta=4755.2,4759.2
Exp/Cntr=0.3,0.1

Type RM Length L Ch R = 1,8207,152,152,152
BEGIN DESCRIPTION:
Clear Creek T 8 18.0
END DESCRIPTION:
XS GIS Cut Line= 3
      2775074.27      6807442.37      2775426.00      6807711.00
      2775675.97      6807960.97
#Sta/Elev= 30
  4557.0  482.40  4564.2  482.89  4578.8  480.45  4585.0  480.97  4607.8  478.96
  4614.1  479.71  4628.6  477.42  4632.8  477.94  4649.5  477.98  4657.7  476.85
  4664.0  477.60  4672.2  476.32  4678.5  477.55  4693.0  476.52  4699.3  477.43
  4707.6  476.24  4713.9  477.04  4722.1  475.99  4728.4  477.13  4757.5  474.09
  4778.3  474.91  4813.6  470.72  4932.6  470.66  5082.4  470.63  5082.7  470.13
  5086.4  470.63  5126.4  471.09  5211.7  482.86  5282.4  496.90  5353.1  507.11
#Mann=6,-1,0
  4557.0     0.1       0  4632.8    0.12       0  4932.6    0.05       0
  5082.4    0.03       0  5086.4    0.05       0  5126.4     0.1       0
Bank Sta=5082.4,5086.4
Exp/Cntr=0.3,0.1

Type RM Length L Ch R = 1,8055,110,110,110
BEGIN DESCRIPTION:
Mapping XS 5f0a4970
END DESCRIPTION:
XS GIS Cut Line= 2
      2774939.66      6807355.90      2775521.73      6808050.19
#Sta/Elev= 30
  4438.1  494.45  4453.5  495.80  4460.0  494.03  4482.1  493.78  4503.0  490.94
  4531.6  491.52  4552.4  489.60  4595.3  488.89  4644.8  484.58  4687.7  486.20
  4708.5  484.20  4716.3  486.45  4722.8  485.58  4751.4  487.94  4780.1  487.67
  4788.7  486.06  4808.7  484.37  4815.2  480.93  4823.0  481.60  4829.5  478.08
  4836.2  477.18  4893.3  472.64  5120.9  474.19  5174.9  471.06  5175.1  470.56
  5178.9  471.06  5219.8  473.14  5255.0  486.32  5284.9  490.13  5344.1  495.84
#Mann=5,-1,0
  4438.1     0.1       0  4788.7    0.12       0  5174.9    0.07       0
  5178.9    0.12       0  5284.9     0.1       0
Bank Sta=5174.9,5178.9
Exp/Cntr=0.3,0.1

Type RM Length L Ch R = 1,7945,504,504,504
BEGIN DESCRIPTION:
Clear Creek T 8 17.0
END DESCRIPTION:
XS GIS Cut Line= 3
      2774918.33      6807400.79      2775198.79      6807811.21
      2775460.02      6808089.65
#Sta/Elev= 30
  4502.9  498.72  4505.3  498.72  4508.4  493.27  4523.3  491.86  4544.3  495.93
  4580.2  495.39  4637.1  490.94  4696.7  482.70  4738.7  483.64  4753.6  481.01
  4774.6  482.56  4789.5  479.62  4810.5  480.58  4825.4  475.45  4846.4  475.95
  4939.2  461.30  4994.8  459.03  4995.1  458.53  4998.8  459.03  5014.9  459.69
  5047.4  460.64  5132.4  469.45  5211.4  472.65  5220.4  474.76  5238.4  476.73
  5245.7  480.69  5259.8  483.06  5309.2  487.96  5358.5  491.60  5381.8  490.74
#Mann=6,-1,0
  4502.9     0.1       0  4994.8    0.07       0  4998.8     0.1       0
  5014.9    0.12       0  5211.4     0.1       0  5220.4    0.12       0
Bank Sta=4994.8,4998.8
Exp/Cntr=0.3,0.1

Type RM Length L Ch R = 1,7441,351,351,351
BEGIN DESCRIPTION:
Clear Creek T 8 16.0
END DESCRIPTION:
XS GIS Cut Line= 3
      2774825.99      6807411.02      2774726.00      6807711.00
      2774626.01      6808010.97
#Sta/Elev= 30
  4688.0  495.01  4690.6  495.01  4709.1  489.30  4740.7  482.42  4761.8  479.96
  4772.3  476.69  4803.9  472.14  4825.0  470.30  4846.1  466.53  4856.6  466.30
  4930.4  459.59  4962.0  458.00  5044.4  457.64  5044.6  457.14  5048.1  457.14
  5048.4  457.64  5056.9  459.31  5078.0  460.94  5088.5  463.51  5109.6  465.43
  5193.9  476.40  5204.5  477.14  5215.0  479.09  5236.1  481.80  5246.6  485.25
  5267.7  489.36  5280.1  492.42  5299.3  495.29  5309.9  497.89  5320.4  499.14
#Mann=4,-1,0
  4688.0    0.12       0  5044.4    0.07       0  5048.4    0.12       0
  5280.1     0.1       0
Bank Sta=5044.4,5048.4
Exp/Cntr=0.3,0.1

Type RM Length L Ch R = 1,7090,458,458,458
BEGIN DESCRIPTION:
Clear Creek T 8 15.0
END DESCRIPTION:
XS GIS Cut Line= 3
      2774625.97      6807311.04      2774426.00      6807561.00
      2774276.01      6807860.98
#Sta/Elev= 30
  4684.7  502.96  4687.9  502.96  4712.7  497.92  4727.1  494.16  4748.7  491.07
  4770.3  486.35  4784.7  484.33  4801.0  480.50  4834.3  474.55  4840.7  474.53
  4869.5  471.04  4876.7  469.19  4904.8  464.85  4927.2  463.42  4948.0  460.40
  4976.8  457.61  4981.2  456.51  4981.4  456.01  4985.2  456.51  5049.5  457.39
  5071.9  456.83  5080.3  458.39  5094.3  458.01  5116.6  459.84  5179.5  466.42
  5242.4  474.32  5250.8  474.78  5264.8  477.15  5287.1  479.20  5340.2  487.99
#Mann=5,-1,0
  4684.7    0.12       0  4801.0     0.1       0  4981.2    0.07       0
  4985.2     0.1       0  5179.5    0.05       0
Bank Sta=4981.2,4985.2
Exp/Cntr=0.3,0.1

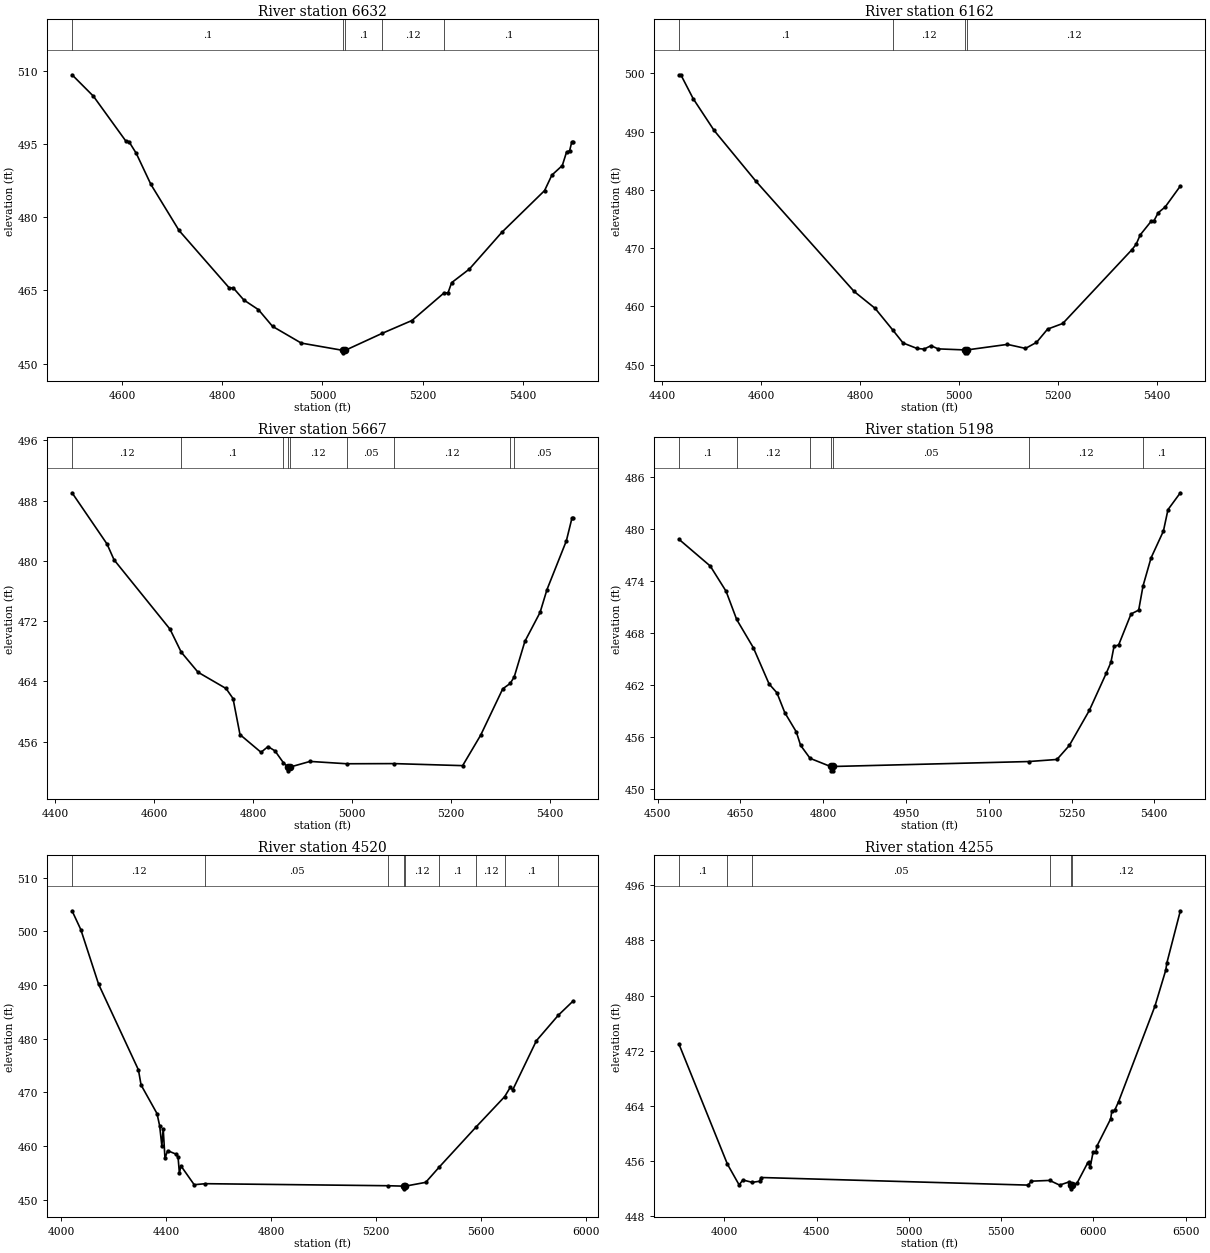
Type RM Length L Ch R = 1,6632,470,470,470
BEGIN DESCRIPTION:
Clear Creek T 8 14.0
END DESCRIPTION:
XS GIS Cut Line= 3
      2774476.00      6807011.00      2774076.00      6807311.00
      2773776.00      6807711.00
#Sta/Elev= 30
  4500.4  509.23  4543.1  504.83  4607.7  495.64  4613.9  495.53  4628.5  493.12
  4657.7  486.75  4713.9  477.30  4813.9  465.54  4822.3  465.50  4843.1  463.05
  4872.3  461.06  4900.4  457.64  4957.7  454.21  5041.1  452.71  5041.4  452.21
  5045.1  452.71  5118.7  456.19  5178.5  458.84  5242.9  464.53  5250.4  464.49
  5257.7  466.60  5293.1  469.39  5357.7  476.91  5443.1  485.48  5457.7  488.66
  5478.5  490.62  5486.9  493.36  5493.1  493.66  5497.3  495.43  5500.4  495.43
#Mann=5,-1,0
  4500.4     0.1       0  5041.1    0.07       0  5045.1     0.1       0
  5118.7    0.12       0  5242.9     0.1       0
Bank Sta=5041.1,5045.1
Exp/Cntr=0.3,0.1

Type RM Length L Ch R = 1,6162,495,495,495
BEGIN DESCRIPTION:
Clear Creek T 8 13.0
END DESCRIPTION:
XS GIS Cut Line= 3
      2774126.01      6806610.99      2773726.00      6807011.00
      2773526.00      6807410.99
#Sta/Elev= 30
  4434.3  499.76  4437.8  499.76  4462.6  495.68  4505.0  490.21  4589.9  481.45
  4787.9  462.58  4830.3  459.68  4866.8  455.88  4886.9  453.73  4915.1  452.79
  4929.3  452.68  4943.4  453.27  4957.6  452.72  5011.9  452.54  5012.2  452.04
  5015.7  452.04  5016.0  452.54  5097.8  453.49  5134.2  452.80  5156.5  453.83
  5178.9  456.11  5209.6  457.08  5349.4  469.75  5357.8  470.66  5366.1  472.28
  5388.5  474.65  5394.1  474.74  5402.5  476.09  5416.5  477.07  5447.2  480.67
#Mann=4,-1,0
  4434.3     0.1       0  4866.8    0.12       0  5011.9    0.07       0
  5016.0    0.12       0
Bank Sta=5011.9,5016
Exp/Cntr=0.3,0.1

Type RM Length L Ch R = 1,5667,469,469,469
BEGIN DESCRIPTION:
Clear Creek T 8 12.0
END DESCRIPTION:
XS GIS Cut Line= 3
      2773776.02      6806260.98      2773376.00      6806661.00
      2772976.02      6806860.99
#Sta/Elev= 30
  4434.3  489.05  4505.0  482.25  4519.2  480.15  4632.3  470.94  4654.9  467.90
  4688.9  465.23  4745.5  463.07  4759.6  461.74  4773.7  456.95  4816.2  454.60
  4830.3  455.36  4844.4  454.79  4861.6  453.20  4870.7  452.64  4871.0  452.14
  4874.8  452.64  4915.2  453.39  4989.6  453.08  5085.2  453.10  5223.6  452.83
  5260.0  456.87  5304.7  463.03  5319.7  463.74  5327.8  464.60  5349.4  469.33
  5380.1  473.17  5394.1  476.21  5433.2  482.67  5444.4  485.66  5447.2  485.66
#Mann=9,-1,0
  4434.3    0.12       0  4654.9     0.1       0  4861.6    0.12       0
  4870.7    0.03       0  4874.8    0.12       0  4989.6    0.05       0
  5085.2    0.12       0  5319.7     0.1       0  5327.8    0.05       0
Bank Sta=4870.7,4874.8
Exp/Cntr=0.3,0.1

Type RM Length L Ch R = 1,5198,678,678,678
BEGIN DESCRIPTION:
Clear Creek T 8 11.0
END DESCRIPTION:
XS GIS Cut Line= 3
      2773376.01      6806060.99      2773026.00      6806361.00
      2772826.00      6806761.00
#Sta/Elev= 30
  4539.0  478.78  4595.5  475.71  4624.1  472.81  4643.3  469.56  4673.5  466.31
  4702.0  462.14  4716.3  461.11  4730.5  458.83  4751.4  456.61  4759.1  455.07
  4776.3  453.57  4813.4  452.63  4813.8  452.13  4817.4  452.13  4817.7  452.63
  5172.2  453.20  5223.6  453.44  5246.0  455.05  5282.3  459.09  5313.0  463.38
  5321.4  464.62  5327.0  466.46  5335.4  466.63  5357.8  470.19  5371.7  470.64
  5379.6  473.43  5394.1  476.65  5416.5  479.74  5424.8  482.21  5447.2  484.15
#Mann=7,-1,0
  4539.0     0.1       0  4643.3    0.12       0  4776.3    0.05       0
  4813.4    0.03       0  4817.7    0.05       0  5172.2    0.12       0
  5379.6     0.1       0
Bank Sta=4813.4,4817.7
Exp/Cntr=0.3,0.1

Type RM Length L Ch R = 1,4520,265,265,265
BEGIN DESCRIPTION:
Clear Creek T 8 10.0
END DESCRIPTION:
XS GIS Cut Line= 3
      2773525.99      6805711.00      2772578.60      6805863.58
      2772676.00      6806810.99
#Sta/Elev= 30
  4040.4  503.86  4073.8  500.36  4141.7  490.17  4293.6  474.21  4303.7  471.39
  4364.5  466.06  4374.6  463.78  4383.0  460.03  4388.1  463.24  4394.9  457.72
  4405.0  459.15  4435.4  458.53  4444.8  457.96  4449.9  454.95  4455.7  456.32
  4506.3  452.80  4549.4  452.99  5245.1  452.61  5306.6  452.53  5307.2  452.03
  5311.5  452.53  5389.5  453.24  5442.0  456.14  5582.9  463.63  5690.7  469.22
  5712.1  470.96  5721.2  470.46  5811.7  479.64  5895.1  484.38  5952.4  487.07
#Mann=9,-1,0
  4040.4    0.12       0  4549.4    0.05       0  5245.1    0.12       0
  5306.6    0.03       0  5311.5    0.12       0  5442.0     0.1       0
  5582.9    0.12       0  5690.7     0.1       0  5895.1    0.05       0
Bank Sta=5306.6,5311.5
Exp/Cntr=0.3,0.1

Type RM Length L Ch R = 1,4255,465,465,465
BEGIN DESCRIPTION:
Clear Creek T 8 9.0
END DESCRIPTION:
XS GIS Cut Line= 3
      2772235.90      6804467.62      2772376.00      6805711.00
      2771630.61      6806973.88
#Sta/Elev= 30
  3754.0  472.91  4015.9  455.57  4079.4  452.56  4099.6  453.27  4150.9  452.93
  4190.1  453.09  4200.2  453.63  5647.2  452.53  5662.8  453.10  5763.2  453.21
  5817.0  452.53  5865.7  452.97  5878.3  452.49  5879.3  451.99  5884.4  452.49
  5911.0  452.79  5969.0  455.74  5977.0  455.83  5982.8  455.13  5998.4  457.28
  6014.1  457.38  6019.9  458.21  6094.0  462.13  6099.9  463.22  6115.5  463.36
  6136.9  464.63  6334.0  478.47  6392.6  483.68  6398.7  484.74  6471.7  492.28
#Mann=6,-1,0
  3754.0     0.1       0  4015.9    0.12       0  4150.9    0.05       0
  5763.2    0.12       0  5878.3    0.03       0  5884.4    0.12       0
Bank Sta=5878.3,5884.4
Exp/Cntr=0.3,0.1

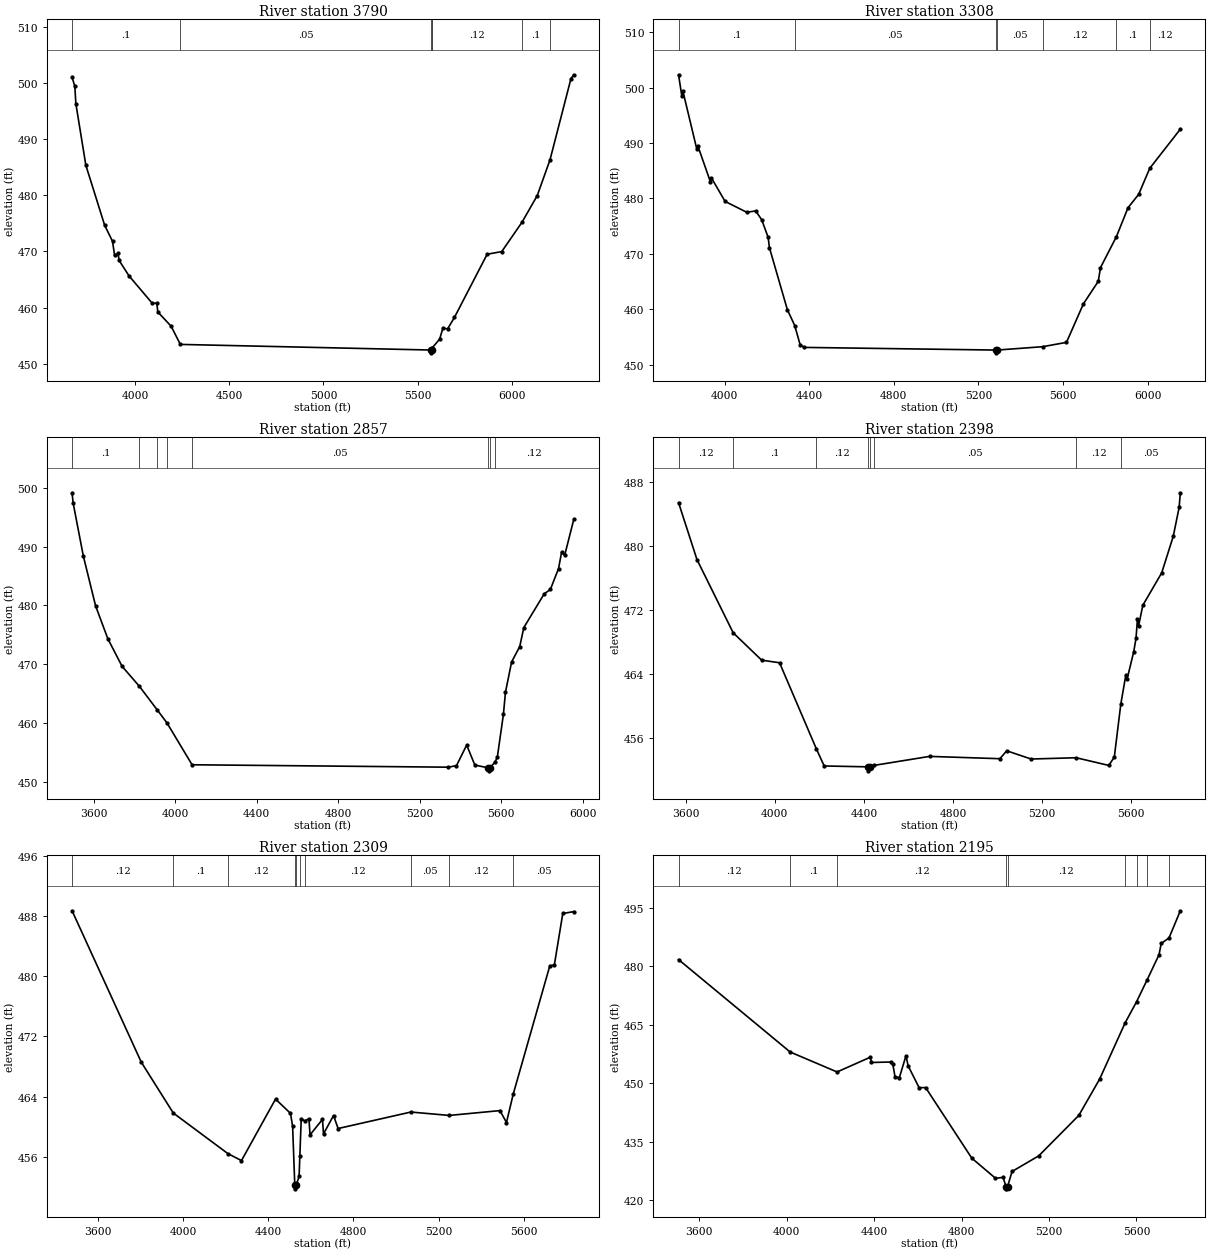
Type RM Length L Ch R = 1,3790,482,482,482
BEGIN DESCRIPTION:
Clear Creek T 8 8.0
END DESCRIPTION:
XS GIS Cut Line= 3
      2771404.79      6804433.60      2771926.00      6805661.00
      2771476.00      6806910.99
#Sta/Elev= 30
  3666.5  500.99  3681.2  499.36  3686.6  496.30  3739.7  485.31  3839.4  474.64
  3881.0  471.80  3892.2  469.29  3910.4  469.64  3915.8  468.40  3968.6  465.64
  4092.3  460.74  4115.9  460.79  4121.4  459.22  4192.3  456.66  4240.9  453.44
  5569.1  452.44  5570.1  451.94  5575.2  452.44  5576.8  452.82  5616.4  454.38
  5633.5  456.30  5658.9  456.22  5694.9  458.24  5868.5  469.49  5945.9  469.96
  6053.5  475.19  6134.3  479.93  6202.2  486.32  6313.2  500.76  6328.5  501.43
#Mann=7,-1,0
  3666.5     0.1       0  4240.9    0.05       0  5569.1    0.03       0
  5575.2    0.05       0  5576.8    0.12       0  6053.5     0.1       0
  6202.2    0.12       0
Bank Sta=5569.1,5575.2
Exp/Cntr=0.3,0.1

Type RM Length L Ch R = 1,3308,451,451,451
BEGIN DESCRIPTION:
Clear Creek T 8 7.0
END DESCRIPTION:
XS GIS Cut Line= 3
      2771298.45      6804451.78      2771476.00      6805661.00
      2771381.45      6806807.52
#Sta/Elev= 30
  3782.2  502.30  3798.1  498.39  3803.2  499.29  3867.9  488.99  3873.0  489.52
  3932.7  483.01  3937.7  483.70  4002.5  479.45  4104.8  477.50  4147.1  477.74
  4175.6  476.14  4205.9  472.97  4211.9  471.12  4296.9  459.91  4331.6  457.06
  4357.5  453.55  4377.7  453.12  5282.2  452.64  5283.2  452.14  5288.4  452.64
  5504.3  453.25  5616.5  454.03  5696.7  460.99  5767.0  465.05  5777.0  467.49
  5852.5  473.09  5907.4  478.31  5957.6  480.72  6010.1  485.42  6154.8  492.49
#Mann=7,-1,0
  3782.2     0.1       0  4331.6    0.05       0  5282.2    0.03       0
  5288.4    0.05       0  5504.3    0.12       0  5852.5     0.1       0
  6010.1    0.12       0
Bank Sta=5282.2,5288.4
Exp/Cntr=0.3,0.1

Type RM Length L Ch R = 1,2857,459,459,459
BEGIN DESCRIPTION:
Clear Creek T 8 6.0
END DESCRIPTION:
XS GIS Cut Line= 3
      2771111.33      6804405.62      2771126.00      6805911.00
      2771173.99      6806866.14
#Sta/Elev= 30
  3494.2  499.11  3499.6  497.34  3549.6  488.36  3609.6  479.94  3669.6  474.36
  3739.6  469.68  3824.3  466.30  3911.8  462.30  3959.8  460.09  4083.0  452.99
  5340.1  452.58  5380.1  452.84  5430.2  456.33  5470.2  452.94  5537.2  452.46
  5538.2  451.96  5543.5  452.46  5568.4  453.41  5580.4  454.25  5610.4  461.53
  5620.4  465.28  5650.5  470.42  5690.5  473.04  5710.6  476.26  5810.7  481.98
  5840.7  482.71  5880.8  486.26  5896.1  489.08  5910.8  488.49  5956.0  494.65
#Mann=8,-1,0
  3494.2     0.1       0  3824.3    0.12       0  3911.8     0.1       0
  3959.8    0.12       0  4083.0    0.05       0  5537.2    0.03       0
  5543.5    0.05       0  5568.4    0.12       0
Bank Sta=5537.2,5543.5
Exp/Cntr=0.3,0.1

Type RM Length L Ch R = 1,2398,89,89,89
BEGIN DESCRIPTION:
Mapping XS 97cf15ed
END DESCRIPTION:
XS GIS Cut Line= 3
      2770671.09      6804588.29      2770617.39      6805570.62
      2770857.14      6806816.26
#Sta/Elev= 30
  3567.7  485.46  3650.5  478.32  3813.0  469.15  3941.0  465.72  4021.1  465.40
  4186.7  454.59  4221.4  452.47  4418.4  452.36  4419.5  451.86  4424.9  452.36
  4444.8  452.54  4694.4  453.67  5010.1  453.38  5040.7  454.37  5150.1  453.34
  5352.5  453.50  5498.9  452.54  5523.7  453.58  5552.9  460.23  5575.6  463.89
  5580.7  463.31  5611.0  466.80  5621.2  468.48  5627.5  470.85  5632.6  470.01
  5651.7  472.60  5736.4  476.66  5788.3  481.24  5814.6  484.85  5820.0  486.69
#Mann=8,-1,0
  3567.7    0.12       0  3813.0     0.1       0  4186.7    0.12       0
  4418.4    0.03       0  4424.9    0.12       0  4444.8    0.05       0
  5352.5    0.12       0  5552.9    0.05       0
Bank Sta=4418.4,4424.9
Exp/Cntr=0.3,0.1

Type RM Length L Ch R = 1,2309,114,114,114
BEGIN DESCRIPTION:
Clear Creek T 8 5.0
END DESCRIPTION:
XS GIS Cut Line= 4
      2770579.24      6804495.89      2770536.30      6805511.78
      2770612.76      6806010.96      2770768.93      6806832.04
#Sta/Elev= 30
  3478.2  488.69  3803.6  468.57  3953.7  461.83  4209.7  456.45  4274.0  455.51
  4434.2  463.68  4504.3  461.79  4514.4  460.07  4524.6  452.26  4525.6  451.76
  4531.1  452.26  4544.8  453.40  4548.3  456.06  4554.9  461.08  4571.0  460.79
  4591.2  461.06  4596.3  458.93  4654.6  460.98  4659.6  459.06  4706.7  461.50
  4728.1  459.77  5070.1  461.96  5250.1  461.51  5488.6  462.15  5519.2  460.57
  5550.6  464.31  5722.8  481.38  5744.0  481.48  5783.8  488.33  5835.8  488.58
#Mann=10,-1,0
  3478.2    0.12       0  3953.7     0.1       0  4209.7    0.12       0
  4524.6    0.07       0  4531.1    0.12       0  4548.3    0.05       0
  4571.0    0.12       0  5070.1    0.05       0  5250.1    0.12       0
  5550.6    0.05       0
Bank Sta=4524.6,4531.1
Exp/Cntr=0.3,0.1

Type RM Length L Ch R = 1,2195,264,264,264
BEGIN DESCRIPTION:
Mapping XS 17eeaff2
END DESCRIPTION:
XS GIS Cut Line= 3
      2770478.60      6804521.13      2770453.51      6805774.39
      2770651.60      6806796.76
#Sta/Elev= 30
  3505.7  481.69  4016.2  457.97  4230.8  452.85  4382.9  456.64  4387.9  455.28
  4475.8  455.41  4485.8  454.85  4495.8  451.59  4515.8  451.42  4545.8  457.00
  4555.8  454.43  4605.8  448.82  4635.8  448.84  4846.7  430.74  4955.3  425.57
  4990.0  425.80  5003.8  423.36  5004.9  422.86  5010.3  423.36  5030.8  427.31
  5153.0  431.32  5336.4  441.71  5431.3  450.99  5548.4  465.48  5600.4  470.86
  5648.6  476.47  5703.1  482.92  5713.2  485.83  5748.8  487.23  5800.6  494.21
#Mann=9,-1,0
  3505.7    0.12       0  4016.2     0.1       0  4230.8    0.12       0
  5003.8    0.07       0  5010.3    0.12       0  5548.4     0.1       0
  5600.4    0.12       0  5648.6     0.1       0  5748.8    0.05       0
Bank Sta=5003.8,5010.3
Exp/Cntr=0.3,0.1

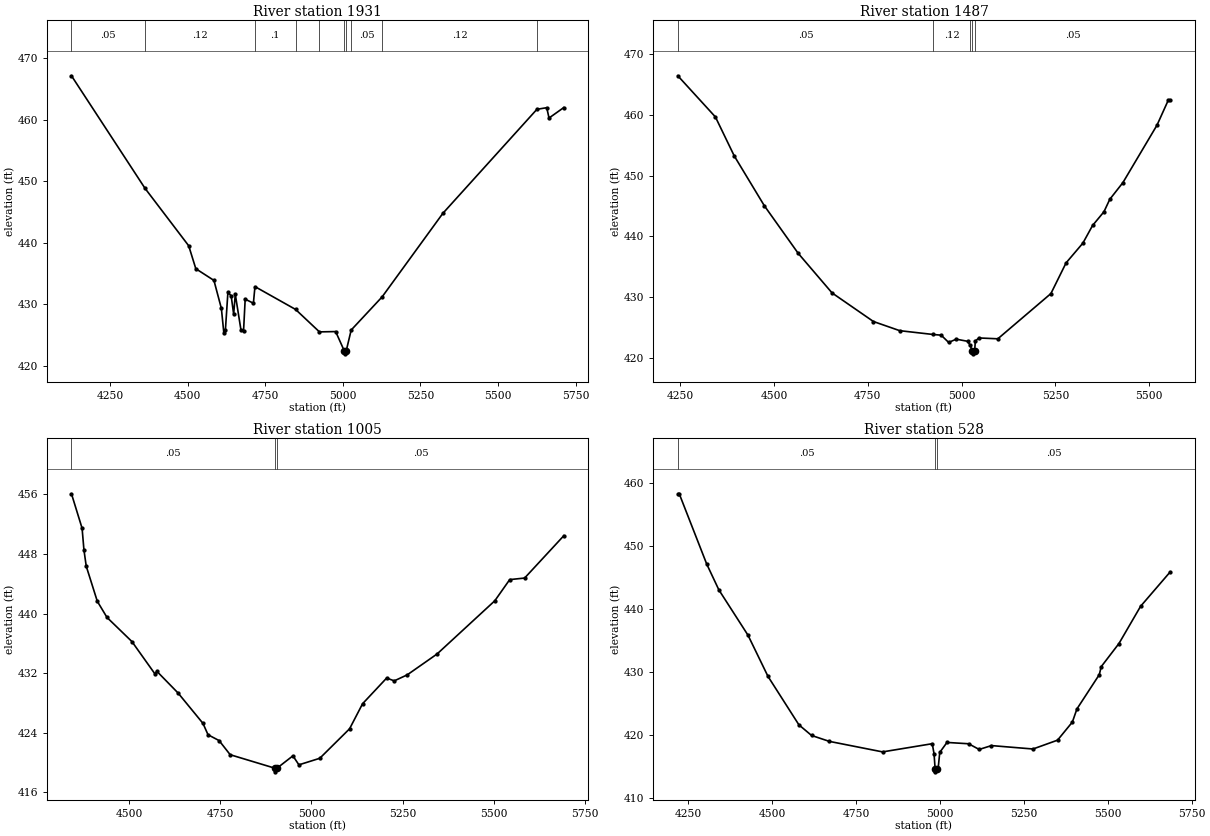
Type RM Length L Ch R = 1,1931,444,444,444
BEGIN DESCRIPTION:
Clear Creek T 8 4.0
END DESCRIPTION:
XS GIS Cut Line= 3
      2770007.04      6805292.07      2770276.00      6806111.00
      2770398.70      6806825.27
#Sta/Elev= 30
  4125.3  467.18  4362.3  448.88  4503.1  439.54  4526.0  435.81  4584.4  433.91
  4608.4  429.35  4616.2  425.43  4621.4  425.86  4629.4  431.96  4639.9  431.41
  4648.0  428.41  4653.2  431.66  4671.5  425.85  4679.8  425.62  4685.1  430.86
  4711.6  430.20  4716.6  432.90  4847.5  429.19  4924.4  425.54  4976.7  425.59
  5004.3  422.47  5005.4  421.97  5010.8  422.47  5026.7  425.84  5126.4  431.23
  5322.1  444.81  5625.3  461.73  5656.9  461.99  5664.3  460.31  5712.0  462.02
#Mann=10,-1,0
  4125.3    0.05       0  4362.3    0.12       0  4716.6     0.1       0
  4847.5    0.05       0  4924.4     0.1       0  5004.3    0.07       0
  5010.8     0.1       0  5026.7    0.05       0  5126.4    0.12       0
  5625.3    0.05       0
Bank Sta=5004.3,5010.8
Exp/Cntr=0.3,0.1

Type RM Length L Ch R = 1,1487,482,482,482
BEGIN DESCRIPTION:
Clear Creek T 8 3.0
END DESCRIPTION:
XS GIS Cut Line= 3
      2769826.00      6805460.98      2769876.00      6806211.00
      2769953.07      6806765.68
#Sta/Elev= 30
  4244.0  466.49  4344.2  459.70  4394.4  453.27  4474.5  445.06  4564.7  437.21
  4654.9  430.68  4765.2  425.96  4835.3  424.45  4924.6  423.82  4945.6  423.71
  4965.6  422.51  4985.7  423.05  5015.9  422.70  5023.1  422.02  5028.2  421.13
  5029.2  420.63  5034.9  421.13  5036.6  422.74  5046.2  423.25  5096.6  423.11
  5238.0  430.57  5278.4  435.63  5323.2  438.89  5349.0  441.80  5379.3  444.06
  5394.9  446.12  5429.8  448.87  5520.7  458.35  5550.8  462.48  5555.7  462.48
#Mann=5,-1,0
  4244.0    0.05       0  4924.6    0.12       0  5023.1    0.05       0
  5028.2    0.07       0  5034.9    0.05       0
Bank Sta=5028.2,5034.9
Exp/Cntr=0.3,0.1

Type RM Length L Ch R = 1,1005,477,477,477
BEGIN DESCRIPTION:
Clear Creek T 8 2.0
END DESCRIPTION:
XS GIS Cut Line= 3
      2769526.00      6805560.99      2769426.00      6806211.00
      2769597.24      6806881.62
#Sta/Elev= 30
  4342.0  456.09  4371.1  451.46  4376.2  448.54  4382.5  446.36  4412.8  441.65
  4439.4  439.48  4507.7  436.24  4570.9  431.89  4576.0  432.25  4634.2  429.33
  4702.5  425.25  4716.4  423.72  4746.7  422.94  4777.1  421.04  4898.9  419.24
  4900.0  418.74  4905.7  419.24  4949.1  420.89  4965.5  419.68  5022.7  420.56
  5104.4  424.52  5140.1  427.89  5206.1  431.34  5226.9  430.96  5262.6  431.77
  5344.3  434.57  5502.6  441.72  5543.4  444.56  5584.3  444.77  5691.8  450.46
#Mann=3,-1,0
  4342.0    0.05       0  4898.9    0.04       0  4905.7    0.05       0
Bank Sta=4898.9,4905.7
Exp/Cntr=0.3,0.1

Type RM Length L Ch R = 1,528,0,0,0
BEGIN DESCRIPTION:
Clear Creek T 8 1.0
END DESCRIPTION:
XS GIS Cut Line= 3
      2769275.03      6805398.11      2768976.00      6806111.00
      2769326.00      6806711.01
#Sta/Elev= 30
  4218.2  458.28  4222.5  458.28  4304.4  447.14  4340.6  443.05  4427.4  435.87
  4487.1  429.33  4579.2  421.66  4616.8  419.98  4669.7  419.04  4828.6  417.37
  4976.7  418.67  4982.1  417.07  4985.2  414.71  4986.3  414.21  4992.0  414.71
  4994.2  414.71  4999.1  417.29  5020.6  418.87  5085.1  418.66  5116.5  417.76
  5153.3  418.37  5277.0  417.83  5350.2  419.23  5394.4  422.10  5408.0  424.18
  5474.6  429.61  5480.4  430.88  5533.3  434.55  5597.8  440.45  5685.9  445.89
#Mann=3,-1,0
  4218.2    0.05       0  4985.2    0.04       0  4992.0    0.05       0
Bank Sta=4985.2,4992
Exp/Cntr=0.3,0.1

Chan Stop Cuts=-1