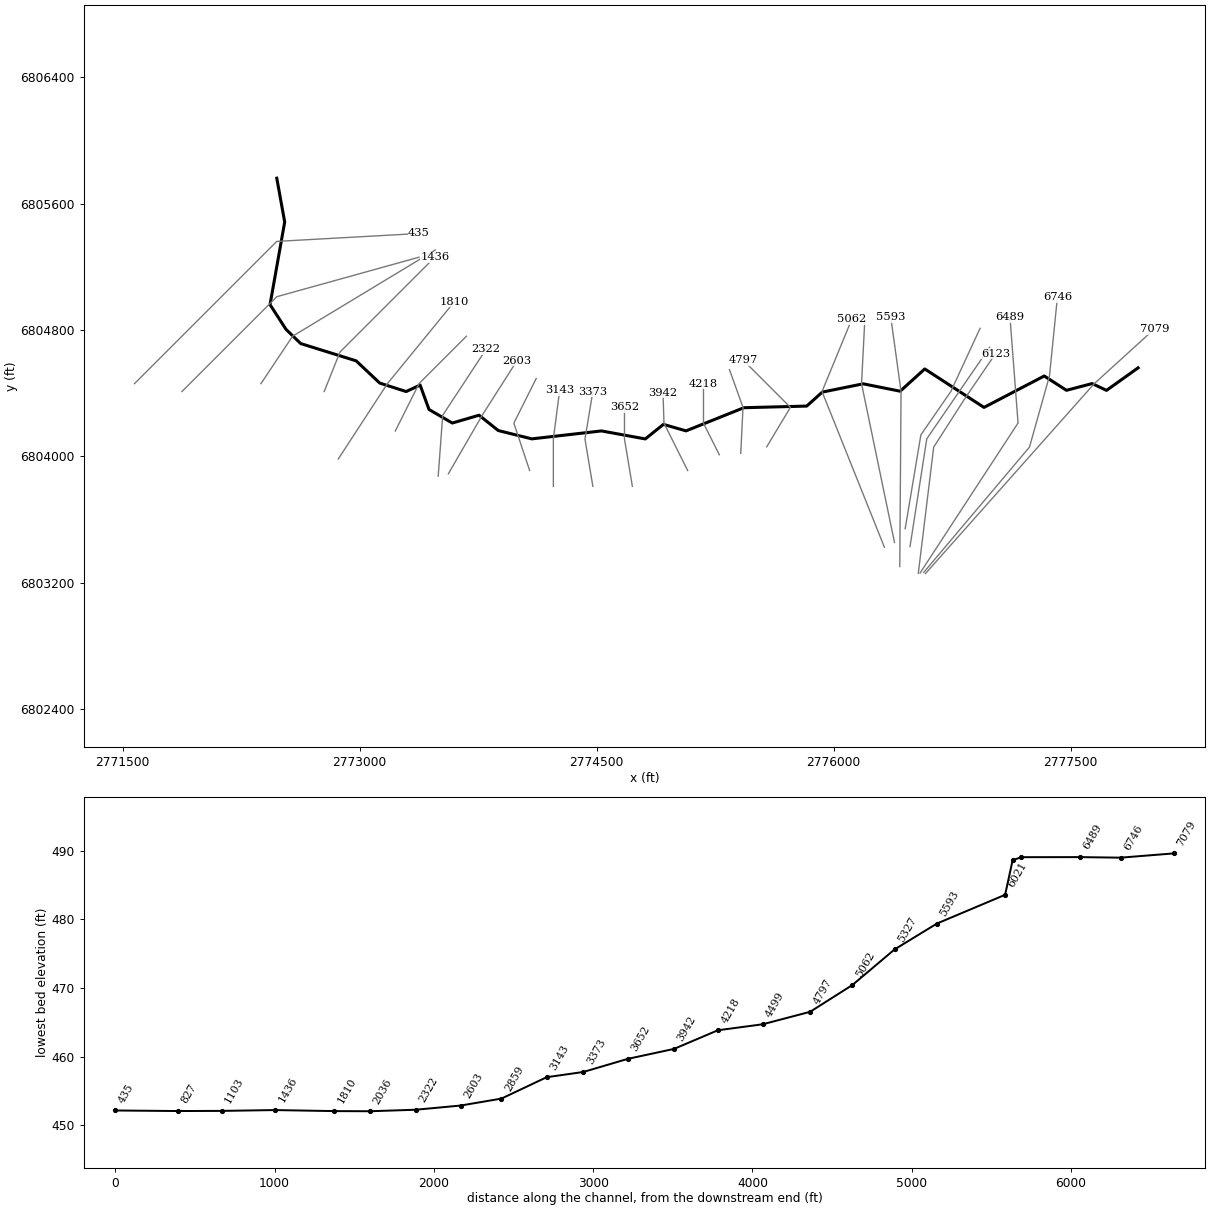
--- Clear Creek T 9.prj (project) ---

Proj Title=Clear Creek T 9 Base Level Engineering
Current Plan=p01
Default Exp/Contr=0.3,0.1
English Units
Geom File=g01
Flow File=f01
Plan File=p01
BEGIN DESCRIPTION:
Clear Creek T 9
END DESCRIPTION:

--- Clear Creek T 9.p01 (plan) ---

Plan Title=Multiple Run
Short Identifier=Multiple
Geom File=g01
Flow File=f01
Subcritical Flow
K Sum by GR= 0
Std Step Tol= 0.01
Critical Tol= 0.01
Num of Std Step Trials= 20
Max Error Tol= 0.3
Flow Tol Ratio= 0.001
Split Flow NTrial= 30
Split Flow Tol= 0.02
Split Flow Ratio= 0.02
Log Output Level= 0
Friction Slope Method= 1
Unsteady Friction Slope Method= 2
Unsteady Bridges Friction Slope Method= 1
Parabolic Critical Depth
Global Vel Dist=  1 , 1 , 1
Global Log Level= 0
CheckData=True
Encroach Param= -1, 0, 0, 0
BEGIN DESCRIPTION:
Multiple Run
END DESCRIPTION:

--- Clear Creek T 9.f01 (steady flow) ---

Flow Title=Multiple
Number of Profiles=7
Profile Names=10-year,25-year,50-year,1pct_min,100-year,1pct_plu,500-year
River Rch & RM= Clear Creek T 9,Reach-1,7079
     256     330     389     229     456     911     629
River Rch & RM= Clear Creek T 9,Reach-1,4797
     383     504     600     356     711    1418     997
Boundary for River Rch & Prof#=Clear Creek T 9,Reach-1,1
Up Type=0
Dn Type=3
Dn Slope=0.005
Boundary for River Rch & Prof#=Clear Creek T 9,Reach-1,2
Up Type=0
Dn Type=3
Dn Slope=0.005
Boundary for River Rch & Prof#=Clear Creek T 9,Reach-1,3
Up Type=0
Dn Type=3
Dn Slope=0.005
Boundary for River Rch & Prof#=Clear Creek T 9,Reach-1,4
Up Type=0
Dn Type=3
Dn Slope=0.005
Boundary for River Rch & Prof#=Clear Creek T 9,Reach-1,5
Up Type=0
Dn Type=3
Dn Slope=0.005
Boundary for River Rch & Prof#=Clear Creek T 9,Reach-1,6
Up Type=0
Dn Type=3
Dn Slope=0.005
Boundary for River Rch & Prof#=Clear Creek T 9,Reach-1,7
Up Type=0
Dn Type=3
Dn Slope=0.005

--- Clear Creek T 9.g01 (geometry) ---

Geom Title=Existing Conditions

River Reach=Clear Creek T 9,Reach-1
Reach XY= 30
      2777926.00      6804561.00      2777726.10      6804418.32
      2777635.28      6804461.45      2777472.59      6804418.81
      2777332.05      6804509.41      2776951.00      6804310.59
      2776576.00      6804553.93      2776420.52      6804413.08
      2776186.55      6804459.90      2775927.46      6804407.44
      2775829.33      6804319.01      2775431.52      6804308.65
      2775065.45      6804162.11      2774922.59      6804203.19
      2774807.78      6804111.10      2774530.56      6804161.78
      2774089.86      6804111.53      2773877.65      6804164.17
      2773755.95      6804261.20      2773586.68      6804211.75
      2773439.26      6804297.35      2773383.06      6804451.99
      2773294.46      6804410.89      2773127.50      6804464.61
      2772978.30      6804605.17      2772627.46      6804714.54
      2772534.15      6804804.93      2772433.33      6804960.90
      2772526.09      6805483.69      2772476.00      6805761.00

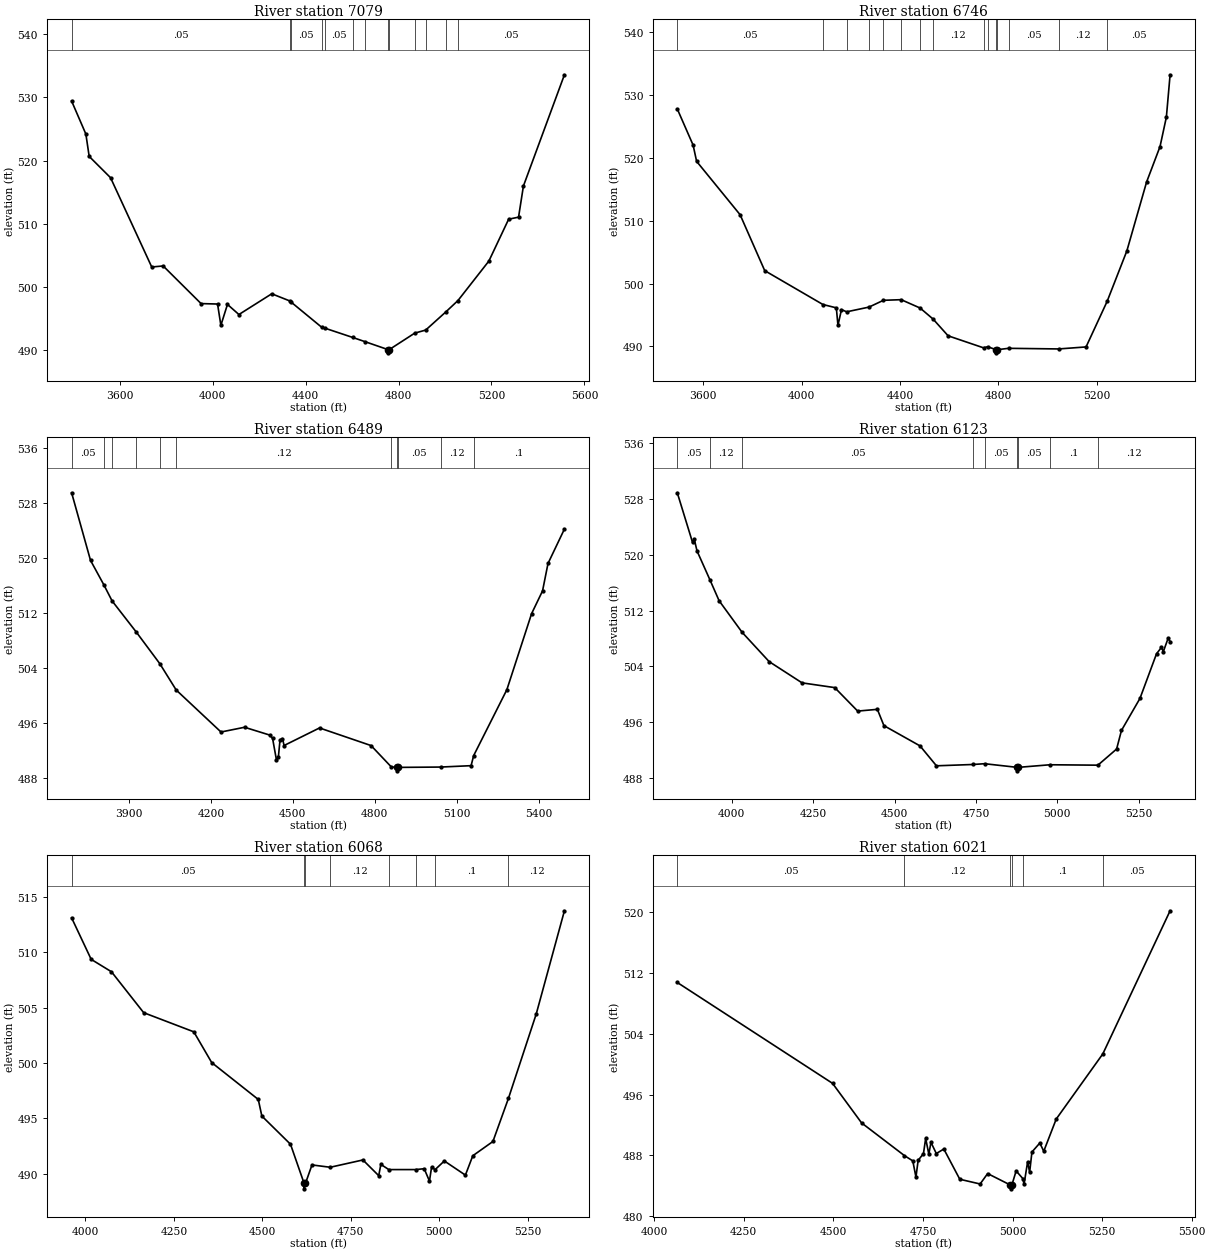
Type RM Length L Ch R = 1,7079,333,333,333
BEGIN DESCRIPTION:
Clear Creek T 9 24.0
END DESCRIPTION:
XS GIS Cut Line= 3
      2776580.75      6803259.50      2777648.87      6804461.23
      2778029.23      6804806.94
#Sta/Elev= 30
  3392.2  529.43  3453.6  524.21  3467.8  520.68  3559.8  517.31  3737.1  503.19
  3786.4  503.35  3949.5  497.40  4020.6  497.33  4034.8  493.96  4063.2  497.27
  4112.5  495.67  4253.9  498.95  4334.2  497.78  4336.1  497.67  4468.1  493.68
  4481.2  493.53  4601.9  492.05  4655.3  491.38  4755.3  490.11  4755.5  489.61
  4759.3  490.11  4869.6  492.73  4916.6  493.21  5003.9  496.10  5055.6  497.88
  5188.8  504.13  5273.9  510.75  5316.5  511.07  5337.5  516.00  5514.0  533.59
#Mann=13,-1,0
  3392.2    0.05       0  4334.2    0.12       0  4336.1    0.05       0
  4468.1    0.12       0  4481.2    0.05       0  4601.9    0.12       0
  4655.3    0.05       0  4755.3    0.04       0  4759.3    0.05       0
  4869.6    0.12       0  4916.6    0.05       0  5003.9    0.12       0
  5055.6    0.05       0
Bank Sta=4755.3,4759.3
Exp/Cntr=0.3,0.1

Type RM Length L Ch R = 1,6746,257,257,257
BEGIN DESCRIPTION:
Clear Creek T 9 23.0
END DESCRIPTION:
XS GIS Cut Line= 4
      2776569.58      6803266.84      2777238.72      6804059.58
      2777365.36      6804510.44      2777415.15      6805006.04
#Sta/Elev= 30
  3494.3  527.80  3558.6  522.05  3572.9  519.46  3749.7  510.97  3849.8  502.07
  4086.5  496.68  4141.0  496.15  4147.6  493.36  4161.9  495.87  4183.2  495.52
  4273.8  496.27  4332.5  497.35  4404.6  497.45  4481.7  496.12  4534.5  494.36
  4595.5  491.70  4739.4  489.79  4756.3  489.96  4790.8  489.49  4791.1  488.99
  4794.8  489.49  4841.8  489.71  5044.9  489.61  5156.4  489.93  5242.2  497.19
  5322.2  505.20  5402.6  516.18  5457.2  521.82  5483.0  526.51  5498.1  533.24
#Mann=15,-1,0
  3494.3    0.05       0  4086.5    0.12       0  4183.2    0.05       0
  4273.8    0.12       0  4332.5    0.05       0  4404.6    0.12       0
  4481.7    0.05       0  4534.5    0.12       0  4739.4    0.05       0
  4756.3    0.12       0  4790.8    0.03       0  4794.8    0.12       0
  4841.8    0.05       0  5044.9    0.12       0  5242.2    0.05       0
Bank Sta=4790.8,4794.8
Exp/Cntr=0.3,0.1

Type RM Length L Ch R = 1,6489,366,366,366
BEGIN DESCRIPTION:
Clear Creek T 9 22.0
END DESCRIPTION:
XS GIS Cut Line= 3
      2776546.70      6803263.05      2777166.39      6804212.08
      2777115.30      6804880.89
#Sta/Elev= 30
  3690.4  529.46  3759.6  519.64  3808.5  516.08  3838.6  513.75  3927.3  509.22
  4013.2  504.64  4073.3  500.81  4237.3  494.71  4323.5  495.40  4417.0  494.25
  4426.2  493.77  4440.4  490.63  4447.3  491.05  4453.2  493.48  4462.4  493.76
  4468.3  492.75  4598.0  495.30  4786.7  492.74  4860.8  489.64  4880.9  489.57
  4881.2  489.07  4884.9  489.57  5041.2  489.62  5152.9  489.82  5162.4  491.29
  5283.8  500.85  5374.4  511.90  5414.5  515.21  5434.5  519.19  5494.6  524.19
#Mann=11,-1,0
  3690.4    0.05       0  3808.5    0.12       0  3838.6    0.05       0
  3927.3    0.12       0  4013.2    0.05       0  4073.3    0.12       0
  4860.8    0.05       0  4880.9    0.03       0  4884.9    0.05       0
  5041.2    0.12       0  5162.4     0.1       0
Bank Sta=4880.9,4884.9
Exp/Cntr=0.3,0.1

Type RM Length L Ch R = 1,6123,55,55,55
BEGIN DESCRIPTION:
Clear Creek T 9 21.0
END DESCRIPTION:
XS GIS Cut Line= 4
      2776535.14      6803260.83      2776632.54      6804059.03
      2776826.00      6804361.00      2777024.07      6804651.08
#Sta/Elev= 30
  3832.6  528.85  3879.5  521.74  3884.6  522.24  3893.2  520.53  3932.9  516.39
  3961.1  513.40  4031.8  508.88  4114.8  504.69  4215.9  501.65  4316.3  500.97
  4386.8  497.61  4447.3  497.86  4467.4  495.53  4578.3  492.63  4628.8  489.78
  4741.4  489.97  4776.6  490.08  4876.7  489.56  4876.9  489.06  4880.7  489.56
  4977.6  489.93  5124.8  489.87  5182.3  492.18  5197.2  494.84  5254.1  499.43
  5304.9  505.81  5319.8  506.71  5325.9  506.13  5340.8  508.06  5346.6  507.56
#Mann=9,-1,0
  3832.6    0.05       0  3932.9    0.12       0  4031.8    0.05       0
  4741.4    0.12       0  4776.6    0.05       0  4876.7    0.07       0
  4880.7    0.05       0  4977.6     0.1       0  5124.8    0.12       0
Bank Sta=4876.7,4880.7
Exp/Cntr=0.3,0.1

Type RM Length L Ch R = 1,6068,47,47,47
BEGIN DESCRIPTION:
Mapping XS 09e818cd
END DESCRIPTION:
XS GIS Cut Line= 3
      2776482.74      6803429.69      2776588.93      6804112.07
      2776986.30      6804691.27
#Sta/Elev= 30
  3960.9  513.11  4016.2  509.36  4073.5  508.24  4164.6  504.54  4306.3  502.81
  4356.9  500.03  4488.5  496.70  4498.6  495.20  4579.6  492.65  4618.0  489.12
  4618.3  488.62  4622.0  489.12  4640.3  490.78  4691.9  490.57  4784.3  491.23
  4829.0  489.81  4835.0  490.83  4857.5  490.36  4933.3  490.36  4957.5  490.44
  4972.4  489.32  4978.5  490.60  4988.2  490.35  5014.4  491.14  5074.0  489.86
  5094.9  491.61  5151.8  492.90  5195.7  496.80  5274.3  504.43  5353.9  513.75
#Mann=8,-1,0
  3960.9    0.05       0  4618.0    0.07       0  4622.0    0.05       0
  4691.9    0.12       0  4857.5    0.05       0  4933.3    0.12       0
  4988.2     0.1       0  5195.7    0.12       0
Bank Sta=4618,4622
Exp/Cntr=0.3,0.1

Type RM Length L Ch R = 1,6021,428,428,428
BEGIN DESCRIPTION:
Clear Creek T 9 20.0
END DESCRIPTION:
XS GIS Cut Line= 4
      2776452.32      6803543.65      2776551.54      6804137.11
      2776741.34      6804411.82      2776925.99      6804810.98
#Sta/Elev= 30
  4064.4  510.75  4497.7  497.47  4578.8  492.26  4698.5  487.95  4721.7  487.26
  4730.5  485.12  4736.6  487.33  4751.5  488.22  4757.6  490.22  4766.4  488.15
  4772.4  489.70  4787.3  488.23  4808.3  488.82  4852.9  484.84  4909.6  484.22
  4930.6  485.59  4994.2  484.08  4994.4  483.58  4998.2  484.08  5010.1  485.94
  5029.0  484.92  5032.2  484.18  5042.2  487.16  5047.8  485.75  5054.2  488.43
  5076.2  489.61  5087.2  488.53  5122.0  492.77  5252.1  501.35  5439.8  520.19
#Mann=6,-1,0
  4064.4    0.05       0  4698.5    0.12       0  4994.2    0.07       0
  4998.2    0.12       0  5029.0     0.1       0  5252.1    0.05       0
Bank Sta=4994.2,4998.2
Exp/Cntr=0.3,0.1

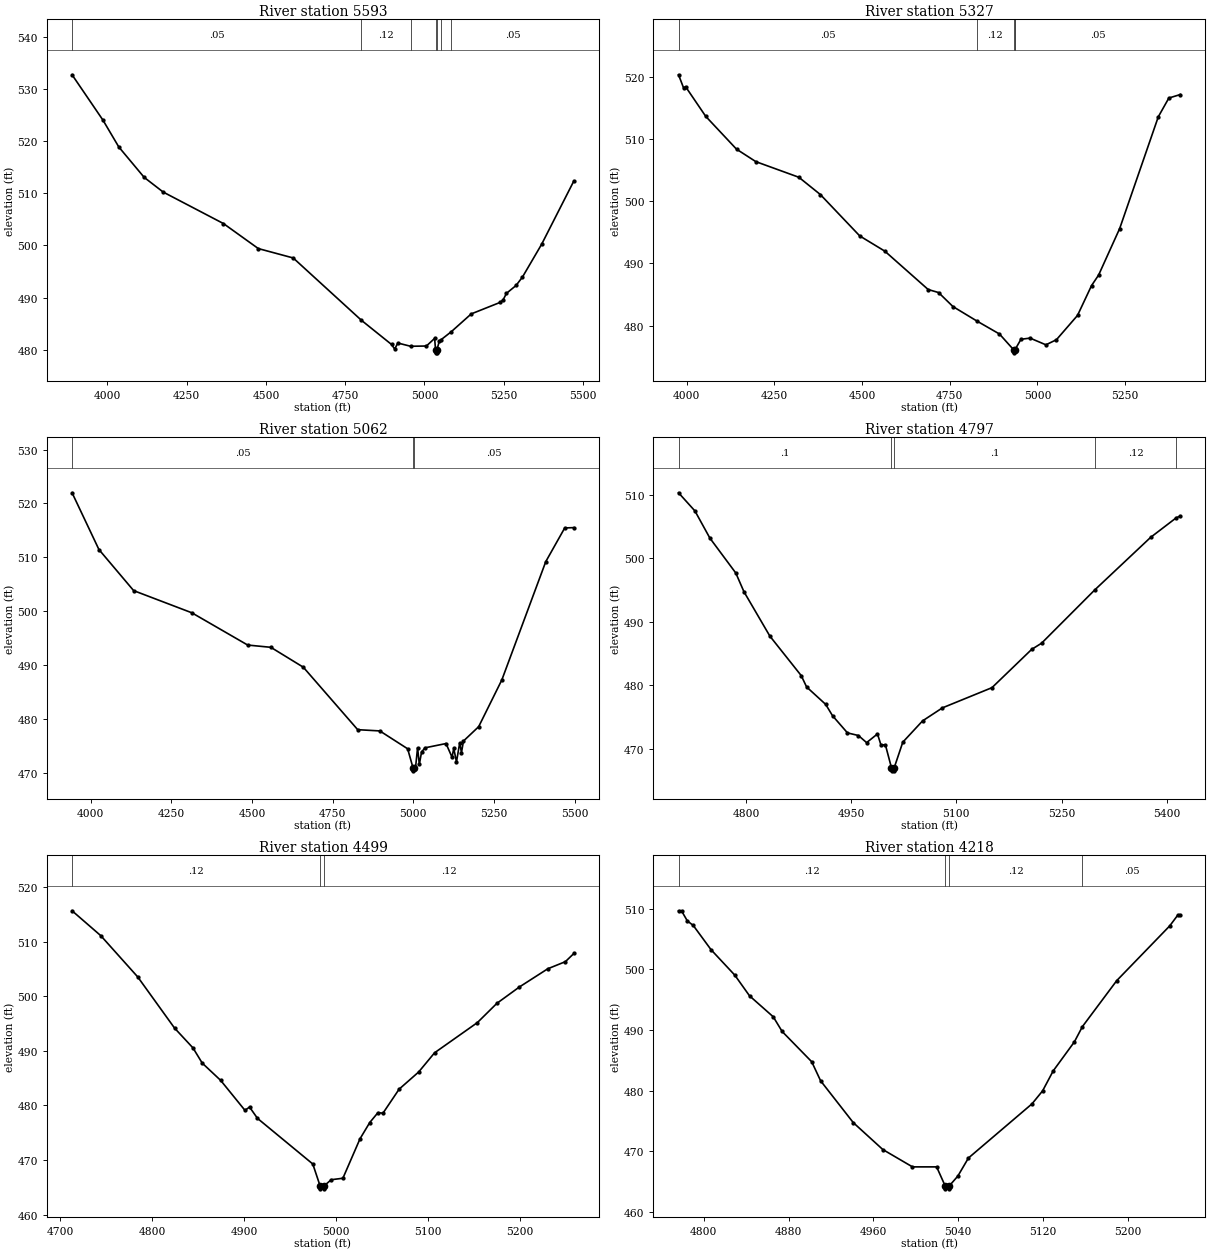
Type RM Length L Ch R = 1,5593,266,266,266
BEGIN DESCRIPTION:
Clear Creek T 9 19.0
END DESCRIPTION:
XS GIS Cut Line= 3
      2776417.98      6803303.60      2776426.00      6804411.00
      2776361.04      6804881.61
#Sta/Elev= 30
  3888.6  532.73  3986.0  524.03  4036.0  518.88  4116.0  513.05  4176.0  510.23
  4366.0  504.19  4476.0  499.39  4586.0  497.59  4801.2  485.63  4896.0  481.00
  4906.0  480.12  4916.0  481.27  4956.3  480.65  5006.1  480.70  5032.0  482.16
  5035.0  479.89  5035.3  479.39  5038.8  479.39  5039.0  479.89  5046.5  481.58
  5053.0  481.94  5084.1  483.42  5147.5  486.86  5238.3  489.06  5247.7  489.51
  5258.5  490.80  5288.8  492.31  5309.0  493.93  5369.5  500.22  5471.1  512.36
#Mann=7,-1,0
  3888.6    0.05       0  4801.2    0.12       0  4956.3    0.05       0
  5035.0    0.04       0  5039.0    0.05       0  5053.0    0.12       0
  5084.1    0.05       0
Bank Sta=5035,5039
Exp/Cntr=0.3,0.1

Type RM Length L Ch R = 1,5327,265,265,265
BEGIN DESCRIPTION:
Clear Creek T 9 18.0
END DESCRIPTION:
XS GIS Cut Line= 3
      2776384.79      6803455.17      2776176.00      6804461.00
      2776196.76      6804863.69
#Sta/Elev= 30
  3976.9  520.36  3991.8  518.17  3996.9  518.45  4054.3  513.68  4142.2  508.39
  4197.4  506.38  4319.9  503.87  4381.2  501.09  4493.5  494.43  4565.0  491.98
  4688.5  485.81  4718.2  485.32  4759.1  483.07  4828.0  480.72  4891.8  478.65
  4932.1  476.12  4932.3  475.62  4936.1  476.12  4936.4  476.16  4953.1  477.80
  4979.1  477.99  5024.2  476.91  5054.2  477.73  5114.3  481.64  5154.4  486.45
  5174.4  488.13  5234.5  495.62  5344.6  513.60  5374.7  516.62  5407.4  517.18
#Mann=5,-1,0
  3976.9    0.05       0  4828.0    0.12       0  4932.1    0.04       0
  4936.1    0.12       0  4936.4    0.05       0
Bank Sta=4932.1,4936.1
Exp/Cntr=0.3,0.1

Type RM Length L Ch R = 1,5062,265,265,265
BEGIN DESCRIPTION:
Clear Creek T 9 17.0
END DESCRIPTION:
XS GIS Cut Line= 3
      2776320.79      6803425.91      2775926.00      6804411.00
      2776113.76      6804867.33
#Sta/Elev= 30
  3942.6  521.98  4025.8  511.46  4133.4  503.84  4313.7  499.73  4486.7  493.75
  4558.5  493.33  4659.1  489.64  4827.6  478.06  4896.1  477.83  4982.3  474.52
  4999.2  470.93  4999.4  470.43  5003.2  470.93  5006.6  470.93  5013.1  474.71
  5018.5  471.62  5025.5  473.94  5036.3  474.70  5101.2  475.49  5119.8  472.97
  5125.2  474.58  5133.6  472.09  5143.7  475.63  5149.1  473.80  5155.2  475.95
  5202.4  478.62  5274.2  487.29  5410.3  509.22  5469.0  515.46  5497.3  515.52
#Mann=3,-1,0
  3942.6    0.05       0  4999.2    0.04       0  5003.2    0.05       0
Bank Sta=4999.2,5003.2
Exp/Cntr=0.3,0.1

Type RM Length L Ch R = 1,4797,298,298,298
BEGIN DESCRIPTION:
Clear Creek T 9 16.0
END DESCRIPTION:
XS GIS Cut Line= 3
      2775575.98      6804060.97      2775726.00      6804311.00
      2775426.03      6804610.97
#Sta/Elev= 30
  4703.7  510.29  4727.1  507.43  4748.4  503.16  4785.4  497.66  4797.0  494.72
  4834.0  487.73  4878.7  481.52  4886.4  479.73  4913.6  476.99  4923.4  475.20
  4944.7  472.50  4960.3  472.09  4972.0  470.97  4987.5  472.34  4992.4  470.62
  4998.8  470.62  5007.4  467.03  5007.7  466.53  5011.2  466.53  5011.4  467.03
  5023.6  471.04  5051.8  474.39  5080.1  476.44  5150.8  479.62  5207.4  485.64
  5221.6  486.62  5297.7  495.03  5377.1  503.27  5413.9  506.37  5419.5  506.62
#Mann=5,-1,0
  4703.7     0.1       0  5007.4    0.07       0  5011.4     0.1       0
  5297.7    0.12       0  5413.9     0.1       0
Bank Sta=5007.4,5011.4
Exp/Cntr=0.3,0.1

Type RM Length L Ch R = 1,4499,281,281,281
BEGIN DESCRIPTION:
Clear Creek T 9 15.0
END DESCRIPTION:
XS GIS Cut Line= 3
      2775411.75      6804019.80      2775426.00      6804311.00
      2775340.34      6804549.64
#Sta/Elev= 30
  4713.1  515.64  4744.3  511.08  4784.4  503.53  4824.4  494.16  4844.5  490.51
  4854.5  487.74  4874.5  484.58  4900.9  479.09  4905.9  479.69  4914.5  477.62
  4974.6  469.26  4982.6  465.21  4982.9  464.71  4986.4  464.71  4986.6  465.21
  4994.6  466.38  5007.3  466.65  5025.9  473.88  5036.5  476.86  5045.4  478.67
  5050.8  478.56  5068.4  482.97  5089.6  486.11  5106.9  489.63  5153.4  495.16
  5174.6  498.69  5199.1  501.69  5229.9  505.02  5249.0  506.32  5258.2  507.82
#Mann=3,-1,0
  4713.1    0.12       0  4982.6    0.07       0  4986.6    0.12       0
Bank Sta=4982.6,4986.6
Exp/Cntr=0.3,0.1

Type RM Length L Ch R = 1,4218,276,276,276
BEGIN DESCRIPTION:
Clear Creek T 9 14.0
END DESCRIPTION:
XS GIS Cut Line= 3
      2775275.98      6804011.03      2775176.00      6804211.00
      2775176.00      6804461.03
#Sta/Elev= 30
  4776.1  509.68  4778.9  509.68  4784.4  508.01  4790.0  507.26  4806.8  503.26
  4829.2  499.07  4843.1  495.66  4865.5  492.20  4873.9  489.78  4901.8  484.79
  4910.2  481.65  4941.0  474.76  4968.9  470.32  4996.9  467.46  5019.7  467.46
  5027.7  464.34  5027.9  463.84  5031.4  463.84  5031.7  464.34  5039.7  465.94
  5049.7  468.92  5109.7  477.85  5119.7  479.99  5129.7  483.28  5149.7  488.07
  5157.3  490.59  5189.7  498.17  5239.7  507.19  5247.2  508.94  5249.7  508.94
#Mann=4,-1,0
  4776.1    0.12       0  5027.7    0.07       0  5031.7    0.12       0
  5157.3    0.05       0
Bank Sta=5027.7,5031.7
Exp/Cntr=0.3,0.1

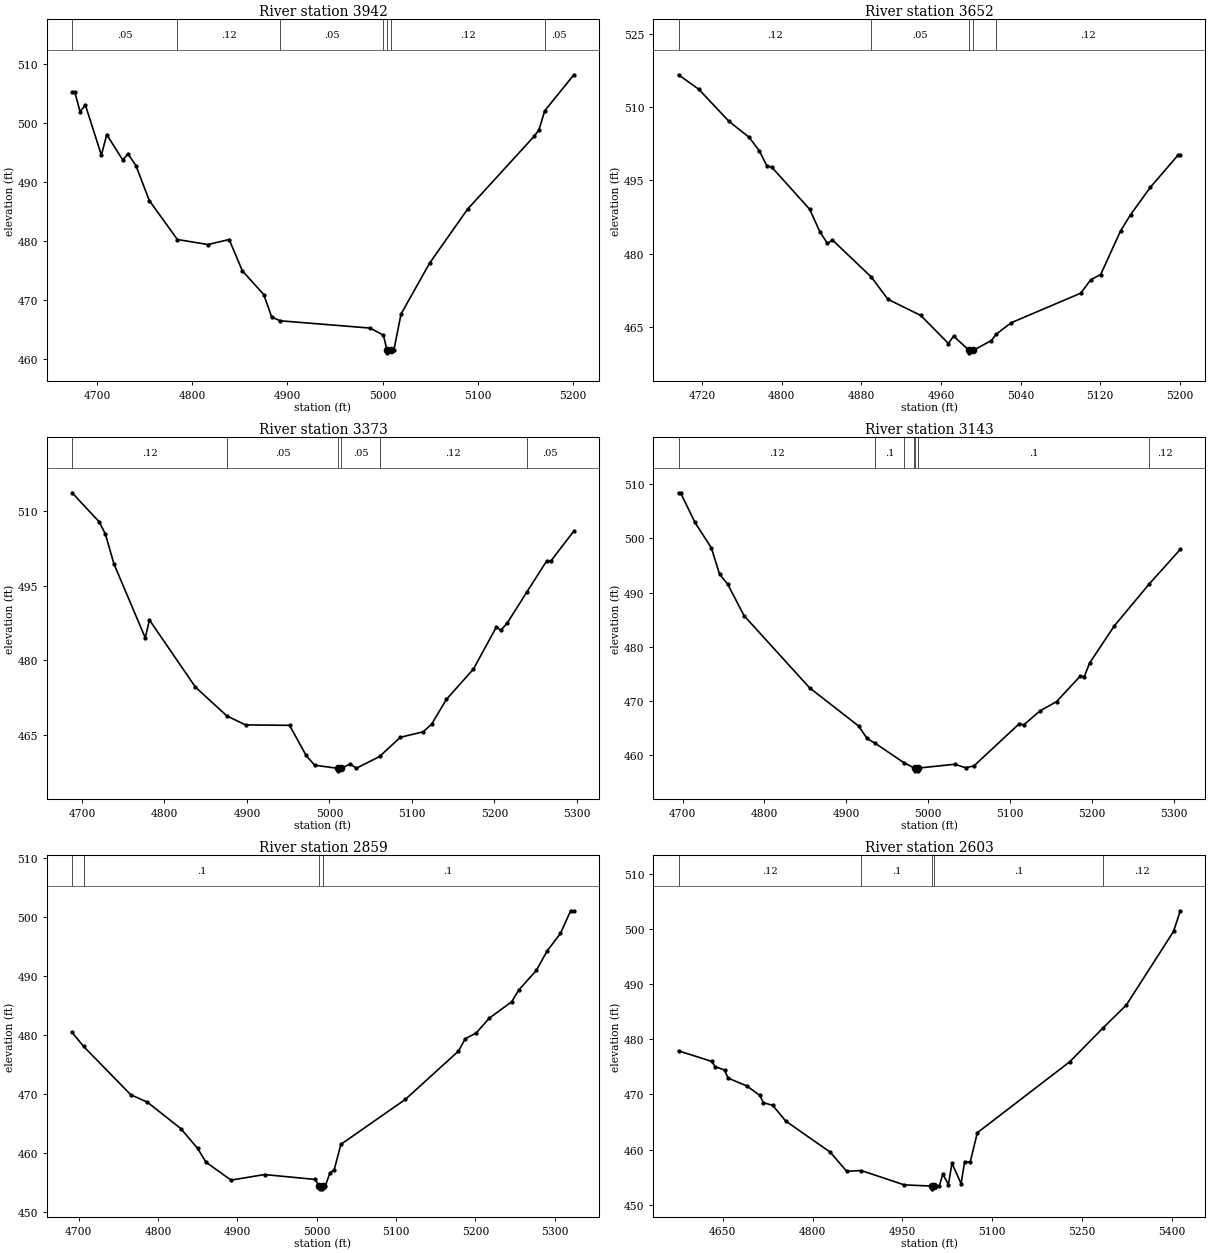
Type RM Length L Ch R = 1,3942,290,290,290
BEGIN DESCRIPTION:
Clear Creek T 9 13.0
END DESCRIPTION:
XS GIS Cut Line= 3
      2775076.02      6803910.96      2774926.00      6804211.00
      2774919.81      6804402.45
#Sta/Elev= 30
  4673.8  505.29  4676.6  505.29  4682.2  501.94  4687.8  503.05  4704.6  494.57
  4710.2  498.06  4727.0  493.77  4732.5  494.80  4740.9  492.80  4754.9  486.90
  4784.4  480.30  4816.4  479.45  4838.8  480.30  4852.7  474.98  4875.1  470.99
  4883.5  467.16  4892.6  466.54  4986.9  465.31  5000.8  464.10  5004.5  461.62
  5004.7  461.12  5008.5  461.62  5011.8  461.62  5019.3  467.69  5049.3  476.30
  5089.3  485.46  5159.2  497.79  5164.2  498.89  5170.2  502.08  5200.8  508.18
#Mann=7,-1,0
  4673.8    0.05       0  4784.4    0.12       0  4892.6    0.05       0
  5000.8    0.12       0  5004.5    0.04       0  5008.5    0.12       0
  5170.2    0.05       0
Bank Sta=5004.5,5008.5
Exp/Cntr=0.3,0.1

Type RM Length L Ch R = 1,3652,279,279,279
BEGIN DESCRIPTION:
Clear Creek T 9 12.0
END DESCRIPTION:
XS GIS Cut Line= 3
      2774726.01      6803810.95      2774676.00      6804111.00
      2774676.00      6804311.01
#Sta/Elev= 30
  4696.2  516.64  4716.5  513.68  4746.9  507.09  4767.2  503.82  4777.4  501.04
  4785.0  497.98  4790.0  497.69  4828.0  489.07  4838.2  484.48  4845.8  482.08
  4850.9  482.78  4889.9  475.20  4906.6  470.64  4939.6  467.33  4967.4  461.58
  4972.5  463.11  4988.2  460.17  4988.5  459.67  4992.2  460.17  5010.4  462.17
  5015.4  463.49  5030.4  465.83  5100.4  471.90  5110.4  474.64  5120.4  475.72
  5140.4  484.68  5150.4  487.97  5170.4  493.62  5197.9  500.13  5200.4  500.13
#Mann=5,-1,0
  4696.2    0.12       0  4889.9    0.05       0  4988.2    0.05       0
  4992.2    0.05       0  5015.4    0.12       0
Bank Sta=4988.2,4992.2
Exp/Cntr=0.3,0.1

Type RM Length L Ch R = 1,3373,230,230,230
BEGIN DESCRIPTION:
Clear Creek T 9 11.0
END DESCRIPTION:
XS GIS Cut Line= 3
      2774476.00      6803811.02      2774426.00      6804111.00
      2774476.01      6804411.04
#Sta/Elev= 30
  4688.0  513.74  4720.9  507.89  4728.5  505.39  4738.7  499.45  4776.7  484.54
  4781.8  488.13  4837.5  474.63  4875.6  468.82  4898.3  467.01  4951.6  466.92
  4971.8  460.85  4982.0  458.90  5010.4  458.26  5010.6  457.76  5014.4  458.26
  5025.1  459.15  5032.7  458.29  5060.8  460.65  5085.9  464.51  5113.8  465.62
  5123.9  467.17  5141.7  472.13  5174.6  478.26  5202.5  486.76  5207.6  486.05
  5215.2  487.43  5239.3  493.75  5263.3  500.01  5268.4  500.00  5296.3  506.04
#Mann=6,-1,0
  4688.0    0.12       0  4875.6    0.05       0  5010.4    0.05       0
  5014.4    0.05       0  5060.8    0.12       0  5239.3    0.05       0
Bank Sta=5010.4,5014.4
Exp/Cntr=0.3,0.1

Type RM Length L Ch R = 1,3143,284,284,284
BEGIN DESCRIPTION:
Clear Creek T 9 10.0
END DESCRIPTION:
XS GIS Cut Line= 3
      2774226.00      6803811.03      2774226.00      6804111.00
      2774266.31      6804420.82
#Sta/Elev= 30
  4695.1  508.46  4697.6  508.46  4715.1  502.98  4735.1  498.28  4745.1  493.41
  4755.1  491.54  4775.1  485.71  4855.1  472.35  4915.1  465.27  4925.1  463.00
  4934.9  462.12  4970.1  458.51  4982.8  457.52  4983.1  457.50  4983.3  457.00
  4986.8  457.00  4987.1  457.50  5032.1  458.22  5045.5  457.57  5055.6  457.91
  5111.2  465.76  5116.2  465.47  5136.3  468.10  5156.4  469.80  5185.2  474.51
  5190.3  474.45  5196.8  476.95  5227.0  483.84  5269.8  491.63  5307.5  497.99
#Mann=7,-1,0
  4695.1    0.12       0  4934.9     0.1       0  4970.1    0.12       0
  4982.8     0.1       0  4983.1    0.07       0  4987.1     0.1       0
  5269.8    0.12       0
Bank Sta=4983.1,4987.1
Exp/Cntr=0.3,0.1

Type RM Length L Ch R = 1,2859,256,256,256
BEGIN DESCRIPTION:
Clear Creek T 9 9.0
END DESCRIPTION:
XS GIS Cut Line= 3
      2774076.00      6803910.99      2773976.00      6804211.00
      2774117.42      6804493.33
#Sta/Elev= 30
  4691.9  480.39  4706.4  478.02  4765.7  469.84  4786.8  468.56  4828.9  464.08
  4850.0  460.74  4860.6  458.39  4892.2  455.36  4934.3  456.30  4997.6  455.48
  5003.5  454.38  5003.7  453.88  5007.2  453.88  5007.5  454.38  5010.9  454.38
  5016.5  456.53  5022.1  457.14  5030.5  461.42  5111.5  469.02  5178.5  477.21
  5187.1  479.32  5200.9  480.29  5217.6  482.83  5245.6  485.58  5254.2  487.52
  5276.6  490.89  5290.3  494.21  5307.0  497.15  5319.8  501.00  5323.9  501.00
#Mann=4,-1,0
  4691.9    0.12       0  4706.4     0.1       0  5003.5    0.07       0
  5007.5     0.1       0
Bank Sta=5003.5,5007.5
Exp/Cntr=0.3,0.1

Type RM Length L Ch R = 1,2603,281,281,281
BEGIN DESCRIPTION:
Clear Creek T 9 8.0
END DESCRIPTION:
XS GIS Cut Line= 3
      2773561.70      6803890.70      2773776.00      6804261.00
      2773996.22      6804607.02
#Sta/Elev= 30
  4576.0  477.88  4631.4  475.97  4637.2  475.01  4653.0  474.40  4658.7  472.94
  4690.3  471.51  4711.8  469.80  4717.6  468.50  4733.3  468.00  4754.9  465.17
  4829.5  459.50  4856.8  456.05  4881.4  456.18  4952.9  453.59  4999.0  453.37
  4999.2  452.87  5003.0  453.37  5011.5  453.40  5017.4  455.55  5026.7  453.64
  5032.6  457.49  5047.9  453.82  5053.8  457.80  5063.1  457.72  5075.0  463.04
  5229.1  475.88  5284.6  482.00  5323.9  486.20  5402.6  499.52  5414.0  503.27
#Mann=5,-1,0
  4576.0    0.12       0  4881.4     0.1       0  4999.0    0.07       0
  5003.0     0.1       0  5284.6    0.12       0
Bank Sta=4999,5003
Exp/Cntr=0.3,0.1

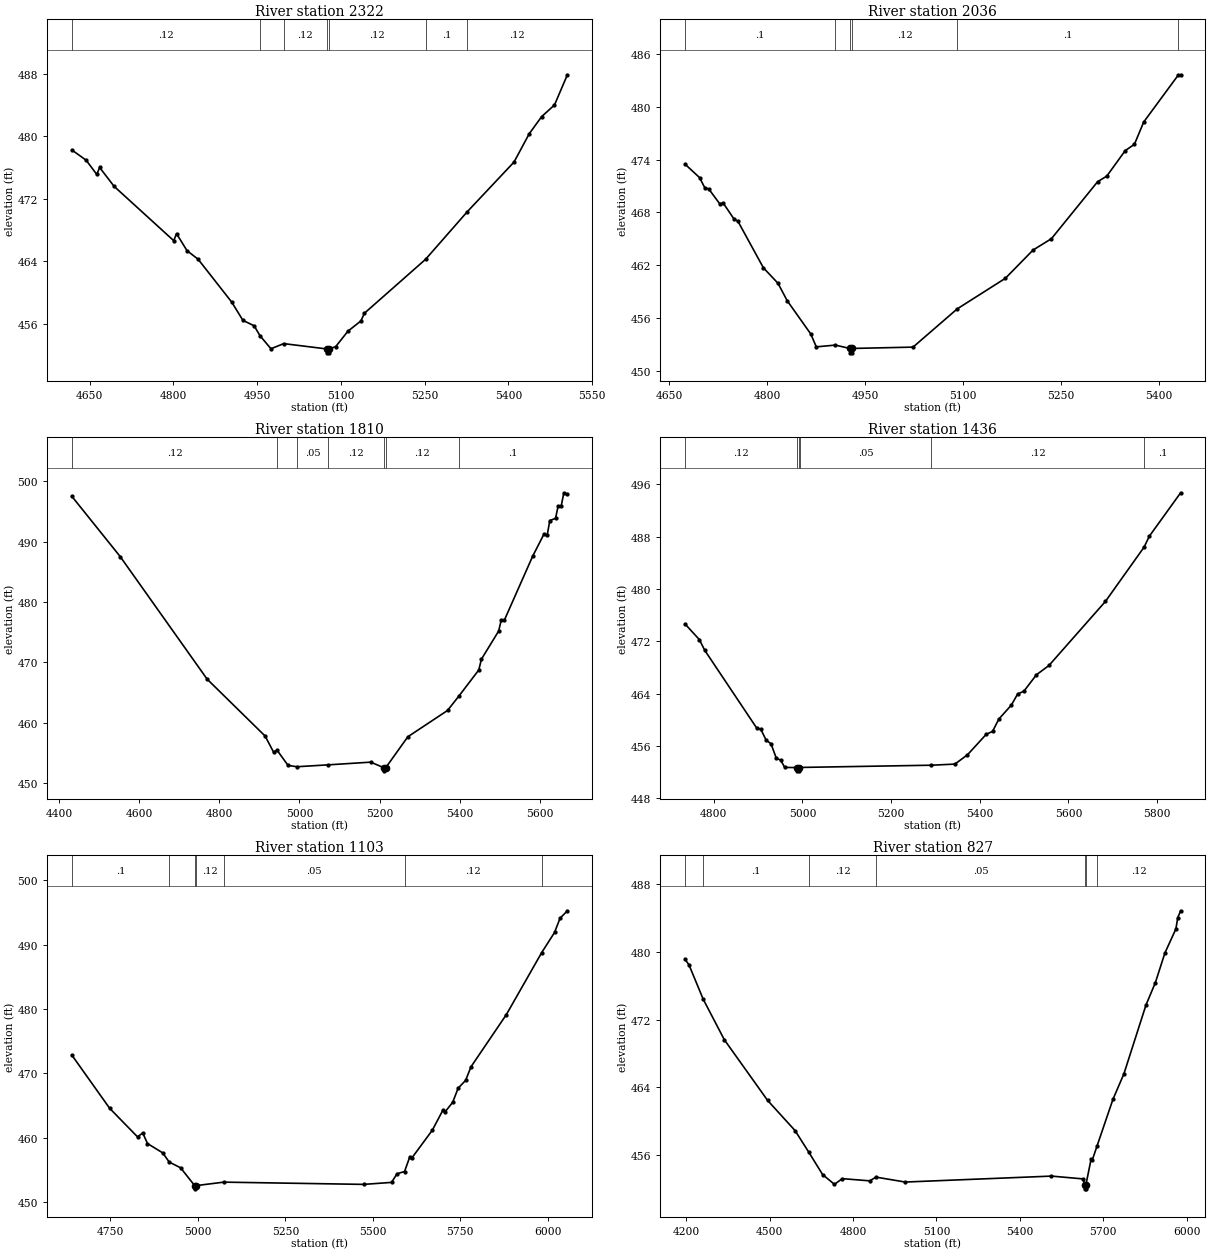
Type RM Length L Ch R = 1,2322,286,286,286
BEGIN DESCRIPTION:
Clear Creek T 9 7.0
END DESCRIPTION:
XS GIS Cut Line= 3
      2773497.38      6803875.30      2773526.00      6804261.00
      2773801.01      6804679.46
#Sta/Elev= 30
  4618.2  478.24  4644.0  476.92  4663.0  475.10  4668.1  475.99  4694.1  473.57
  4800.8  466.62  4805.8  467.52  4824.5  465.35  4844.5  464.24  4904.7  458.75
  4924.7  456.42  4944.8  455.72  4955.2  454.46  4974.9  452.78  4997.7  453.44
  5074.8  452.76  5075.0  452.26  5078.5  452.26  5078.8  452.76  5090.8  453.05
  5112.7  455.03  5136.1  456.35  5142.1  457.32  5251.7  464.23  5326.6  470.34
  5410.2  476.69  5437.3  480.30  5459.7  482.51  5482.6  483.99  5505.7  487.86
#Mann=7,-1,0
  4618.2    0.12       0  4955.2     0.1       0  4997.7    0.12       0
  5074.8    0.07       0  5078.8    0.12       0  5251.7     0.1       0
  5326.6    0.12       0
Bank Sta=5074.8,5078.8
Exp/Cntr=0.3,0.1

Type RM Length L Ch R = 1,2036,226,226,226
BEGIN DESCRIPTION:
Clear Creek T 9 6.0
END DESCRIPTION:
XS GIS Cut Line= 3
      2773226.01      6804161.02      2773376.00      6804461.00
      2773676.03      6804761.03
#Sta/Elev= 30
  4673.9  473.49  4696.2  471.96  4704.6  470.75  4710.2  470.68  4727.0  468.99
  4732.6  469.05  4749.3  467.22  4754.9  467.01  4794.1  461.70  4816.4  459.95
  4830.4  457.98  4866.7  454.18  4875.1  452.72  4904.4  452.92  4926.2  452.54
  4926.5  452.04  4930.0  452.04  4930.2  452.54  5023.4  452.69  5091.2  457.04
  5164.9  460.51  5207.3  463.72  5235.6  465.02  5306.3  471.49  5320.4  472.13
  5348.7  475.03  5362.8  475.75  5377.0  478.28  5430.3  483.65  5433.6  483.65
#Mann=6,-1,0
  4673.9     0.1       0  4904.4    0.12       0  4926.2    0.07       0
  4930.2    0.12       0  5091.2     0.1       0  5430.3    0.12       0
Bank Sta=4926.2,4930.2
Exp/Cntr=0.3,0.1

Type RM Length L Ch R = 1,1810,374,374,374
BEGIN DESCRIPTION:
Clear Creek T 9 5.0
END DESCRIPTION:
XS GIS Cut Line= 3
      2772865.18      6803984.32      2773176.00      6804461.00
      2773599.42      6804979.26
#Sta/Elev= 30
  4431.0  497.52  4551.9  487.54  4769.2  467.24  4914.1  457.82  4935.2  455.16
  4944.2  455.45  4971.4  452.96  4993.6  452.74  5071.3  453.05  5178.1  453.50
  5211.3  452.56  5211.5  452.06  5215.3  452.56  5270.7  457.70  5369.8  462.05
  5398.4  464.45  5448.0  468.76  5454.5  470.54  5497.6  475.20  5504.0  476.99
  5511.9  477.01  5582.3  487.55  5611.0  491.28  5618.9  491.07  5625.4  493.50
  5639.7  493.85  5646.2  495.89  5654.1  495.97  5660.5  498.09  5669.3  497.81
#Mann=7,-1,0
  4431.0    0.12       0  4944.2     0.1       0  4993.6    0.05       0
  5071.3    0.12       0  5211.3    0.03       0  5215.3    0.12       0
  5398.4     0.1       0
Bank Sta=5211.3,5215.3
Exp/Cntr=0.3,0.1

Type RM Length L Ch R = 1,1436,333,333,333
BEGIN DESCRIPTION:
Clear Creek T 9 4.0
END DESCRIPTION:
XS GIS Cut Line= 3
      2772775.98      6804410.96      2772876.00      6804661.00
      2773475.98      6805260.98
#Sta/Elev= 30
  4735.2  474.67  4767.6  472.27  4779.7  470.64  4896.8  458.76  4906.2  458.56
  4918.3  456.88  4929.1  456.36  4941.2  454.11  4950.7  453.87  4960.1  452.73
  4987.7  452.71  4987.9  452.21  4991.4  452.21  4991.7  452.71  4995.4  452.73
  5290.8  453.07  5343.9  453.24  5372.2  454.66  5414.6  457.80  5428.8  458.24
  5442.9  460.12  5471.2  462.26  5485.3  463.95  5499.5  464.39  5527.8  466.90
  5556.0  468.32  5683.3  478.11  5770.7  486.43  5782.3  488.08  5853.0  494.73
#Mann=6,-1,0
  4735.2    0.12       0  4987.7    0.03       0  4991.7    0.12       0
  4995.4    0.05       0  5290.8    0.12       0  5770.7     0.1       0
Bank Sta=4987.7,4991.7
Exp/Cntr=0.3,0.1

Type RM Length L Ch R = 1,1103,276,276,276
BEGIN DESCRIPTION:
Clear Creek T 9 3.0
END DESCRIPTION:
XS GIS Cut Line= 3
      2772375.99      6804460.99      2772576.00      6804761.00
      2773479.10      6805306.83
#Sta/Elev= 30
  4639.9  472.86  4748.1  464.59  4827.7  460.16  4842.7  460.76  4856.2  459.12
  4899.8  457.67  4918.2  456.25  4950.9  455.35  4991.0  452.59  4991.2  452.09
  4995.0  452.59  5074.3  453.13  5473.9  452.78  5553.5  453.09  5569.0  454.43
  5590.6  454.78  5605.8  457.10  5611.7  456.90  5669.9  461.19  5700.9  464.38
  5706.7  464.06  5728.1  465.52  5743.6  467.71  5765.0  468.92  5780.5  471.04
  5881.4  479.13  5982.2  488.74  6019.1  491.88  6034.7  494.08  6055.7  495.24
#Mann=7,-1,0
  4639.9     0.1       0  4918.2    0.12       0  4991.0    0.07       0
  4995.0    0.12       0  5074.3    0.05       0  5590.6    0.12       0
  5982.2     0.1       0
Bank Sta=4991,4995
Exp/Cntr=0.3,0.1

Type RM Length L Ch R = 1,827,392,392,392
BEGIN DESCRIPTION:
Clear Creek T 9 2.0
END DESCRIPTION:
XS GIS Cut Line= 3
      2771876.02      6804411.02      2772476.00      6805011.00
      2773376.02      6805261.01
#Sta/Elev= 30
  4195.8  479.08  4209.9  478.45  4261.2  474.39  4337.2  469.62  4492.8  462.48
  4591.8  458.92  4641.4  456.36  4690.7  453.75  4733.2  452.60  4761.5  453.27
  4860.5  453.01  4882.6  453.45  4987.7  452.87  5513.9  453.57  5627.1  453.24
  5633.9  452.57  5634.1  452.07  5637.6  452.07  5637.9  452.57  5656.1  455.53
  5661.3  455.52  5677.7  457.11  5735.0  462.61  5774.4  465.61  5853.8  473.71
  5887.6  476.35  5921.8  479.83  5961.3  482.66  5968.0  483.98  5978.4  484.80
#Mann=7,-1,0
  4195.8    0.12       0  4261.2     0.1       0  4641.4    0.12       0
  4882.6    0.05       0  5633.9    0.03       0  5637.9    0.05       0
  5677.7    0.12       0
Bank Sta=5633.9,5637.9
Exp/Cntr=0.3,0.1

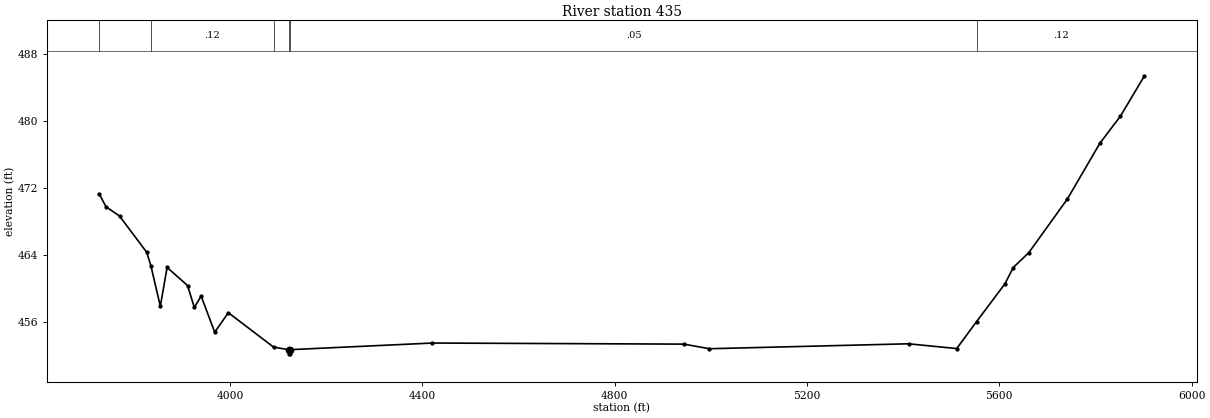
Type RM Length L Ch R = 1,435,0,0,0
BEGIN DESCRIPTION:
Clear Creek T 9 1.0
END DESCRIPTION:
XS GIS Cut Line= 3
      2771575.99      6804460.99      2772476.00      6805361.00
      2773376.00      6805411.00
#Sta/Elev= 30
  3727.7  471.28  3741.9  469.72  3770.1  468.61  3826.7  464.28  3835.3  462.68
  3855.0  457.84  3869.1  462.47  3911.6  460.31  3925.7  457.69  3939.9  459.05
  3968.1  454.73  3996.4  457.07  4090.6  452.95  4121.7  452.65  4121.9  452.15
  4125.4  452.15  4125.7  452.65  4420.7  453.44  4943.9  453.31  4997.0  452.76
  5411.1  453.35  5511.3  452.78  5552.5  455.99  5611.5  460.50  5629.0  462.46
  5661.5  464.25  5741.7  470.66  5809.3  477.32  5851.8  480.53  5901.9  485.36
#Mann=6,-1,0
  3727.7     0.1       0  3835.3    0.12       0  4090.6    0.05       0
  4121.7    0.03       0  4125.7    0.05       0  5552.5    0.12       0
Bank Sta=4121.7,4125.7
Exp/Cntr=0.3,0.1

Chan Stop Cuts=-1