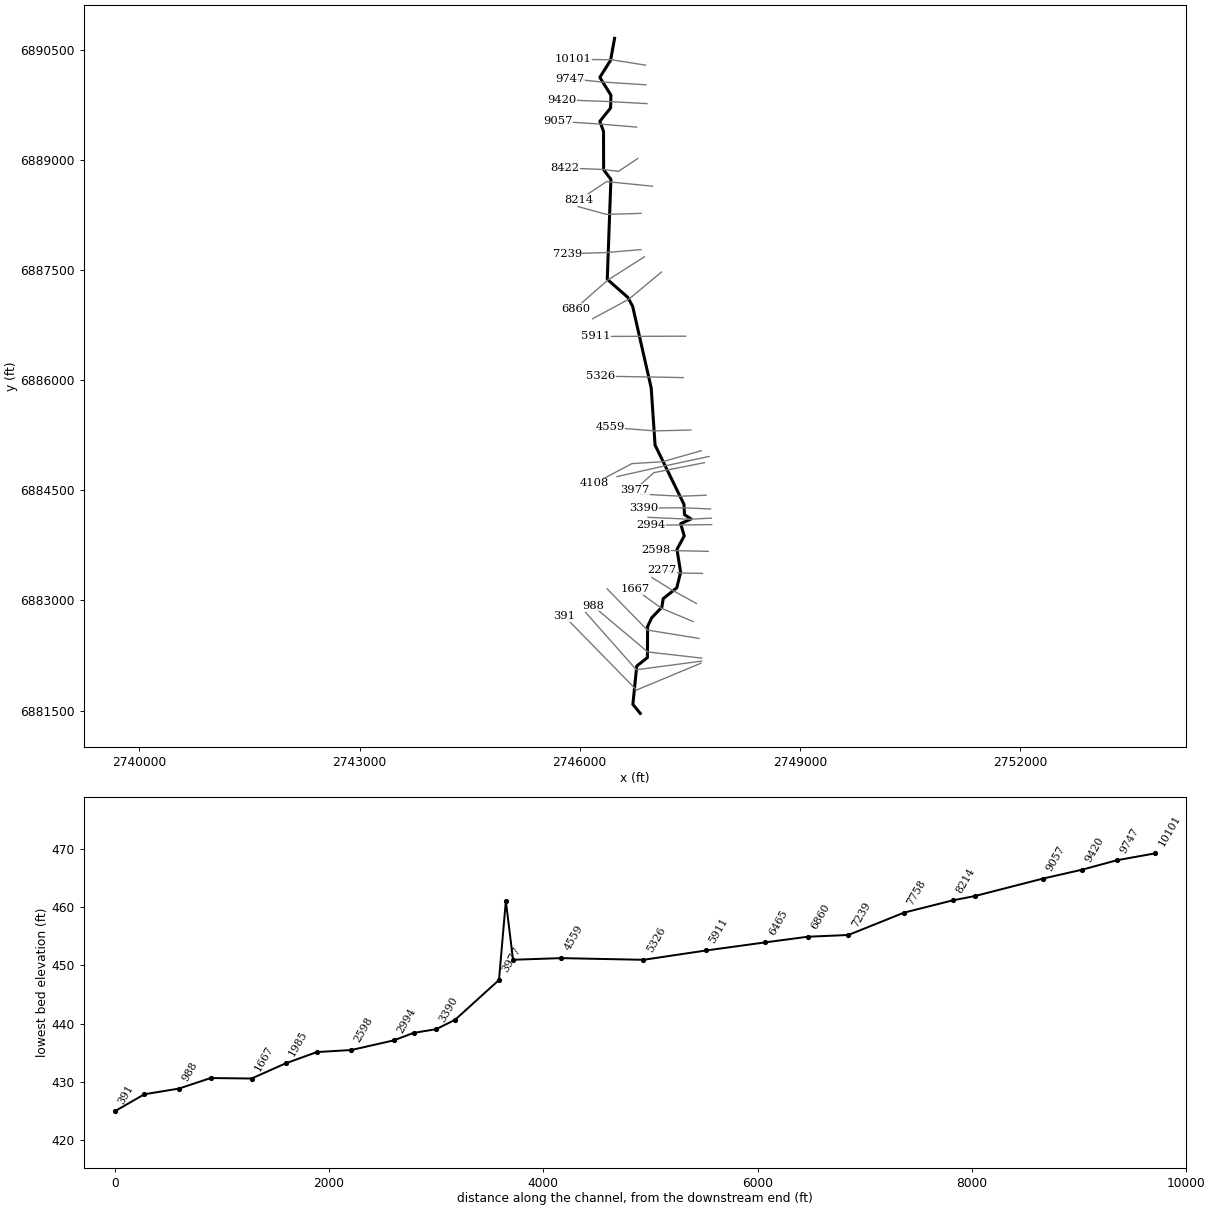
--- Coppers Branch North.prj (project) ---

Proj Title=Coppers Branch North Base Level Engineering
Current Plan=p01
Default Exp/Contr=0.3,0.1
English Units
Geom File=g01
Flow File=f01
Plan File=p01
BEGIN DESCRIPTION:
Coppers Branch North
END DESCRIPTION:

--- Coppers Branch North.p01 (plan) ---

Plan Title=Multiple Run
Short Identifier=Multiple
Geom File=g01
Flow File=f01
Subcritical Flow
K Sum by GR= 0
Std Step Tol= 0.01
Critical Tol= 0.01
Num of Std Step Trials= 20
Max Error Tol= 0.3
Flow Tol Ratio= 0.001
Split Flow NTrial= 30
Split Flow Tol= 0.02
Split Flow Ratio= 0.02
Log Output Level= 0
Friction Slope Method= 1
Unsteady Friction Slope Method= 2
Unsteady Bridges Friction Slope Method= 1
Parabolic Critical Depth
Global Vel Dist=  1 , 1 , 1
Global Log Level= 0
CheckData=True
Encroach Param= -1, 0, 0, 0
BEGIN DESCRIPTION:
Multiple Run
END DESCRIPTION:

--- Coppers Branch North.f01 (steady flow) ---

Flow Title=Multiple
Number of Profiles=7
Profile Names=10-year,25-year,50-year,1pct_min,100-year,1pct_plu,500-year
River Rch & RM= Coppers Branch N,Reach-1,10101
     439     578     688     407     813    1622    1137
River Rch & RM= Coppers Branch N,Reach-1,6860
     525     695     831     494     985    1966    1387
Boundary for River Rch & Prof#=Coppers Branch N,Reach-1,1
Up Type=0
Dn Type=3
Dn Slope=0.005
Boundary for River Rch & Prof#=Coppers Branch N,Reach-1,2
Up Type=0
Dn Type=3
Dn Slope=0.005
Boundary for River Rch & Prof#=Coppers Branch N,Reach-1,3
Up Type=0
Dn Type=3
Dn Slope=0.005
Boundary for River Rch & Prof#=Coppers Branch N,Reach-1,4
Up Type=0
Dn Type=3
Dn Slope=0.005
Boundary for River Rch & Prof#=Coppers Branch N,Reach-1,5
Up Type=0
Dn Type=3
Dn Slope=0.005
Boundary for River Rch & Prof#=Coppers Branch N,Reach-1,6
Up Type=0
Dn Type=3
Dn Slope=0.005
Boundary for River Rch & Prof#=Coppers Branch N,Reach-1,7
Up Type=0
Dn Type=3
Dn Slope=0.005

--- Coppers Branch North.g01 (geometry) ---

Geom Title=Existing Conditions

River Reach=Coppers Branch N,Reach-1
Reach XY= 30
      2746476.00      6890661.00      2746422.38      6890362.50
      2746275.34      6890129.24      2746426.30      6889886.12
      2746422.46      6889712.46      2746275.29      6889529.27
      2746325.79      6889392.73      2746327.21      6888870.59
      2746426.19      6888738.35      2746376.66      6887376.83
      2746656.22      6887131.09      2746722.24      6887009.44
      2746975.32      6885897.08      2747028.26      6885116.94
      2747422.24      6884309.44      2747429.29      6884169.01
      2747519.08      6884110.96      2747376.65      6884046.51
      2747426.19      6883879.43      2747326.67      6883697.09
      2747376.38      6883383.81      2747324.35      6883172.84
      2747139.33      6883024.63      2747120.54      6882908.34
      2746982.06      6882763.23      2746926.51      6882645.79
      2746924.15      6882222.14      2746778.17      6882105.56
      2746725.79      6881583.68      2746826.00      6881461.00

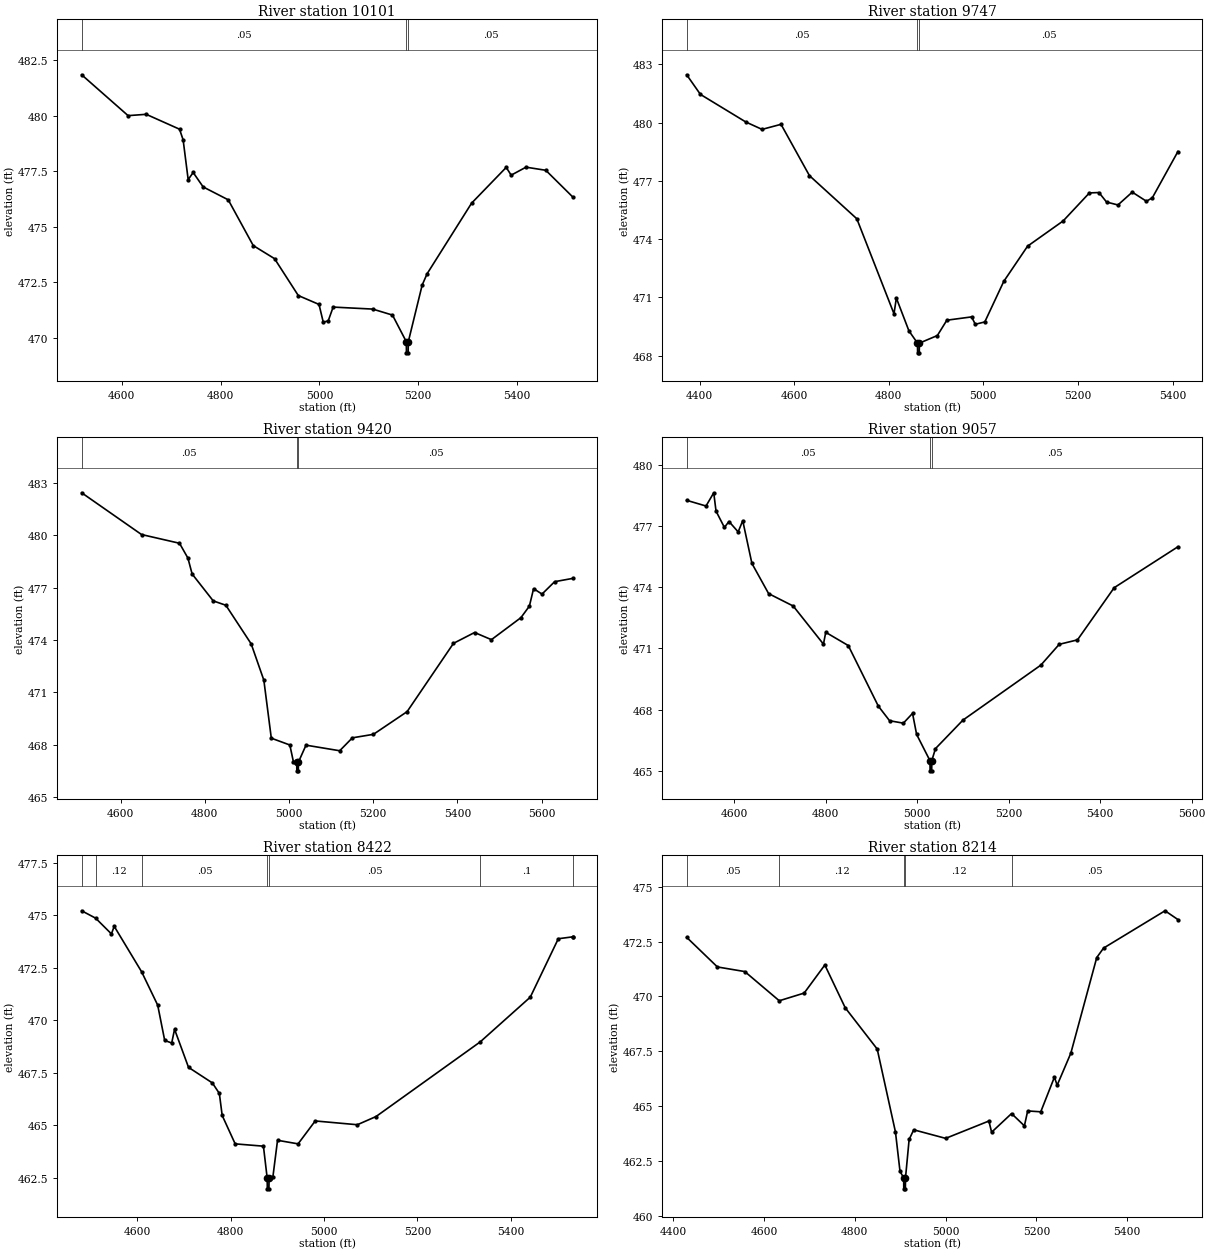
Type RM Length L Ch R = 1,10101,354,354,354
BEGIN DESCRIPTION:
Coppers Branch North 2202
END DESCRIPTION:
XS GIS Cut Line= 3
      2746898.72      6890295.43      2746428.23      6890369.85
      2745911.08      6890373.01
#Sta/Elev= 30
  4519.2  481.84  4613.1  480.00  4649.7  480.06  4717.1  479.39  4724.4  478.91
  4734.6  477.12  4744.7  477.44  4764.9  476.79  4815.6  476.21  4866.2  474.15
  4909.3  473.56  4957.3  471.90  4999.2  471.50  5007.8  470.70  5017.8  470.76
  5027.8  471.38  5107.8  471.29  5147.8  471.02  5175.8  469.82  5176.0  469.32
  5179.5  469.32  5179.8  469.82  5207.8  472.37  5217.8  472.88  5307.8  476.06
  5377.8  477.67  5387.8  477.32  5417.8  477.68  5457.8  477.54  5512.7  476.33
#Mann=3,-1,0
  4519.2    0.05       0  5175.8    0.04       0  5179.8    0.05       0
Bank Sta=5175.8,5179.8
Exp/Cntr=0.3,0.1

Type RM Length L Ch R = 1,9747,327,327,327
BEGIN DESCRIPTION:
Coppers Branch North 2201
END DESCRIPTION:
XS GIS Cut Line= 3
      2746905.08      6890028.03      2746281.47      6890067.59
      2745869.93      6890112.12
#Sta/Elev= 30
  4372.6  482.46  4401.7  481.45  4497.7  480.03  4532.0  479.65  4572.1  479.91
  4632.2  477.27  4732.4  475.05  4811.0  470.16  4816.0  470.97  4842.6  469.28
  4860.7  468.65  4860.9  468.15  4864.4  468.15  4864.7  468.65  4902.7  469.04
  4922.8  469.83  4975.1  470.00  4982.9  469.62  5003.0  469.74  5043.2  471.83
  5093.5  473.64  5168.8  474.94  5224.2  476.38  5244.4  476.40  5260.5  475.91
  5284.6  475.76  5314.8  476.42  5344.9  475.95  5357.3  476.13  5411.4  478.51
#Mann=3,-1,0
  4372.6    0.05       0  4860.7    0.04       0  4864.7    0.05       0
Bank Sta=4860.7,4864.7
Exp/Cntr=0.3,0.1

Type RM Length L Ch R = 1,9420,363,363,363
BEGIN DESCRIPTION:
Coppers Branch North 2200
END DESCRIPTION:
XS GIS Cut Line= 3
      2746917.90      6889771.17      2746424.37      6889798.27
      2745752.63      6889823.69
#Sta/Elev= 30
  4507.7  482.43  4649.8  480.04  4740.0  479.54  4760.0  478.69  4770.0  477.78
  4820.1  476.24  4850.1  475.99  4910.2  473.78  4940.3  471.70  4958.0  468.38
  5002.0  467.99  5010.4  467.04  5018.4  467.01  5018.6  466.51  5022.1  466.51
  5022.4  467.01  5040.4  467.98  5120.4  467.66  5150.5  468.40  5200.5  468.60
  5280.5  469.90  5390.6  473.81  5440.7  474.43  5480.7  474.02  5550.7  475.28
  5570.8  475.94  5580.8  476.94  5600.8  476.63  5630.8  477.34  5674.2  477.53
#Mann=3,-1,0
  4507.7    0.05       0  5018.4    0.04       0  5022.4    0.05       0
Bank Sta=5018.4,5022.4
Exp/Cntr=0.3,0.1

Type RM Length L Ch R = 1,9057,635,635,635
BEGIN DESCRIPTION:
Coppers Branch North 2199
END DESCRIPTION:
XS GIS Cut Line= 3
      2746778.18      6889450.89      2746273.27      6889493.30
      2745706.88      6889529.06
#Sta/Elev= 30
  4495.8  478.27  4538.1  477.99  4555.0  478.64  4560.0  477.74  4578.3  476.94
  4588.3  477.23  4608.4  476.72  4618.4  477.27  4638.5  475.17  4675.0  473.69
  4728.8  473.08  4794.9  471.21  4799.9  471.79  4849.2  471.14  4914.8  468.17
  4939.5  467.45  4969.6  467.33  4989.7  467.81  4998.6  466.78  5027.8  465.49
  5028.1  464.99  5031.6  464.99  5031.8  465.49  5039.8  466.08  5099.9  467.48
  5270.3  470.18  5310.4  471.20  5350.4  471.42  5430.6  473.98  5570.0  475.99
#Mann=3,-1,0
  4495.8    0.05       0  5027.8    0.05       0  5031.8    0.05       0
Bank Sta=5027.8,5031.8
Exp/Cntr=0.3,0.1

Type RM Length L Ch R = 1,8422,208,208,208
BEGIN DESCRIPTION:
Coppers Branch North 2198
END DESCRIPTION:
XS GIS Cut Line= 4
      2746791.26      6889023.18      2746528.90      6888847.61
      2746323.37      6888873.66      2745794.75      6888894.73
#Sta/Elev= 30
  4481.0  475.21  4510.8  474.86  4544.7  474.11  4550.7  474.47  4609.3  472.31
  4643.8  470.72  4658.8  469.04  4673.8  468.92  4679.9  469.57  4709.8  467.76
  4760.8  467.02  4775.8  466.52  4781.9  465.47  4809.7  464.12  4870.2  464.01
  4878.3  462.48  4878.5  461.98  4882.0  461.98  4882.3  462.48  4890.3  462.52
  4900.4  464.29  4944.4  464.12  4981.1  465.21  5071.3  465.03  5111.3  465.42
  5334.3  468.97  5441.6  471.10  5501.6  473.88  5532.6  473.97  5532.9  473.97
#Mann=7,-1,0
  4481.0    0.05       0  4510.8    0.12       0  4609.3    0.05       0
  4878.3    0.04       0  4882.3    0.05       0  5334.3     0.1       0
  5532.6    0.12       0
Bank Sta=4878.3,4882.3
Exp/Cntr=0.3,0.1

Type RM Length L Ch R = 1,8214,456,456,456
BEGIN DESCRIPTION:
Coppers Branch North 2196
END DESCRIPTION:
XS GIS Cut Line= 3
      2746993.37      6888645.58      2746366.95      6888708.45
      2745990.57      6888458.12
#Sta/Elev= 30
  4429.9  472.69  4497.6  471.34  4557.9  471.13  4633.8  469.80  4688.6  470.15
  4734.1  471.43  4779.0  469.48  4849.4  467.60  4889.6  463.82  4899.6  462.03
  4907.7  461.73  4907.9  461.23  4911.4  461.23  4911.7  461.73  4919.7  463.48
  4929.8  463.92  5000.1  463.53  5095.3  464.32  5101.3  463.81  5145.2  464.66
  5173.5  464.10  5180.7  464.78  5209.5  464.74  5239.6  466.32  5245.6  465.95
  5275.7  467.41  5332.8  471.77  5347.8  472.20  5483.1  473.90  5511.5  473.50
#Mann=5,-1,0
  4429.9    0.05       0  4633.8    0.12       0  4907.7    0.07       0
  4911.7    0.12       0  5145.2    0.05       0
Bank Sta=4907.7,4911.7
Exp/Cntr=0.3,0.1

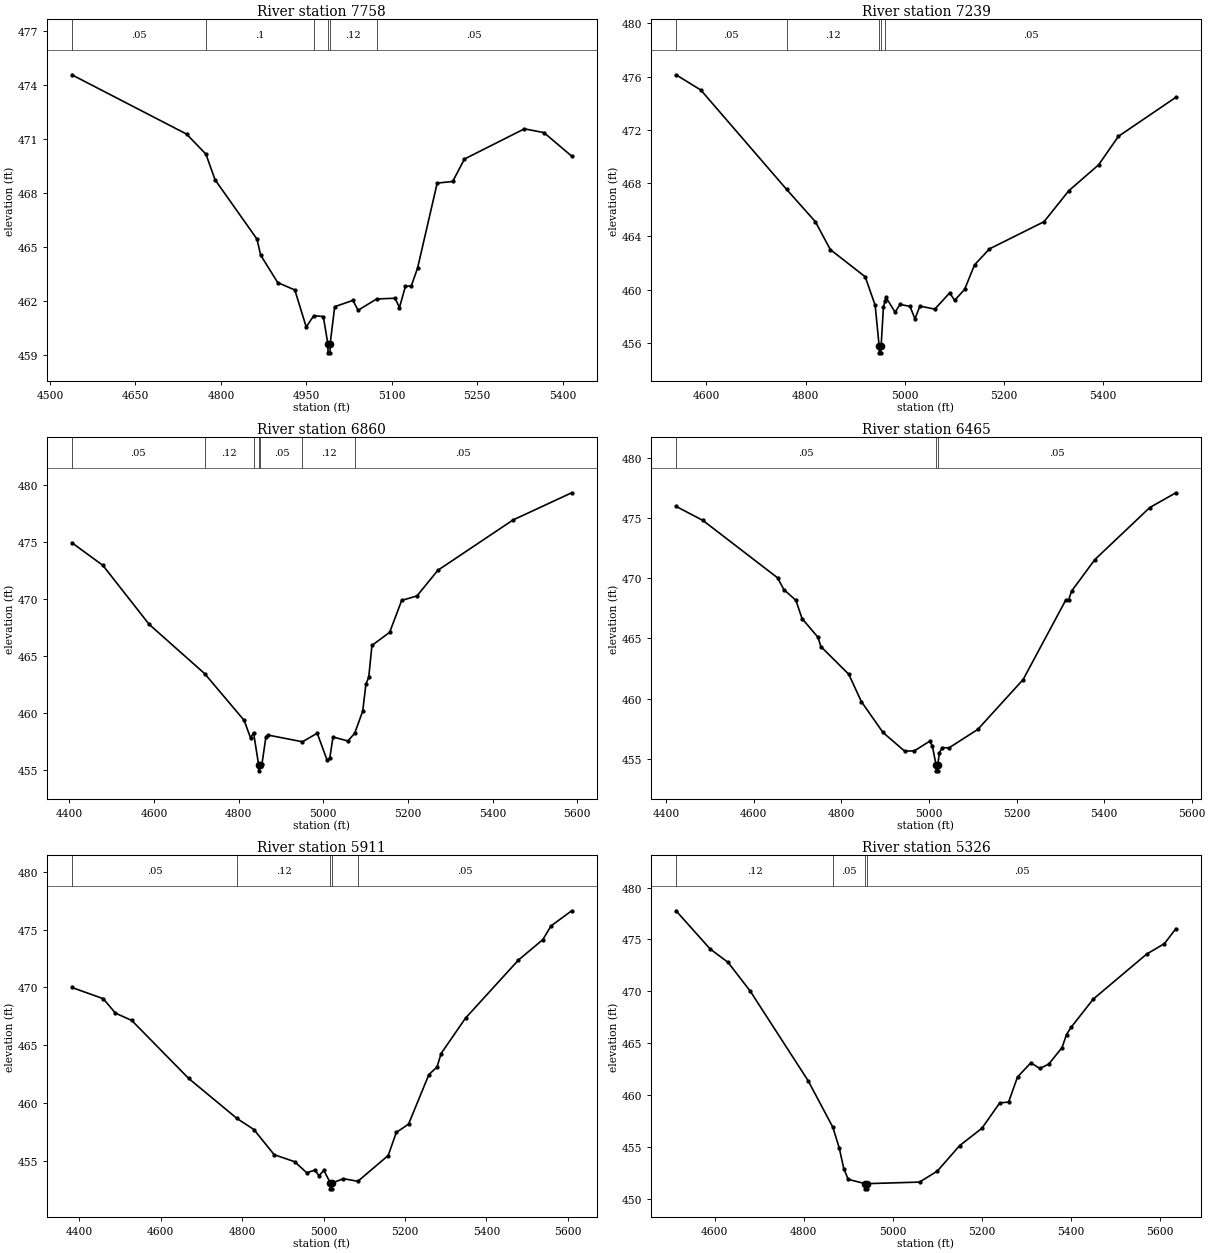
Type RM Length L Ch R = 1,7758,519,519,519
BEGIN DESCRIPTION:
Coppers Branch North 2197
END DESCRIPTION:
XS GIS Cut Line= 3
      2746837.24      6888275.55      2746364.49      6888261.59
      2745974.60      6888369.12
#Sta/Elev= 30
  4538.3  474.59  4739.6  471.29  4773.7  470.17  4789.6  468.75  4863.3  465.44
  4869.7  464.55  4899.7  463.02  4929.7  462.61  4949.7  460.55  4963.0  461.18
  4979.7  461.13  4987.7  459.61  4988.0  459.11  4991.5  459.11  4991.7  459.61
  4999.7  461.68  5031.7  462.03  5040.8  461.48  5073.3  462.11  5105.7  462.15
  5113.4  461.63  5123.8  462.81  5134.2  462.84  5145.2  463.83  5179.6  468.56
  5206.8  468.65  5227.5  469.90  5332.6  471.58  5367.0  471.37  5415.7  470.06
#Mann=6,-1,0
  4538.3    0.05       0  4773.7     0.1       0  4963.0    0.12       0
  4987.7    0.07       0  4991.7    0.12       0  5073.3    0.05       0
Bank Sta=4987.7,4991.7
Exp/Cntr=0.3,0.1

Type RM Length L Ch R = 1,7239,379,379,379
BEGIN DESCRIPTION:
Coppers Branch North 2195
END DESCRIPTION:
XS GIS Cut Line= 3
      2746835.88      6887781.96      2746374.77      6887742.30
      2745830.29      6887724.03
#Sta/Elev= 30
  4538.7  476.13  4588.8  474.98  4761.5  467.53  4819.6  465.10  4849.7  463.01
  4920.0  460.97  4940.1  458.83  4948.1  455.76  4948.3  455.26  4951.8  455.26
  4952.1  455.76  4956.7  458.67  4959.8  459.15  4961.7  459.44  4980.2  458.31
  4990.2  458.89  5010.3  458.75  5020.3  457.81  5030.3  458.77  5060.3  458.54
  5090.3  459.76  5100.3  459.20  5120.4  460.02  5140.4  461.86  5170.4  463.06
  5280.4  465.10  5330.5  467.43  5390.5  469.37  5430.5  471.51  5546.3  474.44
#Mann=5,-1,0
  4538.7    0.05       0  4761.5    0.12       0  4948.1    0.05       0
  4952.1    0.12       0  4959.8    0.05       0
Bank Sta=4948.1,4952.1
Exp/Cntr=0.3,0.1

Type RM Length L Ch R = 1,6860,395,395,395
BEGIN DESCRIPTION:
Coppers Branch North 2194
END DESCRIPTION:
XS GIS Cut Line= 3
      2746884.45      6887684.40      2746383.81      6887365.85
      2745942.02      6886978.57
#Sta/Elev= 30
  4406.1  474.97  4479.5  472.98  4588.7  467.81  4719.8  463.49  4813.1  459.39
  4828.3  457.85  4835.4  458.31  4847.5  455.46  4847.7  454.96  4851.5  455.46
  4855.4  455.60  4864.7  457.96  4870.6  458.09  4951.0  457.51  4985.8  458.26
  5008.8  455.93  5015.5  456.08  5023.1  457.93  5058.2  457.58  5074.3  458.25
  5093.3  460.20  5100.9  462.57  5107.5  463.17  5115.1  465.96  5156.9  467.11
  5185.4  469.91  5221.4  470.30  5270.8  472.55  5448.2  476.96  5587.0  479.35
#Mann=7,-1,0
  4406.1    0.05       0  4719.8    0.12       0  4835.4    0.05       0
  4847.5    0.07       0  4851.5    0.05       0  4951.0    0.12       0
  5074.3    0.05       0
Bank Sta=4847.5,4851.5
Exp/Cntr=0.3,0.1

Type RM Length L Ch R = 1,6465,554,554,554
BEGIN DESCRIPTION:
Coppers Branch North 2193
END DESCRIPTION:
XS GIS Cut Line= 3
      2747116.11      6887476.98      2746673.88      6887107.86
      2746176.45      6886838.74
#Sta/Elev= 30
  4422.4  475.98  4483.8  474.81  4654.3  470.04  4668.6  469.06  4696.1  468.17
  4710.2  466.65  4746.7  465.09  4753.2  464.32  4816.9  462.02  4845.6  459.75
  4895.0  457.18  4944.5  455.63  4966.6  455.65  5002.0  456.46  5007.7  456.07
  5016.2  454.49  5016.5  453.99  5020.0  453.99  5020.2  454.49  5023.9  455.48
  5030.1  455.92  5045.8  455.90  5111.4  457.43  5215.1  461.58  5313.1  468.23
  5318.8  468.18  5325.7  468.93  5378.8  471.55  5504.3  475.88  5564.0  477.11
#Mann=3,-1,0
  4422.4    0.05       0  5016.2    0.04       0  5020.2    0.05       0
Bank Sta=5016.2,5020.2
Exp/Cntr=0.3,0.1

Type RM Length L Ch R = 1,5911,585,585,585
BEGIN DESCRIPTION:
Coppers Branch North 2192
END DESCRIPTION:
XS GIS Cut Line= 3
      2747443.08      6886601.62      2746826.93      6886599.79
      2746215.19      6886598.07
#Sta/Elev= 30
  4381.7  470.00  4458.8  469.03  4488.8  467.78  4528.8  467.15  4668.8  462.13
  4787.2  458.68  4828.8  457.72  4878.8  455.54  4928.8  454.94  4958.8  453.98
  4978.8  454.21  4988.8  453.72  5000.8  454.19  5016.8  453.09  5017.0  452.59
  5020.5  452.59  5020.8  453.09  5048.8  453.47  5084.2  453.24  5158.8  455.47
  5178.8  457.47  5208.8  458.18  5258.8  462.47  5278.8  463.12  5288.8  464.29
  5348.8  467.35  5478.8  472.37  5538.8  474.14  5558.8  475.32  5609.6  476.63
#Mann=5,-1,0
  4381.7    0.05       0  4787.2    0.12       0  5016.8    0.07       0
  5020.8    0.12       0  5084.2    0.05       0
Bank Sta=5016.8,5020.8
Exp/Cntr=0.3,0.1

Type RM Length L Ch R = 1,5326,767,767,767
BEGIN DESCRIPTION:
Coppers Branch North 2191
END DESCRIPTION:
XS GIS Cut Line= 3
      2747412.56      6886037.19      2746919.47      6886046.11
      2746290.44      6886056.94
#Sta/Elev= 30
  4513.5  477.76  4590.1  474.08  4630.1  472.80  4680.1  470.02  4810.1  461.39
  4865.6  456.91  4880.1  454.89  4890.1  452.93  4900.1  451.89  4938.1  451.48
  4938.4  450.98  4941.9  450.98  4942.1  451.48  5060.2  451.63  5100.2  452.69
  5150.2  455.14  5200.2  456.81  5240.2  459.25  5260.2  459.34  5280.2  461.75
  5310.2  463.12  5330.2  462.57  5350.2  462.99  5380.2  464.58  5390.2  465.84
  5400.2  466.52  5450.2  469.25  5570.2  473.59  5610.2  474.60  5635.8  476.04
#Mann=4,-1,0
  4513.5    0.12       0  4865.6    0.05       0  4938.1    0.03       0
  4942.1    0.05       0
Bank Sta=4938.1,4942.1
Exp/Cntr=0.3,0.1

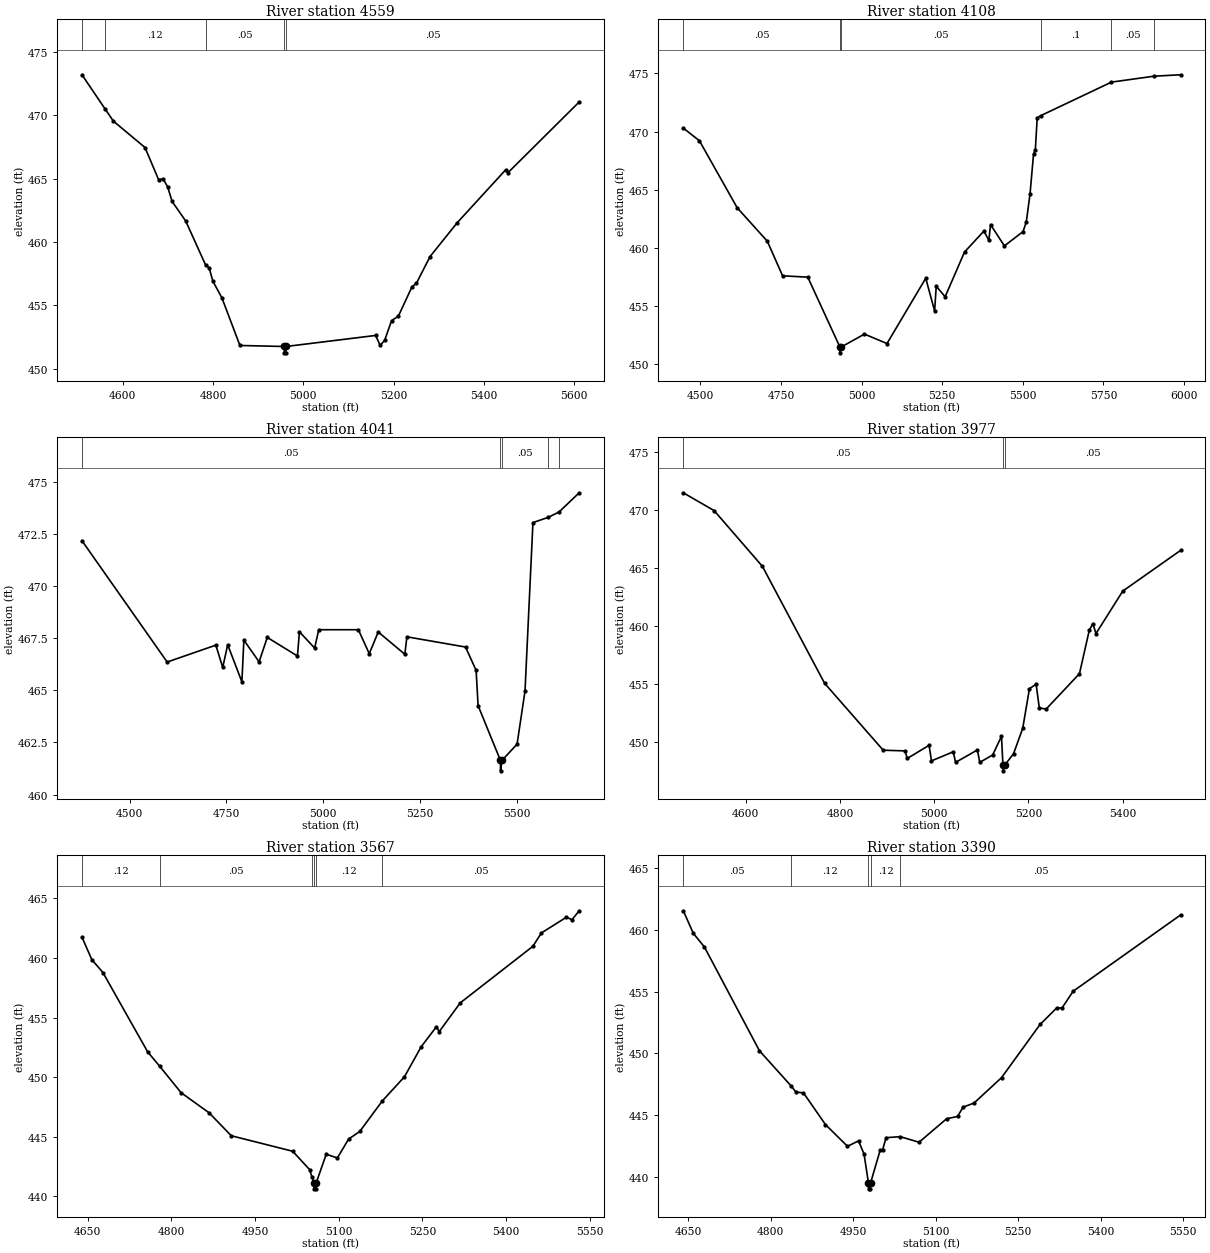
Type RM Length L Ch R = 1,4559,451,451,451
BEGIN DESCRIPTION:
Coppers Branch North 2190
END DESCRIPTION:
XS GIS Cut Line= 3
      2747515.58      6885322.70      2747022.97      6885310.85
      2746416.70      6885358.61
#Sta/Elev= 30
  4510.1  473.17  4561.8  470.45  4579.7  469.52  4649.7  467.44  4679.7  464.91
  4689.7  464.97  4699.7  464.35  4709.7  463.19  4739.7  461.66  4783.7  458.20
  4791.8  457.96  4799.8  456.92  4819.8  455.61  4859.8  451.85  4957.8  451.77
  4958.1  451.27  4961.6  451.27  4961.8  451.77  5160.3  452.64  5170.3  451.85
  5180.4  452.27  5195.6  453.81  5210.5  454.15  5240.6  456.46  5250.6  456.75
  5280.7  458.85  5340.9  461.52  5448.3  465.69  5453.3  465.46  5611.0  471.03
#Mann=5,-1,0
  4510.1    0.05       0  4561.8    0.12       0  4783.7    0.05       0
  4957.8    0.03       0  4961.8    0.05       0
Bank Sta=4957.8,4961.8
Exp/Cntr=0.3,0.1

Type RM Length L Ch R = 1,4108,67,67,67
BEGIN DESCRIPTION:
Coppers Branch North 2189
END DESCRIPTION:
XS GIS Cut Line= 4
      2747656.68      6885040.36      2747127.72      6884889.95
      2746713.00      6884864.97      2746202.76      6884595.76
#Sta/Elev= 30
  4447.0  470.30  4497.0  469.21  4614.2  463.45  4707.6  460.58  4754.9  457.61
  4833.1  457.49  4932.7  451.49  4932.9  450.99  4936.7  451.49  5008.7  452.60
  5078.8  451.79  5199.0  457.40  5226.5  454.58  5231.5  456.71  5259.1  455.81
  5319.2  459.65  5379.3  461.45  5394.8  460.65  5399.9  462.01  5442.9  460.18
  5500.5  461.40  5510.8  462.22  5522.5  464.66  5533.3  468.06  5538.9  468.45
  5544.7  471.19  5556.6  471.38  5775.1  474.25  5907.3  474.76  5989.3  474.88
#Mann=6,-1,0
  4447.0    0.05       0  4932.7    0.04       0  4936.7    0.05       0
  5556.6     0.1       0  5775.1    0.05       0  5907.3    0.12       0
Bank Sta=4932.7,4936.7
Exp/Cntr=0.3,0.1

Type RM Length L Ch R = 1,4041,64,64,64
BEGIN DESCRIPTION:
Coppers Branch North 2187
END DESCRIPTION:
XS GIS Cut Line= 3
      2747764.14      6884962.41      2747146.76      6884830.66
      2746509.32      6884688.39
#Sta/Elev= 30
  4376.7  472.18  4596.8  466.36  4722.5  467.17  4740.3  466.10  4753.1  467.19
  4789.8  465.41  4794.9  467.41  4834.2  466.37  4855.4  467.54  4933.3  466.65
  4938.4  467.81  4977.7  467.03  4988.3  467.91  5090.7  467.91  5118.8  466.76
  5142.0  467.80  5210.8  466.73  5215.9  467.57  5367.4  467.08  5394.8  465.96
  5399.9  464.27  5457.6  461.64  5457.8  461.14  5461.6  461.64  5500.6  462.42
  5521.1  464.97  5541.6  473.05  5580.9  473.30  5609.1  473.56  5661.1  474.48
#Mann=5,-1,0
  4376.7    0.05       0  5457.6    0.04       0  5461.6    0.05       0
  5580.9     0.1       0  5609.1    0.05       0
Bank Sta=5457.6,5461.6
Exp/Cntr=0.3,0.1

Type RM Length L Ch R = 1,3977,410,410,410
BEGIN DESCRIPTION:
Coppers Branch North 2188
END DESCRIPTION:
XS GIS Cut Line= 3
      2747700.17      6884877.74      2747012.45      6884741.70
      2746748.54      6884505.08
#Sta/Elev= 30
  4467.5  471.48  4533.0  469.94  4635.5  465.13  4767.4  455.05  4891.8  449.28
  4937.9  449.22  4943.0  448.57  4989.2  449.70  4994.3  448.36  5040.4  449.14
  5045.5  448.23  5091.7  449.30  5096.8  448.23  5124.2  448.87  5142.9  450.48
  5146.0  448.00  5146.3  447.50  5150.0  448.00  5168.5  448.98  5188.0  451.17
  5202.2  454.58  5216.4  454.97  5223.1  452.95  5237.3  452.81  5308.4  455.88
  5329.3  459.63  5336.8  460.19  5343.5  459.34  5400.3  463.00  5523.0  466.51
#Mann=3,-1,0
  4467.5    0.05       0  5146.0    0.04       0  5150.0    0.05       0
Bank Sta=5146,5150
Exp/Cntr=0.3,0.1

Type RM Length L Ch R = 1,3567,177,177,177
BEGIN DESCRIPTION:
Coppers Branch North 2186
END DESCRIPTION:
XS GIS Cut Line= 3
      2747723.60      6884434.20      2747374.49      6884420.50
      2746833.05      6884449.63
#Sta/Elev= 30
  4639.7  461.74  4657.3  459.86  4677.3  458.77  4757.4  452.13  4779.2  450.91
  4817.4  448.70  4867.5  447.02  4907.5  445.09  5017.6  443.79  5047.7  442.26
  5052.1  441.64  5055.6  441.14  5055.9  440.64  5059.4  440.64  5059.7  441.14
  5077.7  443.54  5097.7  443.23  5117.8  444.81  5137.8  445.45  5178.1  448.00
  5217.9  450.03  5247.9  452.55  5275.3  454.23  5280.3  453.82  5318.0  456.23
  5448.2  460.97  5463.5  462.09  5508.3  463.41  5518.3  463.20  5531.3  463.95
#Mann=6,-1,0
  4639.7    0.12       0  4779.2    0.05       0  5052.1    0.12       0
  5055.6    0.05       0  5059.7    0.12       0  5178.1    0.05       0
Bank Sta=5055.6,5059.7
Exp/Cntr=0.3,0.1

Type RM Length L Ch R = 1,3390,211,211,211
BEGIN DESCRIPTION:
Coppers Branch North 2184
END DESCRIPTION:
XS GIS Cut Line= 3
      2747784.22      6884246.52      2747422.29      6884263.20
      2746880.62      6884259.24
#Sta/Elev= 30
  4641.4  461.57  4659.6  459.74  4679.7  458.64  4779.8  450.22  4837.5  447.36
  4846.1  446.87  4859.9  446.80  4899.9  444.23  4939.9  442.47  4960.0  442.91
  4970.0  441.84  4977.9  439.52  4978.2  439.02  4981.7  439.02  4982.0  439.52
  4999.4  442.17  5003.7  442.17  5010.0  443.17  5035.9  443.25  5070.0  442.80
  5120.0  444.70  5140.0  444.89  5150.0  445.64  5170.0  445.98  5220.0  448.04
  5290.0  452.35  5320.0  453.68  5330.0  453.69  5350.0  455.04  5545.4  461.23
#Mann=5,-1,0
  4641.4    0.05       0  4837.5    0.12       0  4977.9    0.07       0
  4982.0    0.12       0  5035.9    0.05       0
Bank Sta=4977.9,4982
Exp/Cntr=0.3,0.1

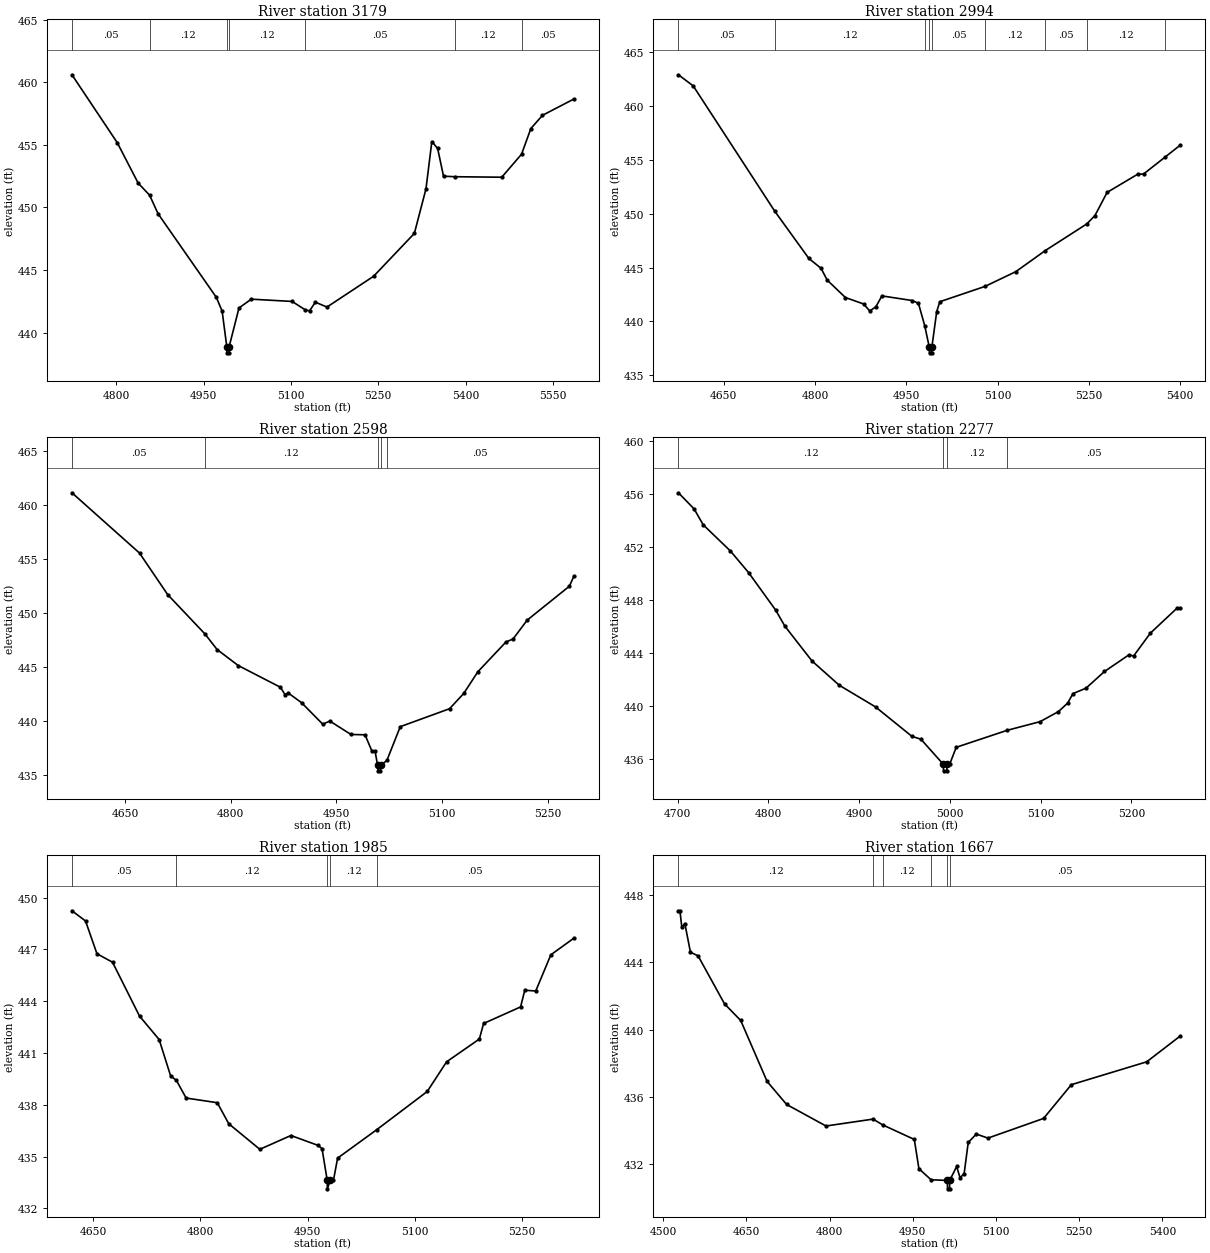
Type RM Length L Ch R = 1,3179,185,185,185
BEGIN DESCRIPTION:
Coppers Branch North 2185
END DESCRIPTION:
XS GIS Cut Line= 3
      2747793.78      6884122.06      2747503.08      6884106.68
      2746932.20      6884133.33
#Sta/Elev= 30
  4723.6  460.61  4801.5  455.18  4837.4  451.95  4857.1  450.98  4871.6  449.50
  4971.7  442.82  4981.7  441.72  4989.7  438.88  4990.0  438.38  4993.5  438.38
  4993.8  438.88  5010.7  441.97  5031.8  442.67  5101.9  442.49  5124.2  441.83
  5131.9  441.73  5141.9  442.43  5161.9  442.04  5242.0  444.50  5312.1  447.93
  5332.1  451.50  5342.1  455.27  5352.1  454.72  5362.2  452.50  5382.4  452.46
  5462.3  452.42  5496.3  454.26  5512.3  456.31  5532.3  457.37  5586.2  458.67
#Mann=7,-1,0
  4723.6    0.05       0  4857.1    0.12       0  4989.7    0.07       0
  4993.8    0.12       0  5124.2    0.05       0  5382.4    0.12       0
  5496.3    0.05       0
Bank Sta=4989.7,4993.8
Exp/Cntr=0.3,0.1

Type RM Length L Ch R = 1,2994,396,396,396
BEGIN DESCRIPTION:
Coppers Branch North 2183
END DESCRIPTION:
XS GIS Cut Line= 3
      2747800.34      6884033.89      2747370.73      6884028.16
      2746975.68      6884027.86
#Sta/Elev= 30
  4575.7  462.88  4600.0  461.85  4734.2  450.21  4790.1  445.84  4810.1  444.93
  4820.1  443.84  4850.1  442.22  4880.1  441.62  4890.1  440.97  4900.1  441.36
  4910.1  442.37  4960.1  441.94  4970.1  441.68  4980.4  439.61  4988.0  437.59
  4988.3  437.09  4991.8  437.09  4992.1  437.59  5000.1  440.91  5005.2  441.83
  5079.4  443.25  5130.1  444.62  5178.4  446.57  5246.8  449.05  5260.1  449.82
  5280.1  451.97  5330.1  453.65  5340.1  453.68  5375.7  455.26  5400.4  456.36
#Mann=9,-1,0
  4575.7    0.05       0  4734.2    0.12       0  4980.4    0.05       0
  4988.0    0.05       0  4992.1    0.05       0  5079.4    0.12       0
  5178.4    0.05       0  5246.8    0.12       0  5375.7    0.05       0
Bank Sta=4988,4992.1
Exp/Cntr=0.3,0.1

Type RM Length L Ch R = 1,2598,321,321,321
BEGIN DESCRIPTION:
Coppers Branch North 2182
END DESCRIPTION:
XS GIS Cut Line= 3
      2747751.90      6883669.05      2747321.91      6883678.90
      2747039.70      6883685.62
#Sta/Elev= 30
  4574.7  461.12  4670.6  455.55  4710.6  451.71  4763.6  448.07  4780.7  446.64
  4810.7  445.16  4870.7  443.15  4877.0  442.48  4882.0  442.61  4900.7  441.72
  4930.7  439.74  4940.7  440.03  4970.7  438.79  4990.7  438.76  5000.3  437.28
  5004.8  437.28  5008.6  435.93  5009.0  435.43  5012.5  435.43  5012.8  435.93
  5021.7  436.39  5040.7  439.51  5110.7  441.17  5130.8  442.58  5150.8  444.58
  5190.8  447.34  5200.8  447.61  5220.8  449.35  5280.8  452.49  5287.1  453.41
#Mann=5,-1,0
  4574.7    0.05       0  4763.6    0.12       0  5008.6    0.07       0
  5012.8    0.12       0  5021.7    0.05       0
Bank Sta=5008.6,5012.8
Exp/Cntr=0.3,0.1

Type RM Length L Ch R = 1,2277,292,292,292
BEGIN DESCRIPTION:
Coppers Branch North 2181
END DESCRIPTION:
XS GIS Cut Line= 3
      2747673.29      6883368.42      2747377.67      6883373.71
      2747123.43      6883414.73
#Sta/Elev= 30
  4700.8  456.10  4718.1  454.88  4728.1  453.68  4758.1  451.70  4778.1  450.07
  4808.1  447.22  4818.1  446.02  4848.1  443.38  4878.1  441.55  4918.1  439.91
  4958.1  437.69  4968.1  437.47  4992.7  435.58  4993.0  435.08  4996.6  435.08
  4996.9  435.58  4999.8  435.58  5007.0  436.86  5063.0  438.14  5099.5  438.80
  5119.7  439.56  5129.8  440.20  5135.7  440.92  5150.1  441.33  5170.4  442.59
  5197.4  443.85  5202.5  443.76  5221.0  445.49  5250.1  447.36  5254.0  447.36
#Mann=4,-1,0
  4700.8    0.12       0  4992.7    0.07       0  4996.9    0.12       0
  5063.0    0.05       0
Bank Sta=4992.7,4996.9
Exp/Cntr=0.3,0.1

Type RM Length L Ch R = 1,1985,318,318,318
BEGIN DESCRIPTION:
Coppers Branch North 2180
END DESCRIPTION:
XS GIS Cut Line= 3
      2747590.76      6882958.58      2747253.34      6883144.72
      2746984.58      6883313.65
#Sta/Elev= 30
  4620.0  449.24  4639.0  448.65  4655.0  446.75  4676.8  446.26  4714.6  443.14
  4742.1  441.78  4758.2  439.67  4766.3  439.41  4779.9  438.39  4823.5  438.12
  4839.6  436.90  4883.1  435.42  4926.6  436.22  4964.5  435.65  4970.2  435.46
  4977.4  433.63  4977.7  433.13  4981.6  433.63  4986.2  433.63  4992.0  434.91
  5046.9  436.56  5117.5  438.77  5144.6  440.49  5190.5  441.81  5196.4  442.71
  5248.2  443.67  5254.1  444.64  5269.4  444.59  5290.6  446.69  5322.8  447.65
#Mann=5,-1,0
  4620.0    0.05       0  4766.3    0.12       0  4977.4    0.07       0
  4981.6    0.12       0  5046.9    0.05       0
Bank Sta=4977.4,4981.6
Exp/Cntr=0.3,0.1

Type RM Length L Ch R = 1,1667,382,382,382
BEGIN DESCRIPTION:
Coppers Branch North 2179
END DESCRIPTION:
XS GIS Cut Line= 3
      2747546.02      6882713.33      2747111.90      6882894.53
      2746761.96      6883151.71
#Sta/Elev= 30
  4527.5  447.07  4530.2  447.07  4533.7  446.08  4539.1  446.31  4549.2  444.60
  4562.9  444.39  4610.6  441.53  4639.8  440.54  4687.4  436.91  4722.6  435.54
  4793.5  434.26  4878.4  434.67  4895.5  434.33  4952.7  433.46  4961.0  431.72
  4982.9  431.06  5012.3  431.02  5012.6  430.52  5016.2  430.52  5016.5  431.02
  5029.0  431.85  5035.2  431.18  5042.5  431.42  5049.9  433.28  5064.5  433.78
  5085.4  433.54  5185.7  434.71  5235.8  436.72  5371.6  438.08  5432.2  439.62
#Mann=6,-1,0
  4527.5    0.12       0  4878.4     0.1       0  4895.5    0.12       0
  4982.9    0.05       0  5012.3    0.04       0  5016.5    0.05       0
Bank Sta=5012.3,5016.5
Exp/Cntr=0.3,0.1

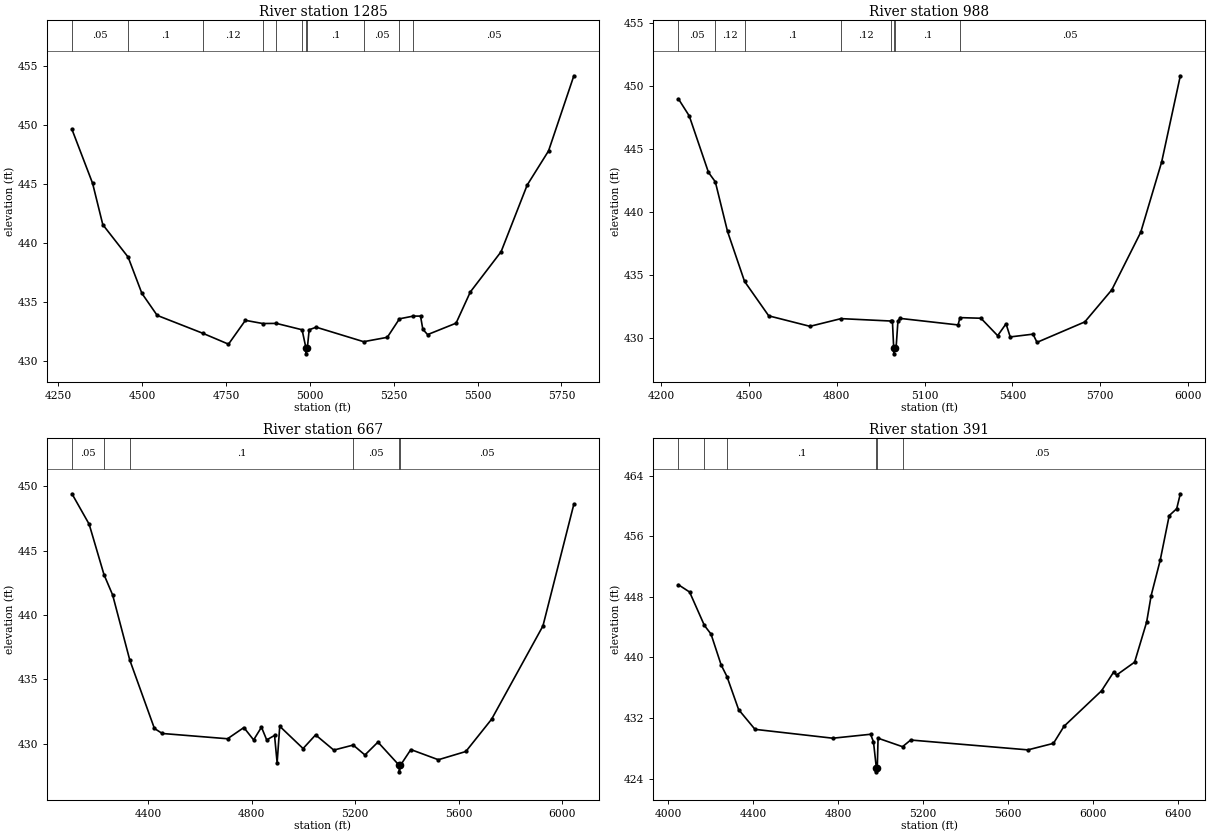
Type RM Length L Ch R = 1,1285,297,297,297
BEGIN DESCRIPTION:
Coppers Branch North 2178
END DESCRIPTION:
XS GIS Cut Line= 3
      2747626.83      6882482.72      2746923.20      6882596.46
      2746375.47      6883157.16
#Sta/Elev= 30
  4290.6  449.63  4352.2  445.05  4382.6  441.55  4458.1  438.80  4499.1  435.73
  4544.7  433.86  4680.2  432.35  4757.4  431.42  4807.8  433.44  4859.5  433.17
  4900.2  433.18  4976.8  432.64  4988.3  431.10  4988.6  430.60  4992.5  431.10
  4998.0  432.64  5018.8  432.86  5160.4  431.63  5230.9  432.00  5267.2  433.57
  5308.7  433.80  5330.0  433.80  5336.9  432.68  5351.1  432.23  5436.0  433.20
  5478.4  435.84  5570.3  439.26  5648.1  444.91  5711.7  447.80  5787.2  454.17
#Mann=11,-1,0
  4290.6    0.05       0  4458.1     0.1       0  4680.2    0.12       0
  4859.5     0.1       0  4900.2    0.12       0  4976.8     0.1       0
  4988.3    0.07       0  4992.5     0.1       0  5160.4    0.05       0
  5267.2     0.1       0  5308.7    0.05       0
Bank Sta=4988.3,4992.5
Exp/Cntr=0.3,0.1

Type RM Length L Ch R = 1,988,321,321,321
BEGIN DESCRIPTION:
Coppers Branch North 2177
END DESCRIPTION:
XS GIS Cut Line= 3
      2747662.72      6882214.34      2746928.18      6882297.84
      2746181.22      6882926.24
#Sta/Elev= 30
  4258.7  448.98  4295.7  447.63  4361.5  443.15  4384.8  442.41  4426.5  438.48
  4484.7  434.52  4567.4  431.79  4708.3  430.96  4814.6  431.57  4984.2  431.38
  4990.1  431.39  4994.4  429.28  4994.8  428.78  4998.7  429.28  5002.7  429.28
  5009.0  431.38  5015.5  431.59  5214.5  431.07  5221.0  431.65  5292.6  431.60
  5349.8  430.22  5378.4  431.16  5392.7  430.12  5470.7  430.34  5484.3  429.69
  5647.6  431.31  5739.9  433.85  5838.8  438.41  5910.3  443.98  5974.1  450.81
#Mann=8,-1,0
  4258.7    0.05       0  4384.8    0.12       0  4484.7     0.1       0
  4814.6    0.12       0  4984.2     0.1       0  4994.4    0.07       0
  4998.7     0.1       0  5221.0    0.05       0
Bank Sta=4994.4,4998.7
Exp/Cntr=0.3,0.1

Type RM Length L Ch R = 1,667,276,276,276
BEGIN DESCRIPTION:
Coppers Branch North 2176
END DESCRIPTION:
XS GIS Cut Line= 3
      2747661.85      6882173.06      2746773.36      6882055.13
      2746082.43      6882836.21
#Sta/Elev= 30
  4105.9  449.41  4172.3  447.05  4229.7  443.13  4263.1  441.55  4329.2  436.50
  4424.5  431.18  4454.8  430.79  4707.0  430.38  4770.1  431.25  4807.8  430.29
  4838.1  431.28  4858.3  430.29  4888.6  430.64  4898.6  428.51  4908.7  431.35
  4998.9  429.62  5047.2  430.68  5117.4  429.50  5192.5  429.89  5237.9  429.12
  5288.1  430.12  5370.4  428.31  5370.8  427.81  5374.7  428.31  5415.2  429.54
  5521.5  428.75  5627.7  429.39  5727.3  431.90  5925.5  439.14  6045.0  448.60
#Mann=6,-1,0
  4105.9    0.05       0  4229.7    0.12       0  4329.2     0.1       0
  5192.5    0.05       0  5370.4    0.07       0  5374.7    0.05       0
Bank Sta=5370.4,5374.7
Exp/Cntr=0.3,0.1

Type RM Length L Ch R = 1,391,0,0,0
BEGIN DESCRIPTION:
Coppers Branch North 2175
END DESCRIPTION:
XS GIS Cut Line= 3
      2747653.37      6882144.64      2746775.79      6881779.27
      2745789.05      6882788.15
#Sta/Elev= 30
  4049.4  449.58  4102.0  448.62  4171.6  444.21  4202.8  443.07  4250.5  438.99
  4277.8  437.46  4332.8  433.09  4409.8  430.49  4776.0  429.32  4953.7  429.84
  4967.3  428.84  4980.9  425.38  4981.2  424.88  4985.2  425.38  4988.9  429.32
  5104.0  428.20  5142.4  429.08  5694.1  427.78  5814.2  428.64  5863.8  430.89
  6040.5  435.58  6097.1  438.04  6111.3  437.66  6196.1  439.36  6252.7  444.65
  6274.0  448.16  6316.4  452.80  6358.9  458.71  6394.2  459.62  6411.2  461.59
#Mann=6,-1,0
  4049.4    0.05       0  4171.6    0.12       0  4277.8     0.1       0
  4980.9    0.07       0  4985.2     0.1       0  5104.0    0.05       0
Bank Sta=4980.9,4985.2
Exp/Cntr=0.3,0.1

Chan Stop Cuts=-1