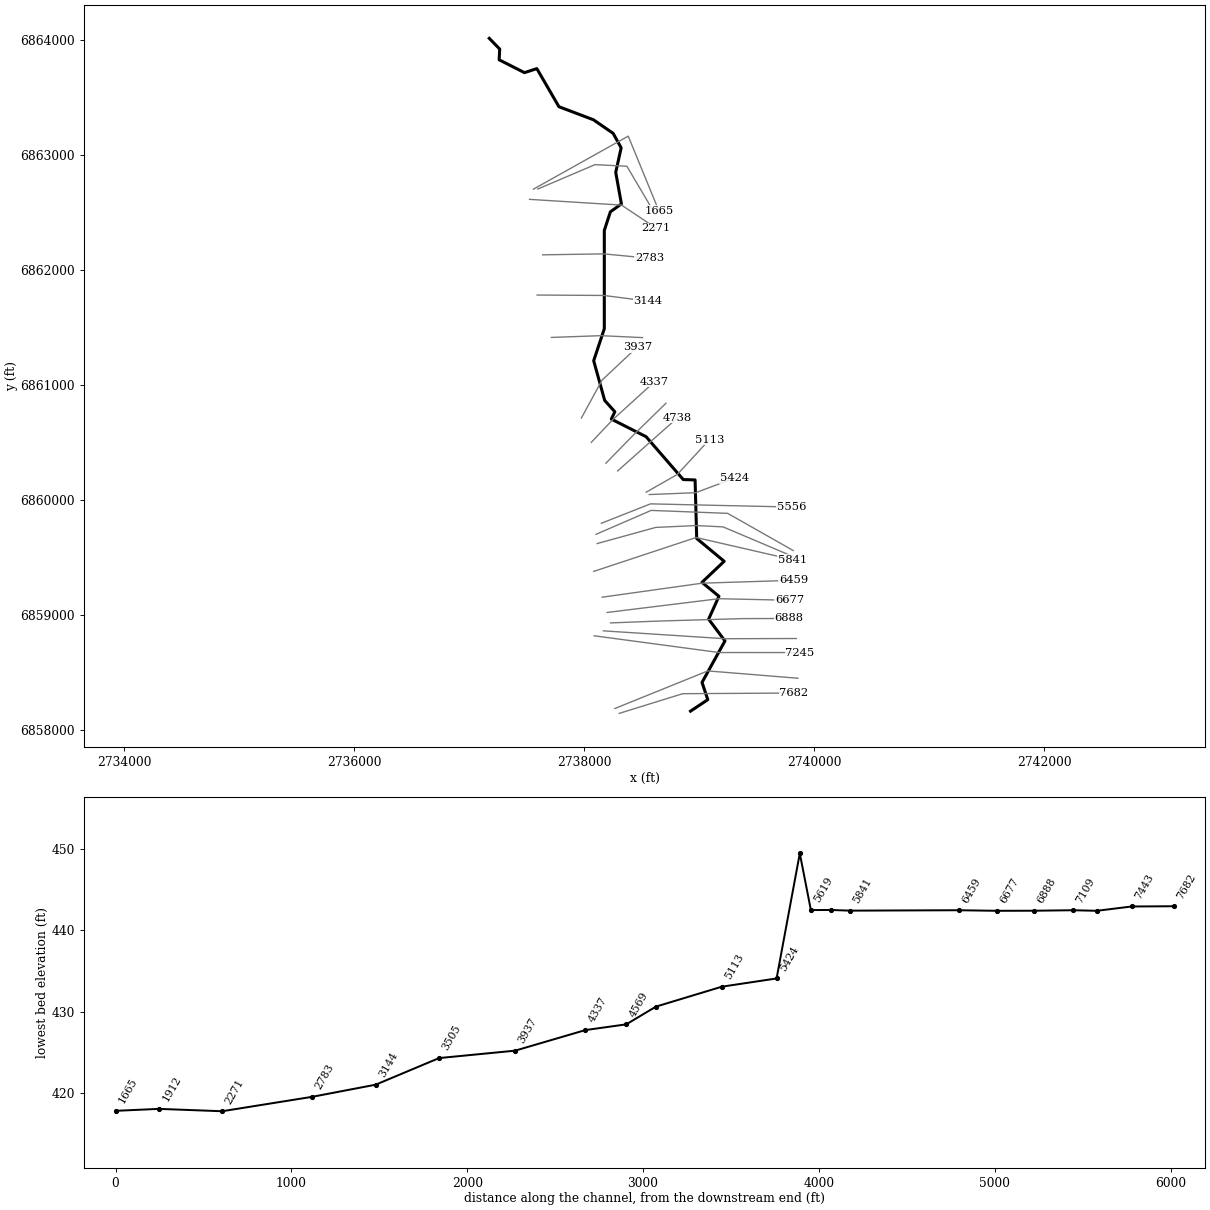
--- Coppers Branch South.prj (project) ---

Proj Title=Coppers Branch South Base Level Engineering
Current Plan=p01
Default Exp/Contr=0.3,0.1
English Units
Geom File=g01
Flow File=f01
Plan File=p01
BEGIN DESCRIPTION:
Coppers Branch South
END DESCRIPTION:

--- Coppers Branch South.p01 (plan) ---

Plan Title=Multiple Run
Short Identifier=Multiple
Geom File=g01
Flow File=f01
Subcritical Flow
K Sum by GR= 0
Std Step Tol= 0.01
Critical Tol= 0.01
Num of Std Step Trials= 20
Max Error Tol= 0.3
Flow Tol Ratio= 0.001
Split Flow NTrial= 30
Split Flow Tol= 0.02
Split Flow Ratio= 0.02
Log Output Level= 0
Friction Slope Method= 1
Unsteady Friction Slope Method= 2
Unsteady Bridges Friction Slope Method= 1
Parabolic Critical Depth
Global Vel Dist=  1 , 1 , 1
Global Log Level= 0
CheckData=True
Encroach Param= -1, 0, 0, 0
BEGIN DESCRIPTION:
Multiple Run
END DESCRIPTION:

--- Coppers Branch South.f01 (steady flow) ---

Flow Title=Multiple
Number of Profiles=7
Profile Names=10-year,25-year,50-year,1pct_min,100-year,1pct_plu,500-year
River Rch & RM= Coppers Branch S,Reach-1,7682
     513     674     801     472     943    1881    1304
River Rch & RM= Coppers Branch S,Reach-1,3505
     835    1131    1372     824    1645    3281    2363
Boundary for River Rch & Prof#=Coppers Branch S,Reach-1,1
Up Type=0
Dn Type=3
Dn Slope=0.005
Boundary for River Rch & Prof#=Coppers Branch S,Reach-1,2
Up Type=0
Dn Type=3
Dn Slope=0.005
Boundary for River Rch & Prof#=Coppers Branch S,Reach-1,3
Up Type=0
Dn Type=3
Dn Slope=0.005
Boundary for River Rch & Prof#=Coppers Branch S,Reach-1,4
Up Type=0
Dn Type=3
Dn Slope=0.005
Boundary for River Rch & Prof#=Coppers Branch S,Reach-1,5
Up Type=0
Dn Type=3
Dn Slope=0.005
Boundary for River Rch & Prof#=Coppers Branch S,Reach-1,6
Up Type=0
Dn Type=3
Dn Slope=0.005
Boundary for River Rch & Prof#=Coppers Branch S,Reach-1,7
Up Type=0
Dn Type=3
Dn Slope=0.005

--- Coppers Branch South.g01 (geometry) ---

Geom Title=Existing Conditions

River Reach=Coppers Branch S,Reach-1
Reach XY= 30
      2738926.00      6858161.00      2739076.00      6858261.00
      2739026.00      6858411.00      2739225.30      6858771.70
      2739083.29      6858960.91      2739172.96      6859159.58
      2739025.48      6859281.06      2739218.49      6859464.16
      2738979.53      6859662.45      2738965.56      6860171.49
      2738862.67      6860174.65      2738539.33      6860547.61
      2738237.11      6860700.68      2738267.98      6860764.32
      2738179.57      6860862.47      2738083.89      6861207.74
      2738176.21      6861485.91      2738176.29      6862340.71
      2738229.11      6862502.68      2738325.00      6862571.29
      2738275.57      6862845.83      2738322.76      6863058.94
      2738253.15      6863184.84      2738082.05      6863302.84
      2737781.61      6863416.59      2737589.79      6863747.63
      2737482.06      6863712.67      2737261.91      6863824.40
      2737266.82      6863917.66      2737176.00      6864011.00

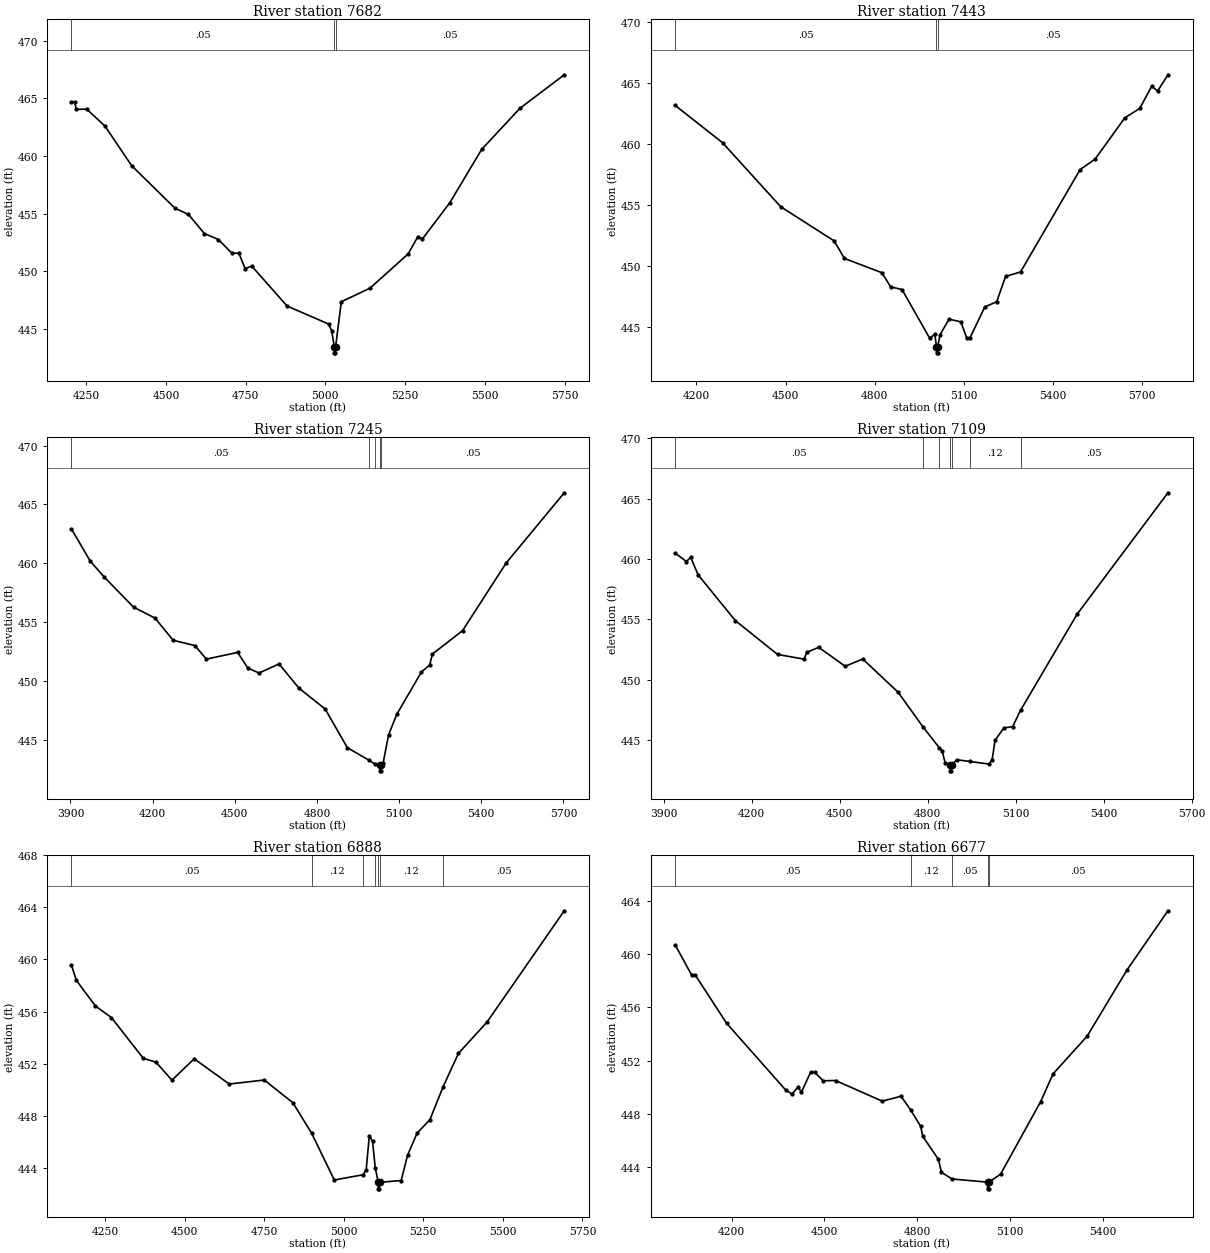
Type RM Length L Ch R = 1,7682,239,239,239
BEGIN DESCRIPTION:
Coppers Branch South 1701
END DESCRIPTION:
XS GIS Cut Line= 3
      2738305.93      6858141.77      2738857.98      6858312.92
      2739825.09      6858318.62
#Sta/Elev= 30
  4204.0  464.65  4213.8  464.70  4219.0  464.05  4251.6  464.07  4308.8  462.61
  4392.5  459.17  4528.6  455.47  4570.5  454.94  4620.6  453.28  4664.7  452.76
  4706.6  451.58  4728.8  451.57  4748.5  450.24  4769.4  450.45  4880.0  446.99
  5010.0  445.43  5020.0  444.85  5028.0  443.43  5028.3  442.93  5031.8  442.93
  5032.0  443.43  5050.0  447.36  5140.0  448.54  5260.0  451.52  5290.0  453.01
  5304.6  452.82  5390.0  455.94  5490.0  460.57  5610.0  464.14  5749.1  467.05
#Mann=3,-1,0
  4204.0    0.05       0  5028.0    0.04       0  5032.0    0.05       0
Bank Sta=5028,5032
Exp/Cntr=0.3,0.1

Type RM Length L Ch R = 1,7443,198,198,198
BEGIN DESCRIPTION:
Coppers Branch South 1700
END DESCRIPTION:
XS GIS Cut Line= 3
      2738268.21      6858184.17      2739076.00      6858511.00
      2739860.51      6858447.19
#Sta/Elev= 30
  4128.6  463.19  4288.0  460.13  4483.8  454.88  4663.5  452.08  4698.4  450.64
  4824.4  449.47  4853.9  448.31  4892.1  448.09  4985.2  444.10  5002.5  444.42
  5008.0  443.40  5008.3  442.90  5011.8  442.90  5012.0  443.40  5020.1  444.38
  5050.2  445.66  5090.3  445.44  5110.4  444.08  5120.4  444.10  5170.6  446.66
  5210.7  447.09  5240.8  449.17  5291.0  449.53  5491.6  457.93  5541.8  458.78
  5642.1  462.17  5692.3  462.94  5732.4  464.76  5752.5  464.37  5787.1  465.70
#Mann=3,-1,0
  4128.6    0.05       0  5008.0    0.04       0  5012.0    0.05       0
Bank Sta=5008,5012
Exp/Cntr=0.3,0.1

Type RM Length L Ch R = 1,7245,136,136,136
BEGIN DESCRIPTION:
Coppers Branch South 1699
END DESCRIPTION:
XS GIS Cut Line= 3
      2738087.97      6858816.33      2739174.36      6858670.78
      2739877.26      6858670.55
#Sta/Elev= 30
  3903.9  462.91  3972.5  460.18  4023.0  458.84  4130.6  456.27  4208.6  455.35
  4275.2  453.46  4354.6  453.01  4396.3  451.86  4510.6  452.43  4547.6  451.10
  4588.6  450.68  4661.6  451.45  4734.5  449.39  4830.1  447.62  4910.9  444.34
  4991.7  443.25  5012.0  442.94  5029.6  442.87  5029.9  442.37  5033.4  442.37
  5033.6  442.87  5041.6  443.03  5061.6  445.43  5091.6  447.18  5181.6  450.77
  5211.6  451.36  5221.6  452.29  5331.6  454.28  5491.6  460.05  5702.9  465.99
#Mann=5,-1,0
  3903.9    0.05       0  4991.7    0.12       0  5012.0    0.05       0
  5029.6    0.07       0  5033.6    0.05       0
Bank Sta=5029.6,5033.6
Exp/Cntr=0.3,0.1

Type RM Length L Ch R = 1,7109,221,221,221
BEGIN DESCRIPTION:
Coppers Branch South 1697
END DESCRIPTION:
XS GIS Cut Line= 4
      2738167.72      6858859.35      2739226.41      6858790.87
      2739503.83      6858791.65      2739845.50      6858792.63
#Sta/Elev= 30
  3939.1  460.49  3977.5  459.79  3991.8  460.15  4017.5  458.68  4144.4  454.89
  4288.1  452.09  4378.3  451.70  4388.3  452.27  4428.4  452.68  4518.6  451.11
  4578.7  451.71  4699.0  448.96  4783.5  446.10  4839.0  444.37  4849.3  444.10
  4859.3  443.12  4877.3  442.94  4877.6  442.44  4881.1  442.44  4881.3  442.94
  4899.4  443.36  4942.6  443.22  5009.6  443.00  5019.6  443.33  5029.6  444.96
  5059.6  446.00  5089.6  446.10  5116.5  447.45  5309.6  455.43  5619.1  465.49
#Mann=7,-1,0
  3939.1    0.05       0  4783.5    0.12       0  4839.0    0.05       0
  4877.3    0.07       0  4881.3    0.05       0  4942.6    0.12       0
  5116.5    0.05       0
Bank Sta=4877.3,4881.3
Exp/Cntr=0.3,0.1

Type RM Length L Ch R = 1,6888,211,211,211
BEGIN DESCRIPTION:
Coppers Branch South 1698
END DESCRIPTION:
XS GIS Cut Line= 4
      2738230.65      6858928.34      2738661.44      6858944.79
      2739376.64      6858965.62      2739778.43      6858966.93
#Sta/Elev= 30
  4144.6  459.55  4160.0  458.39  4220.0  456.42  4270.0  455.54  4370.1  452.41
  4410.1  452.11  4460.2  450.73  4530.2  452.37  4640.3  450.43  4750.3  450.74
  4840.4  448.99  4899.0  446.66  4970.4  443.06  5060.6  443.46  5070.5  443.83
  5080.5  446.45  5090.5  446.03  5099.2  443.99  5108.5  442.88  5108.7  442.38
  5112.2  442.38  5112.5  442.88  5180.5  443.02  5200.5  444.95  5230.5  446.66
  5270.6  447.68  5312.5  450.23  5360.6  452.79  5450.6  455.20  5693.0  463.74
#Mann=7,-1,0
  4144.6    0.05       0  4899.0    0.12       0  5060.6    0.05       0
  5099.2    0.12       0  5108.5    0.07       0  5112.5    0.12       0
  5312.5    0.05       0
Bank Sta=5108.5,5112.5
Exp/Cntr=0.3,0.1

Type RM Length L Ch R = 1,6677,218,218,218
BEGIN DESCRIPTION:
Coppers Branch South 1696
END DESCRIPTION:
XS GIS Cut Line= 4
      2738200.97      6859019.24      2738649.19      6859074.39
      2739172.55      6859138.79      2739787.50      6859125.17
#Sta/Elev= 30
  4017.5  460.68  4070.4  458.43  4083.0  458.40  4183.8  454.80  4375.2  449.78
  4395.4  449.49  4415.5  450.02  4425.6  449.61  4455.8  451.13  4469.1  451.12
  4496.1  450.48  4536.4  450.50  4687.5  448.95  4748.0  449.32  4779.6  448.28
  4811.7  447.06  4818.5  446.31  4868.9  444.59  4879.0  443.61  4913.2  443.11
  5027.9  442.87  5028.1  442.37  5031.6  442.37  5031.9  442.87  5069.9  443.46
  5199.9  448.92  5239.9  451.00  5349.9  453.82  5480.0  458.83  5611.5  463.24
#Mann=5,-1,0
  4017.5    0.05       0  4779.6    0.12       0  4913.2    0.05       0
  5027.9    0.03       0  5031.9    0.05       0
Bank Sta=5027.9,5031.9
Exp/Cntr=0.3,0.1

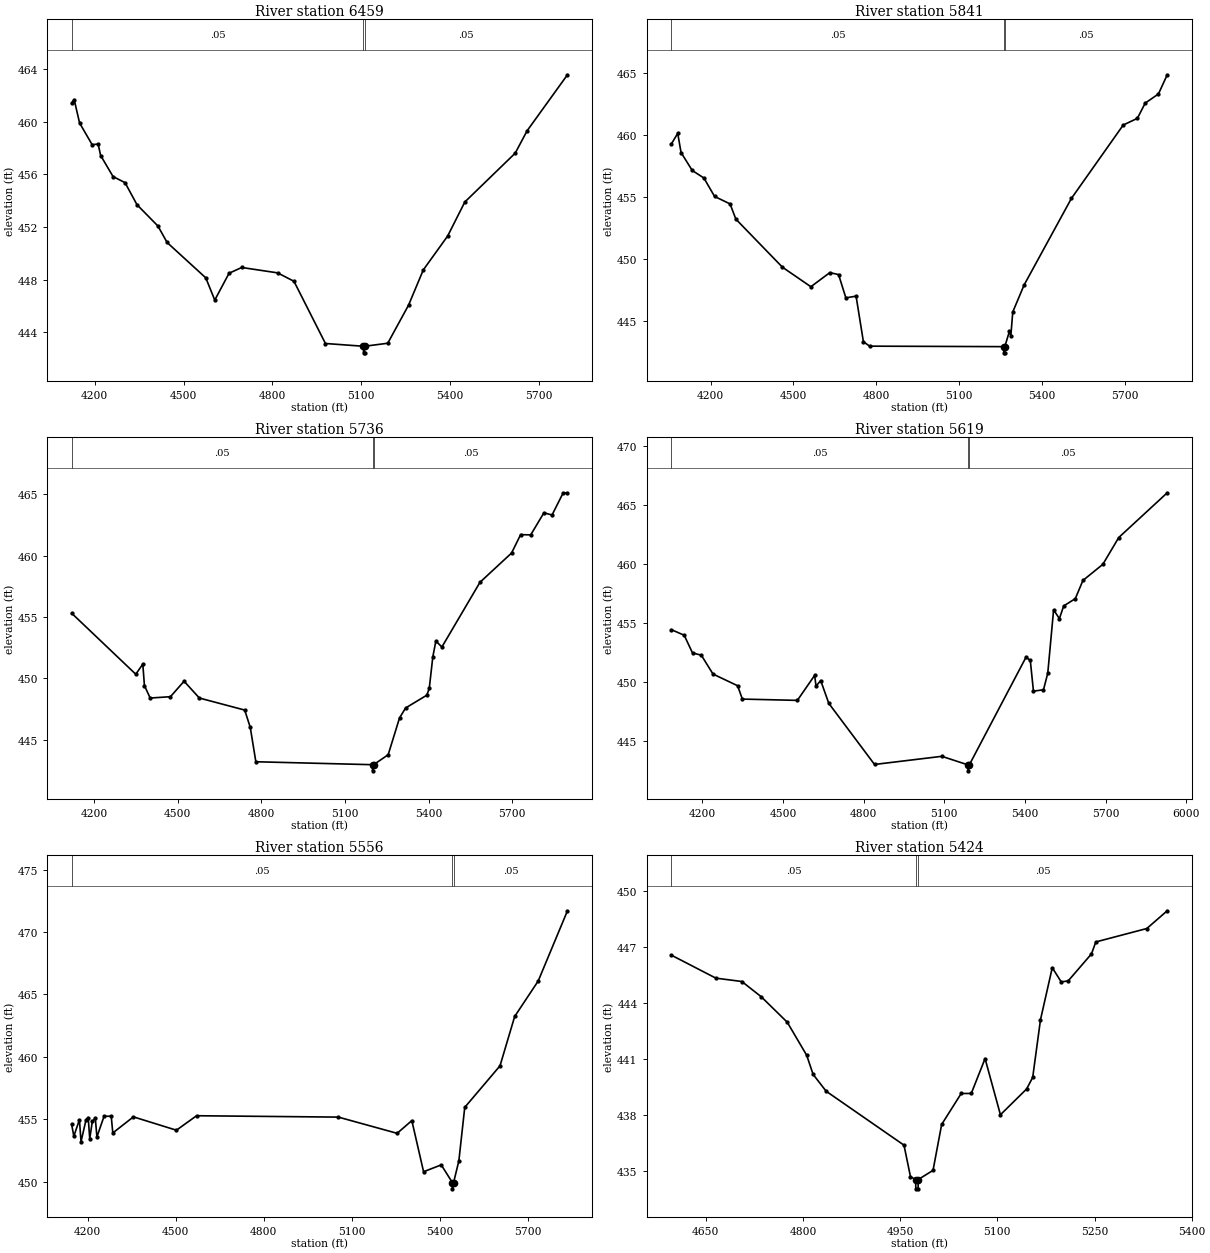
Type RM Length L Ch R = 1,6459,618,618,618
BEGIN DESCRIPTION:
Coppers Branch South 1695
END DESCRIPTION:
XS GIS Cut Line= 4
      2738157.57      6859151.88      2738470.11      6859195.68
      2739028.02      6859273.89      2739822.27      6859298.74
#Sta/Elev= 30
  4122.2  461.44  4130.7  461.70  4148.9  459.92  4191.3  458.27  4211.5  458.31
  4220.2  457.44  4262.0  455.84  4302.4  455.38  4342.8  453.70  4413.5  452.08
  4444.4  450.83  4575.0  448.14  4605.3  446.45  4653.5  448.49  4696.2  448.93
  4817.4  448.52  4872.6  447.88  4978.9  443.15  5107.2  442.94  5107.4  442.44
  5110.9  442.44  5111.2  442.94  5189.2  443.17  5259.3  446.06  5309.3  448.75
  5391.4  451.32  5449.4  453.91  5619.4  457.62  5659.5  459.32  5795.8  463.58
#Mann=3,-1,0
  4122.2    0.05       0  5107.2    0.04       0  5111.2    0.05       0
Bank Sta=5107.2,5111.2
Exp/Cntr=0.3,0.1

Type RM Length L Ch R = 1,5841,105,105,105
BEGIN DESCRIPTION:
Coppers Branch South 1694
END DESCRIPTION:
XS GIS Cut Line= 4
      2738084.30      6859376.20      2738439.17      6859493.68
      2738974.53      6859670.93      2739811.49      6859478.71
#Sta/Elev= 30
  4058.2  459.27  4081.1  460.12  4093.1  458.57  4133.7  457.12  4175.9  456.51
  4214.7  455.02  4270.7  454.42  4291.7  453.19  4460.3  449.31  4563.5  447.73
  4632.2  448.87  4663.9  448.71  4690.3  446.83  4727.3  446.97  4753.8  443.29
  4776.3  442.93  5262.2  442.89  5262.5  442.39  5266.0  442.39  5266.2  442.89
  5282.8  444.12  5288.0  443.76  5295.0  445.69  5336.1  447.87  5507.4  454.86
  5695.2  460.79  5746.5  461.33  5774.8  462.56  5822.8  463.30  5854.7  464.85
#Mann=3,-1,0
  4058.2    0.05       0  5262.2    0.03       0  5266.2    0.05       0
Bank Sta=5262.2,5266.2
Exp/Cntr=0.3,0.1

Type RM Length L Ch R = 1,5736,117,117,117
BEGIN DESCRIPTION:
Coppers Branch South 1692
END DESCRIPTION:
XS GIS Cut Line= 6
      2738114.28      6859618.33      2738623.37      6859758.58
      2738977.56      6859774.91      2739209.09      6859763.10
      2739455.67      6859658.57      2739820.65      6859503.84
#Sta/Elev= 30
  4119.5  455.31  4349.5  450.34  4374.8  451.16  4380.6  449.41  4401.3  448.40
  4474.0  448.51  4522.8  449.77  4577.7  448.40  4740.3  447.42  4760.3  446.01
  4780.3  443.21  5198.8  442.97  5199.1  442.47  5202.8  442.97  5255.0  443.78
  5295.8  446.78  5317.5  447.59  5393.5  448.63  5402.4  449.18  5415.2  451.76
  5426.1  453.04  5447.8  452.56  5584.4  457.83  5697.6  460.21  5730.2  461.71
  5766.4  461.69  5813.7  463.49  5842.9  463.31  5882.3  465.09  5898.2  465.12
#Mann=3,-1,0
  4119.5    0.05       0  5198.8    0.03       0  5202.8    0.05       0
Bank Sta=5198.8,5202.8
Exp/Cntr=0.3,0.1

Type RM Length L Ch R = 1,5619,63,63,63
BEGIN DESCRIPTION:
Coppers Branch South 1691
END DESCRIPTION:
XS GIS Cut Line= 5
      2738104.08      6859698.54      2738583.74      6859906.48
      2739248.50      6859880.93      2739490.35      6859743.82
      2739818.69      6859557.66
#Sta/Elev= 30
  4085.4  454.42  4132.9  453.95  4163.8  452.45  4196.5  452.26  4240.1  450.66
  4331.6  449.67  4349.1  448.54  4553.7  448.43  4618.0  450.55  4623.0  449.64
  4640.5  450.11  4670.5  448.18  4840.6  443.00  5090.8  443.69  5188.9  442.96
  5189.1  442.46  5192.9  442.96  5403.9  452.09  5419.8  451.81  5431.5  449.21
  5468.8  449.33  5484.7  450.73  5506.4  456.10  5528.0  455.36  5543.9  456.43
  5587.1  457.05  5615.4  458.59  5689.6  459.96  5748.7  462.23  5928.9  466.02
#Mann=3,-1,0
  4085.4    0.05       0  5188.9    0.03       0  5192.9    0.05       0
Bank Sta=5188.9,5192.9
Exp/Cntr=0.3,0.1

Type RM Length L Ch R = 1,5556,132,132,132
BEGIN DESCRIPTION:
Coppers Branch South 1689
END DESCRIPTION:
XS GIS Cut Line= 5
      2738150.45      6859794.65      2738578.21      6859963.46
      2738969.62      6859954.39      2739533.35      6859941.83
      2739805.53      6859935.77
#Sta/Elev= 30
  4145.8  454.58  4153.3  453.64  4172.3  454.96  4177.7  453.20  4194.8  454.96
  4202.1  455.13  4207.4  453.45  4216.3  454.84  4226.4  455.07  4231.8  453.58
  4256.2  455.24  4280.5  455.24  4285.9  453.90  4356.0  455.19  4502.4  454.12
  4571.0  455.28  5053.6  455.17  5253.6  453.87  5303.6  454.89  5343.6  450.79
  5403.7  451.34  5441.7  449.92  5441.9  449.42  5445.7  449.92  5463.7  451.67
  5483.7  455.95  5603.7  459.28  5653.7  463.24  5733.7  466.08  5833.3  471.71
#Mann=3,-1,0
  4145.8    0.05       0  5441.7    0.04       0  5445.7    0.05       0
Bank Sta=5441.7,5445.7
Exp/Cntr=0.3,0.1

Type RM Length L Ch R = 1,5424,311,311,311
BEGIN DESCRIPTION:
Coppers Branch South 1690
END DESCRIPTION:
XS GIS Cut Line= 3
      2738567.43      6860044.41      2738970.77      6860060.49
      2739309.12      6860187.61
#Sta/Elev= 30
  4597.1  446.58  4665.7  445.35  4705.8  445.17  4735.8  444.35  4775.8  442.99
  4805.8  441.22  4815.8  440.19  4835.9  439.29  4956.0  436.40  4966.0  434.71
  4974.0  434.56  4974.2  434.06  4977.7  434.06  4978.0  434.56  5000.8  435.05
  5014.1  437.51  5044.3  439.17  5059.8  439.17  5081.1  441.04  5104.8  438.03
  5145.2  439.41  5154.6  440.03  5166.6  443.12  5184.8  445.91  5198.6  445.15
  5209.3  445.20  5245.3  446.65  5252.0  447.29  5330.7  448.01  5362.2  448.96
#Mann=3,-1,0
  4597.1    0.05       0  4974.0    0.04       0  4978.0    0.05       0
Bank Sta=4974,4978
Exp/Cntr=0.3,0.1

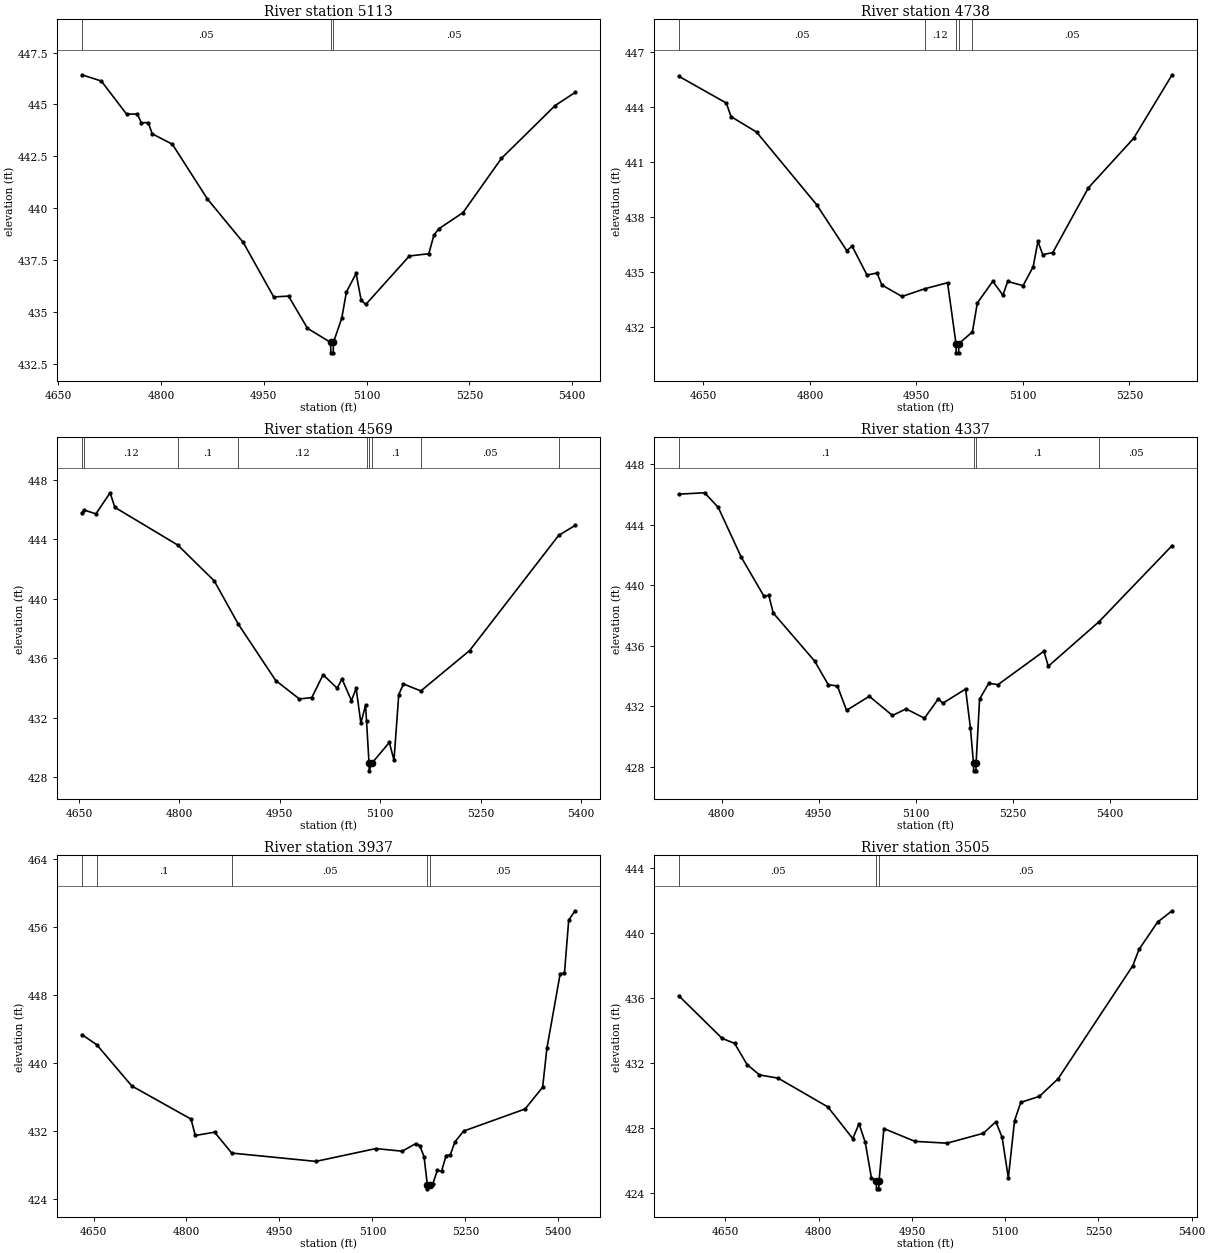
Type RM Length L Ch R = 1,5113,375,375,375
BEGIN DESCRIPTION:
Coppers Branch South 1693
END DESCRIPTION:
XS GIS Cut Line= 3
      2738541.23      6860065.45      2738811.00      6860219.05
      2739088.30      6860520.05
#Sta/Elev= 30
  4684.4  446.43  4712.9  446.13  4749.7  444.54  4765.5  444.54  4771.3  444.12
  4781.4  444.13  4787.1  443.59  4816.5  443.09  4867.8  440.45  4920.0  438.36
  4964.4  435.74  4986.0  435.78  5013.7  434.23  5047.5  433.55  5047.7  433.05
  5051.2  433.05  5051.5  433.55  5063.7  434.72  5070.5  435.98  5084.6  436.87
  5092.0  435.58  5098.8  435.38  5162.3  437.71  5190.7  437.82  5198.1  438.71
  5204.9  439.01  5240.6  439.80  5296.7  442.41  5375.0  444.95  5404.1  445.58
#Mann=3,-1,0
  4684.4    0.05       0  5047.5    0.04       0  5051.5    0.05       0
Bank Sta=5047.5,5051.5
Exp/Cntr=0.3,0.1

Type RM Length L Ch R = 1,4738,169,169,169
BEGIN DESCRIPTION:
Coppers Branch South 1687
END DESCRIPTION:
XS GIS Cut Line= 3
      2738292.73      6860250.03      2738580.29      6860505.80
      2738812.50      6860711.40
#Sta/Elev= 30
  4615.3  445.67  4682.2  444.21  4688.9  443.47  4724.8  442.63  4809.3  438.68
  4851.9  436.17  4859.5  436.41  4880.4  434.84  4894.6  434.95  4901.3  434.30
  4929.7  433.67  4961.7  434.09  4993.9  434.42  5005.8  431.10  5006.0  430.60
  5009.5  430.60  5009.8  431.10  5028.9  431.74  5035.9  433.32  5057.7  434.50
  5071.9  433.74  5078.6  434.49  5100.3  434.26  5114.5  435.29  5121.2  436.67
  5128.0  435.95  5142.1  436.06  5192.3  439.59  5255.9  442.28  5310.3  445.75
#Mann=5,-1,0
  4615.3    0.05       0  4961.7    0.12       0  5005.8    0.07       0
  5009.8    0.12       0  5028.9    0.05       0
Bank Sta=5005.8,5009.8
Exp/Cntr=0.3,0.1

Type RM Length L Ch R = 1,4569,232,232,232
BEGIN DESCRIPTION:
Coppers Branch South 1686
END DESCRIPTION:
XS GIS Cut Line= 3
      2738190.18      6860316.84      2738430.28      6860562.85
      2738711.84      6860837.95
#Sta/Elev= 30
  4654.0  445.80  4657.5  445.98  4675.1  445.72  4696.4  447.14  4703.4  446.16
  4797.5  443.62  4852.0  441.21  4887.8  438.31  4943.9  434.50  4979.3  433.26
  4997.8  433.35  5014.7  434.89  5035.8  433.98  5042.9  434.61  5057.1  433.15
  5064.1  433.97  5071.2  431.63  5078.2  432.85  5079.6  431.79  5083.4  428.92
  5083.6  428.42  5087.4  428.92  5113.7  430.33  5120.7  429.14  5127.8  433.55
  5134.8  434.27  5160.8  433.80  5233.8  436.52  5366.8  444.27  5391.4  444.94
#Mann=9,-1,0
  4654.0    0.05       0  4657.5    0.12       0  4797.5     0.1       0
  4887.8    0.12       0  5079.6     0.1       0  5083.4    0.07       0
  5087.4     0.1       0  5160.8    0.05       0  5366.8     0.1       0
Bank Sta=5083.4,5087.4
Exp/Cntr=0.3,0.1

Type RM Length L Ch R = 1,4337,400,400,400
BEGIN DESCRIPTION:
Coppers Branch South 1688
END DESCRIPTION:
XS GIS Cut Line= 3
      2738062.96      6860497.86      2738249.12      6860694.92
      2738612.30      6861024.77
#Sta/Elev= 30
  4734.0  446.02  4773.8  446.11  4794.8  445.15  4830.4  441.85  4865.6  439.26
  4872.9  439.33  4879.8  438.16  4943.7  434.98  4964.7  433.42  4978.9  433.33
  4993.0  431.72  5028.1  432.65  5063.9  431.38  5084.9  431.82  5113.3  431.20
  5134.9  432.49  5141.6  432.19  5176.8  433.13  5184.2  430.57  5189.0  428.22
  5189.2  427.72  5192.7  427.72  5193.0  428.22  5198.4  432.47  5212.6  433.51
  5226.8  433.42  5297.7  435.63  5304.5  434.64  5382.7  437.58  5495.7  442.62
#Mann=4,-1,0
  4734.0     0.1       0  5189.0    0.07       0  5193.0     0.1       0
  5382.7    0.05       0
Bank Sta=5189,5193
Exp/Cntr=0.3,0.1

Type RM Length L Ch R = 1,3937,432,432,432
BEGIN DESCRIPTION:
Coppers Branch South 1668
END DESCRIPTION:
XS GIS Cut Line= 3
      2737977.17      6860710.15      2738156.52      6861039.08
      2738463.51      6861327.82
#Sta/Elev= 30
  4631.0  443.35  4655.1  442.16  4711.7  437.30  4807.3  433.40  4814.2  431.47
  4845.3  431.86  4873.0  429.40  5008.7  428.42  5105.6  429.93  5148.1  429.62
  5169.6  430.50  5176.4  430.29  5183.4  428.95  5188.6  425.69  5188.8  425.19
  5192.6  425.69  5197.4  425.76  5204.7  427.35  5211.6  427.27  5218.9  429.11
  5225.8  429.21  5233.1  430.71  5247.2  431.99  5346.4  434.59  5374.7  437.15
  5381.6  441.74  5403.0  450.51  5409.9  450.57  5416.8  456.83  5427.1  457.92
#Mann=5,-1,0
  4631.0    0.12       0  4655.1     0.1       0  4873.0    0.05       0
  5188.6    0.04       0  5192.6    0.05       0
Bank Sta=5188.6,5192.6
Exp/Cntr=0.3,0.1

Type RM Length L Ch R = 1,3505,361,361,361
BEGIN DESCRIPTION:
Coppers Branch South 1667
END DESCRIPTION:
XS GIS Cut Line= 3
      2737716.31      6861410.59      2738147.76      6861425.75
      2738509.25      6861408.97
#Sta/Elev= 30
  4574.9  436.16  4644.6  433.54  4664.6  433.23  4684.7  431.93  4704.7  431.29
  4734.7  431.09  4814.7  429.32  4854.8  427.37  4864.8  428.29  4874.8  427.14
  4884.8  424.94  4892.5  424.78  4893.0  424.28  4896.6  424.28  4897.0  424.78
  4904.8  427.99  4954.8  427.20  5006.6  427.09  5064.9  427.70  5084.9  428.41
  5095.0  427.45  5105.0  424.95  5115.0  428.48  5125.0  429.60  5155.0  429.97
  5185.0  431.05  5305.2  438.01  5315.2  439.01  5345.2  440.70  5368.5  441.39
#Mann=3,-1,0
  4574.9    0.05       0  4892.5    0.05       0  4897.0    0.05       0
Bank Sta=4892.5,4897
Exp/Cntr=0.3,0.1

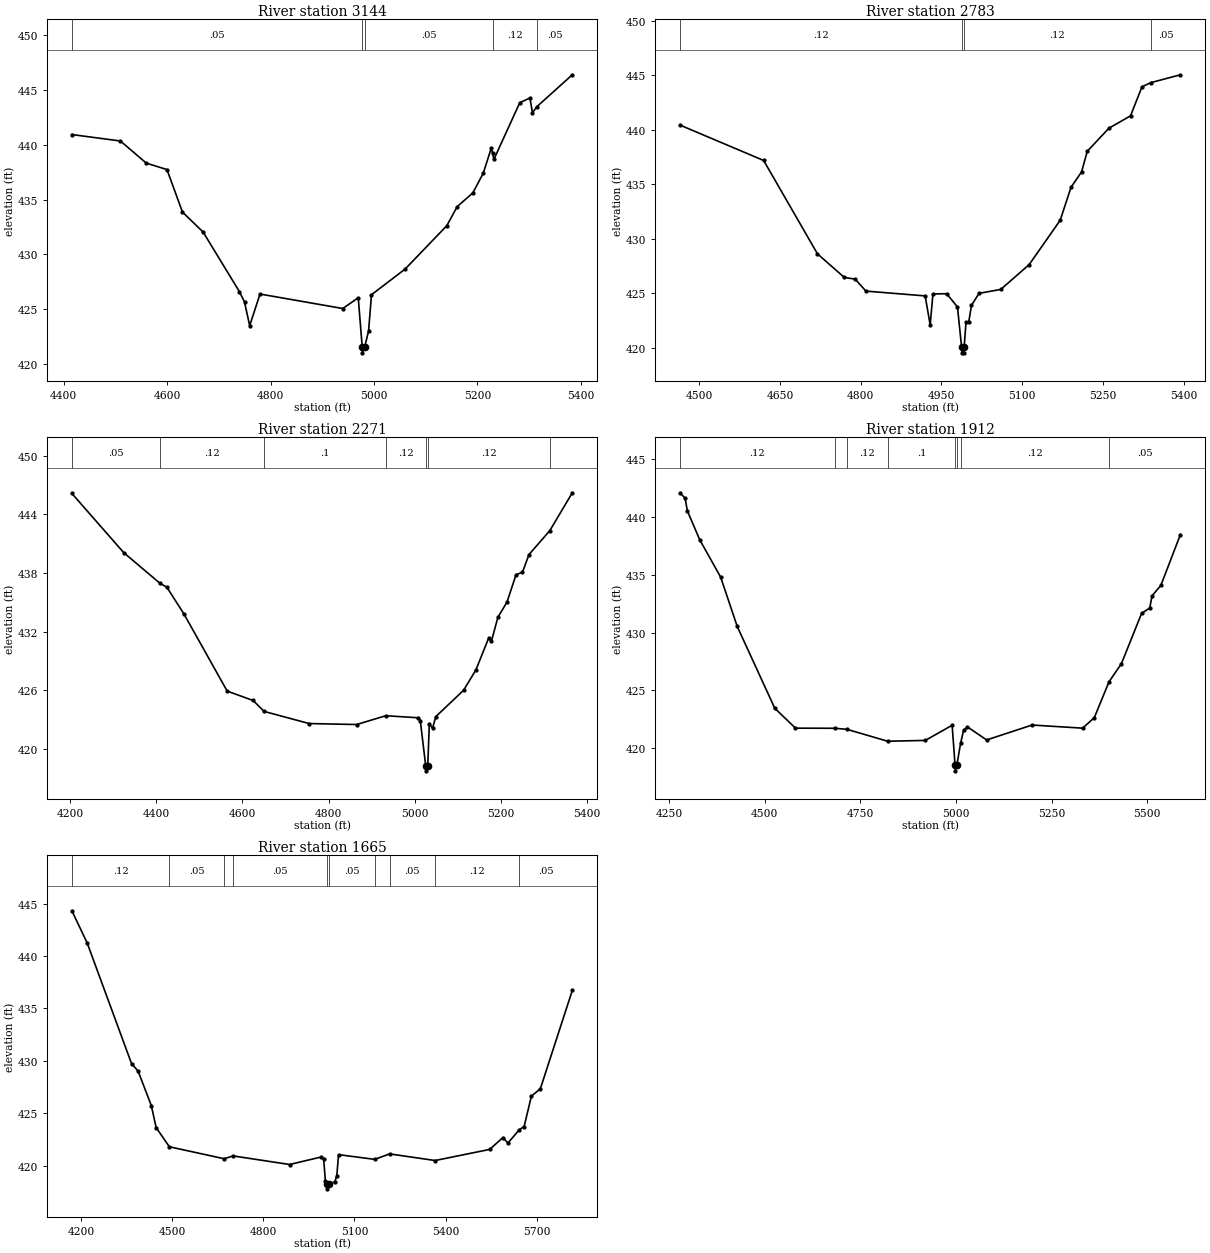
Type RM Length L Ch R = 1,3144,361,361,361
BEGIN DESCRIPTION:
Coppers Branch South 1666
END DESCRIPTION:
XS GIS Cut Line= 3
      2737592.08      6861779.00      2738172.06      6861775.46
      2738556.82      6861726.15
#Sta/Elev= 30
  4415.8  440.95  4509.7  440.36  4559.7  438.34  4599.7  437.75  4629.7  433.87
  4669.7  432.04  4739.7  426.61  4749.7  425.66  4759.7  423.49  4779.7  426.38
  4939.7  425.06  4969.7  426.04  4977.4  421.51  4977.9  421.01  4982.0  421.51
  4989.7  423.03  4995.3  426.32  5060.3  428.66  5140.9  432.62  5161.1  434.37
  5191.3  435.62  5211.5  437.42  5227.1  439.73  5229.5  439.23  5232.1  438.69
  5282.1  443.86  5301.7  444.29  5306.7  442.94  5315.0  443.49  5383.7  446.41
#Mann=5,-1,0
  4415.8    0.05       0  4977.4    0.05       0  4982.0    0.05       0
  5229.5    0.12       0  5315.0    0.05       0
Bank Sta=4977.4,4982
Exp/Cntr=0.3,0.1

Type RM Length L Ch R = 1,2783,512,512,512
BEGIN DESCRIPTION:
Coppers Branch South 1665
END DESCRIPTION:
XS GIS Cut Line= 3
      2737640.66      6862128.68      2738172.64      6862136.98
      2738568.15      6862098.75
#Sta/Elev= 30
  4464.3  440.44  4619.7  437.19  4719.7  428.61  4769.7  426.44  4789.7  426.29
  4809.7  425.19  4919.7  424.75  4929.0  422.08  4934.1  424.93  4959.7  424.95
  4979.7  423.73  4987.4  420.02  4987.9  419.52  4991.6  419.52  4992.1  420.02
  4995.5  422.31  5000.5  422.31  5005.7  423.88  5019.8  424.99  5060.0  425.34
  5112.9  427.63  5170.5  431.70  5190.6  434.73  5210.1  436.13  5220.7  438.03
  5260.9  440.15  5301.1  441.29  5322.3  443.95  5338.2  444.33  5393.7  445.06
#Mann=4,-1,0
  4464.3    0.12       0  4987.4    0.07       0  4992.1    0.12       0
  5338.2    0.05       0
Bank Sta=4987.4,4992.1
Exp/Cntr=0.3,0.1

Type RM Length L Ch R = 1,2271,359,359,359
BEGIN DESCRIPTION:
Coppers Branch South 48
END DESCRIPTION:
XS GIS Cut Line= 3
      2737525.96      6862611.00      2738326.00      6862561.00
      2738626.04      6862360.97
#Sta/Elev= 30
  4204.0  446.14  4324.3  440.09  4408.7  436.94  4424.5  436.55  4464.5  433.79
  4564.7  425.91  4624.9  424.95  4650.5  423.83  4755.1  422.59  4865.3  422.49
  4933.0  423.39  5008.6  423.18  5013.1  422.90  5025.8  418.25  5026.3  417.75
  5030.5  418.25  5034.1  422.53  5041.7  422.12  5049.2  423.30  5113.8  426.00
  5142.3  428.08  5172.4  431.39  5178.4  431.02  5193.4  433.47  5214.4  435.01
  5235.5  437.82  5250.5  438.08  5265.5  439.88  5314.0  442.34  5366.2  446.21
#Mann=7,-1,0
  4204.0    0.05       0  4408.7    0.12       0  4650.5     0.1       0
  4933.0    0.12       0  5025.8    0.07       0  5030.5    0.12       0
  5314.0    0.05       0
Bank Sta=5025.8,5030.5
Exp/Cntr=0.3,0.1

Type RM Length L Ch R = 1,1912,247,247,247
BEGIN DESCRIPTION:
Coppers Branch South 1669
END DESCRIPTION:
XS GIS Cut Line= 4
      2737598.23      6862700.88      2738095.85      6862912.89
      2738372.62      6862898.88      2738621.68      6862477.15
#Sta/Elev= 30
  4278.6  442.08  4292.1  441.61  4297.9  440.52  4330.5  438.00  4384.9  434.79
  4428.3  430.52  4526.4  423.45  4580.5  421.73  4683.4  421.72  4714.9  421.63
  4821.3  420.60  4919.8  420.67  4989.9  421.98  4997.5  418.54  4998.0  418.04
  5002.3  418.54  5012.0  420.43  5019.9  421.56  5029.9  421.84  5080.0  420.71
  5198.7  422.00  5330.8  421.73  5361.3  422.63  5399.9  425.74  5432.3  427.31
  5485.0  431.65  5506.4  432.12  5512.2  433.17  5535.5  434.08  5586.4  438.47
#Mann=8,-1,0
  4278.6    0.12       0  4683.4    0.05       0  4714.9    0.12       0
  4821.3     0.1       0  4997.5    0.07       0  5002.3     0.1       0
  5012.0    0.12       0  5399.9    0.05       0
Bank Sta=4997.5,5002.3
Exp/Cntr=0.3,0.1

Type RM Length L Ch R = 1,1665,0,0,0
BEGIN DESCRIPTION:
Coppers Branch South 3426
END DESCRIPTION:
XS GIS Cut Line= 3
      2737560.12      6862699.74      2738384.43      6863160.62
      2738651.26      6862509.36
#Sta/Elev= 30
  4169.3  444.31  4219.6  441.25  4365.8  429.74  4387.5  429.02  4430.9  425.74
  4446.9  423.64  4490.4  421.81  4670.9  420.67  4700.0  420.94  4886.4  420.12
  4989.5  420.83  4998.5  420.66  5004.2  418.58  5010.0  418.30  5010.5  417.80
  5014.8  418.30  5035.3  418.45  5041.9  419.07  5047.6  421.06  5166.8  420.61
  5215.8  421.13  5365.6  420.50  5545.6  421.56  5588.8  422.69  5605.4  422.16
  5642.7  423.43  5658.8  423.74  5682.8  426.64  5712.2  427.34  5817.5  436.72
#Mann=10,-1,0
  4169.3    0.12       0  4490.4    0.05       0  4670.9    0.12       0
  4700.0    0.05       0  5010.0    0.04       0  5014.8    0.05       0
  5166.8     0.1       0  5215.8    0.05       0  5365.6    0.12       0
  5642.7    0.05       0
Bank Sta=5010,5014.8
Exp/Cntr=0.3,0.1

Chan Stop Cuts=-1