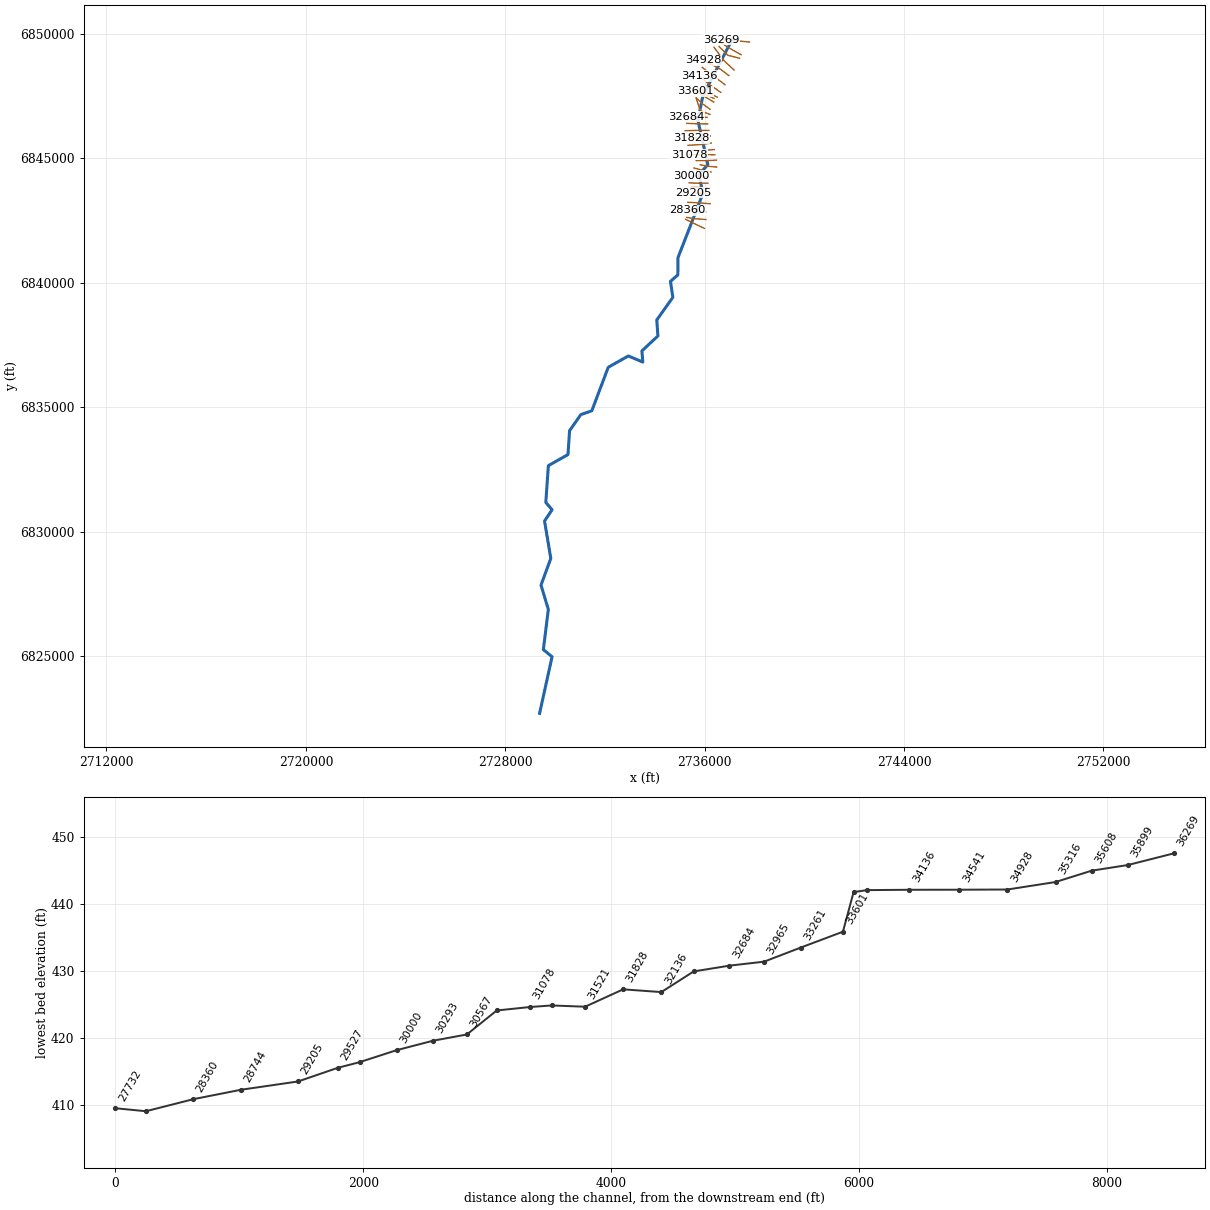
--- Dry Creek.prj (project) ---

Proj Title=Dry Creek Base Level Engineering
Current Plan=p01
Default Exp/Contr=0.3,0.1
English Units
Geom File=g01
Flow File=f01
Plan File=p01
BEGIN DESCRIPTION:
Dry Creek
END DESCRIPTION:

--- Dry Creek.p01 (plan) ---

Plan Title=Multiple Run
Short Identifier=Multiple
Geom File=g01
Flow File=f01
Subcritical Flow
K Sum by GR= 0
Std Step Tol= 0.01
Critical Tol= 0.01
Num of Std Step Trials= 20
Max Error Tol= 0.3
Flow Tol Ratio= 0.001
Split Flow NTrial= 30
Split Flow Tol= 0.02
Split Flow Ratio= 0.02
Log Output Level= 0
Friction Slope Method= 1
Unsteady Friction Slope Method= 2
Unsteady Bridges Friction Slope Method= 1
Parabolic Critical Depth
Global Vel Dist=  1 , 1 , 1
Global Log Level= 0
CheckData=True
Encroach Param= -1, 0, 0, 0
BEGIN DESCRIPTION:
Multiple Run
END DESCRIPTION:

--- Dry Creek.f01 (steady flow) ---

Flow Title=Multiple
Number of Profiles=7
Profile Names=10-year,25-year,50-year,1pct_min,100-year,1pct_plu,500-year
River Rch & RM= Dry Creek,Reach-1,36269
     510     668     793     466     930    1856    1280
River Rch & RM= Dry Creek,Reach-1,32684
     993    1350    1642     988    1971    3932    2840
River Rch & RM= Dry Creek,Reach-1,23892
    1617    2249    2778    1694    3381    6745    5010
River Rch & RM= Dry Creek,Reach-1,22826
    1852    2593    3215    1968    3927    7836    5864
River Rch & RM= Dry Creek,Reach-1,16201
    1860    2607    3234    1981    3953    7887    5908
River Rch & RM= Dry Creek,Reach-1,14499
    1994    2800    3479    2133    4256    8491    6374
River Rch & RM= Dry Creek,Reach-1,11071
    2103    2954    3671    2251    4491    8960    6726
River Rch & RM= Dry Creek,Reach-1,8625
    2211    3108    3863    2369    4726    9430    7079
Boundary for River Rch & Prof#=Dry Creek,Reach-1,1
Up Type=0
Dn Type=3
Dn Slope=0.005
Boundary for River Rch & Prof#=Dry Creek,Reach-1,2
Up Type=0
Dn Type=3
Dn Slope=0.005
Boundary for River Rch & Prof#=Dry Creek,Reach-1,3
Up Type=0
Dn Type=3
Dn Slope=0.005
Boundary for River Rch & Prof#=Dry Creek,Reach-1,4
Up Type=0
Dn Type=3
Dn Slope=0.005
Boundary for River Rch & Prof#=Dry Creek,Reach-1,5
Up Type=0
Dn Type=3
Dn Slope=0.005
Boundary for River Rch & Prof#=Dry Creek,Reach-1,6
Up Type=0
Dn Type=3
Dn Slope=0.005
Boundary for River Rch & Prof#=Dry Creek,Reach-1,7
Up Type=0
Dn Type=3
Dn Slope=0.005

--- Dry Creek.g01 (geometry) ---

Geom Title=Existing Conditions

River Reach=Dry Creek,Reach-1
Reach XY= 30
      2737126.00      6849811.00      2735928.38      6847505.47
      2735725.55      6846521.19      2736126.10      6844740.90
      2735777.20      6844351.41      2735924.95      6843570.49
      2734927.97      6841005.64      2734922.46      6840312.46
      2734628.09      6840055.74      2734722.49      6839412.25
      2734078.17      6838505.55      2734122.45      6837862.47
      2733481.08      6837263.28      2733517.52      6836814.31
      2732936.27      6837060.02      2732131.58      6836605.42
      2731470.58      6834858.25      2731031.42      6834705.82
      2730579.27      6834059.66      2730515.05      6833100.98
      2729727.97      6832655.32      2729625.61      6831179.47
      2729876.56      6830883.83      2729575.64      6830435.80
      2729826.30      6828933.76      2729433.56      6827861.00
      2729726.45      6826884.06      2729527.13      6825270.44
      2729876.61      6824983.71      2729376.00      6822711.00

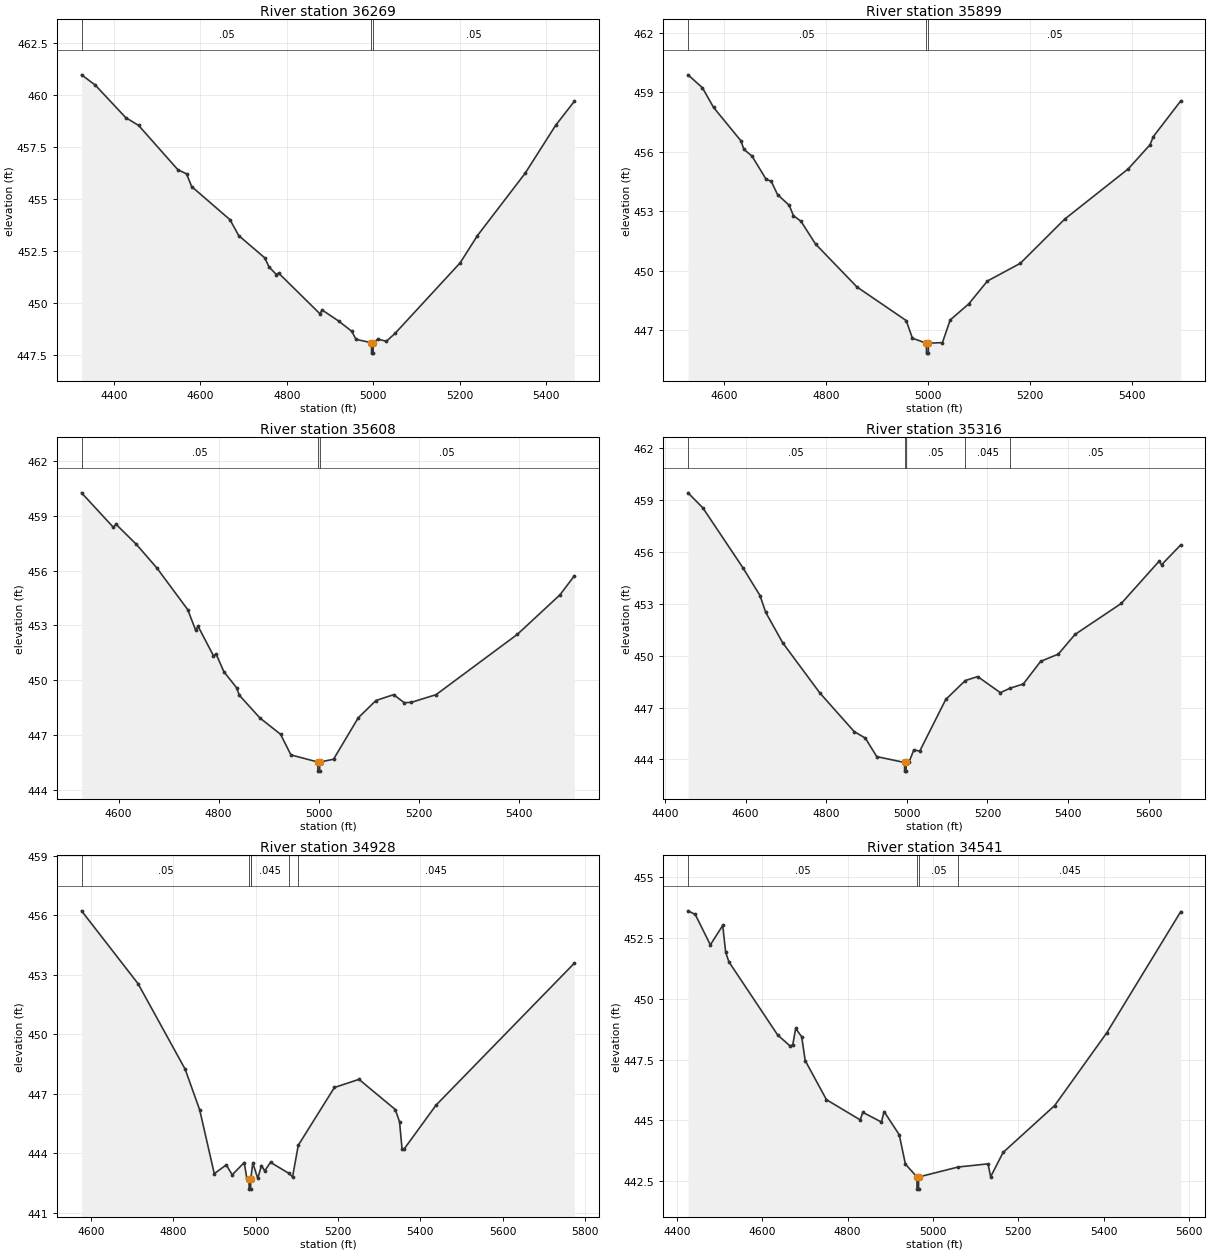
Type RM Length L Ch R = 1,36269,370,370,370
BEGIN DESCRIPTION:
Dry Creek36268.899
END DESCRIPTION:
XS GIS Cut Line= 3
      2737797.48      6849661.00      2737126.03      6849728.12
      2736662.72      6849761.36
#Sta/Elev= 30
  4325.2  460.95  4356.8  460.46  4427.2  458.90  4457.3  458.52  4547.8  456.40
  4567.9  456.20  4579.8  455.59  4668.4  454.00  4688.5  453.24  4748.8  452.17
  4758.8  451.73  4775.8  451.37  4780.8  451.44  4876.3  449.49  4881.3  449.67
  4919.6  449.14  4949.8  448.65  4959.8  448.26  4995.5  448.10  4995.8  447.60
  4999.3  447.60  4999.5  448.10  5010.1  448.27  5030.1  448.17  5050.2  448.55
  5200.5  451.93  5240.6  453.24  5350.9  456.23  5421.1  458.52  5464.5  459.68
#Mann=3,-1,0
  4325.2    0.05       0  4995.5    0.05       0  4999.5    0.05       0
Bank Sta=4995.5,4999.5
Exp/Cntr=0.3,0.1

Type RM Length L Ch R = 1,35899,291,291,291
BEGIN DESCRIPTION:
Dry Creek35899.11
END DESCRIPTION:
XS GIS Cut Line= 3
      2737459.20      6849154.22      2737048.41      6849383.45
      2736630.57      6849648.62
#Sta/Elev= 30
  4529.8  459.87  4558.0  459.22  4579.8  458.23  4633.4  456.55  4639.2  456.12
  4655.1  455.78  4682.6  454.62  4692.8  454.51  4705.2  453.84  4728.1  453.30
  4736.3  452.78  4751.0  452.50  4779.7  451.35  4860.8  449.19  4957.2  447.50
  4969.4  446.61  4996.7  446.36  4997.0  445.86  5000.5  445.86  5000.7  446.36
  5028.2  446.39  5043.4  447.53  5079.8  448.34  5116.3  449.49  5180.7  450.38
  5267.9  452.61  5392.4  455.14  5434.8  456.35  5441.3  456.76  5495.1  458.56
#Mann=3,-1,0
  4529.8    0.05       0  4996.7    0.05       0  5000.7    0.05       0
Bank Sta=4996.7,5000.7
Exp/Cntr=0.3,0.1

Type RM Length L Ch R = 1,35608,292,292,292
BEGIN DESCRIPTION:
Dry Creek35607.92
END DESCRIPTION:
XS GIS Cut Line= 3
      2737401.71      6849010.18      2736937.72      6849127.34
      2736576.80      6849482.47
#Sta/Elev= 30
  4526.1  460.27  4589.7  458.38  4594.9  458.55  4635.9  457.44  4677.0  456.14
  4738.3  453.87  4753.9  452.76  4759.1  452.95  4789.8  451.34  4795.0  451.44
  4810.5  450.47  4836.0  449.59  4841.4  449.18  4882.7  447.93  4923.9  447.04
  4944.5  445.91  4998.2  445.52  4998.5  445.02  5002.0  445.02  5002.2  445.52
  5029.7  445.67  5079.1  447.94  5114.5  448.89  5149.8  449.21  5171.1  448.77
  5185.3  448.79  5234.7  449.21  5397.4  452.52  5482.3  454.68  5511.0  455.72
#Mann=3,-1,0
  4526.1    0.05       0  4998.2    0.05       0  5002.2    0.05       0
Bank Sta=4998.2,5002.2
Exp/Cntr=0.3,0.1

Type RM Length L Ch R = 1,35316,388,388,388
BEGIN DESCRIPTION:
Dry Creek35315.61
END DESCRIPTION:
XS GIS Cut Line= 3
      2737177.80      6848540.77      2736778.32      6848912.28
      2736371.86      6849453.39
#Sta/Elev= 30
  4457.2  459.42  4494.0  458.55  4593.2  455.09  4635.7  453.48  4649.9  452.51
  4691.9  450.75  4784.3  447.84  4869.3  445.61  4897.1  445.23  4925.4  444.16
  4994.3  443.82  4994.5  443.32  4998.0  443.32  4998.3  443.82  5005.1  443.83
  5017.4  444.55  5032.0  444.48  5096.6  447.47  5145.0  448.56  5175.7  448.79
  5231.9  447.86  5256.4  448.12  5288.8  448.36  5331.9  449.67  5375.7  450.09
  5417.3  451.23  5531.9  453.02  5625.6  455.46  5631.9  455.26  5679.5  456.41
#Mann=5,-1,0
  4457.2    0.05       0  4994.3    0.05       0  4998.3    0.05       0
  5145.0   0.045       0  5256.4    0.05       0
Bank Sta=4994.3,4998.3
Exp/Cntr=0.3,0.1

Type RM Length L Ch R = 1,34928,387,387,387
BEGIN DESCRIPTION:
Dry Creek34928.33
END DESCRIPTION:
XS GIS Cut Line= 3
      2736971.70      6848314.20      2736630.69      6848572.82
      2735950.29      6848930.35
#Sta/Elev= 30
  4577.4  456.22  4714.6  452.55  4829.0  448.24  4864.3  446.19  4899.7  442.98
  4928.8  443.42  4943.3  442.92  4972.4  443.54  4978.7  442.75  4984.2  442.70
  4984.4  442.20  4987.9  442.20  4988.2  442.70  4988.8  442.80  4993.3  443.52
  5005.2  442.74  5014.3  443.39  5022.0  443.12  5036.3  443.55  5081.2  442.99
  5089.8  442.82  5103.7  444.41  5191.4  447.32  5251.1  447.73  5339.3  446.21
  5349.6  445.59  5355.7  444.22  5361.4  444.24  5438.2  446.43  5774.0  453.58
#Mann=6,-1,0
  4577.4    0.05       0  4984.2   0.045       0  4988.2    0.05       0
  4988.8   0.045       0  5081.2    0.05       0  5103.7   0.045       0
Bank Sta=4984.2,4988.2
Exp/Cntr=0.3,0.1

Type RM Length L Ch R = 1,34541,405,405,405
BEGIN DESCRIPTION:
Dry Creek34541.44
END DESCRIPTION:
XS GIS Cut Line= 3
      2736815.93      6847946.81      2736361.12      6848296.27
      2735897.51      6848645.52
#Sta/Elev= 30
  4426.5  453.62  4443.5  453.47  4478.8  452.22  4507.8  453.02  4514.7  451.91
  4522.3  451.52  4636.5  448.51  4665.5  448.06  4671.8  448.11  4678.6  448.78
  4692.7  448.44  4700.9  447.46  4750.7  445.85  4829.6  445.02  4835.9  445.33
  4879.4  444.93  4885.7  445.36  4921.1  444.41  4935.6  443.20  4962.6  442.67
  4962.8  442.17  4966.3  442.17  4966.6  442.67  5059.2  443.08  5129.0  443.21
  5135.3  442.68  5164.4  443.68  5285.2  445.61  5407.1  448.60  5580.5  453.59
#Mann=4,-1,0
  4426.5    0.05       0  4962.6    0.05       0  4966.6    0.05       0
  5059.2   0.045       0
Bank Sta=4962.6,4966.6
Exp/Cntr=0.3,0.1

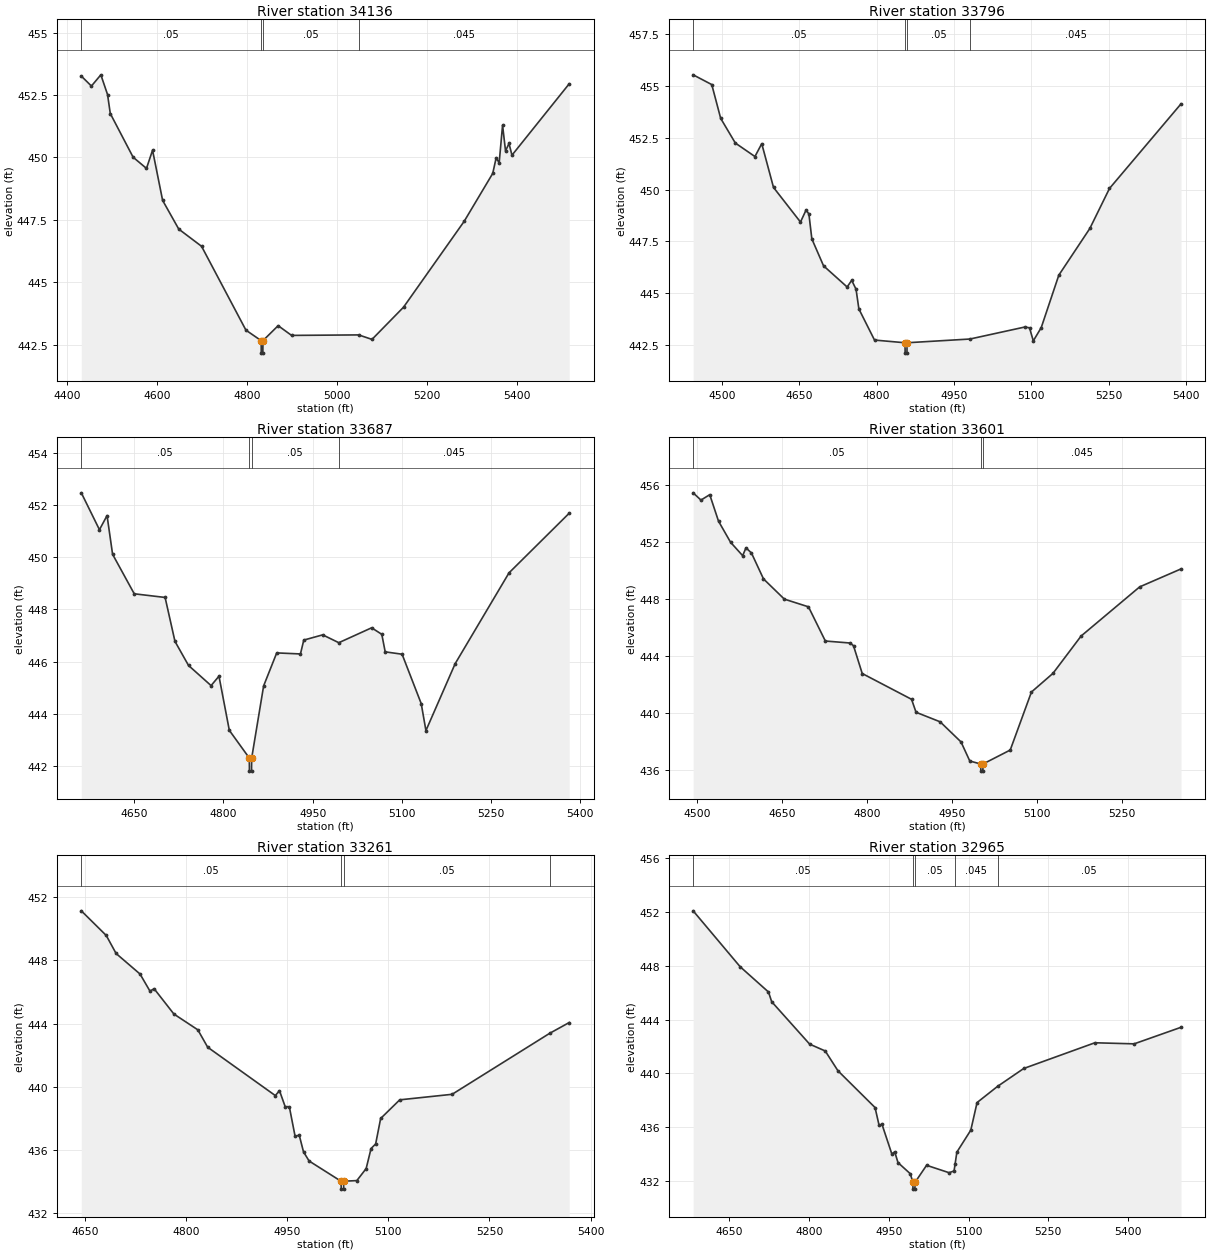
Type RM Length L Ch R = 1,34136,340,340,340
BEGIN DESCRIPTION:
Dry Creek34135.81
END DESCRIPTION:
XS GIS Cut Line= 3
      2736646.93      6847641.47      2736172.13      6847966.21
      2735785.32      6848299.92
#Sta/Elev= 30
  4431.1  453.26  4453.6  452.86  4474.6  453.31  4489.5  452.52  4495.6  451.76
  4546.4  450.01  4576.2  449.56  4589.7  450.29  4612.1  448.28  4648.0  447.13
  4698.8  446.44  4797.6  443.08  4831.5  442.66  4831.7  442.16  4835.2  442.16
  4835.5  442.66  4869.3  443.26  4899.2  442.87  5048.5  442.89  5078.2  442.71
  5148.4  444.00  5283.4  447.44  5347.0  449.36  5354.7  449.99  5361.3  449.78
  5368.9  451.29  5375.5  450.26  5383.2  450.56  5389.8  450.09  5517.2  452.95
#Mann=4,-1,0
  4431.1    0.05       0  4831.5    0.05       0  4835.5    0.05       0
  5048.5   0.045       0
Bank Sta=4831.5,4835.5
Exp/Cntr=0.3,0.1

Type RM Length L Ch R = 1,33796,109,109,109
BEGIN DESCRIPTION:
Dry Creek33796.32
END DESCRIPTION:
XS GIS Cut Line= 3
      2736504.50      6847451.10      2735996.58      6847688.43
      2735657.38      6847870.90
#Sta/Elev= 30
  4444.4  455.53  4480.5  455.06  4497.8  453.43  4526.2  452.24  4564.2  451.59
  4577.4  452.21  4600.2  450.10  4652.5  448.43  4663.3  449.01  4668.8  448.82
  4674.5  447.62  4697.2  446.32  4742.9  445.30  4751.8  445.62  4760.2  445.19
  4765.7  444.24  4796.0  442.74  4855.1  442.61  4855.4  442.11  4858.9  442.11
  4859.1  442.61  4981.0  442.79  5087.6  443.37  5096.5  443.33  5103.8  442.70
  5119.2  443.34  5153.3  445.87  5213.4  448.12  5251.5  450.05  5390.2  454.13
#Mann=4,-1,0
  4444.4    0.05       0  4855.1   0.045       0  4859.1    0.05       0
  4981.0   0.045       0
Bank Sta=4855.1,4859.1
Exp/Cntr=0.3,0.1

Type RM Length L Ch R = 1,33687,86,86,86
BEGIN DESCRIPTION:
Mapping XS f282cbba
END DESCRIPTION:
XS GIS Cut Line= 4
      2736373.65      6847399.22      2735974.85      6847585.90
      2735845.63      6847646.48      2735639.46      6847764.09
#Sta/Elev= 30
  4560.9  452.46  4591.4  451.05  4604.2  451.59  4613.5  450.11  4649.9  448.60
  4701.8  448.46  4718.4  446.78  4741.2  445.86  4779.1  445.09  4792.4  445.45
  4809.8  443.38  4843.4  442.32  4843.6  441.82  4847.1  441.82  4847.4  442.32
  4867.5  445.08  4889.5  446.34  4929.4  446.30  4935.0  446.83  4966.8  447.03
  4993.9  446.73  5049.1  447.30  5066.2  447.05  5071.9  446.38  5100.3  446.29
  5132.5  444.40  5140.4  443.37  5189.6  445.93  5280.1  449.40  5381.3  451.68
#Mann=4,-1,0
  4560.9    0.05       0  4843.4   0.045       0  4847.4    0.05       0
  4993.9   0.045       0
Bank Sta=4843.4,4847.4
Exp/Cntr=0.3,0.1

Type RM Length L Ch R = 1,33601,340,340,340
BEGIN DESCRIPTION:
Dry Creek33601
END DESCRIPTION:
XS GIS Cut Line= 3
      2736365.35      6847250.36      2735927.20      6847517.08
      2735620.86      6847682.92
#Sta/Elev= 30
  4492.9  455.42  4506.7  454.91  4522.2  455.29  4537.7  453.43  4559.0  451.95
  4580.3  451.01  4586.2  451.56  4595.8  451.20  4617.1  449.38  4653.9  447.96
  4696.5  447.42  4726.3  445.02  4770.1  444.88  4776.0  444.69  4791.4  442.74
  4878.5  440.93  4886.4  440.02  4929.0  439.35  4965.8  437.94  4981.3  436.60
  5000.6  436.39  5000.8  435.89  5004.3  435.89  5004.6  436.39  5052.7  437.37
  5090.1  441.44  5128.1  442.75  5177.8  445.37  5281.2  448.82  5354.2  450.08
#Mann=3,-1,0
  4492.9    0.05       0  5000.6    0.05       0  5004.6   0.045       0
Bank Sta=5000.6,5004.6
Exp/Cntr=0.3,0.1

Type RM Length L Ch R = 1,33261,296,296,296
BEGIN DESCRIPTION:
Mapping XS e41c643c
END DESCRIPTION:
XS GIS Cut Line= 3
      2736211.37      6846964.50      2735923.61      6847176.32
      2735655.18      6847425.39
#Sta/Elev= 30
  4644.8  451.13  4681.8  449.57  4696.4  448.43  4731.9  447.13  4746.6  446.05
  4752.8  446.20  4782.1  444.60  4817.6  443.60  4832.2  442.50  4932.5  439.44
  4938.7  439.75  4947.1  438.74  4953.3  438.73  4961.8  436.87  4968.0  436.93
  4974.3  435.88  4982.6  435.30  5030.0  434.02  5030.3  433.52  5033.8  433.52
  5034.0  434.02  5053.4  434.06  5067.2  434.82  5074.5  436.09  5081.3  436.38
  5088.7  437.99  5117.0  439.17  5194.7  439.52  5339.4  443.38  5368.3  444.06
#Mann=4,-1,0
  4644.8    0.05       0  5030.0    0.05       0  5034.0    0.05       0
  5339.4   0.045       0
Bank Sta=5030,5034
Exp/Cntr=0.3,0.1

Type RM Length L Ch R = 1,32965,281,281,281
BEGIN DESCRIPTION:
Dry Creek33167.51
END DESCRIPTION:
XS GIS Cut Line= 3
      2736212.70      6846752.39      2735825.60      6846911.17
      2735665.52      6847384.53
#Sta/Elev= 30
  4581.6  452.08  4670.0  447.93  4723.4  446.05  4729.4  445.33  4800.8  442.18
  4830.2  441.67  4854.1  440.20  4923.9  437.47  4931.5  436.15  4936.9  436.23
  4955.5  434.02  4960.9  434.18  4967.1  433.38  4990.3  432.55  4995.1  431.91
  4995.3  431.41  4998.8  431.41  4999.1  431.91  5020.9  433.18  5063.2  432.63
  5072.6  432.76  5074.5  433.26  5077.9  434.16  5104.1  435.79  5115.9  437.84
  5154.4  439.04  5203.7  440.37  5337.6  442.28  5411.5  442.20  5499.7  443.43
#Mann=5,-1,0
  4581.6    0.05       0  4995.1    0.05       0  4999.1    0.05       0
  5074.5   0.045       0  5154.4    0.05       0
Bank Sta=4995.1,4999.1
Exp/Cntr=0.3,0.1

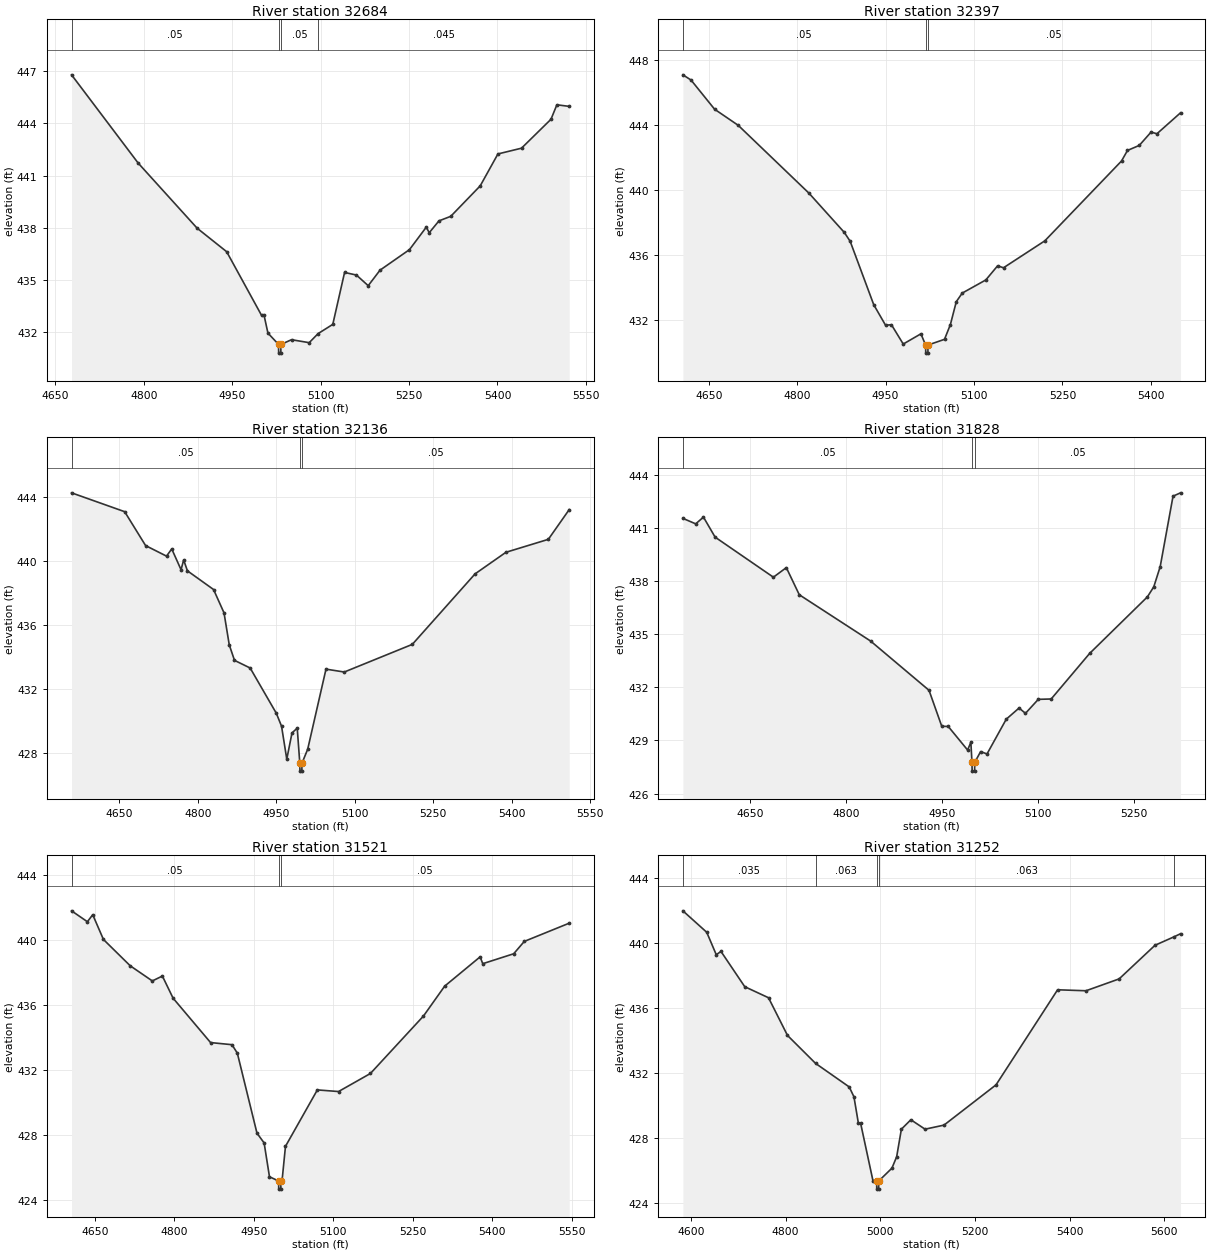
Type RM Length L Ch R = 1,32684,287,287,287
BEGIN DESCRIPTION:
Dry Creek32684.29
END DESCRIPTION:
XS GIS Cut Line= 3
      2736098.85      6846636.49      2735772.47      6846649.54
      2735255.15      6846661.54
#Sta/Elev= 30
  4677.6  446.78  4790.5  441.72  4890.6  437.98  4940.7  436.63  5000.0  432.97
  5004.2  432.97  5010.7  431.96  5028.7  431.31  5028.9  430.81  5032.5  430.81
  5032.8  431.31  5050.7  431.58  5080.7  431.41  5095.8  431.93  5120.7  432.46
  5140.7  435.44  5160.8  435.29  5180.8  434.68  5200.8  435.57  5250.8  436.75
  5279.3  438.04  5284.3  437.72  5300.8  438.40  5320.8  438.66  5370.8  440.41
  5400.8  442.24  5440.8  442.57  5490.8  444.23  5500.8  445.06  5521.7  444.97
#Mann=4,-1,0
  4677.6    0.05       0  5028.7    0.05       0  5032.8    0.05       0
  5095.8   0.045       0
Bank Sta=5028.7,5032.8
Exp/Cntr=0.3,0.1

Type RM Length L Ch R = 1,32397,261,261,261
BEGIN DESCRIPTION:
Dry Creek32396.83
END DESCRIPTION:
XS GIS Cut Line= 3
      2736119.75      6846373.75      2735723.08      6846378.21
      2735276.05      6846398.80
#Sta/Elev= 30
  4606.2  447.10  4620.0  446.78  4660.0  444.98  4700.0  443.99  4820.0  439.81
  4880.0  437.39  4890.0  436.84  4930.0  432.93  4950.0  431.67  4960.0  431.70
  4980.0  430.51  5010.0  431.14  5017.9  430.45  5018.2  429.95  5021.8  429.95
  5022.1  430.45  5050.0  430.80  5060.0  431.71  5070.0  433.12  5080.1  433.65
  5120.1  434.46  5140.1  435.33  5150.1  435.21  5220.2  436.87  5350.3  441.79
  5360.4  442.44  5380.4  442.75  5400.4  443.57  5410.4  443.47  5450.4  444.76
#Mann=3,-1,0
  4606.2    0.05       0  5017.9    0.05       0  5022.1    0.05       0
Bank Sta=5017.9,5022.1
Exp/Cntr=0.3,0.1

Type RM Length L Ch R = 1,32136,308,308,308
BEGIN DESCRIPTION:
Dry Creek32135.95
END DESCRIPTION:
XS GIS Cut Line= 3
      2736167.57      6846114.77      2735726.91      6846117.32
      2735216.09      6846102.63
#Sta/Elev= 30
  4558.4  444.27  4660.0  443.09  4700.0  440.97  4740.0  440.31  4750.0  440.76
  4767.8  439.46  4772.8  440.07  4780.0  439.39  4830.0  438.22  4850.0  436.76
  4860.0  434.76  4870.0  433.79  4900.0  433.31  4950.0  430.48  4960.0  429.67
  4970.0  427.61  4980.0  429.25  4990.0  429.55  4994.9  427.36  4995.2  426.86
  4998.8  426.86  4999.1  427.36  5010.0  428.23  5045.0  433.24  5080.0  433.06
  5210.1  434.79  5330.1  439.20  5389.1  440.55  5470.2  441.36  5510.1  443.22
#Mann=3,-1,0
  4558.4    0.05       0  4994.9    0.05       0  4999.1    0.05       0
Bank Sta=4994.9,4999.1
Exp/Cntr=0.3,0.1

Type RM Length L Ch R = 1,31828,307,307,307
BEGIN DESCRIPTION:
Dry Creek31827.85
END DESCRIPTION:
XS GIS Cut Line= 3
      2736225.78      6845890.15      2735773.49      6845824.89
      2735454.32      6845812.14
#Sta/Elev= 30
  4545.7  441.53  4565.7  441.22  4577.8  441.60  4596.0  440.47  4686.9  438.21
  4707.1  438.75  4727.3  437.22  4838.5  434.61  4929.7  431.83  4949.6  429.80
  4959.7  429.79  4989.9  428.46  4995.0  428.90  4996.7  427.77  4997.0  427.27
  5000.8  427.27  5001.1  427.77  5010.2  428.37  5020.2  428.24  5050.2  430.20
  5070.2  430.83  5080.2  430.53  5100.2  431.32  5120.3  431.34  5180.3  433.91
  5270.4  437.10  5280.4  437.67  5290.4  438.81  5310.4  442.78  5322.1  442.97
#Mann=3,-1,0
  4545.7    0.05       0  4996.7    0.05       0  5001.1    0.05       0
Bank Sta=4996.7,5001.1
Exp/Cntr=0.3,0.1

Type RM Length L Ch R = 1,31521,269,269,269
BEGIN DESCRIPTION:
Dry Creek31520.76
END DESCRIPTION:
XS GIS Cut Line= 3
      2736265.58      6845607.95      2735872.55      6845549.28
      2735331.37      6845515.69
#Sta/Elev= 30
  4606.0  441.78  4635.9  441.11  4646.0  441.54  4666.2  440.02  4716.8  438.40
  4758.5  437.47  4777.5  437.77  4797.7  436.41  4868.5  433.68  4908.9  433.55
  4919.0  433.03  4956.1  428.11  4969.6  427.51  4979.7  425.43  4996.9  425.17
  4997.2  424.67  5001.1  424.67  5001.4  425.17  5003.4  425.17  5009.9  427.30
  5070.1  430.77  5110.1  430.67  5170.3  431.78  5270.4  435.31  5310.5  437.15
  5377.4  438.95  5382.4  438.53  5440.8  439.14  5460.8  439.90  5545.6  441.02
#Mann=3,-1,0
  4606.0    0.05       0  4996.9    0.05       0  5001.4    0.05       0
Bank Sta=4996.9,5001.4
Exp/Cntr=0.3,0.1

Type RM Length L Ch R = 1,31252,174,174,174
BEGIN DESCRIPTION:
Dry Creek31252.38
END DESCRIPTION:
XS GIS Cut Line= 3
      2736386.28      6845345.84      2735970.69      6845312.62
      2735336.35      6845305.40
#Sta/Elev= 30
  4583.0  441.99  4633.4  440.67  4653.5  439.29  4663.5  439.49  4713.7  437.32
  4763.9  436.64  4804.0  434.32  4863.3  432.60  4934.4  431.15  4944.4  430.54
  4953.5  428.96  4958.5  428.91  4984.6  425.37  4992.3  425.36  4992.6  424.86
  4996.5  424.86  4996.8  425.36  5024.6  426.15  5034.6  426.85  5044.6  428.55
  5064.6  429.13  5094.6  428.55  5134.6  428.80  5244.6  431.28  5374.6  437.13
  5434.6  437.07  5504.6  437.80  5580.4  439.87  5621.3  440.40  5634.3  440.58
#Mann=5,-1,0
  4583.0   0.035       0  4863.3   0.063       0  4992.3   0.063       0
  4996.8   0.063       0  5621.3   0.035       0
Bank Sta=4992.3,4996.8
Exp/Cntr=0.3,0.1

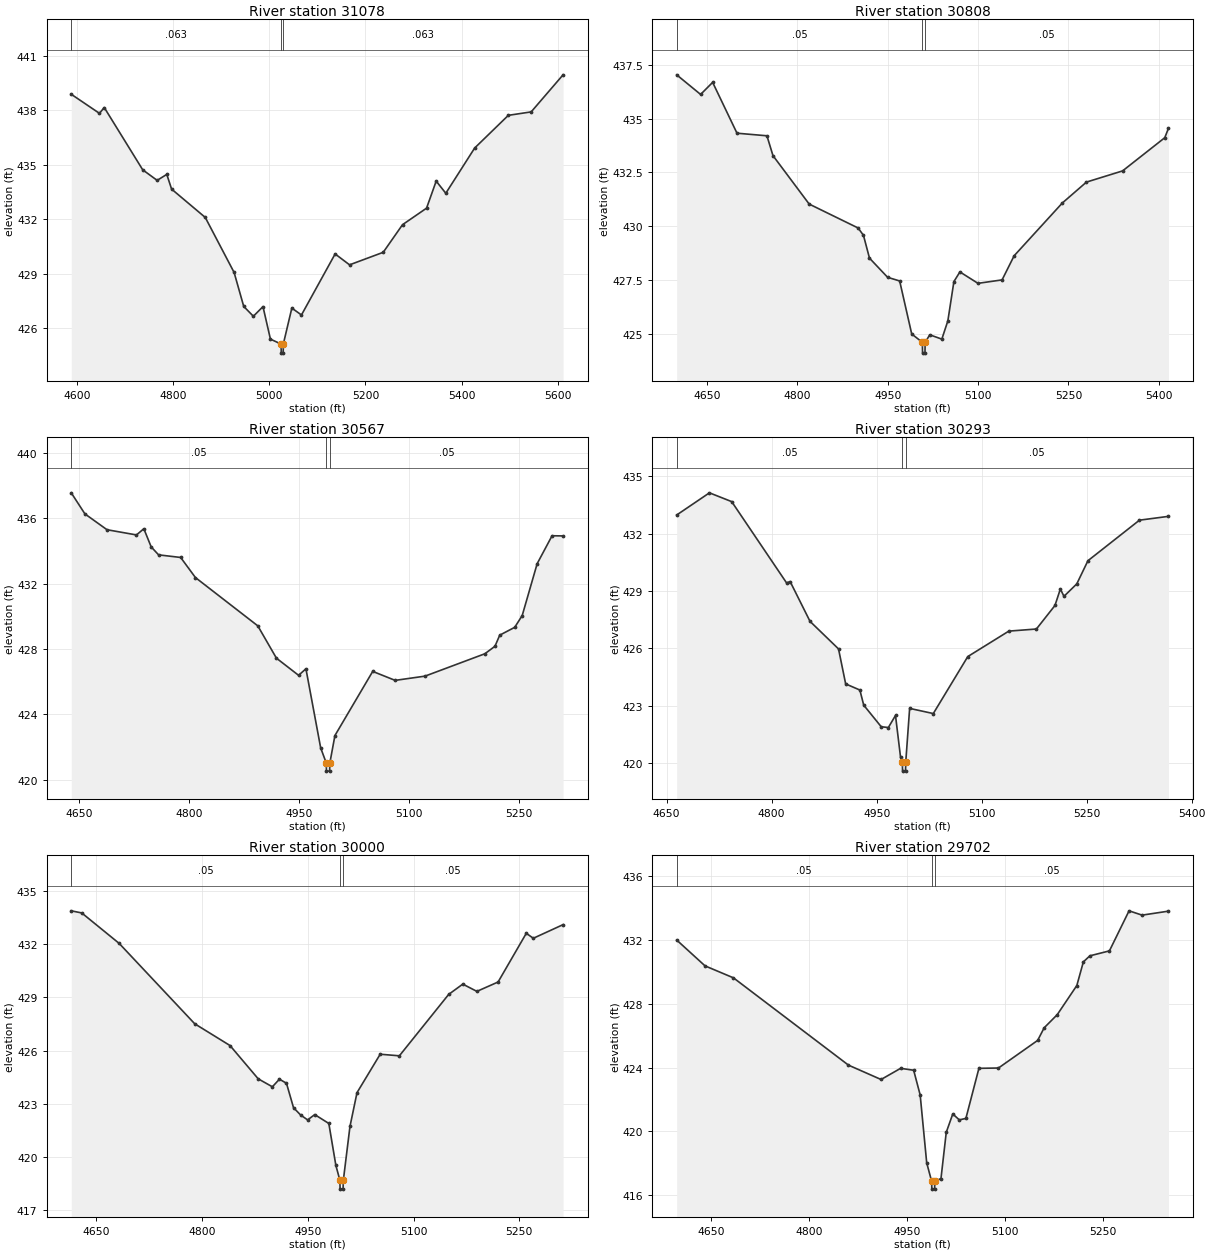
Type RM Length L Ch R = 1,31078,270,270,270
BEGIN DESCRIPTION:
Dry Creek31078.25
END DESCRIPTION:
XS GIS Cut Line= 3
      2736404.54      6845135.86      2735990.11      6845144.23
      2735382.19      6845135.03
#Sta/Elev= 30
  4588.4  438.88  4647.0  437.83  4657.0  438.15  4737.0  434.72  4767.0  434.14
  4787.0  434.47  4797.0  433.66  4867.0  432.10  4927.0  429.07  4947.0  427.20
  4967.0  426.66  4987.0  427.19  5002.5  425.40  5024.7  425.13  5025.0  424.63
  5029.0  424.63  5029.3  425.13  5047.0  427.11  5067.0  426.73  5137.0  430.09
  5167.0  429.49  5237.0  430.18  5277.1  431.70  5327.1  432.61  5347.1  434.10
  5367.1  433.43  5427.1  435.92  5497.1  437.72  5544.6  437.91  5610.9  439.95
#Mann=3,-1,0
  4588.4   0.063       0  5024.7   0.063       0  5029.3   0.063       0
Bank Sta=5024.7,5029.3
Exp/Cntr=0.3,0.1

Type RM Length L Ch R = 1,30808,241,241,241
BEGIN DESCRIPTION:
Dry Creek30808.07
END DESCRIPTION:
XS GIS Cut Line= 3
      2736475.64      6844920.73      2736075.13      6844900.85
      2735659.84      6844898.79
#Sta/Elev= 30
  4599.8  437.03  4639.5  436.12  4659.5  436.68  4699.9  434.32  4749.6  434.20
  4759.6  433.28  4819.7  431.03  4900.9  429.92  4909.8  429.58  4919.8  428.52
  4949.9  427.63  4969.9  427.46  4989.9  425.00  5007.6  424.61  5007.9  424.11
  5011.9  424.11  5012.2  424.61  5019.9  424.96  5039.9  424.76  5049.9  425.61
  5059.9  427.43  5069.9  427.88  5099.9  427.35  5139.9  427.51  5159.9  428.63
  5239.9  431.08  5279.9  432.05  5339.9  432.57  5409.9  434.11  5416.1  434.55
#Mann=3,-1,0
  4599.8    0.05       0  5007.6    0.05       0  5012.2    0.05       0
Bank Sta=5007.6,5012.2
Exp/Cntr=0.3,0.1

Type RM Length L Ch R = 1,30567,274,274,274
BEGIN DESCRIPTION:
Dry Creek30566.61
END DESCRIPTION:
XS GIS Cut Line= 3
      2736484.50      6844642.98      2736122.32      6844675.97
      2735821.30      6844733.78
#Sta/Elev= 30
  4639.7  437.57  4658.3  436.28  4688.4  435.31  4728.6  434.99  4738.6  435.37
  4748.6  434.26  4758.7  433.77  4788.8  433.61  4808.9  432.38  4893.9  429.42
  4919.3  427.44  4949.5  426.39  4959.5  426.79  4979.6  421.94  4987.2  421.02
  4987.5  420.52  4991.7  420.52  4992.1  421.02  4999.0  422.70  5050.5  426.63
  5081.1  426.08  5121.8  426.34  5203.3  427.71  5217.1  428.17  5223.6  428.85
  5244.0  429.33  5254.2  430.05  5274.6  433.23  5294.9  434.94  5309.9  434.93
#Mann=3,-1,0
  4639.7    0.05       0  4987.2    0.05       0  4992.1    0.05       0
Bank Sta=4987.2,4992.1
Exp/Cntr=0.3,0.1

Type RM Length L Ch R = 1,30293,293,293,293
BEGIN DESCRIPTION:
Dry Creek30292.98
END DESCRIPTION:
XS GIS Cut Line= 3
      2736253.21      6844446.66      2735921.22      6844508.94
      2735569.76      6844606.76
#Sta/Elev= 30
  4664.3  432.97  4711.1  434.13  4742.9  433.67  4821.3  429.42  4826.4  429.49
  4854.8  427.41  4895.5  425.97  4905.7  424.14  4926.0  423.82  4931.5  423.03
  4956.5  421.90  4966.7  421.86  4976.9  422.49  4984.1  420.31  4986.7  420.08
  4987.0  419.58  4991.2  419.58  4991.6  420.08  4997.1  422.86  5030.9  422.59
  5080.2  425.57  5138.8  426.90  5178.2  427.01  5204.7  428.24  5212.4  429.10
  5217.6  428.72  5235.9  429.37  5251.8  430.58  5325.4  432.70  5366.9  432.90
#Mann=3,-1,0
  4664.3    0.05       0  4986.7    0.05       0  4991.6    0.05       0
Bank Sta=4986.7,4991.6
Exp/Cntr=0.3,0.1

Type RM Length L Ch R = 1,30000,298,298,298
BEGIN DESCRIPTION:
Dry Creek29999.8
END DESCRIPTION:
XS GIS Cut Line= 3
      2736160.90      6844252.25      2735774.75      6844274.28
      2735463.82      6844285.10
#Sta/Elev= 30
  4614.3  433.89  4629.2  433.77  4682.3  432.05  4789.5  427.51  4839.6  426.28
  4879.6  424.40  4899.7  423.95  4909.7  424.38  4919.7  424.15  4929.7  422.77
  4939.7  422.36  4949.7  422.08  4959.8  422.38  4979.8  421.88  4989.8  419.51
  4995.5  418.67  4995.8  418.17  5000.0  418.17  5000.4  418.67  5009.8  421.71
  5019.8  423.62  5052.7  425.79  5079.9  425.70  5149.9  429.17  5169.9  429.75
  5189.9  429.34  5220.0  429.87  5260.0  432.62  5270.0  432.34  5312.2  433.11
#Mann=3,-1,0
  4614.3    0.05       0  4995.5    0.05       0  5000.4    0.05       0
Bank Sta=4995.5,5000.4
Exp/Cntr=0.3,0.1

Type RM Length L Ch R = 1,29702,175,175,175
BEGIN DESCRIPTION:
Dry Creek29702.01
END DESCRIPTION:
XS GIS Cut Line= 3
      2736129.48      6843996.93      2735724.13      6843992.53
      2735375.55      6844010.26
#Sta/Elev= 30
  4596.7  431.99  4640.2  430.37  4683.8  429.62  4860.2  424.15  4910.2  423.25
  4940.2  423.95  4960.2  423.83  4970.2  422.28  4980.2  418.03  4987.7  416.88
  4988.1  416.38  4992.3  416.38  4992.7  416.88  5002.1  417.04  5010.2  419.94
  5020.2  421.09  5030.2  420.72  5040.3  420.81  5060.3  423.95  5090.3  423.97
  5150.4  425.70  5160.4  426.49  5180.4  427.31  5210.5  429.14  5220.5  430.62
  5230.5  431.00  5260.5  431.31  5290.6  433.82  5310.6  433.55  5351.1  433.80
#Mann=3,-1,0
  4596.7    0.05       0  4987.7    0.05       0  4992.7    0.05       0
Bank Sta=4987.7,4992.7
Exp/Cntr=0.3,0.1

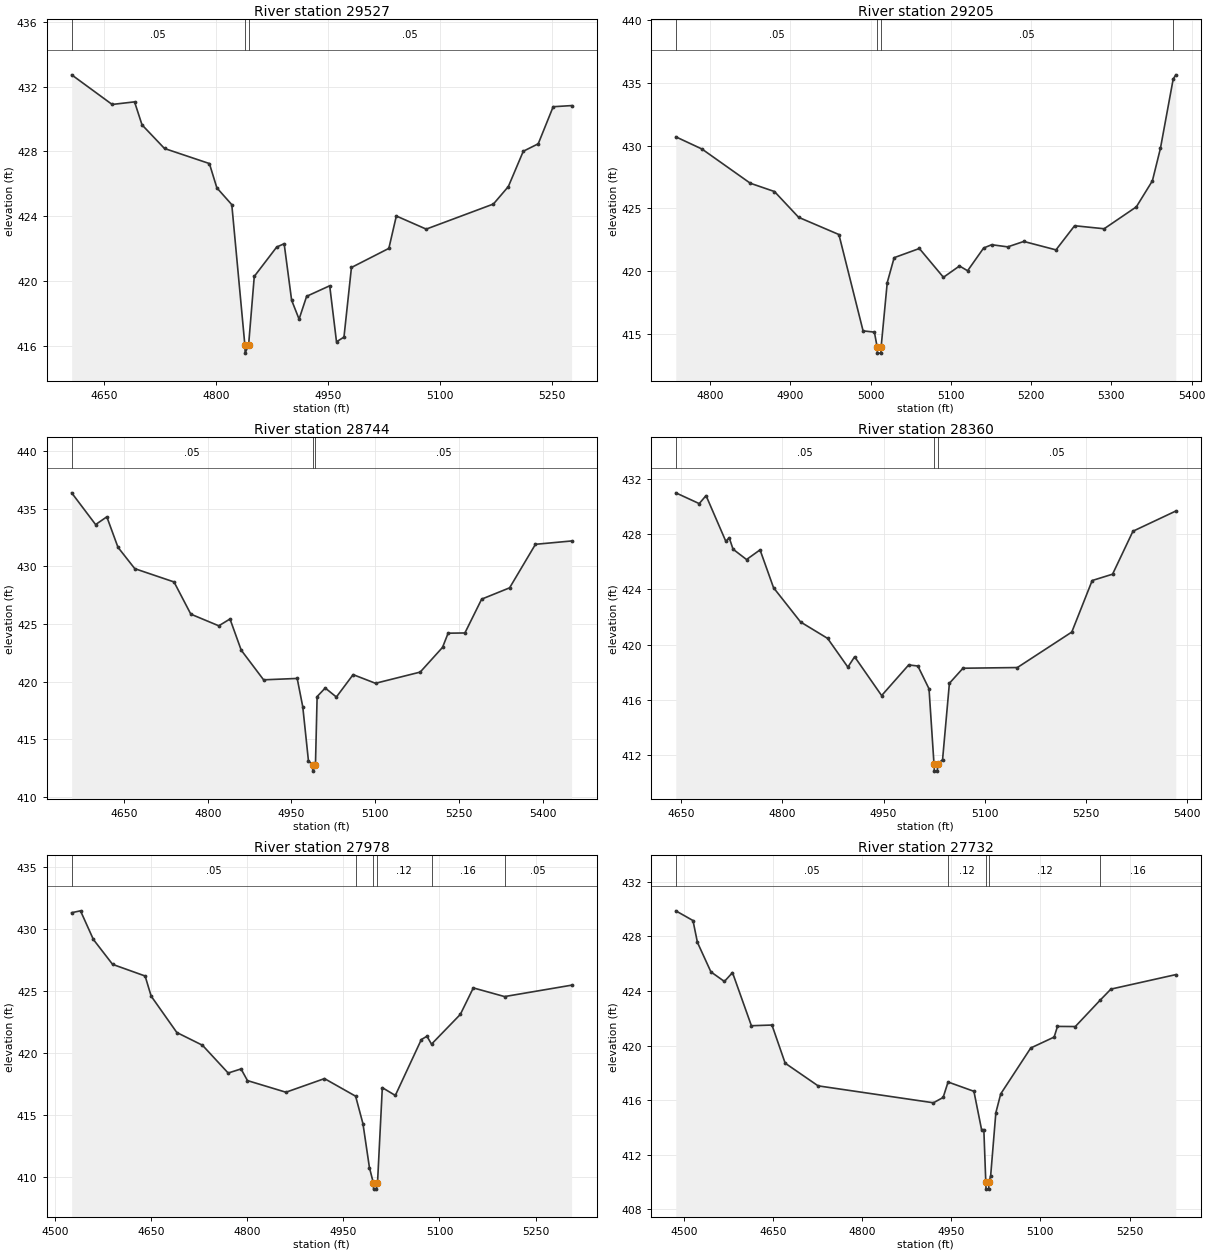
Type RM Length L Ch R = 1,29527,322,322,322
BEGIN DESCRIPTION:
Dry Creek29527.3
END DESCRIPTION:
XS GIS Cut Line= 3
      2736150.12      6843807.93      2735754.81      6843828.88
      2735481.28      6843826.73
#Sta/Elev= 30
  4606.8  432.73  4661.0  430.90  4691.0  431.06  4701.0  429.64  4731.1  428.18
  4791.2  427.25  4801.2  425.75  4821.2  424.71  4838.7  416.04  4839.1  415.54
  4843.7  416.04  4851.3  420.28  4881.3  422.09  4891.3  422.30  4901.3  418.81
  4911.3  417.64  4921.4  419.05  4952.3  419.70  4961.4  416.24  4971.4  416.53
  4981.4  420.83  5031.5  422.01  5041.5  424.01  5081.5  423.20  5171.5  424.75
  5191.5  425.83  5211.5  428.01  5231.5  428.47  5251.5  430.76  5276.2  430.83
#Mann=3,-1,0
  4606.8    0.05       0  4838.7    0.05       0  4843.7    0.05       0
Bank Sta=4838.7,4843.7
Exp/Cntr=0.3,0.1

Type RM Length L Ch R = 1,29205,461,461,461
BEGIN DESCRIPTION:
Dry Creek29205.14
END DESCRIPTION:
XS GIS Cut Line= 3
      2736168.51      6843574.57      2735921.94      6843594.72
      2735546.92      6843611.82
#Sta/Elev= 30
  4757.4  430.69  4790.0  429.72  4850.2  427.00  4880.3  426.34  4910.4  424.29
  4960.6  422.92  4990.7  415.26  5004.8  415.16  5008.2  413.99  5008.6  413.49
  5012.9  413.49  5013.2  413.99  5020.8  419.10  5029.4  421.08  5060.8  421.81
  5090.8  419.52  5110.8  420.42  5120.9  420.04  5140.9  421.85  5150.9  422.11
  5170.9  421.94  5190.9  422.37  5231.0  421.70  5254.2  423.62  5291.0  423.38
  5331.1  425.12  5351.1  427.19  5361.1  429.77  5377.0  435.28  5380.2  435.62
#Mann=4,-1,0
  4757.4    0.05       0  5008.2    0.05       0  5013.2    0.05       0
  5377.0   0.033       0
Bank Sta=5008.2,5013.2
Exp/Cntr=0.3,0.1

Type RM Length L Ch R = 1,28744,384,384,384
BEGIN DESCRIPTION:
Dry Creek28613.66
END DESCRIPTION:
XS GIS Cut Line= 3
      2736218.74      6843169.86      2735776.44      6843206.27
      2735325.02      6843229.22
#Sta/Elev= 30
  4556.2  436.36  4599.1  433.61  4619.2  434.28  4639.2  431.64  4669.3  429.79
  4739.6  428.64  4769.7  425.85  4819.8  424.84  4839.9  425.43  4860.0  422.73
  4900.1  420.16  4960.3  420.28  4970.3  417.82  4980.4  413.17  4987.8  412.75
  4988.2  412.25  4993.0  412.75  4996.0  418.71  5010.5  419.45  5030.5  418.67
  5060.5  420.61  5100.6  419.86  5180.7  420.83  5220.7  422.97  5230.7  424.20
  5260.8  424.22  5290.8  427.15  5340.9  428.13  5387.2  431.90  5452.0  432.19
#Mann=3,-1,0
  4556.2    0.05       0  4987.8    0.05       0  4993.0    0.05       0
Bank Sta=4987.8,4993
Exp/Cntr=0.3,0.1

Type RM Length L Ch R = 1,28360,382,382,382
BEGIN DESCRIPTION:
Dry Creek28360.3
END DESCRIPTION:
XS GIS Cut Line= 3
      2736040.72      6842843.12      2735682.35      6842856.28
      2735303.04      6842901.42
#Sta/Elev= 30
  4642.3  430.99  4677.0  430.21  4687.1  430.79  4716.4  427.48  4721.4  427.74
  4727.1  426.91  4747.1  426.16  4767.1  426.86  4787.1  424.12  4827.1  421.64
  4867.2  420.45  4897.2  418.37  4907.2  419.12  4947.2  416.31  4987.3  418.53
  5000.9  418.45  5017.4  416.80  5024.8  411.34  5025.3  410.84  5029.7  410.84
  5030.1  411.34  5037.5  411.68  5047.6  417.20  5067.7  418.29  5148.3  418.34
  5228.9  420.91  5259.1  424.64  5289.3  425.10  5319.5  428.21  5382.9  429.67
#Mann=3,-1,0
  4642.3    0.05       0  5024.8    0.05       0  5030.1    0.05       0
Bank Sta=5024.8,5030.1
Exp/Cntr=0.3,0.1

Type RM Length L Ch R = 1,27978,246,246,246
BEGIN DESCRIPTION:
Dry Creek27977.86
END DESCRIPTION:
XS GIS Cut Line= 3
      2736049.78      6842538.11      2735573.39      6842572.29
      2735274.69      6842623.67
#Sta/Elev= 30
  4525.7  431.35  4539.5  431.50  4559.6  429.19  4589.6  427.18  4640.4  426.24
  4649.8  424.62  4689.9  421.68  4730.0  420.65  4770.1  418.41  4790.2  418.74
  4800.2  417.80  4860.3  416.86  4920.5  417.96  4969.1  416.54  4980.6  414.31
  4990.7  410.77  4996.8  409.54  4997.2  409.04  5001.7  409.04  5002.1  409.54
  5003.3  409.54  5010.8  417.23  5031.1  416.60  5071.7  421.11  5080.5  421.38
  5087.6  420.74  5132.6  423.14  5152.9  425.28  5201.7  424.58  5306.4  425.50
#Mann=6,-1,0
  4525.7    0.05       0  4969.1    0.12       0  4996.8    0.07       0
  5002.1    0.12       0  5087.6    0.16       0  5201.7    0.05       0
Bank Sta=4996.8,5002.1
Exp/Cntr=0.3,0.1

Type RM Length L Ch R = 1,27732,211,211,211
BEGIN DESCRIPTION:
Dry Creek27732.15
END DESCRIPTION:
XS GIS Cut Line= 3
      2735992.14      6842179.58      2735524.16      6842402.27
      2735234.36      6842544.77
#Sta/Elev= 30
  4486.6  429.86  4515.5  429.15  4523.0  427.55  4545.7  425.39  4568.4  424.69
  4582.0  425.34  4613.8  421.45  4648.4  421.50  4670.6  418.71  4726.0  417.05
  4920.1  415.81  4936.4  416.20  4944.7  417.33  4988.2  416.65  5001.1  413.84
  5004.9  413.84  5008.2  409.99  5008.6  409.49  5013.1  409.49  5013.5  409.99
  5016.4  410.48  5025.1  415.08  5033.3  416.46  5083.8  419.82  5123.2  420.62
  5128.8  421.40  5158.8  421.39  5200.8  423.33  5218.7  424.13  5327.8  425.19
#Mann=5,-1,0
  4486.6    0.05       0  4944.7    0.12       0  5008.2    0.07       0
  5013.5    0.12       0  5200.8    0.16       0
Bank Sta=5008.2,5013.5
Exp/Cntr=0.3,0.1