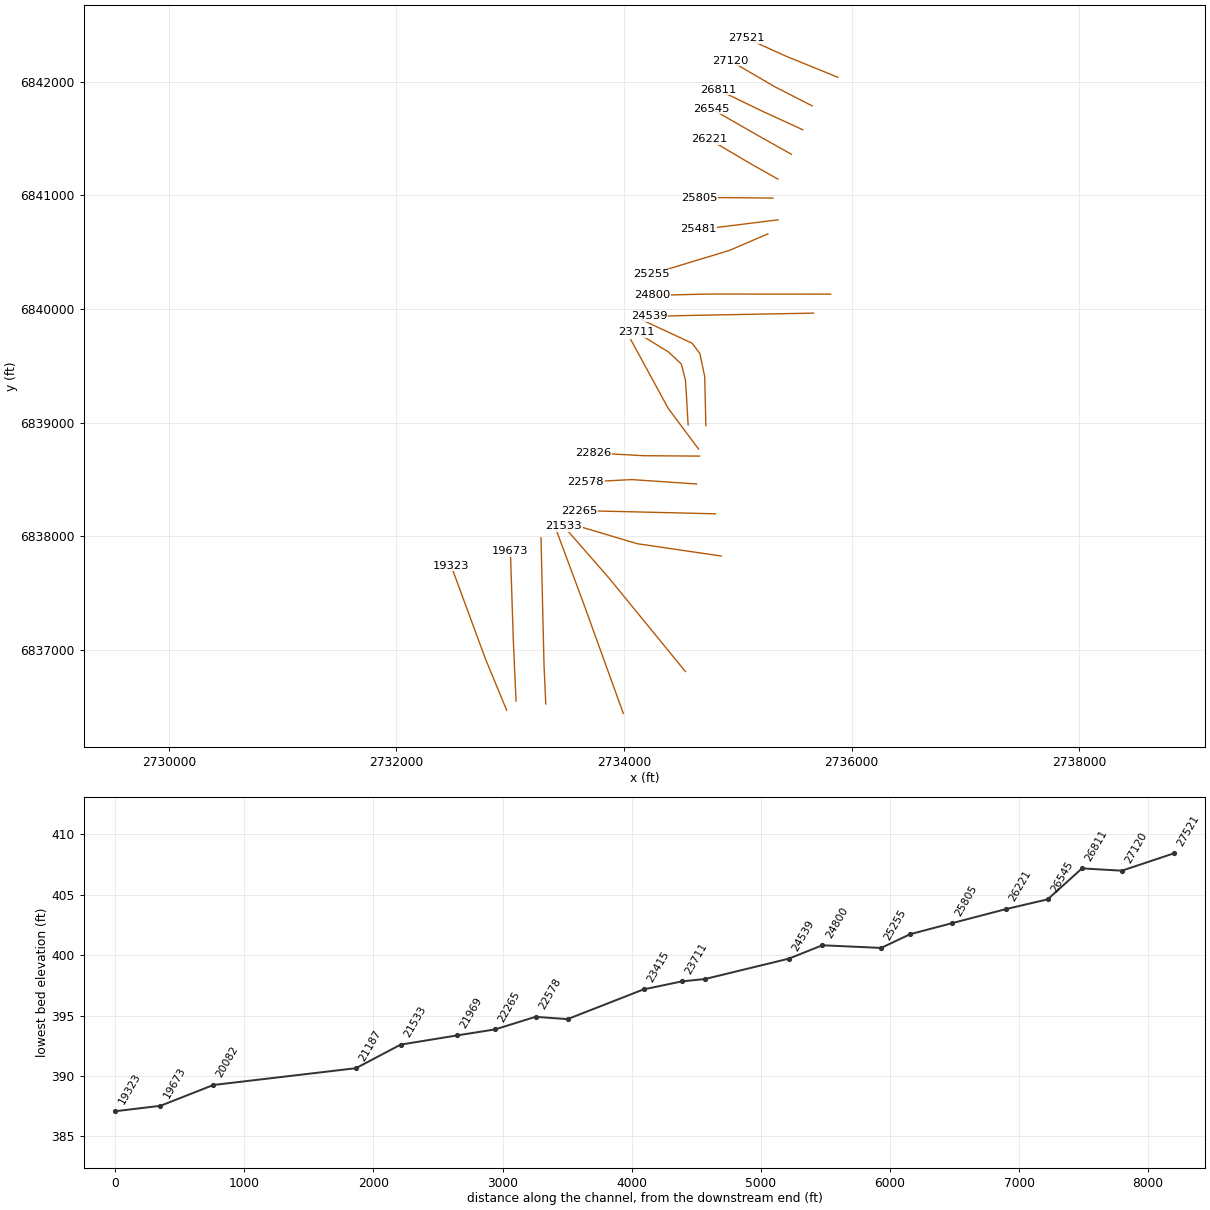
HEC-RAS study Dry Creek.prj: Dry Creek Base Level Engineering

--- Dry Creek.g01 (geometry) --- (continued)

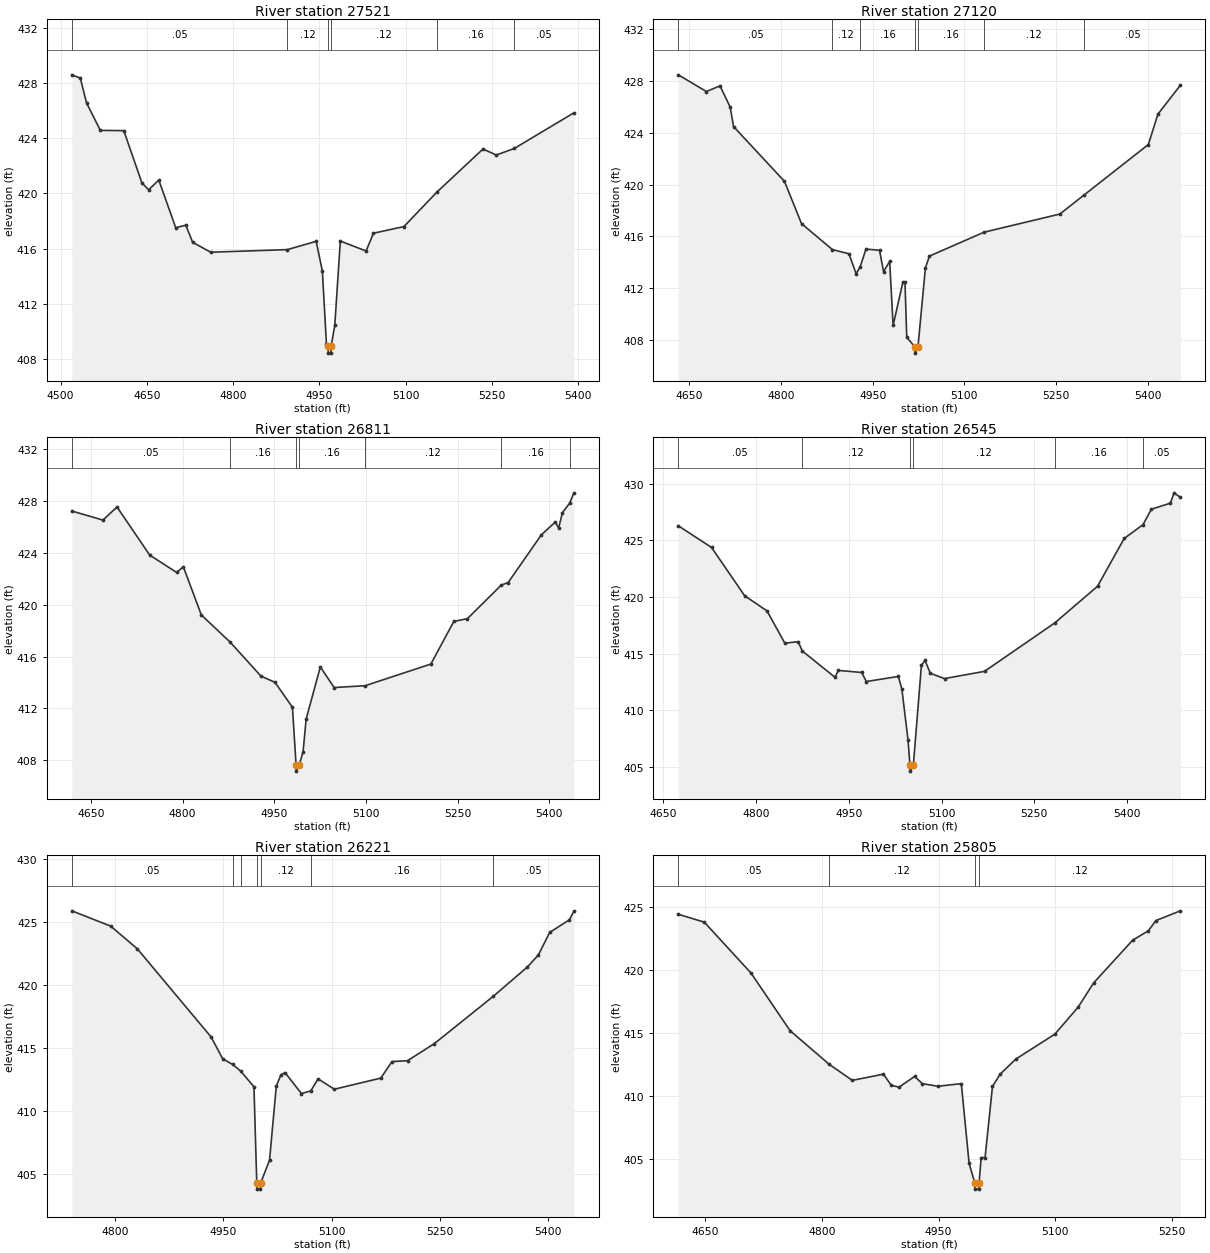
Type RM Length L Ch R = 1,27521,401,401,401
BEGIN DESCRIPTION:
Dry Creek27521.11
END DESCRIPTION:
XS GIS Cut Line= 3
      2735879.79      6842038.38      2735427.42      6842222.48
      2735076.61      6842380.87
#Sta/Elev= 30
  4519.4  428.60  4534.3  428.36  4545.1  426.56  4569.1  424.57  4609.9  424.55
  4641.3  420.77  4653.0  420.26  4670.8  420.96  4700.2  417.51  4717.8  417.69
  4729.7  416.45  4761.0  415.73  4894.4  415.92  4944.5  416.52  4955.3  414.35
  4962.4  409.06  4965.1  408.91  4965.6  408.41  4970.1  408.41  4970.5  408.91
  4976.9  410.44  4986.5  416.54  5031.3  415.82  5044.2  417.11  5097.1  417.59
  5154.7  420.10  5234.7  423.22  5257.8  422.78  5289.2  423.26  5392.7  425.84
#Mann=6,-1,0
  4519.4    0.05       0  4894.4    0.12       0  4965.1    0.07       0
  4970.5    0.12       0  5154.7    0.16       0  5289.2    0.05       0
Bank Sta=4965.1,4970.5
Exp/Cntr=0.3,0.1

Type RM Length L Ch R = 1,27120,309,309,309
BEGIN DESCRIPTION:
Dry Creek27120.31
END DESCRIPTION:
XS GIS Cut Line= 3
      2735655.01      6841786.54      2735324.88      6841955.38
      2734936.09      6842182.57
#Sta/Elev= 30
  4632.0  428.49  4678.1  427.20  4700.3  427.64  4716.9  426.00  4722.5  424.49
  4805.7  420.26  4833.6  416.99  4884.2  414.98  4911.2  414.66  4922.9  413.12
  4929.4  413.63  4939.0  415.02  4961.2  414.93  4967.8  413.28  4977.8  414.07
  4983.4  409.12  4999.4  412.47  5002.8  412.47  5005.7  408.20  5018.7  407.48
  5019.1  406.98  5024.1  407.48  5036.2  413.56  5042.8  414.48  5132.3  416.33
  5256.1  417.73  5296.2  419.22  5400.8  423.10  5416.5  425.45  5453.1  427.68
#Mann=7,-1,0
  4632.0    0.05       0  4884.2    0.12       0  4929.4    0.16       0
  5018.7    0.07       0  5024.1    0.16       0  5132.3    0.12       0
  5296.2    0.05       0
Bank Sta=5018.7,5024.1
Exp/Cntr=0.3,0.1

Type RM Length L Ch R = 1,26811,266,266,266
BEGIN DESCRIPTION:
Dry Creek26810.78
END DESCRIPTION:
XS GIS Cut Line= 3
      2735571.83      6841576.76      2735222.07      6841737.34
      2734829.30      6841927.17
#Sta/Elev= 30
  4618.9  427.21  4669.9  426.51  4692.9  427.52  4746.4  423.81  4790.4  422.48
  4801.4  422.91  4830.8  419.20  4877.7  417.12  4928.3  414.49  4951.3  414.01
  4979.8  412.09  4985.7  407.67  4986.1  407.17  4991.1  407.67  4997.2  408.67
  5002.2  411.18  5025.4  415.20  5048.0  413.61  5098.7  413.75  5206.2  415.42
  5243.7  418.70  5266.0  418.92  5321.3  421.50  5332.6  421.70  5387.0  425.38
  5409.6  426.36  5415.1  425.90  5421.4  427.09  5433.3  427.82  5440.0  428.61
#Mann=7,-1,0
  4618.9    0.05       0  4877.7    0.16       0  4985.7    0.07       0
  4991.1    0.16       0  5098.7    0.12       0  5321.3    0.16       0
  5433.3    0.05       0
Bank Sta=4985.7,4991.1
Exp/Cntr=0.3,0.1

Type RM Length L Ch R = 1,26545,324,324,324
BEGIN DESCRIPTION:
Dry Creek26544.83
END DESCRIPTION:
XS GIS Cut Line= 3
      2735471.14      6841361.38      2735183.06      6841523.40
      2734765.36      6841762.89
#Sta/Elev= 30
  4674.2  426.30  4728.1  424.38  4781.6  420.11  4817.8  418.77  4846.6  415.92
  4868.3  416.05  4874.8  415.23  4927.6  412.91  4933.3  413.51  4970.9  413.33
  4978.4  412.53  5030.1  412.98  5035.9  411.86  5045.9  407.33  5049.0  405.11
  5049.4  404.61  5054.4  405.11  5067.5  413.97  5073.3  414.40  5082.0  413.25
  5104.9  412.79  5169.6  413.43  5283.4  417.72  5352.3  420.95  5395.5  425.18
  5425.8  426.39  5439.4  427.76  5470.3  428.30  5476.0  429.21  5486.2  428.82
#Mann=6,-1,0
  4674.2    0.05       0  4874.8    0.12       0  5049.0    0.07       0
  5054.4    0.12       0  5283.4    0.16       0  5425.8    0.05       0
Bank Sta=5049,5054.4
Exp/Cntr=0.3,0.1

Type RM Length L Ch R = 1,26221,416,416,416
BEGIN DESCRIPTION:
Dry Creek26221.24
END DESCRIPTION:
XS GIS Cut Line= 3
      2735352.93      6841142.96      2735122.88      6841272.60
      2734750.34      6841491.99
#Sta/Elev= 30
  4739.7  425.86  4793.6  424.65  4830.6  422.85  4933.1  415.85  4949.0  414.13
  4962.9  413.68  4974.0  413.16  4992.4  411.91  4996.3  404.30  4996.8  403.80
  5001.4  403.80  5001.8  404.30  5014.0  406.09  5023.4  411.96  5029.7  412.85
  5035.5  413.04  5058.2  411.38  5071.1  411.58  5081.4  412.54  5103.9  411.72
  5168.3  412.60  5183.9  413.91  5205.4  413.98  5242.5  415.33  5324.5  419.09
  5371.5  421.40  5386.9  422.36  5402.6  424.15  5429.8  425.14  5436.1  425.81
#Mann=7,-1,0
  4739.7    0.05       0  4962.9    0.16       0  4974.0    0.12       0
  4996.3    0.07       0  5001.8    0.12       0  5071.1    0.16       0
  5324.5    0.05       0
Bank Sta=4996.3,5001.8
Exp/Cntr=0.3,0.1

Type RM Length L Ch R = 1,25805,324,324,324
BEGIN DESCRIPTION:
Dry Creek25805.31
END DESCRIPTION:
XS GIS Cut Line= 3
      2735309.49      6840975.90      2734920.10      6840979.68
      2734664.81      6840980.14
#Sta/Elev= 30
  4615.7  424.45  4649.2  423.82  4709.2  419.78  4759.2  415.22  4809.4  412.55
  4839.2  411.27  4879.2  411.76  4889.2  410.88  4899.2  410.73  4919.2  411.58
  4929.2  411.01  4949.2  410.80  4979.2  411.01  4989.2  404.68  4996.5  403.14
  4996.9  402.64  5001.5  402.64  5002.0  403.14  5004.7  405.14  5009.7  405.14
  5019.2  410.79  5029.2  411.77  5049.2  412.96  5099.2  414.93  5129.2  417.08
  5149.2  419.01  5199.2  422.39  5219.2  423.13  5229.2  423.95  5260.4  424.72
#Mann=4,-1,0
  4615.7    0.05       0  4809.4    0.12       0  4996.5    0.07       0
  5002.0    0.12       0
Bank Sta=4996.5,5002
Exp/Cntr=0.3,0.1

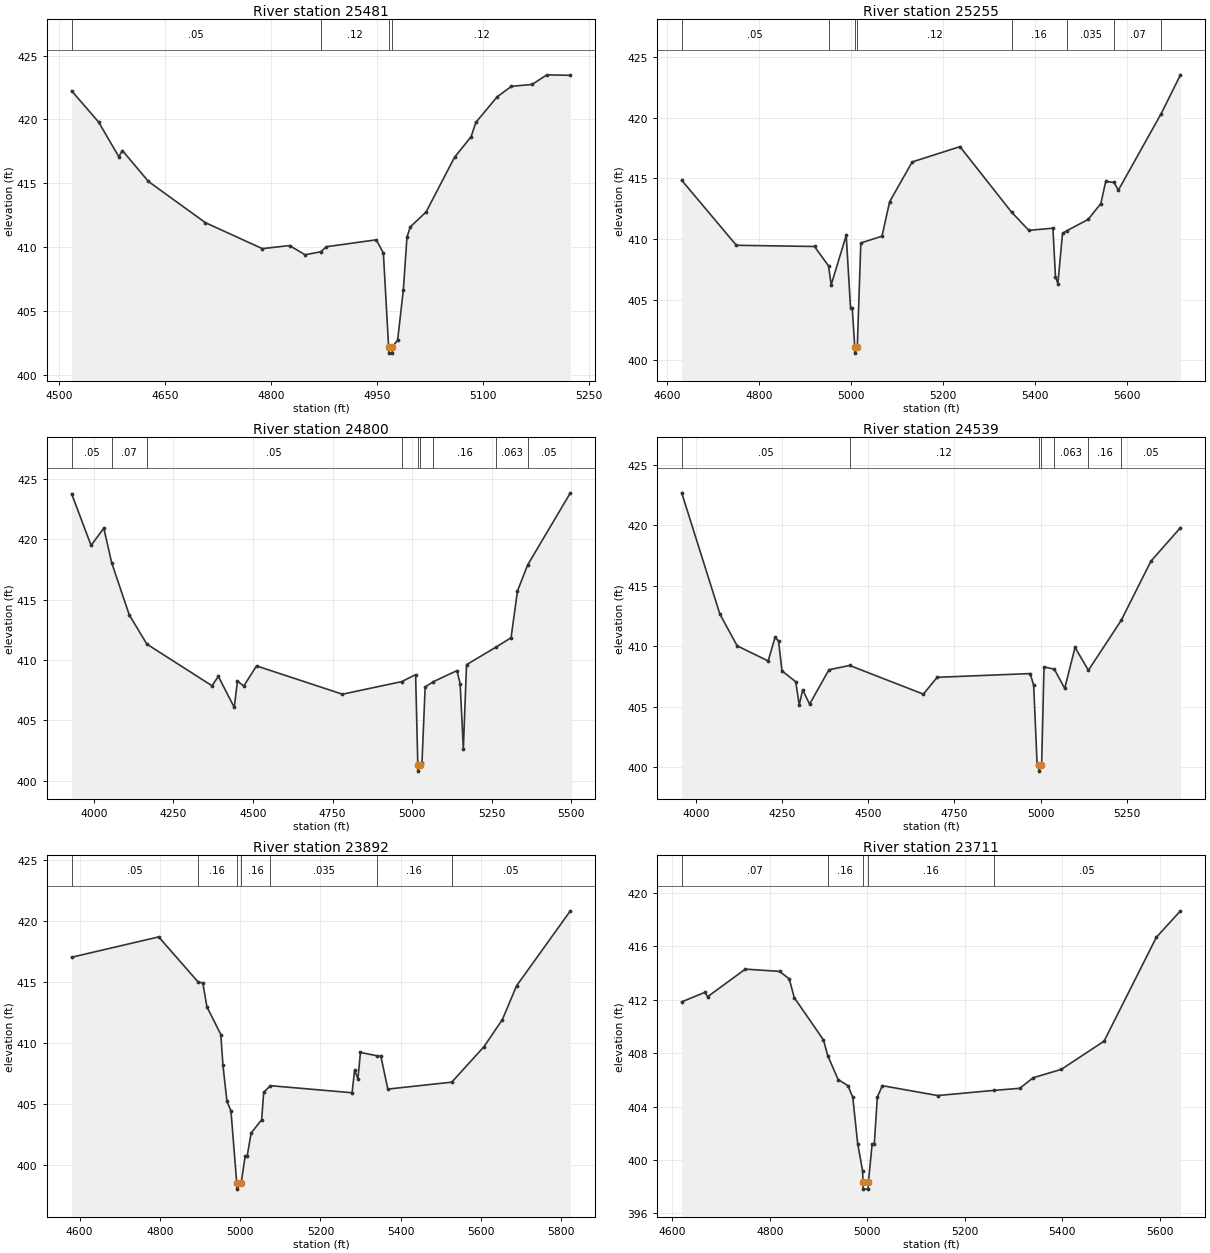
Type RM Length L Ch R = 1,25481,226,226,226
BEGIN DESCRIPTION:
Dry Creek25480.541
END DESCRIPTION:
XS GIS Cut Line= 3
      2735353.93      6840784.73      2734875.46      6840724.82
      2734652.98      6840700.61
#Sta/Elev= 30
  4517.8  422.24  4556.0  419.80  4584.6  417.09  4589.7  417.57  4626.6  415.15
  4707.2  411.93  4787.8  409.90  4826.3  410.14  4848.3  409.42  4870.7  409.66
  4878.5  410.05  4949.1  410.59  4959.1  409.55  4966.5  402.23  4966.9  401.73
  4971.5  401.73  4972.0  402.23  4979.3  402.75  4987.4  406.69  4992.5  410.80
  4997.2  411.60  5019.6  412.77  5059.8  417.04  5083.3  418.65  5090.0  419.77
  5120.2  421.77  5140.3  422.59  5169.7  422.74  5190.6  423.49  5223.8  423.45
#Mann=4,-1,0
  4517.8    0.05       0  4870.7    0.12       0  4966.5    0.07       0
  4972.0    0.12       0
Bank Sta=4966.5,4972
Exp/Cntr=0.3,0.1

Type RM Length L Ch R = 1,25255,455,455,455
BEGIN DESCRIPTION:
Dry Creek25254.88
END DESCRIPTION:
XS GIS Cut Line= 3
      2735264.78      6840661.06      2734926.63      6840515.37
      2734240.33      6840307.12
#Sta/Elev= 30
  4631.6  414.84  4750.5  409.48  4920.6  409.38  4951.1  407.78  4956.9  406.22
  4989.6  410.30  4999.0  404.32  5002.7  404.32  5008.2  401.09  5008.6  400.59
  5013.7  401.09  5021.4  409.67  5067.4  410.23  5084.1  413.07  5133.2  416.35
  5237.1  417.61  5349.7  412.20  5387.1  410.71  5439.4  410.89  5445.0  406.88
  5450.2  406.32  5460.3  410.46  5469.8  410.68  5516.0  411.61  5543.7  412.92
  5554.3  414.74  5572.5  414.66  5581.8  414.02  5675.1  420.34  5717.0  423.53
#Mann=8,-1,0
  4631.6    0.05       0  4951.1    0.12       0  5008.2    0.07       0
  5013.7    0.12       0  5349.7    0.16       0  5469.8   0.035       0
  5572.5    0.07       0  5675.1    0.05       0
Bank Sta=5008.2,5013.7
Exp/Cntr=0.3,0.1

Type RM Length L Ch R = 1,24800,261,261,261
BEGIN DESCRIPTION:
Dry Creek24799.52
END DESCRIPTION:
XS GIS Cut Line= 3
      2735817.16      6840131.20      2734748.38      6840131.90
      2734249.70      6840120.11
#Sta/Elev= 30
  3930.0  423.75  3991.2  419.47  4031.2  420.90  4055.9  418.04  4111.2  413.73
  4166.6  411.31  4371.2  407.87  4391.2  408.64  4441.2  406.08  4451.2  408.25
  4471.2  407.85  4511.2  409.51  4781.2  407.17  4967.4  408.21  5011.2  408.79
  5018.1  401.31  5018.6  400.81  5024.3  401.31  5031.2  401.52  5041.2  407.77
  5066.4  408.20  5141.2  409.12  5151.2  408.03  5161.2  402.65  5171.2  409.61
  5264.3  411.07  5311.2  411.84  5331.3  415.70  5363.2  417.85  5497.6  423.82
#Mann=9,-1,0
  3930.0    0.05       0  4055.9    0.07       0  4166.6    0.05       0
  4967.4    0.12       0  5018.1    0.07       0  5024.3    0.12       0
  5066.4    0.16       0  5264.3   0.063       0  5363.2    0.05       0
Bank Sta=5018.1,5024.3
Exp/Cntr=0.3,0.1

Type RM Length L Ch R = 1,24539,647,647,647
BEGIN DESCRIPTION:
Dry Creek24539.21
END DESCRIPTION:
XS GIS Cut Line= 3
      2735666.84      6839963.99      2734625.00      6839944.54
      2734220.33      6839934.98
#Sta/Elev= 30
  3958.9  422.69  4069.8  412.66  4119.8  410.05  4209.8  408.80  4229.8  410.77
  4239.8  410.44  4249.8  407.98  4289.8  407.08  4299.8  405.16  4309.8  406.43
  4329.8  405.23  4386.0  408.07  4445.9  408.43  4659.9  406.06  4699.9  407.45
  4969.9  407.76  4979.9  406.78  4989.9  400.23  4994.8  400.20  4995.3  399.70
  5001.0  400.20  5002.9  400.20  5009.9  408.31  5039.7  408.12  5069.9  406.54
  5099.9  409.92  5138.6  408.03  5233.9  412.16  5320.0  417.05  5405.7  419.81
#Mann=7,-1,0
  3958.9    0.05       0  4445.9    0.12       0  4994.8    0.07       0
  5001.0    0.12       0  5039.7   0.063       0  5138.6    0.16       0
  5233.9    0.05       0
Bank Sta=4994.8,5001
Exp/Cntr=0.3,0.1

Type RM Length L Ch R = 1,23892,181,181,181
BEGIN DESCRIPTION:
Dry Creek23891.61
END DESCRIPTION:
XS GIS Cut Line= 5
      2734719.78      6838974.04      2734709.55      6839406.73
      2734666.55      6839610.07      2734599.82      6839698.54
      2734154.38      6839906.12
#Sta/Elev= 30
  4580.0  417.05  4797.0  418.72  4894.5  415.05  4907.1  414.92  4917.1  412.99
  4951.8  410.71  4957.1  408.20  4967.1  405.22  4977.1  404.45  4991.5  398.52
  4992.0  398.02  5002.6  398.52  5012.4  400.73  5017.5  400.73  5027.4  402.63
  5053.6  403.71  5058.7  405.97  5075.5  406.51  5278.9  405.93  5285.2  407.77
  5293.5  407.09  5299.8  409.24  5340.1  408.97  5350.7  408.92  5368.0  406.23
  5527.4  406.80  5607.8  409.72  5653.5  411.94  5688.7  414.70  5822.9  420.86
#Mann=7,-1,0
  4580.0    0.05       0  4894.5    0.16       0  4991.5    0.07       0
  5002.6    0.16       0  5075.5   0.035       0  5340.1    0.16       0
  5527.4    0.05       0
Bank Sta=4991.5,5002.6
Exp/Cntr=0.3,0.1

Type RM Length L Ch R = 1,23711,296,296,296
BEGIN DESCRIPTION:
Dry Creek23711.14
END DESCRIPTION:
XS GIS Cut Line= 6
      2734563.89      6838980.72      2734548.87      6839243.61
      2734539.88      6839375.01      2734504.23      6839516.18
      2734393.04      6839620.92      2734112.76      6839794.39
#Sta/Elev= 30
  4619.4  411.83  4667.4  412.55  4672.4  412.21  4749.9  414.28  4820.0  414.11
  4840.0  413.55  4850.2  412.15  4910.2  408.98  4918.9  407.81  4940.2  406.02
  4960.3  405.56  4970.3  404.69  4980.3  401.23  4990.4  399.20  4991.2  398.32
  4991.7  397.82  5001.8  397.82  5002.3  398.32  5009.9  401.18  5014.4  401.18
  5020.6  404.70  5030.9  405.56  5144.4  404.82  5260.2  405.21  5312.8  405.36
  5340.1  406.15  5398.0  406.78  5485.7  408.89  5592.9  416.66  5642.4  418.64
#Mann=5,-1,0
  4619.4    0.07       0  4918.9    0.16       0  4991.2    0.07       0
  5002.3    0.16       0  5260.2    0.05       0
Bank Sta=4991.2,5002.3
Exp/Cntr=0.3,0.1

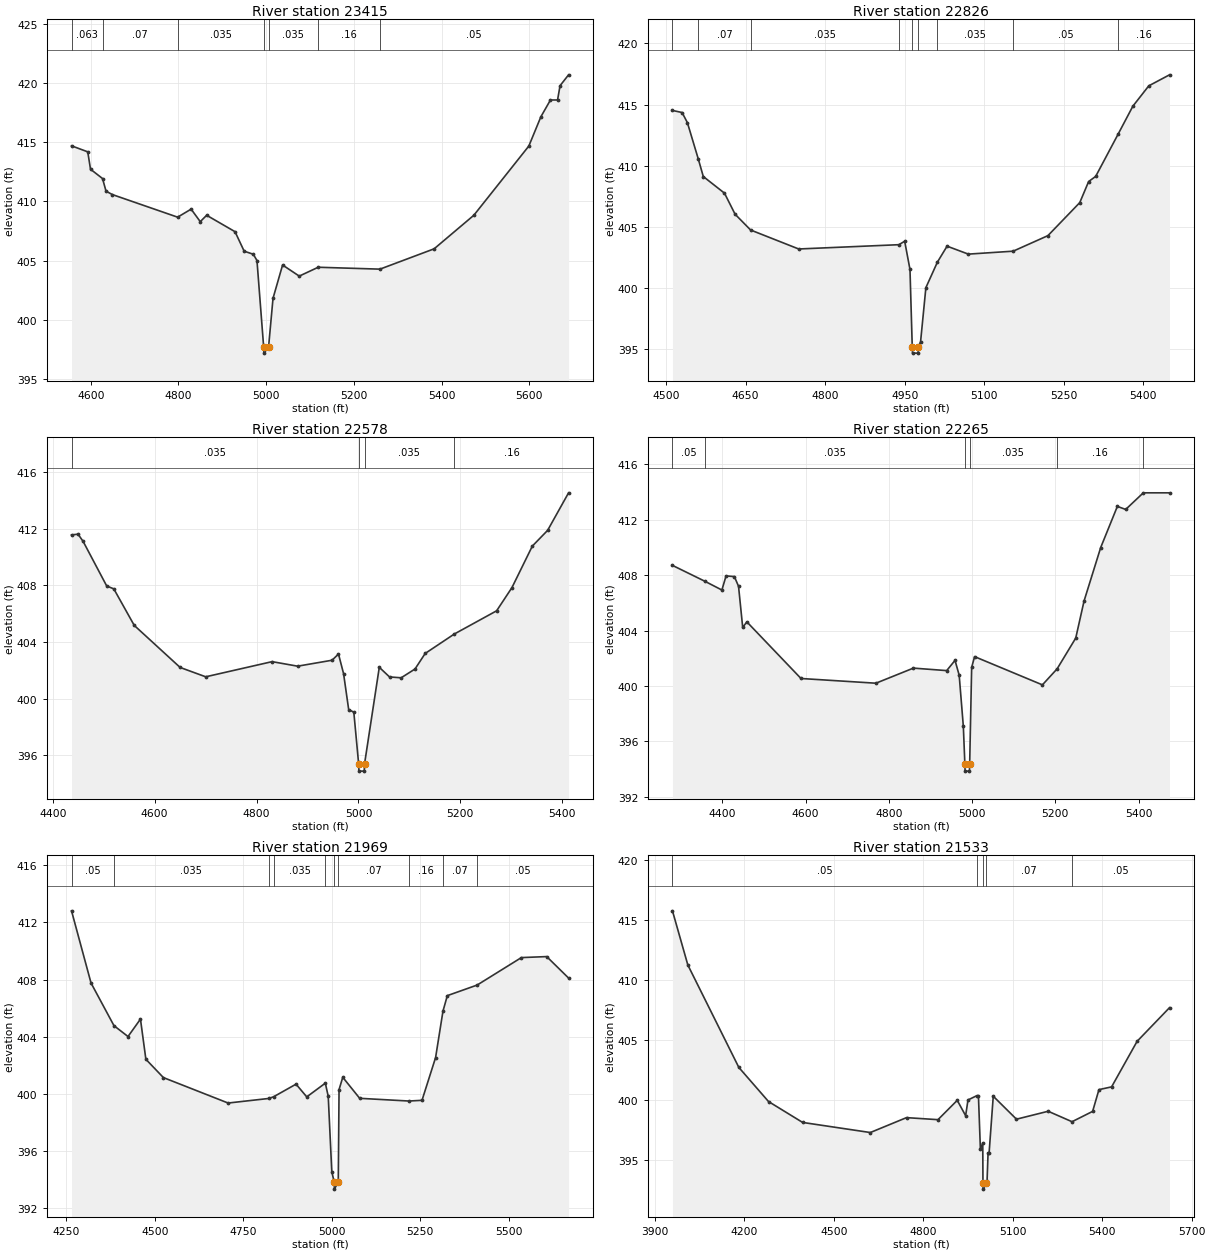
Type RM Length L Ch R = 1,23415,589,589,589
BEGIN DESCRIPTION:
Dry Creek23415.43
END DESCRIPTION:
XS GIS Cut Line= 3
      2734655.15      6838768.99      2734388.85      6839126.40
      2734060.20      6839730.25
#Sta/Elev= 30
  4556.2  414.71  4593.2  414.20  4599.5  412.73  4626.9  411.94  4634.9  410.87
  4649.5  410.58  4798.1  408.67  4828.9  409.35  4849.7  408.29  4864.3  408.83
  4929.0  407.44  4949.8  405.79  4970.7  405.53  4979.0  405.00  4994.3  397.66
  4994.8  397.16  5005.4  397.66  5015.6  401.80  5037.4  404.62  5075.4  403.68
  5118.6  404.43  5259.4  404.27  5382.9  405.99  5473.4  408.83  5598.8  414.69
  5626.3  417.17  5648.1  418.59  5664.3  418.59  5670.0  419.80  5689.4  420.72
#Mann=7,-1,0
  4556.2   0.063       0  4626.9    0.07       0  4798.1   0.035       0
  4994.3   0.035       0  5005.4   0.035       0  5118.6    0.16       0
  5259.4    0.05       0
Bank Sta=4994.3,5005.4
Exp/Cntr=0.3,0.1

Type RM Length L Ch R = 1,22826,248,248,248
BEGIN DESCRIPTION:
Dry Creek22826.07
END DESCRIPTION:
XS GIS Cut Line= 3
      2734664.19      6838706.47      2734173.79      6838710.03
      2733726.95      6838734.12
#Sta/Elev= 30
  4511.9  414.53  4530.1  414.36  4540.1  413.53  4560.4  410.60  4570.1  409.13
  4610.1  407.77  4630.1  406.05  4659.4  404.76  4750.1  403.21  4939.1  403.56
  4950.1  403.84  4960.1  401.54  4964.4  395.20  4964.9  394.70  4975.4  394.70
  4975.9  395.20  4980.1  395.63  4990.1  400.05  5011.9  402.14  5030.1  403.44
  5070.2  402.79  5154.8  403.03  5220.4  404.30  5280.5  407.00  5297.2  408.72
  5310.5  409.14  5353.3  412.63  5380.7  414.88  5410.7  416.54  5449.8  417.44
#Mann=9,-1,0
  4511.9   0.063       0  4560.4    0.07       0  4659.4   0.035       0
  4939.1    0.07       0  4964.4    0.07       0  4975.9    0.07       0
  5011.9   0.035       0  5154.8    0.05       0  5353.3    0.16       0
Bank Sta=4964.4,4975.9
Exp/Cntr=0.3,0.1

Type RM Length L Ch R = 1,22578,313,313,313
BEGIN DESCRIPTION:
Dry Creek22578.19
END DESCRIPTION:
XS GIS Cut Line= 3
      2734638.78      6838461.25      2734070.40      6838499.78
      2733665.00      6838479.38
#Sta/Elev= 30
  4436.8  411.57  4449.6  411.62  4459.6  411.11  4505.9  407.96  4519.8  407.76
  4559.9  405.18  4650.0  402.21  4700.2  401.55  4830.5  402.62  4880.6  402.30
  4948.2  402.72  4960.8  403.16  4970.8  401.77  4980.8  399.24  4990.9  399.05
  5000.4  395.39  5000.9  394.89  5011.4  394.89  5011.9  395.39  5040.9  402.22
  5061.0  401.54  5083.8  401.48  5111.0  402.10  5131.0  403.20  5188.1  404.57
  5271.2  406.21  5301.3  407.85  5341.3  410.78  5371.3  411.89  5412.4  414.54
#Mann=4,-1,0
  4436.8   0.035       0  5000.4   0.035       0  5011.9   0.035       0
  5188.1    0.16       0
Bank Sta=5000.4,5011.9
Exp/Cntr=0.3,0.1

Type RM Length L Ch R = 1,22265,296,296,296
BEGIN DESCRIPTION:
Dry Creek22264.62
END DESCRIPTION:
XS GIS Cut Line= 3
      2734804.79      6838198.91      2734077.10      6838216.36
      2733610.72      6838226.98
#Sta/Elev= 30
  4279.9  408.71  4358.0  407.56  4398.7  406.93  4408.7  407.95  4428.7  407.90
  4438.7  407.20  4448.7  404.23  4458.7  404.63  4588.8  400.54  4768.8  400.20
  4858.9  401.29  4938.9  401.11  4958.9  401.85  4968.9  400.78  4978.9  397.08
  4982.6  394.35  4983.1  393.85  4993.6  393.85  4994.1  394.35  4998.9  401.34
  5005.9  402.12  5168.9  400.08  5204.3  401.24  5249.0  403.46  5269.0  406.14
  5309.0  410.00  5349.0  412.97  5369.0  412.75  5411.4  413.95  5474.3  413.95
#Mann=6,-1,0
  4279.9    0.05       0  4358.0   0.035       0  4982.6   0.035       0
  4994.1   0.035       0  5204.3    0.16       0  5411.4    0.05       0
Bank Sta=4982.6,4994.1
Exp/Cntr=0.3,0.1

Type RM Length L Ch R = 1,21969,436,436,436
BEGIN DESCRIPTION:
Dry Creek21968.73
END DESCRIPTION:
XS GIS Cut Line= 3
      2734853.97      6837827.74      2734116.78      6837935.88
      2733484.27      6838124.42
#Sta/Elev= 30
  4264.5  412.81  4319.7  407.76  4384.5  404.78  4424.2  404.02  4459.4  405.24
  4474.7  402.43  4524.2  401.15  4707.2  399.37  4822.4  399.69  4835.9  399.81
  4899.2  400.69  4929.5  399.80  4982.0  400.76  4990.2  399.84  5000.3  394.56
  5007.1  393.85  5007.6  393.35  5018.6  393.85  5020.8  400.31  5031.3  401.17
  5079.1  399.70  5218.3  399.51  5255.3  399.56  5293.7  402.55  5314.6  405.80
  5326.9  406.88  5411.2  407.62  5536.2  409.54  5607.8  409.61  5669.6  408.11
#Mann=10,-1,0
  4264.5    0.05       0  4384.5   0.035       0  4822.4    0.05       0
  4835.9   0.035       0  4982.0    0.07       0  5007.1    0.07       0
  5018.6    0.07       0  5218.3    0.16       0  5314.6    0.07       0
  5411.2    0.05       0
Bank Sta=5007.1,5018.6
Exp/Cntr=0.3,0.1

Type RM Length L Ch R = 1,21533,346,346,346
BEGIN DESCRIPTION:
Dry Creek21532.55
END DESCRIPTION:
XS GIS Cut Line= 3
      2734540.00      6836811.59      2733870.53      6837631.33
      2733470.68      6838089.12
#Sta/Elev= 30
  3959.5  415.75  4011.1  411.24  4182.0  402.72  4281.5  399.88  4395.9  398.14
  4622.8  397.30  4744.1  398.54  4849.6  398.37  4914.2  399.98  4942.3  398.70
  4950.2  400.01  4979.2  400.36  4985.3  400.31  4991.8  395.90  4999.7  396.44
  5000.4  393.09  5000.9  392.59  5012.0  393.09  5014.1  393.23  5017.5  395.61
  5021.0  395.61  5034.9  400.32  5112.7  398.41  5219.0  399.07  5299.0  398.20
  5368.0  399.06  5389.2  400.87  5431.6  401.10  5517.1  404.89  5625.7  407.69
#Mann=5,-1,0
  3959.5    0.05       0  4979.2    0.07       0  5000.4    0.07       0
  5012.0    0.07       0  5299.0    0.05       0
Bank Sta=5000.4,5012
Exp/Cntr=0.3,0.1

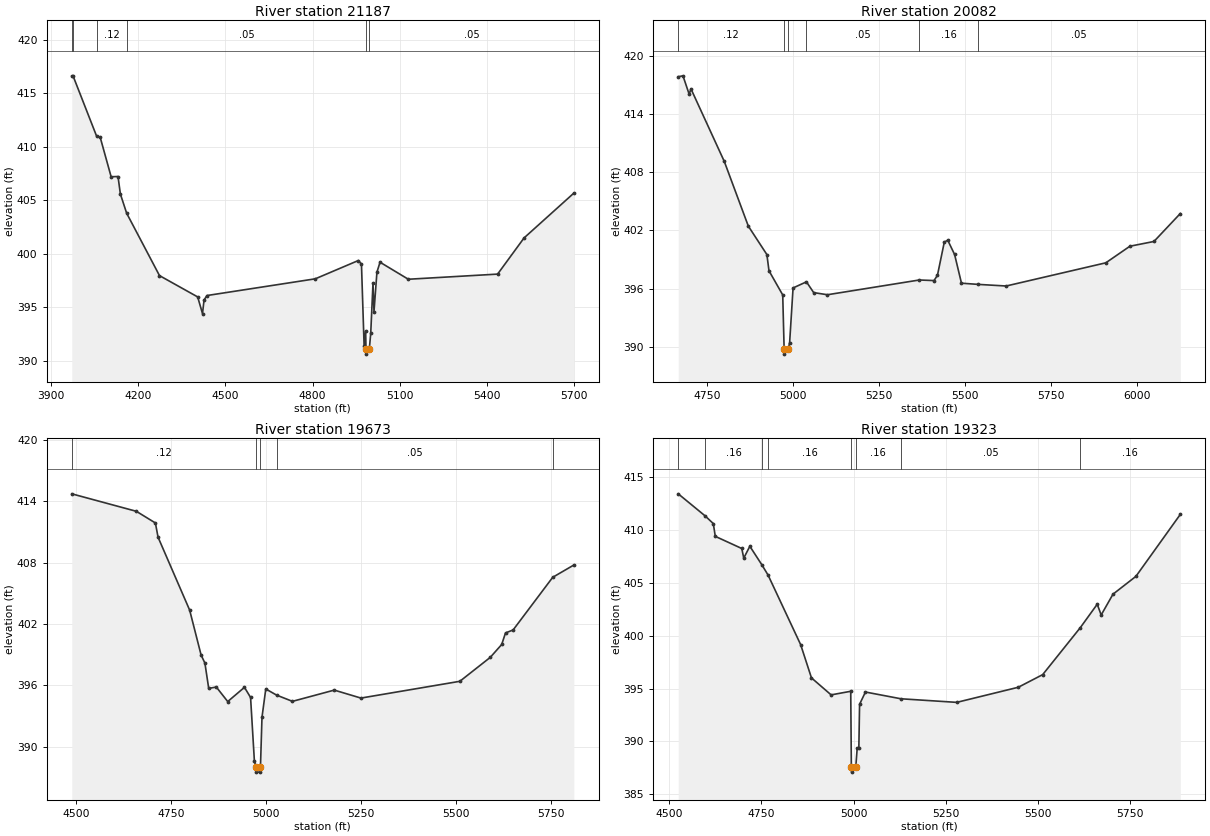
Type RM Length L Ch R = 1,21187,1105,1105,1105
BEGIN DESCRIPTION:
Dry Creek21187.01
END DESCRIPTION:
XS GIS Cut Line= 3
      2733994.09      6836443.61      2733640.39      6837422.41
      2733401.19      6838066.06
#Sta/Elev= 30
  3971.2  416.58  3975.5  416.62  4056.9  410.97  4069.0  410.88  4106.6  407.20
  4130.3  407.22  4138.5  405.58  4160.1  403.79  4273.0  397.97  4404.4  395.98
  4421.0  394.42  4426.3  395.69  4436.3  396.11  4809.0  397.67  4957.3  399.38
  4967.9  399.04  4977.0  391.44  4982.3  392.80  4983.4  391.14  4983.9  390.64
  4995.0  391.14  4999.8  392.58  5007.6  397.29  5011.0  394.61  5021.1  398.29
  5031.8  399.22  5129.1  397.63  5436.3  398.11  5527.4  401.49  5698.6  405.67
#Mann=6,-1,0
  3971.2    0.05       0  3975.5    0.16       0  4056.9    0.12       0
  4160.1    0.05       0  4983.4    0.05       0  4995.0    0.05       0
Bank Sta=4983.4,4995
Exp/Cntr=0.3,0.1

Type RM Length L Ch R = 1,20082,409,409,409
BEGIN DESCRIPTION:
Dry Creek20082.27
END DESCRIPTION:
XS GIS Cut Line= 3
      2733312.57      6836527.17      2733297.16      6836868.80
      2733270.76      6837987.71
#Sta/Elev= 30
  4666.0  417.84  4679.8  417.93  4697.9  416.02  4702.9  416.60  4800.0  409.11
  4870.0  402.44  4924.0  399.51  4930.1  397.84  4970.1  395.35  4974.2  389.75
  4974.7  389.25  4986.2  389.75  4990.2  390.44  5000.2  396.07  5039.1  396.70
  5060.2  395.59  5100.2  395.37  5367.6  396.89  5410.3  396.83  5420.3  397.36
  5440.3  400.79  5450.3  400.99  5470.3  399.52  5490.3  396.56  5537.5  396.44
  5620.4  396.27  5910.4  398.66  5980.5  400.37  6050.5  400.86  6127.2  403.74
#Mann=6,-1,0
  4666.0    0.12       0  4974.2    0.07       0  4986.2    0.12       0
  5039.1    0.05       0  5367.6    0.16       0  5537.5    0.05       0
Bank Sta=4974.2,4986.2
Exp/Cntr=0.3,0.1

Type RM Length L Ch R = 1,19673,350,350,350
BEGIN DESCRIPTION:
Dry Creek19673.34
END DESCRIPTION:
XS GIS Cut Line= 3
      2733051.21      6836551.28      2733027.85      6837074.59
      2733001.72      6837870.63
#Sta/Elev= 30
  4489.6  414.74  4659.5  413.03  4709.5  411.89  4716.5  410.50  4799.6  403.37
  4829.7  398.98  4839.7  398.19  4849.7  395.72  4869.7  395.85  4899.7  394.43
  4943.7  395.82  4959.8  394.83  4969.8  388.64  4973.8  388.03  4974.3  387.53
  4985.3  387.53  4985.8  388.03  4989.8  392.89  4999.8  395.66  5028.2  395.06
  5069.9  394.45  5179.9  395.55  5250.0  394.77  5510.1  396.41  5590.1  398.75
  5620.2  400.01  5630.2  401.14  5650.2  401.43  5754.4  406.58  5809.9  407.78
#Mann=5,-1,0
  4489.6    0.12       0  4973.8    0.07       0  4985.8    0.12       0
  5028.2    0.05       0  5754.4    0.07       0
Bank Sta=4973.8,4985.8
Exp/Cntr=0.3,0.1

Type RM Length L Ch R = 1,19323,275,275,275
BEGIN DESCRIPTION:
Dry Creek19323.22
END DESCRIPTION:
XS GIS Cut Line= 3
      2732968.73      6836471.53      2732781.75      6836924.28
      2732480.67      6837742.40
#Sta/Elev= 30
  4524.4  413.45  4597.3  411.36  4619.5  410.63  4624.9  409.42  4696.7  408.27
  4702.1  407.36  4718.6  408.48  4750.7  406.75  4767.9  405.76  4856.4  399.16
  4885.7  396.01  4939.0  394.40  4992.2  394.74  4993.9  387.58  4994.4  387.08
  5005.9  387.58  5009.8  389.38  5014.2  389.38  5016.2  393.51  5032.1  394.67
  5128.4  394.03  5279.7  393.69  5446.5  395.12  5512.8  396.32  5615.0  400.78
  5660.7  402.99  5671.4  401.97  5703.4  403.94  5765.6  405.63  5886.0  411.50
#Mann=8,-1,0
  4524.4    0.12       0  4597.3    0.16       0  4750.7    0.05       0
  4767.9    0.16       0  4993.9    0.07       0  5005.9    0.16       0
  5128.4    0.05       0  5615.0    0.16       0
Bank Sta=4993.9,5005.9
Exp/Cntr=0.3,0.1