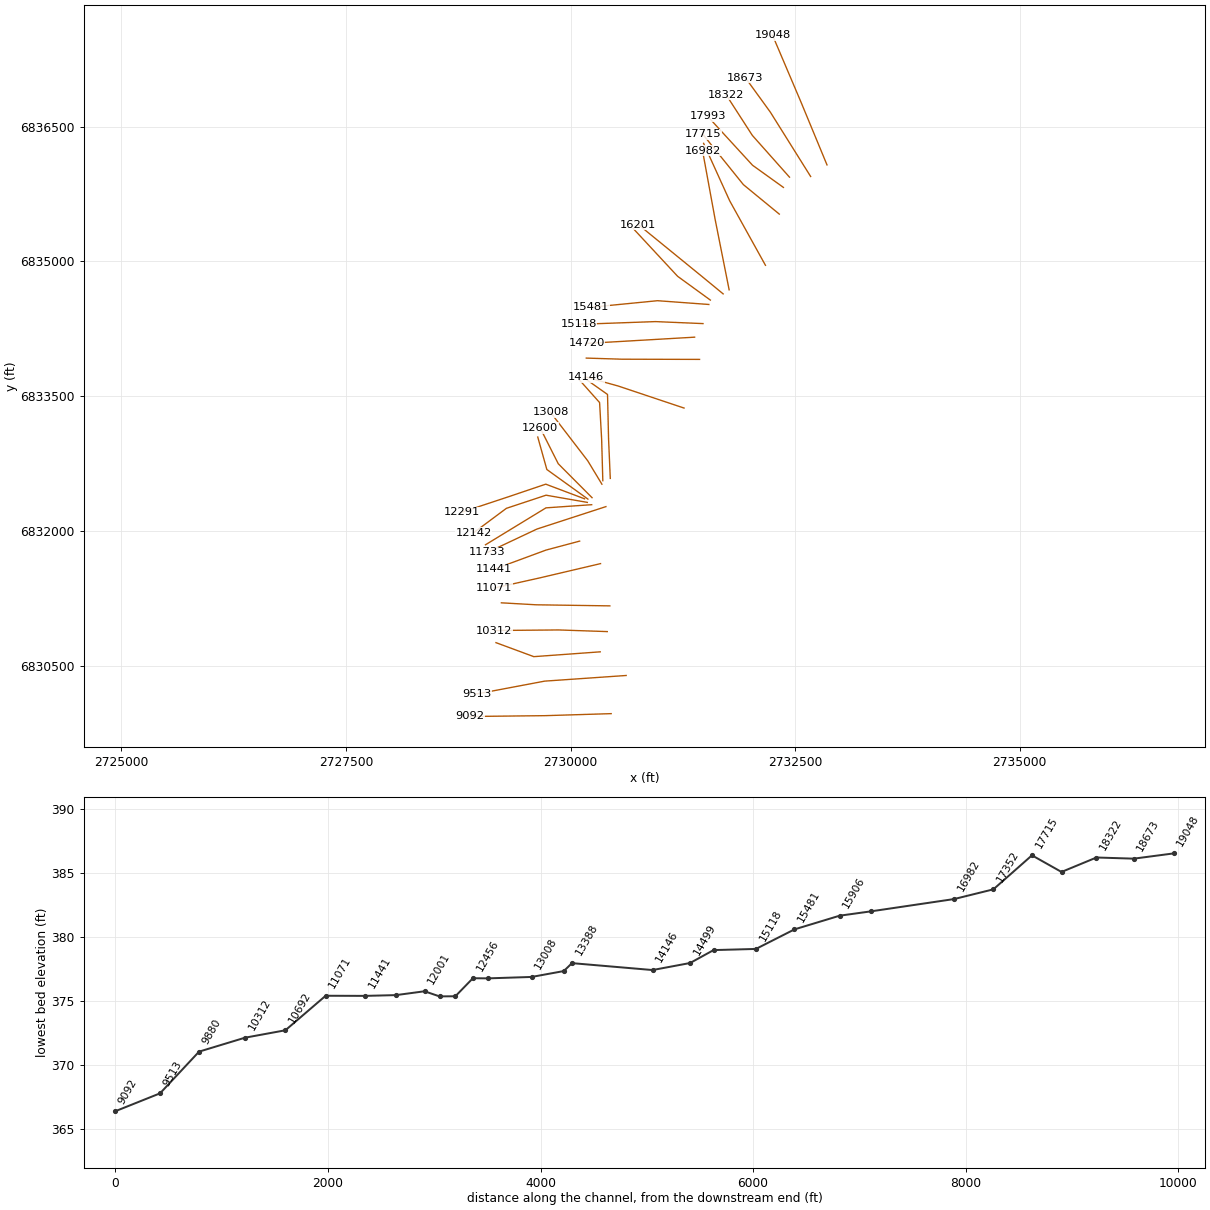
HEC-RAS study Dry Creek.prj: Dry Creek Base Level Engineering

--- Dry Creek.g01 (geometry) --- (continued)

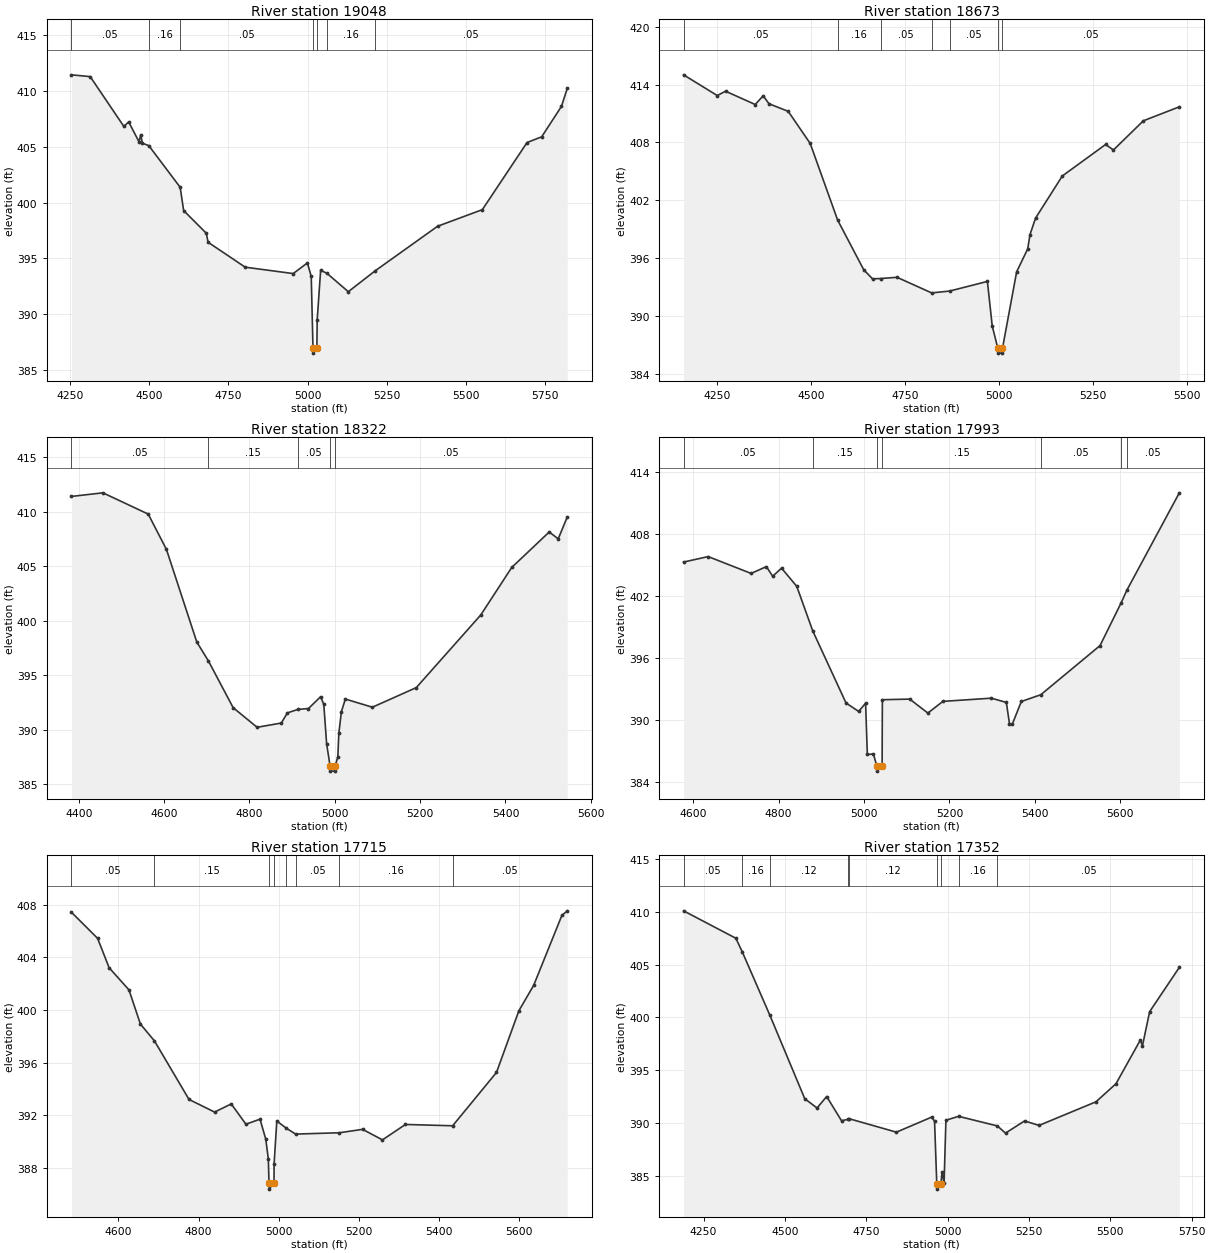
Type RM Length L Ch R = 1,19048,375,375,375
BEGIN DESCRIPTION:
Dry Creek19047.64
END DESCRIPTION:
XS GIS Cut Line= 3
      2732854.71      6836073.94      2732564.92      6836773.70
      2732248.37      6837517.77
#Sta/Elev= 30
  4254.2  411.41  4313.4  411.25  4419.7  406.80  4435.0  407.20  4467.5  405.43
  4472.9  406.04  4478.4  405.30  4498.6  405.08  4597.6  401.36  4608.6  399.28
  4680.3  397.25  4685.7  396.45  4803.0  394.22  4954.6  393.65  4999.5  394.60
  5011.6  393.39  5017.1  387.04  5017.6  386.54  5029.4  387.04  5030.4  389.51
  5041.3  393.94  5060.9  393.68  5128.7  392.03  5213.3  393.89  5410.8  397.88
  5552.0  399.36  5693.3  405.36  5739.5  405.87  5802.0  408.59  5820.2  410.19
#Mann=7,-1,0
  4254.2    0.05       0  4498.6    0.16       0  4597.6    0.05       0
  5017.1    0.05       0  5029.4    0.05       0  5060.9    0.16       0
  5213.3    0.05       0
Bank Sta=5017.1,5029.4
Exp/Cntr=0.3,0.1

Type RM Length L Ch R = 1,18673,351,351,351
BEGIN DESCRIPTION:
Dry Creek18672.85
END DESCRIPTION:
XS GIS Cut Line= 3
      2732672.60      6835944.99      2732223.75      6836661.75
      2731945.85      6837044.86
#Sta/Elev= 30
  4160.1  415.01  4249.8  412.86  4271.8  413.31  4350.8  411.93  4372.0  412.84
  4387.3  412.01  4438.6  411.22  4497.0  407.89  4570.0  399.94  4639.6  394.77
  4662.8  393.84  4684.3  393.87  4728.0  394.00  4820.1  392.38  4867.7  392.57
  4968.5  393.57  4981.3  388.95  4996.2  386.63  4996.7  386.13  5008.1  386.13
  5008.6  386.63  5046.3  394.57  5075.7  396.95  5081.9  398.44  5096.6  400.14
  5167.7  404.51  5282.9  407.78  5303.8  407.21  5383.4  410.24  5479.1  411.69
#Mann=7,-1,0
  4160.1    0.05       0  4570.0    0.16       0  4684.3    0.05       0
  4820.1    0.16       0  4867.7    0.05       0  4996.2    0.05       0
  5008.6    0.05       0
Bank Sta=4996.2,5008.6
Exp/Cntr=0.3,0.1

Type RM Length L Ch R = 1,18322,329,329,329
BEGIN DESCRIPTION:
Dry Creek18322.22
END DESCRIPTION:
XS GIS Cut Line= 3
      2732437.13      6835937.67      2732023.57      6836402.46
      2731730.99      6836855.92
#Sta/Elev= 30
  4382.9  411.41  4456.6  411.74  4562.8  409.79  4605.5  406.55  4676.6  398.06
  4703.9  396.32  4761.8  392.04  4817.9  390.24  4874.7  390.63  4888.9  391.56
  4913.7  391.88  4938.3  391.96  4966.7  393.04  4974.2  392.35  4980.9  388.72
  4988.9  386.72  4989.4  386.22  5000.8  386.22  5001.3  386.72  5007.1  387.55
  5009.5  389.70  5015.5  391.67  5024.7  392.83  5088.1  392.08  5191.0  393.88
  5342.1  400.54  5414.7  404.90  5502.5  408.15  5523.6  407.52  5544.7  409.52
#Mann=5,-1,0
  4382.9    0.05       0  4703.9    0.15       0  4913.7    0.05       0
  4988.9    0.05       0  5001.3    0.05       0
Bank Sta=4988.9,5001.3
Exp/Cntr=0.3,0.1

Type RM Length L Ch R = 1,17993,278,278,278
BEGIN DESCRIPTION:
Dry Creek17834.55
END DESCRIPTION:
XS GIS Cut Line= 3
      2732369.48      6835823.57      2732026.04      6836069.98
      2731526.64      6836614.16
#Sta/Elev= 30
  4577.3  405.32  4635.0  405.85  4735.6  404.22  4771.3  404.88  4786.0  403.95
  4806.9  404.73  4842.5  402.97  4879.7  398.68  4957.9  391.68  4987.4  390.87
  5003.7  391.66  5007.8  386.70  5022.0  386.75  5029.9  385.59  5030.4  385.09
  5042.4  385.59  5043.0  392.00  5107.1  392.06  5149.6  390.71  5184.8  391.84
  5298.2  392.15  5333.4  391.74  5340.7  389.69  5347.6  389.66  5368.5  391.83
  5414.0  392.48  5552.9  397.24  5602.5  401.39  5616.0  402.62  5738.6  412.02
#Mann=7,-1,0
  4577.3    0.05       0  4879.7    0.15       0  5029.9    0.07       0
  5042.4    0.15       0  5414.0    0.05       0  5602.5    0.12       0
  5616.0    0.05       0
Bank Sta=5029.9,5042.4
Exp/Cntr=0.3,0.1

Type RM Length L Ch R = 1,17715,363,363,363
BEGIN DESCRIPTION:
Dry Creek17535.81
END DESCRIPTION:
XS GIS Cut Line= 3
      2732323.58      6835526.36      2731923.74      6835854.58
      2731471.80      6836415.45
#Sta/Elev= 30
  4482.7  407.41  4548.0  405.43  4576.7  403.20  4626.2  401.52  4654.9  398.92
  4690.0  397.64  4776.1  393.20  4840.0  392.24  4881.6  392.86  4918.2  391.32
  4953.4  391.70  4967.7  390.19  4974.2  388.68  4975.8  386.89  4976.3  386.39
  4988.3  386.89  4988.5  388.28  4995.3  391.56  5018.9  391.02  5042.2  390.57
  5151.7  390.67  5209.4  390.93  5259.0  390.13  5316.5  391.30  5434.3  391.20
  5543.7  395.25  5599.7  399.94  5636.5  401.86  5706.9  407.17  5720.3  407.52
#Mann=8,-1,0
  4482.7    0.05       0  4690.0    0.15       0  4975.8    0.07       0
  4988.3    0.15       0  5018.9    0.12       0  5042.2    0.05       0
  5151.7    0.16       0  5434.3    0.05       0
Bank Sta=4975.8,4988.3
Exp/Cntr=0.3,0.1

Type RM Length L Ch R = 1,17352,370,370,370
BEGIN DESCRIPTION:
Mapping XS a29c9135
END DESCRIPTION:
XS GIS Cut Line= 3
      2732169.55      6834956.39      2731771.34      6835674.39
      2731480.90      6836314.11
#Sta/Elev= 30
  4188.6  410.11  4349.4  407.51  4369.6  406.18  4453.9  400.21  4561.1  392.30
  4598.9  391.42  4628.4  392.51  4674.1  390.21  4694.2  390.35  4696.8  390.41
  4842.7  389.13  4951.4  390.56  4960.0  390.16  4966.8  384.23  4967.3  383.73
  4979.4  384.23  4982.9  385.37  4989.2  384.31  4994.9  390.26  5033.9  390.63
  5153.0  389.72  5178.0  389.04  5236.5  390.19  5281.2  389.77  5456.2  392.01
  5517.5  393.72  5592.2  397.85  5599.0  397.33  5620.9  400.55  5712.2  404.75
#Mann=9,-1,0
  4188.6    0.05       0  4369.6    0.16       0  4453.9    0.12       0
  4694.2    0.15       0  4696.8    0.12       0  4966.8    0.07       0
  4979.4    0.12       0  5033.9    0.16       0  5153.0    0.05       0
Bank Sta=4966.8,4979.4
Exp/Cntr=0.3,0.1

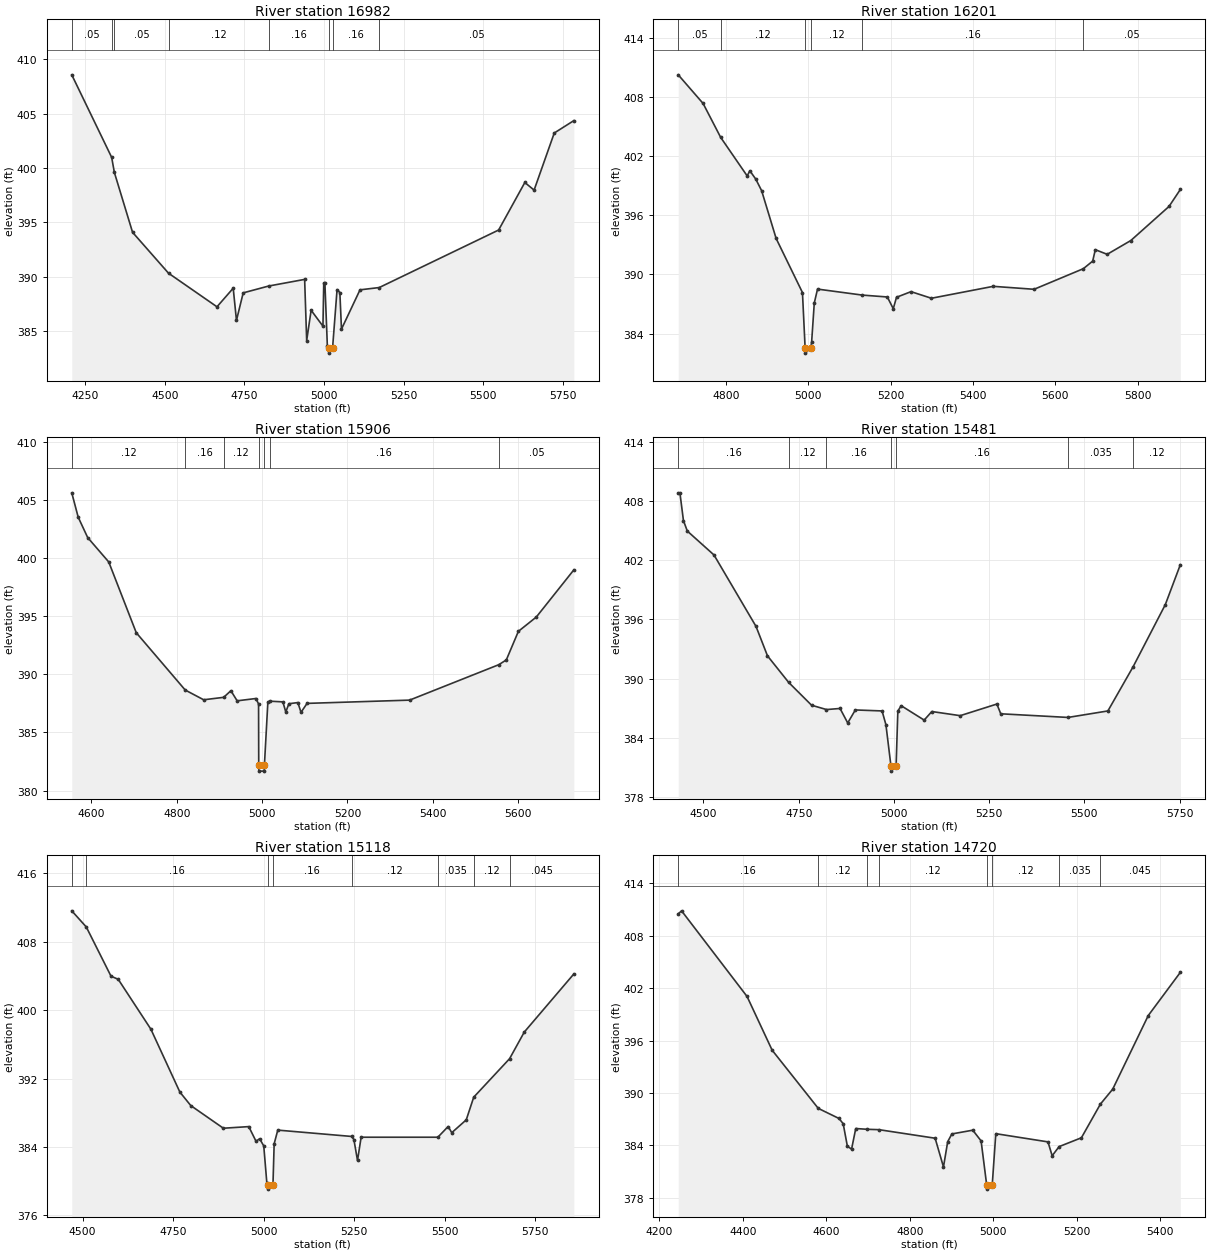
Type RM Length L Ch R = 1,16982,781,781,781
BEGIN DESCRIPTION:
Dry Creek17111.81
END DESCRIPTION:
XS GIS Cut Line= 3
      2731765.16      6834683.78      2731610.61      6835460.86
      2731469.17      6836232.41
#Sta/Elev= 30
  4207.7  408.56  4333.0  400.97  4341.5  399.58  4398.6  394.08  4511.5  390.32
  4663.7  387.23  4714.7  388.94  4724.9  385.98  4746.0  388.51  4826.1  389.14
  4939.0  389.75  4945.4  384.13  4959.4  386.91  4996.5  385.45  4999.0  389.41
  5002.6  389.41  5010.3  383.65  5014.1  383.47  5014.6  382.97  5026.8  383.47
  5040.8  388.81  5049.6  388.54  5054.7  385.18  5112.9  388.79  5173.2  389.00
  5548.2  394.29  5630.5  398.66  5659.6  397.96  5722.9  403.21  5784.4  404.35
#Mann=8,-1,0
  4207.7    0.05       0  4333.0    0.16       0  4341.5    0.05       0
  4511.5    0.12       0  4826.1    0.16       0  5014.1    0.07       0
  5026.8    0.16       0  5173.2    0.05       0
Bank Sta=5014.1,5026.8
Exp/Cntr=0.3,0.1

Type RM Length L Ch R = 1,16201,295,295,295
BEGIN DESCRIPTION:
Dry Creek16201.08
END DESCRIPTION:
XS GIS Cut Line= 3
      2731698.51      6834638.36      2731452.80      6834840.38
      2730754.75      6835409.27
#Sta/Elev= 30
  4684.7  410.26  4745.1  407.35  4787.7  403.91  4852.0  400.00  4858.5  400.52
  4872.8  399.68  4887.1  398.50  4922.3  393.65  4986.2  388.16  4992.7  382.51
  4993.2  382.01  5006.0  382.51  5008.4  383.09  5014.9  387.10  5022.8  388.51
  5131.7  387.90  5192.2  387.71  5206.6  386.52  5214.5  387.68  5249.7  388.25
  5299.2  387.58  5449.3  388.79  5548.4  388.49  5667.9  390.58  5690.6  391.35
  5697.0  392.51  5725.8  392.04  5783.2  393.44  5875.9  396.90  5903.3  398.62
#Mann=6,-1,0
  4684.7    0.05       0  4787.7    0.12       0  4992.7    0.07       0
  5006.0    0.12       0  5131.7    0.16       0  5667.9    0.05       0
Bank Sta=4992.7,5006
Exp/Cntr=0.3,0.1

Type RM Length L Ch R = 1,15906,425,425,425
BEGIN DESCRIPTION:
Dry Creek15905.56
END DESCRIPTION:
XS GIS Cut Line= 3
      2731556.14      6834569.20      2731191.40      6834834.23
      2730697.13      6835366.18
#Sta/Elev= 30
  4553.9  405.62  4569.0  403.52  4591.2  401.77  4640.6  399.67  4705.1  393.58
  4819.8  388.65  4863.1  387.81  4910.0  388.02  4926.9  388.59  4941.6  387.72
  4985.6  387.92  4991.8  387.45  4992.2  382.17  4992.7  381.67  5005.0  381.67
  5005.5  382.17  5013.6  387.61  5017.9  387.69  5048.8  387.63  5055.6  386.76
  5062.9  387.47  5083.9  387.57  5091.3  386.73  5105.5  387.50  5345.8  387.78
  5555.0  390.83  5572.6  391.24  5600.9  393.70  5642.9  394.93  5730.9  398.99
#Mann=7,-1,0
  4553.9    0.12       0  4819.8    0.16       0  4910.0    0.12       0
  4992.2    0.07       0  5005.5    0.12       0  5017.9    0.16       0
  5555.0    0.05       0
Bank Sta=4992.2,5005.5
Exp/Cntr=0.3,0.1

Type RM Length L Ch R = 1,15481,363,363,363
BEGIN DESCRIPTION:
Dry Creek15480.872
END DESCRIPTION:
XS GIS Cut Line= 3
      2731539.69      6834520.31      2730968.58      6834562.29
      2730226.80      6834489.44
#Sta/Elev= 30
  4433.8  408.85  4438.2  408.85  4447.5  406.03  4457.6  404.97  4527.7  402.54
  4638.0  395.29  4668.1  392.30  4723.6  389.61  4783.8  387.29  4823.0  386.85
  4858.6  386.96  4878.7  385.49  4898.7  386.81  4968.9  386.71  4979.0  385.31
  4992.3  381.10  4992.8  380.60  5005.7  381.10  5010.3  386.70  5019.1  387.24
  5079.4  385.78  5099.5  386.65  5174.0  386.23  5270.3  387.41  5280.4  386.42
  5457.0  386.05  5561.7  386.71  5628.1  391.21  5712.4  397.50  5751.8  401.55
#Mann=7,-1,0
  4433.8    0.16       0  4723.6    0.12       0  4823.0    0.16       0
  4992.3    0.07       0  5005.7    0.16       0  5457.0   0.035       0
  5628.1    0.12       0
Bank Sta=4992.3,5005.7
Exp/Cntr=0.3,0.1

Type RM Length L Ch R = 1,15118,398,398,398
BEGIN DESCRIPTION:
Dry Creek15117.58
END DESCRIPTION:
XS GIS Cut Line= 3
      2731474.18      6834307.49      2730944.66      6834329.67
      2730089.18      6834299.19
#Sta/Elev= 30
  4470.1  411.61  4510.2  409.72  4578.4  403.97  4598.4  403.60  4688.5  397.77
  4768.5  390.42  4798.6  388.84  4888.6  386.19  4958.7  386.38  4978.7  384.67
  4988.7  384.96  5000.1  384.12  5008.7  379.74  5012.1  379.57  5012.6  379.07
  5025.5  379.57  5028.8  384.37  5038.8  385.97  5242.4  385.23  5248.9  384.87
  5258.9  382.42  5268.9  385.14  5480.7  385.14  5509.1  386.39  5519.1  385.67
  5559.1  387.17  5579.7  389.82  5678.7  394.32  5719.2  397.43  5856.1  404.23
#Mann=8,-1,0
  4470.1    0.05       0  4510.2    0.16       0  5012.1    0.07       0
  5025.5    0.16       0  5242.4    0.12       0  5480.7   0.035       0
  5579.7    0.12       0  5678.7   0.045       0
Bank Sta=5012.1,5025.5
Exp/Cntr=0.3,0.1

Type RM Length L Ch R = 1,14720,221,221,221
BEGIN DESCRIPTION:
Dry Creek14719.757
END DESCRIPTION:
XS GIS Cut Line= 3
      2731380.77      6834156.36      2730620.61      6834112.23
      2730179.29      6834086.61
#Sta/Elev= 30
  4245.0  410.50  4253.0  410.85  4410.0  401.04  4470.1  394.89  4580.6  388.23
  4630.4  387.07  4640.4  386.47  4650.4  383.90  4660.5  383.56  4670.5  385.92
  4698.6  385.83  4725.9  385.79  4860.8  384.81  4880.8  381.52  4890.9  384.41
  4900.9  385.30  4951.0  385.73  4971.0  384.50  4984.3  379.48  4984.8  378.98
  4997.7  379.48  5006.2  385.33  5131.3  384.39  5141.3  382.80  5158.0  383.85
  5211.4  384.86  5257.0  388.72  5286.5  390.43  5371.7  398.86  5448.5  403.80
#Mann=8,-1,0
  4245.0    0.16       0  4580.6    0.12       0  4698.6    0.16       0
  4725.9    0.12       0  4984.3    0.07       0  4997.7    0.12       0
  5158.0   0.035       0  5257.0   0.045       0
Bank Sta=4984.3,4997.7
Exp/Cntr=0.3,0.1

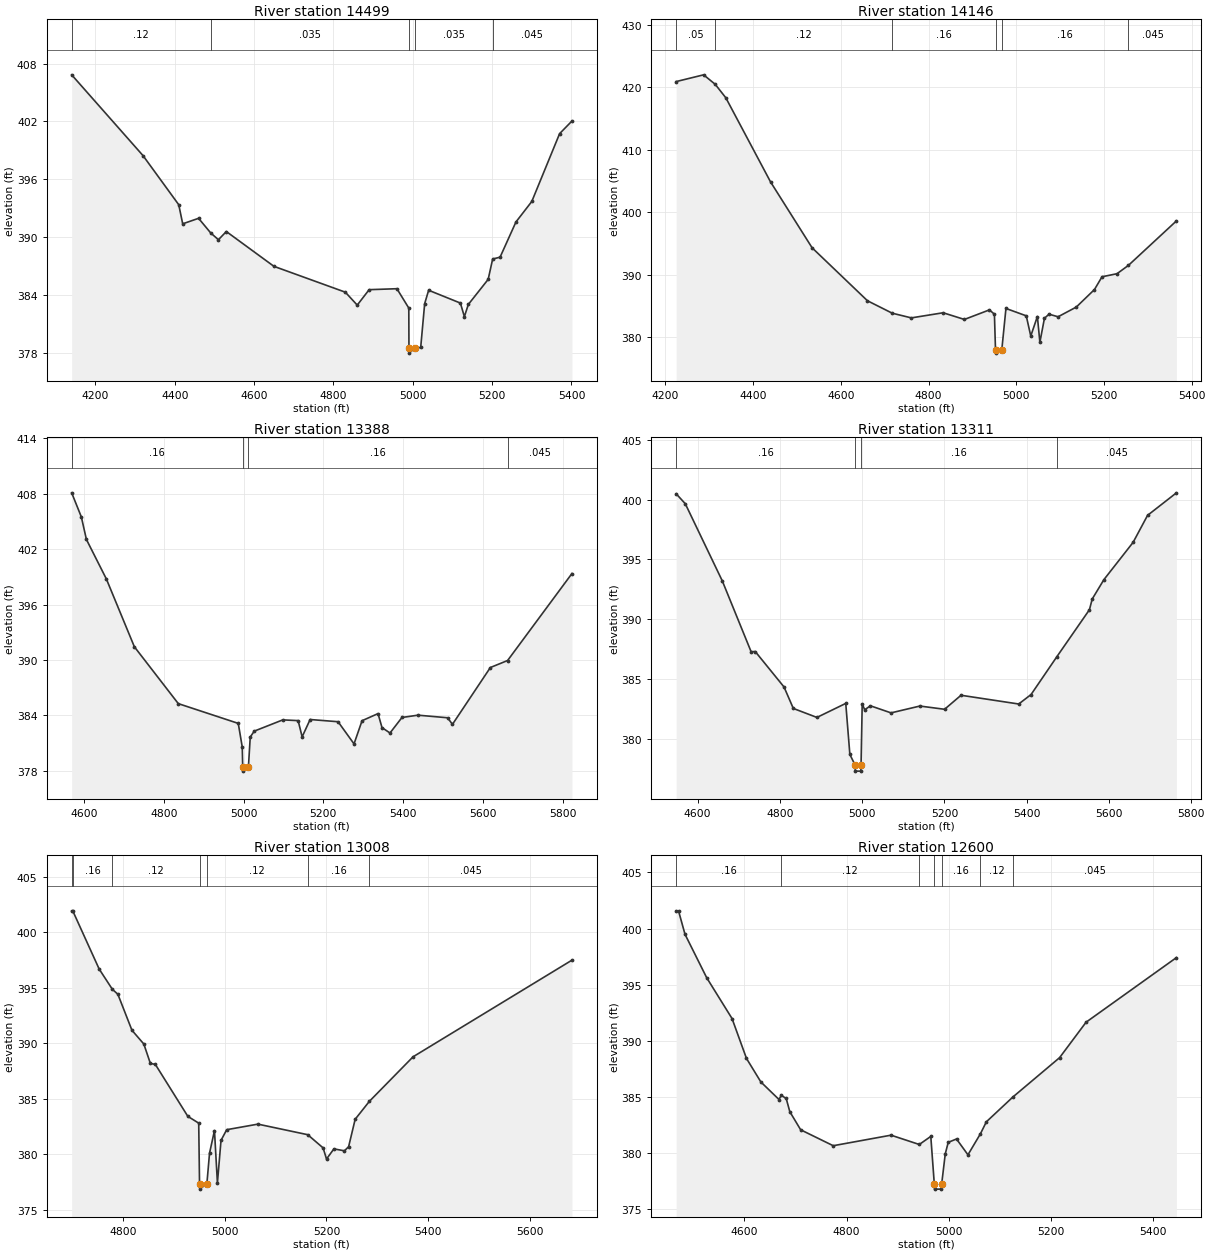
Type RM Length L Ch R = 1,14499,353,353,353
BEGIN DESCRIPTION:
Dry Creek14499.135
END DESCRIPTION:
XS GIS Cut Line= 3
      2731435.90      6833908.92      2730576.00      6833911.00
      2730174.89      6833923.43
#Sta/Elev= 30
  4140.0  406.83  4319.9  398.45  4409.9  393.36  4419.9  391.38  4459.9  391.95
  4490.4  390.44  4509.9  389.73  4529.9  390.58  4649.9  386.97  4829.9  384.29
  4859.9  382.95  4889.9  384.55  4959.9  384.65  4989.9  382.64  4990.3  378.47
  4990.8  377.97  5004.5  378.47  5019.9  378.56  5029.9  383.10  5039.9  384.49
  5120.0  383.16  5130.0  381.75  5140.0  383.02  5190.0  385.62  5201.3  387.73
  5220.0  387.92  5260.0  391.57  5300.0  393.70  5370.1  400.73  5401.2  402.04
#Mann=5,-1,0
  4140.0    0.12       0  4490.4   0.035       0  4990.3   0.035       0
  5004.5   0.035       0  5201.3   0.045       0
Bank Sta=4990.3,5004.5
Exp/Cntr=0.3,0.1

Type RM Length L Ch R = 1,14146,758,758,758
BEGIN DESCRIPTION:
Dry Creek14146.123
END DESCRIPTION:
XS GIS Cut Line= 3
      2731263.47      6833367.16      2730527.94      6833613.21
      2730175.97      6833711.01
#Sta/Elev= 30
  4224.4  420.88  4287.0  421.96  4313.5  420.44  4337.7  418.28  4439.6  404.83
  4534.4  394.28  4660.7  385.80  4717.2  383.81  4760.7  383.06  4833.3  383.88
  4881.7  382.81  4938.8  384.34  4950.2  383.65  4952.7  377.92  4953.2  377.42
  4967.0  377.92  4976.5  384.57  5022.8  383.39  5033.1  380.16  5048.2  383.28
  5053.9  379.16  5064.3  383.00  5074.7  383.65  5095.4  383.24  5136.9  384.79
  5178.4  387.60  5195.6  389.64  5229.8  390.13  5255.9  391.47  5365.3  398.58
#Mann=6,-1,0
  4224.4    0.05       0  4313.5    0.12       0  4717.2    0.16       0
  4952.7    0.07       0  4967.0    0.16       0  5255.9   0.045       0
Bank Sta=4952.7,4967
Exp/Cntr=0.3,0.1

Type RM Length L Ch R = 1,13388,77,77,77
BEGIN DESCRIPTION:
Dry Creek13388.34
END DESCRIPTION:
XS GIS Cut Line= 4
      2730442.15      6832584.14      2730423.03      6833022.67
      2730411.38      6833518.55      2730151.39      6833702.08
#Sta/Elev= 30
  4569.5  408.10  4593.7  405.49  4606.4  403.05  4656.4  398.77  4726.5  391.43
  4836.6  385.27  4986.8  383.13  4996.8  380.57  4997.9  378.46  4998.4  377.96
  5012.3  378.46  5016.8  381.65  5026.8  382.29  5098.3  383.51  5136.8  383.43
  5146.8  381.67  5166.8  383.55  5236.8  383.31  5276.8  380.91  5296.9  383.42
  5336.9  384.19  5346.9  382.67  5366.9  382.09  5396.9  383.77  5436.9  384.02
  5511.0  383.74  5523.4  383.03  5618.3  389.18  5661.5  389.94  5822.7  399.36
#Mann=4,-1,0
  4569.5    0.16       0  4997.9    0.07       0  5012.3    0.16       0
  5661.5   0.045       0
Bank Sta=4997.9,5012.3
Exp/Cntr=0.3,0.1

Type RM Length L Ch R = 1,13311,303,303,303
BEGIN DESCRIPTION:
Dry Creek13310.79
END DESCRIPTION:
XS GIS Cut Line= 4
      2730358.99      6832558.81      2730345.99      6833018.27
      2730323.12      6833428.46      2730092.97      6833686.85
#Sta/Elev= 30
  4547.7  400.48  4569.9  399.65  4659.9  393.21  4730.0  387.30  4740.0  387.32
  4810.0  384.36  4832.6  382.57  4890.0  381.82  4960.1  382.99  4970.1  378.73
  4982.9  377.84  4983.4  377.34  4996.8  377.34  4997.3  377.84  5000.1  382.94
  5006.2  382.46  5020.1  382.79  5070.2  382.20  5140.3  382.77  5200.4  382.50
  5240.4  383.67  5380.7  382.94  5410.7  383.73  5473.3  386.88  5552.7  390.81
  5559.4  391.70  5587.9  393.32  5658.9  396.43  5694.0  398.68  5764.2  400.56
#Mann=4,-1,0
  4547.7    0.16       0  4982.9    0.07       0  4997.3    0.16       0
  5473.3   0.045       0
Bank Sta=4982.9,4997.3
Exp/Cntr=0.3,0.1

Type RM Length L Ch R = 1,13008,408,408,408
BEGIN DESCRIPTION:
Dry Creek13007.98
END DESCRIPTION:
XS GIS Cut Line= 3
      2730348.90      6832519.57      2730190.67      6832780.83
      2729776.85      6833319.24
#Sta/Elev= 30
  4698.7  401.93  4700.8  401.93  4752.8  396.69  4778.7  394.87  4789.6  394.42
  4817.3  391.18  4840.7  389.94  4853.6  388.19  4863.3  388.11  4927.3  383.43
  4948.7  382.82  4950.3  377.38  4950.8  376.88  4964.8  377.38  4970.0  380.12
  4979.7  382.15  4985.5  377.44  4992.6  381.27  5003.8  382.23  5065.2  382.73
  5163.2  381.78  5193.5  380.59  5200.2  379.59  5214.7  380.50  5235.5  380.33
  5243.7  380.70  5256.6  383.17  5284.5  384.78  5370.5  388.79  5683.2  397.49
#Mann=7,-1,0
  4698.7    0.12       0  4700.8    0.16       0  4778.7    0.12       0
  4950.3    0.07       0  4964.8    0.12       0  5163.2    0.16       0
  5284.5   0.045       0
Bank Sta=4950.3,4964.8
Exp/Cntr=0.3,0.1

Type RM Length L Ch R = 1,12600,144,144,144
BEGIN DESCRIPTION:
Dry Creek12599.667
END DESCRIPTION:
XS GIS Cut Line= 3
      2730239.08      6832369.54      2729862.76      6832747.43
      2729661.93      6833145.09
#Sta/Elev= 30
  4466.7  401.58  4471.3  401.58  4484.0  399.49  4526.5  395.61  4576.0  391.98
  4604.3  388.42  4632.5  386.32  4667.9  384.76  4672.4  385.13  4682.0  384.85
  4689.1  383.67  4710.3  382.06  4774.0  380.64  4887.1  381.58  4942.4  380.75
  4964.9  381.47  4971.7  377.27  4972.2  376.77  4985.8  376.77  4986.3  377.27
  4993.2  379.91  4999.0  380.94  5015.2  381.24  5037.6  379.83  5062.1  381.71
  5073.6  382.77  5125.7  384.99  5216.9  388.49  5268.7  391.65  5445.5  397.41
#Mann=7,-1,0
  4466.7    0.16       0  4672.4    0.12       0  4942.4    0.16       0
  4971.7    0.07       0  4986.3    0.16       0  5062.1    0.12       0
  5125.7   0.045       0
Bank Sta=4971.7,4986.3
Exp/Cntr=0.3,0.1

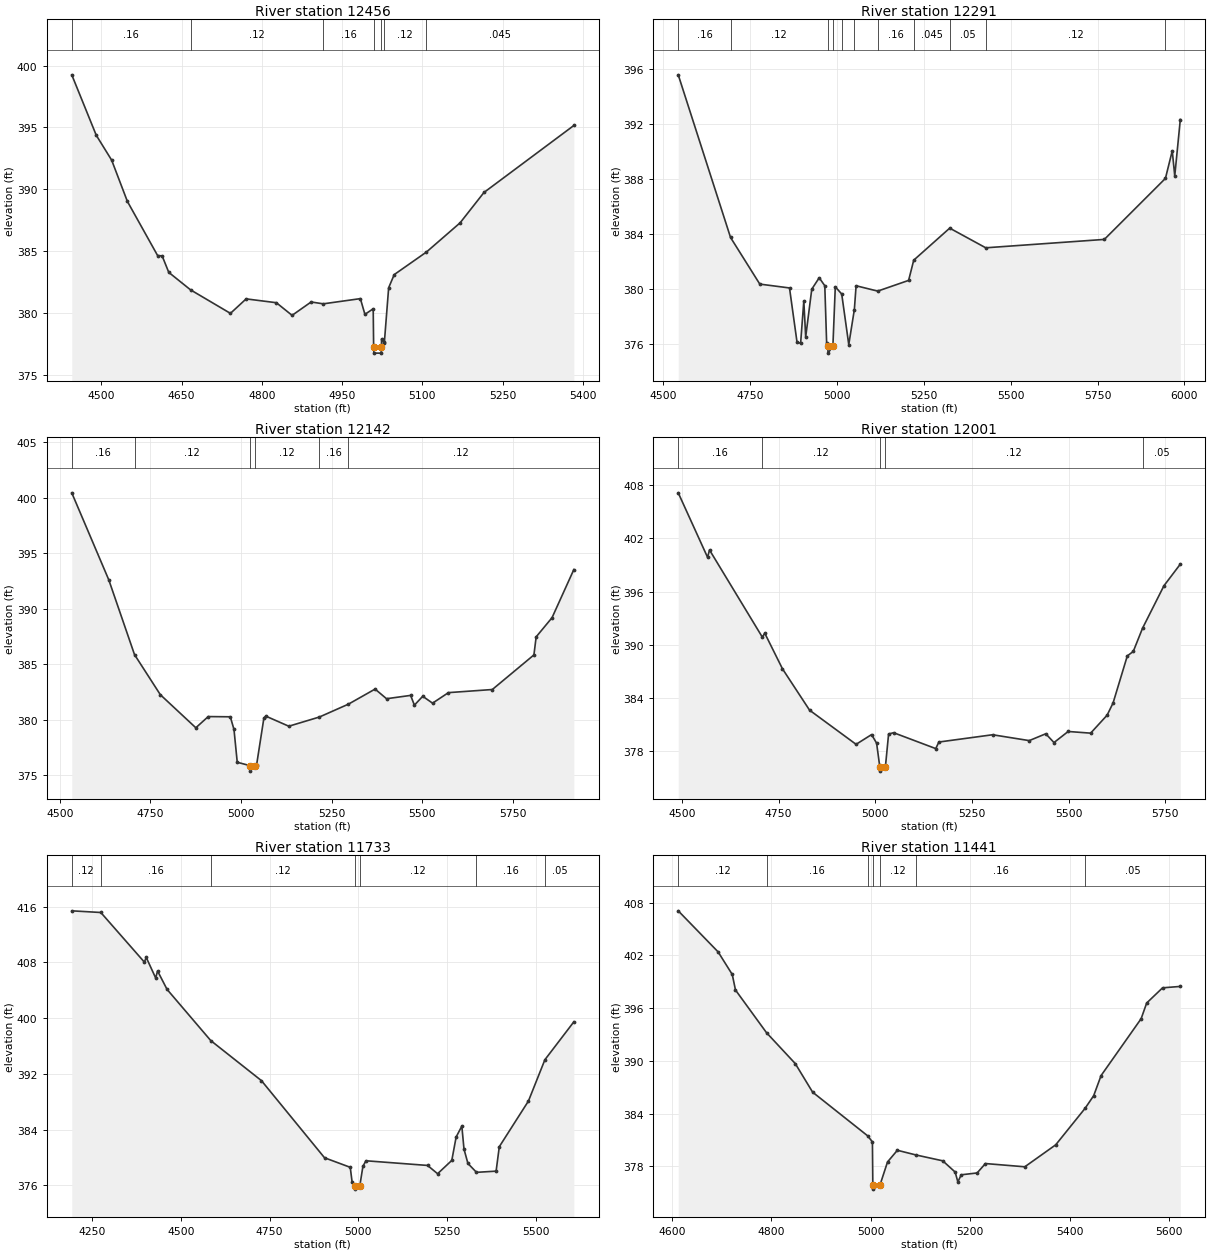
Type RM Length L Ch R = 1,12456,165,165,165
BEGIN DESCRIPTION:
Mapping XS 259990f3
END DESCRIPTION:
XS GIS Cut Line= 3
      2730193.19      6832353.64      2729735.80      6832683.19
      2729634.75      6833044.48
#Sta/Elev= 30
  4444.5  399.25  4490.3  394.37  4519.1  392.36  4548.5  389.03  4605.0  384.66
  4613.5  384.63  4625.9  383.30  4666.6  381.89  4741.2  379.99  4770.6  381.16
  4827.1  380.85  4856.5  379.83  4892.1  380.91  4914.8  380.76  4984.2  381.18
  4992.7  379.91  5008.2  380.36  5009.0  377.28  5009.5  376.78  5023.1  376.78
  5023.6  377.28  5023.8  377.92  5028.3  377.65  5029.0  377.61  5037.1  382.06
  5047.5  383.12  5107.7  384.94  5170.7  387.30  5215.3  389.75  5383.4  395.16
#Mann=7,-1,0
  4444.5    0.16       0  4666.6    0.12       0  4914.8    0.16       0
  5009.0    0.07       0  5023.6    0.16       0  5028.3    0.12       0
  5107.7   0.045       0
Bank Sta=5009,5023.6
Exp/Cntr=0.3,0.1

Type RM Length L Ch R = 1,12291,149,149,149
BEGIN DESCRIPTION:
Mapping XS 07ed2c6b
END DESCRIPTION:
XS GIS Cut Line= 4
      2730155.63      6832356.94      2729723.81      6832519.99
      2729318.89      6832383.05      2728790.85      6832208.07
#Sta/Elev= 30
  4543.0  395.61  4693.6  383.78  4777.8  380.39  4863.3  380.11  4885.0  376.16
  4895.3  376.09  4904.5  379.16  4909.9  376.55  4927.4  380.02  4948.8  380.85
  4964.9  380.27  4970.2  376.10  4973.6  375.87  4974.1  375.37  4988.2  375.87
  4995.1  380.19  5013.6  379.67  5033.9  375.99  5050.0  378.54  5055.0  380.27
  5117.2  379.88  5206.2  380.66  5220.9  382.13  5324.5  384.46  5428.2  383.03
  5769.6  383.64  5945.5  388.08  5965.1  390.08  5972.3  388.26  5988.3  392.36
#Mann=11,-1,0
  4543.0    0.16       0  4693.6    0.12       0  4973.6    0.07       0
  4988.2    0.12       0  5013.6    0.16       0  5050.0    0.12       0
  5117.2    0.16       0  5220.9   0.045       0  5324.5    0.05       0
  5428.2    0.12       0  5945.5    0.05       0
Bank Sta=4973.6,4988.2
Exp/Cntr=0.3,0.1

Type RM Length L Ch R = 1,12142,141,141,141
BEGIN DESCRIPTION:
Mapping XS 92203875
END DESCRIPTION:
XS GIS Cut Line= 4
      2730186.72      6832317.12      2729726.83      6832397.14
      2729285.74      6832251.01      2728922.39      6831980.41
#Sta/Elev= 30
  4533.2  400.46  4635.4  392.60  4706.2  385.87  4777.5  382.25  4875.3  379.27
  4909.5  380.28  4970.4  380.26  4980.5  379.12  4989.5  376.16  5024.0  375.86
  5024.5  375.36  5038.6  375.86  5043.0  375.95  5063.0  380.15  5068.3  380.32
  5131.7  379.41  5216.0  380.24  5296.1  381.40  5369.6  382.76  5401.2  381.89
  5467.6  382.19  5478.0  381.31  5501.0  382.11  5528.1  381.49  5571.9  382.44
  5692.9  382.72  5807.6  385.84  5813.8  387.47  5857.6  389.20  5917.7  393.54
#Mann=6,-1,0
  4533.2    0.16       0  4706.2    0.12       0  5024.0    0.07       0
  5038.6    0.12       0  5216.0    0.16       0  5296.1    0.12       0
Bank Sta=5024,5038.6
Exp/Cntr=0.3,0.1

Type RM Length L Ch R = 1,12001,268,268,268
BEGIN DESCRIPTION:
Dry Creek11875.811
END DESCRIPTION:
XS GIS Cut Line= 3
      2730235.03      6832291.34      2729726.43      6832256.27
      2729052.82      6831845.27
#Sta/Elev= 30
  4490.2  407.13  4566.1  399.86  4571.1  400.69  4707.8  390.86  4714.0  391.31
  4759.9  387.29  4830.0  382.63  4950.3  378.78  4990.4  379.88  5003.4  378.91
  5011.6  376.26  5012.1  375.76  5026.2  376.26  5034.4  379.94  5047.4  380.09
  5156.4  378.30  5164.5  379.04  5303.5  379.86  5398.3  379.20  5441.0  379.97
  5462.3  378.98  5499.0  380.23  5557.1  380.04  5599.8  382.07  5615.2  383.45
  5652.0  388.75  5667.4  389.25  5691.4  391.87  5746.8  396.66  5789.1  399.09
#Mann=5,-1,0
  4490.2    0.16       0  4707.8    0.12       0  5011.6    0.07       0
  5026.2    0.12       0  5691.4    0.05       0
Bank Sta=5011.6,5026.2
Exp/Cntr=0.3,0.1

Type RM Length L Ch R = 1,11733,292,292,292
BEGIN DESCRIPTION:
Dry Creek11733.258
END DESCRIPTION:
XS GIS Cut Line= 3
      2730393.47      6832269.94      2729625.54      6832020.28
      2729076.03      6831761.01
#Sta/Elev= 30
  4192.5  415.40  4274.4  415.16  4397.1  408.04  4402.4  408.71  4429.0  405.76
  4434.3  406.77  4461.0  404.13  4584.2  396.78  4727.1  391.03  4904.9  379.96
  4977.4  378.59  4982.6  376.48  4989.8  375.96  4990.3  375.46  5004.4  375.96
  5013.1  378.73  5021.6  379.53  5195.3  378.86  5223.6  377.67  5263.6  379.58
  5275.9  382.95  5291.9  384.50  5298.0  381.20  5309.1  379.14  5333.2  377.87
  5388.5  378.04  5397.5  381.55  5479.6  388.10  5526.0  394.03  5607.6  399.47
#Mann=7,-1,0
  4192.5    0.12       0  4274.4    0.16       0  4584.2    0.12       0
  4989.8    0.07       0  5004.4    0.12       0  5333.2    0.16       0
  5526.0    0.05       0
Bank Sta=4989.8,5004.4
Exp/Cntr=0.3,0.1

Type RM Length L Ch R = 1,11441,370,370,370
BEGIN DESCRIPTION:
Dry Creek11440.942
END DESCRIPTION:
XS GIS Cut Line= 3
      2730101.02      6831886.01      2729726.61      6831786.16
      2729142.49      6831570.37
#Sta/Elev= 30
  4612.5  407.06  4692.7  402.39  4721.2  399.82  4727.7  398.05  4790.2  393.19
  4848.0  389.68  4882.9  386.43  4993.7  381.46  5003.2  380.77  5004.0  375.90
  5004.5  375.40  5018.6  375.90  5033.6  378.49  5053.4  379.82  5090.6  379.29
  5144.7  378.62  5169.7  377.34  5175.1  376.22  5181.9  377.03  5213.9  377.24
  5230.6  378.31  5309.8  377.94  5372.0  380.44  5431.2  384.60  5448.4  386.03
  5463.3  388.32  5543.9  394.79  5555.0  396.57  5587.0  398.30  5622.7  398.46
#Mann=7,-1,0
  4612.5    0.12       0  4790.2    0.16       0  4993.7    0.12       0
  5004.0    0.07       0  5018.6    0.12       0  5090.6    0.16       0
  5431.2    0.05       0
Bank Sta=5004,5018.6
Exp/Cntr=0.3,0.1

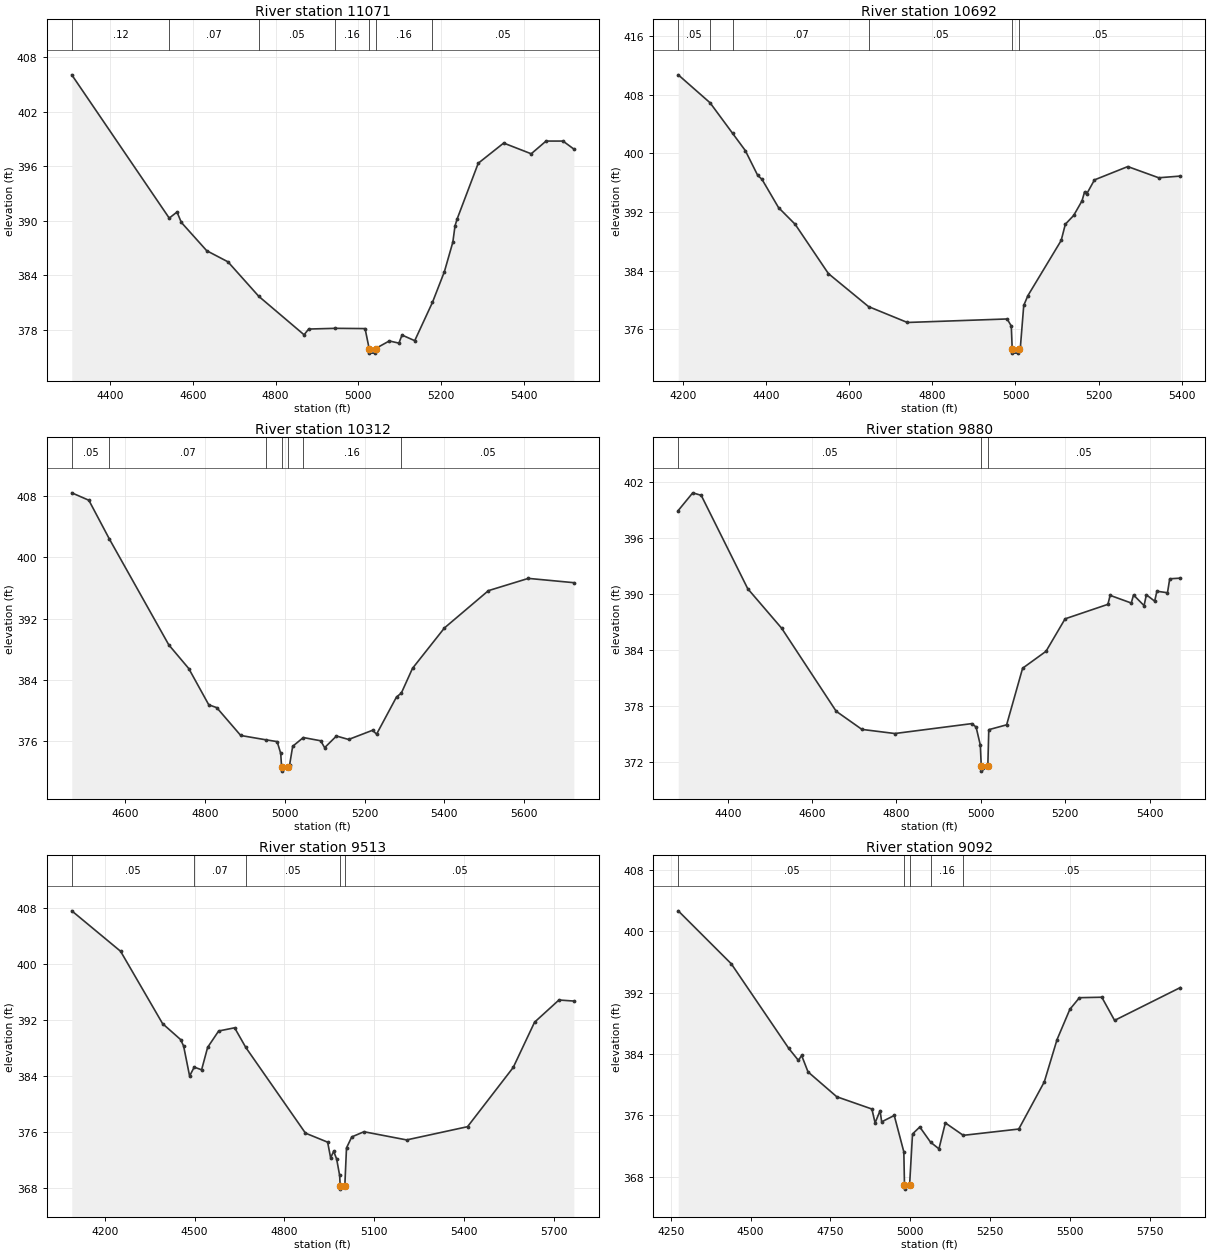
Type RM Length L Ch R = 1,11071,379,379,379
BEGIN DESCRIPTION:
Dry Creek11070.99
END DESCRIPTION:
XS GIS Cut Line= 3
      2730333.71      6831635.44      2729645.37      6831473.80
      2729150.36      6831363.58
#Sta/Elev= 30
  4307.2  406.04  4542.9  390.27  4561.7  390.94  4572.1  389.80  4633.6  386.68
  4684.9  385.46  4759.5  381.66  4869.0  377.43  4880.1  378.06  4944.7  378.14
  5016.5  378.11  5026.4  375.91  5026.9  375.41  5041.3  375.41  5041.8  375.91
  5075.1  376.75  5098.4  376.51  5105.8  377.40  5136.6  376.78  5179.5  381.00
  5208.3  384.37  5228.8  387.63  5234.0  389.41  5239.2  390.18  5290.2  396.31
  5351.7  398.53  5418.3  397.35  5454.2  398.75  5495.1  398.75  5521.4  397.87
#Mann=7,-1,0
  4307.2    0.12       0  4542.9    0.07       0  4759.5    0.05       0
  4944.7    0.16       0  5026.4    0.07       0  5041.8    0.16       0
  5179.5    0.05       0
Bank Sta=5026.4,5041.8
Exp/Cntr=0.3,0.1

Type RM Length L Ch R = 1,10692,380,380,380
BEGIN DESCRIPTION:
Dry Creek10692.09
END DESCRIPTION:
XS GIS Cut Line= 3
      2730437.37      6831165.10      2729617.07      6831177.00
      2729229.78      6831198.99
#Sta/Elev= 30
  4188.4  410.75  4265.0  406.93  4319.4  402.74  4349.8  400.40  4379.8  396.99
  4389.8  396.48  4429.8  392.60  4469.8  390.32  4549.8  383.58  4646.4  379.07
  4739.8  376.90  4979.9  377.38  4989.9  376.42  4992.2  373.21  4992.7  372.71
  5007.1  372.71  5007.6  373.21  5011.8  373.51  5019.9  379.23  5029.9  380.57
  5110.0  388.11  5120.0  390.33  5140.1  391.53  5160.1  393.52  5166.3  394.75
  5171.3  394.46  5190.1  396.39  5270.3  398.21  5344.7  396.68  5396.7  396.91
#Mann=6,-1,0
  4188.4    0.05       0  4265.0    0.12       0  4319.4    0.07       0
  4646.4    0.05       0  4992.2    0.05       0  5007.6    0.05       0
Bank Sta=4992.2,5007.6
Exp/Cntr=0.3,0.1

Type RM Length L Ch R = 1,10312,432,432,432
BEGIN DESCRIPTION:
Dry Creek10312.13
END DESCRIPTION:
XS GIS Cut Line= 3
      2730408.78      6830878.68      2729866.11      6830897.11
      2729152.12      6830890.74
#Sta/Elev= 30
  4467.0  408.43  4509.8  407.46  4560.9  402.43  4709.9  388.60  4759.9  385.51
  4810.0  380.78  4830.0  380.41  4890.0  376.78  4952.4  376.22  4981.2  375.98
  4990.1  374.45  4992.4  372.63  4992.9  372.13  5007.8  372.63  5012.5  372.98
  5020.1  375.37  5046.7  376.51  5090.1  376.09  5100.1  375.19  5129.6  376.71
  5160.1  376.26  5220.1  377.46  5230.1  376.95  5280.1  381.81  5292.0  382.30
  5320.1  385.54  5400.1  390.81  5510.1  395.67  5610.1  397.27  5724.0  396.71
#Mann=7,-1,0
  4467.0    0.05       0  4560.9    0.07       0  4952.4    0.05       0
  4992.4    0.05       0  5007.8    0.05       0  5046.7    0.16       0
  5292.0    0.05       0
Bank Sta=4992.4,5007.8
Exp/Cntr=0.3,0.1

Type RM Length L Ch R = 1,9880,367,367,367
BEGIN DESCRIPTION:
Dry Creek9879.64
END DESCRIPTION:
XS GIS Cut Line= 3
      2730330.34      6830653.44      2729590.94      6830599.71
      2729169.80      6830755.55
#Sta/Elev= 30
  4282.6  398.90  4317.0  400.79  4337.1  400.52  4447.4  390.54  4527.9  386.31
  4657.1  377.44  4718.1  375.50  4796.2  375.06  4978.8  376.12  4988.8  375.75
  4998.8  373.83  5001.1  371.54  5001.6  371.04  5016.6  371.54  5018.9  375.47
  5061.2  375.99  5099.1  382.04  5154.6  383.85  5199.8  387.32  5301.3  388.87
  5306.6  389.83  5356.7  389.01  5362.1  389.87  5387.1  388.73  5392.5  389.89
  5412.2  389.21  5417.5  390.27  5442.6  390.11  5447.9  391.60  5473.0  391.67
#Mann=3,-1,0
  4282.6    0.05       0  5001.1    0.05       0  5016.6    0.05       0
Bank Sta=5001.1,5016.6
Exp/Cntr=0.3,0.1

Type RM Length L Ch R = 1,9513,421,421,421
BEGIN DESCRIPTION:
Dry Creek9512.8
END DESCRIPTION:
XS GIS Cut Line= 3
      2730618.68      6830390.06      2729711.96      6830327.20
      2728957.07      6830184.80
#Sta/Elev= 30
  4090.0  407.54  4253.1  401.76  4393.4  391.42  4453.5  389.15  4463.6  388.22
  4483.6  383.94  4499.0  385.21  4523.7  384.83  4543.8  388.03  4580.6  390.37
  4634.0  390.83  4671.3  388.02  4870.6  375.78  4944.7  374.49  4954.7  372.25
  4964.8  373.19  4974.8  372.08  4984.8  369.73  4986.6  368.28  4987.1  367.78
  5002.1  368.28  5007.7  373.67  5025.3  375.24  5066.0  375.98  5208.5  374.81
  5412.0  376.70  5564.7  385.17  5635.9  391.63  5717.3  394.80  5767.1  394.65
#Mann=5,-1,0
  4090.0    0.05       0  4499.0    0.07       0  4671.3    0.05       0
  4986.6    0.05       0  5002.1    0.05       0
Bank Sta=4986.6,5002.1
Exp/Cntr=0.3,0.1

Type RM Length L Ch R = 1,9092,467,467,467
BEGIN DESCRIPTION:
Dry Creek9091.77
END DESCRIPTION:
XS GIS Cut Line= 3
      2730452.27      6829965.32      2729716.58      6829942.85
      2728880.07      6829933.60
#Sta/Elev= 30
  4273.4  402.65  4439.7  395.74  4619.8  384.71  4649.8  383.16  4659.9  383.80
  4679.9  381.66  4769.9  378.42  4880.0  376.82  4890.0  375.01  4905.6  376.61
  4910.6  375.15  4950.0  375.98  4980.0  371.24  4982.1  366.88  4982.6  366.38
  4998.0  366.88  5007.2  373.57  5030.0  374.48  5063.7  372.50  5090.0  371.63
  5110.0  375.01  5166.2  373.39  5340.0  374.21  5420.0  380.36  5460.0  385.88
  5500.0  389.81  5530.0  391.33  5600.1  391.39  5640.1  388.37  5846.0  392.65
#Mann=5,-1,0
  4273.4    0.05       0  4982.1    0.05       0  4998.0    0.05       0
  5063.7    0.16       0  5166.2    0.05       0
Bank Sta=4982.1,4998
Exp/Cntr=0.3,0.1