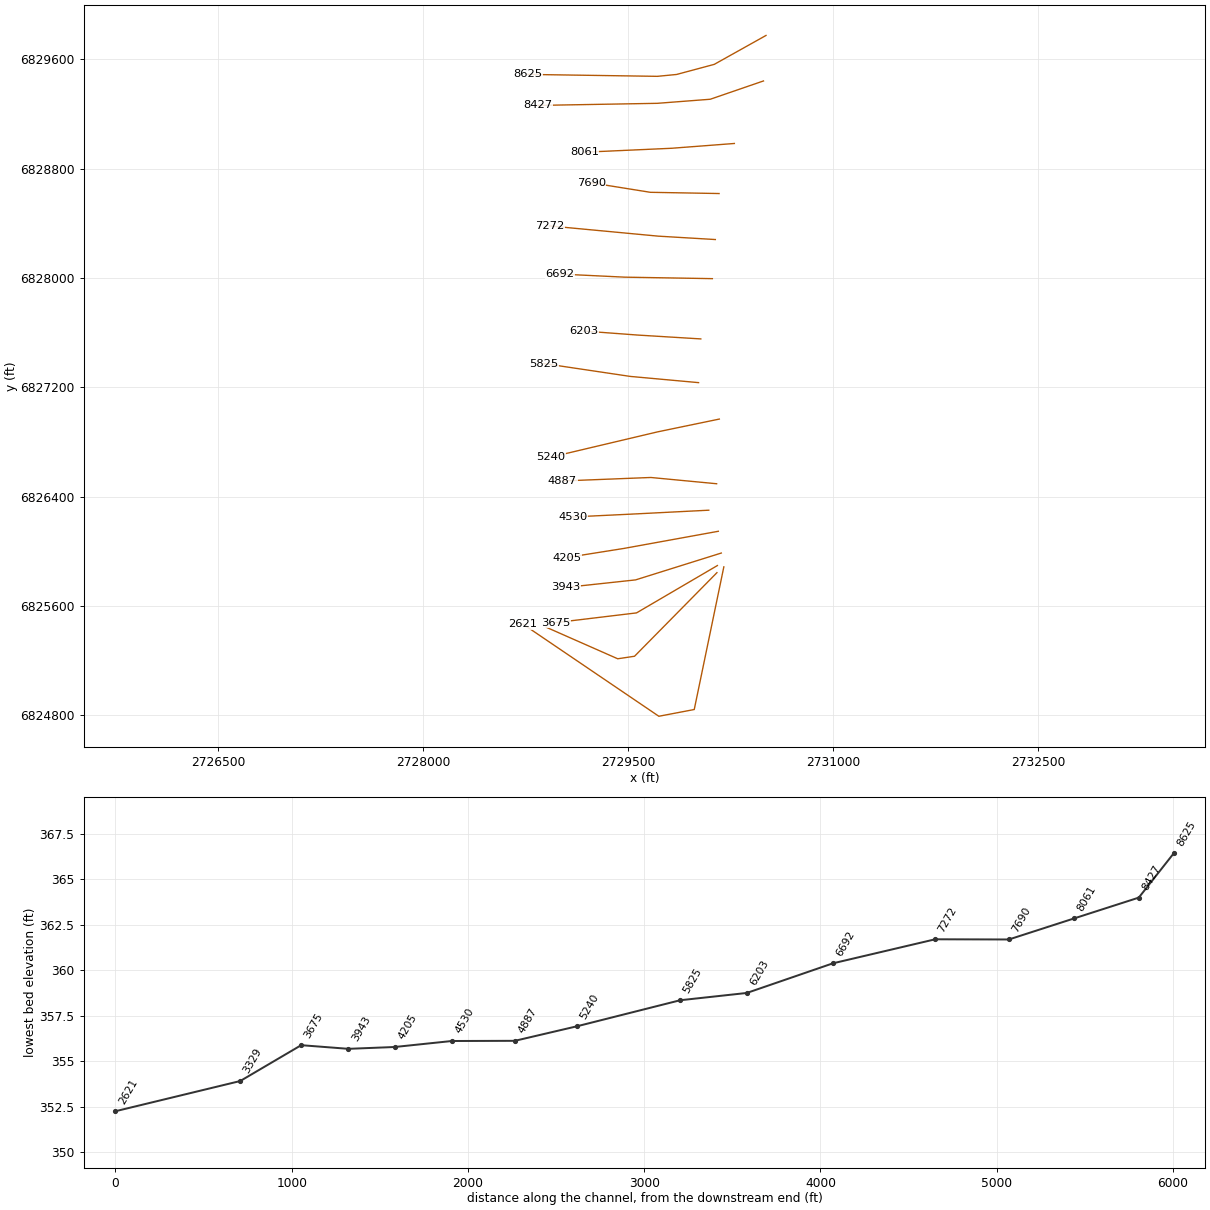
HEC-RAS study Dry Creek.prj: Dry Creek Base Level Engineering

--- Dry Creek.g01 (geometry) --- (continued)

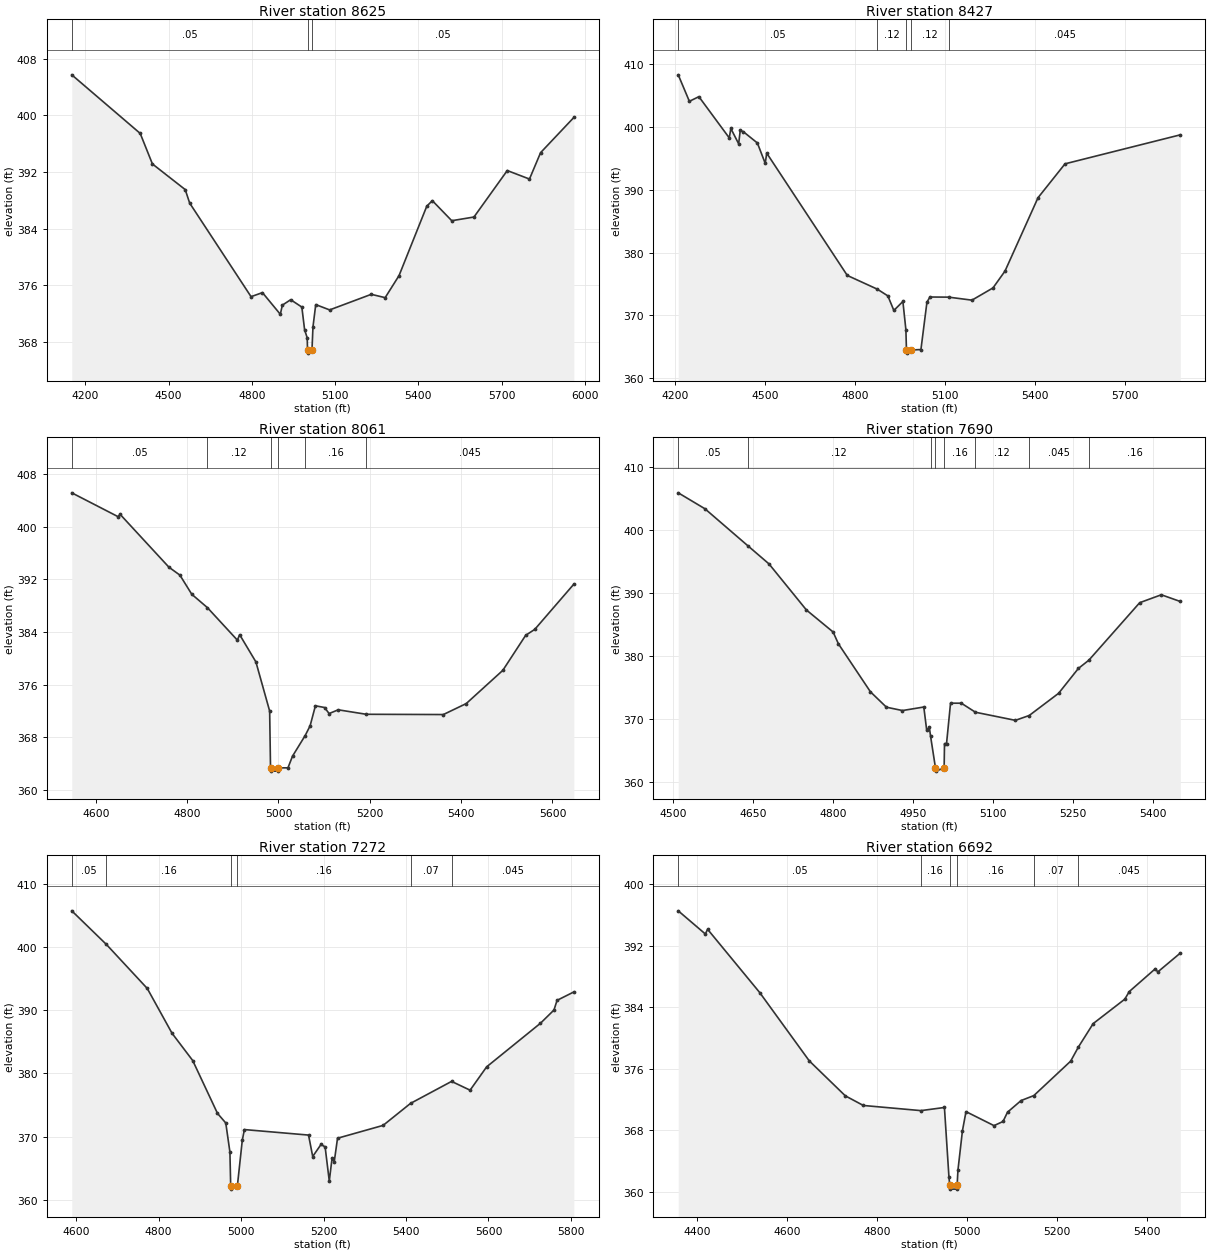
Type RM Length L Ch R = 1,8625,198,198,198
BEGIN DESCRIPTION:
Dry Creek8624.98
END DESCRIPTION:
XS GIS Cut Line= 5
      2730509.66      6829774.43      2730131.10      6829562.93
      2729855.09      6829488.91      2729714.33      6829475.22
      2728766.15      6829489.33
#Sta/Elev= 30
  4150.9  405.70  4397.5  397.43  4441.5  393.12  4559.7  389.50  4575.7  387.60
  4796.9  374.39  4838.0  374.96  4902.4  371.90  4909.6  373.19  4939.7  373.96
  4979.9  372.92  4989.9  369.71  4999.3  368.57  5000.3  366.92  5000.8  366.42
  5016.5  366.92  5020.0  370.12  5030.0  373.27  5080.1  372.52  5230.1  374.72
  5280.1  374.25  5330.1  377.36  5430.1  387.16  5450.1  387.94  5520.1  385.11
  5600.1  385.63  5720.1  392.19  5800.1  390.99  5840.1  394.71  5960.0  399.68
#Mann=3,-1,0
  4150.9    0.05       0  5000.3    0.05       0  5016.5    0.05       0
Bank Sta=5000.3,5016.5
Exp/Cntr=0.3,0.1

Type RM Length L Ch R = 1,8427,366,366,366
BEGIN DESCRIPTION:
Dry Creek8427.31
END DESCRIPTION:
XS GIS Cut Line= 4
      2730491.10      6829441.52      2730101.83      6829307.67
      2729714.56      6829277.80      2728841.95      6829262.52
#Sta/Elev= 30
  4211.4  408.33  4248.5  404.11  4280.2  404.85  4381.4  398.28  4386.7  399.78
  4412.7  397.34  4418.0  399.47  4428.3  399.27  4475.1  397.47  4501.1  394.24
  4506.4  395.84  4774.6  376.37  4874.7  374.18  4909.8  373.11  4929.8  370.79
  4959.9  372.22  4969.9  367.71  4971.8  364.49  4972.3  363.99  4988.0  364.49
  5020.0  364.56  5040.0  372.10  5050.0  372.93  5112.2  372.91  5190.0  372.43
  5260.1  374.38  5300.1  377.06  5410.1  388.75  5500.1  394.15  5884.2  398.77
#Mann=5,-1,0
  4211.4    0.05       0  4874.7    0.12       0  4971.8    0.07       0
  4988.0    0.12       0  5112.2   0.045       0
Bank Sta=4971.8,4988
Exp/Cntr=0.3,0.1

Type RM Length L Ch R = 1,8061,371,371,371
BEGIN DESCRIPTION:
Dry Creek8060.8
END DESCRIPTION:
XS GIS Cut Line= 3
      2730278.04      6828983.99      2729820.37      6828948.99
      2729180.63      6828920.13
#Sta/Elev= 30
  4547.4  405.15  4648.4  401.54  4653.4  401.87  4760.1  393.85  4784.2  392.64
  4810.2  389.73  4844.4  387.70  4910.0  382.76  4915.0  383.59  4950.6  379.45
  4980.7  371.98  4982.6  363.35  4983.1  362.85  4998.3  362.85  4998.8  363.35
  5020.8  363.35  5030.8  365.13  5058.5  368.26  5069.3  369.74  5080.9  372.78
  5100.9  372.52  5110.9  371.60  5130.9  372.17  5192.3  371.49  5361.1  371.45
  5411.2  373.12  5491.3  378.17  5541.3  383.49  5561.3  384.40  5646.8  391.27
#Mann=6,-1,0
  4547.4    0.05       0  4844.4    0.12       0  4982.6    0.07       0
  4998.8    0.12       0  5058.5    0.16       0  5192.3   0.045       0
Bank Sta=4982.6,4998.8
Exp/Cntr=0.3,0.1

Type RM Length L Ch R = 1,7690,418,418,418
BEGIN DESCRIPTION:
Dry Creek7690.12
END DESCRIPTION:
XS GIS Cut Line= 3
      2730166.12      6828617.69      2729663.35      6828626.66
      2729230.81      6828695.96
#Sta/Elev= 30
  4509.7  405.97  4559.8  403.43  4640.1  397.55  4679.8  394.66  4749.9  387.33
  4799.9  383.83  4809.9  381.94  4869.9  374.31  4899.9  371.86  4929.9  371.33
  4969.9  371.89  4975.3  368.22  4980.3  368.64  4982.6  367.24  4991.8  362.19
  4992.3  361.69  5008.0  362.19  5008.7  366.07  5012.5  366.07  5020.0  372.50
  5040.2  372.50  5066.7  371.06  5141.5  369.77  5167.4  370.54  5222.5  374.07
  5259.6  378.03  5279.2  379.34  5374.5  388.49  5415.0  389.75  5450.6  388.68
#Mann=8,-1,0
  4509.7    0.05       0  4640.1    0.12       0  4982.6    0.16       0
  4991.8    0.07       0  5008.0    0.16       0  5066.7    0.12       0
  5167.4   0.045       0  5279.2    0.16       0
Bank Sta=4991.8,5008
Exp/Cntr=0.3,0.1

Type RM Length L Ch R = 1,7272,580,580,580
BEGIN DESCRIPTION:
Dry Creek7271.72
END DESCRIPTION:
XS GIS Cut Line= 3
      2730138.82      6828281.07      2729720.84      6828305.90
      2728925.47      6828380.75
#Sta/Elev= 30
  4589.5  405.72  4673.5  400.40  4772.6  393.44  4832.7  386.35  4882.8  382.04
  4942.9  373.68  4963.0  372.16  4973.0  367.58  4974.9  362.20  4975.4  361.70
  4991.1  362.20  5003.0  369.41  5008.1  371.12  5163.7  370.25  5173.8  366.86
  5193.9  368.76  5203.9  368.38  5214.0  362.98  5220.9  366.67  5225.9  365.97
  5234.0  369.75  5344.5  371.78  5411.0  375.26  5510.6  378.74  5555.5  377.35
  5595.6  381.04  5726.2  387.94  5758.9  390.03  5766.4  391.56  5807.1  392.89
#Mann=6,-1,0
  4589.5    0.05       0  4673.5    0.16       0  4974.9    0.07       0
  4991.1    0.16       0  5411.0    0.07       0  5510.6   0.045       0
Bank Sta=4974.9,4991.1
Exp/Cntr=0.3,0.1

Type RM Length L Ch R = 1,6692,489,489,489
BEGIN DESCRIPTION:
Dry Creek6692.21
END DESCRIPTION:
XS GIS Cut Line= 3
      2730116.92      6827994.91      2729475.18      6828005.81
      2729002.86      6828028.51
#Sta/Elev= 30
  4359.0  396.54  4419.2  393.53  4424.2  394.14  4539.9  385.92  4650.0  377.04
  4730.0  372.50  4770.0  371.25  4897.9  370.58  4950.0  370.99  4960.0  361.98
  4961.8  360.88  4962.3  360.38  4977.7  360.38  4978.2  360.88  4980.0  362.84
  4990.0  367.97  4997.9  370.45  5060.1  368.63  5080.1  369.17  5090.1  370.38
  5120.2  371.89  5148.4  372.53  5230.3  377.01  5247.6  378.86  5280.3  381.89
  5350.4  385.06  5360.4  386.05  5418.5  389.03  5423.5  388.59  5473.7  391.05
#Mann=6,-1,0
  4359.0    0.05       0  4897.9    0.16       0  4961.8    0.07       0
  4978.2    0.16       0  5148.4    0.07       0  5247.6   0.045       0
Bank Sta=4961.8,4978.2
Exp/Cntr=0.3,0.1

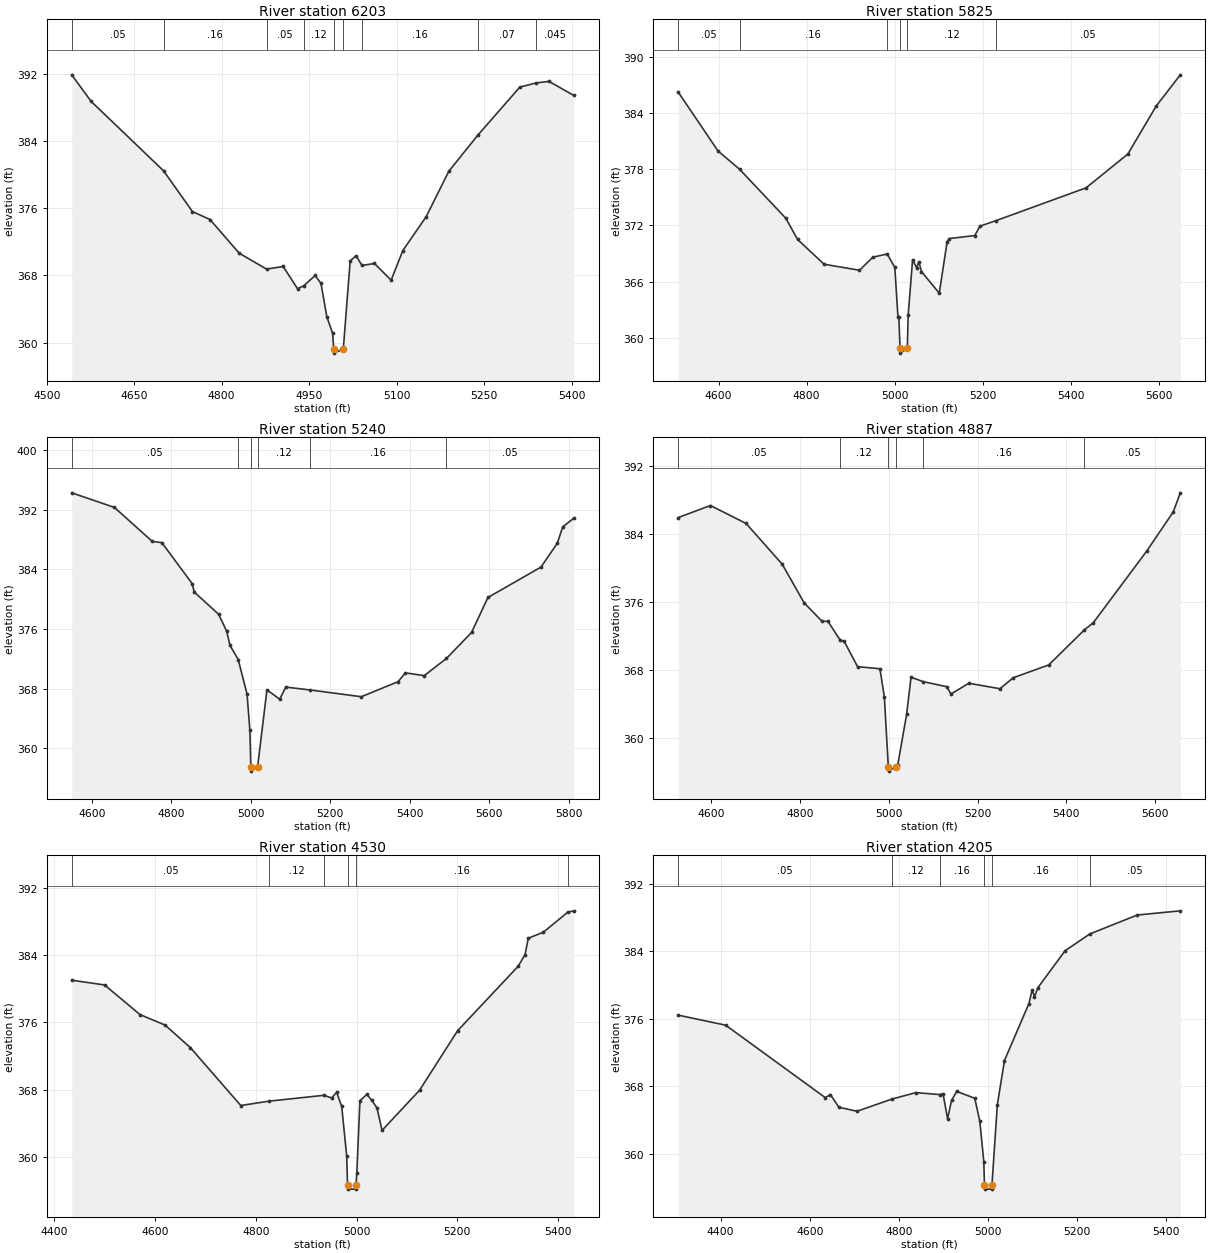
Type RM Length L Ch R = 1,6203,378,378,378
BEGIN DESCRIPTION:
Dry Creek6202.71
END DESCRIPTION:
XS GIS Cut Line= 3
      2730032.52      6827553.91      2729571.10      6827582.05
      2729173.58      6827611.69
#Sta/Elev= 30
  4543.0  391.87  4575.9  388.73  4700.5  380.44  4749.9  375.60  4780.0  374.65
  4830.1  370.64  4877.0  368.75  4905.5  369.06  4930.2  366.41  4941.2  366.79
  4960.3  367.99  4970.3  367.05  4980.3  363.09  4990.3  361.09  4992.1  359.25
  4992.6  358.75  5008.6  359.25  5020.4  369.72  5030.4  370.35  5040.6  369.18
  5062.0  369.42  5090.6  367.43  5110.7  370.96  5150.8  375.00  5189.4  380.38
  5239.4  384.70  5311.2  390.40  5338.8  390.90  5361.4  391.09  5403.9  389.41
#Mann=9,-1,0
  4543.0    0.05       0  4700.5    0.16       0  4877.0    0.05       0
  4941.2    0.12       0  4992.1    0.07       0  5008.6    0.12       0
  5040.6    0.16       0  5239.4    0.07       0  5338.8   0.045       0
Bank Sta=4992.1,5008.6
Exp/Cntr=0.3,0.1

Type RM Length L Ch R = 1,5825,585,585,585
BEGIN DESCRIPTION:
Dry Creek5824.81
END DESCRIPTION:
XS GIS Cut Line= 3
      2730016.18      6827234.02      2729516.92      6827279.45
      2728884.23      6827373.70
#Sta/Elev= 30
  4508.1  386.25  4598.7  379.95  4647.4  378.01  4752.5  372.77  4779.4  370.50
  4839.6  367.85  4920.0  367.21  4950.1  368.60  4983.0  368.95  5000.3  367.51
  5007.4  362.25  5009.4  362.25  5012.2  358.85  5012.7  358.35  5028.7  358.85
  5030.6  362.38  5040.7  368.34  5049.8  367.48  5054.9  368.13  5060.9  367.06
  5101.3  364.76  5119.1  370.24  5124.2  370.60  5182.2  370.92  5193.5  371.92
  5230.7  372.52  5435.0  376.02  5530.0  379.64  5594.3  384.76  5649.1  388.10
#Mann=6,-1,0
  4508.1    0.05       0  4647.4    0.16       0  4983.0    0.12       0
  5012.2    0.07       0  5028.7    0.12       0  5230.7    0.05       0
Bank Sta=5012.2,5028.7
Exp/Cntr=0.3,0.1

Type RM Length L Ch R = 1,5240,353,353,353
BEGIN DESCRIPTION:
Dry Creek5240.02
END DESCRIPTION:
XS GIS Cut Line= 3
      2730168.01      6826967.43      2729716.03      6826873.69
      2728935.55      6826689.12
#Sta/Elev= 30
  4549.2  394.25  4656.6  392.29  4751.8  387.73  4775.9  387.57  4852.1  382.08
  4857.6  380.94  4918.9  377.95  4939.3  375.66  4947.3  373.79  4968.1  371.89
  4990.4  367.23  4997.5  362.37  4999.9  357.42  5000.4  356.92  5016.7  357.42
  5040.4  367.82  5072.5  366.57  5087.8  368.19  5148.7  367.81  5278.0  366.90
  5370.5  368.92  5388.9  370.10  5436.3  369.73  5492.1  372.03  5555.4  375.52
  5596.5  380.21  5730.1  384.29  5771.2  387.49  5784.8  389.68  5812.8  390.85
#Mann=6,-1,0
  4549.2    0.05       0  4968.1    0.12       0  4999.9    0.07       0
  5016.7    0.12       0  5148.7    0.16       0  5492.1    0.05       0
Bank Sta=4999.9,5016.7
Exp/Cntr=0.3,0.1

Type RM Length L Ch R = 1,4887,357,357,357
BEGIN DESCRIPTION:
Dry Creek4887.22
END DESCRIPTION:
XS GIS Cut Line= 3
      2730148.22      6826494.19      2729666.55      6826540.02
      2729020.00      6826514.48
#Sta/Elev= 30
  4525.7  385.93  4598.2  387.35  4678.6  385.24  4760.0  380.44  4809.2  375.91
  4849.4  373.75  4863.0  373.73  4890.4  371.52  4899.6  371.37  4929.7  368.40
  4980.0  368.16  4990.0  364.83  4998.9  356.62  4999.4  356.12  5015.7  356.62
  5020.1  356.83  5040.1  362.78  5050.1  367.16  5076.9  366.65  5130.2  366.05
  5140.2  365.19  5180.2  366.45  5250.3  365.81  5280.3  367.10  5360.1  368.60
  5440.6  372.73  5460.4  373.55  5580.5  381.96  5640.6  386.59  5656.6  388.84
#Mann=6,-1,0
  4525.7    0.05       0  4890.4    0.12       0  4998.9    0.07       0
  5015.7    0.12       0  5076.9    0.16       0  5440.6    0.05       0
Bank Sta=4998.9,5015.7
Exp/Cntr=0.3,0.1

Type RM Length L Ch R = 1,4530,325,325,325
BEGIN DESCRIPTION:
Dry Creek4529.86
END DESCRIPTION:
XS GIS Cut Line= 3
      2730091.08      6826300.62      2729518.53      6826271.59
      2729095.70      6826251.28
#Sta/Elev= 30
  4434.8  381.05  4500.0  380.48  4570.1  376.95  4620.1  375.69  4670.2  373.00
  4770.3  366.09  4826.1  366.61  4935.6  367.31  4950.5  366.99  4960.6  367.66
  4970.6  365.99  4980.6  360.01  4982.2  356.61  4982.7  356.11  4998.5  356.11
  4999.0  356.61  5000.6  358.04  5006.8  366.67  5020.6  367.42  5030.6  366.69
  5040.7  365.79  5050.7  363.12  5125.1  367.91  5200.8  375.03  5321.0  382.72
  5334.5  384.10  5341.0  386.06  5371.0  386.78  5418.9  389.15  5431.4  389.33
#Mann=6,-1,0
  4434.8    0.05       0  4826.1    0.12       0  4935.6    0.16       0
  4982.2    0.07       0  4999.0    0.16       0  5418.9    0.05       0
Bank Sta=4982.2,4999
Exp/Cntr=0.3,0.1

Type RM Length L Ch R = 1,4205,262,262,262
BEGIN DESCRIPTION:
Dry Creek4205.15
END DESCRIPTION:
XS GIS Cut Line= 3
      2730160.83      6826146.40      2729471.50      6826021.11
      2729050.41      6825954.16
#Sta/Elev= 30
  4304.8  376.44  4411.3  375.25  4635.0  366.64  4646.4  367.01  4665.4  365.50
  4706.1  365.03  4785.3  366.49  4838.2  367.24  4891.5  367.01  4899.2  367.10
  4909.4  364.14  4918.3  366.31  4929.7  367.39  4970.4  366.57  4981.8  363.82
  4990.7  359.05  4992.2  356.28  4992.7  355.78  5008.5  355.78  5009.0  356.28
  5021.1  365.80  5037.1  371.05  5092.0  377.82  5099.4  379.46  5104.4  378.62
  5112.2  379.71  5173.0  384.08  5228.5  386.08  5335.0  388.33  5431.8  388.83
#Mann=6,-1,0
  4304.8    0.05       0  4785.3    0.12       0  4891.5    0.16       0
  4992.2    0.07       0  5009.0    0.16       0  5228.5    0.05       0
Bank Sta=4992.2,5009
Exp/Cntr=0.3,0.1

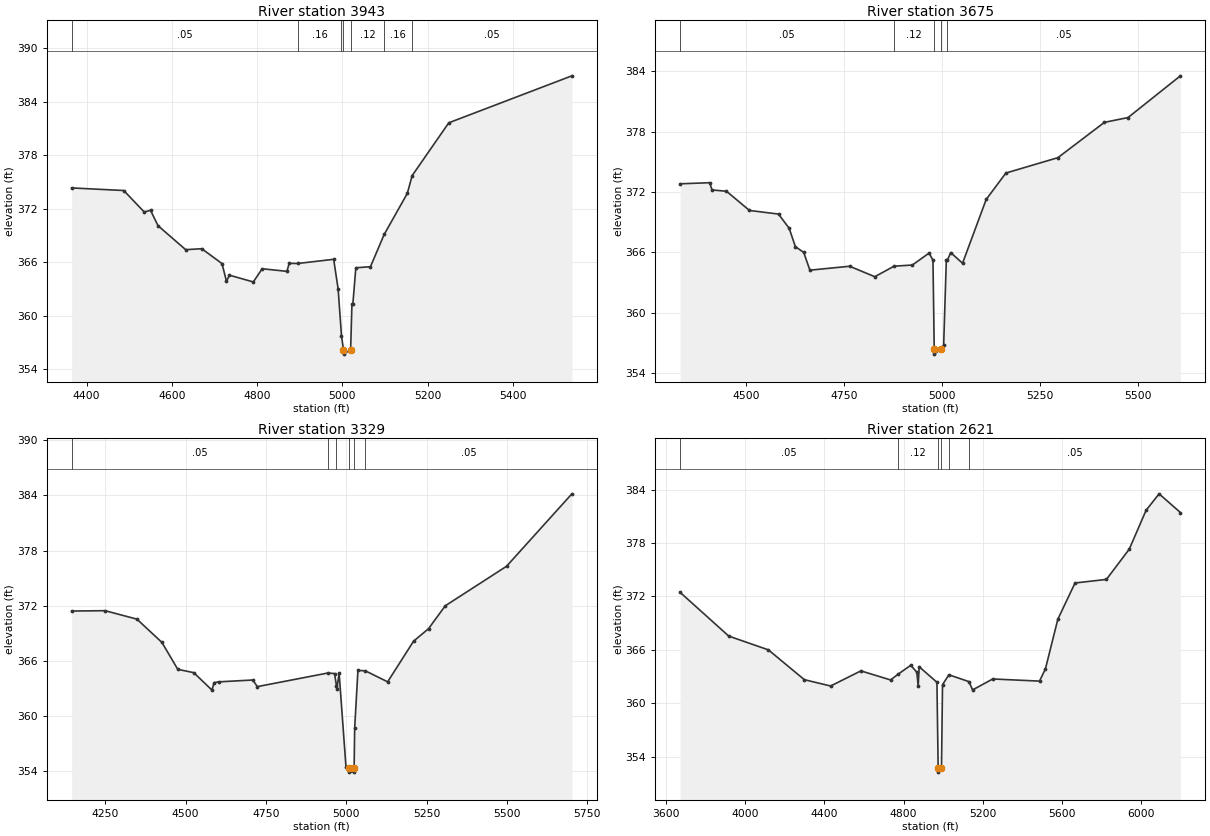
Type RM Length L Ch R = 1,3943,268,268,268
BEGIN DESCRIPTION:
Dry Creek3943.07
END DESCRIPTION:
XS GIS Cut Line= 3
      2730182.57      6825987.16      2729555.17      6825790.58
      2729042.02      6825735.24
#Sta/Elev= 30
  4364.8  374.33  4487.0  374.04  4535.0  371.63  4549.8  371.82  4567.4  370.09
  4632.3  367.40  4670.0  367.51  4717.5  365.84  4728.0  363.85  4734.9  364.54
  4790.9  363.78  4811.8  365.26  4869.9  364.97  4875.1  365.87  4894.9  365.85
  4979.5  366.32  4990.0  362.98  4997.8  357.74  5002.5  356.18  5003.0  355.68
  5019.3  356.18  5022.3  361.25  5024.4  361.25  5031.5  365.37  5065.8  365.49
  5098.0  369.11  5152.2  373.71  5163.7  375.72  5249.6  381.64  5538.4  386.91
#Mann=7,-1,0
  4364.8    0.05       0  4894.9    0.16       0  4997.8    0.12       0
  5002.5    0.07       0  5019.3    0.12       0  5098.0    0.16       0
  5163.7    0.05       0
Bank Sta=5002.5,5019.3
Exp/Cntr=0.3,0.1

Type RM Length L Ch R = 1,3675,346,346,346
BEGIN DESCRIPTION:
Mapping XS 05e53e9e
END DESCRIPTION:
XS GIS Cut Line= 3
      2730153.72      6825895.54      2729562.20      6825549.15
      2728973.04      6825478.18
#Sta/Elev= 30
  4330.7  372.82  4406.2  372.93  4412.0  372.21  4449.1  372.08  4507.8  370.17
  4582.1  369.81  4609.4  368.39  4625.1  366.58  4646.6  365.99  4662.3  364.23
  4763.9  364.62  4828.3  363.58  4877.6  364.63  4924.2  364.74  4967.1  365.93
  4977.0  365.22  4980.2  356.38  4980.7  355.88  4997.0  356.38  5004.3  356.75
  5011.1  365.20  5013.6  365.20  5022.4  365.98  5052.6  364.92  5113.1  371.27
  5163.4  373.89  5296.4  375.42  5415.2  378.93  5475.7  379.41  5609.6  383.56
#Mann=5,-1,0
  4330.7    0.05       0  4877.6    0.12       0  4980.2    0.07       0
  4997.0    0.12       0  5013.6    0.05       0
Bank Sta=4980.2,4997
Exp/Cntr=0.3,0.1

Type RM Length L Ch R = 1,3329,708,708,708
BEGIN DESCRIPTION:
Mapping XS 0d305e82
END DESCRIPTION:
XS GIS Cut Line= 4
      2730150.56      6825843.55      2729547.60      6825231.90
      2729424.57      6825213.42      2728899.92      6825444.79
#Sta/Elev= 30
  4145.6  371.43  4249.6  371.47  4348.6  370.55  4426.4  368.02  4475.9  365.09
  4525.4  364.73  4582.0  362.84  4589.0  363.64  4603.2  363.73  4709.3  363.93
  4723.4  363.21  4942.7  364.69  4963.8  364.63  4969.5  363.31  4970.9  362.99
  4977.9  364.69  4999.2  354.50  5007.8  354.41  5008.3  353.91  5024.1  353.91
  5024.6  354.41  5026.3  358.70  5036.4  364.97  5059.5  364.93  5128.9  363.73
  5209.5  368.15  5256.1  369.51  5308.2  372.00  5498.9  376.30  5702.3  384.18
#Mann=6,-1,0
  4145.6    0.05       0  4942.7    0.12       0  4969.5    0.16       0
  5007.8    0.07       0  5024.6    0.16       0  5059.5    0.05       0
Bank Sta=5007.8,5024.6
Exp/Cntr=0.3,0.1

Type RM Length L Ch R = 1,2621,0,0,0
BEGIN DESCRIPTION:
Dry Creek3385.172
END DESCRIPTION:
XS GIS Cut Line= 4
      2730201.01      6825886.02      2729984.45      6824842.11
      2729725.34      6824792.78      2728731.87      6825466.56
#Sta/Elev= 30
  3670.1  372.45  3915.8  367.54  4116.4  365.99  4298.2  362.64  4431.0  361.93
  4584.2  363.63  4734.3  362.61  4773.8  363.28  4836.5  364.26  4867.0  363.48
  4874.0  361.93  4879.1  364.09  4968.8  362.35  4975.0  352.75  4975.5  352.25
  4991.9  352.75  4997.1  362.08  5029.3  363.19  5130.8  362.42  5149.3  361.49
  5251.0  362.72  5487.7  362.48  5517.6  363.85  5580.5  369.44  5667.4  373.51
  5826.1  373.91  5941.7  377.31  6026.8  381.68  6092.6  383.53  6200.4  381.43
#Mann=6,-1,0
  3670.1    0.05       0  4773.8    0.12       0  4975.0    0.07       0
  4991.9    0.12       0  5029.3    0.16       0  5130.8    0.05       0
Bank Sta=4975,4991.9
Exp/Cntr=0.3,0.1

Chan Stop Cuts=-1