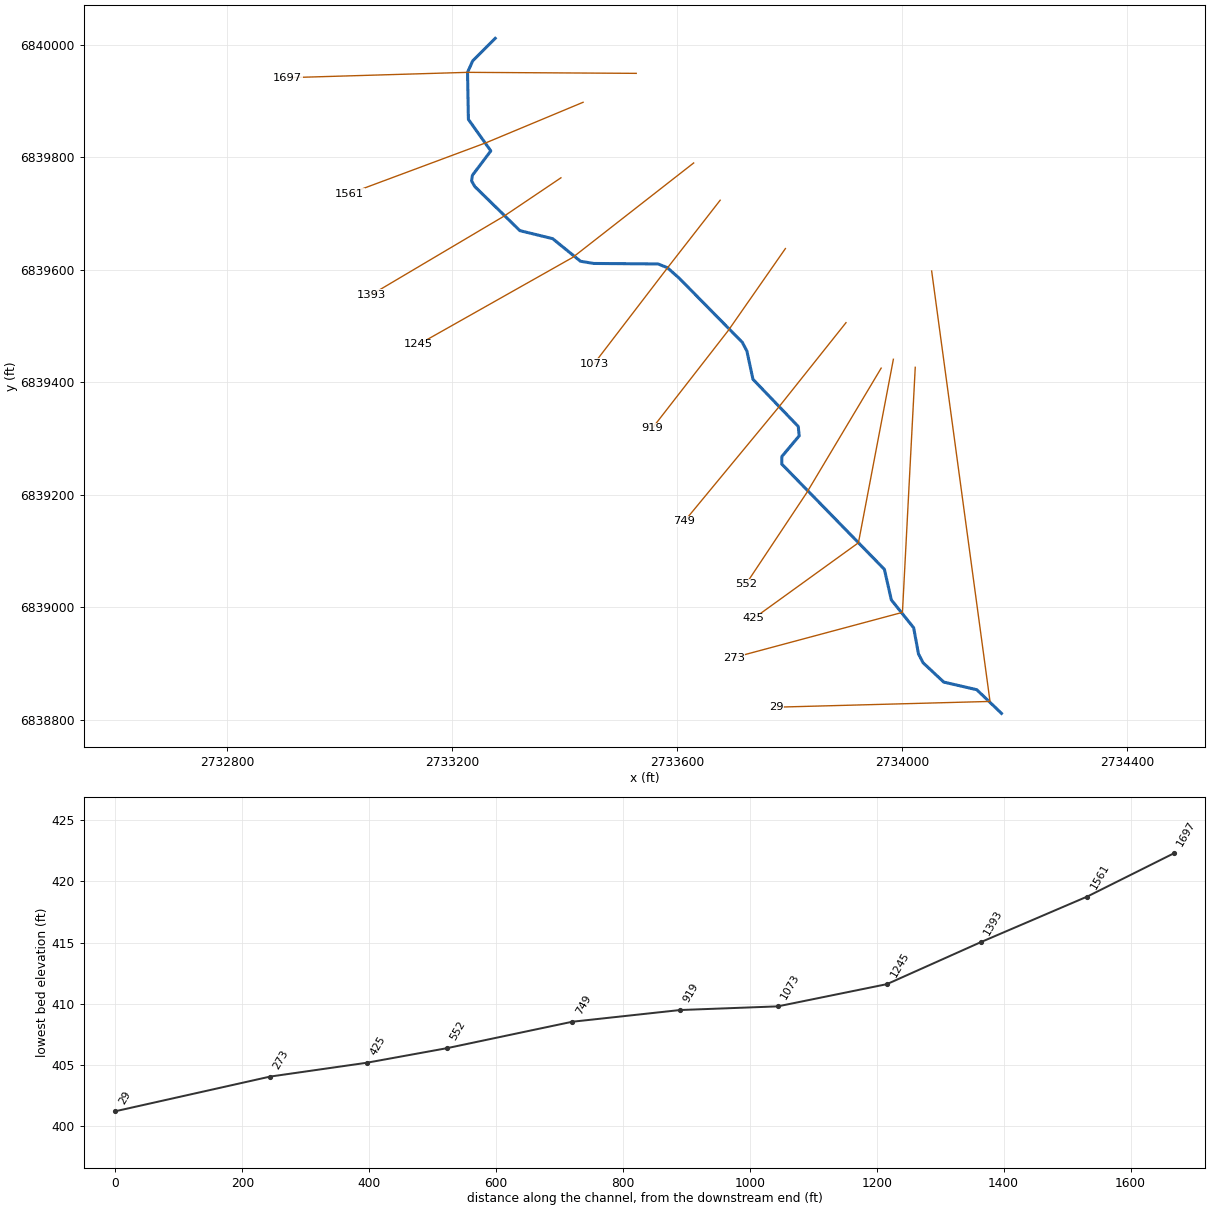
--- Dry Creek Trib 1.prj (project) ---

Proj Title=Dry Creek Trib 1 Base Level Engineering
Current Plan=p01
Default Exp/Contr=0.3,0.1
English Units
Geom File=g01
Flow File=f01
Plan File=p01
BEGIN DESCRIPTION:
Dry Creek Trib 1
END DESCRIPTION:

--- Dry Creek Trib 1.p01 (plan) ---

Plan Title=Multiple Run
Short Identifier=Multiple
Geom File=g01
Flow File=f01
Subcritical Flow
K Sum by GR= 0
Std Step Tol= 0.01
Critical Tol= 0.01
Num of Std Step Trials= 20
Max Error Tol= 0.3
Flow Tol Ratio= 0.001
Split Flow NTrial= 30
Split Flow Tol= 0.02
Split Flow Ratio= 0.02
Log Output Level= 0
Friction Slope Method= 1
Unsteady Friction Slope Method= 2
Unsteady Bridges Friction Slope Method= 1
Parabolic Critical Depth
Global Vel Dist=  1 , 1 , 1
Global Log Level= 0
CheckData=True
Encroach Param= -1, 0, 0, 0
BEGIN DESCRIPTION:
Multiple Run
END DESCRIPTION:

--- Dry Creek Trib 1.f01 (steady flow) ---

Flow Title=Multiple
Number of Profiles=7
Profile Names=10-year,25-year,50-year,1pct_min,100-year,1pct_plu,500-year
River Rch & RM= Dry Creek Trib 1,Reach-1,1697
     201     249     286     163     326     650     422
River Rch & RM= Dry Creek Trib 1,Reach-1,29
    1852    2593    3215    1968    3927    7836    5864
Boundary for River Rch & Prof#=Dry Creek Trib 1,Reach-1,1
Up Type=0
Dn Type=3
Dn Slope=0.005
Boundary for River Rch & Prof#=Dry Creek Trib 1,Reach-1,2
Up Type=0
Dn Type=3
Dn Slope=0.005
Boundary for River Rch & Prof#=Dry Creek Trib 1,Reach-1,3
Up Type=0
Dn Type=3
Dn Slope=0.005
Boundary for River Rch & Prof#=Dry Creek Trib 1,Reach-1,4
Up Type=0
Dn Type=3
Dn Slope=0.005
Boundary for River Rch & Prof#=Dry Creek Trib 1,Reach-1,5
Up Type=0
Dn Type=3
Dn Slope=0.005
Boundary for River Rch & Prof#=Dry Creek Trib 1,Reach-1,6
Up Type=0
Dn Type=3
Dn Slope=0.005
Boundary for River Rch & Prof#=Dry Creek Trib 1,Reach-1,7
Up Type=0
Dn Type=3
Dn Slope=0.005

--- Dry Creek Trib 1.g01 (geometry) ---

Geom Title=Existing Conditions

River Reach=Dry Creek Trib 1,Reach-1
Reach XY= 30
      2733276.00      6840011.00      2733235.99      6839970.95
      2733226.82      6839950.54      2733228.35      6839866.88
      2733268.19      6839810.90      2733235.59      6839767.65
      2733233.99      6839757.65      2733239.63      6839747.64
      2733319.91      6839669.14      2733378.17      6839654.86
      2733427.56      6839614.76      2733450.92      6839610.81
      2733565.56      6839609.94      2733582.19      6839603.18
      2733602.88      6839584.83      2733715.22      6839470.68
      2733723.47      6839454.95      2733734.20      6839404.95
      2733814.74      6839320.99      2733816.38      6839304.33
      2733785.62      6839267.67      2733785.30      6839254.33
      2733967.86      6839067.06      2733980.19      6839012.73
      2734019.89      6838963.16      2734028.42      6838916.85
      2734036.62      6838900.99      2734073.39      6838866.61
      2734132.11      6838853.05      2734176.00      6838811.00

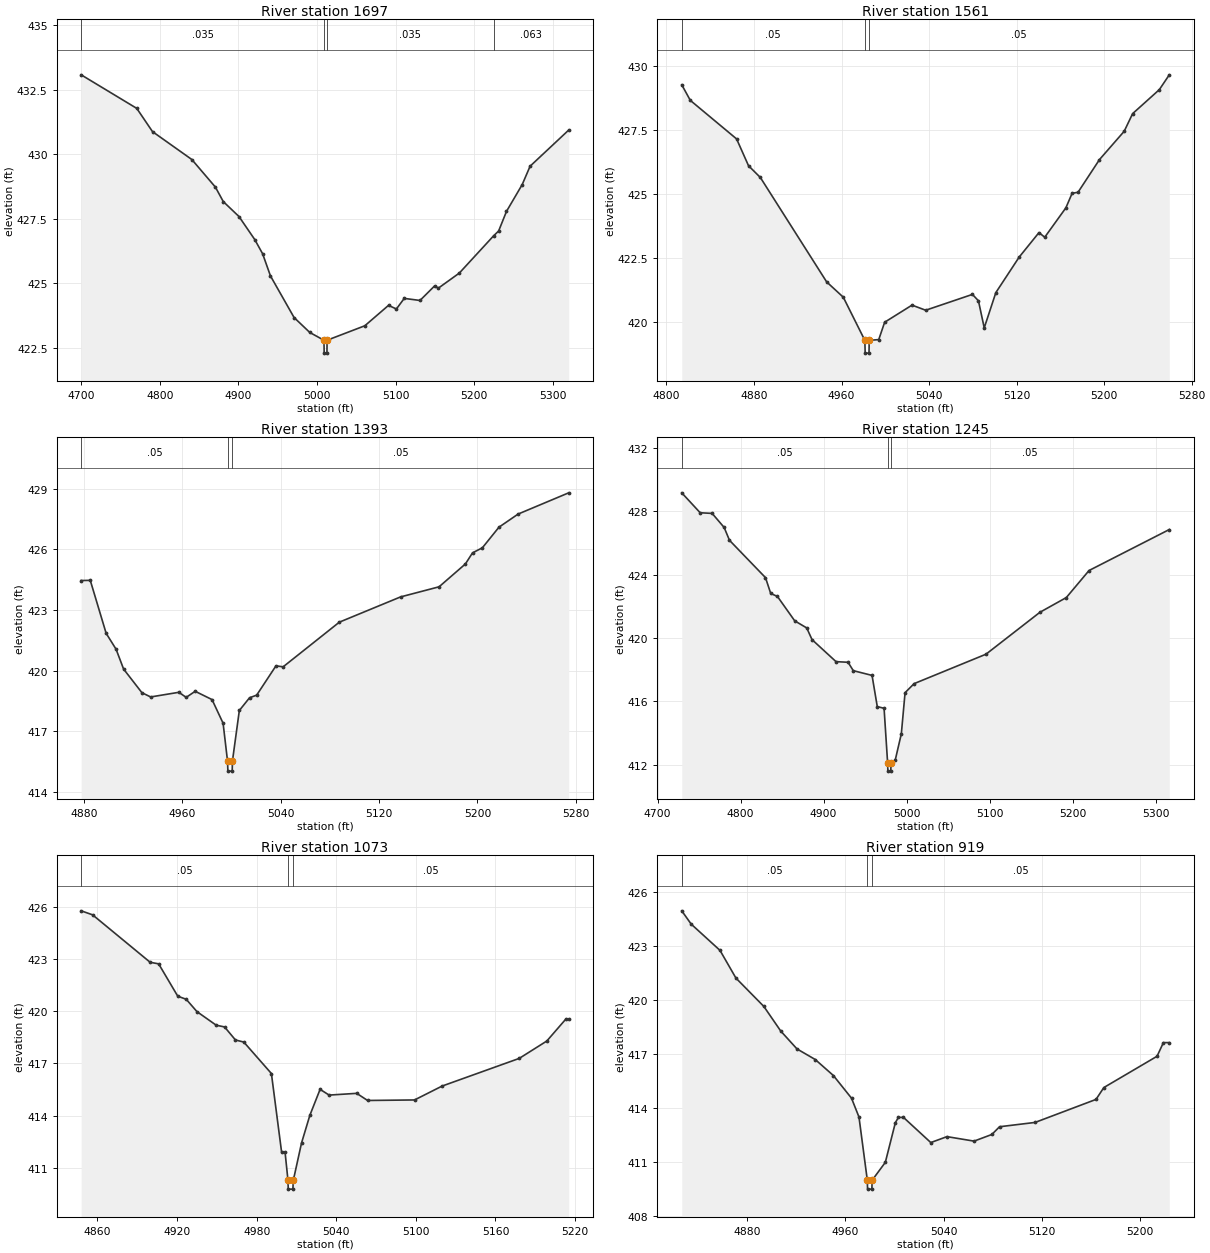
Type RM Length L Ch R = 1,1697,136,136,136
BEGIN DESCRIPTION:
Dry Creek Trib 11697.389
END DESCRIPTION:
XS GIS Cut Line= 3
      2733526.72      6839948.74      2733226.82      6839950.54
      2732906.96      6839941.04
#Sta/Elev= 30
  4700.1  433.08  4770.8  431.78  4790.8  430.88  4840.8  429.80  4870.8  428.73
  4880.8  428.17  4900.8  427.59  4920.8  426.70  4930.8  426.15  4940.8  425.29
  4970.8  423.68  4990.8  423.10  5008.8  422.80  5009.1  422.30  5012.6  422.30
  5012.8  422.80  5060.8  423.36  5090.9  424.15  5100.9  424.01  5110.9  424.42
  5130.9  424.34  5149.4  424.90  5154.4  424.82  5180.9  425.40  5224.4  426.84
  5230.9  427.03  5240.9  427.79  5260.9  428.83  5270.9  429.54  5320.0  430.94
#Mann=4,-1,0
  4700.1   0.035       0  5008.8   0.035       0  5012.8   0.035       0
  5224.4   0.063       0
Bank Sta=5008.8,5012.8
Exp/Cntr=0.3,0.1

Type RM Length L Ch R = 1,1561,168,168,168
BEGIN DESCRIPTION:
Dry Creek Trib 11560.7
END DESCRIPTION:
XS GIS Cut Line= 3
      2733432.27      6839897.33      2733260.60      6839825.73
      2733017.43      6839735.15
#Sta/Elev= 30
  4814.0  429.28  4821.8  428.67  4864.1  427.16  4875.0  426.11  4885.8  425.65
  4946.4  421.56  4961.6  420.96  4981.3  419.27  4981.6  418.77  4985.1  418.77
  4985.3  419.27  4994.0  419.30  4999.4  419.98  5024.4  420.65  5036.9  420.45
  5079.6  421.07  5085.1  420.82  5090.4  419.76  5101.0  421.14  5122.3  422.53
  5140.4  423.49  5145.7  423.31  5165.0  424.46  5170.7  425.03  5176.1  425.07
  5195.7  426.35  5218.3  427.46  5226.0  428.15  5250.4  429.09  5259.5  429.67
#Mann=3,-1,0
  4814.0    0.05       0  4981.3    0.05       0  4985.3    0.05       0
Bank Sta=4981.3,4985.3
Exp/Cntr=0.3,0.1

Type RM Length L Ch R = 1,1393,148,148,148
BEGIN DESCRIPTION:
Dry Creek Trib 11392.88
END DESCRIPTION:
XS GIS Cut Line= 3
      2733392.85      6839763.06      2733291.60      6839694.85
      2733055.55      6839555.09
#Sta/Elev= 30
  4877.8  424.46  4885.2  424.47  4898.1  421.85  4906.2  421.06  4912.3  420.08
  4927.2  418.91  4934.3  418.70  4957.2  418.93  4963.2  418.68  4970.5  418.98
  4984.2  418.57  4993.2  417.40  4996.8  415.53  4997.1  415.03  5000.6  415.03
  5000.8  415.53  5006.4  418.03  5014.7  418.66  5020.5  418.79  5036.2  420.24
  5042.0  420.19  5087.7  422.40  5137.5  423.65  5168.8  424.15  5190.2  425.28
  5196.0  425.83  5204.0  426.08  5217.5  427.10  5233.1  427.75  5274.2  428.80
#Mann=3,-1,0
  4877.8    0.05       0  4996.8    0.05       0  5000.8    0.05       0
Bank Sta=4996.8,5000.8
Exp/Cntr=0.3,0.1

Type RM Length L Ch R = 1,1245,172,172,172
BEGIN DESCRIPTION:
Dry Creek Trib 11244.68
END DESCRIPTION:
XS GIS Cut Line= 3
      2733628.78      6839789.42      2733413.80      6839621.54
      2733139.69      6839466.87
#Sta/Elev= 30
  4729.1  429.18  4751.3  427.92  4765.7  427.88  4780.2  426.99  4786.6  426.18
  4830.0  423.82  4836.3  422.82  4844.4  422.63  4865.2  421.09  4879.7  420.64
  4886.1  419.90  4915.0  418.51  4929.5  418.47  4935.8  417.94  4958.4  417.64
  4964.7  415.67  4972.9  415.56  4977.2  412.09  4977.5  411.59  4981.0  411.59
  4981.2  412.09  4986.4  412.30  4993.7  413.95  4998.2  416.55  5009.1  417.12
  5095.7  418.98  5160.7  421.63  5192.5  422.56  5219.9  424.27  5316.6  426.86
#Mann=3,-1,0
  4729.1    0.05       0  4977.2    0.05       0  4981.2    0.05       0
Bank Sta=4977.2,4981.2
Exp/Cntr=0.3,0.1

Type RM Length L Ch R = 1,1073,154,154,154
BEGIN DESCRIPTION:
Dry Creek Trib 11073.18
END DESCRIPTION:
XS GIS Cut Line= 3
      2733675.94      6839723.22      2733581.50      6839601.97
      2733451.47      6839432.24
#Sta/Elev= 30
  4847.7  425.78  4856.3  425.55  4899.7  422.82  4906.1  422.73  4920.5  420.87
  4926.9  420.69  4935.0  419.98  4949.5  419.20  4955.8  419.10  4964.0  418.35
  4970.3  418.23  4991.1  416.42  4998.8  411.89  5001.4  411.89  5003.6  410.27
  5003.8  409.77  5007.3  409.77  5007.6  410.27  5013.8  412.42  5020.1  414.02
  5027.8  415.51  5034.6  415.18  5055.4  415.28  5063.6  414.87  5099.0  414.90
  5119.8  415.70  5177.9  417.29  5198.7  418.29  5212.9  419.54  5215.2  419.54
#Mann=3,-1,0
  4847.7    0.05       0  5003.6    0.05       0  5007.6    0.05       0
Bank Sta=5003.6,5007.6
Exp/Cntr=0.3,0.1

Type RM Length L Ch R = 1,919,170,170,170
BEGIN DESCRIPTION:
Dry Creek Trib 1918.61
END DESCRIPTION:
XS GIS Cut Line= 3
      2733791.88      6839637.28      2733690.61      6839491.98
      2733555.14      6839317.76
#Sta/Elev= 30
  4826.4  424.95  4834.1  424.21  4857.6  422.75  4870.6  421.21  4893.4  419.63
  4907.2  418.26  4920.4  417.27  4935.3  416.68  4950.1  415.79  4964.9  414.53
  4971.0  413.48  4977.8  409.97  4978.0  409.47  4981.5  409.47  4981.8  409.97
  4992.5  410.96  5000.7  413.17  5003.2  413.46  5007.3  413.46  5029.6  412.06
  5042.8  412.39  5064.9  412.14  5079.4  412.51  5085.7  412.94  5114.7  413.18
  5164.4  414.46  5170.8  415.12  5214.2  416.86  5219.4  417.62  5224.2  417.62
#Mann=3,-1,0
  4826.4    0.05       0  4977.8    0.05       0  4981.8    0.05       0
Bank Sta=4977.8,4981.8
Exp/Cntr=0.3,0.1

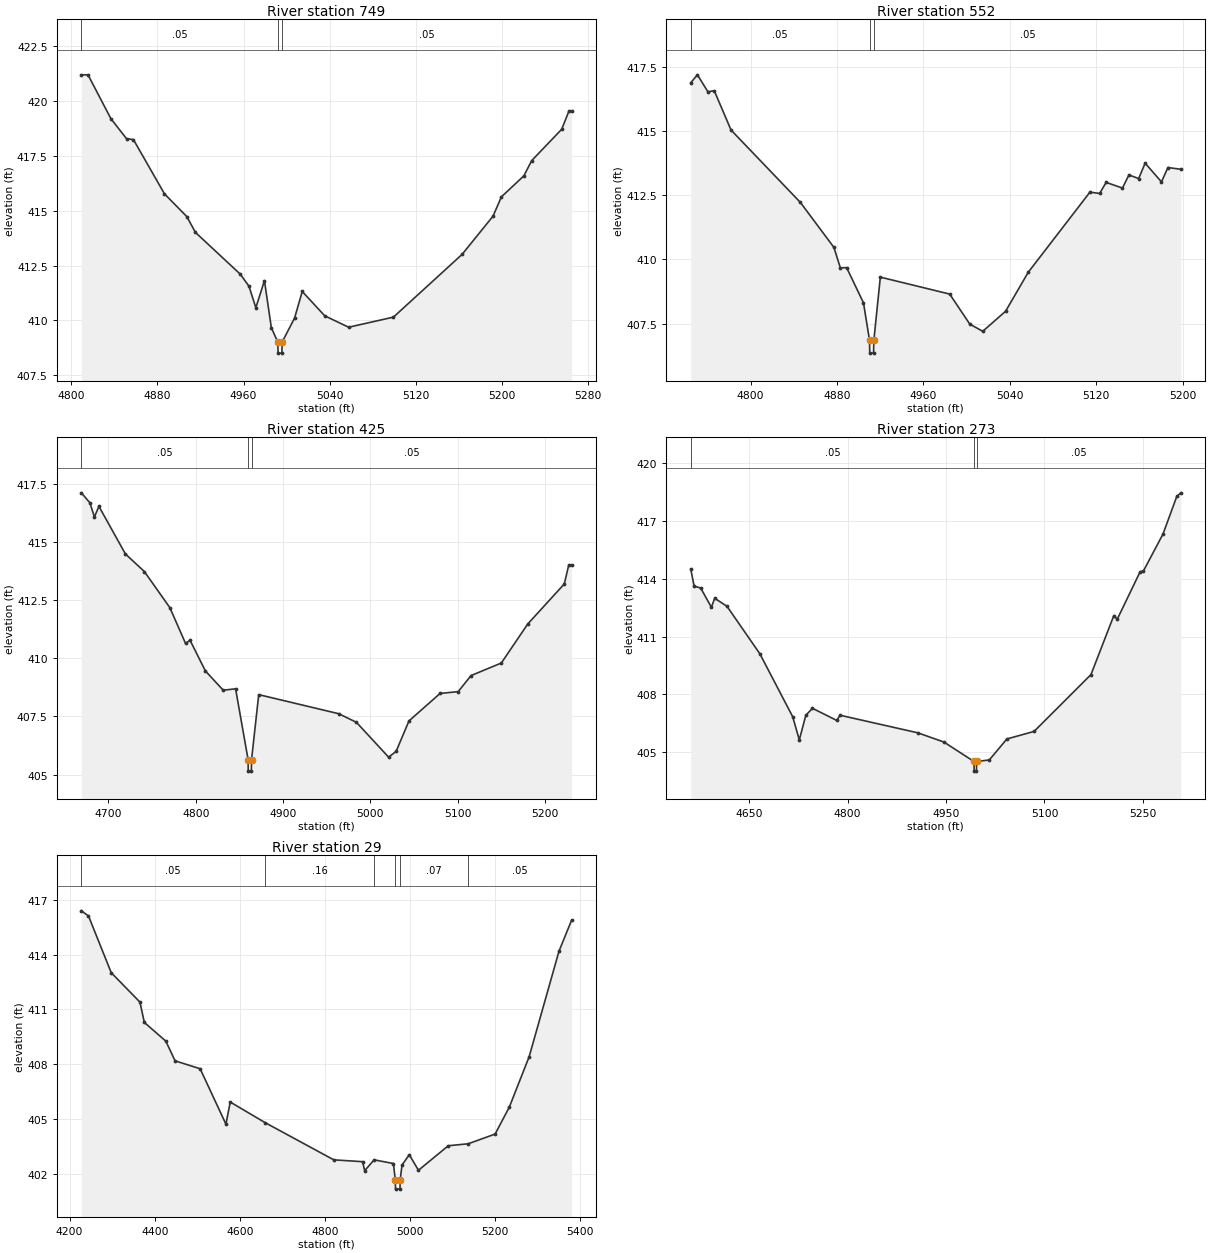
Type RM Length L Ch R = 1,749,197,197,197
BEGIN DESCRIPTION:
Dry Creek Trib 1748.52
END DESCRIPTION:
XS GIS Cut Line= 3
      2733899.62      6839505.56      2733780.14      6839355.55
      2733612.29      6839152.40
#Sta/Elev= 30
  4809.4  421.19  4815.5  421.19  4836.8  419.19  4851.3  418.28  4857.7  418.24
  4886.5  415.77  4907.3  414.73  4915.3  414.01  4956.9  412.11  4965.0  411.56
  4971.4  410.58  4979.4  411.81  4985.8  409.67  4991.8  409.01  4992.1  408.51
  4995.6  408.51  4995.8  409.01  5007.4  410.11  5014.5  411.32  5035.4  410.21
  5057.6  409.69  5099.2  410.15  5163.0  413.01  5191.7  414.75  5199.5  415.63
  5220.4  416.59  5227.6  417.28  5255.5  418.71  5262.3  419.55  5264.7  419.55
#Mann=3,-1,0
  4809.4    0.05       0  4991.8    0.05       0  4995.8    0.05       0
Bank Sta=4991.8,4995.8
Exp/Cntr=0.3,0.1

Type RM Length L Ch R = 1,552,127,127,127
BEGIN DESCRIPTION:
Dry Creek Trib 1552.49
END DESCRIPTION:
XS GIS Cut Line= 3
      2733962.12      6839424.75      2733829.65      6839203.02
      2733721.47      6839040.29
#Sta/Elev= 30
  4744.6  416.88  4750.8  417.19  4760.5  416.53  4766.4  416.57  4781.9  415.04
  4846.1  412.22  4877.1  410.47  4883.1  409.67  4888.9  409.68  4904.5  408.31
  4910.1  406.85  4910.3  406.35  4913.8  406.35  4914.1  406.85  4920.1  409.31
  4984.3  408.65  5002.9  407.48  5014.9  407.20  5036.0  407.98  5057.0  409.50
  5114.1  412.62  5123.1  412.57  5129.1  413.00  5144.2  412.78  5150.2  413.29
  5159.2  413.15  5165.2  413.75  5180.3  413.02  5186.3  413.58  5198.3  413.51
#Mann=3,-1,0
  4744.6    0.05       0  4910.1    0.05       0  4914.1    0.05       0
Bank Sta=4910.1,4914.1
Exp/Cntr=0.3,0.1

Type RM Length L Ch R = 1,425,152,152,152
BEGIN DESCRIPTION:
Dry Creek Trib 1424.52
END DESCRIPTION:
XS GIS Cut Line= 3
      2733983.82      6839440.49      2733921.73      6839114.28
      2733735.71      6838979.98
#Sta/Elev= 30
  4669.0  417.12  4678.7  416.69  4683.9  416.08  4689.0  416.54  4719.4  414.49
  4741.2  413.73  4770.3  412.18  4788.3  410.64  4793.4  410.78  4811.0  409.46
  4831.4  408.63  4845.6  408.69  4859.9  405.65  4860.1  405.15  4863.6  405.15
  4863.9  405.65  4872.1  408.44  4963.7  407.62  4984.0  407.25  5020.9  405.75
  5029.5  406.00  5044.2  407.31  5079.8  408.49  5100.6  408.57  5115.3  409.26
  5150.0  409.80  5180.3  411.48  5222.1  413.20  5227.2  414.01  5230.5  414.01
#Mann=3,-1,0
  4669.0    0.05       0  4859.9    0.05       0  4863.9    0.05       0
Bank Sta=4859.9,4863.9
Exp/Cntr=0.3,0.1

Type RM Length L Ch R = 1,273,244,244,244
BEGIN DESCRIPTION:
Dry Creek Trib 1272.79
END DESCRIPTION:
XS GIS Cut Line= 3
      2734022.71      6839426.20      2733999.95      6838990.57
      2733699.96      6838910.16
#Sta/Elev= 30
  4561.1  414.51  4566.3  413.62  4576.3  413.52  4592.6  412.52  4597.6  412.99
  4616.4  412.57  4666.4  410.11  4716.5  406.84  4726.5  405.64  4736.5  406.92
  4746.6  407.28  4783.6  406.65  4788.6  406.92  4906.8  406.01  4946.8  405.53
  4992.6  404.52  4992.9  404.02  4996.4  404.02  4996.6  404.52  5016.0  404.60
  5042.8  405.69  5084.2  406.08  5170.9  409.03  5205.7  412.09  5210.9  411.90
  5245.7  414.36  5250.9  414.41  5280.6  416.32  5301.7  418.28  5307.9  418.46
#Mann=3,-1,0
  4561.1    0.05       0  4992.6    0.05       0  4996.6    0.05       0
Bank Sta=4992.6,4996.6
Exp/Cntr=0.3,0.1

Type RM Length L Ch R = 1,29,0,0,0
BEGIN DESCRIPTION:
Dry Creek Trib 129.435
END DESCRIPTION:
XS GIS Cut Line= 3
      2734051.88      6839597.42      2734155.60      6838832.22
      2733776.34      6838822.04
#Sta/Elev= 30
  4227.8  416.39  4244.4  416.11  4297.8  413.01  4365.3  411.40  4375.6  410.29
  4426.0  409.27  4447.9  408.19  4506.7  407.76  4567.3  404.73  4577.4  405.94
  4658.9  404.82  4820.7  402.78  4888.2  402.68  4893.3  402.19  4915.4  402.78
  4960.8  402.58  4965.2  401.68  4965.7  401.18  4976.2  401.18  4976.7  401.68
  4981.0  402.50  4998.1  403.06  5019.6  402.21  5089.6  403.55  5136.7  403.66
  5199.7  404.19  5233.2  405.67  5279.7  408.42  5349.7  414.18  5379.4  415.88
#Mann=6,-1,0
  4227.8    0.05       0  4658.9    0.16       0  4915.4    0.07       0
  4965.2    0.07       0  4976.7    0.07       0  5136.7    0.05       0
Bank Sta=4965.2,4976.7
Exp/Cntr=0.3,0.1

Chan Stop Cuts=-1