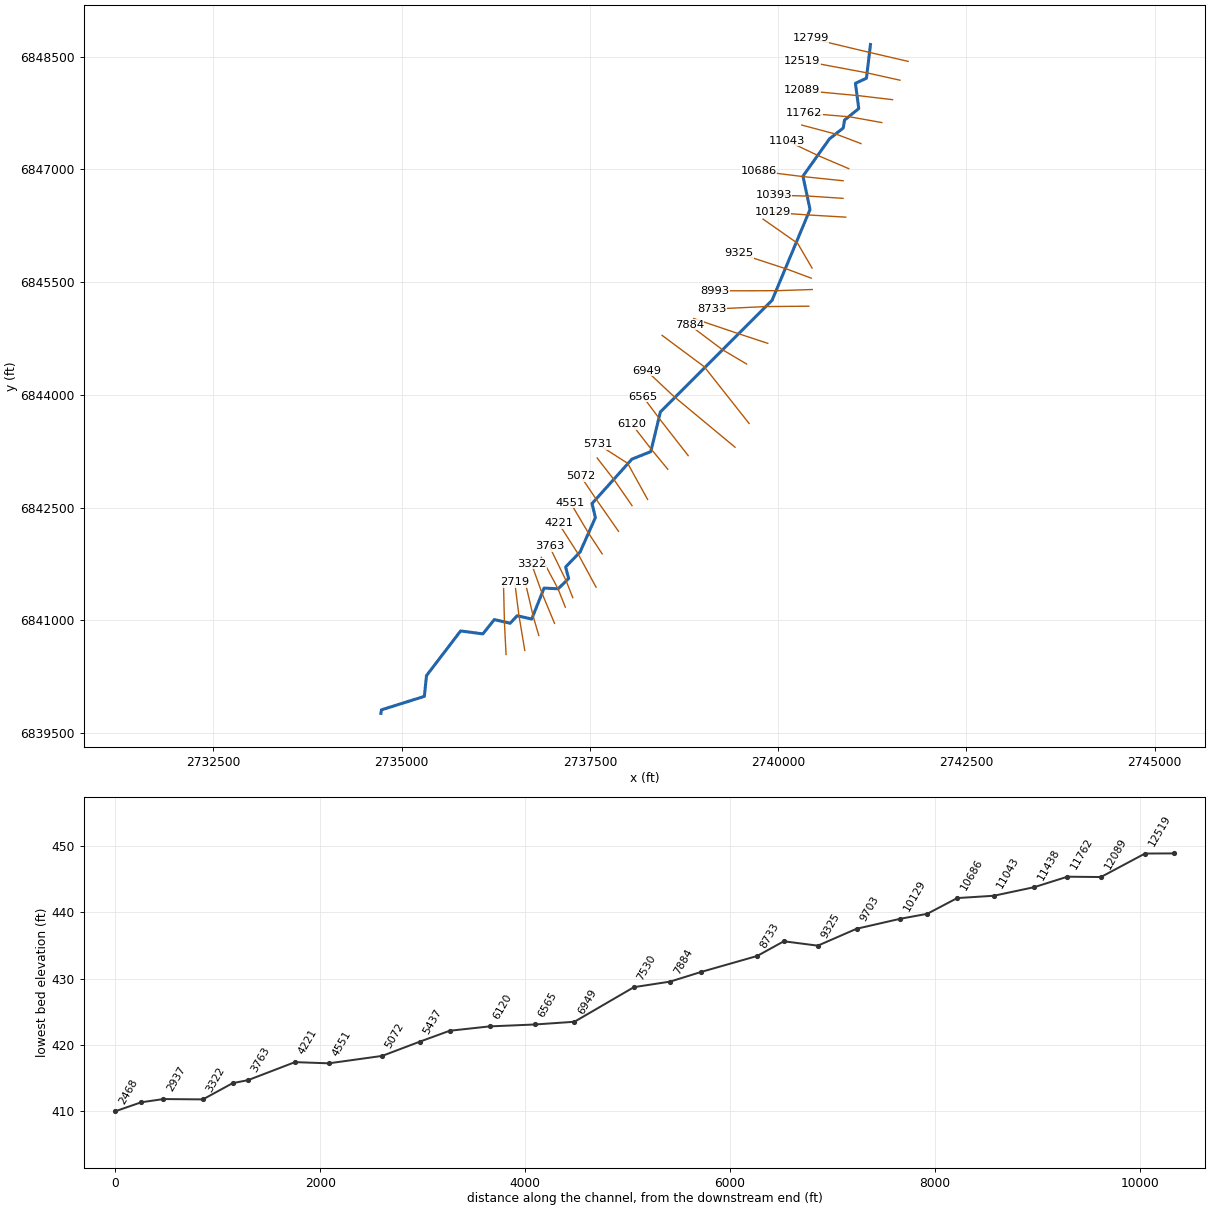
--- Dry Creek Trib A.prj (project) ---

Proj Title=Dry Creek Trib A Base Level Engineering
Current Plan=p01
Default Exp/Contr=0.3,0.1
English Units
Geom File=g01
Flow File=f01
Plan File=p01
BEGIN DESCRIPTION:
Dry Creek Trib A
END DESCRIPTION:

--- Dry Creek Trib A.p01 (plan) ---

Plan Title=Multiple Run
Short Identifier=Multiple
Geom File=g01
Flow File=f01
Subcritical Flow
K Sum by GR= 0
Std Step Tol= 0.01
Critical Tol= 0.01
Num of Std Step Trials= 20
Max Error Tol= 0.3
Flow Tol Ratio= 0.001
Split Flow NTrial= 30
Split Flow Tol= 0.02
Split Flow Ratio= 0.02
Log Output Level= 0
Friction Slope Method= 1
Unsteady Friction Slope Method= 2
Unsteady Bridges Friction Slope Method= 1
Parabolic Critical Depth
Global Vel Dist=  1 , 1 , 1
Global Log Level= 0
CheckData=True
Encroach Param= -1, 0, 0, 0
BEGIN DESCRIPTION:
Multiple Run
END DESCRIPTION:

--- Dry Creek Trib A.f01 (steady flow) ---

Flow Title=Multiple
Number of Profiles=7
Profile Names=10-year,25-year,50-year,1pct_min,100-year,1pct_plu,500-year
River Rch & RM= Dry Creek Trib A,Reach-1,12799
     510     675     808     480     957    1910    1348
River Rch & RM= Dry Creek Trib A,Reach-1,9703
     868    1168    1411     844    1683    3359    2395
Boundary for River Rch & Prof#=Dry Creek Trib A,Reach-1,1
Up Type=0
Dn Type=3
Dn Slope=0.005
Boundary for River Rch & Prof#=Dry Creek Trib A,Reach-1,2
Up Type=0
Dn Type=3
Dn Slope=0.005
Boundary for River Rch & Prof#=Dry Creek Trib A,Reach-1,3
Up Type=0
Dn Type=3
Dn Slope=0.005
Boundary for River Rch & Prof#=Dry Creek Trib A,Reach-1,4
Up Type=0
Dn Type=3
Dn Slope=0.005
Boundary for River Rch & Prof#=Dry Creek Trib A,Reach-1,5
Up Type=0
Dn Type=3
Dn Slope=0.005
Boundary for River Rch & Prof#=Dry Creek Trib A,Reach-1,6
Up Type=0
Dn Type=3
Dn Slope=0.005
Boundary for River Rch & Prof#=Dry Creek Trib A,Reach-1,7
Up Type=0
Dn Type=3
Dn Slope=0.005

--- Dry Creek Trib A.g01 (geometry) ---

Geom Title=Existing Conditions

River Reach=Dry Creek Trib A,Reach-1
Reach XY= 30
      2741226.00      6848661.00      2741172.56      6848212.22
      2741026.42      6848145.36      2741070.54      6847808.55
      2740881.26      6847655.53      2740865.47      6847551.25
      2740681.59      6847405.39      2740329.47      6846909.50
      2740423.65      6846466.52      2739920.17      6845258.70
      2738436.47      6843770.82      2738309.55      6843243.87
      2738059.32      6843144.36      2737529.16      6842552.94
      2737574.06      6842366.71      2737370.48      6841908.57
      2737179.13      6841709.37      2737218.52      6841554.94
      2737079.42      6841418.80      2736892.44      6841428.15
      2736728.71      6841016.28      2736535.63      6841060.29
      2736441.53      6840960.33      2736231.62      6841009.27
      2736079.67      6840818.69      2735784.28      6840857.94
      2735331.47      6840263.45      2735303.16      6839987.42
      2734733.45      6839808.02      2734726.00      6839761.00

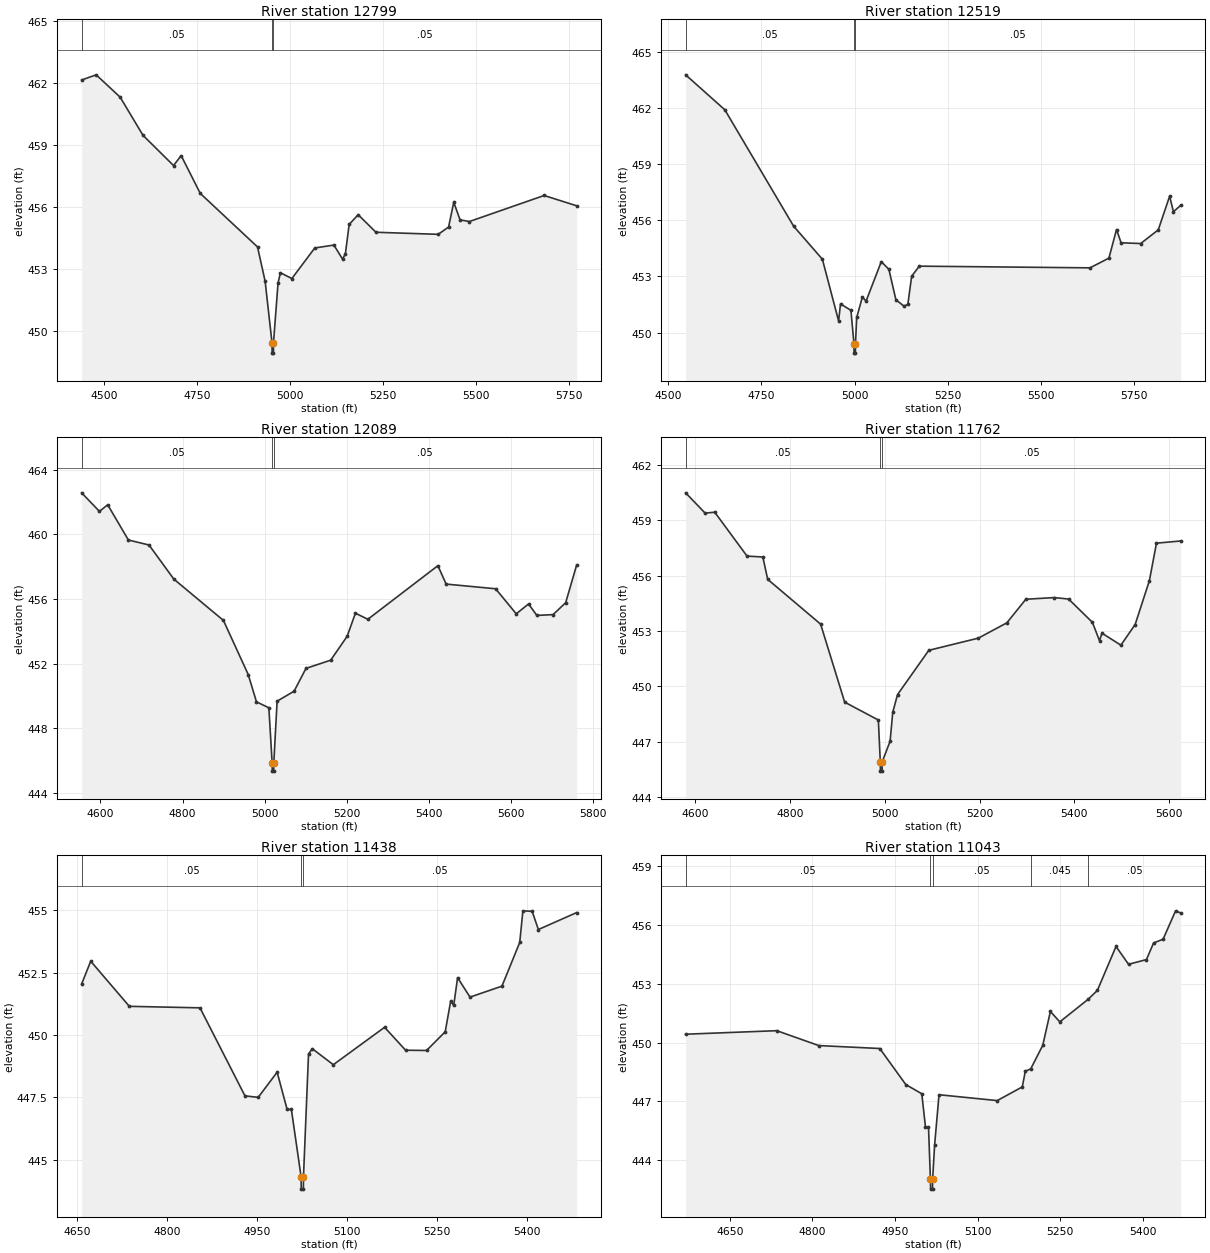
Type RM Length L Ch R = 1,12799,280,280,280
BEGIN DESCRIPTION:
Dry Creek Trib A12799.041
END DESCRIPTION:
XS GIS Cut Line= 3
      2741726.79      6848436.65      2741181.53      6848563.42
      2740430.81      6848743.42
#Sta/Elev= 30
  4440.2  462.14  4479.2  462.39  4543.7  461.31  4605.3  459.46  4687.4  458.00
  4707.9  458.48  4759.3  456.65  4913.3  454.06  4933.8  452.40  4952.3  449.42
  4952.6  448.92  4956.1  448.92  4956.3  449.42  4968.5  452.31  4974.9  452.81
  5005.7  452.53  5067.4  454.01  5118.8  454.15  5142.1  453.47  5149.7  453.73
  5159.9  455.15  5184.1  455.62  5231.9  454.77  5399.3  454.67  5427.3  455.02
  5441.3  456.22  5458.2  455.37  5483.4  455.29  5684.4  456.55  5772.0  456.05
#Mann=3,-1,0
  4440.2    0.05       0  4952.3    0.05       0  4956.3    0.05       0
Bank Sta=4952.3,4956.3
Exp/Cntr=0.3,0.1

Type RM Length L Ch R = 1,12519,430,430,430
BEGIN DESCRIPTION:
Dry Creek Trib A12519.48
END DESCRIPTION:
XS GIS Cut Line= 3
      2741618.56      6848186.08      2741169.70      6848286.20
      2740316.93      6848445.99
#Sta/Elev= 30
  4546.8  463.78  4651.9  461.91  4836.3  455.69  4913.5  453.92  4957.0  450.62
  4962.1  451.53  4990.0  451.19  4998.2  449.40  4998.5  448.90  5002.0  448.90
  5002.2  449.40  5005.6  450.81  5020.6  451.89  5030.8  451.69  5071.5  453.79
  5091.8  453.38  5110.7  451.75  5132.5  451.41  5142.7  451.51  5152.9  453.01
  5173.4  453.55  5631.1  453.46  5681.9  453.98  5702.3  455.51  5714.5  454.80
  5767.1  454.76  5814.2  455.49  5844.7  457.29  5854.9  456.46  5874.3  456.80
#Mann=3,-1,0
  4546.8    0.05       0  4998.2    0.05       0  5002.2    0.05       0
Bank Sta=4998.2,5002.2
Exp/Cntr=0.3,0.1

Type RM Length L Ch R = 1,12089,327,327,327
BEGIN DESCRIPTION:
Dry Creek Trib A12089.2
END DESCRIPTION:
XS GIS Cut Line= 3
      2741518.99      6847927.39      2741080.08      6847979.27
      2740319.32      6848050.98
#Sta/Elev= 30
  4554.3  462.58  4597.6  461.43  4617.7  461.84  4668.1  459.66  4718.4  459.35
  4778.8  457.24  4899.7  454.68  4960.1  451.33  4980.2  449.64  5010.4  449.27
  5018.4  445.85  5018.7  445.35  5022.2  445.35  5022.4  445.85  5030.5  449.68
  5071.9  450.30  5100.8  451.71  5161.1  452.22  5201.2  453.70  5221.3  455.13
  5251.5  454.75  5422.2  458.07  5442.3  456.93  5562.8  456.64  5613.1  455.09
  5643.2  455.70  5663.3  454.99  5702.9  455.04  5733.6  455.78  5760.4  458.12
#Mann=3,-1,0
  4554.3    0.05       0  5018.4    0.05       0  5022.4    0.05       0
Bank Sta=5018.4,5022.4
Exp/Cntr=0.3,0.1

Type RM Length L Ch R = 1,11762,324,324,324
BEGIN DESCRIPTION:
Dry Creek Trib A11761.92
END DESCRIPTION:
XS GIS Cut Line= 3
      2741376.47      6847622.66      2740951.63      6847699.12
      2740340.23      6847750.27
#Sta/Elev= 30
  4579.4  460.49  4620.5  459.39  4640.8  459.44  4709.0  457.06  4742.4  457.01
  4752.6  455.80  4864.4  453.37  4915.2  449.14  4986.3  448.17  4990.4  445.90
  4990.7  445.40  4994.2  445.40  4994.4  445.90  5011.1  447.02  5016.7  448.59
  5026.8  449.55  5092.8  451.95  5197.3  452.61  5257.6  453.44  5297.7  454.72
  5357.9  454.81  5388.0  454.73  5438.2  453.47  5453.3  452.47  5458.4  452.88
  5498.4  452.23  5528.5  453.35  5558.6  455.73  5573.5  457.76  5624.6  457.88
#Mann=3,-1,0
  4579.4    0.05       0  4990.4    0.05       0  4994.4    0.05       0
Bank Sta=4990.4,4994.4
Exp/Cntr=0.3,0.1

Type RM Length L Ch R = 1,11438,395,395,395
BEGIN DESCRIPTION:
Dry Creek Trib A11438.14
END DESCRIPTION:
XS GIS Cut Line= 3
      2741100.15      6847342.77      2740779.96      6847465.03
      2740314.33      6847589.02
#Sta/Elev= 30
  4657.5  452.05  4672.6  452.96  4736.9  451.15  4854.6  451.09  4929.5  447.56
  4951.6  447.50  4983.1  448.51  4999.7  447.02  5006.8  447.02  5023.0  444.32
  5023.3  443.82  5026.8  443.82  5027.0  444.32  5035.4  449.24  5041.7  449.45
  5076.7  448.81  5162.1  450.31  5197.1  449.39  5232.0  449.38  5263.1  450.13
  5272.1  451.35  5277.3  451.19  5283.7  452.30  5304.4  451.52  5357.6  451.96
  5387.2  453.71  5392.5  454.98  5407.9  454.96  5418.3  454.23  5482.1  454.91
#Mann=3,-1,0
  4657.5    0.05       0  5023.0    0.05       0  5027.0    0.05       0
Bank Sta=5023,5027
Exp/Cntr=0.3,0.1

Type RM Length L Ch R = 1,11043,357,357,357
BEGIN DESCRIPTION:
Dry Creek Trib A11042.84
END DESCRIPTION:
XS GIS Cut Line= 3
      2740938.47      6847009.00      2740535.56      6847181.25
      2740119.93      6847378.63
#Sta/Elev= 30
  4570.0  450.43  4735.4  450.61  4811.6  449.85  4922.3  449.70  4969.5  447.86
  4998.5  447.39  5005.2  445.70  5010.7  445.70  5014.2  443.02  5014.5  442.52
  5018.0  442.52  5018.2  443.02  5021.8  444.77  5029.8  447.34  5135.4  447.04
  5180.9  447.74  5186.4  448.54  5196.2  448.66  5218.0  449.86  5231.9  451.59
  5249.0  451.06  5300.7  452.22  5317.2  452.67  5351.0  454.91  5373.7  454.00
  5406.2  454.24  5419.2  455.09  5436.4  455.28  5459.1  456.73  5468.3  456.62
#Mann=5,-1,0
  4570.0    0.05       0  5014.2    0.05       0  5018.2    0.05       0
  5196.2   0.045       0  5300.7    0.05       0
Bank Sta=5014.2,5018.2
Exp/Cntr=0.3,0.1

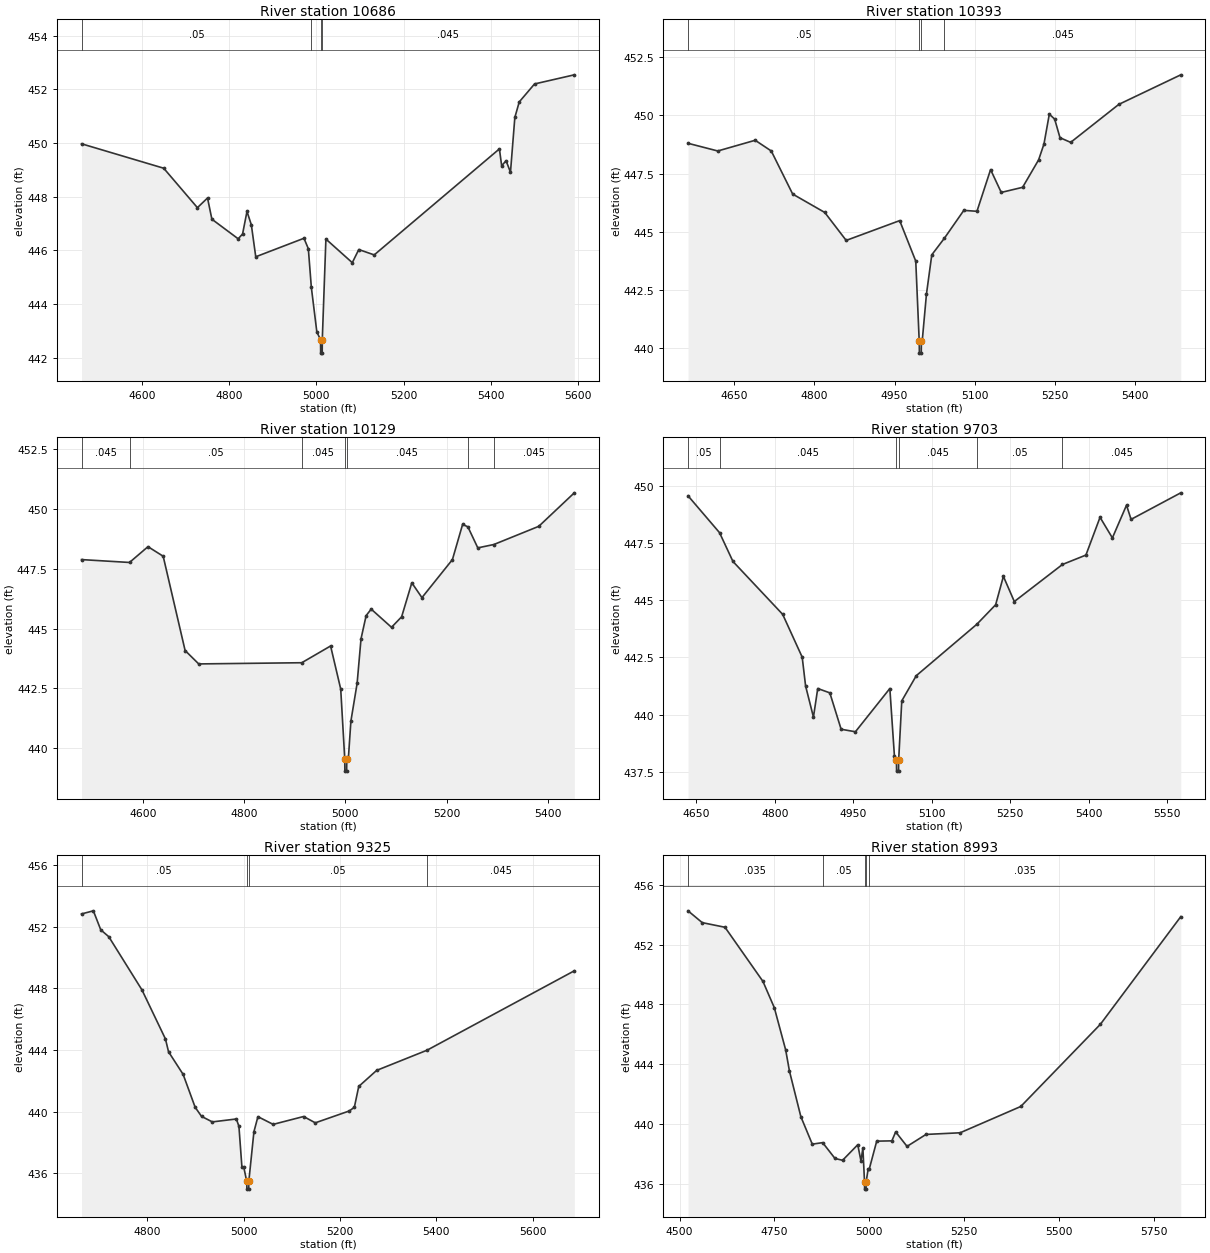
Type RM Length L Ch R = 1,10686,293,293,293
BEGIN DESCRIPTION:
Dry Creek Trib A10685.94
END DESCRIPTION:
XS GIS Cut Line= 3
      2740863.34      6846848.27      2740322.24      6846904.64
      2739740.69      6846977.33
#Sta/Elev= 30
  4461.5  449.97  4649.9  449.06  4727.2  447.59  4750.4  447.95  4760.4  447.16
  4820.7  446.43  4830.8  446.61  4840.9  447.45  4850.9  446.95  4861.0  445.76
  4971.6  446.45  4981.6  446.06  4988.5  444.62  5001.1  442.96  5009.6  442.67
  5009.9  442.17  5013.4  442.17  5013.6  442.67  5021.9  446.42  5082.4  445.54
  5097.3  446.03  5132.7  445.83  5419.8  449.78  5425.0  449.15  5435.1  449.34
  5445.2  448.91  5455.2  450.95  5465.3  451.53  5500.4  452.20  5591.6  452.54
#Mann=4,-1,0
  4461.5    0.05       0  4988.5   0.045       0  5009.6   0.045       0
  5013.6   0.045       0
Bank Sta=5009.6,5013.6
Exp/Cntr=0.3,0.1

Type RM Length L Ch R = 1,10393,264,264,264
BEGIN DESCRIPTION:
Dry Creek Trib A10392.76
END DESCRIPTION:
XS GIS Cut Line= 3
      2740861.56      6846614.43      2740423.95      6846642.97
      2739939.91      6846657.36
#Sta/Elev= 30
  4563.3  448.80  4619.0  448.47  4689.1  448.93  4719.2  448.47  4759.3  446.62
  4819.4  445.83  4859.5  444.63  4959.7  445.48  4989.8  443.74  4996.3  440.29
  4996.6  439.79  5000.1  439.79  5000.3  440.29  5001.8  440.29  5009.8  442.32
  5019.8  444.01  5043.3  444.72  5079.8  445.92  5104.4  445.88  5129.9  447.67
  5149.9  446.69  5189.9  446.91  5219.9  448.09  5229.9  448.77  5239.9  450.05
  5249.9  449.84  5259.9  449.04  5279.9  448.84  5370.0  450.47  5486.1  451.74
#Mann=4,-1,0
  4563.3    0.05       0  4996.3    0.05       0  5000.3    0.05       0
  5043.3   0.045       0
Bank Sta=4996.3,5000.3
Exp/Cntr=0.3,0.1

Type RM Length L Ch R = 1,10129,426,426,426
BEGIN DESCRIPTION:
Dry Creek Trib A10128.66
END DESCRIPTION:
XS GIS Cut Line= 3
      2740896.96      6846364.16      2740371.10      6846394.93
      2739925.96      6846427.63
#Sta/Elev= 30
  4479.0  447.88  4573.7  447.76  4610.2  448.42  4640.2  448.02  4683.5  444.08
  4710.4  443.52  4913.9  443.57  4970.8  444.27  4990.8  442.47  4998.8  439.54
  4999.0  439.04  5002.5  439.04  5002.8  439.54  5005.8  439.54  5010.9  441.13
  5023.2  442.71  5030.9  444.57  5041.0  445.54  5051.0  445.81  5091.1  445.05
  5111.1  445.49  5131.2  446.91  5151.2  446.29  5211.4  447.88  5231.5  449.35
  5241.9  449.25  5261.5  448.37  5293.2  448.51  5381.9  449.27  5452.1  450.67
#Mann=7,-1,0
  4479.0   0.045       0  4573.7    0.05       0  4913.9   0.045       0
  4998.8   0.045       0  5002.8   0.045       0  5241.9    0.05       0
  5293.2   0.045       0
Bank Sta=4998.8,5002.8
Exp/Cntr=0.3,0.1

Type RM Length L Ch R = 1,9703,378,378,378
BEGIN DESCRIPTION:
Dry Creek Trib A9702.92
END DESCRIPTION:
XS GIS Cut Line= 3
      2740450.39      6845686.79      2740258.96      6846015.59
      2739799.60      6846338.04
#Sta/Elev= 30
  4634.2  449.56  4694.4  447.95  4720.1  446.69  4815.1  444.38  4852.4  442.51
  4858.9  441.25  4873.9  439.89  4882.1  441.14  4905.2  440.95  4926.8  439.36
  4954.1  439.25  5019.9  441.14  5028.6  438.21  5032.5  438.03  5032.8  437.53
  5036.5  437.53  5036.8  438.03  5042.7  440.60  5070.4  441.70  5186.3  443.95
  5222.1  444.80  5236.9  446.04  5257.8  444.94  5349.8  446.56  5394.6  446.97
  5421.6  448.62  5445.2  447.72  5472.2  449.15  5480.9  448.53  5575.9  449.69
#Mann=6,-1,0
  4634.2    0.05       0  4694.4   0.045       0  5032.5   0.045       0
  5036.8   0.045       0  5186.3    0.05       0  5349.8   0.045       0
Bank Sta=5032.5,5036.8
Exp/Cntr=0.3,0.1

Type RM Length L Ch R = 1,9325,332,332,332
BEGIN DESCRIPTION:
Dry Creek Trib A9324.97
END DESCRIPTION:
XS GIS Cut Line= 3
      2740438.94      6845552.28      2740123.97      6845670.35
      2739472.58      6845884.31
#Sta/Elev= 30
  4664.1  452.83  4688.6  453.03  4703.9  451.80  4720.6  451.35  4789.4  447.90
  4838.1  444.72  4844.5  443.89  4874.8  442.42  4899.7  440.29  4912.9  439.70
  4935.3  439.34  4985.2  439.53  4990.5  439.05  4996.7  436.41  5000.5  436.41
  5006.7  435.48  5007.0  434.98  5010.8  434.98  5011.0  435.48  5021.6  438.70
  5029.9  439.68  5061.5  439.18  5124.6  439.69  5148.9  439.28  5219.4  440.05
  5229.9  440.29  5239.0  441.64  5276.1  442.68  5380.7  443.99  5686.1  449.14
#Mann=4,-1,0
  4664.1    0.05       0  5006.7    0.05       0  5011.0    0.05       0
  5380.7   0.045       0
Bank Sta=5006.7,5011
Exp/Cntr=0.3,0.1

Type RM Length L Ch R = 1,8993,260,260,260
BEGIN DESCRIPTION:
Dry Creek Trib A8993.31
END DESCRIPTION:
XS GIS Cut Line= 3
      2740453.49      6845401.11      2739976.52      6845385.42
      2739154.05      6845383.17
#Sta/Elev= 30
  4522.2  454.26  4559.7  453.47  4619.7  453.16  4719.8  449.54  4749.8  447.78
  4779.8  444.95  4789.8  443.53  4819.8  440.49  4849.9  438.65  4877.3  438.75
  4909.9  437.69  4929.9  437.57  4969.9  438.61  4978.4  437.52  4983.4  438.40
  4987.7  436.14  4988.0  435.64  4991.8  435.64  4992.1  436.14  4997.2  436.97
  5000.1  436.97  5019.9  438.85  5059.9  438.87  5069.9  439.47  5099.9  438.50
  5149.9  439.30  5239.9  439.41  5399.9  441.17  5609.9  446.67  5821.9  453.87
#Mann=5,-1,0
  4522.2   0.035       0  4877.3    0.05       0  4987.7    0.05       0
  4992.1    0.05       0  5000.1   0.035       0
Bank Sta=4987.7,4992.1
Exp/Cntr=0.3,0.1

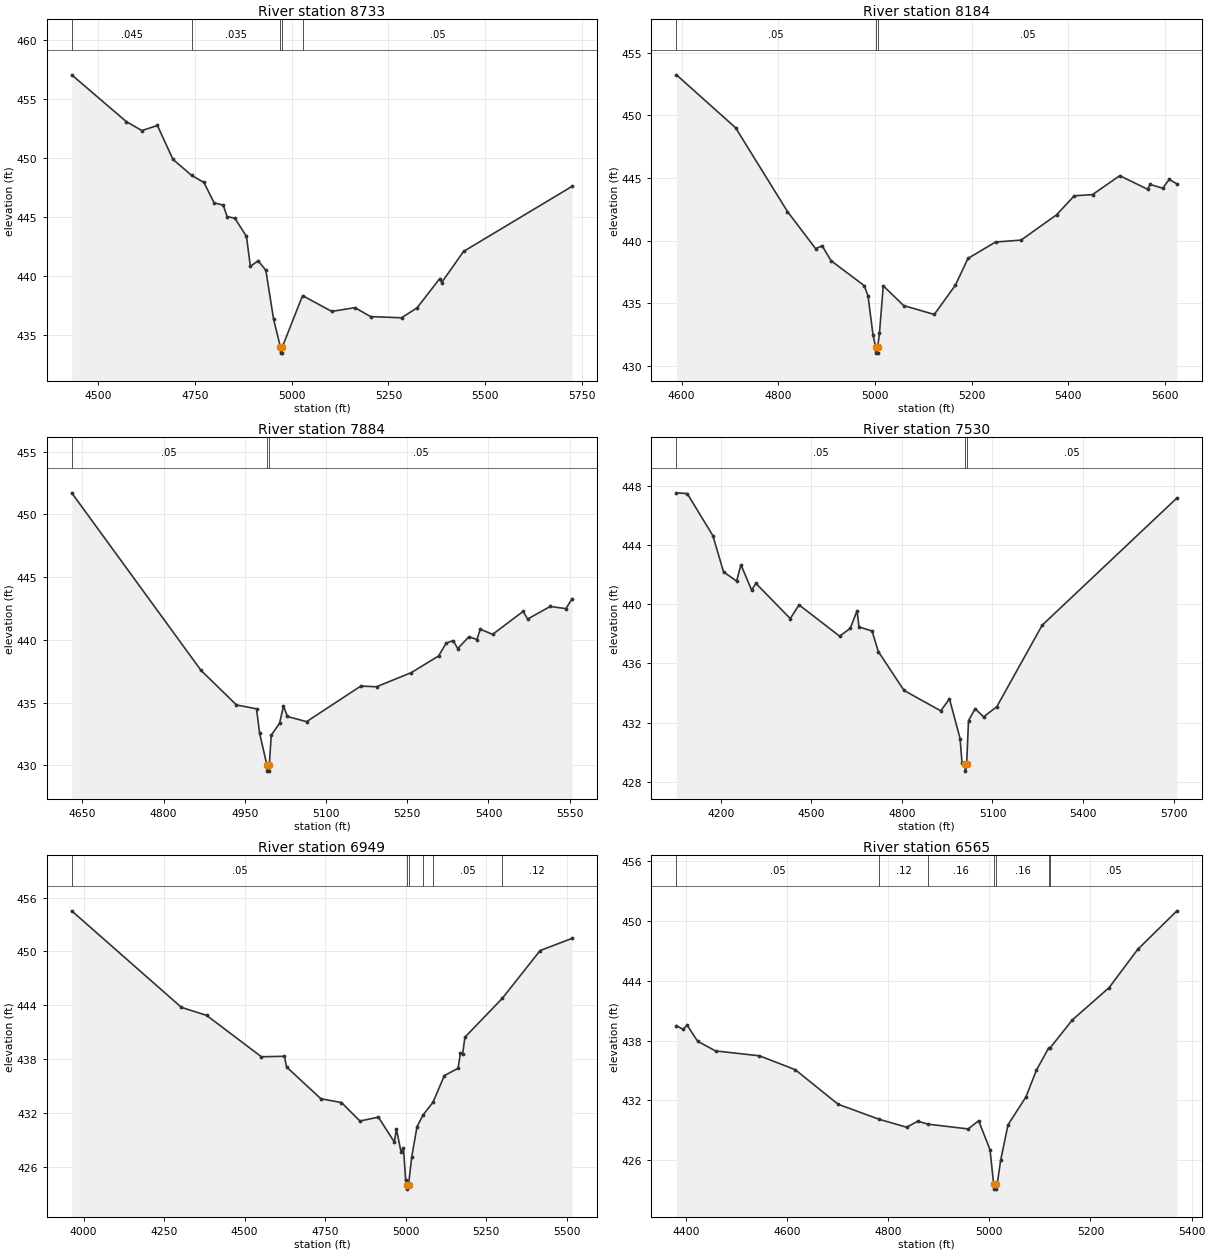
Type RM Length L Ch R = 1,8733,549,549,549
BEGIN DESCRIPTION:
Dry Creek Trib A8733.09
END DESCRIPTION:
XS GIS Cut Line= 3
      2740407.42      6845179.21      2739834.66      6845174.23
      2739115.76      6845139.81
#Sta/Elev= 30
  4431.9  457.04  4573.3  453.06  4613.3  452.31  4653.3  452.74  4693.3  449.87
  4741.8  448.50  4773.3  447.91  4799.7  446.18  4823.3  445.98  4833.3  445.01
  4853.3  444.87  4883.3  443.32  4893.3  440.78  4913.3  441.26  4933.3  440.45
  4953.3  436.29  4971.1  433.92  4971.4  433.42  4975.3  433.42  4975.6  433.92
  5028.1  438.30  5103.5  436.96  5163.5  437.28  5203.6  436.52  5283.7  436.42
  5323.7  437.26  5382.3  439.74  5387.3  439.41  5443.8  442.05  5724.4  447.58
#Mann=5,-1,0
  4431.9   0.045       0  4741.8   0.035       0  4971.1   0.035       0
  4975.6   0.035       0  5028.1    0.05       0
Bank Sta=4971.1,4975.6
Exp/Cntr=0.3,0.1

Type RM Length L Ch R = 1,8184,300,300,300
BEGIN DESCRIPTION:
Dry Creek Trib A8184.23
END DESCRIPTION:
XS GIS Cut Line= 3
      2739862.19      6844684.76      2739466.84      6844815.64
      2738880.74      6845014.60
#Sta/Elev= 30
  4589.4  453.24  4711.8  449.01  4819.2  442.31  4877.4  439.35  4890.9  439.58
  4909.1  438.39  4977.8  436.40  4985.7  435.60  4996.2  432.44  5001.4  431.50
  5001.7  431.00  5005.6  431.00  5005.9  431.50  5009.5  432.62  5017.3  436.38
  5059.5  434.80  5122.9  434.09  5166.5  436.43  5192.6  438.57  5249.6  439.88
  5302.4  440.03  5375.7  442.05  5412.4  443.57  5450.3  443.67  5506.5  445.18
  5564.0  444.10  5569.3  444.48  5595.4  444.18  5608.7  444.88  5624.8  444.53
#Mann=3,-1,0
  4589.4    0.05       0  5001.4    0.05       0  5005.9    0.05       0
Bank Sta=5001.4,5005.9
Exp/Cntr=0.3,0.1

Type RM Length L Ch R = 1,7884,354,354,354
BEGIN DESCRIPTION:
Mapping XS b7881b64
END DESCRIPTION:
XS GIS Cut Line= 3
      2739581.34      6844410.05      2739257.31      6844602.34
      2738820.39      6844931.80
#Sta/Elev= 30
  4630.5  451.71  4869.3  437.57  4934.7  434.82  4971.7  434.51  4977.5  432.56
  4990.8  430.05  4991.2  429.55  4995.1  429.55  4995.4  430.05  4998.9  432.40
  5014.3  433.37  5021.5  434.72  5028.8  433.90  5064.2  433.49  5164.2  436.32
  5193.3  436.27  5257.8  437.40  5307.8  438.72  5322.0  439.75  5334.9  439.94
  5343.2  439.31  5364.0  440.25  5378.6  440.03  5384.8  440.85  5407.7  440.44
  5463.9  442.27  5472.2  441.66  5513.9  442.66  5543.0  442.49  5554.5  443.29
#Mann=3,-1,0
  4630.5    0.05       0  4990.8    0.05       0  4995.4    0.05       0
Bank Sta=4990.8,4995.4
Exp/Cntr=0.3,0.1

Type RM Length L Ch R = 1,7530,581,581,581
BEGIN DESCRIPTION:
Dry Creek Trib A7530.38
END DESCRIPTION:
XS GIS Cut Line= 3
      2739614.26      6843619.05      2739019.05      6844373.78
      2738459.67      6844790.62
#Sta/Elev= 30
  4052.4  447.54  4088.3  447.49  4173.3  444.64  4208.5  442.19  4251.9  441.57
  4266.3  442.67  4301.6  440.96  4316.0  441.41  4429.8  439.03  4458.7  439.96
  4593.4  437.84  4628.6  438.37  4651.1  439.56  4657.5  438.47  4700.8  438.19
  4721.6  436.80  4806.6  434.17  4928.5  432.79  4957.4  433.60  4992.6  430.91
  4999.0  429.26  5009.7  429.21  5010.0  428.71  5014.4  429.21  5020.5  432.12
  5042.3  432.94  5070.5  432.38  5114.3  433.07  5264.5  438.58  5711.2  447.19
#Mann=3,-1,0
  4052.4    0.05       0  5009.7    0.05       0  5014.4    0.05       0
Bank Sta=5009.7,5014.4
Exp/Cntr=0.3,0.1

Type RM Length L Ch R = 1,6949,384,384,384
BEGIN DESCRIPTION:
Dry Creek Trib A6949.05
END DESCRIPTION:
XS GIS Cut Line= 3
      2739427.88      6843302.89      2738614.18      6843979.70
      2738253.55      6844319.23
#Sta/Elev= 30
  3963.1  454.53  4303.7  443.76  4381.8  442.87  4552.0  438.25  4623.6  438.30
  4630.1  437.11  4736.8  433.56  4800.6  433.14  4857.9  431.08  4915.1  431.51
  4964.7  428.74  4971.2  430.18  4985.5  427.63  4993.1  428.05  4999.8  424.47
  5003.9  423.98  5004.3  423.48  5008.8  423.98  5018.6  427.05  5035.1  430.44
  5053.9  431.76  5084.4  433.15  5120.1  436.15  5162.6  436.96  5169.9  438.68
  5176.8  438.56  5183.8  440.43  5299.5  444.75  5417.3  450.10  5516.8  451.46
#Mann=6,-1,0
  3963.1    0.05       0  5003.9    0.05       0  5008.8    0.05       0
  5053.9    0.12       0  5084.4    0.05       0  5299.5    0.12       0
Bank Sta=5003.9,5008.8
Exp/Cntr=0.3,0.1

Type RM Length L Ch R = 1,6565,445,445,445
BEGIN DESCRIPTION:
Dry Creek Trib A6565.25
END DESCRIPTION:
XS GIS Cut Line= 3
      2738805.54      6843191.26      2738419.14      6843688.62
      2738203.63      6843976.97
#Sta/Elev= 30
  4381.1  439.50  4394.1  439.13  4402.3  439.55  4423.1  437.93  4458.4  436.96
  4545.3  436.47  4615.9  435.08  4700.9  431.60  4781.9  430.09  4836.6  429.29
  4858.4  429.90  4878.6  429.60  4958.0  429.12  4978.8  429.94  5001.3  427.03
  5008.5  423.57  5008.8  423.07  5013.0  423.07  5013.4  423.57  5015.5  423.57
  5022.3  425.97  5036.9  429.54  5072.3  432.33  5093.2  435.04  5117.5  437.28
  5120.6  437.29  5164.0  440.07  5237.0  443.33  5293.3  447.16  5370.9  451.04
#Mann=7,-1,0
  4381.1    0.05       0  4781.9    0.12       0  4878.6    0.16       0
  5008.5    0.07       0  5013.4    0.16       0  5117.5    0.12       0
  5120.6    0.05       0
Bank Sta=5008.5,5013.4
Exp/Cntr=0.3,0.1

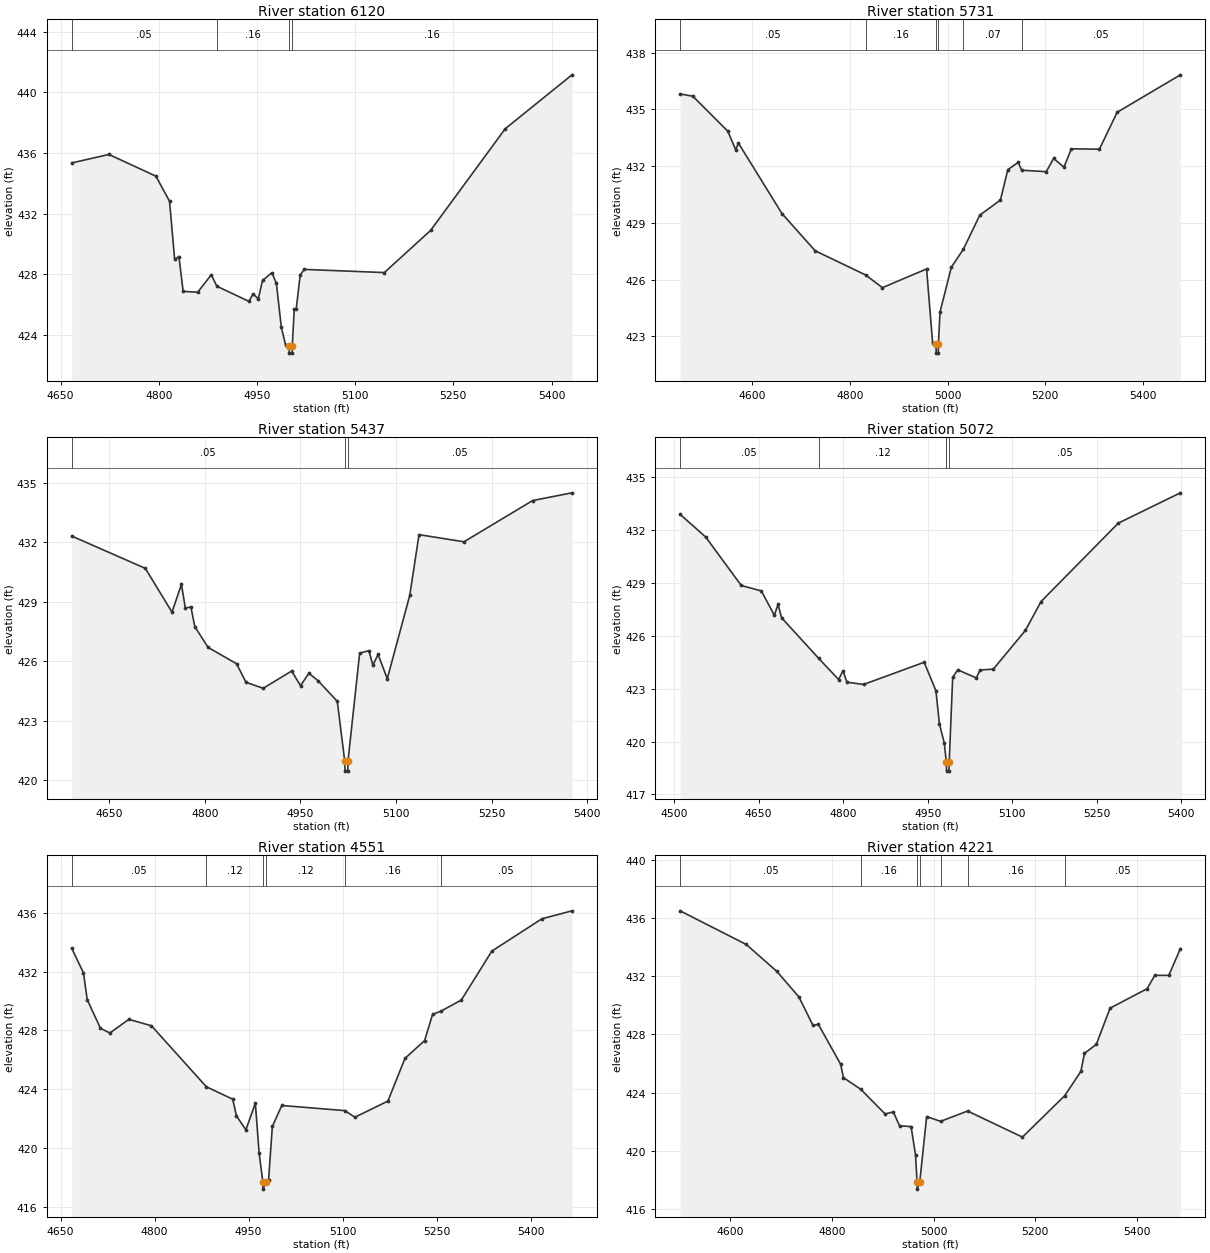
Type RM Length L Ch R = 1,6120,389,389,389
BEGIN DESCRIPTION:
Mapping XS 956859aa
END DESCRIPTION:
XS GIS Cut Line= 3
      2738535.00      6843009.42      2738317.17      6843274.40
      2738059.00      6843607.31
#Sta/Elev= 30
  4667.0  435.34  4723.9  435.90  4795.6  434.47  4816.5  432.81  4824.3  428.97
  4830.8  429.16  4837.3  426.86  4859.5  426.80  4880.3  427.96  4888.7  427.20
  4937.7  426.20  4944.2  426.69  4952.1  426.36  4958.5  427.58  4972.9  428.09
  4979.7  427.39  4987.2  424.50  4993.7  423.33  4999.1  423.28  4999.5  422.78
  5003.7  422.78  5004.0  423.28  5007.0  425.68  5010.0  425.68  5016.1  427.95
  5022.4  428.31  5144.6  428.10  5215.2  430.88  5329.3  437.60  5431.3  441.16
#Mann=4,-1,0
  4667.0    0.05       0  4888.7    0.16       0  4999.1    0.07       0
  5004.0    0.16       0
Bank Sta=4999.1,5004
Exp/Cntr=0.3,0.1

Type RM Length L Ch R = 1,5731,294,294,294
BEGIN DESCRIPTION:
Dry Creek Trib A5951.11
END DESCRIPTION:
XS GIS Cut Line= 3
      2738266.91      6842608.16      2738002.59      6843087.75
      2737601.60      6843345.71
#Sta/Elev= 30
  4452.4  435.82  4478.5  435.70  4550.1  433.85  4566.2  432.87  4571.9  433.22
  4661.2  429.49  4729.0  427.53  4832.4  426.25  4866.7  425.58  4957.1  426.57
  4969.5  422.67  4976.4  422.62  4976.8  422.12  4981.0  422.12  4981.4  422.62
  4984.6  424.29  5007.8  426.66  5032.4  427.61  5066.0  429.41  5108.3  430.21
  5123.5  431.82  5144.6  432.20  5151.9  431.79  5202.1  431.71  5217.2  432.41
  5238.4  431.95  5253.6  432.92  5311.0  432.90  5347.3  434.85  5476.8  436.83
#Mann=6,-1,0
  4452.4    0.05       0  4832.4    0.16       0  4976.4    0.07       0
  4981.4    0.16       0  5032.4    0.07       0  5151.9    0.05       0
Bank Sta=4976.4,4981.4
Exp/Cntr=0.3,0.1

Type RM Length L Ch R = 1,5437,365,365,365
BEGIN DESCRIPTION:
Dry Creek Trib A5437.17
END DESCRIPTION:
XS GIS Cut Line= 3
      2738059.94      6842525.55      2737824.15      6842866.33
      2737596.84      6843159.67
#Sta/Elev= 30
  4590.8  432.32  4706.4  430.69  4748.3  428.48  4763.1  429.88  4769.2  428.69
  4778.0  428.74  4784.1  427.75  4805.0  426.70  4849.6  425.88  4864.5  424.94
  4891.5  424.64  4936.1  425.51  4950.1  424.77  4963.2  425.40  4978.0  425.01
  5007.8  423.98  5019.5  420.96  5019.9  420.46  5024.2  420.46  5024.6  420.96
  5042.9  426.41  5057.4  426.54  5063.7  425.80  5071.8  426.35  5086.3  425.12
  5121.6  429.33  5136.1  432.39  5206.7  432.03  5314.5  434.11  5376.3  434.50
#Mann=3,-1,0
  4590.8    0.05       0  5019.5    0.05       0  5024.6    0.05       0
Bank Sta=5019.5,5024.6
Exp/Cntr=0.3,0.1

Type RM Length L Ch R = 1,5072,521,521,521
BEGIN DESCRIPTION:
Dry Creek Trib A5072.01
END DESCRIPTION:
XS GIS Cut Line= 3
      2737880.73      6842183.65      2737599.38      6842588.24
      2737378.70      6842916.20
#Sta/Elev= 30
  4510.5  432.90  4556.0  431.61  4619.1  428.86  4654.8  428.55  4677.8  427.17
  4684.5  427.79  4690.6  427.03  4756.3  424.73  4791.9  423.52  4799.6  424.02
  4806.7  423.37  4836.1  423.24  4943.8  424.50  4964.7  422.88  4970.8  421.01
  4979.6  419.90  4983.0  418.85  4983.1  418.82  4983.5  418.32  4987.9  418.32
  4988.2  418.82  4994.4  423.64  5003.3  424.07  5036.5  423.61  5042.8  424.06
  5066.5  424.11  5123.5  426.31  5151.3  427.95  5288.4  432.40  5398.6  434.12
#Mann=5,-1,0
  4510.5    0.05       0  4756.3    0.12       0  4983.0    0.05       0
  4983.1    0.05       0  4988.2    0.05       0
Bank Sta=4983.1,4988.2
Exp/Cntr=0.3,0.1

Type RM Length L Ch R = 1,4551,330,330,330
BEGIN DESCRIPTION:
Dry Creek Trib A4550.54
END DESCRIPTION:
XS GIS Cut Line= 3
      2737663.84      6841884.05      2737473.33      6842173.94
      2737243.75      6842562.49
#Sta/Elev= 30
  4667.8  433.59  4686.6  431.91  4692.6  430.09  4713.7  428.14  4728.8  427.82
  4759.0  428.75  4795.1  428.31  4882.7  424.16  4924.7  423.32  4930.6  422.19
  4945.7  421.23  4960.8  423.05  4966.8  419.68  4972.7  417.70  4973.1  417.20
  4977.9  417.70  4981.9  417.81  4987.9  421.46  5003.0  422.89  5103.6  422.54
  5119.6  422.09  5172.3  423.19  5199.6  426.10  5230.8  427.30  5243.6  429.09
  5256.2  429.29  5289.4  430.06  5338.1  433.39  5418.0  435.59  5466.0  436.13
#Mann=6,-1,0
  4667.8    0.05       0  4882.7    0.12       0  4972.7    0.07       0
  4977.9    0.12       0  5103.6    0.16       0  5256.2    0.05       0
Bank Sta=4972.7,4977.9
Exp/Cntr=0.3,0.1

Type RM Length L Ch R = 1,4221,458,458,458
BEGIN DESCRIPTION:
Dry Creek Trib A4220.97
END DESCRIPTION:
XS GIS Cut Line= 3
      2737582.52      6841440.56      2737340.52      6841889.38
      2737084.98      6842290.25
#Sta/Elev= 30
  4500.8  436.48  4631.2  434.17  4691.2  432.33  4735.0  430.56  4762.6  428.61
  4773.1  428.69  4816.9  425.96  4822.6  425.03  4856.7  424.23  4904.5  422.54
  4920.7  422.68  4933.0  421.73  4955.7  421.67  4964.5  419.73  4967.5  417.88
  4967.9  417.38  4972.8  417.88  4986.4  422.36  5013.8  422.03  5067.0  422.74
  5175.0  420.95  5258.2  423.79  5290.1  425.46  5297.2  426.70  5320.5  427.31
  5347.6  429.80  5420.4  431.13  5435.7  432.05  5463.3  432.05  5486.1  433.89
#Mann=7,-1,0
  4500.8    0.05       0  4856.7    0.16       0  4967.5    0.07       0
  4972.8    0.16       0  5013.8    0.12       0  5067.0    0.16       0
  5258.2    0.05       0
Bank Sta=4967.5,4972.8
Exp/Cntr=0.3,0.1

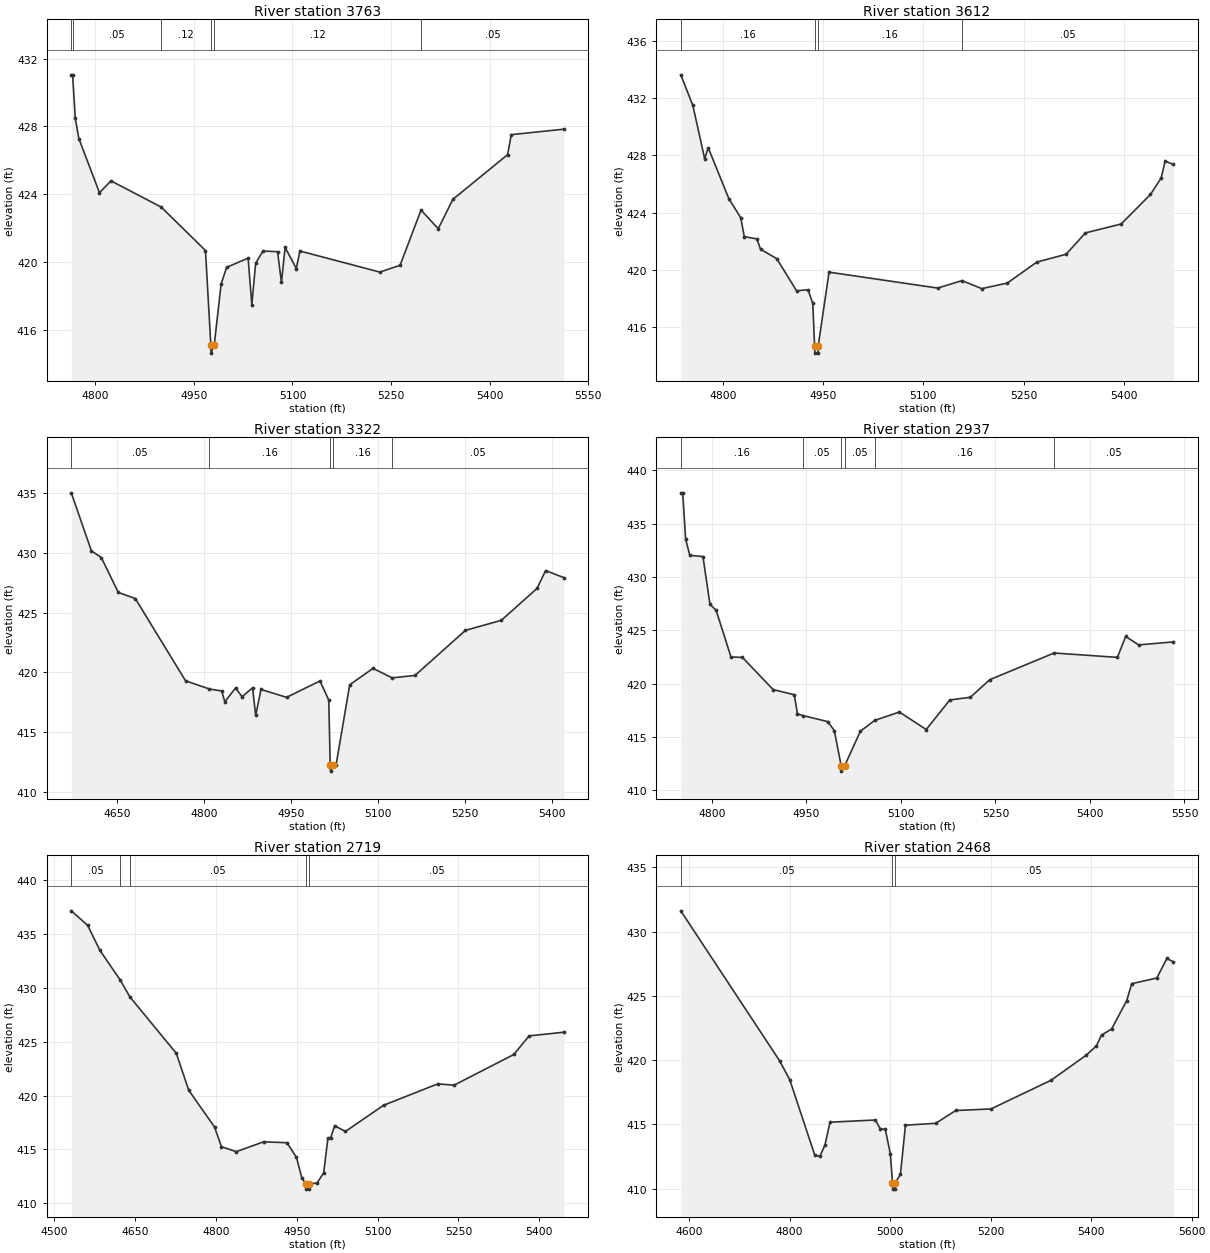
Type RM Length L Ch R = 1,3763,151,151,151
BEGIN DESCRIPTION:
Dry Creek Trib A3762.78
END DESCRIPTION:
XS GIS Cut Line= 3
      2737273.54      6841301.05      2737182.88      6841530.97
      2736963.57      6841982.92
#Sta/Elev= 30
  4763.4  431.04  4765.4  431.04  4769.5  428.48  4774.9  427.29  4806.3  424.10
  4823.7  424.80  4900.1  423.26  4967.6  420.70  4975.7  415.16  4976.1  414.66
  4981.0  415.16  4991.4  418.73  4999.8  419.71  5032.5  420.25  5038.1  417.50
  5043.9  419.94  5055.0  420.67  5077.3  420.63  5083.2  418.82  5088.8  420.88
  5105.8  419.64  5111.3  420.67  5232.9  419.43  5263.7  419.83  5295.6  423.08
  5321.8  421.98  5344.0  423.71  5427.3  426.34  5433.0  427.52  5512.9  427.84
#Mann=6,-1,0
  4763.4    0.07       0  4765.4    0.05       0  4900.1    0.12       0
  4975.7    0.07       0  4981.0    0.12       0  5295.6    0.05       0
Bank Sta=4975.7,4981
Exp/Cntr=0.3,0.1

Type RM Length L Ch R = 1,3612,290,290,290
BEGIN DESCRIPTION:
Mapping XS 28239f90
END DESCRIPTION:
XS GIS Cut Line= 3
      2737174.76      6841174.18      2737076.36      6841421.21
      2736855.47      6841837.08
#Sta/Elev= 30
  4737.0  433.62  4755.1  431.48  4772.7  427.77  4778.1  428.53  4808.9  424.98
  4826.7  423.65  4832.0  422.33  4850.9  422.17  4856.3  421.45  4880.6  420.79
  4910.2  418.55  4927.3  418.62  4934.5  417.67  4937.2  414.70  4937.6  414.20
  4942.1  414.20  4942.6  414.70  4958.8  419.85  5121.2  418.74  5157.7  419.26
  5187.2  418.70  5225.5  419.09  5269.5  420.55  5313.4  421.10  5342.4  422.59
  5395.7  423.21  5439.6  425.27  5455.6  426.42  5461.6  427.60  5473.8  427.37
#Mann=4,-1,0
  4737.0    0.16       0  4937.2    0.07       0  4942.6    0.16       0
  5157.7    0.05       0
Bank Sta=4937.2,4942.6
Exp/Cntr=0.3,0.1

Type RM Length L Ch R = 1,3322,385,385,385
BEGIN DESCRIPTION:
Dry Creek Trib A3458.86
END DESCRIPTION:
XS GIS Cut Line= 3
      2737031.12      6840959.06      2736867.21      6841354.97
      2736725.90      6841750.59
#Sta/Elev= 30
  4571.5  435.02  4606.1  430.17  4623.2  429.61  4652.5  426.69  4681.8  426.18
  4768.4  419.30  4809.3  418.62  4830.6  418.45  4836.0  417.55  4854.5  418.70
  4865.8  417.97  4883.8  418.72  4889.2  416.41  4898.3  418.58  4942.4  417.92
  5000.0  419.29  5015.1  417.69  5017.6  412.25  5018.1  411.75  5023.1  412.25
  5027.6  412.25  5051.2  418.97  5091.3  420.34  5124.4  419.55  5163.7  419.75
  5250.6  423.52  5312.4  424.36  5374.0  427.03  5388.7  428.52  5420.1  427.93
#Mann=5,-1,0
  4571.5    0.05       0  4809.3    0.16       0  5017.6    0.07       0
  5023.1    0.16       0  5124.4    0.05       0
Bank Sta=5017.6,5023.1
Exp/Cntr=0.3,0.1

Type RM Length L Ch R = 1,2937,218,218,218
BEGIN DESCRIPTION:
Dry Creek Trib A2937.14
END DESCRIPTION:
XS GIS Cut Line= 3
      2736822.72      6840797.18      2736749.20      6841048.25
      2736631.42      6841554.62
#Sta/Elev= 30
  4750.8  437.88  4753.9  437.88  4758.5  433.53  4765.2  432.02  4786.0  431.91
  4797.1  427.43  4806.9  426.87  4830.5  422.49  4848.6  422.46  4897.4  419.44
  4930.8  418.96  4936.0  417.16  4944.6  417.01  4984.0  416.44  4994.4  415.60
  5005.3  412.30  5005.7  411.80  5010.8  412.30  5035.8  415.54  5058.4  416.55
  5097.6  417.34  5140.2  415.70  5177.7  418.47  5210.3  418.72  5241.1  420.37
  5343.2  422.87  5443.6  422.46  5456.7  424.42  5477.3  423.63  5532.3  423.91
#Mann=6,-1,0
  4750.8    0.16       0  4944.6    0.05       0  5005.3    0.05       0
  5010.8    0.05       0  5058.4    0.16       0  5343.2    0.05       0
Bank Sta=5005.3,5010.8
Exp/Cntr=0.3,0.1

Type RM Length L Ch R = 1,2719,251,251,251
BEGIN DESCRIPTION:
Dry Creek Trib A2719.19
END DESCRIPTION:
XS GIS Cut Line= 3
      2736636.45      6840598.75      2736557.67      6841071.42
      2736503.36      6841503.13
#Sta/Elev= 30
  4531.3  437.17  4561.7  435.82  4584.3  433.51  4622.5  430.71  4640.1  429.17
  4726.2  423.93  4749.2  420.51  4797.2  417.08  4810.1  415.25  4837.7  414.79
  4888.4  415.71  4931.7  415.62  4949.2  414.27  4959.4  412.33  4966.8  411.81
  4967.2  411.31  4971.8  411.31  4972.3  411.81  4987.5  411.87  4999.9  412.85
  5007.7  416.07  5012.8  416.07  5020.1  417.20  5040.3  416.67  5110.9  419.10
  5211.6  421.09  5241.9  420.97  5352.7  423.82  5381.2  425.55  5445.6  425.89
#Mann=5,-1,0
  4531.3    0.05       0  4622.5    0.16       0  4640.1    0.05       0
  4966.8    0.05       0  4972.3    0.05       0
Bank Sta=4966.8,4972.3
Exp/Cntr=0.3,0.1

Type RM Length L Ch R = 1,2468,261,261,261
BEGIN DESCRIPTION:
Dry Creek Trib A2468.3
END DESCRIPTION:
XS GIS Cut Line= 3
      2736387.99      6840544.43      2736366.16      6840969.91
      2736353.04      6841523.82
#Sta/Elev= 30
  4583.4  431.62  4780.2  419.94  4800.3  418.47  4850.3  412.58  4860.3  412.52
  4870.3  413.39  4880.4  415.17  4970.5  415.34  4980.5  414.65  4990.5  414.61
  5000.5  412.68  5004.7  410.46  5005.2  409.96  5009.8  409.96  5010.2  410.46
  5020.5  411.10  5030.5  414.94  5090.6  415.08  5130.6  416.08  5200.6  416.20
  5320.6  418.44  5390.6  420.40  5410.6  421.11  5420.6  421.95  5440.6  422.42
  5470.7  424.62  5480.7  425.95  5530.7  426.39  5550.7  427.91  5563.5  427.65
#Mann=3,-1,0
  4583.4    0.05       0  5004.7    0.05       0  5010.2    0.05       0
Bank Sta=5004.7,5010.2
Exp/Cntr=0.3,0.1