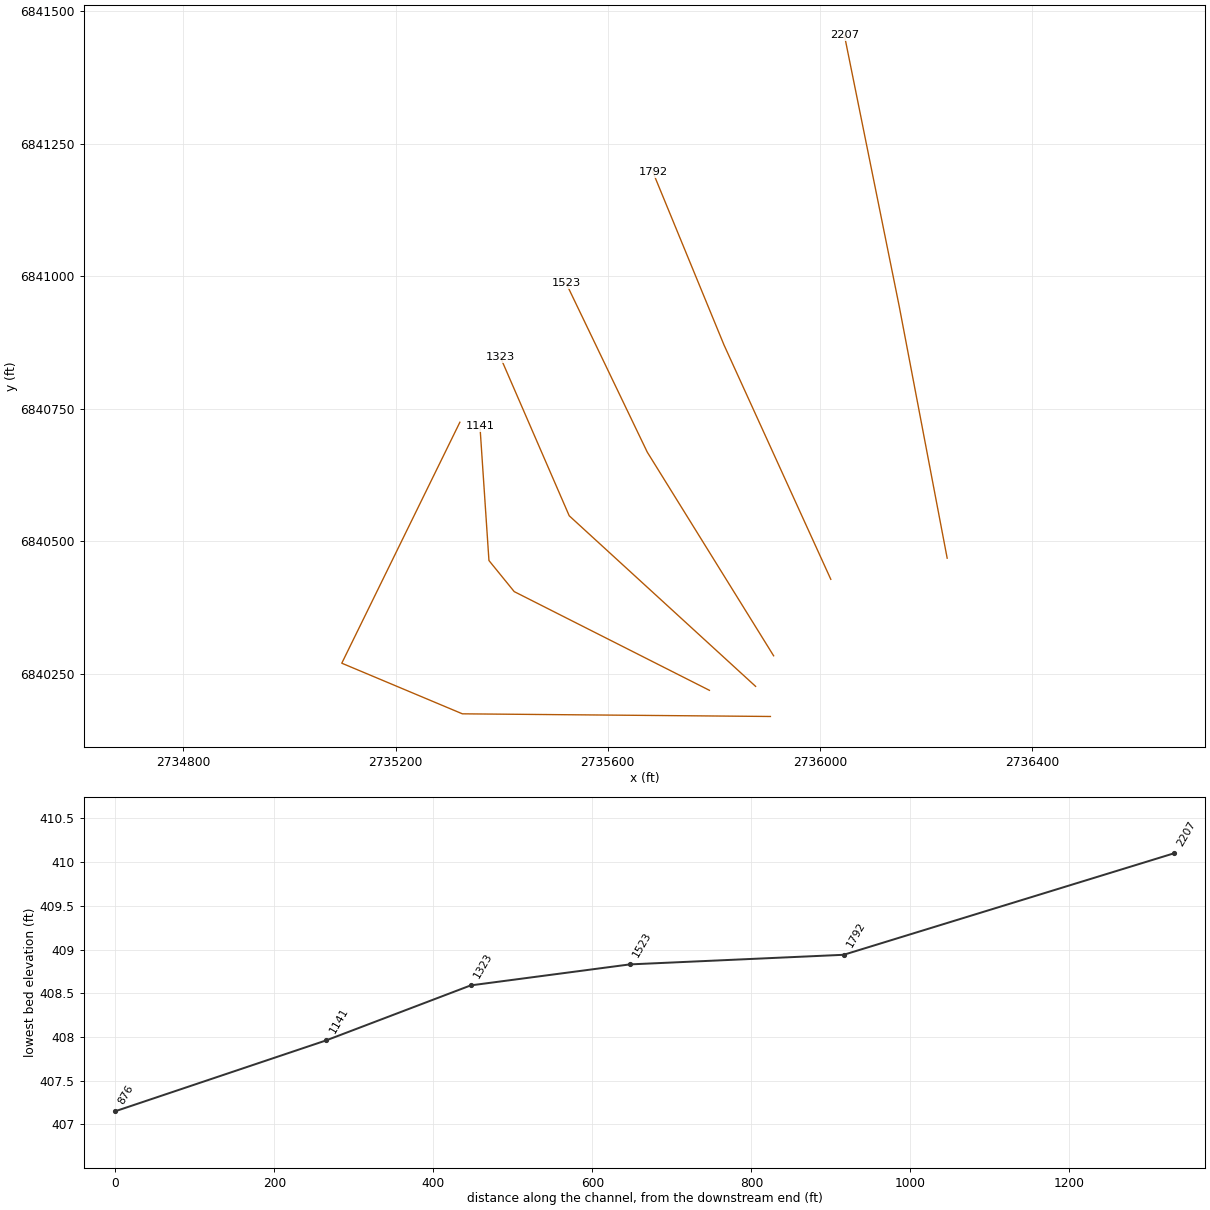
HEC-RAS study Dry Creek Trib A.prj: Dry Creek Trib A Base Level Engineering

--- Dry Creek Trib A.g01 (geometry) --- (continued)

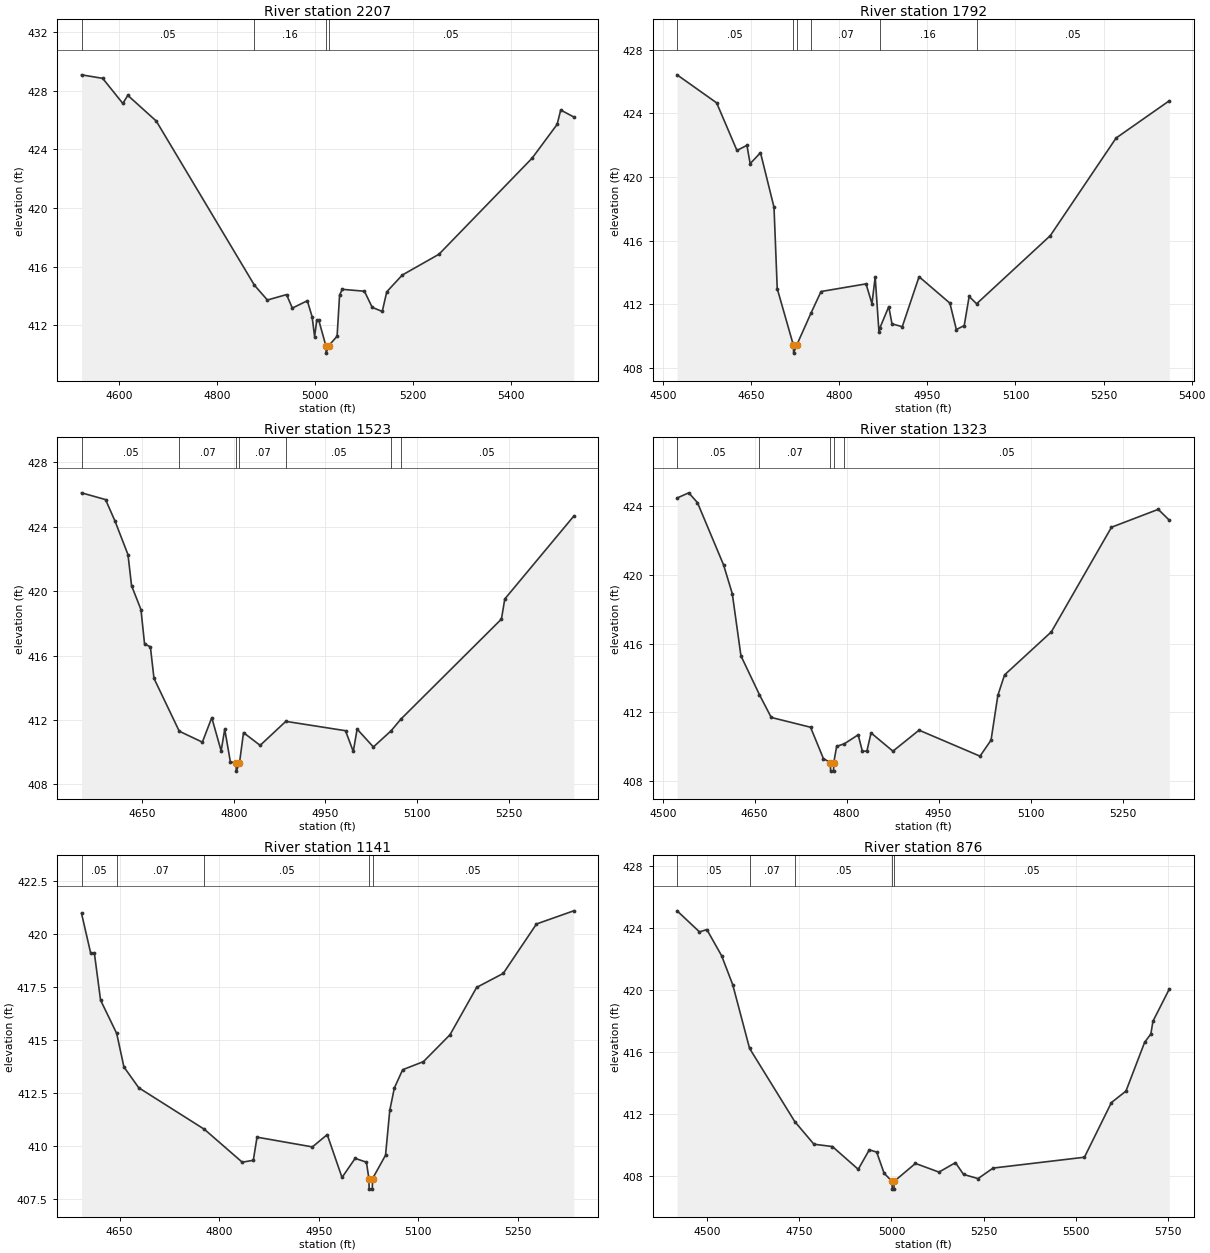
Type RM Length L Ch R = 1,2207,415,415,415
BEGIN DESCRIPTION:
Dry Creek Trib A2207.19
END DESCRIPTION:
XS GIS Cut Line= 3
      2736239.95      6840468.17      2736149.35      6840943.99
      2736046.18      6841454.19
#Sta/Elev= 30
  4523.4  429.07  4566.6  428.83  4607.7  427.12  4617.9  427.67  4676.0  425.92
  4876.4  414.73  4902.9  413.72  4942.0  414.09  4953.8  413.17  4984.4  413.67
  4994.2  412.58  4999.3  411.22  5003.7  412.34  5007.8  412.34  5022.3  410.60
  5022.8  410.10  5027.9  410.60  5045.2  411.25  5050.3  414.06  5055.7  414.45
  5101.0  414.32  5116.9  413.22  5137.4  412.94  5146.6  414.28  5178.2  415.42
  5253.2  416.84  5443.4  423.39  5494.4  425.69  5501.8  426.67  5528.3  426.20
#Mann=4,-1,0
  4523.4    0.05       0  4876.4    0.16       0  5022.3    0.07       0
  5027.9    0.05       0
Bank Sta=5022.3,5027.9
Exp/Cntr=0.3,0.1

Type RM Length L Ch R = 1,1792,269,269,269
BEGIN DESCRIPTION:
Dry Creek Trib A1792.37
END DESCRIPTION:
XS GIS Cut Line= 3
      2736020.55      6840428.29      2735819.08      6840870.36
      2735685.06      6841196.16
#Sta/Elev= 30
  4523.8  426.42  4591.1  424.66  4625.7  421.67  4642.7  421.99  4648.2  420.84
  4665.8  421.53  4688.8  418.10  4694.3  412.99  4721.8  409.44  4722.2  408.94
  4727.4  409.44  4752.1  411.48  4768.9  412.81  4845.5  413.29  4855.6  412.05
  4861.1  413.72  4867.5  410.28  4869.3  410.54  4884.2  411.86  4889.7  410.78
  4907.2  410.60  4935.8  413.74  4988.3  412.08  4999.3  410.42  5012.7  410.67
  5021.1  412.50  5033.8  412.04  5159.3  416.32  5271.3  422.45  5361.9  424.79
#Mann=6,-1,0
  4523.8    0.05       0  4721.8    0.07       0  4727.4    0.05       0
  4752.1    0.07       0  4869.3    0.16       0  5033.8    0.05       0
Bank Sta=4721.8,4727.4
Exp/Cntr=0.3,0.1

Type RM Length L Ch R = 1,1523,200,200,200
BEGIN DESCRIPTION:
Dry Creek Trib A1522.66
END DESCRIPTION:
XS GIS Cut Line= 3
      2735912.71      6840284.14      2735674.45      6840668.14
      2735521.62      6840986.33
#Sta/Elev= 30
  4551.1  426.11  4590.4  425.69  4605.8  424.36  4627.1  422.27  4632.9  420.35
  4648.3  418.86  4654.2  416.72  4663.7  416.55  4669.6  414.59  4710.9  411.31
  4748.7  410.63  4764.1  412.15  4779.4  410.09  4785.3  411.43  4794.5  409.41
  4803.8  409.33  4804.2  408.83  4809.4  409.33  4816.0  411.22  4843.2  410.43
  4885.2  411.92  4982.8  411.34  4995.5  410.05  5001.8  411.44  5028.4  410.33
  5057.5  411.34  5073.4  412.06  5237.8  418.27  5243.3  419.52  5356.0  424.66
#Mann=7,-1,0
  4551.1    0.05       0  4710.9    0.07       0  4803.8    0.05       0
  4809.4    0.07       0  4885.2    0.05       0  5057.5    0.07       0
  5073.4    0.05       0
Bank Sta=4803.8,4809.4
Exp/Cntr=0.3,0.1

Type RM Length L Ch R = 1,1323,182,182,182
BEGIN DESCRIPTION:
Dry Creek Trib A1322.74
END DESCRIPTION:
XS GIS Cut Line= 3
      2735878.70      6840226.50      2735527.30      6840548.11
      2735397.41      6840847.49
#Sta/Elev= 30
  4523.5  424.46  4542.5  424.76  4556.7  424.19  4599.3  420.57  4613.5  418.90
  4627.6  415.29  4657.8  413.03  4677.0  411.71  4741.1  411.14  4762.1  409.32
  4773.4  409.09  4773.9  408.59  4778.6  408.59  4779.0  409.09  4783.7  410.03
  4796.3  410.18  4818.8  410.70  4825.6  409.75  4833.0  409.75  4839.8  410.81
  4875.5  409.75  4918.1  410.97  5017.5  409.46  5035.5  410.39  5046.6  412.99
  5057.5  414.18  5133.8  416.68  5231.9  422.76  5308.2  423.80  5326.2  423.17
#Mann=5,-1,0
  4523.5    0.05       0  4657.8    0.07       0  4773.4    0.05       0
  4779.0    0.07       0  4796.3    0.05       0
Bank Sta=4773.4,4779
Exp/Cntr=0.3,0.1

Type RM Length L Ch R = 1,1141,265,265,265
BEGIN DESCRIPTION:
Mapping XS 7a0fbe81
END DESCRIPTION:
XS GIS Cut Line= 4
      2735791.64      6840219.00      2735423.61      6840405.13
      2735375.95      6840463.74      2735358.98      6840717.01
#Sta/Elev= 30
  4592.6  420.96  4606.3  419.10  4611.9  419.10  4621.3  416.87  4645.6  415.30
  4656.5  413.72  4678.8  412.74  4777.8  410.78  4834.8  409.23  4851.5  409.32
  4857.1  410.41  4940.6  409.95  4962.9  410.53  4985.2  408.51  5005.0  409.41
  5022.0  409.23  5025.7  408.46  5026.1  407.96  5030.8  407.96  5031.3  408.46
  5050.8  409.56  5057.2  411.68  5064.1  412.73  5076.6  413.59  5107.9  413.97
  5148.0  415.24  5188.1  417.47  5228.2  418.13  5278.3  420.46  5334.4  421.08
#Mann=5,-1,0
  4592.6    0.05       0  4645.6    0.07       0  4777.8    0.05       0
  5025.7    0.05       0  5031.3    0.05       0
Bank Sta=5025.7,5031.3
Exp/Cntr=0.3,0.1

Type RM Length L Ch R = 1,876,0,0,0
BEGIN DESCRIPTION:
Dry Creek Trib A983.309
END DESCRIPTION:
XS GIS Cut Line= 4
      2735906.65      6840169.69      2735325.87      6840174.69
      2735098.47      6840270.15      2735321.14      6840724.49
#Sta/Elev= 30
  4419.2  425.12  4479.8  423.76  4499.8  423.91  4539.8  422.22  4569.9  420.35
  4615.5  416.24  4738.0  411.51  4789.9  410.05  4839.9  409.90  4909.9  408.43
  4939.9  409.69  4959.9  409.54  4979.9  408.18  5001.5  407.65  5002.0  407.15
  5006.7  407.15  5007.1  407.65  5064.9  408.81  5128.6  408.25  5173.4  408.86
  5195.1  408.10  5234.5  407.83  5275.3  408.51  5522.7  409.21  5595.8  412.74
  5635.2  413.48  5685.8  416.63  5702.7  417.17  5708.3  417.99  5752.6  420.07
#Mann=5,-1,0
  4419.2    0.05       0  4615.5    0.07       0  4738.0    0.05       0
  5001.5    0.05       0  5007.1    0.05       0
Bank Sta=5001.5,5007.1
Exp/Cntr=0.3,0.1

Chan Stop Cuts=-1