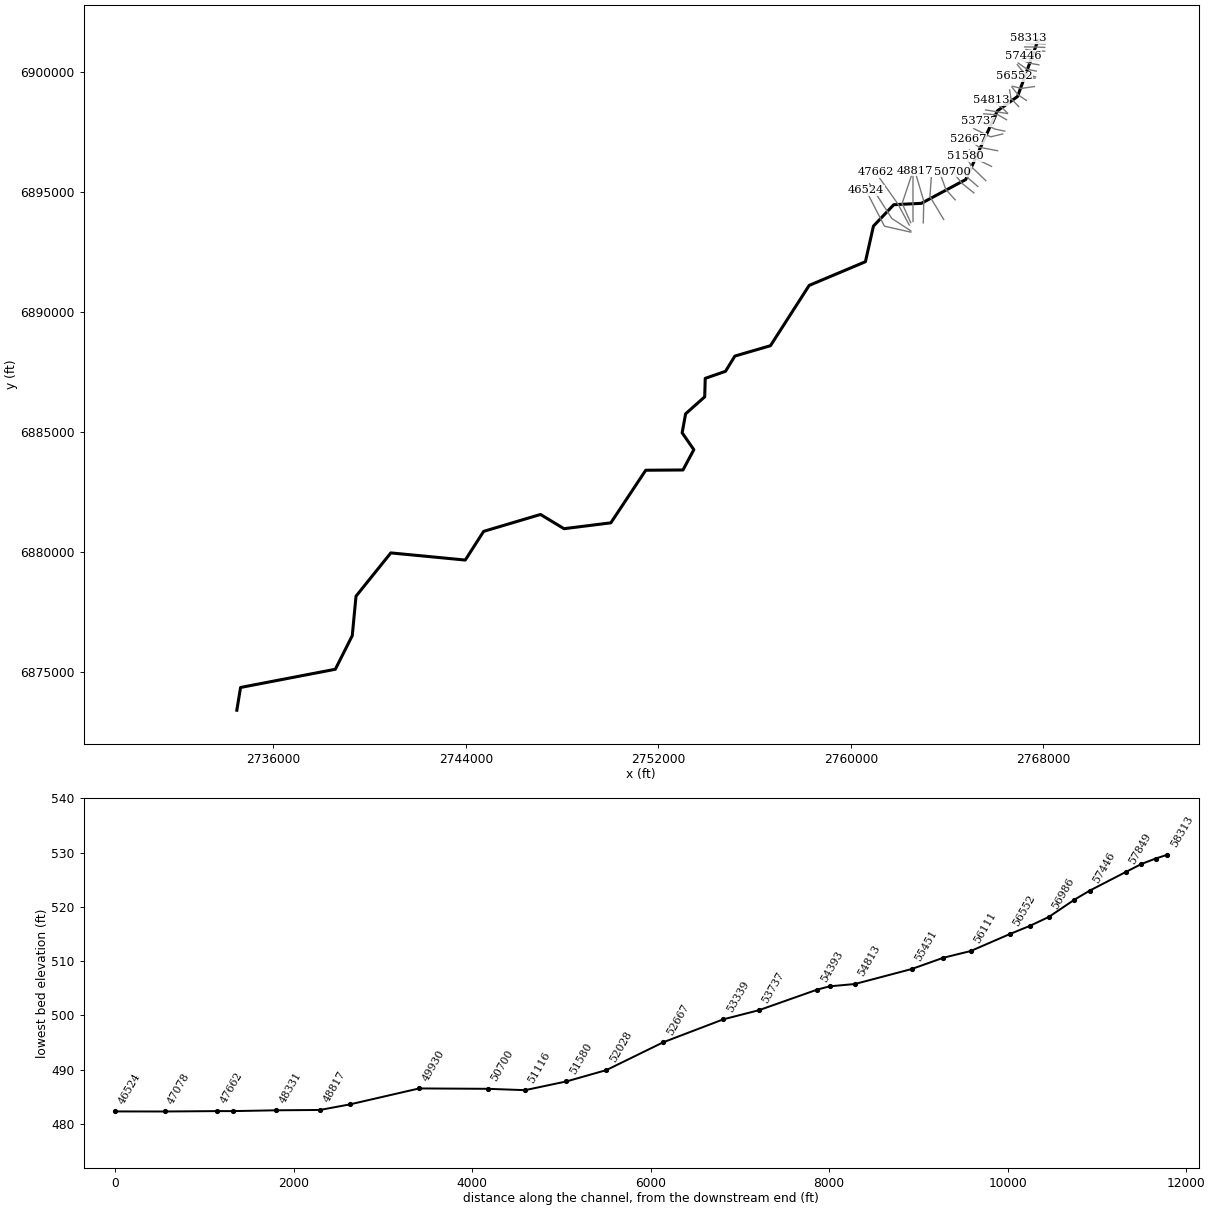
--- Dry Lacy Fork.prj (project) ---

Proj Title=Dry Lacy Fork Base Level Engineering
Current Plan=p01
Default Exp/Contr=0.3,0.1
English Units
Geom File=g01
Flow File=f01
Plan File=p01
BEGIN DESCRIPTION:
Dry Lacy Fork
END DESCRIPTION:

--- Dry Lacy Fork.p01 (plan) ---

Plan Title=Multiple Run
Short Identifier=Multiple
Geom File=g01
Flow File=f01
Subcritical Flow
K Sum by GR= 0
Std Step Tol= 0.01
Critical Tol= 0.01
Num of Std Step Trials= 20
Max Error Tol= 0.3
Flow Tol Ratio= 0.001
Split Flow NTrial= 30
Split Flow Tol= 0.02
Split Flow Ratio= 0.02
Log Output Level= 0
Friction Slope Method= 1
Unsteady Friction Slope Method= 2
Unsteady Bridges Friction Slope Method= 1
Parabolic Critical Depth
Global Vel Dist=  1 , 1 , 1
Global Log Level= 0
CheckData=True
Encroach Param= -1, 0, 0, 0
BEGIN DESCRIPTION:
Multiple Run
END DESCRIPTION:

--- Dry Lacy Fork.f01 (steady flow) ---

Flow Title=Multiple
Number of Profiles=7
Profile Names=10-year,25-year,50-year,1pct_min,100-year,1pct_plu,500-year
River Rch & RM= Dry Lacy Fork,Reach-1,58313
     132     159     180     101     202     404     255
River Rch & RM= Dry Lacy Fork,Reach-1,56986
     243     309     359     208     415     828     556
River Rch & RM= Dry Lacy Fork,Reach-1,54813
     435     572     683     405     808    1612    1134
River Rch & RM= Dry Lacy Fork,Reach-1,52667
     530     707     849     508    1013    2021    1442
River Rch & RM= Dry Lacy Fork,Reach-1,52028
     620     831    1003     602    1201    2395    1722
River Rch & RM= Dry Lacy Fork,Reach-1,49154
     755    1023    1243     749    1495    2984    2170
River Rch & RM= Dry Lacy Fork,Reach-1,48817
     942    1291    1580     960    1915    3820    2818
River Rch & RM= Dry Lacy Fork,Reach-1,47662
    1054    1451    1780    1083    2161    4311    3193
River Rch & RM= Dry Lacy Fork,Reach-1,44491
    1491    2072    2559    1564    3121    6226    4655
River Rch & RM= Dry Lacy Fork,Reach-1,38333
    1942    2729    3395    2089    4168    8316    6302
River Rch & RM= Dry Lacy Fork,Reach-1,36001
    2112    2977    3711    2288    4565    9109    6928
River Rch & RM= Dry Lacy Fork,Reach-1,35287
    2118    2984    3718    2291    4571    9121    6930
River Rch & RM= Dry Lacy Fork,Reach-1,33885
    2091    2933    3646    2240    4469    8917    6736
River Rch & RM= Dry Lacy Fork,Reach-1,30616
    2228    3132    3896    2396    4781    9540    7221
River Rch & RM= Dry Lacy Fork,Reach-1,28566
    2229    3131    3893    2392    4773    9524    7199
River Rch & RM= Dry Lacy Fork,Reach-1,26858
    2267    3184    3960    2434    4857    9690    7326
River Rch & RM= Dry Lacy Fork,Reach-1,26035
    2281    3199    3975    2440    4869    9715    7328
River Rch & RM= Dry Lacy Fork,Reach-1,21651
    2282    3199    3973    2438    4864    9706    7315
River Rch & RM= Dry Lacy Fork,Reach-1,20811
    2441    3431    4269    2624    5235   10445    7896
River Rch & RM= Dry Lacy Fork,Reach-1,19101
    2634    3705    4611    2834    5655   11284    8531
River Rch & RM= Dry Lacy Fork,Reach-1,13264
    2717    3823    4761    2928    5841   11655    8818
River Rch & RM= Dry Lacy Fork,Reach-1,11593
    2990    4207    5237    3217    6420   12809    9675
Boundary for River Rch & Prof#=Dry Lacy Fork,Reach-1,1
Up Type=0
Dn Type=3
Dn Slope=0.005
Boundary for River Rch & Prof#=Dry Lacy Fork,Reach-1,2
Up Type=0
Dn Type=3
Dn Slope=0.005
Boundary for River Rch & Prof#=Dry Lacy Fork,Reach-1,3
Up Type=0
Dn Type=3
Dn Slope=0.005
Boundary for River Rch & Prof#=Dry Lacy Fork,Reach-1,4
Up Type=0
Dn Type=3
Dn Slope=0.005
Boundary for River Rch & Prof#=Dry Lacy Fork,Reach-1,5
Up Type=0
Dn Type=3
Dn Slope=0.005
Boundary for River Rch & Prof#=Dry Lacy Fork,Reach-1,6
Up Type=0
Dn Type=3
Dn Slope=0.005
Boundary for River Rch & Prof#=Dry Lacy Fork,Reach-1,7
Up Type=0
Dn Type=3
Dn Slope=0.005

--- Dry Lacy Fork.g01 (geometry) ---

Geom Title=Existing Conditions

River Reach=Dry Lacy Fork,Reach-1
Reach XY= 30
      2767776.00      6901311.00      2766922.15      6898962.39
      2766081.82      6898363.31      2764768.60      6895505.23
      2762924.53      6894514.55      2761777.47      6894457.46
      2760933.74      6893567.46      2760599.52      6892083.88
      2758262.26      6891097.80      2756653.19      6888587.02
      2755173.46      6888155.70      2754786.17      6887521.33
      2753942.39      6887227.78      2753920.92      6886458.72
      2753126.49      6885750.55      2752983.52      6884961.05
      2753468.51      6884257.83      2753018.18      6883413.37
      2751469.94      6883402.86      2750020.32      6881212.97
      2748072.69      6880969.07      2747096.34      6881561.29
      2744733.98      6880857.78      2743970.04      6879663.14
      2740876.00      6879961.00      2739429.82      6878159.42
      2739273.77      6876516.90      2738570.39      6875116.59
      2734631.85      6874358.94      2734476.00      6873411.00

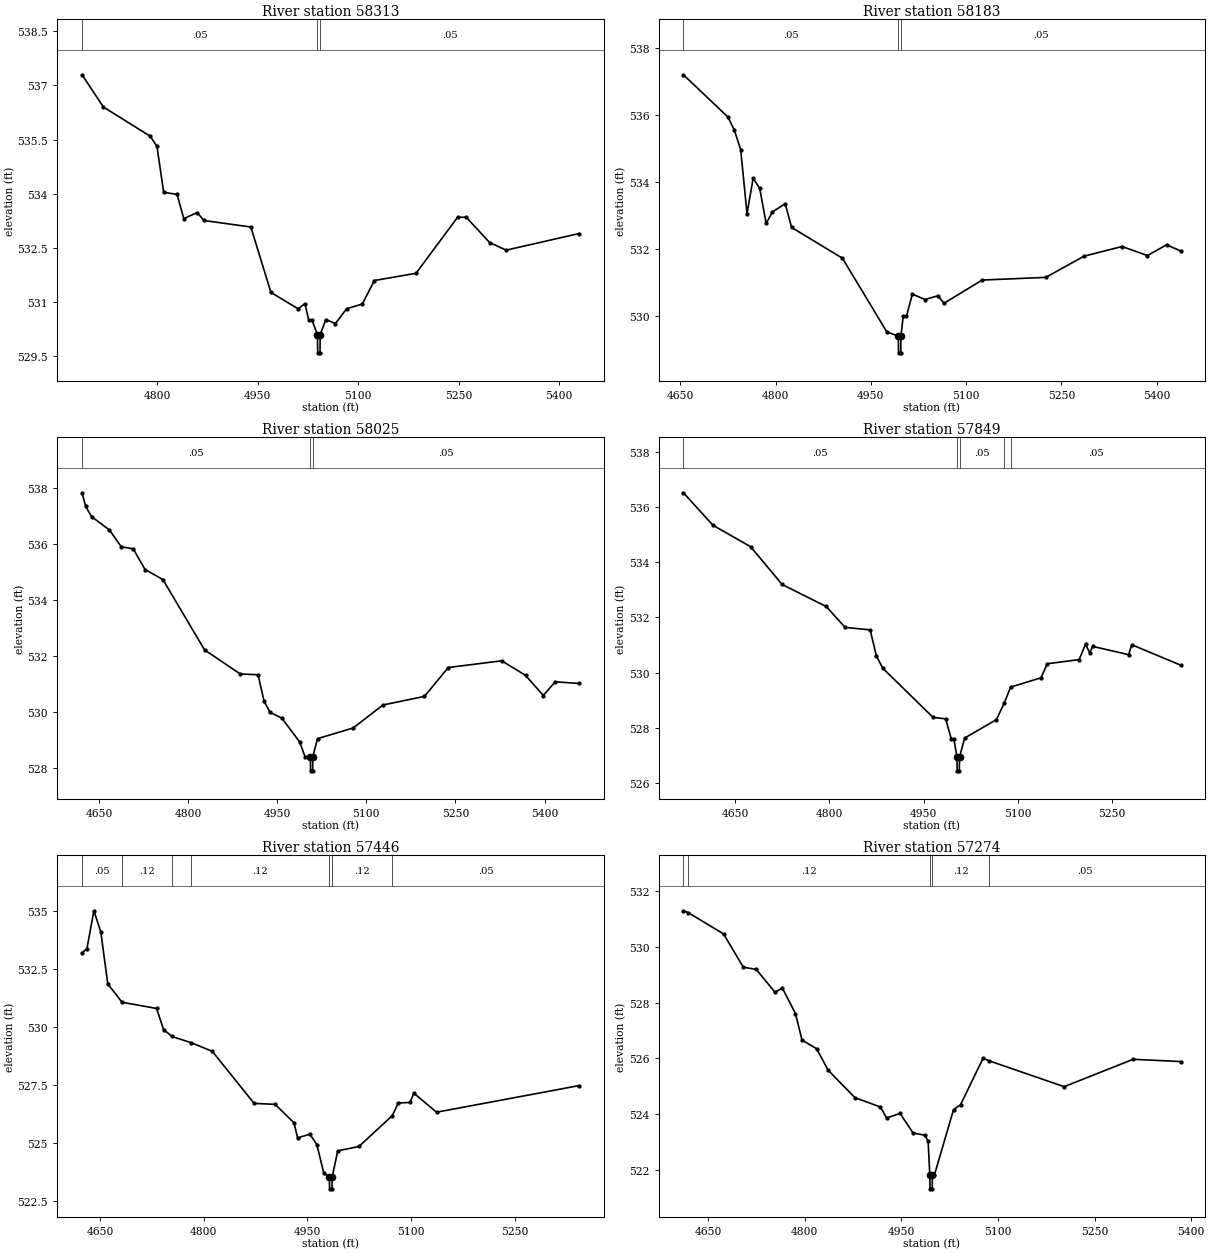
Type RM Length L Ch R = 1,58313,130,130,130
BEGIN DESCRIPTION:
Dry Lacy Fork 2864
END DESCRIPTION:
XS GIS Cut Line= 3
      2768087.67      6901283.55      2767775.90      6901279.19
      2767360.80      6901390.24
#Sta/Elev= 30
  4688.2  537.29  4719.9  536.40  4789.9  535.59  4799.9  535.31  4809.9  534.04
  4829.9  533.98  4839.9  533.31  4859.9  533.48  4869.9  533.26  4939.9  533.08
  4969.9  531.27  5010.2  530.82  5020.6  530.96  5026.1  530.52  5031.2  530.50
  5039.3  530.10  5039.6  529.60  5043.1  529.60  5043.3  530.10  5051.7  530.52
  5066.1  530.41  5082.7  530.82  5106.2  530.95  5124.1  531.60  5186.3  531.80
  5248.3  533.35  5261.2  533.35  5296.1  532.65  5320.8  532.44  5429.7  532.90
#Mann=3,-1,0
  4688.2    0.05       0  5039.3    0.04       0  5043.3    0.05       0
Bank Sta=5039.3,5043.3
Exp/Cntr=0.3,0.1

Type RM Length L Ch R = 1,58183,158,158,158
BEGIN DESCRIPTION:
Dry Lacy Fork 2862
END DESCRIPTION:
XS GIS Cut Line= 3
      2768066.05      6901151.39      2767719.59      6901165.35
      2767283.88      6901171.91
#Sta/Elev= 30
  4655.0  537.20  4725.1  535.94  4735.1  535.55  4745.1  534.97  4755.1  533.06
  4764.8  534.12  4775.1  533.81  4785.2  532.77  4795.2  533.11  4815.2  533.36
  4825.2  532.65  4905.3  531.73  4975.3  529.53  4993.3  529.41  4993.6  528.91
  4997.1  528.91  4997.3  529.41  5001.0  530.00  5006.0  530.00  5015.3  530.66
  5035.3  530.50  5055.3  530.61  5065.3  530.39  5125.3  531.08  5225.4  531.16
  5285.4  531.79  5345.4  532.08  5385.4  531.81  5415.4  532.13  5437.5  531.95
#Mann=3,-1,0
  4655.0    0.05       0  4993.3    0.04       0  4997.3    0.05       0
Bank Sta=4993.3,4997.3
Exp/Cntr=0.3,0.1

Type RM Length L Ch R = 1,58025,176,176,176
BEGIN DESCRIPTION:
Dry Lacy Fork 2861
END DESCRIPTION:
XS GIS Cut Line= 3
      2768051.93      6901007.31      2767673.27      6901022.20
      2767215.64      6901026.48
#Sta/Elev= 30
  4621.7  537.84  4627.6  537.36  4637.6  536.99  4667.7  536.51  4687.7  535.91
  4707.7  535.84  4727.7  535.10  4757.7  534.74  4827.8  532.23  4887.8  531.37
  4917.9  531.34  4927.9  530.40  4937.9  530.00  4957.9  529.79  4987.9  528.94
  4996.8  528.42  5005.9  528.41  5006.2  527.91  5009.7  527.91  5009.9  528.41
  5017.9  529.06  5077.9  529.44  5127.9  530.26  5197.9  530.57  5237.9  531.60
  5327.9  531.84  5367.9  531.32  5397.9  530.60  5417.9  531.09  5458.3  531.03
#Mann=3,-1,0
  4621.7    0.05       0  5005.9    0.04       0  5009.9    0.05       0
Bank Sta=5005.9,5009.9
Exp/Cntr=0.3,0.1

Type RM Length L Ch R = 1,57849,403,403,403
BEGIN DESCRIPTION:
Dry Lacy Fork 2863
END DESCRIPTION:
XS GIS Cut Line= 3
      2768052.96      6900848.01      2767622.98      6900861.63
      2767266.71      6900918.63
#Sta/Elev= 30
  4567.7  536.53  4614.7  535.35  4674.7  534.57  4724.7  533.20  4794.8  532.40
  4825.0  531.64  4864.8  531.55  4874.8  530.60  4884.8  530.16  4964.9  528.37
  4984.9  528.32  4993.9  527.59  4997.9  527.59  5003.0  526.93  5003.2  526.43
  5006.7  526.43  5007.0  526.93  5015.1  527.62  5065.7  528.29  5078.3  528.90
  5088.3  529.47  5136.6  529.81  5146.7  530.32  5197.4  530.47  5207.5  531.03
  5214.0  530.72  5219.1  530.95  5276.0  530.65  5281.1  531.01  5358.7  530.27
#Mann=5,-1,0
  4567.7    0.05       0  5003.0    0.04       0  5007.0    0.05       0
  5078.3    0.12       0  5088.3    0.05       0
Bank Sta=5003,5007
Exp/Cntr=0.3,0.1

Type RM Length L Ch R = 1,57446,172,172,172
BEGIN DESCRIPTION:
Dry Lacy Fork 2860
END DESCRIPTION:
XS GIS Cut Line= 3
      2767852.93      6900456.87      2767477.82      6900504.75
      2767169.35      6900650.45
#Sta/Elev= 30
  4624.2  533.20  4631.2  533.38  4641.3  535.02  4651.3  534.10  4661.4  531.86
  4682.0  531.07  4732.0  530.80  4742.1  529.89  4754.4  529.59  4782.2  529.32
  4812.6  528.95  4873.1  526.70  4903.4  526.66  4930.9  525.86  4936.0  525.21
  4953.8  525.37  4963.9  524.92  4973.9  523.69  4982.0  523.51  4982.3  523.01
  4985.8  523.01  4986.0  523.51  4994.1  524.65  5024.8  524.84  5073.0  526.17
  5081.8  526.72  5098.7  526.74  5104.2  527.14  5137.1  526.32  5343.5  527.47
#Mann=7,-1,0
  4624.2    0.05       0  4682.0    0.12       0  4754.4    0.05       0
  4782.2    0.12       0  4982.0    0.07       0  4986.0    0.12       0
  5073.0    0.05       0
Bank Sta=4982,4986
Exp/Cntr=0.3,0.1

Type RM Length L Ch R = 1,57274,288,288,288
BEGIN DESCRIPTION:
Dry Lacy Fork 2859
END DESCRIPTION:
XS GIS Cut Line= 3
      2767807.44      6900280.83      2767425.97      6900347.60
      2767069.22      6900492.19
#Sta/Elev= 30
  4611.4  531.29  4619.1  531.22  4673.8  530.46  4704.4  529.27  4724.5  529.19
  4753.7  528.37  4765.1  528.52  4785.4  527.61  4795.6  526.66  4818.2  526.35
  4836.2  525.58  4877.6  524.60  4917.4  524.26  4926.9  523.87  4947.9  524.03
  4968.2  523.33  4986.4  523.25  4991.5  523.04  4994.1  521.83  4994.4  521.33
  4997.9  521.33  4998.1  521.83  5001.3  521.83  5031.0  524.17  5041.8  524.34
  5076.9  526.01  5085.6  525.92  5202.8  524.99  5310.0  525.97  5383.6  525.89
#Mann=5,-1,0
  4611.4    0.05       0  4619.1    0.12       0  4994.1    0.07       0
  4998.1    0.12       0  5085.6    0.05       0
Bank Sta=4994.1,4998.1
Exp/Cntr=0.3,0.1

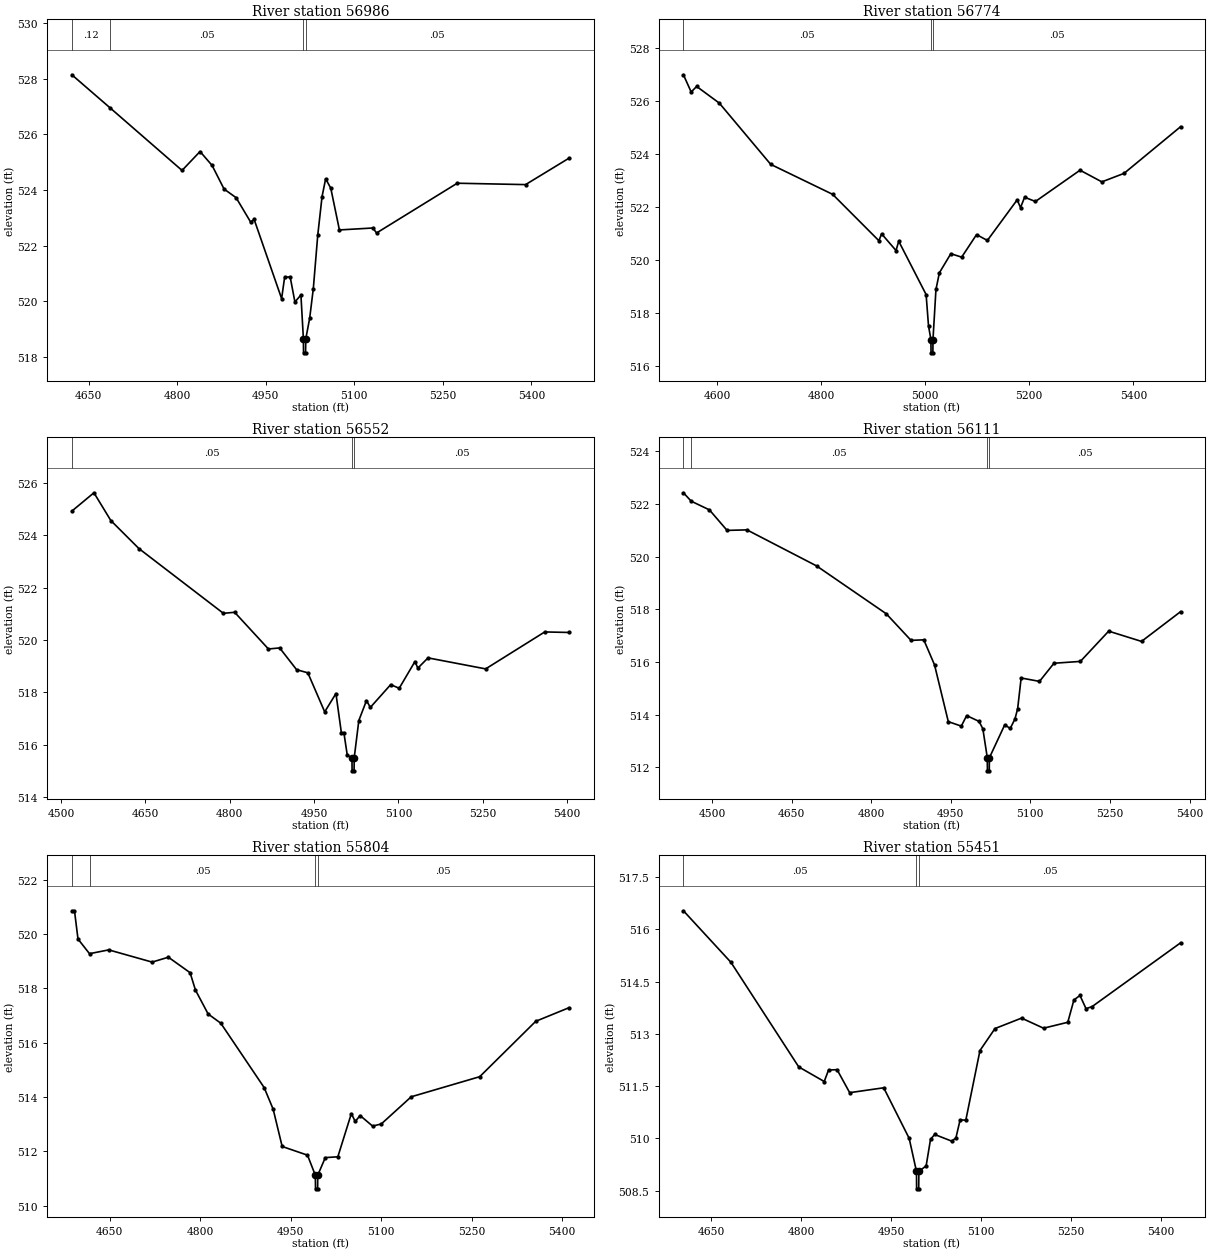
Type RM Length L Ch R = 1,56986,212,212,212
BEGIN DESCRIPTION:
Dry Lacy Fork 2858
END DESCRIPTION:
XS GIS Cut Line= 3
      2767699.49      6900020.12      2767325.27      6900090.54
      2766948.08      6900356.30
#Sta/Elev= 30
  4621.4  528.14  4686.2  526.95  4808.1  524.70  4838.6  525.38  4859.0  524.88
  4879.3  524.03  4899.7  523.72  4924.4  522.84  4930.2  522.94  4976.8  520.09
  4981.9  520.86  4991.3  520.87  4999.3  519.97  5009.5  520.22  5013.7  518.64
  5013.9  518.14  5017.4  518.14  5017.7  518.64  5024.3  519.38  5030.5  520.45
  5038.0  522.37  5045.3  523.76  5051.4  524.40  5060.1  524.06  5074.7  522.56
  5131.5  522.63  5137.6  522.45  5274.3  524.24  5390.1  524.19  5463.6  525.14
#Mann=4,-1,0
  4621.4    0.12       0  4686.2    0.05       0  5013.7    0.05       0
  5017.7    0.05       0
Bank Sta=5013.7,5017.7
Exp/Cntr=0.3,0.1

Type RM Length L Ch R = 1,56774,222,222,222
BEGIN DESCRIPTION:
Dry Lacy Fork 2857
END DESCRIPTION:
XS GIS Cut Line= 3
      2767670.28      6899776.95      2767227.04      6899911.47
      2766908.51      6900286.16
#Sta/Elev= 30
  4535.6  526.99  4550.5  526.34  4561.0  526.55  4604.6  525.92  4703.3  523.61
  4822.2  522.48  4911.1  520.73  4916.3  520.99  4944.0  520.36  4949.2  520.71
  5001.8  518.70  5006.4  517.52  5011.0  517.00  5011.3  516.50  5014.8  516.50
  5015.0  517.00  5020.7  518.89  5027.3  519.52  5049.3  520.24  5070.1  520.11
  5098.7  520.96  5119.5  520.74  5176.7  522.27  5183.2  521.98  5191.0  522.37
  5211.8  522.21  5297.5  523.39  5339.4  522.95  5382.0  523.27  5490.6  525.03
#Mann=3,-1,0
  4535.6    0.05       0  5011.0    0.04       0  5015.0    0.05       0
Bank Sta=5011,5015
Exp/Cntr=0.3,0.1

Type RM Length L Ch R = 1,56552,441,441,441
BEGIN DESCRIPTION:
Dry Lacy Fork 2856
END DESCRIPTION:
XS GIS Cut Line= 3
      2767655.27      6899731.54      2767171.95      6899707.48
      2766781.49      6899796.10
#Sta/Elev= 30
  4519.1  524.92  4558.4  525.62  4588.5  524.56  4638.5  523.49  4788.7  521.02
  4808.7  521.06  4868.8  519.66  4888.8  519.70  4918.9  518.87  4938.9  518.75
  4968.9  517.26  4988.9  517.96  4998.5  516.47  5003.0  516.47  5009.1  515.60
  5017.4  515.51  5017.6  515.01  5021.1  515.01  5021.4  515.51  5029.6  516.93
  5043.2  517.69  5050.1  517.43  5086.3  518.30  5101.4  518.16  5129.4  519.18
  5134.6  518.93  5152.7  519.32  5255.2  518.90  5360.3  520.31  5403.4  520.29
#Mann=3,-1,0
  4519.1    0.05       0  5017.4    0.04       0  5021.4    0.05       0
Bank Sta=5017.4,5021.4
Exp/Cntr=0.3,0.1

Type RM Length L Ch R = 1,56111,307,307,307
BEGIN DESCRIPTION:
Dry Lacy Fork 2855
END DESCRIPTION:
XS GIS Cut Line= 3
      2767624.46      6899377.49      2767075.00      6899298.11
      2766704.57      6899391.16
#Sta/Elev= 30
  4446.0  522.43  4460.7  522.11  4495.0  521.78  4528.3  521.00  4565.7  521.02
  4697.0  519.65  4828.4  517.83  4875.0  516.82  4899.1  516.84  4919.3  515.89
  4945.3  513.73  4969.8  513.56  4979.9  513.96  5003.2  513.74  5010.4  513.46
  5018.8  512.36  5019.0  511.86  5022.5  511.86  5022.8  512.36  5051.7  513.61
  5062.0  513.47  5070.9  513.83  5076.0  514.22  5082.6  515.39  5117.2  515.26
  5144.5  515.95  5194.3  516.02  5247.6  517.17  5309.5  516.78  5383.1  517.91
#Mann=4,-1,0
  4446.0    0.12       0  4460.7    0.05       0  5018.8    0.05       0
  5022.8    0.05       0
Bank Sta=5018.8,5022.8
Exp/Cntr=0.3,0.1

Type RM Length L Ch R = 1,55804,353,353,353
BEGIN DESCRIPTION:
Dry Lacy Fork 2854
END DESCRIPTION:
XS GIS Cut Line= 3
      2767288.22      6898799.42      2766942.22      6899033.33
      2766688.03      6899350.88
#Sta/Elev= 30
  4587.1  520.86  4591.5  520.86  4597.3  519.82  4616.4  519.28  4648.3  519.42
  4720.2  518.97  4747.2  519.15  4783.2  518.58  4792.1  517.94  4813.1  517.06
  4834.1  516.72  4906.0  514.35  4921.0  513.55  4935.9  512.18  4977.9  511.86
  4990.9  511.12  4991.2  510.62  4994.7  510.62  4994.9  511.12  5007.4  511.77
  5028.2  511.80  5050.6  513.39  5057.1  513.10  5065.1  513.32  5085.9  512.93
  5100.3  513.01  5149.9  514.01  5263.5  514.75  5356.4  516.79  5411.5  517.29
#Mann=4,-1,0
  4587.1    0.12       0  4616.4    0.05       0  4990.9    0.04       0
  4994.9    0.05       0
Bank Sta=4990.9,4994.9
Exp/Cntr=0.3,0.1

Type RM Length L Ch R = 1,55451,638,638,638
BEGIN DESCRIPTION:
Dry Lacy Fork 2782
END DESCRIPTION:
XS GIS Cut Line= 3
      2766969.67      6898542.84      2766644.50      6898882.93
      2766591.86      6899236.81
#Sta/Elev= 30
  4603.8  516.53  4683.0  515.05  4795.9  512.05  4838.4  511.63  4845.6  511.96
  4859.8  511.97  4880.8  511.31  4937.5  511.45  4979.9  510.00  4992.1  509.05
  4992.3  508.55  4995.8  508.55  4996.1  509.05  5008.2  509.21  5015.5  509.97
  5022.4  510.11  5050.7  509.92  5057.8  510.01  5064.8  510.53  5074.3  510.52
  5097.9  512.52  5122.9  513.15  5167.2  513.45  5203.8  513.16  5244.2  513.33
  5254.4  513.97  5264.5  514.10  5274.6  513.72  5284.7  513.78  5432.1  515.61
#Mann=3,-1,0
  4603.8    0.05       0  4992.1    0.04       0  4996.1    0.05       0
Bank Sta=4992.1,4996.1
Exp/Cntr=0.3,0.1

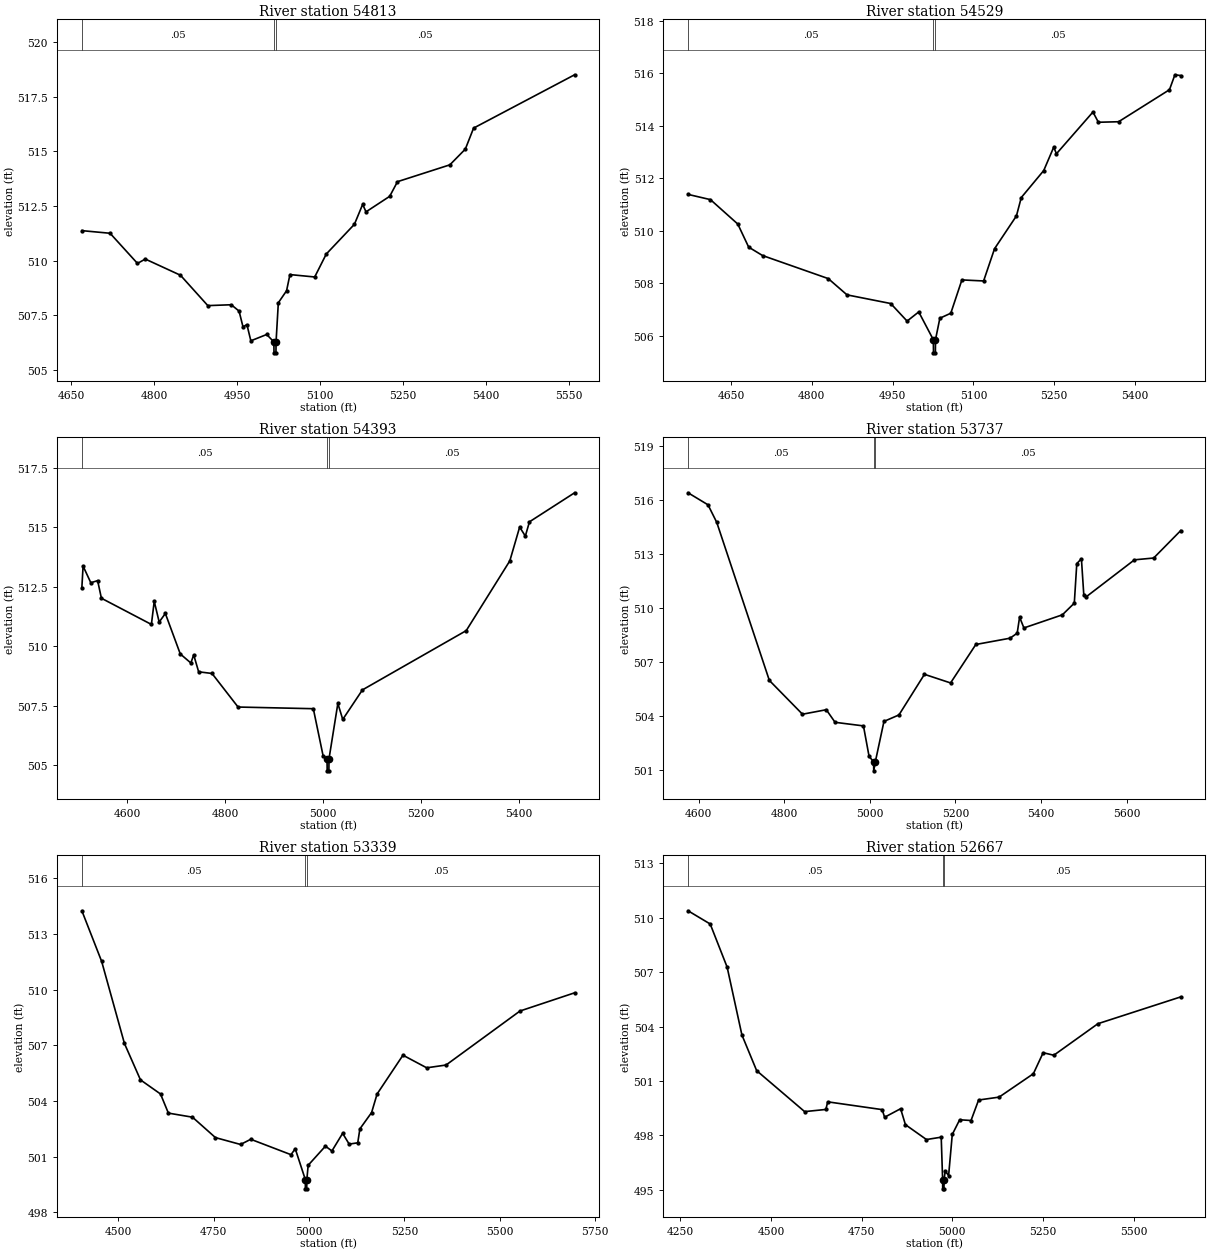
Type RM Length L Ch R = 1,54813,284,284,284
BEGIN DESCRIPTION:
Dry Lacy Fork 2830
END DESCRIPTION:
XS GIS Cut Line= 3
      2766505.82      6898268.68      2766277.92      6898499.78
      2765809.51      6898818.44
#Sta/Elev= 30
  4669.1  511.37  4720.1  511.25  4769.7  509.87  4783.8  510.07  4847.4  509.33
  4896.9  507.94  4939.3  507.98  4953.4  507.69  4960.5  506.97  4967.6  507.07
  4974.7  506.33  5003.4  506.62  5016.3  506.28  5016.6  505.78  5020.1  505.78
  5020.3  506.28  5024.4  508.07  5039.3  508.62  5045.4  509.36  5090.2  509.25
  5111.1  510.30  5162.0  511.66  5176.9  512.57  5183.0  512.23  5225.8  512.94
  5239.9  513.61  5334.6  514.38  5362.6  515.10  5377.5  516.06  5560.2  518.50
#Mann=3,-1,0
  4669.1    0.05       0  5016.3    0.05       0  5020.3    0.05       0
Bank Sta=5016.3,5020.3
Exp/Cntr=0.3,0.1

Type RM Length L Ch R = 1,54529,136,136,136
BEGIN DESCRIPTION:
Dry Lacy Fork 2780
END DESCRIPTION:
XS GIS Cut Line= 3
      2766497.02      6898253.33      2766074.69      6898323.36
      2765595.30      6898405.06
#Sta/Elev= 30
  4570.3  511.39  4611.9  511.19  4662.6  510.26  4682.8  509.38  4708.5  509.06
  4830.5  508.18  4865.3  507.56  4946.4  507.23  4976.8  506.56  4998.4  506.91
  5025.5  505.85  5025.8  505.35  5029.3  505.35  5029.5  505.85  5037.6  506.67
  5057.9  506.86  5078.5  508.13  5118.8  508.09  5139.1  509.32  5179.7  510.57
  5188.7  511.27  5230.4  512.30  5248.9  513.19  5254.0  512.94  5321.7  514.53
  5331.8  514.14  5369.3  514.16  5463.7  515.38  5473.8  515.95  5484.7  515.92
#Mann=3,-1,0
  4570.3    0.05       0  5025.5    0.05       0  5029.5    0.05       0
Bank Sta=5025.5,5029.5
Exp/Cntr=0.3,0.1

Type RM Length L Ch R = 1,54393,656,656,656
BEGIN DESCRIPTION:
Dry Lacy Fork 2779
END DESCRIPTION:
XS GIS Cut Line= 4
      2766463.98      6897995.27      2766104.65      6898200.95
      2766021.14      6898202.54      2765514.14      6898244.60
#Sta/Elev= 30
  4507.8  512.46  4510.3  513.36  4526.1  512.66  4540.0  512.75  4547.7  512.01
  4649.8  510.91  4655.6  511.88  4665.7  511.01  4678.3  511.37  4708.8  509.67
  4730.4  509.29  4736.2  509.63  4746.3  508.92  4773.6  508.85  4826.8  507.44
  4980.5  507.37  5000.4  505.40  5008.5  505.26  5008.8  504.76  5012.3  504.76
  5012.5  505.26  5030.6  507.59  5040.6  506.92  5080.8  508.16  5292.8  510.65
  5381.8  513.58  5401.9  515.00  5413.5  514.62  5421.9  515.22  5514.1  516.44
#Mann=3,-1,0
  4507.8    0.05       0  5008.5    0.05       0  5012.5    0.05       0
Bank Sta=5008.5,5012.5
Exp/Cntr=0.3,0.1

Type RM Length L Ch R = 1,53737,398,398,398
BEGIN DESCRIPTION:
Dry Lacy Fork 2728
END DESCRIPTION:
XS GIS Cut Line= 3
      2766391.58      6897519.20      2765975.77      6897609.40
      2765329.61      6897939.10
#Sta/Elev= 30
  4575.3  516.42  4621.9  515.75  4642.4  514.77  4765.2  505.98  4842.6  504.10
  4898.2  504.35  4918.7  503.65  4985.0  503.45  4998.1  501.76  5008.7  501.45
  5009.0  500.95  5012.7  501.45  5032.9  503.70  5067.9  504.06  5127.5  506.32
  5188.5  505.84  5247.5  507.98  5327.5  508.33  5344.1  508.61  5349.7  509.50
  5359.8  508.90  5449.6  509.63  5477.5  510.28  5483.3  512.48  5494.1  512.75
  5499.7  510.73  5505.7  510.64  5618.0  512.69  5662.9  512.79  5726.2  514.32
#Mann=3,-1,0
  4575.3    0.05       0  5008.7    0.04       0  5012.7    0.05       0
Bank Sta=5008.7,5012.7
Exp/Cntr=0.3,0.1

Type RM Length L Ch R = 1,53339,672,672,672
BEGIN DESCRIPTION:
Dry Lacy Fork 2729
END DESCRIPTION:
XS GIS Cut Line= 3
      2766306.43      6897402.80      2765807.82      6897283.14
      2765107.21      6897622.65
#Sta/Elev= 30
  4404.8  514.25  4456.7  511.52  4516.4  507.10  4558.4  505.14  4610.9  504.38
  4631.5  503.35  4694.7  503.13  4754.9  502.03  4820.7  501.66  4847.4  501.94
  4952.9  501.11  4964.0  501.43  4990.4  499.77  4990.6  499.27  4994.1  499.27
  4994.4  499.77  4997.9  500.54  5043.1  501.57  5060.1  501.31  5088.2  502.26
  5105.3  501.68  5127.8  501.75  5133.4  502.50  5164.1  503.38  5178.5  504.38
  5246.3  506.47  5308.5  505.79  5359.2  505.94  5553.0  508.85  5696.1  509.83
#Mann=3,-1,0
  4404.8    0.05       0  4990.4    0.04       0  4994.4    0.05       0
Bank Sta=4990.4,4994.4
Exp/Cntr=0.3,0.1

Type RM Length L Ch R = 1,52667,639,639,639
BEGIN DESCRIPTION:
Dry Lacy Fork 2727
END DESCRIPTION:
XS GIS Cut Line= 3
      2766091.90      6896704.80      2765331.61      6896848.85
      2764856.84      6897190.44
#Sta/Elev= 30
  4271.2  510.39  4332.3  509.66  4379.0  507.28  4419.7  503.54  4460.4  501.57
  4592.7  499.31  4651.2  499.43  4656.3  499.85  4806.5  499.42  4813.2  499.00
  4857.3  499.47  4870.6  498.59  4928.6  497.77  4969.3  497.90  4973.2  495.55
  4973.4  495.05  4976.9  495.05  4977.2  495.55  4980.3  496.04  4989.7  495.78
  4999.8  498.05  5020.2  498.86  5051.5  498.82  5072.4  499.95  5128.9  500.11
  5223.4  501.40  5250.4  502.56  5279.8  502.42  5401.4  504.16  5629.9  505.64
#Mann=3,-1,0
  4271.2    0.05       0  4973.2    0.05       0  4977.2    0.05       0
Bank Sta=4973.2,4977.2
Exp/Cntr=0.3,0.1

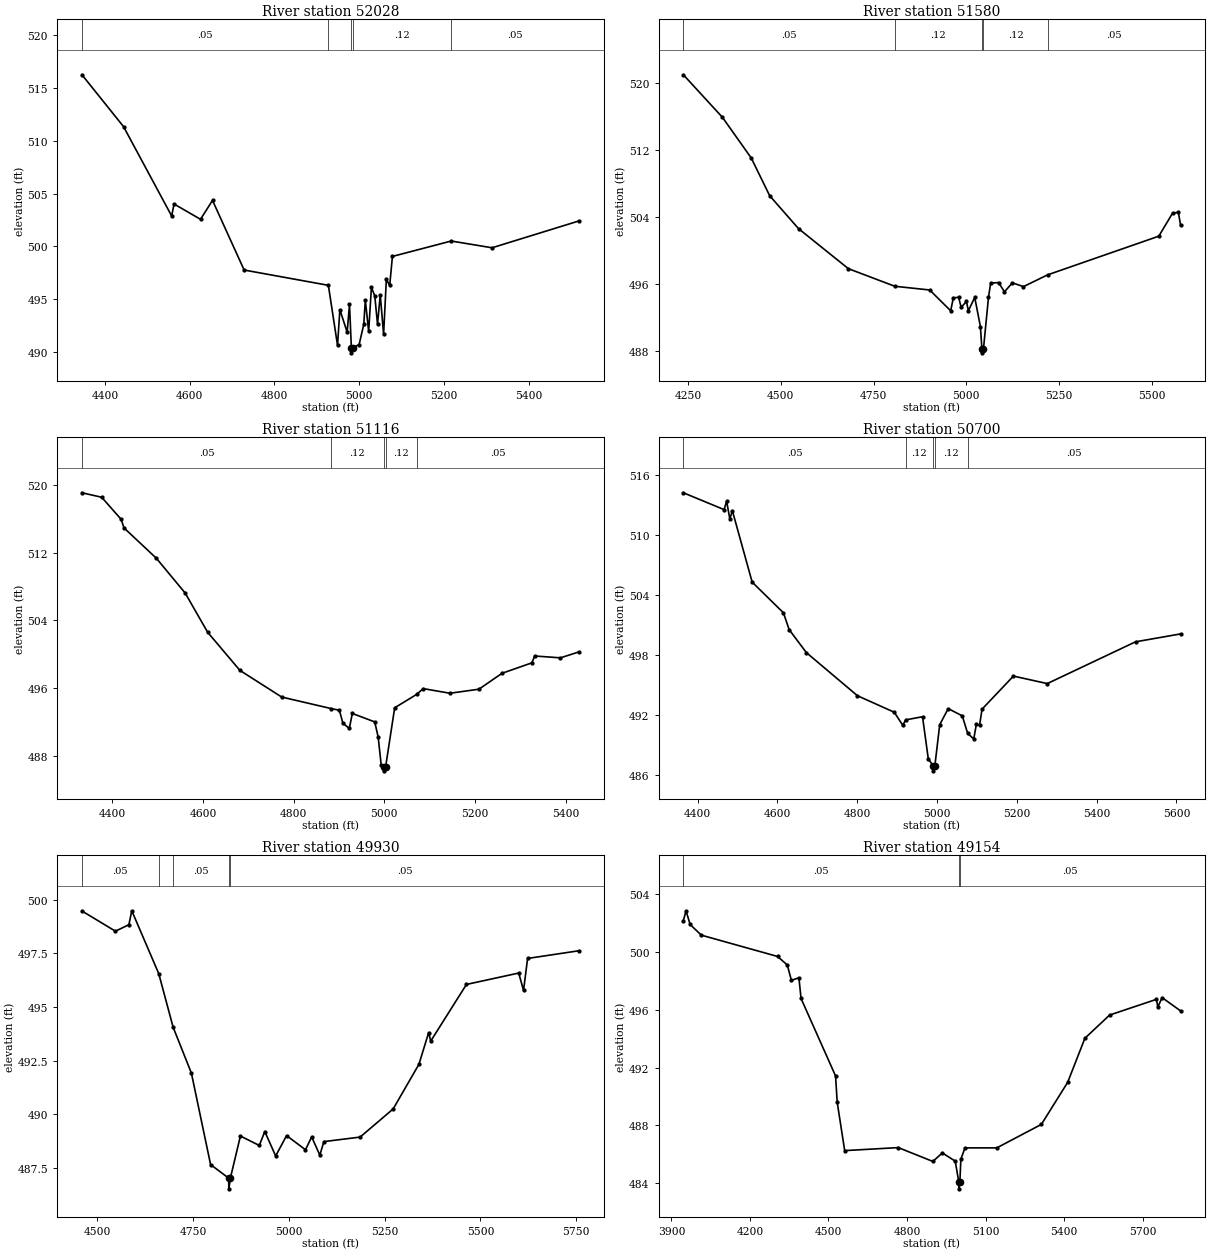
Type RM Length L Ch R = 1,52028,448,448,448
BEGIN DESCRIPTION:
Dry Lacy Fork 2724
END DESCRIPTION:
XS GIS Cut Line= 3
      2765841.00      6896054.39      2765241.46      6896340.93
      2764920.89      6896734.76
#Sta/Elev= 30
  4346.1  516.27  4444.2  511.35  4557.6  502.88  4563.2  504.02  4625.6  502.57
  4653.9  504.36  4728.5  497.76  4927.1  496.31  4948.7  490.62  4954.2  494.00
  4971.4  491.87  4976.9  494.51  4981.3  490.41  4981.6  489.91  4985.5  490.41
  4999.6  490.70  5010.6  492.61  5014.2  494.92  5022.1  491.95  5028.6  496.12
  5036.5  495.31  5043.0  492.62  5049.4  495.40  5057.3  491.67  5063.8  496.87
  5071.7  496.30  5078.1  499.05  5216.8  500.51  5313.0  499.87  5518.4  502.42
#Mann=5,-1,0
  4346.1    0.05       0  4927.1    0.12       0  4981.3    0.07       0
  4985.5    0.12       0  5216.8    0.05       0
Bank Sta=4981.3,4985.5
Exp/Cntr=0.3,0.1

Type RM Length L Ch R = 1,51580,464,464,464
BEGIN DESCRIPTION:
Dry Lacy Fork 2726
END DESCRIPTION:
XS GIS Cut Line= 3
      2765603.44      6895459.67      2765050.55      6895993.33
      2764761.08      6896486.07
#Sta/Elev= 30
  4237.6  520.95  4342.9  515.88  4420.6  511.03  4470.2  506.54  4547.9  502.62
  4682.2  497.85  4807.5  495.75  4901.4  495.31  4958.0  492.83  4965.2  494.38
  4979.3  494.43  4986.3  493.24  5000.4  493.94  5005.7  492.84  5022.8  494.42
  5038.1  490.95  5042.1  488.32  5042.5  487.82  5046.4  488.32  5059.9  494.43
  5065.7  496.13  5087.2  496.19  5102.9  495.09  5124.3  496.16  5154.1  495.71
  5219.1  497.11  5518.9  501.72  5556.1  504.47  5571.6  504.56  5577.5  503.05
#Mann=5,-1,0
  4237.6    0.05       0  4807.5    0.12       0  5042.1    0.07       0
  5046.4    0.12       0  5219.1    0.05       0
Bank Sta=5042.1,5046.4
Exp/Cntr=0.3,0.1

Type RM Length L Ch R = 1,51116,416,416,416
BEGIN DESCRIPTION:
Dry Lacy Fork 2725
END DESCRIPTION:
XS GIS Cut Line= 3
      2765272.08      6895216.01      2764762.57      6895657.20
      2764525.85      6896007.06
#Sta/Elev= 30
  4333.3  519.11  4376.8  518.58  4419.5  515.98  4426.1  514.95  4497.4  511.36
  4561.0  507.24  4610.4  502.61  4681.7  498.09  4773.8  494.94  4882.6  493.58
  4901.0  493.38  4908.7  491.84  4922.9  491.23  4929.5  493.00  4978.9  492.00
  4986.5  490.20  4993.2  486.89  4998.6  486.71  4999.0  486.21  5003.0  486.71
  5022.9  493.67  5071.2  495.25  5085.9  495.94  5144.7  495.39  5208.7  495.87
  5259.6  497.75  5325.5  498.99  5331.6  499.80  5388.5  499.58  5429.7  500.29
#Mann=5,-1,0
  4333.3    0.05       0  4882.6    0.12       0  4998.6    0.07       0
  5003.0    0.12       0  5071.2    0.05       0
Bank Sta=4998.6,5003
Exp/Cntr=0.3,0.1

Type RM Length L Ch R = 1,50700,770,770,770
BEGIN DESCRIPTION:
Dry Lacy Fork 2666
END DESCRIPTION:
XS GIS Cut Line= 3
      2765106.91      6894949.10      2764601.48      6895357.92
      2764230.83      6895824.42
#Sta/Elev= 30
  4364.5  514.22  4466.5  512.54  4472.9  513.38  4480.9  511.61  4487.3  512.43
  4536.9  505.30  4615.2  502.24  4629.6  500.56  4672.8  498.26  4800.7  493.96
  4893.0  492.31  4914.2  491.01  4921.7  491.55  4963.8  491.86  4978.2  487.67
  4990.3  486.96  4990.7  486.46  4994.7  486.96  5006.9  491.07  5028.2  492.67
  5063.4  491.95  5076.9  490.20  5092.2  489.64  5098.6  491.09  5106.7  491.01
  5113.0  492.62  5191.6  495.92  5276.4  495.17  5497.5  499.34  5610.4  500.13
#Mann=5,-1,0
  4364.5    0.05       0  4921.7    0.12       0  4990.3    0.07       0
  4994.7    0.12       0  5076.9    0.05       0
Bank Sta=4990.3,4994.7
Exp/Cntr=0.3,0.1

Type RM Length L Ch R = 1,49930,776,776,776
BEGIN DESCRIPTION:
Dry Lacy Fork 2665
END DESCRIPTION:
XS GIS Cut Line= 3
      2764328.58      6894660.25      2763940.58      6895096.18
      2763698.73      6895767.56
#Sta/Elev= 30
  4460.5  499.47  4547.8  498.53  4582.9  498.83  4590.5  499.48  4660.9  496.55
  4698.3  494.06  4746.0  491.92  4796.1  487.66  4843.2  487.03  4843.7  486.53
  4847.7  487.03  4873.9  488.99  4923.2  488.55  4937.5  489.20  4965.9  488.06
  4994.3  489.01  5043.7  488.35  5059.8  488.95  5081.1  488.10  5091.7  488.73
  5186.2  488.94  5272.4  490.25  5339.7  492.33  5365.1  493.81  5370.4  493.41
  5463.7  496.05  5600.0  496.58  5612.6  495.77  5623.2  497.26  5757.7  497.62
#Mann=5,-1,0
  4460.5    0.05       0  4660.9     0.1       0  4698.3    0.05       0
  4843.2    0.04       0  4847.7    0.05       0
Bank Sta=4843.2,4847.7
Exp/Cntr=0.3,0.1

Type RM Length L Ch R = 1,49154,337,337,337
BEGIN DESCRIPTION:
Dry Lacy Fork 2664
END DESCRIPTION:
XS GIS Cut Line= 3
      2763853.35      6893842.34      2763280.57      6894798.11
      2763337.40      6895581.29
#Sta/Elev= 30
  3945.6  502.19  3955.8  502.87  3971.4  501.92  4014.2  501.18  4305.8  499.70
  4342.7  499.11  4358.3  498.05  4387.1  498.22  4395.2  496.79  4527.0  491.42
  4533.3  489.60  4561.9  486.24  4766.6  486.45  4898.8  485.49  4935.0  486.08
  4984.3  485.51  4997.6  484.09  4998.1  483.59  5002.1  484.09  5005.7  485.63
  5021.3  486.43  5143.0  486.43  5313.4  488.06  5413.7  490.97  5479.6  494.03
  5574.1  495.64  5753.1  496.73  5758.1  496.19  5774.6  496.85  5845.1  495.93
#Mann=3,-1,0
  3945.6    0.05       0  4997.6    0.04       0  5002.1    0.05       0
Bank Sta=4997.6,5002.1
Exp/Cntr=0.3,0.1

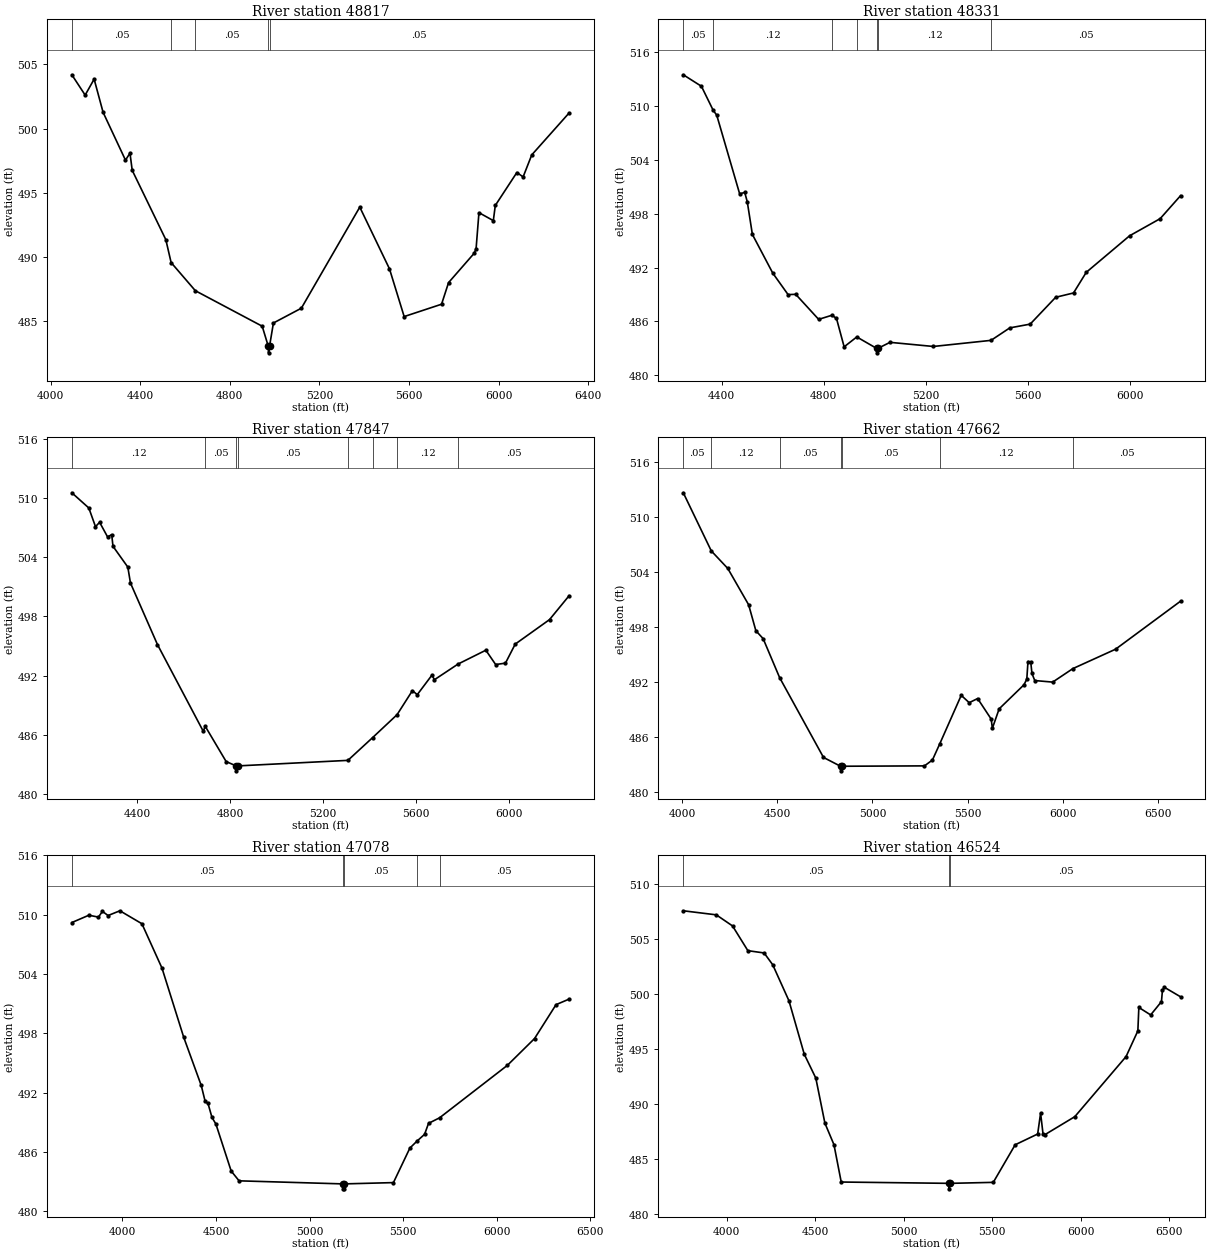
Type RM Length L Ch R = 1,48817,486,486,486
BEGIN DESCRIPTION:
Dry Lacy Fork 27
END DESCRIPTION:
XS GIS Cut Line= 3
      2763004.07      6893701.58      2763026.00      6894611.00
      2762653.95      6895866.86
#Sta/Elev= 30
  4094.8  504.18  4154.2  502.60  4194.3  503.84  4234.3  501.26  4334.3  497.54
  4354.3  498.09  4364.3  496.75  4514.3  491.36  4537.9  489.58  4646.1  487.39
  4944.5  484.63  4971.8  483.06  4972.6  482.56  4977.1  483.06  4994.5  484.88
  5119.2  486.03  5380.0  493.89  5512.6  489.09  5578.1  485.38  5745.0  486.34
  5776.3  488.02  5891.0  490.31  5899.2  490.67  5911.9  493.46  5976.1  492.84
  5984.9  494.02  6081.1  496.58  6109.1  496.24  6147.6  497.95  6314.3  501.21
#Mann=5,-1,0
  4094.8    0.05       0  4537.9    0.12       0  4646.1    0.05       0
  4971.8    0.04       0  4977.1    0.05       0
Bank Sta=4971.8,4977.1
Exp/Cntr=0.3,0.1

Type RM Length L Ch R = 1,48331,484,484,484
BEGIN DESCRIPTION:
Dry Lacy Fork 26
END DESCRIPTION:
XS GIS Cut Line= 3
      2762576.91      6893759.87      2762576.00      6894511.00
      2762576.00      6895710.97
#Sta/Elev= 30
  4248.9  513.48  4320.0  512.20  4366.4  509.51  4380.0  508.99  4470.0  500.22
  4490.0  500.37  4500.0  499.32  4520.0  495.69  4600.0  491.38  4660.0  488.99
  4690.0  489.02  4780.0  486.23  4832.3  486.69  4850.0  486.33  4880.0  483.17
  4929.6  484.27  5007.3  483.00  5008.1  482.50  5012.7  483.00  5060.0  483.67
  5230.0  483.21  5456.3  483.89  5530.0  485.28  5610.0  485.70  5710.0  488.69
  5780.0  489.17  5830.0  491.47  6000.0  495.54  6120.0  497.45  6200.0  500.01
#Mann=7,-1,0
  4248.9    0.05       0  4366.4    0.12       0  4832.3    0.05       0
  4929.6    0.12       0  5007.3    0.07       0  5012.7    0.12       0
  5456.3    0.05       0
Bank Sta=5007.3,5012.7
Exp/Cntr=0.3,0.1

Type RM Length L Ch R = 1,47847,185,185,185
BEGIN DESCRIPTION:
Dry Lacy Fork 25
END DESCRIPTION:
XS GIS Cut Line= 3
      2762481.31      6893710.72      2762126.00      6894511.00
      2762525.99      6895710.97
#Sta/Elev= 30
  4119.6  510.52  4192.7  508.98  4221.4  507.09  4239.2  507.53  4273.4  506.05
  4291.2  506.28  4296.7  505.10  4360.6  502.99  4371.9  501.38  4488.2  495.14
  4685.3  486.36  4693.9  486.86  4783.8  483.29  4827.0  482.85  4828.0  482.35
  4833.7  482.85  5307.9  483.41  5414.0  485.71  5519.6  488.04  5585.5  490.47
  5606.6  490.07  5669.8  492.05  5680.4  491.58  5782.2  493.17  5901.7  494.57
  5943.9  493.12  5986.1  493.26  6028.2  495.19  6175.8  497.67  6260.1  500.09
#Mann=8,-1,0
  4119.6    0.12       0  4693.9    0.05       0  4827.0    0.03       0
  4833.7    0.05       0  5307.9    0.12       0  5414.0     0.1       0
  5519.6    0.12       0  5782.2    0.05       0
Bank Sta=4827,4833.7
Exp/Cntr=0.3,0.1

Type RM Length L Ch R = 1,47662,584,584,584
BEGIN DESCRIPTION:
Dry Lacy Fork 2637
END DESCRIPTION:
XS GIS Cut Line= 3
      2762422.16      6893610.56      2761946.92      6894493.92
      2761017.45      6895810.13
#Sta/Elev= 30
  4005.6  512.62  4152.8  506.29  4239.6  504.38  4349.1  500.43  4387.2  497.60
  4425.4  496.74  4512.0  492.50  4742.7  483.81  4832.3  482.85  4833.4  482.35
  4839.7  482.85  5273.7  482.89  5315.5  483.53  5353.8  485.28  5466.9  490.57
  5508.8  489.77  5553.1  490.22  5624.5  487.98  5630.6  486.98  5666.3  489.10
  5796.9  491.72  5811.7  492.34  5817.8  494.25  5832.6  494.15  5838.7  492.95
  5853.5  492.18  5947.7  492.01  6053.9  493.48  6278.3  495.59  6620.0  500.82
#Mann=7,-1,0
  4005.6    0.05       0  4152.8    0.12       0  4512.0    0.05       0
  4832.3    0.03       0  4839.7    0.05       0  5353.8    0.12       0
  6053.9    0.05       0
Bank Sta=4832.3,4839.7
Exp/Cntr=0.3,0.1

Type RM Length L Ch R = 1,47078,554,554,554
BEGIN DESCRIPTION:
Dry Lacy Fork 2636
END DESCRIPTION:
XS GIS Cut Line= 3
      2762489.75      6893368.01      2761698.23      6893883.75
      2760774.16      6895326.10
#Sta/Elev= 30
  3729.6  509.20  3820.6  509.94  3871.9  509.75  3893.0  510.33  3923.2  509.91
  3986.5  510.39  4104.1  509.08  4211.5  504.59  4327.6  497.60  4421.2  492.73
  4442.3  491.11  4457.4  490.91  4478.5  489.50  4499.6  488.83  4581.2  484.08
  4623.4  483.09  5177.9  482.78  5179.1  482.28  5184.4  482.28  5185.5  482.78
  5448.4  482.91  5536.3  486.40  5574.0  487.10  5614.9  487.79  5636.0  488.90
  5694.9  489.46  6057.1  494.76  6202.5  497.47  6317.5  500.90  6387.3  501.46
#Mann=5,-1,0
  3729.6    0.05       0  5177.9    0.03       0  5185.5    0.05       0
  5574.0    0.12       0  5694.9    0.05       0
Bank Sta=5177.9,5185.5
Exp/Cntr=0.3,0.1

Type RM Length L Ch R = 1,46524,122,122,122
BEGIN DESCRIPTION:
Dry Lacy Fork 2550
END DESCRIPTION:
XS GIS Cut Line= 3
      2762486.55      6893316.01      2761390.49      6893562.01
      2760622.14      6895062.72
#Sta/Elev= 30
  3754.0  507.60  3940.4  507.23  4032.2  506.22  4118.8  503.97  4210.6  503.76
  4259.1  502.69  4350.9  499.41  4437.5  494.54  4502.7  492.37  4554.0  488.27
  4605.2  486.31  4646.2  482.91  5254.3  482.79  5255.4  482.29  5262.1  482.79
  5505.3  482.88  5628.9  486.30  5756.0  487.28  5772.6  489.18  5786.2  487.31
  5794.8  487.20  5965.9  488.86  6255.5  494.33  6322.1  496.67  6327.7  498.80
  6394.4  498.12  6455.4  499.33  6461.0  500.36  6471.5  500.64  6563.3  499.77
#Mann=3,-1,0
  3754.0    0.05       0  5254.3    0.03       0  5262.1    0.05       0
Bank Sta=5254.3,5262.1
Exp/Cntr=0.3,0.1