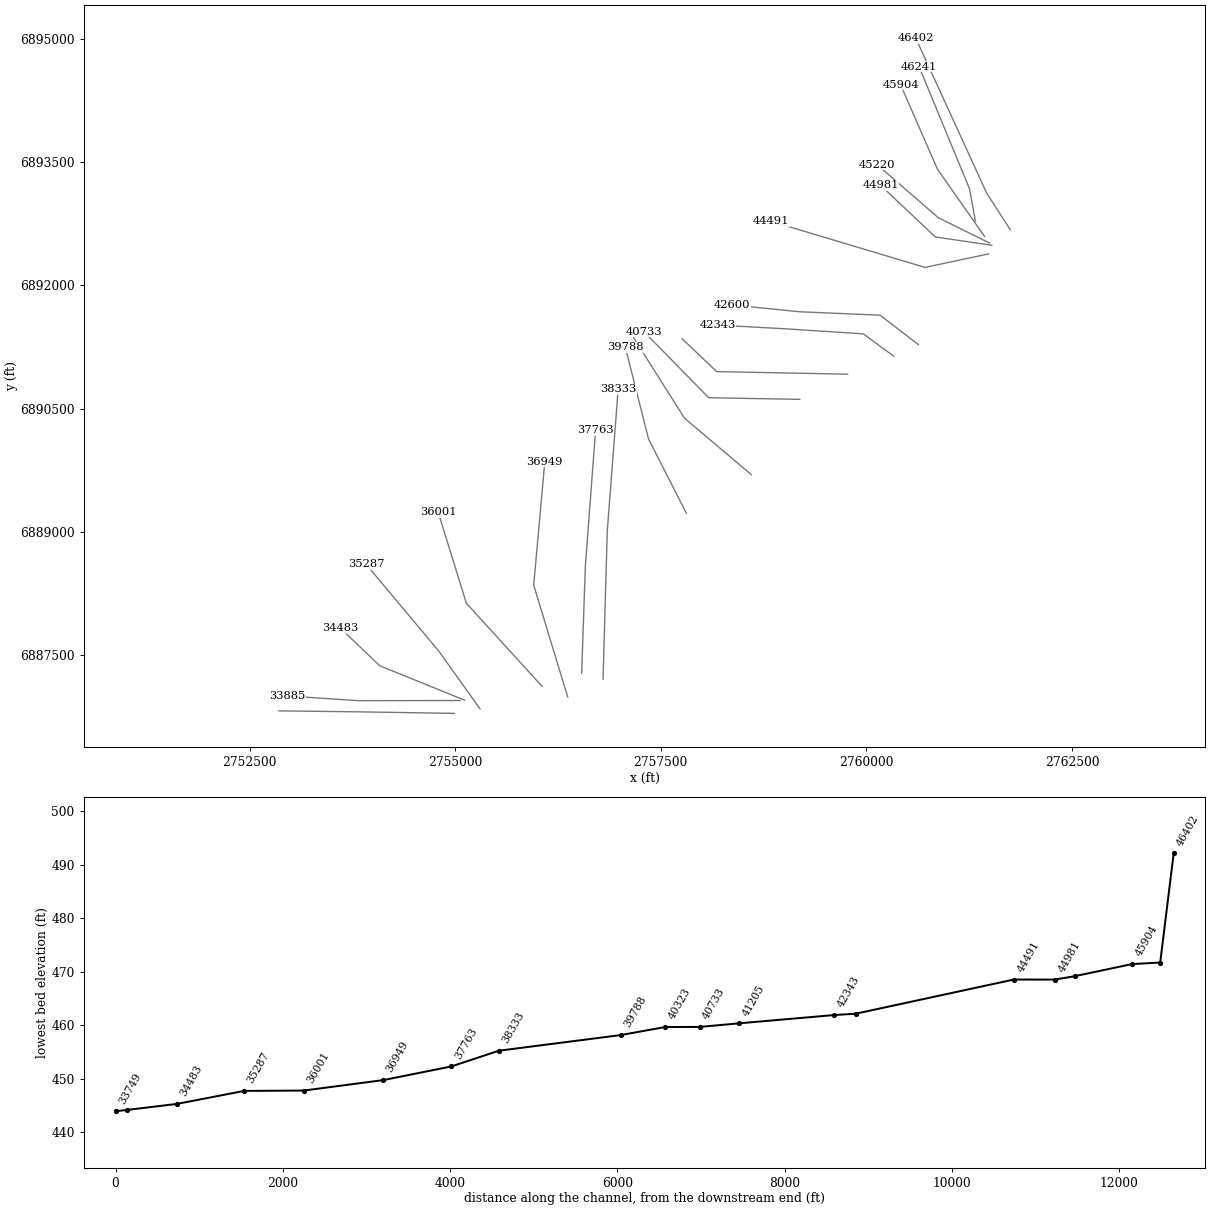
HEC-RAS study Dry Lacy Fork.prj: Dry Lacy Fork Base Level Engineering

--- Dry Lacy Fork.g01 (geometry) --- (continued)

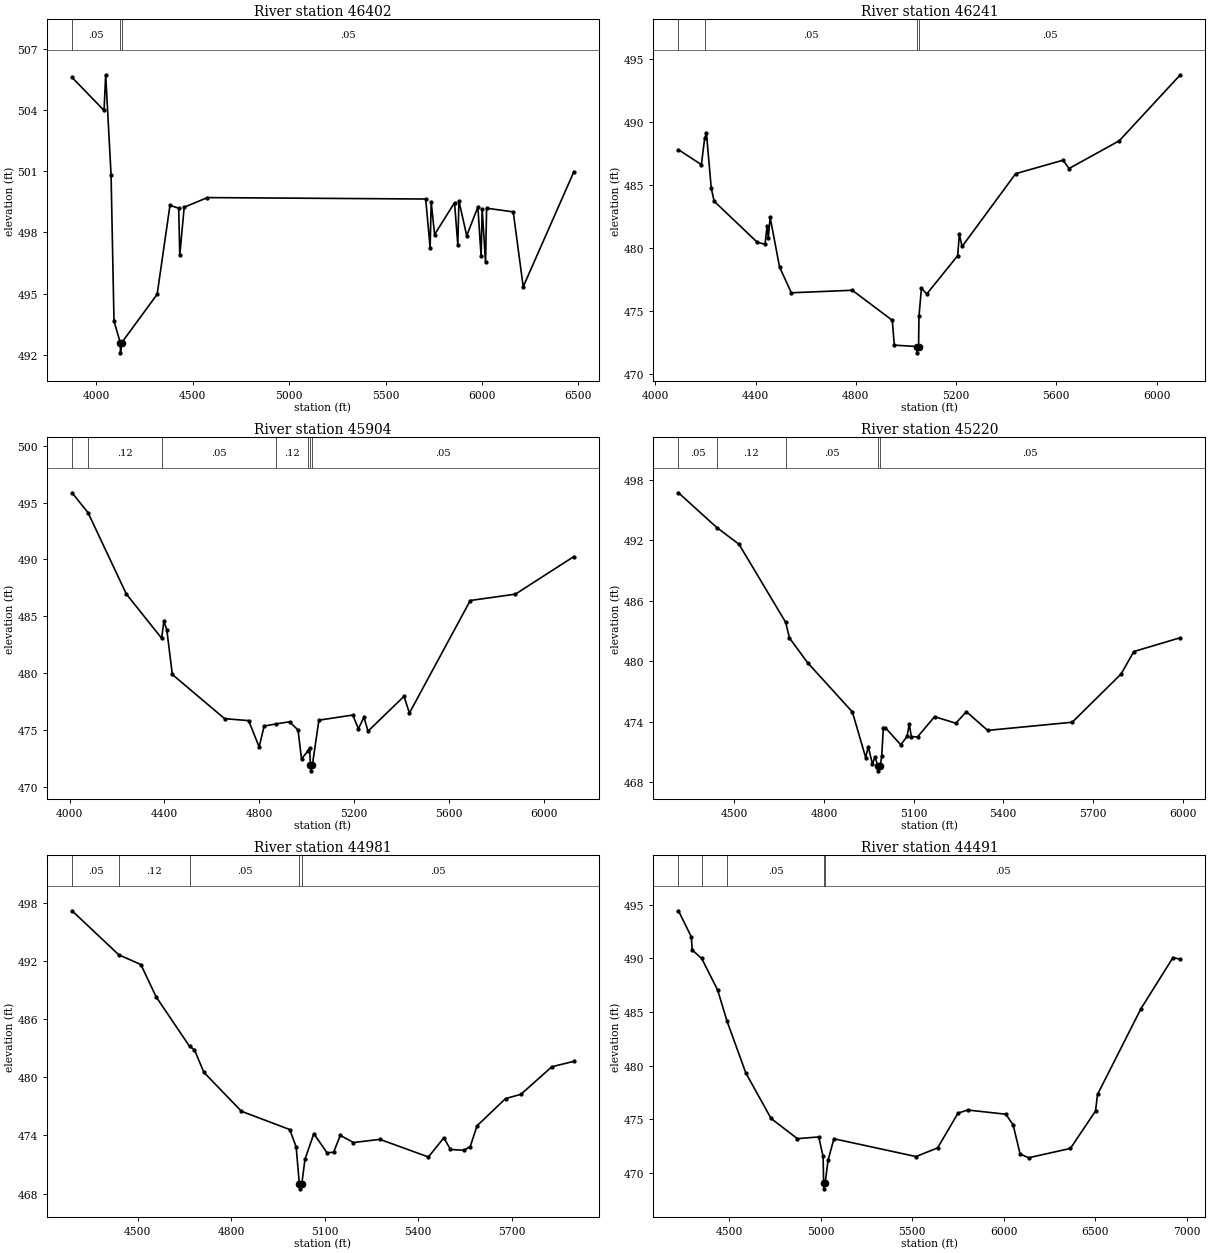
Type RM Length L Ch R = 1,46402,161,161,161
BEGIN DESCRIPTION:
Dry Lacy Fork 2549
END DESCRIPTION:
XS GIS Cut Line= 3
      2761749.58      6892674.62      2761463.71      6893117.86
      2760601.02      6895003.78
#Sta/Elev= 30
  3875.1  505.60  4040.9  503.98  4049.3  505.73  4077.2  500.84  4092.4  493.66
  4124.8  492.60  4126.0  492.10  4132.6  492.60  4316.2  494.97  4382.5  499.33
  4427.8  499.19  4433.3  496.89  4456.3  499.24  4576.9  499.71  5708.1  499.64
  5731.1  497.25  5736.6  499.49  5754.2  497.90  5857.5  499.46  5874.7  497.37
  5880.2  499.55  5920.8  497.84  5978.5  499.25  5995.3  496.83  6000.8  499.16
  6018.3  496.53  6023.8  499.19  6161.9  499.01  6213.5  495.34  6476.4  500.98
#Mann=3,-1,0
  3875.1    0.05       0  4124.8    0.04       0  4132.6    0.05       0
Bank Sta=4124.8,4132.6
Exp/Cntr=0.3,0.1

Type RM Length L Ch R = 1,46241,337,337,337
BEGIN DESCRIPTION:
Dry Lacy Fork 2551
END DESCRIPTION:
XS GIS Cut Line= 3
      2761325.28      6892781.11      2761253.34      6893173.32
      2760641.41      6894656.16
#Sta/Elev= 30
  4092.1  487.79  4183.5  486.61  4196.7  488.71  4203.8  489.08  4222.9  484.74
  4234.3  483.71  4407.2  480.44  4437.7  480.31  4445.6  481.73  4450.6  480.79
  4458.0  482.43  4495.4  478.50  4542.4  476.45  4785.6  476.65  4945.4  474.27
  4953.5  472.30  5042.6  472.19  5043.7  471.69  5050.4  472.19  5051.9  474.58
  5061.7  476.80  5083.3  476.36  5206.3  479.39  5213.2  481.08  5224.0  480.12
  5437.8  485.89  5626.9  486.96  5650.9  486.30  5851.4  488.50  6095.0  493.73
#Mann=4,-1,0
  4092.1    0.12       0  4196.7    0.05       0  5042.6    0.04       0
  5050.4    0.05       0
Bank Sta=5042.6,5050.4
Exp/Cntr=0.3,0.1

Type RM Length L Ch R = 1,45904,684,684,684
BEGIN DESCRIPTION:
Dry Lacy Fork 2552
END DESCRIPTION:
XS GIS Cut Line= 3
      2761436.23      6892593.30      2760862.40      6893414.85
      2760416.24      6894437.33
#Sta/Elev= 30
  4010.4  495.87  4077.8  494.12  4239.4  486.96  4388.3  483.07  4397.8  484.56
  4410.1  483.81  4433.5  479.88  4654.2  475.99  4755.4  475.82  4799.9  473.50
  4820.8  475.34  4871.1  475.53  4928.1  475.72  4963.8  474.99  4978.7  472.45
  5004.9  473.13  5012.5  473.42  5016.4  471.90  5017.6  471.40  5024.3  471.90
  5052.0  475.86  5195.1  476.31  5218.6  475.10  5242.0  476.12  5259.3  474.89
  5411.3  477.96  5433.8  476.48  5690.7  486.39  5881.2  486.95  6128.1  490.26
#Mann=7,-1,0
  4010.4    0.05       0  4077.8    0.12       0  4388.3    0.05       0
  4871.1    0.12       0  5004.9    0.05       0  5016.4    0.07       0
  5024.3    0.05       0
Bank Sta=5016.4,5024.3
Exp/Cntr=0.3,0.1

Type RM Length L Ch R = 1,45220,239,239,239
BEGIN DESCRIPTION:
Dry Lacy Fork 2554
END DESCRIPTION:
XS GIS Cut Line= 3
      2761497.42      6892513.27      2760873.25      6892821.97
      2760131.56      6893466.13
#Sta/Elev= 30
  4313.6  496.71  4442.4  493.25  4516.0  491.61  4672.1  483.87  4684.8  482.31
  4746.5  479.83  4895.3  474.98  4939.9  470.45  4948.4  471.55  4962.2  469.83
  4970.9  470.51  4980.6  469.64  4981.8  469.14  4988.5  469.64  4993.3  470.57
  4998.9  473.37  5005.6  473.42  5057.2  471.72  5078.1  472.55  5085.7  473.78
  5092.4  472.54  5113.2  472.50  5170.2  474.51  5241.5  473.86  5276.6  475.01
  5347.8  473.15  5630.8  473.96  5794.1  478.74  5836.8  480.97  5992.3  482.34
#Mann=5,-1,0
  4313.6    0.05       0  4442.4    0.12       0  4672.1    0.05       0
  4980.6    0.04       0  4988.5    0.05       0
Bank Sta=4980.6,4988.5
Exp/Cntr=0.3,0.1

Type RM Length L Ch R = 1,44981,490,490,490
BEGIN DESCRIPTION:
Dry Lacy Fork 2553
END DESCRIPTION:
XS GIS Cut Line= 3
      2761524.48      6892486.21      2760838.53      6892587.17
      2760171.26      6893216.25
#Sta/Elev= 30
  4289.7  497.15  4439.7  492.61  4510.5  491.61  4559.5  488.28  4666.9  483.17
  4682.4  482.83  4712.7  480.50  4833.3  476.49  4988.2  474.61  5008.8  472.81
  5019.0  469.00  5020.2  468.50  5026.9  469.00  5037.1  471.56  5065.5  474.18
  5107.9  472.22  5129.0  472.27  5150.4  474.01  5192.7  473.27  5277.4  473.60
  5433.2  471.78  5482.6  473.76  5504.0  472.56  5546.5  472.47  5567.5  472.86
  5589.0  474.99  5680.8  477.80  5730.2  478.24  5829.3  481.08  5900.1  481.64
#Mann=5,-1,0
  4289.7    0.05       0  4439.7    0.12       0  4666.9    0.05       0
  5019.0    0.04       0  5026.9    0.05       0
Bank Sta=5019,5026.9
Exp/Cntr=0.3,0.1

Type RM Length L Ch R = 1,44491,1891,1891,1891
BEGIN DESCRIPTION:
Dry Lacy Fork 3462
END DESCRIPTION:
XS GIS Cut Line= 3
      2761485.99      6892381.35      2760712.65      6892216.94
      2758842.01      6892777.33
#Sta/Elev= 30
  4221.6  494.44  4291.7  492.01  4296.8  490.78  4348.6  489.99  4435.4  487.06
  4487.6  484.12  4589.6  479.32  4727.9  475.07  4871.6  473.19  4988.4  473.35
  5012.2  471.53  5015.2  469.01  5016.4  468.51  5023.2  469.01  5039.3  471.18
  5071.4  473.18  5520.2  471.52  5638.2  472.33  5749.9  475.57  5802.1  475.86
  6010.9  475.47  6050.9  474.48  6089.2  471.76  6136.1  471.41  6364.3  472.28
  6501.5  475.77  6512.3  477.31  6749.1  485.29  6924.9  490.08  6965.0  489.92
#Mann=5,-1,0
  4221.6    0.05       0  4348.6    0.12       0  4487.6    0.05       0
  5015.2    0.04       0  5023.2    0.05       0
Bank Sta=5015.2,5023.2
Exp/Cntr=0.3,0.1

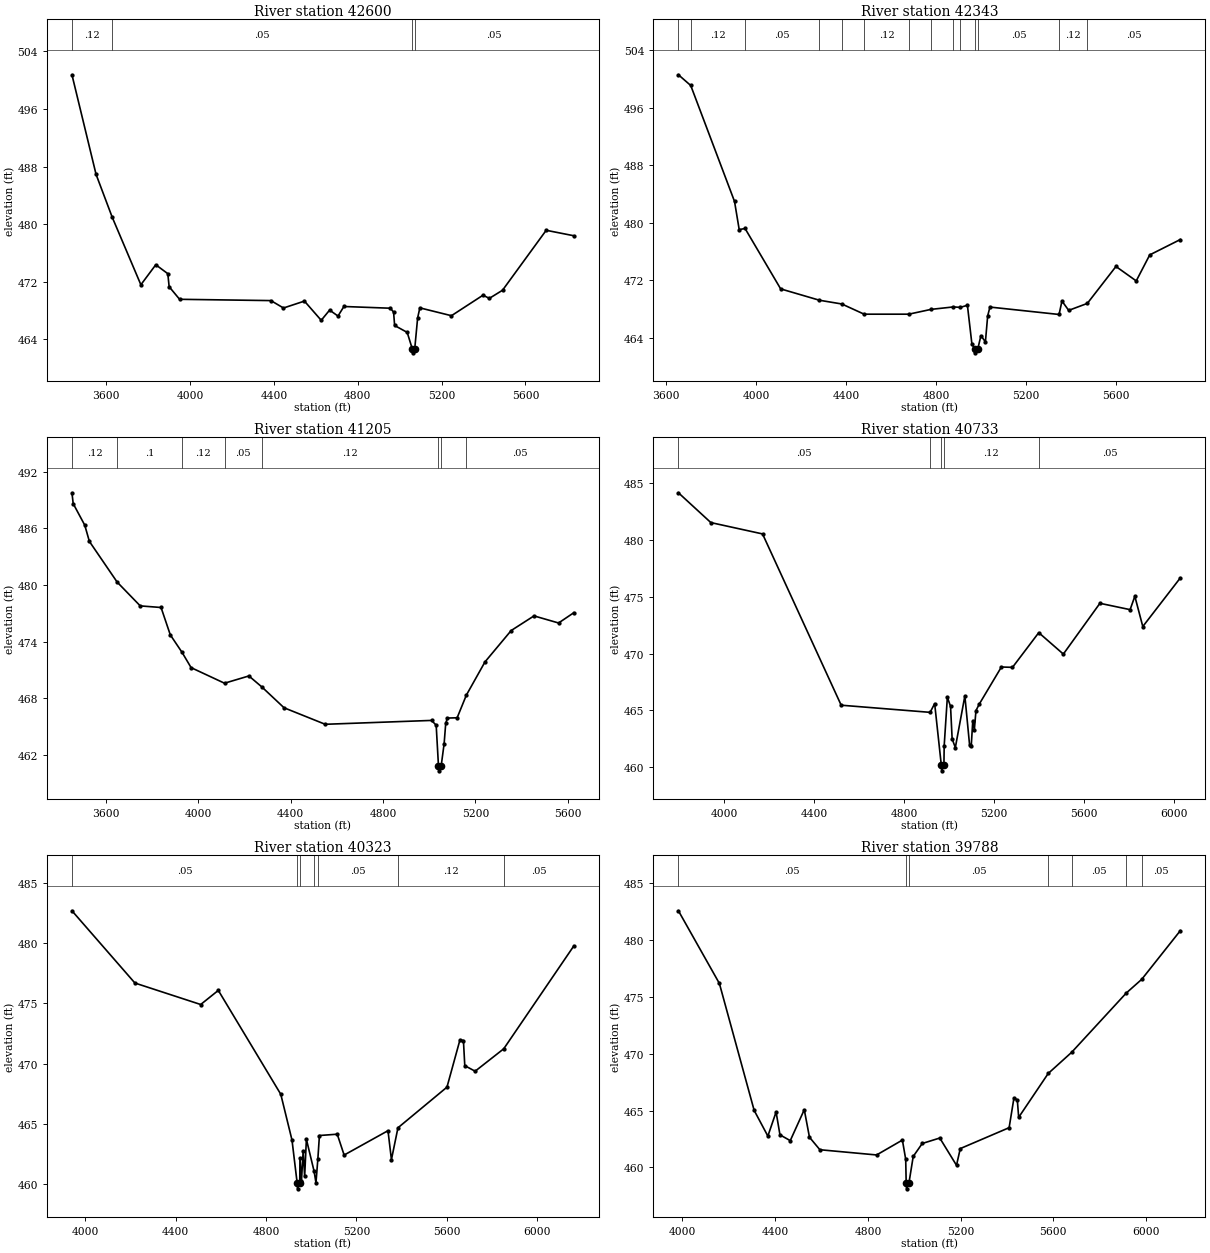
Type RM Length L Ch R = 1,42600,257,257,257
BEGIN DESCRIPTION:
Dry Lacy Fork 2351
END DESCRIPTION:
XS GIS Cut Line= 4
      2760632.99      6891276.34      2760166.55      6891635.54
      2759186.75      6891677.46      2758364.64      6891760.40
#Sta/Elev= 30
  3435.7  500.76  3550.8  486.92  3627.7  480.98  3764.7  471.58  3835.8  474.36
  3893.3  473.12  3899.6  471.31  3949.5  469.56  4385.3  469.38  4445.4  468.35
  4545.4  469.31  4625.5  466.64  4665.6  468.06  4705.6  467.23  4733.8  468.56
  4955.8  468.32  4970.9  467.78  4975.9  465.92  5036.0  464.96  5060.7  462.62
  5062.2  462.12  5071.7  462.62  5085.7  466.97  5096.3  468.37  5247.1  467.28
  5397.8  470.13  5428.0  469.69  5491.0  470.82  5699.4  479.15  5831.4  478.39
#Mann=4,-1,0
  3435.7    0.12       0  3627.7    0.05       0  5060.7    0.05       0
  5071.7    0.05       0
Bank Sta=5060.7,5071.7
Exp/Cntr=0.3,0.1

Type RM Length L Ch R = 1,42343,1138,1138,1138
BEGIN DESCRIPTION:
Dry Lacy Fork 2349
END DESCRIPTION:
XS GIS Cut Line= 4
      2760331.26      6891137.37      2759963.33      6891408.21
      2759072.73      6891466.42      2758190.08      6891515.77
#Sta/Elev= 30
  3654.2  500.57  3709.0  499.08  3903.9  482.94  3924.7  479.02  3950.7  479.18
  4109.2  470.77  4281.8  469.19  4381.2  468.67  4480.6  467.25  4679.3  467.25
  4778.7  467.92  4878.0  468.26  4908.6  468.20  4940.2  468.49  4960.2  463.09
  4974.5  462.37  4976.1  461.87  4986.0  462.37  5000.3  464.26  5020.3  463.40
  5030.3  467.00  5040.4  468.24  5348.0  467.21  5360.9  469.08  5390.9  467.78
  5473.8  468.75  5601.2  473.89  5691.4  471.88  5751.5  475.50  5887.6  477.64
#Mann=14,-1,0
  3654.2    0.05       0  3709.0    0.12       0  3950.7    0.05       0
  4281.8    0.12       0  4381.2     0.1       0  4480.6    0.12       0
  4679.3     0.1       0  4778.7    0.12       0  4878.0     0.1       0
  4908.6    0.05       0  4974.5    0.05       0  4986.0    0.05       0
  5348.0    0.12       0  5473.8    0.05       0
Bank Sta=4974.5,4986
Exp/Cntr=0.3,0.1

Type RM Length L Ch R = 1,41205,472,472,472
BEGIN DESCRIPTION:
Dry Lacy Fork 2350
END DESCRIPTION:
XS GIS Cut Line= 3
      2759771.39      6890918.03      2758179.58      6890949.32
      2757759.80      6891348.36
#Sta/Elev= 30
  3454.2  489.77  3459.6  488.62  3509.6  486.34  3529.6  484.62  3649.8  480.31
  3749.6  477.79  3839.7  477.62  3879.7  474.72  3930.7  472.86  3969.7  471.25
  4114.2  469.60  4219.7  470.37  4276.9  469.18  4371.7  467.00  4549.8  465.25
  5009.9  465.66  5029.9  465.15  5039.9  460.82  5041.4  460.32  5051.4  460.82
  5064.3  463.20  5071.2  465.35  5078.5  465.91  5120.6  465.94  5160.5  468.34
  5241.1  471.86  5354.4  475.18  5453.1  476.73  5559.4  475.98  5625.5  477.07
#Mann=8,-1,0
  3454.2    0.12       0  3649.8     0.1       0  3930.7    0.12       0
  4114.2    0.05       0  4276.9    0.12       0  5039.9    0.07       0
  5051.4    0.12       0  5160.5    0.05       0
Bank Sta=5039.9,5051.4
Exp/Cntr=0.3,0.1

Type RM Length L Ch R = 1,40733,410,410,410
BEGIN DESCRIPTION:
Dry Lacy Fork 2352
END DESCRIPTION:
XS GIS Cut Line= 3
      2759190.33      6890611.59      2758082.45      6890631.76
      2757294.46      6891435.58
#Sta/Elev= 30
  3796.6  484.18  3941.0  481.55  4171.0  480.55  4521.0  465.44  4916.8  464.81
  4937.0  465.58  4966.6  460.15  4968.2  459.65  4978.2  460.15  4979.4  461.86
  4993.5  466.15  5007.7  465.33  5014.8  462.47  5029.0  461.70  5071.4  466.26
  5092.5  461.92  5099.7  461.82  5106.7  464.08  5113.7  463.28  5120.8  464.96
  5135.0  465.52  5234.0  468.81  5283.4  468.78  5400.3  471.84  5509.7  469.95
  5672.5  474.43  5806.8  473.87  5827.9  475.05  5863.3  472.38  6030.3  476.67
#Mann=5,-1,0
  3796.6    0.05       0  4916.8    0.12       0  4966.6    0.07       0
  4978.2    0.12       0  5400.3    0.05       0
Bank Sta=4966.6,4978.2
Exp/Cntr=0.3,0.1

Type RM Length L Ch R = 1,40323,535,535,535
BEGIN DESCRIPTION:
Dry Lacy Fork 2353
END DESCRIPTION:
XS GIS Cut Line= 3
      2758602.12      6889694.53      2757788.18      6890382.56
      2757170.39      6891360.13
#Sta/Elev= 30
  3940.7  482.68  4219.5  476.69  4510.7  474.91  4588.7  476.08  4865.3  467.47
  4915.0  463.67  4937.7  460.13  4939.4  459.63  4949.4  460.13  4950.1  462.20
  4957.0  460.32  4964.4  462.77  4971.0  460.66  4978.7  463.74  5012.9  461.08
  5021.1  460.13  5029.6  462.14  5036.4  464.05  5115.3  464.16  5145.8  462.43
  5340.0  464.45  5355.2  462.05  5384.1  464.69  5601.1  468.06  5658.8  471.99
  5674.0  471.92  5680.0  469.84  5725.8  469.38  5852.5  471.24  6162.9  479.77
#Mann=7,-1,0
  3940.7    0.05       0  4937.7    0.04       0  4949.4    0.05       0
  5012.9    0.12       0  5029.6    0.05       0  5384.1    0.12       0
  5852.5    0.05       0
Bank Sta=4937.7,4949.4
Exp/Cntr=0.3,0.1

Type RM Length L Ch R = 1,39788,1455,1455,1455
BEGIN DESCRIPTION:
Dry Lacy Fork 2354
END DESCRIPTION:
XS GIS Cut Line= 3
      2757810.42      6889227.05      2757350.98      6890129.88
      2757068.32      6891247.07
#Sta/Elev= 30
  3982.4  482.58  4159.1  476.19  4309.2  465.02  4368.3  462.76  4403.8  464.88
  4420.5  462.87  4464.9  462.36  4525.4  465.08  4547.8  462.66  4592.7  461.56
  4837.5  461.10  4948.7  462.41  4963.0  460.72  4965.1  458.62  4966.7  458.12
  4976.9  458.62  4995.4  460.97  5034.4  462.11  5110.0  462.59  5182.2  460.19
  5198.4  461.66  5409.2  463.50  5429.8  466.09  5444.5  465.95  5450.4  464.41
  5577.9  468.27  5679.0  470.13  5914.9  475.35  5981.3  476.55  6147.8  480.83
#Mann=7,-1,0
  3982.4    0.05       0  4965.1    0.04       0  4976.9    0.05       0
  5577.9    0.12       0  5679.0    0.05       0  5914.9    0.12       0
  5981.3    0.05       0
Bank Sta=4965.1,4976.9
Exp/Cntr=0.3,0.1

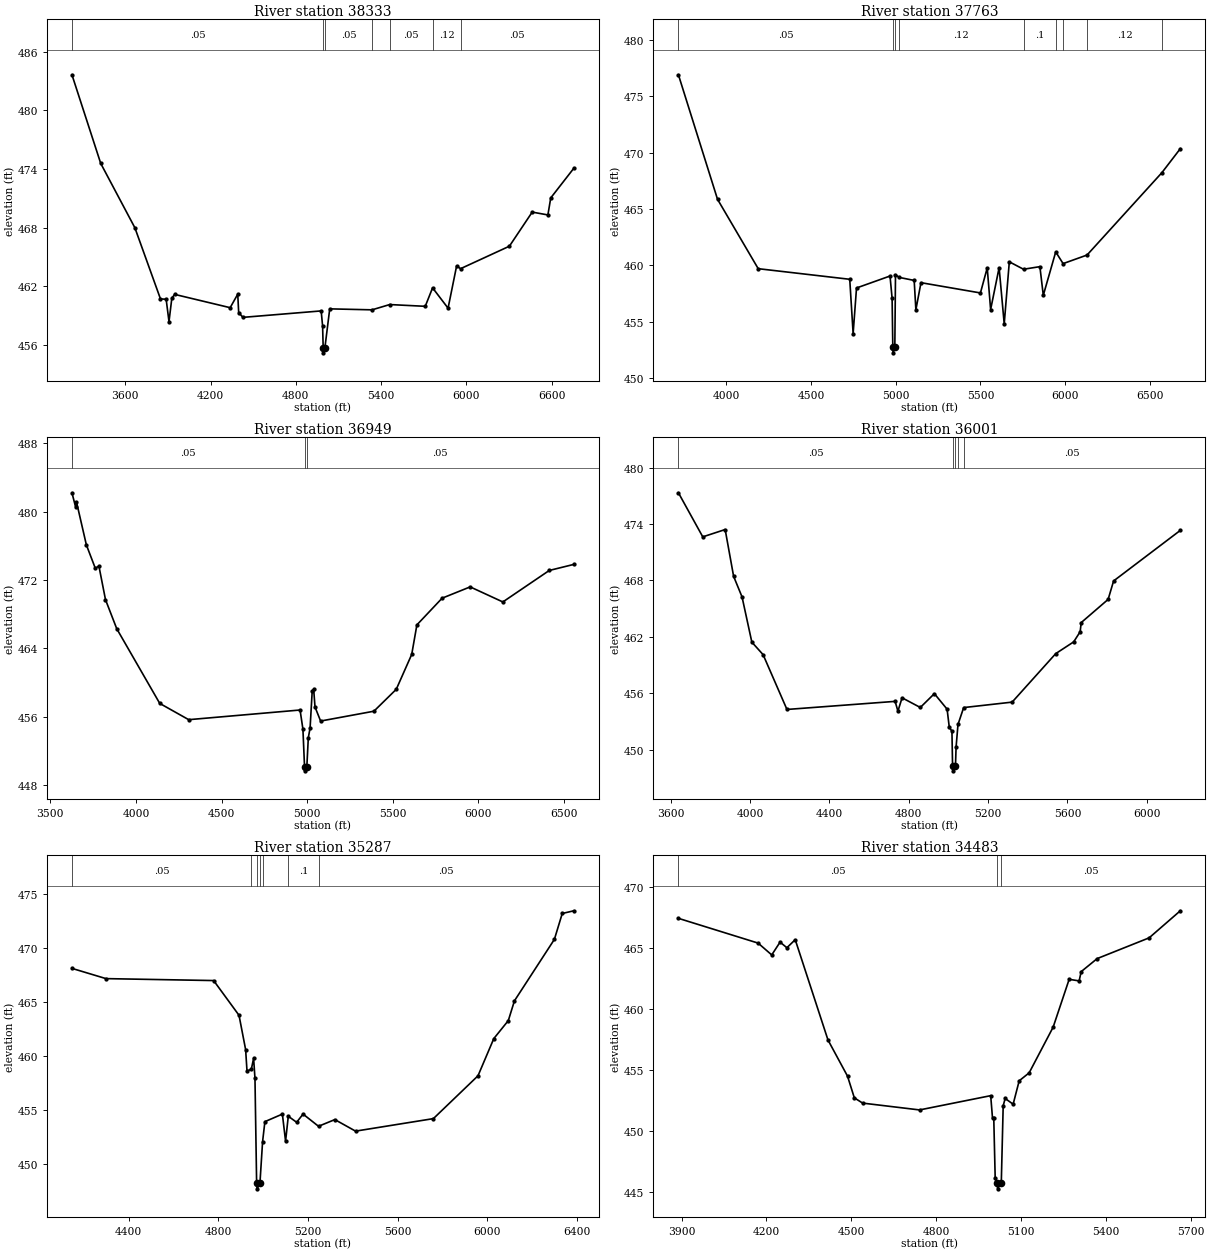
Type RM Length L Ch R = 1,38333,570,570,570
BEGIN DESCRIPTION:
Dry Lacy Fork 2347
END DESCRIPTION:
XS GIS Cut Line= 3
      2756797.88      6887208.70      2756849.11      6889008.86
      2756981.57      6890733.09
#Sta/Elev= 30
  3225.3  483.65  3427.7  474.58  3667.8  468.00  3847.9  460.72  3887.9  460.68
  3907.9  458.40  3927.9  460.80  3947.9  461.18  4338.1  459.82  4391.4  461.20
  4398.1  459.31  4428.1  458.83  4978.3  459.49  4988.3  457.94  4992.4  455.70
  4994.0  455.20  5004.3  455.70  5038.4  459.70  5335.9  459.60  5460.5  460.14
  5710.3  459.96  5761.8  461.85  5870.8  459.77  5931.0  464.10  5958.6  463.81
  6302.1  466.11  6462.6  469.60  6572.9  469.31  6592.9  471.05  6755.5  474.09
#Mann=7,-1,0
  3225.3    0.05       0  4992.4    0.05       0  5004.3    0.05       0
  5335.9    0.12       0  5460.5    0.05       0  5761.8    0.12       0
  5958.6    0.05       0
Bank Sta=4992.4,5004.3
Exp/Cntr=0.3,0.1

Type RM Length L Ch R = 1,37763,814,814,814
BEGIN DESCRIPTION:
Dry Lacy Fork 2346
END DESCRIPTION:
XS GIS Cut Line= 3
      2756537.57      6887280.23      2756582.89      6888585.87
      2756707.44      6890237.65
#Sta/Elev= 30
  3717.4  476.90  3948.3  465.86  4188.5  459.71  4728.8  458.77  4748.8  453.96
  4768.8  458.00  4966.6  459.06  4978.9  457.08  4983.0  452.75  4984.6  452.25
  4994.9  452.75  4998.9  459.18  5019.8  458.94  5109.2  458.67  5119.2  456.07
  5149.3  458.47  5500.3  457.56  5540.4  459.78  5560.5  456.09  5610.6  459.80
  5640.7  454.82  5670.8  460.32  5754.6  459.66  5851.3  459.89  5871.4  457.35
  5944.8  461.20  5988.3  460.16  6129.6  460.92  6571.4  468.22  6680.3  470.35
#Mann=9,-1,0
  3717.4    0.05       0  4983.0    0.04       0  4994.9    0.05       0
  5019.8    0.12       0  5754.6     0.1       0  5944.8    0.12       0
  5988.3     0.1       0  6129.6    0.12       0  6571.4    0.05       0
Bank Sta=4983,4994.9
Exp/Cntr=0.3,0.1

Type RM Length L Ch R = 1,36949,948,948,948
BEGIN DESCRIPTION:
Dry Lacy Fork 2348
END DESCRIPTION:
XS GIS Cut Line= 3
      2756368.57      6886990.43      2755954.51      6888351.07
      2756089.84      6889854.04
#Sta/Elev= 30
  3626.1  482.20  3647.2  480.56  3652.5  481.14  3710.3  476.11  3762.6  473.37
  3783.5  473.64  3822.0  469.71  3887.7  466.31  4138.9  457.58  4308.0  455.68
  4958.4  456.81  4975.1  454.57  4984.4  450.20  4986.4  449.70  4998.0  450.20
  5006.5  453.56  5016.9  454.71  5029.3  459.02  5037.8  459.24  5045.7  457.16
  5078.4  455.52  5389.7  456.67  5520.2  459.23  5610.5  463.31  5640.7  466.76
  5788.0  469.88  5951.9  471.20  6142.7  469.44  6413.8  473.12  6557.4  473.83
#Mann=3,-1,0
  3626.1    0.05       0  4984.4    0.04       0  4998.0    0.05       0
Bank Sta=4984.4,4998
Exp/Cntr=0.3,0.1

Type RM Length L Ch R = 1,36001,714,714,714
BEGIN DESCRIPTION:
Dry Lacy Fork 2344
END DESCRIPTION:
XS GIS Cut Line= 3
      2756057.37      6887119.20      2755135.21      6888132.42
      2754792.87      6889241.14
#Sta/Elev= 30
  3638.4  477.33  3761.2  472.64  3874.1  473.42  3916.7  468.44  3959.2  466.25
  4008.6  461.44  4065.3  460.11  4185.6  454.28  4730.9  455.14  4745.1  454.10
  4766.0  455.52  4857.9  454.49  4928.8  455.96  4993.0  454.31  5004.1  452.37
  5017.4  451.97  5020.6  448.25  5022.6  447.75  5035.2  448.25  5038.3  450.28
  5047.9  452.68  5076.5  454.48  5320.9  455.06  5540.7  460.22  5631.2  461.47
  5663.9  462.55  5669.1  463.52  5804.9  465.99  5832.4  467.95  6168.8  473.33
#Mann=5,-1,0
  3638.4    0.05       0  5020.6    0.04       0  5035.2    0.05       0
  5047.9    0.12       0  5076.5    0.05       0
Bank Sta=5020.6,5035.2
Exp/Cntr=0.3,0.1

Type RM Length L Ch R = 1,35287,804,804,804
BEGIN DESCRIPTION:
Dry Lacy Fork 2345
END DESCRIPTION:
XS GIS Cut Line= 3
      2755302.18      6886846.26      2754800.99      6887548.47
      2753917.18      6888605.03
#Sta/Elev= 30
  4146.8  468.12  4298.8  467.17  4779.2  466.99  4892.5  463.77  4922.0  460.59
  4928.1  458.61  4947.4  458.76  4957.6  459.78  4963.7  457.93  4971.1  448.18
  4973.1  447.68  4985.8  448.18  4997.7  452.06  5008.0  453.91  5086.0  454.61
  5100.3  452.10  5112.4  454.41  5149.7  453.85  5178.4  454.61  5247.3  453.48
  5320.2  454.10  5412.6  453.03  5760.0  454.19  5959.1  458.16  6029.7  461.61
  6094.5  463.28  6121.8  465.11  6300.1  470.81  6335.2  473.21  6387.0  473.46
#Mann=7,-1,0
  4146.8    0.05       0  4947.4     0.1       0  4971.1    0.07       0
  4985.8     0.1       0  4997.7    0.12       0  5112.4     0.1       0
  5247.3    0.05       0
Bank Sta=4971.1,4985.8
Exp/Cntr=0.3,0.1

Type RM Length L Ch R = 1,34483,598,598,598
BEGIN DESCRIPTION:
Dry Lacy Fork 2343
END DESCRIPTION:
XS GIS Cut Line= 3
      2755116.24      6886951.73      2754082.81      6887370.84
      2753605.67      6887826.43
#Sta/Elev= 30
  3889.0  467.43  4170.8  465.40  4219.0  464.43  4248.5  465.48  4272.6  465.02
  4302.1  465.68  4418.0  457.45  4487.0  454.49  4511.1  452.71  4540.5  452.28
  4741.8  451.72  4993.3  452.89  4999.8  451.03  5004.2  451.03  5009.2  446.15
  5015.8  445.75  5017.8  445.25  5030.8  445.75  5037.5  452.06  5044.4  452.66
  5072.7  452.19  5094.1  454.11  5129.3  454.76  5214.2  458.51  5270.8  462.43
  5306.1  462.30  5313.3  463.06  5369.9  464.13  5553.6  465.83  5663.9  468.05
#Mann=3,-1,0
  3889.0    0.05       0  5015.8    0.04       0  5030.8    0.05       0
Bank Sta=5015.8,5030.8
Exp/Cntr=0.3,0.1

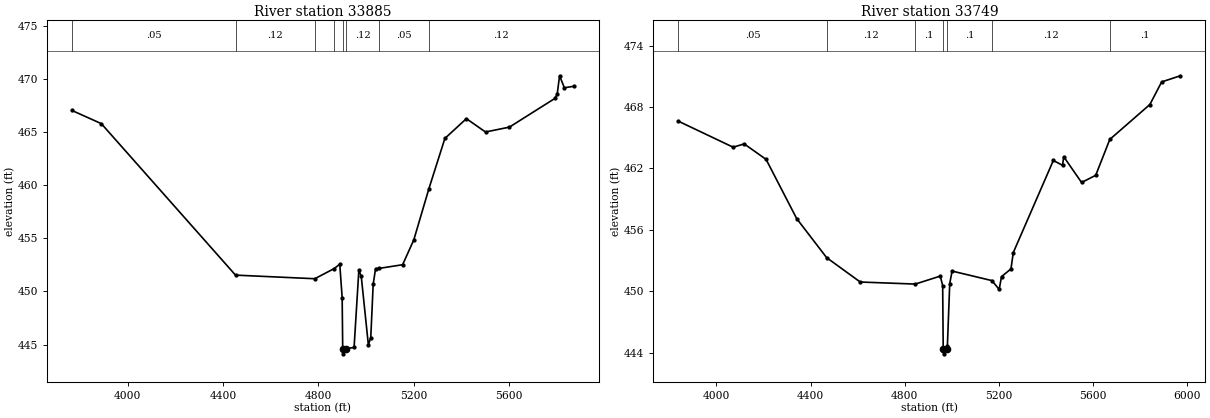
Type RM Length L Ch R = 1,33885,136,136,136
BEGIN DESCRIPTION:
Dry Lacy Fork 2342
END DESCRIPTION:
XS GIS Cut Line= 3
      2755059.11      6886947.75      2753822.44      6886946.29
      2752956.28      6887003.22
#Sta/Elev= 30
  3767.0  467.06  3890.1  465.82  4452.9  451.54  4785.3  451.20  4866.9  452.16
  4890.1  452.57  4900.1  449.41  4902.4  444.62  4904.4  444.12  4917.8  444.62
  4950.1  444.72  4970.1  452.01  4980.1  451.44  5010.1  444.95  5020.1  445.66
  5030.2  450.68  5040.2  452.15  5053.7  452.17  5153.6  452.52  5200.5  454.86
  5263.9  459.69  5330.8  464.42  5421.0  466.29  5501.2  465.03  5601.4  465.49
  5791.8  468.19  5801.8  468.59  5811.8  470.33  5831.9  469.20  5871.7  469.34
#Mann=8,-1,0
  3767.0    0.05       0  4452.9    0.12       0  4785.3    0.05       0
  4866.9    0.12       0  4902.4    0.07       0  4917.8    0.12       0
  5053.7    0.05       0  5263.9    0.12       0
Bank Sta=4902.4,4917.8
Exp/Cntr=0.3,0.1

Type RM Length L Ch R = 1,33749,713,713,713
BEGIN DESCRIPTION:
Dry Lacy Fork 2326
END DESCRIPTION:
XS GIS Cut Line= 3
      2754988.24      6886791.45      2753810.51      6886810.48
      2752856.66      6886821.99
#Sta/Elev= 30
  3838.7  466.62  4071.0  464.08  4118.1  464.40  4211.0  462.89  4341.0  457.10
  4468.4  453.28  4611.0  450.90  4844.8  450.70  4951.1  451.48  4961.1  450.54
  4963.4  444.38  4965.4  443.88  4978.8  444.38  4981.1  444.64  4991.1  450.75
  5001.1  451.97  5170.1  451.04  5201.1  450.18  5211.1  451.43  5251.1  452.18
  5261.1  453.78  5431.1  462.78  5470.2  462.31  5475.2  463.15  5551.1  460.63
  5611.1  461.33  5671.0  464.84  5841.2  468.25  5891.2  470.46  5970.5  471.06
#Mann=7,-1,0
  3838.7    0.05       0  4468.4    0.12       0  4844.8     0.1       0
  4963.4    0.07       0  4978.8     0.1       0  5170.1    0.12       0
  5671.0     0.1       0
Bank Sta=4963.4,4978.8
Exp/Cntr=0.3,0.1