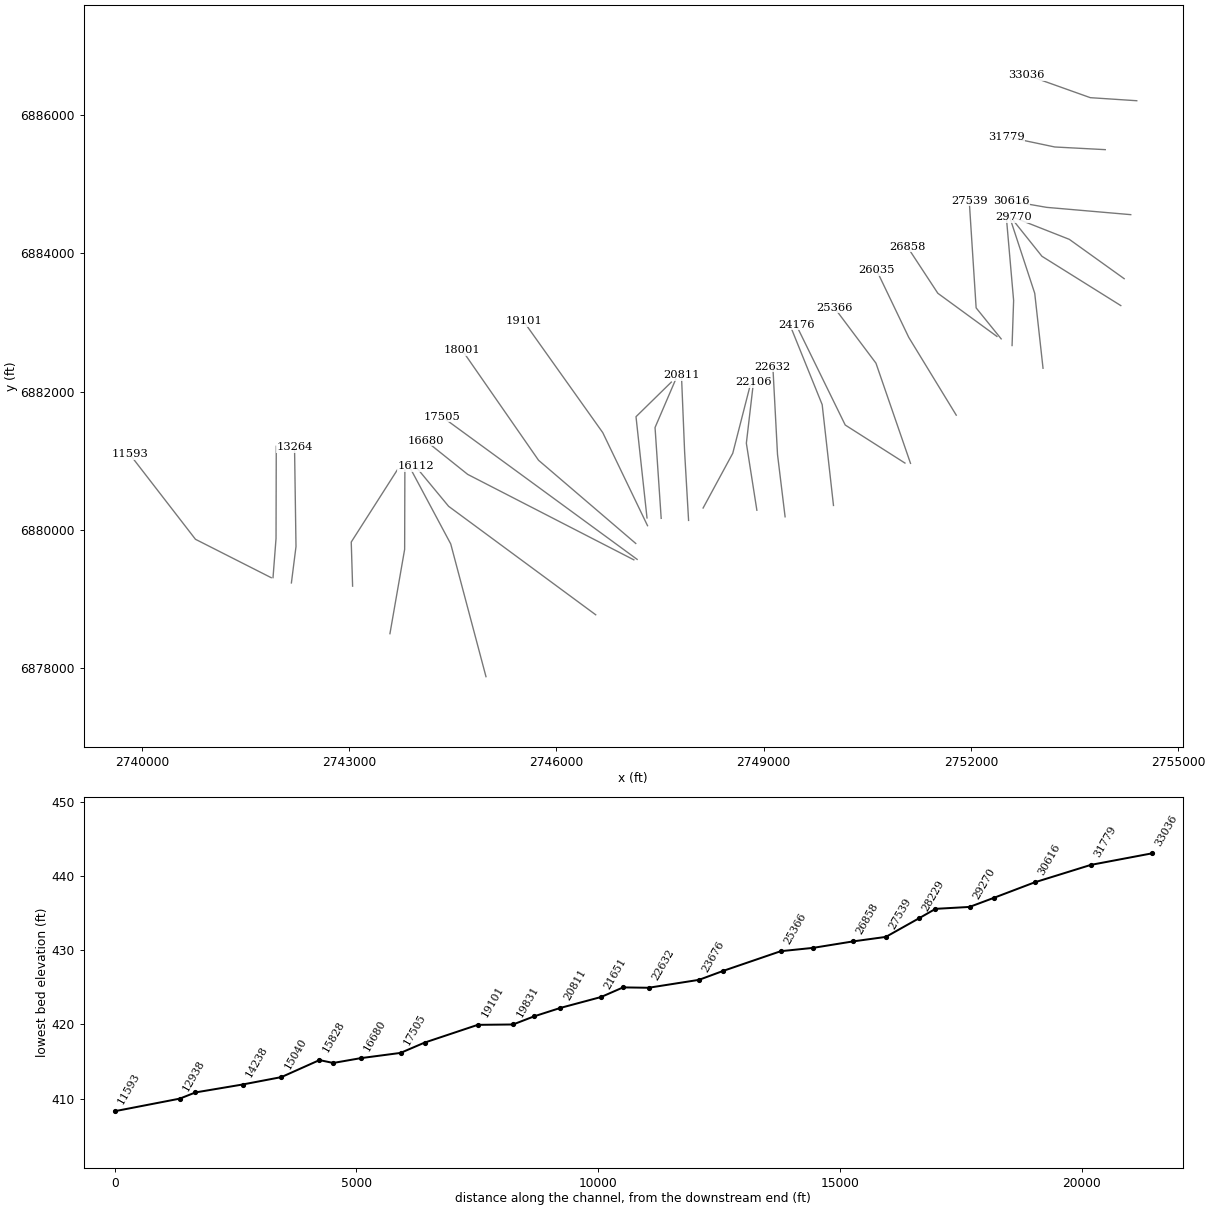
HEC-RAS study Dry Lacy Fork.prj: Dry Lacy Fork Base Level Engineering

--- Dry Lacy Fork.g01 (geometry) --- (continued)

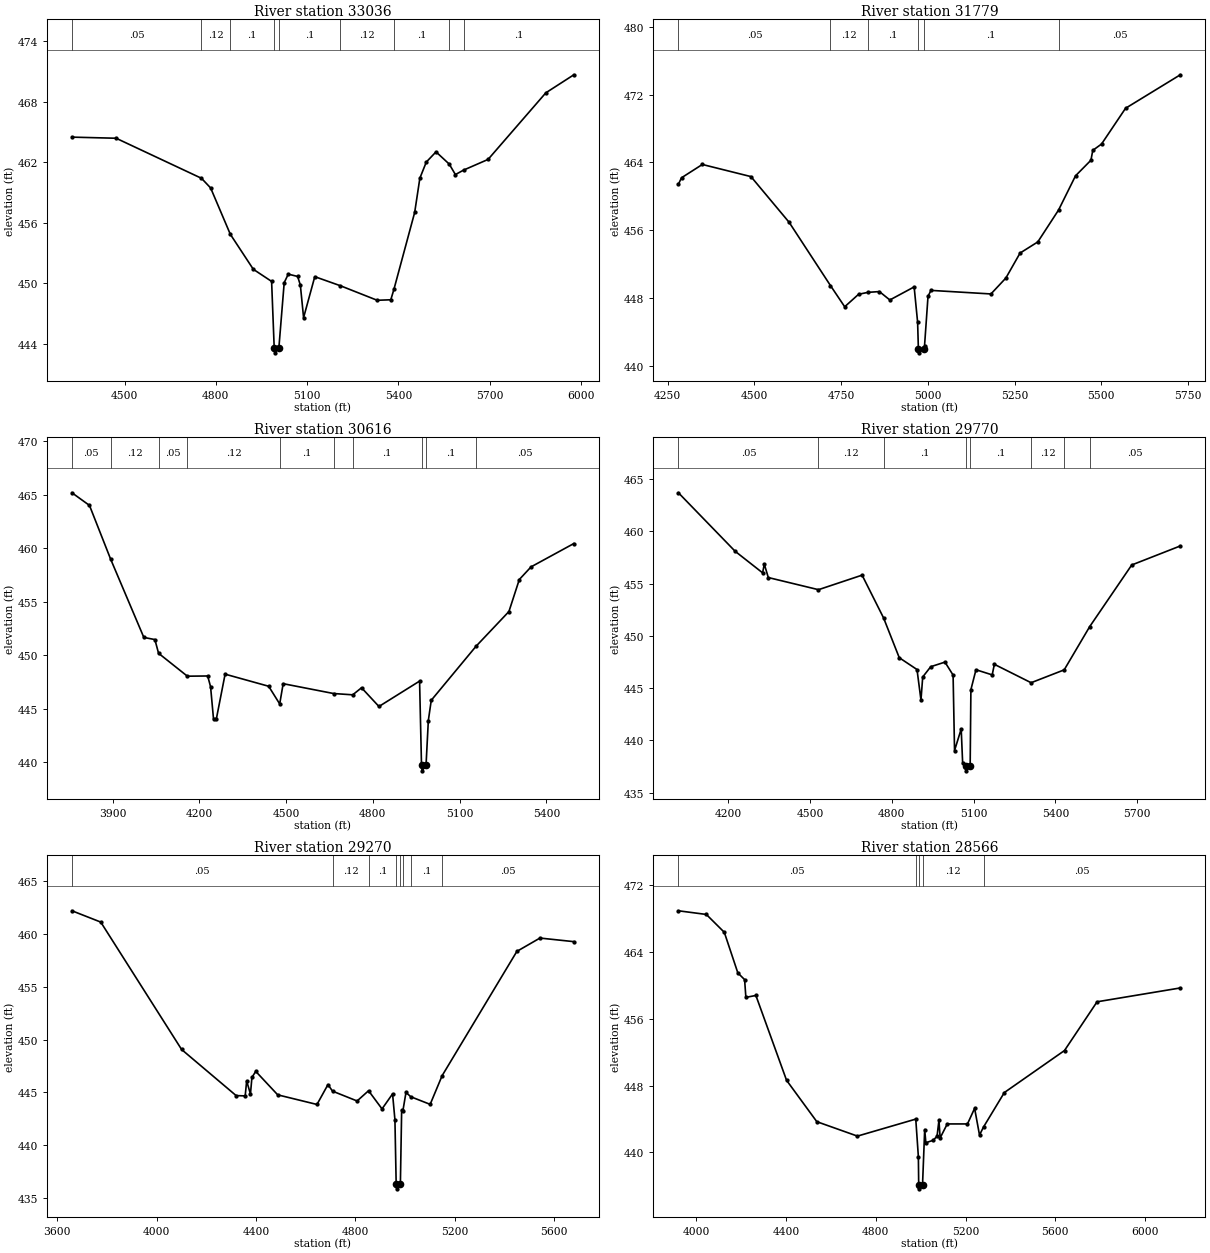
Type RM Length L Ch R = 1,33036,1257,1257,1257
BEGIN DESCRIPTION:
Dry Lacy Fork 2327
END DESCRIPTION:
XS GIS Cut Line= 3
      2754400.87      6886210.02      2753728.65      6886254.31
      2752809.19      6886582.05
#Sta/Elev= 30
  4327.0  464.49  4472.2  464.38  4752.8  460.41  4782.9  459.45  4847.6  454.86
  4923.2  451.39  4983.3  450.19  4991.8  443.61  4993.8  443.11  5007.2  443.61
  5024.7  450.07  5038.1  450.91  5068.9  450.68  5077.8  449.82  5088.4  446.60
  5125.2  450.66  5209.4  449.76  5330.3  448.32  5375.1  448.37  5385.5  449.42
  5453.6  457.03  5470.6  460.42  5491.8  462.02  5523.7  463.03  5567.1  461.82
  5587.4  460.78  5614.9  461.23  5694.8  462.28  5884.6  468.88  5976.8  470.67
#Mann=9,-1,0
  4327.0    0.05       0  4752.8    0.12       0  4847.6     0.1       0
  4991.8    0.07       0  5007.2     0.1       0  5209.4    0.12       0
  5385.5     0.1       0  5567.1    0.12       0  5614.9     0.1       0
Bank Sta=4991.8,5007.2
Exp/Cntr=0.3,0.1

Type RM Length L Ch R = 1,31779,1163,1163,1163
BEGIN DESCRIPTION:
Dry Lacy Fork 2325
END DESCRIPTION:
XS GIS Cut Line= 3
      2753944.91      6885501.90      2753214.15      6885540.45
      2752513.70      6885688.00
#Sta/Elev= 30
  4280.6  461.43  4289.5  462.19  4349.6  463.76  4489.8  462.33  4600.0  456.94
  4719.1  449.49  4760.2  446.99  4800.2  448.46  4827.5  448.69  4860.3  448.78
  4890.4  447.79  4960.5  449.33  4970.5  445.17  4972.7  442.06  4974.7  441.56
  4988.3  442.06  4990.5  442.40  5000.5  448.22  5009.0  448.92  5182.0  448.50
  5225.1  450.38  5266.0  453.32  5317.1  454.63  5377.0  458.39  5425.9  462.42
  5470.4  464.26  5475.7  465.42  5501.0  466.17  5570.2  470.38  5728.2  474.33
#Mann=6,-1,0
  4280.6    0.05       0  4719.1    0.12       0  4827.5     0.1       0
  4972.7    0.07       0  4988.3     0.1       0  5377.0    0.05       0
Bank Sta=4972.7,4988.3
Exp/Cntr=0.3,0.1

Type RM Length L Ch R = 1,30616,846,846,846
BEGIN DESCRIPTION:
Dry Lacy Fork 2273
END DESCRIPTION:
XS GIS Cut Line= 3
      2754313.63      6884560.95      2753096.33      6884666.50
      2752590.20      6884754.54
#Sta/Elev= 30
  3759.4  465.17  3820.0  463.99  3893.2  458.97  4008.0  451.66  4046.2  451.46
  4058.9  450.18  4158.5  448.04  4228.8  448.06  4238.8  447.05  4248.9  444.05
  4258.9  444.07  4289.0  448.23  4439.6  447.10  4477.8  445.45  4489.8  447.34
  4664.3  446.42  4730.3  446.30  4760.8  446.96  4821.0  445.21  4961.5  447.58
  4968.2  439.70  4970.2  439.20  4983.8  439.70  4991.8  443.90  5001.9  445.79
  5156.6  450.83  5270.5  454.08  5306.4  457.07  5347.0  458.25  5495.0  460.43
#Mann=10,-1,0
  3759.4    0.05       0  3893.2    0.12       0  4058.9    0.05       0
  4158.5    0.12       0  4477.8     0.1       0  4664.3    0.12       0
  4730.3     0.1       0  4968.2    0.07       0  4983.8     0.1       0
  5156.6    0.05       0
Bank Sta=4968.2,4983.8
Exp/Cntr=0.3,0.1

Type RM Length L Ch R = 1,29770,500,500,500
BEGIN DESCRIPTION:
Dry Lacy Fork 2272
END DESCRIPTION:
XS GIS Cut Line= 3
      2754218.78      6883633.88      2753424.45      6884203.40
      2752621.59      6884519.92
#Sta/Elev= 30
  4017.4  463.67  4225.4  458.08  4326.1  456.02  4332.3  456.85  4347.0  455.57
  4531.0  454.41  4690.9  455.80  4769.7  451.71  4827.2  447.91  4892.3  446.78
  4906.8  443.86  4913.2  446.07  4942.6  447.05  4994.8  447.49  5024.6  446.25
  5029.9  439.04  5054.3  441.10  5059.7  437.81  5070.2  437.60  5072.2  437.10
  5087.2  437.60  5089.9  444.86  5108.5  446.76  5168.0  446.27  5175.9  447.28
  5310.7  445.52  5432.0  446.75  5525.5  450.88  5679.6  456.77  5857.8  458.59
#Mann=8,-1,0
  4017.4    0.05       0  4531.0    0.12       0  4769.7     0.1       0
  5070.2    0.07       0  5087.2     0.1       0  5310.7    0.12       0
  5432.0     0.1       0  5525.5    0.05       0
Bank Sta=5070.2,5087.2
Exp/Cntr=0.3,0.1

Type RM Length L Ch R = 1,29270,704,704,704
BEGIN DESCRIPTION:
Dry Lacy Fork 2271
END DESCRIPTION:
XS GIS Cut Line= 3
      2754169.56      6883244.74      2753028.40      6883958.28
      2752607.77      6884484.94
#Sta/Elev= 30
  3659.4  462.18  3775.3  461.11  4100.7  449.06  4320.1  444.70  4356.6  444.67
  4362.5  446.08  4377.8  444.85  4383.7  446.42  4399.1  446.99  4487.5  444.77
  4645.5  443.86  4689.7  445.74  4708.1  445.12  4807.0  444.19  4853.1  445.16
  4907.3  443.44  4949.7  444.86  4959.2  442.42  4964.2  436.38  4966.2  435.88
  4981.2  436.38  4986.3  443.33  4991.2  443.25  5003.7  445.00  5023.0  444.59
  5101.0  443.87  5149.3  446.59  5450.0  458.34  5542.9  459.60  5679.3  459.26
#Mann=8,-1,0
  3659.4    0.05       0  4708.1    0.12       0  4853.1     0.1       0
  4964.2    0.07       0  4981.2     0.1       0  4991.2    0.12       0
  5023.0     0.1       0  5149.3    0.05       0
Bank Sta=4964.2,4981.2
Exp/Cntr=0.3,0.1

Type RM Length L Ch R = 1,28566,337,337,337
BEGIN DESCRIPTION:
Dry Lacy Fork 2270
END DESCRIPTION:
XS GIS Cut Line= 3
      2753044.20      6882337.66      2752924.01      6883422.35
      2752566.05      6884511.61
#Sta/Elev= 30
  3919.9  468.95  4044.4  468.51  4124.5  466.37  4184.9  461.50  4215.0  460.70
  4220.7  458.57  4265.3  458.80  4402.1  448.63  4537.0  443.67  4718.1  441.94
  4978.2  443.98  4989.8  439.48  4991.3  436.12  4993.3  435.62  5008.4  436.12
  5018.0  442.73  5023.2  441.15  5055.0  441.43  5073.0  441.91  5081.6  443.84
  5086.8  441.72  5118.7  443.40  5208.8  443.40  5240.6  445.27  5262.4  442.07
  5280.5  443.04  5373.1  447.16  5641.4  452.20  5786.6  458.04  6157.8  459.70
#Mann=5,-1,0
  3919.9    0.05       0  4978.2    0.12       0  4991.3    0.07       0
  5008.4    0.12       0  5280.5    0.05       0
Bank Sta=4991.3,5008.4
Exp/Cntr=0.3,0.1

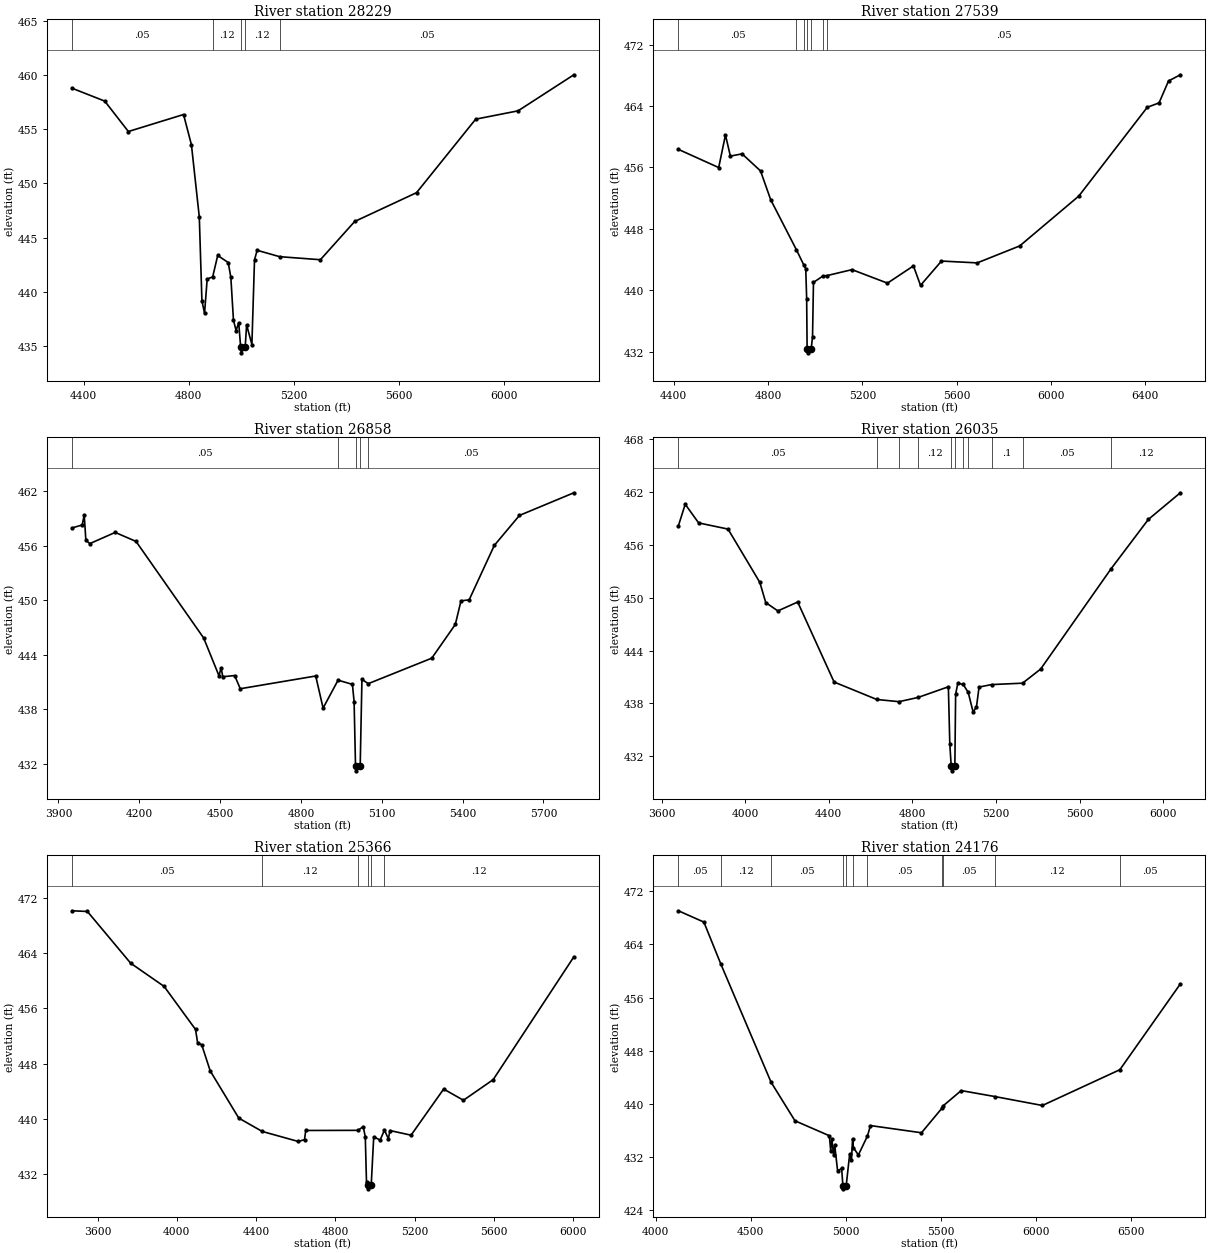
Type RM Length L Ch R = 1,28229,690,690,690
BEGIN DESCRIPTION:
Dry Lacy Fork 2269
END DESCRIPTION:
XS GIS Cut Line= 3
      2752596.07      6882666.26      2752618.43      6883317.97
      2752508.82      6884572.59
#Sta/Elev= 30
  4355.1  458.80  4479.9  457.61  4570.0  454.80  4780.1  456.37  4810.1  453.58
  4840.1  446.91  4850.1  439.17  4860.1  438.01  4870.1  441.17  4891.1  441.38
  4910.2  443.35  4950.2  442.70  4960.2  441.35  4970.2  437.38  4980.2  436.42
  4990.2  437.15  4997.7  434.86  4999.7  434.36  5014.8  434.86  5020.3  436.94
  5040.4  435.13  5050.4  442.95  5060.4  443.83  5146.2  443.24  5301.3  442.96
  5431.8  446.49  5667.4  449.15  5892.7  455.94  6054.2  456.71  6266.6  460.04
#Mann=5,-1,0
  4355.1    0.05       0  4891.1    0.12       0  4997.7    0.07       0
  5014.8    0.12       0  5146.2    0.05       0
Bank Sta=4997.7,5014.8
Exp/Cntr=0.3,0.1

Type RM Length L Ch R = 1,27539,681,681,681
BEGIN DESCRIPTION:
Dry Lacy Fork 24
END DESCRIPTION:
XS GIS Cut Line= 3
      2752438.22      6882762.88      2752076.00      6883211.00
      2751976.00      6884760.97
#Sta/Elev= 30
  4419.6  458.34  4590.5  455.97  4619.2  460.22  4640.0  457.46  4689.6  457.76
  4768.0  455.53  4811.1  451.78  4920.2  445.26  4951.8  443.26  4959.8  442.78
  4963.7  438.90  4965.6  432.33  4967.6  431.83  4982.8  432.33  4988.6  433.91
  4992.6  441.01  5032.8  441.84  5049.3  441.89  5156.1  442.67  5306.5  440.91
  5416.7  443.16  5446.7  440.62  5535.7  443.79  5687.2  443.55  5867.6  445.76
  6118.1  452.25  6408.7  463.82  6458.8  464.40  6498.9  467.25  6549.0  468.06
#Mann=7,-1,0
  4419.6    0.05       0  4920.2    0.12       0  4951.8    0.05       0
  4965.6    0.04       0  4982.8    0.05       0  5032.8    0.12       0
  5049.3    0.05       0
Bank Sta=4965.6,4982.8
Exp/Cntr=0.3,0.1

Type RM Length L Ch R = 1,26858,823,823,823
BEGIN DESCRIPTION:
Dry Lacy Fork 2251
END DESCRIPTION:
XS GIS Cut Line= 3
      2752376.69      6882798.35      2751521.62      6883422.74
      2751080.48      6884095.18
#Sta/Elev= 30
  3950.0  457.93  3988.0  458.26  3995.5  459.35  4001.7  456.58  4016.4  456.21
  4110.6  457.44  4187.9  456.45  4438.9  445.83  4495.7  441.68  4503.7  442.54
  4509.9  441.57  4553.9  441.70  4574.8  440.25  4854.8  441.65  4882.2  438.12
  4937.8  441.19  4991.0  440.73  4997.3  438.84  5002.6  431.72  5004.6  431.22
  5019.9  431.72  5026.4  441.27  5050.1  440.81  5285.6  443.61  5373.0  447.32
  5394.1  449.92  5424.3  450.02  5517.7  456.01  5611.1  459.31  5813.0  461.80
#Mann=5,-1,0
  3950.0    0.05       0  4937.8    0.12       0  5002.6    0.07       0
  5019.9    0.12       0  5050.1    0.05       0
Bank Sta=5002.6,5019.9
Exp/Cntr=0.3,0.1

Type RM Length L Ch R = 1,26035,669,669,669
BEGIN DESCRIPTION:
Dry Lacy Fork 2252
END DESCRIPTION:
XS GIS Cut Line= 3
      2751788.05      6881658.43      2751100.56      6882784.78
      2750633.15      6883760.63
#Sta/Elev= 30
  3680.8  458.17  3713.3  460.61  3777.5  458.49  3918.1  457.79  4070.4  451.74
  4098.6  449.45  4156.6  448.50  4251.5  449.51  4425.7  440.43  4629.8  438.45
  4736.3  438.20  4827.5  438.68  4972.5  439.89  4979.4  433.38  4986.2  430.85
  4988.2  430.35  5003.5  430.85  5007.3  439.05  5017.7  440.29  5043.5  440.15
  5067.4  439.26  5091.2  437.00  5107.1  437.64  5119.4  439.86  5178.9  440.14
  5327.5  440.30  5414.0  441.90  5750.6  453.27  5929.2  458.88  6082.4  461.91
#Mann=11,-1,0
  3680.8    0.05       0  4629.8    0.12       0  4736.3    0.05       0
  4827.5    0.12       0  4986.2    0.07       0  5003.5    0.12       0
  5043.5     0.1       0  5067.4    0.12       0  5178.9     0.1       0
  5327.5    0.05       0  5750.6    0.12       0
Bank Sta=4986.2,5003.5
Exp/Cntr=0.3,0.1

Type RM Length L Ch R = 1,25366,1190,1190,1190
BEGIN DESCRIPTION:
Dry Lacy Fork 23
END DESCRIPTION:
XS GIS Cut Line= 3
      2751125.99      6880961.02      2750626.00      6882411.00
      2750025.98      6883211.03
#Sta/Elev= 30
  3470.6  470.11  3548.6  470.01  3767.0  462.53  3936.0  459.17  4094.4  452.95
  4105.3  450.98  4125.6  450.74  4168.7  446.95  4312.8  440.13  4431.1  438.20
  4613.0  436.75  4644.7  437.01  4650.8  438.34  4914.3  438.36  4940.9  438.89
  4951.5  437.43  4957.6  430.85  4964.0  430.40  4966.0  429.90  4981.3  430.40
  4994.1  437.43  5026.2  436.95  5048.4  438.39  5067.9  437.14  5076.2  438.33
  5182.5  437.66  5347.1  444.33  5447.1  442.71  5597.1  445.69  6004.4  463.45
#Mann=6,-1,0
  3470.6    0.05       0  4431.1    0.12       0  4914.3     0.1       0
  4964.0    0.07       0  4981.3     0.1       0  5048.4    0.12       0
Bank Sta=4964,4981.3
Exp/Cntr=0.3,0.1

Type RM Length L Ch R = 1,24176,500,500,500
BEGIN DESCRIPTION:
Dry Lacy Fork 2248
END DESCRIPTION:
XS GIS Cut Line= 3
      2751045.54      6880965.04      2750181.19      6881515.67
      2749471.30      6882966.14
#Sta/Elev= 30
  4120.1  469.04  4254.0  467.34  4342.8  461.06  4607.2  443.28  4733.1  437.47
  4914.0  435.22  4921.0  433.00  4927.0  434.67  4936.3  432.37  4942.2  433.77
  4957.4  429.93  4978.6  430.30  4985.1  427.74  4987.1  427.24  5002.6  427.74
  5020.9  432.49  5030.2  431.58  5036.2  434.77  5040.3  433.44  5066.6  432.33
  5114.4  435.19  5130.1  436.75  5398.5  435.67  5508.1  439.43  5511.7  439.70
  5607.3  442.01  5783.3  441.12  6034.3  439.77  6441.9  445.15  6759.8  458.04
#Mann=11,-1,0
  4120.1    0.05       0  4342.8    0.12       0  4607.2    0.05       0
  4985.1    0.07       0  5002.6    0.05       0  5040.3    0.12       0
  5114.4    0.05       0  5508.1    0.12       0  5511.7    0.05       0
  5783.3    0.12       0  6441.9    0.05       0
Bank Sta=4985.1,5002.6
Exp/Cntr=0.3,0.1

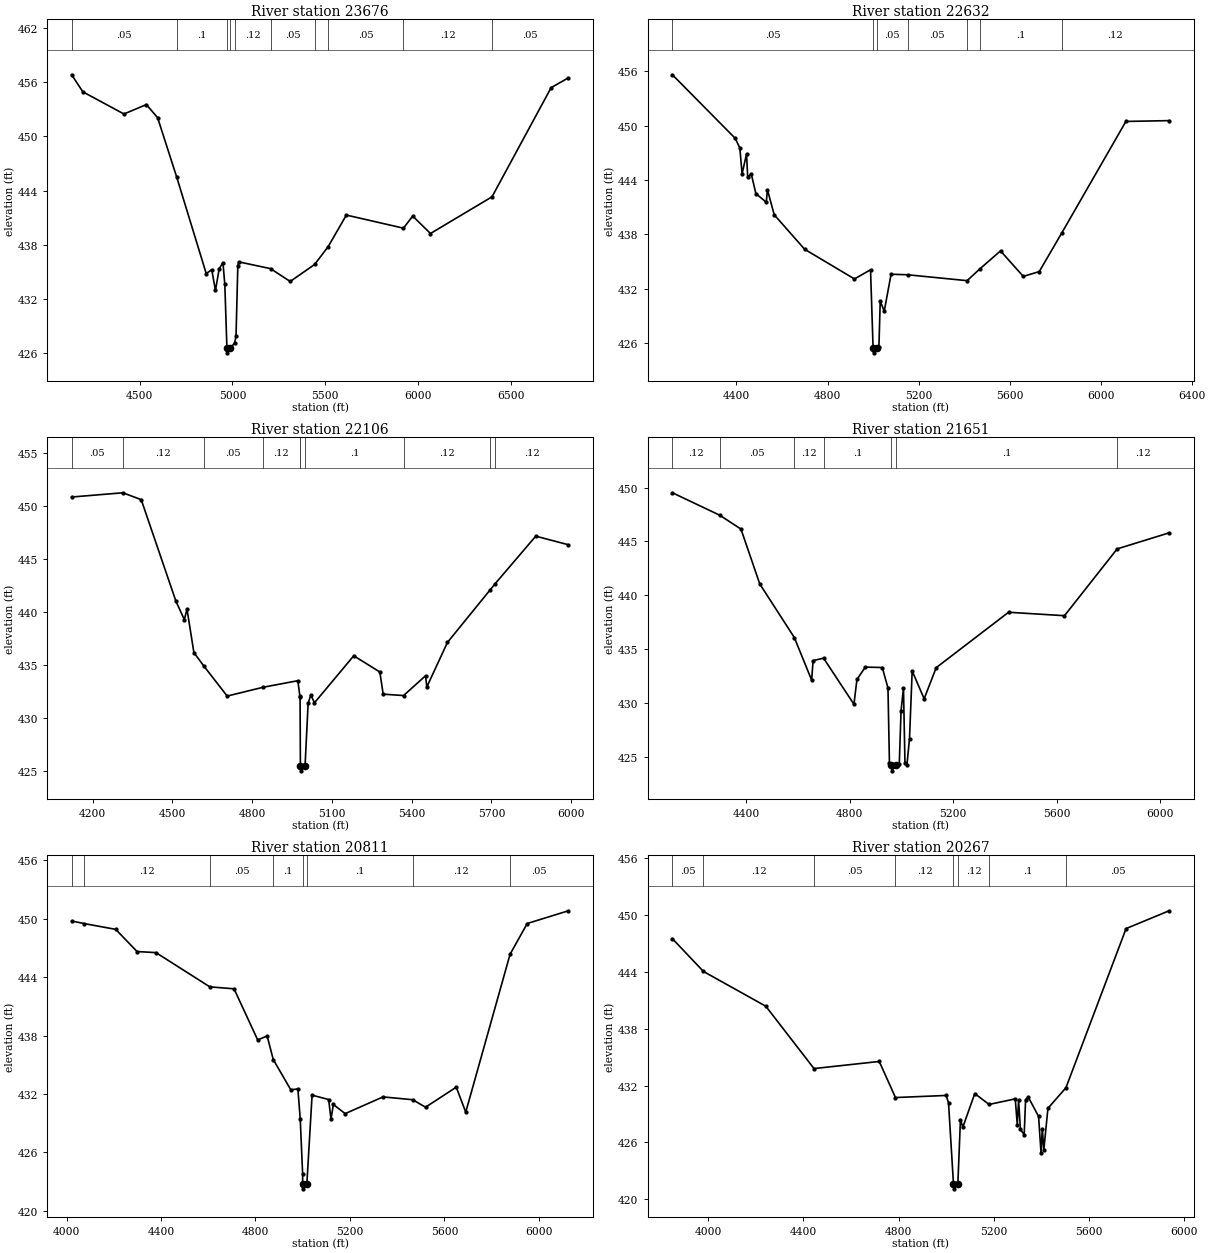
Type RM Length L Ch R = 1,23676,1044,1044,1044
BEGIN DESCRIPTION:
Dry Lacy Fork 2249
END DESCRIPTION:
XS GIS Cut Line= 3
      2750011.23      6880351.22      2749847.61      6881810.68
      2749395.11      6882929.76
#Sta/Elev= 30
  4134.1  456.81  4194.3  454.92  4415.6  452.47  4536.4  453.51  4596.8  452.07
  4699.0  445.54  4858.8  434.81  4888.6  435.23  4908.7  432.94  4928.8  435.35
  4949.0  436.01  4959.0  433.60  4970.4  426.53  4972.4  426.03  4987.9  426.53
  5012.2  427.13  5019.4  427.89  5029.1  435.66  5034.1  436.10  5205.5  435.35
  5311.2  433.93  5442.7  435.81  5515.9  437.79  5613.8  441.28  5921.4  439.83
  5971.2  441.17  6066.9  439.24  6398.4  443.30  6716.8  455.38  6809.8  456.47
#Mann=10,-1,0
  4134.1    0.05       0  4699.0     0.1       0  4970.4    0.07       0
  4987.9     0.1       0  5012.2    0.12       0  5205.5    0.05       0
  5442.7    0.12       0  5515.9    0.05       0  5921.4    0.12       0
  6398.4    0.05       0
Bank Sta=4970.4,4987.9
Exp/Cntr=0.3,0.1

Type RM Length L Ch R = 1,22632,526,526,526
BEGIN DESCRIPTION:
Dry Lacy Fork 2250
END DESCRIPTION:
XS GIS Cut Line= 3
      2749310.88      6880187.11      2749201.07      6881089.37
      2749133.74      6882360.58
#Sta/Elev= 30
  4118.7  455.59  4394.6  448.59  4414.8  447.54  4424.8  444.68  4444.4  446.88
  4449.4  444.29  4465.1  444.67  4485.3  442.50  4531.1  441.55  4536.1  442.93
  4565.9  440.17  4699.5  436.37  4918.4  433.10  4989.0  434.11  5000.3  425.46
  5002.3  424.96  5017.9  425.46  5025.9  425.63  5031.6  430.64  5049.3  429.56
  5079.3  433.62  5152.0  433.56  5413.2  432.91  5470.3  434.23  5560.0  436.19
  5660.1  433.38  5730.2  433.91  5828.3  438.13  6110.8  450.45  6300.6  450.54
#Mann=7,-1,0
  4118.7    0.05       0  5000.3    0.05       0  5017.9    0.05       0
  5152.0    0.05       0  5413.2    0.12       0  5470.3     0.1       0
  5828.3    0.12       0
Bank Sta=5000.3,5017.9
Exp/Cntr=0.3,0.1

Type RM Length L Ch R = 1,22106,455,455,455
BEGIN DESCRIPTION:
Dry Lacy Fork 2174
END DESCRIPTION:
XS GIS Cut Line= 3
      2748902.30      6880282.41      2748750.17      6881252.40
      2748852.93      6882132.88
#Sta/Elev= 30
  4121.3  450.83  4313.8  451.23  4382.9  450.58  4513.3  441.01  4545.0  439.27
  4555.1  440.25  4581.0  436.16  4617.3  434.93  4706.2  432.06  4841.0  432.89
  4972.0  433.51  4979.4  432.11  4980.3  431.94  4981.6  425.51  4983.6  425.01
  4999.2  425.51  5010.6  431.36  5020.7  432.16  5034.6  431.43  5182.3  435.86
  5280.4  434.33  5293.0  432.24  5369.7  432.11  5452.2  433.97  5457.2  432.92
  5534.7  437.12  5695.5  442.08  5714.7  442.67  5866.9  447.14  5989.6  446.33
#Mann=10,-1,0
  4121.3    0.05       0  4313.8    0.12       0  4617.3    0.05       0
  4841.0    0.12       0  4979.4     0.1       0  4981.6    0.07       0
  4999.2     0.1       0  5369.7    0.12       0  5695.5     0.1       0
  5714.7    0.12       0
Bank Sta=4981.6,4999.2
Exp/Cntr=0.3,0.1

Type RM Length L Ch R = 1,21651,840,840,840
BEGIN DESCRIPTION:
Dry Lacy Fork 2172
END DESCRIPTION:
XS GIS Cut Line= 3
      2748124.25      6880314.31      2748553.40      6881106.95
      2748806.22      6882092.38
#Sta/Elev= 30
  4115.6  449.52  4298.2  447.44  4380.4  446.15  4453.0  441.06  4586.6  436.08
  4653.4  432.13  4659.1  433.94  4699.4  434.17  4816.9  429.89  4828.4  432.19
  4860.8  433.34  4926.4  433.30  4948.3  431.39  4954.0  424.42  4961.3  424.21
  4963.3  423.71  4979.0  424.21  4992.0  424.34  4998.8  429.28  5008.2  431.38
  5013.9  424.46  5021.6  424.27  5031.5  426.71  5041.8  432.98  5088.0  430.40
  5134.7  433.29  5414.2  438.43  5630.2  438.11  5833.6  444.31  6034.3  445.80
#Mann=7,-1,0
  4115.6    0.12       0  4298.2    0.05       0  4586.6    0.12       0
  4699.4     0.1       0  4961.3    0.07       0  4979.0     0.1       0
  5833.6    0.12       0
Bank Sta=4961.3,4979
Exp/Cntr=0.3,0.1

Type RM Length L Ch R = 1,20811,544,544,544
BEGIN DESCRIPTION:
Dry Lacy Fork 2173
END DESCRIPTION:
XS GIS Cut Line= 3
      2747913.96      6880134.77      2747856.77      6881123.94
      2747810.97      6882235.28
#Sta/Elev= 30
  4021.7  449.77  4075.5  449.50  4208.2  448.91  4298.4  446.63  4378.5  446.52
  4606.6  443.00  4709.1  442.80  4809.2  437.55  4849.3  437.95  4875.2  435.53
  4949.5  432.42  4979.5  432.51  4989.5  429.39  4999.6  423.78  4999.7  422.74
  5001.7  422.24  5017.4  422.74  5039.6  431.87  5109.7  431.42  5119.7  429.41
  5129.7  430.91  5179.7  429.97  5339.9  431.69  5465.5  431.40  5520.0  430.63
  5650.1  432.69  5690.2  430.12  5877.9  446.35  5950.4  449.51  6124.8  450.82
#Mann=8,-1,0
  4021.7    0.05       0  4075.5    0.12       0  4606.6    0.05       0
  4875.2     0.1       0  4999.7    0.07       0  5017.4     0.1       0
  5465.5    0.12       0  5877.9    0.05       0
Bank Sta=4999.7,5017.4
Exp/Cntr=0.3,0.1

Type RM Length L Ch R = 1,20267,436,436,436
BEGIN DESCRIPTION:
Dry Lacy Fork 2170
END DESCRIPTION:
XS GIS Cut Line= 3
      2747517.44      6880164.54      2747428.57      6881479.48
      2747731.05      6882184.59
#Sta/Elev= 30
  3850.3  447.51  3980.8  444.05  4242.5  440.38  4444.7  433.80  4718.7  434.55
  4786.7  430.74  4999.4  430.96  5009.4  430.20  5030.3  421.60  5032.3  421.10
  5048.6  421.60  5059.5  428.41  5069.5  427.61  5119.7  431.16  5179.6  430.01
  5289.6  430.60  5298.1  427.88  5303.6  430.47  5311.4  427.38  5327.1  426.81
  5333.1  430.53  5344.0  430.80  5387.5  428.75  5397.8  424.90  5403.3  427.45
  5409.3  425.18  5426.8  429.60  5502.5  431.78  5754.9  448.58  5935.5  450.46
#Mann=8,-1,0
  3850.3    0.05       0  3980.8    0.12       0  4444.7    0.05       0
  4786.7    0.12       0  5030.3    0.07       0  5048.6    0.12       0
  5179.6     0.1       0  5502.5    0.05       0
Bank Sta=5030.3,5048.6
Exp/Cntr=0.3,0.1

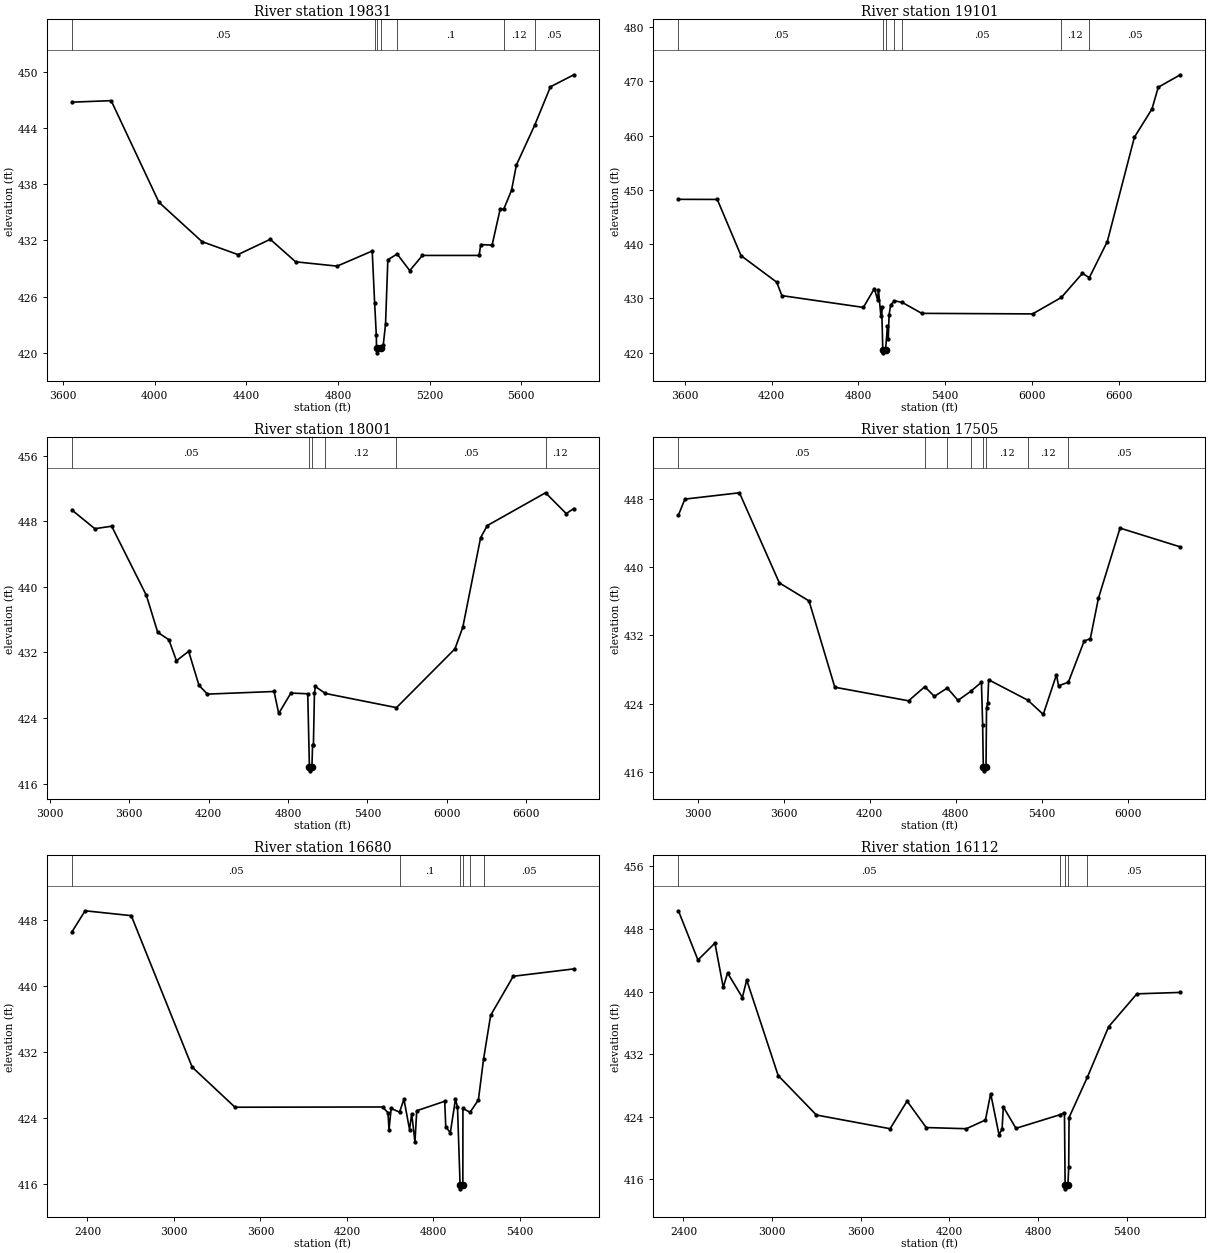
Type RM Length L Ch R = 1,19831,730,730,730
BEGIN DESCRIPTION:
Dry Lacy Fork 2171
END DESCRIPTION:
XS GIS Cut Line= 3
      2747312.23      6880170.89      2747152.99      6881636.07
      2747664.40      6882137.04
#Sta/Elev= 30
  3639.7  446.74  3810.8  446.90  4019.2  436.06  4207.3  431.86  4364.0  430.48
  4504.9  432.11  4615.5  429.71  4796.6  429.25  4949.7  430.86  4960.2  425.34
  4967.6  421.88  4968.4  420.50  4970.4  420.00  4986.8  420.50  4997.8  420.81
  5007.8  423.05  5017.9  429.93  5058.4  430.54  5113.5  428.77  5168.6  430.39
  5416.1  430.39  5423.2  431.55  5472.7  431.49  5508.1  435.35  5523.3  435.31
  5557.5  437.34  5578.8  440.04  5658.7  444.29  5727.3  448.38  5829.4  449.66
#Mann=7,-1,0
  3639.7    0.05       0  4960.2    0.12       0  4968.4    0.07       0
  4986.8    0.12       0  5058.4     0.1       0  5523.3    0.12       0
  5658.7    0.05       0
Bank Sta=4968.4,4986.8
Exp/Cntr=0.3,0.1

Type RM Length L Ch R = 1,19101,1100,1100,1100
BEGIN DESCRIPTION:
Dry Lacy Fork 2169
END DESCRIPTION:
XS GIS Cut Line= 3
      2747319.69      6880058.53      2746672.16      6881405.00
      2745527.18      6883015.36
#Sta/Elev= 30
  3555.6  448.26  3824.3  448.24  3988.3  437.88  4235.2  432.98  4271.0  430.50
  4834.4  428.33  4910.2  431.80  4932.9  429.72  4938.4  431.59  4955.5  426.74
  4961.0  428.45  4968.6  420.45  4970.6  419.95  4987.7  420.45  5000.8  424.97
  5006.3  422.48  5012.0  426.95  5023.1  428.78  5048.5  429.54  5101.3  429.27
  5238.2  427.23  6004.4  427.13  6202.9  430.16  6348.8  434.61  6396.3  433.81
  6520.9  440.48  6707.9  459.70  6829.6  464.92  6873.0  468.93  7025.6  471.23
#Mann=7,-1,0
  3555.6    0.05       0  4968.6    0.04       0  4987.7    0.05       0
  5048.5     0.1       0  5101.3    0.05       0  6202.9    0.12       0
  6396.3    0.05       0
Bank Sta=4968.6,4987.7
Exp/Cntr=0.3,0.1

Type RM Length L Ch R = 1,18001,496,496,496
BEGIN DESCRIPTION:
Dry Lacy Fork 2168
END DESCRIPTION:
XS GIS Cut Line= 3
      2747149.43      6879801.15      2745742.33      6881005.57
      2744635.91      6882600.01
#Sta/Elev= 30
  3167.4  449.36  3340.2  447.09  3467.6  447.39  3729.9  438.95  3815.5  434.45
  3900.0  433.54  3957.1  430.98  4049.3  432.13  4127.3  427.98  4190.9  426.91
  4694.8  427.23  4729.9  424.55  4822.1  427.04  4949.4  426.95  4961.8  418.05
  4963.8  417.55  4980.9  418.05  4985.7  420.67  4992.2  420.73  4999.9  427.01
  5006.5  427.84  5082.5  426.99  5619.9  425.26  6061.8  432.43  6121.3  435.08
  6255.7  445.99  6306.3  447.47  6746.3  451.47  6902.7  448.93  6960.3  449.55
#Mann=6,-1,0
  3167.4    0.05       0  4961.8    0.04       0  4980.9    0.05       0
  5082.5    0.12       0  5619.9    0.05       0  6746.3    0.12       0
Bank Sta=4961.8,4980.9
Exp/Cntr=0.3,0.1

Type RM Length L Ch R = 1,17505,825,825,825
BEGIN DESCRIPTION:
Dry Lacy Fork 2166
END DESCRIPTION:
XS GIS Cut Line= 3
      2747169.30      6879570.85      2745441.23      6880835.12
      2744344.43      6881636.09
#Sta/Elev= 30
  2865.9  446.06  2910.9  447.94  3291.3  448.68  3569.5  438.14  3776.5  436.03
  3956.3  425.94  4470.6  424.35  4583.6  426.00  4650.5  424.87  4740.5  425.85
  4815.3  424.40  4903.0  425.45  4978.6  426.52  4987.1  421.51  4991.5  416.66
  4993.5  416.16  5010.6  416.66  5014.1  423.51  5022.6  424.13  5028.8  426.81
  5302.3  424.42  5409.5  422.76  5501.5  427.39  5516.1  426.11  5584.5  426.52
  5694.6  431.33  5737.8  431.63  5794.2  436.34  5944.8  444.55  6365.2  442.35
#Mann=8,-1,0
  2865.9    0.05       0  4583.6    0.12       0  4740.5    0.05       0
  4903.0    0.12       0  4991.5    0.04       0  5010.6    0.12       0
  5302.3    0.12       0  5584.5    0.05       0
Bank Sta=4991.5,5010.6
Exp/Cntr=0.3,0.1

Type RM Length L Ch R = 1,16680,568,568,568
BEGIN DESCRIPTION:
Dry Lacy Fork 2167
END DESCRIPTION:
XS GIS Cut Line= 3
      2747121.74      6879564.10      2744717.22      6880800.86
      2744110.21      6881286.64
#Sta/Elev= 30
  2292.5  446.53  2383.7  449.08  2703.8  448.49  3126.5  430.17  3423.5  425.32
  4446.8  425.35  4484.6  424.66  4491.8  422.61  4506.7  425.17  4564.6  424.73
  4595.4  426.28  4634.2  422.62  4649.2  424.53  4671.7  421.11  4684.1  424.90
  4878.1  426.04  4885.4  422.98  4916.8  422.22  4952.8  426.29  4966.8  425.35
  4984.7  415.95  4986.7  415.45  5003.9  415.95  5004.5  425.17  5054.1  424.71
  5111.8  426.21  5147.5  431.13  5196.6  436.43  5353.5  441.16  5773.9  442.05
#Mann=6,-1,0
  2292.5    0.05       0  4564.6     0.1       0  4984.7    0.07       0
  5003.9     0.1       0  5054.1    0.12       0  5147.5    0.05       0
Bank Sta=4984.7,5003.9
Exp/Cntr=0.3,0.1

Type RM Length L Ch R = 1,16112,284,284,284
BEGIN DESCRIPTION:
Dry Lacy Fork 1992
END DESCRIPTION:
XS GIS Cut Line= 3
      2746569.54      6878768.95      2744440.89      6880338.83
      2743960.70      6880919.20
#Sta/Elev= 30
  2365.6  450.32  2497.9  444.03  2612.8  446.19  2669.2  440.54  2698.4  442.38
  2798.7  439.24  2827.9  441.48  3041.0  429.27  3299.9  424.23  3798.9  422.48
  3913.8  426.01  4043.3  422.63  4314.8  422.48  4444.3  423.59  4479.8  426.96
  4536.1  421.72  4557.0  422.43  4565.4  425.27  4651.0  422.53  4946.3  424.25
  4979.3  424.52  4983.8  415.30  4985.8  414.80  5003.0  415.30  5008.1  417.57
  5010.5  423.91  5135.1  429.09  5278.2  435.50  5469.7  439.71  5763.8  439.89
#Mann=5,-1,0
  2365.6    0.05       0  4946.3    0.12       0  4983.8    0.07       0
  5003.0    0.12       0  5135.1    0.05       0
Bank Sta=4983.8,5003
Exp/Cntr=0.3,0.1

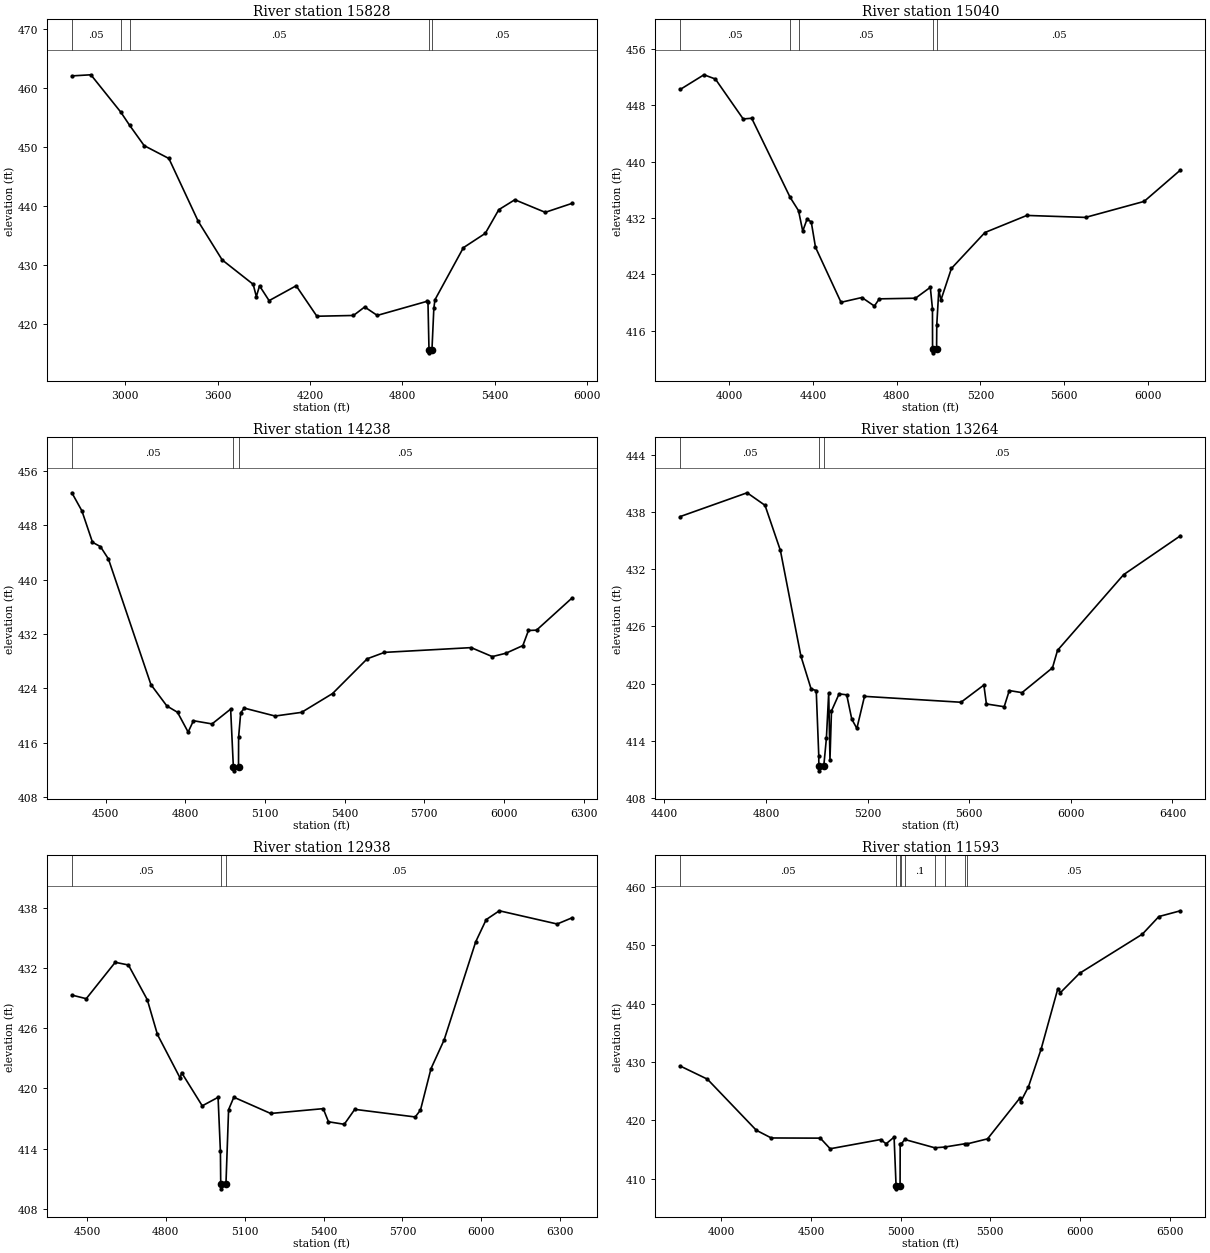
Type RM Length L Ch R = 1,15828,788,788,788
BEGIN DESCRIPTION:
Dry Lacy Fork 1994
END DESCRIPTION:
XS GIS Cut Line= 3
      2744981.66      6877872.71      2744471.55      6879794.05
      2743877.35      6880906.61
#Sta/Elev= 30
  2653.3  462.10  2776.8  462.29  2971.2  455.96  3027.7  453.76  3122.9  450.29
  3283.6  448.11  3474.2  437.46  3629.7  430.93  3831.0  426.80  3851.7  424.72
  3872.4  426.54  3934.5  424.03  4110.4  426.55  4244.9  421.39  4482.6  421.52
  4555.3  422.96  4637.0  421.53  4960.8  423.92  4966.5  423.83  4973.2  415.69
  4975.2  415.19  4992.4  415.69  5004.7  422.74  5011.9  424.18  5196.6  433.00
  5338.9  435.43  5426.7  439.44  5530.8  441.12  5728.3  438.99  5902.5  440.51
#Mann=5,-1,0
  2653.3    0.05       0  2971.2    0.12       0  3027.7    0.05       0
  4973.2    0.04       0  4992.4    0.05       0
Bank Sta=4973.2,4992.4
Exp/Cntr=0.3,0.1

Type RM Length L Ch R = 1,15040,802,802,802
BEGIN DESCRIPTION:
Dry Lacy Fork 1993
END DESCRIPTION:
XS GIS Cut Line= 3
      2743591.45      6878494.91      2743804.33      6879715.71
      2743807.64      6880863.98
#Sta/Elev= 30
  3766.7  450.21  3880.0  452.29  3934.5  451.69  4067.3  446.03  4107.9  446.13
  4291.4  434.92  4331.5  433.03  4351.5  430.14  4371.8  431.80  4392.1  431.46
  4412.4  427.85  4534.2  420.05  4634.0  420.73  4693.5  419.52  4716.9  420.54
  4889.5  420.63  4960.5  422.17  4970.7  419.14  4971.2  413.39  4973.2  412.89
  4990.4  413.39  4991.3  416.85  5001.0  421.81  5011.2  420.38  5061.2  424.85
  5221.2  429.94  5421.2  432.36  5701.2  432.08  5981.2  434.35  6154.2  438.79
#Mann=5,-1,0
  3766.7    0.05       0  4291.4    0.12       0  4331.5    0.05       0
  4971.2    0.04       0  4990.4    0.05       0
Bank Sta=4971.2,4990.4
Exp/Cntr=0.3,0.1

Type RM Length L Ch R = 1,14238,974,974,974
BEGIN DESCRIPTION:
Dry Lacy Fork 1991
END DESCRIPTION:
XS GIS Cut Line= 3
      2743051.12      6879183.33      2743031.44      6879821.90
      2743701.40      6880871.19
#Sta/Elev= 30
  4372.5  452.78  4410.2  450.13  4450.2  445.50  4480.2  444.86  4510.2  443.05
  4670.3  424.57  4730.3  421.43  4770.4  420.50  4810.4  417.59  4830.4  419.26
  4900.4  418.79  4970.5  420.97  4980.8  412.39  4982.8  411.89  5000.1  412.39
  5000.5  416.85  5008.4  420.44  5022.2  421.11  5137.8  419.95  5237.6  420.49
  5354.4  423.26  5484.9  428.37  5549.8  429.31  5876.4  430.01  5955.9  428.69
  6006.9  429.18  6071.0  430.31  6092.1  432.53  6122.6  432.58  6256.3  437.31
#Mann=3,-1,0
  4372.5    0.05       0  4980.8    0.04       0  5000.1    0.05       0
Bank Sta=4980.8,5000.1
Exp/Cntr=0.3,0.1

Type RM Length L Ch R = 1,13264,326,326,326
BEGIN DESCRIPTION:
Dry Lacy Fork 1998
END DESCRIPTION:
XS GIS Cut Line= 3
      2742165.20      6879229.74      2742231.86      6879756.02
      2742210.68      6881194.68
#Sta/Elev= 30
  4461.9  437.55  4725.3  440.05  4795.8  438.73  4856.3  433.99  4936.9  422.90
  4977.2  419.43  4997.4  419.26  5007.4  412.41  5007.6  411.32  5009.6  410.82
  5027.1  411.32  5037.4  414.23  5046.5  419.01  5051.5  411.99  5057.4  417.11
  5087.4  418.91  5117.4  418.81  5137.4  416.25  5157.4  415.28  5187.4  418.65
  5567.4  418.03  5657.4  419.84  5667.4  417.85  5737.4  417.56  5757.5  419.26
  5807.5  419.04  5927.5  421.65  5947.5  423.49  6207.5  431.44  6431.2  435.53
#Mann=3,-1,0
  4461.9    0.05       0  5007.6    0.04       0  5027.1    0.05       0
Bank Sta=5007.6,5027.1
Exp/Cntr=0.3,0.1

Type RM Length L Ch R = 1,12938,1345,1345,1345
BEGIN DESCRIPTION:
Dry Lacy Fork 1987
END DESCRIPTION:
XS GIS Cut Line= 3
      2741899.24      6879306.48      2741942.91      6879873.81
      2741946.22      6881207.59
#Sta/Elev= 30
  4442.4  429.31  4497.1  428.95  4607.4  432.58  4657.6  432.31  4729.3  428.85
  4767.9  425.38  4854.7  421.01  4859.7  421.58  4938.4  418.26  4998.6  419.11
  5007.5  413.71  5008.7  410.48  5010.7  409.98  5028.6  410.48  5038.6  417.88
  5058.6  419.12  5198.6  417.50  5398.6  417.98  5418.6  416.67  5478.6  416.42
  5518.6  417.91  5748.6  417.15  5768.6  417.84  5808.6  421.97  5858.6  424.84
  5978.6  434.62  6018.6  436.84  6068.6  437.72  6288.6  436.40  6345.2  437.02
#Mann=3,-1,0
  4442.4    0.05       0  5008.7    0.04       0  5028.6    0.05       0
Bank Sta=5008.7,5028.6
Exp/Cntr=0.3,0.1

Type RM Length L Ch R = 1,11593,1036,1036,1036
BEGIN DESCRIPTION:
Dry Lacy Fork 1990
END DESCRIPTION:
XS GIS Cut Line= 3
      2741872.81      6879305.86      2740776.69      6879861.55
      2739822.88      6881096.07
#Sta/Elev= 30
  3770.6  429.33  3922.1  427.08  4194.9  418.32  4278.4  417.00  4551.8  416.97
  4606.8  415.15  4888.2  416.73  4918.6  416.00  4963.1  417.14  4974.2  408.78
  4976.5  408.28  4996.5  408.78  4997.1  415.91  5001.5  415.91  5022.6  416.74
  5189.6  415.32  5244.5  415.44  5356.7  416.00  5367.2  415.96  5484.3  416.85
  5662.7  423.77  5669.0  423.20  5712.5  425.79  5783.1  432.25  5876.4  442.61
  5890.9  441.92  5997.2  445.22  6347.4  451.93  6439.5  454.95  6559.6  455.94
#Mann=9,-1,0
  3770.6    0.05       0  4974.2    0.04       0  4996.5    0.05       0
  5001.5    0.12       0  5022.6     0.1       0  5189.6    0.12       0
  5244.5    0.05       0  5356.7    0.12       0  5367.2    0.05       0
Bank Sta=4974.2,4996.5
Exp/Cntr=0.3,0.1