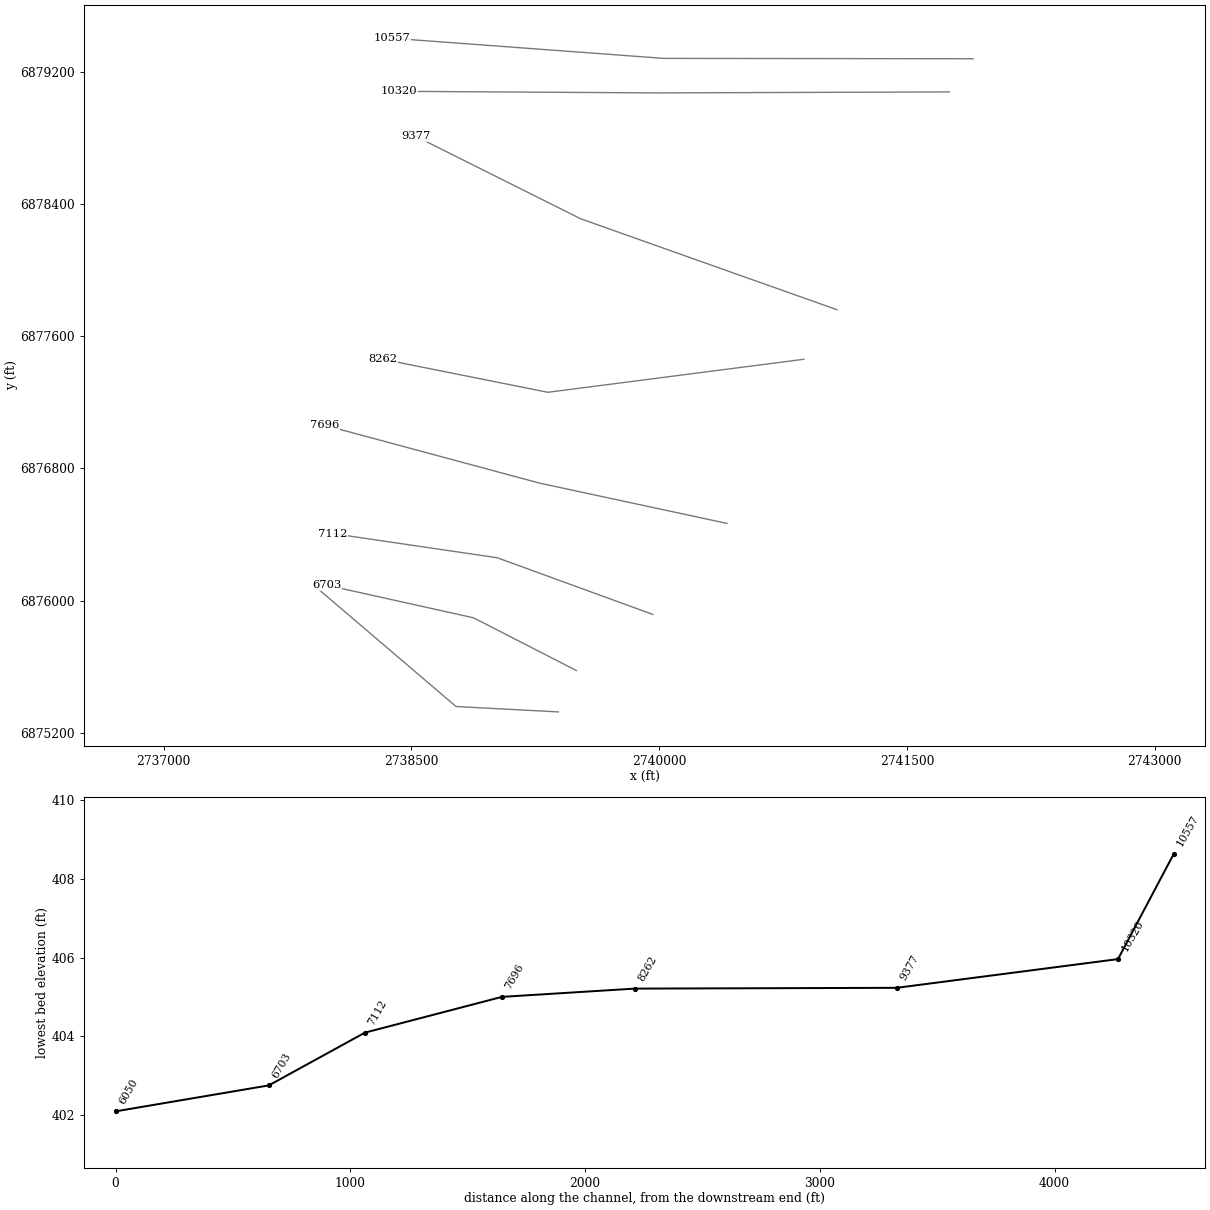
HEC-RAS study Dry Lacy Fork.prj: Dry Lacy Fork Base Level Engineering

--- Dry Lacy Fork.g01 (geometry) --- (continued)

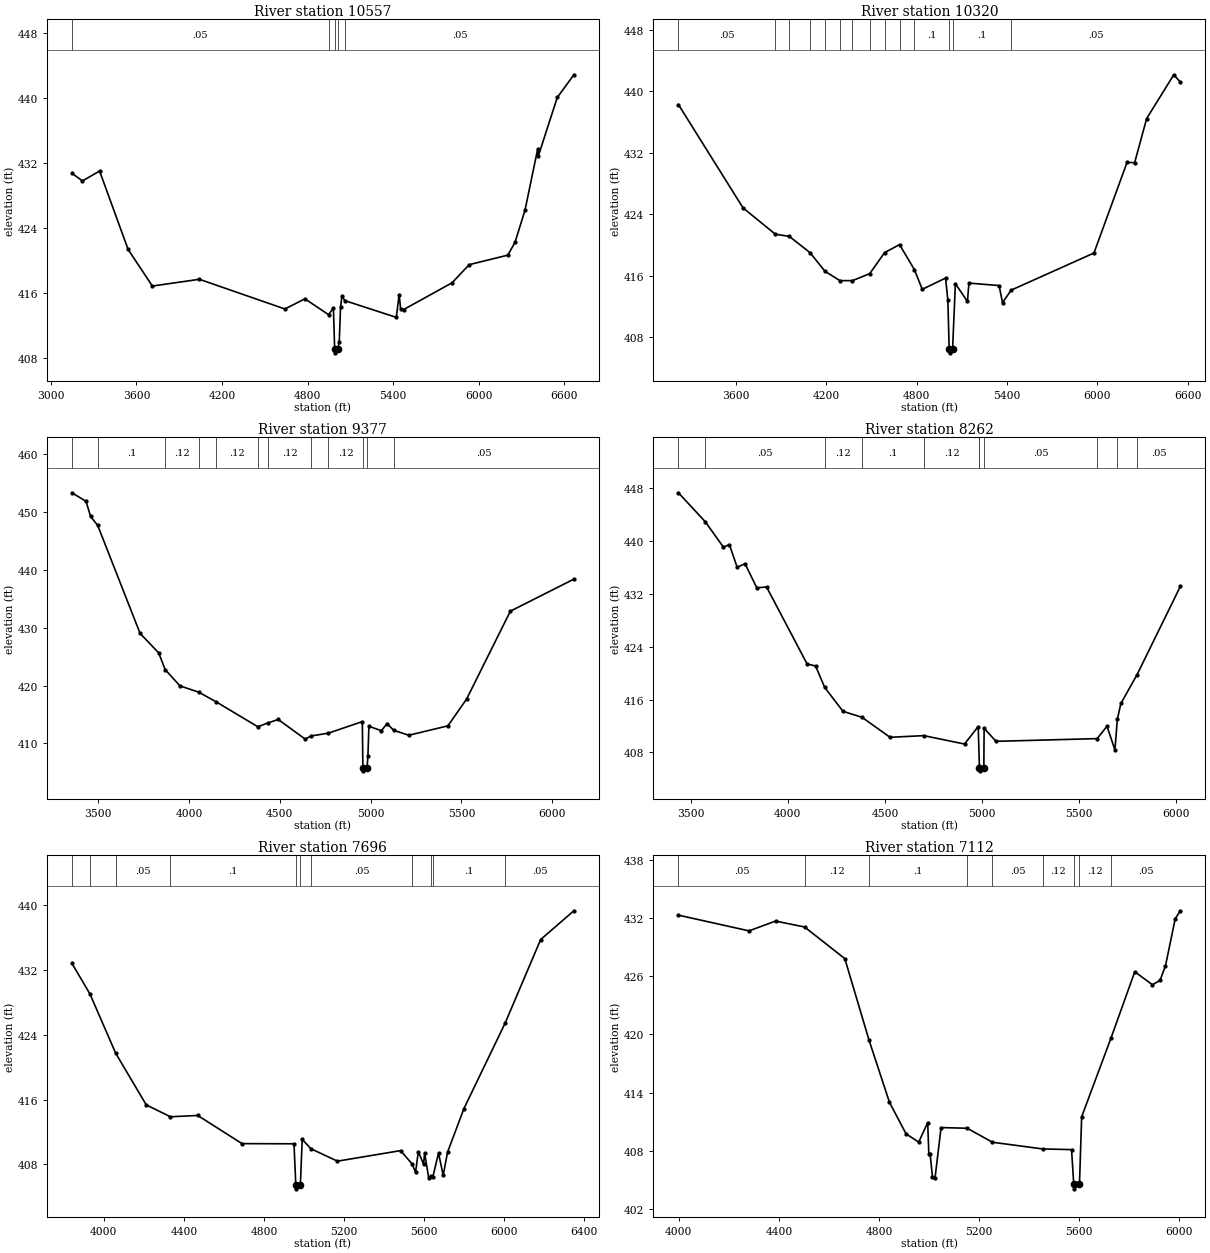
Type RM Length L Ch R = 1,10557,237,237,237
BEGIN DESCRIPTION:
Dry Lacy Fork 1988
END DESCRIPTION:
XS GIS Cut Line= 3
      2741899.88      6879280.51      2740028.95      6879282.62
      2738384.09      6879404.52
#Sta/Elev= 30
  3147.7  430.70  3221.6  429.76  3341.6  430.98  3541.6  421.34  3711.6  416.84
  4041.6  417.67  4641.6  414.02  4781.6  415.27  4947.7  413.32  4981.6  414.15
  4990.2  409.13  4992.5  408.63  5012.9  409.13  5022.6  410.00  5031.6  414.26
  5041.6  415.59  5062.9  415.04  5422.7  412.99  5442.7  415.80  5452.8  414.06
  5474.0  413.95  5813.8  417.24  5934.1  419.47  6204.8  420.64  6255.0  422.20
  6325.2  426.15  6413.9  433.65  6418.9  432.83  6551.7  440.02  6668.0  442.81
#Mann=5,-1,0
  3147.7    0.05       0  4947.7    0.12       0  4990.2    0.07       0
  5012.9    0.12       0  5062.9    0.05       0
Bank Sta=4990.2,5012.9
Exp/Cntr=0.3,0.1

Type RM Length L Ch R = 1,10320,943,943,943
BEGIN DESCRIPTION:
Dry Lacy Fork 1989
END DESCRIPTION:
XS GIS Cut Line= 3
      2741755.00      6879079.62      2739981.11      6879073.67
      2738422.54      6879083.32
#Sta/Elev= 30
  3218.7  438.25  3647.7  424.81  3862.1  421.39  3955.3  421.10  4093.0  418.98
  4192.0  416.56  4291.0  415.35  4374.2  415.35  4488.9  416.26  4587.9  419.00
  4686.9  420.03  4785.9  416.77  4837.7  414.22  4992.6  415.68  5007.7  412.82
  5016.4  406.46  5018.7  405.96  5039.1  406.46  5057.7  414.96  5137.7  412.64
  5147.7  415.03  5347.7  414.71  5370.9  412.48  5427.6  414.11  5977.7  418.94
  6197.7  430.74  6247.7  430.68  6327.7  436.43  6507.7  442.12  6551.2  441.17
#Mann=14,-1,0
  3218.7    0.05       0  3862.1    0.12       0  3955.3    0.05       0
  4093.0     0.1       0  4192.0    0.12       0  4291.0     0.1       0
  4374.2    0.12       0  4488.9    0.05       0  4587.9     0.1       0
  4686.9    0.05       0  4785.9     0.1       0  5016.4    0.07       0
  5039.1     0.1       0  5427.6    0.05       0
Bank Sta=5016.4,5039.1
Exp/Cntr=0.3,0.1

Type RM Length L Ch R = 1,9377,1115,1115,1115
BEGIN DESCRIPTION:
Dry Lacy Fork 22
END DESCRIPTION:
XS GIS Cut Line= 3
      2741075.99      6877761.00      2739526.00      6878311.00
      2738526.01      6878810.99
#Sta/Elev= 30
  3356.0  453.36  3433.2  451.89  3458.7  449.26  3497.6  447.72  3731.2  429.01
  3833.5  425.65  3868.9  422.77  3950.2  419.94  4054.4  418.84  4148.9  417.19
  4379.0  412.86  4437.6  413.55  4491.4  414.12  4639.9  410.72  4671.9  411.26
  4768.1  411.76  4954.4  413.75  4957.5  405.73  4959.7  405.23  4980.2  405.73
  4985.2  407.81  4990.6  412.95  5059.4  412.17  5090.1  413.41  5127.4  412.24
  5210.3  411.39  5425.5  413.02  5528.9  417.69  5769.3  432.87  6118.7  438.41
#Mann=12,-1,0
  3356.0    0.12       0  3497.6     0.1       0  3868.9    0.12       0
  4054.4    0.05       0  4148.9    0.12       0  4379.0     0.1       0
  4437.6    0.12       0  4671.9     0.1       0  4768.1    0.12       0
  4957.5    0.07       0  4980.2    0.12       0  5127.4    0.05       0
Bank Sta=4957.5,4980.2
Exp/Cntr=0.3,0.1

Type RM Length L Ch R = 1,8262,566,566,566
BEGIN DESCRIPTION:
Dry Lacy Fork 21
END DESCRIPTION:
XS GIS Cut Line= 3
      2740875.96      6877461.00      2739326.00      6877261.00
      2738326.02      6877461.00
#Sta/Elev= 30
  3437.6  447.32  3575.9  442.93  3669.5  439.07  3699.7  439.48  3740.0  436.03
  3780.4  436.58  3840.9  432.93  3891.3  433.05  4099.9  421.39  4143.4  421.09
  4190.3  417.84  4284.5  414.22  4382.1  413.32  4526.5  410.29  4700.2  410.54
  4909.7  409.27  4980.2  411.91  4986.3  405.91  4986.5  405.71  4988.8  405.21
  5009.2  405.71  5010.6  411.65  5071.8  409.68  5592.2  410.09  5642.9  411.96
  5683.7  408.38  5696.1  413.01  5714.3  415.41  5797.6  419.78  6020.2  433.13
#Mann=11,-1,0
  3437.6    0.12       0  3575.9    0.05       0  4190.3    0.12       0
  4382.1     0.1       0  4700.2    0.12       0  4986.3    0.05       0
  4986.5    0.04       0  5009.2    0.05       0  5592.2     0.1       0
  5696.1    0.12       0  5797.6    0.05       0
Bank Sta=4986.5,5009.2
Exp/Cntr=0.3,0.1

Type RM Length L Ch R = 1,7696,584,584,584
BEGIN DESCRIPTION:
Dry Lacy Fork 20
END DESCRIPTION:
XS GIS Cut Line= 3
      2740410.06      6876467.17      2739276.00      6876711.00
      2737975.97      6877061.01
#Sta/Elev= 30
  3841.1  432.78  3930.7  429.02  4060.1  421.68  4212.3  415.34  4333.0  413.88
  4469.2  414.04  4690.5  410.57  4949.9  410.55  4958.9  405.50  4961.2  405.00
  4981.8  405.50  4990.9  411.09  5035.2  409.93  5166.8  408.41  5482.3  409.71
  5539.8  408.06  5557.0  407.03  5570.7  409.59  5596.9  408.04  5602.1  409.42
  5622.4  406.39  5635.5  406.59  5643.0  406.44  5671.6  409.41  5694.9  406.66
  5716.8  409.52  5798.5  414.89  6004.8  425.45  6181.7  435.72  6347.4  439.26
#Mann=11,-1,0
  3841.1    0.05       0  3930.7    0.12       0  4060.1    0.05       0
  4333.0     0.1       0  4958.9    0.07       0  4981.8     0.1       0
  5035.2    0.05       0  5539.8     0.1       0  5635.5    0.12       0
  5643.0     0.1       0  6004.8    0.05       0
Bank Sta=4958.9,4981.8
Exp/Cntr=0.3,0.1

Type RM Length L Ch R = 1,7112,409,409,409
BEGIN DESCRIPTION:
Dry Lacy Fork 1986
END DESCRIPTION:
XS GIS Cut Line= 3
      2739961.00      6875916.12      2739019.76      6876259.15
      2738025.82      6876405.14
#Sta/Elev= 30
  3998.2  432.28  4280.3  430.66  4386.7  431.67  4502.6  431.06  4663.4  427.80
  4760.3  419.40  4841.9  413.00  4908.4  409.75  4958.9  408.90  4994.7  410.92
  4999.3  407.65  5004.4  407.65  5013.9  405.30  5024.0  405.21  5048.2  410.40
  5153.0  410.33  5253.4  408.89  5454.3  408.20  5569.8  408.13  5578.5  404.59
  5580.8  404.09  5601.5  404.59  5610.2  411.51  5727.5  419.62  5822.5  426.45
  5893.2  425.11  5923.6  425.56  5945.3  427.06  5984.2  431.91  6004.6  432.73
#Mann=9,-1,0
  3998.2    0.05       0  4502.6    0.12       0  4760.3     0.1       0
  5153.0    0.12       0  5253.4    0.05       0  5454.3    0.12       0
  5578.5    0.07       0  5601.5    0.12       0  5727.5    0.05       0
Bank Sta=5578.5,5601.5
Exp/Cntr=0.3,0.1

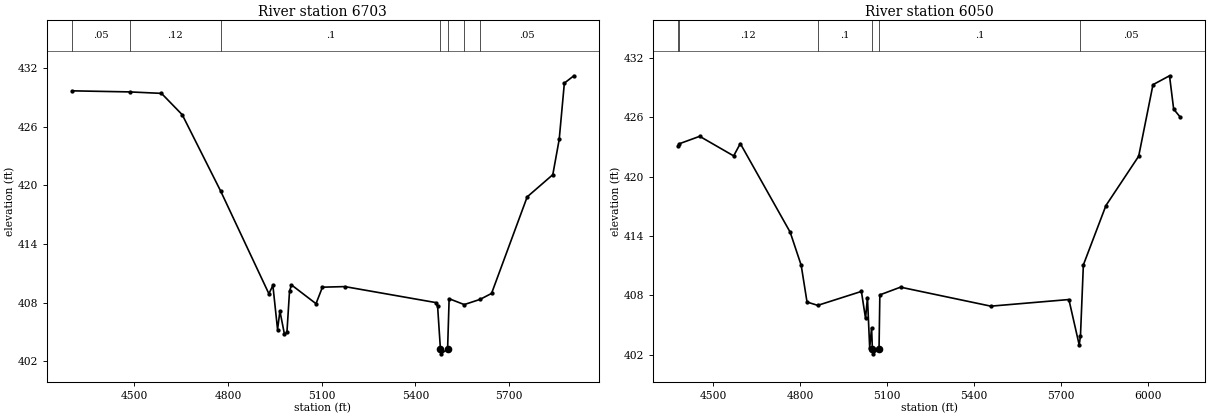
Type RM Length L Ch R = 1,6703,653,653,653
BEGIN DESCRIPTION:
Dry Lacy Fork 1985
END DESCRIPTION:
XS GIS Cut Line= 3
      2739498.42      6875576.43      2738876.10      6875895.60
      2737990.18      6876092.35
#Sta/Elev= 30
  4300.6  429.66  4485.1  429.55  4587.2  429.40  4653.8  427.21  4776.6  419.41
  4931.1  408.90  4943.9  409.75  4958.9  405.24  4966.4  407.13  4981.1  404.73
  4988.9  404.95  4997.2  409.16  5003.5  409.80  5082.0  407.88  5102.5  409.57
  5174.2  409.63  5464.6  408.00  5471.3  407.60  5480.3  403.25  5482.6  402.75
  5503.3  403.25  5508.2  408.39  5556.6  407.79  5607.1  408.32  5644.0  408.93
  5758.1  418.81  5840.1  421.08  5860.6  424.69  5877.1  430.45  5907.5  431.20
#Mann=7,-1,0
  4300.6    0.05       0  4485.1    0.12       0  4776.6     0.1       0
  5480.3    0.07       0  5503.3     0.1       0  5556.6    0.12       0
  5607.1    0.05       0
Bank Sta=5480.3,5503.3
Exp/Cntr=0.3,0.1

Type RM Length L Ch R = 1,6050,0,0,0
BEGIN DESCRIPTION:
Dry Lacy Fork 1984
END DESCRIPTION:
XS GIS Cut Line= 3
      2739389.44      6875325.84      2738770.20      6875358.50
      2737923.14      6876080.63
#Sta/Elev= 30
  4379.9  423.06  4382.2  423.32  4453.4  424.08  4570.7  422.10  4593.6  423.35
  4765.8  414.39  4803.9  411.04  4824.0  407.33  4860.9  406.99  5011.8  408.40
  5026.1  405.67  5032.7  407.78  5040.4  402.70  5047.0  404.73  5049.7  402.59
  5052.0  402.09  5072.7  402.59  5075.5  408.05  5146.9  408.83  5458.7  406.91
  5728.3  407.58  5764.0  402.98  5768.3  403.92  5778.3  411.08  5856.2  417.08
  5969.3  422.07  6018.7  429.30  6075.8  430.20  6090.1  426.83  6113.1  426.01
#Mann=6,-1,0
  4379.9    0.05       0  4382.2    0.12       0  4860.9     0.1       0
  5049.7    0.07       0  5072.7     0.1       0  5768.3    0.05       0
Bank Sta=5049.7,5072.7
Exp/Cntr=0.3,0.1

Chan Stop Cuts=-1