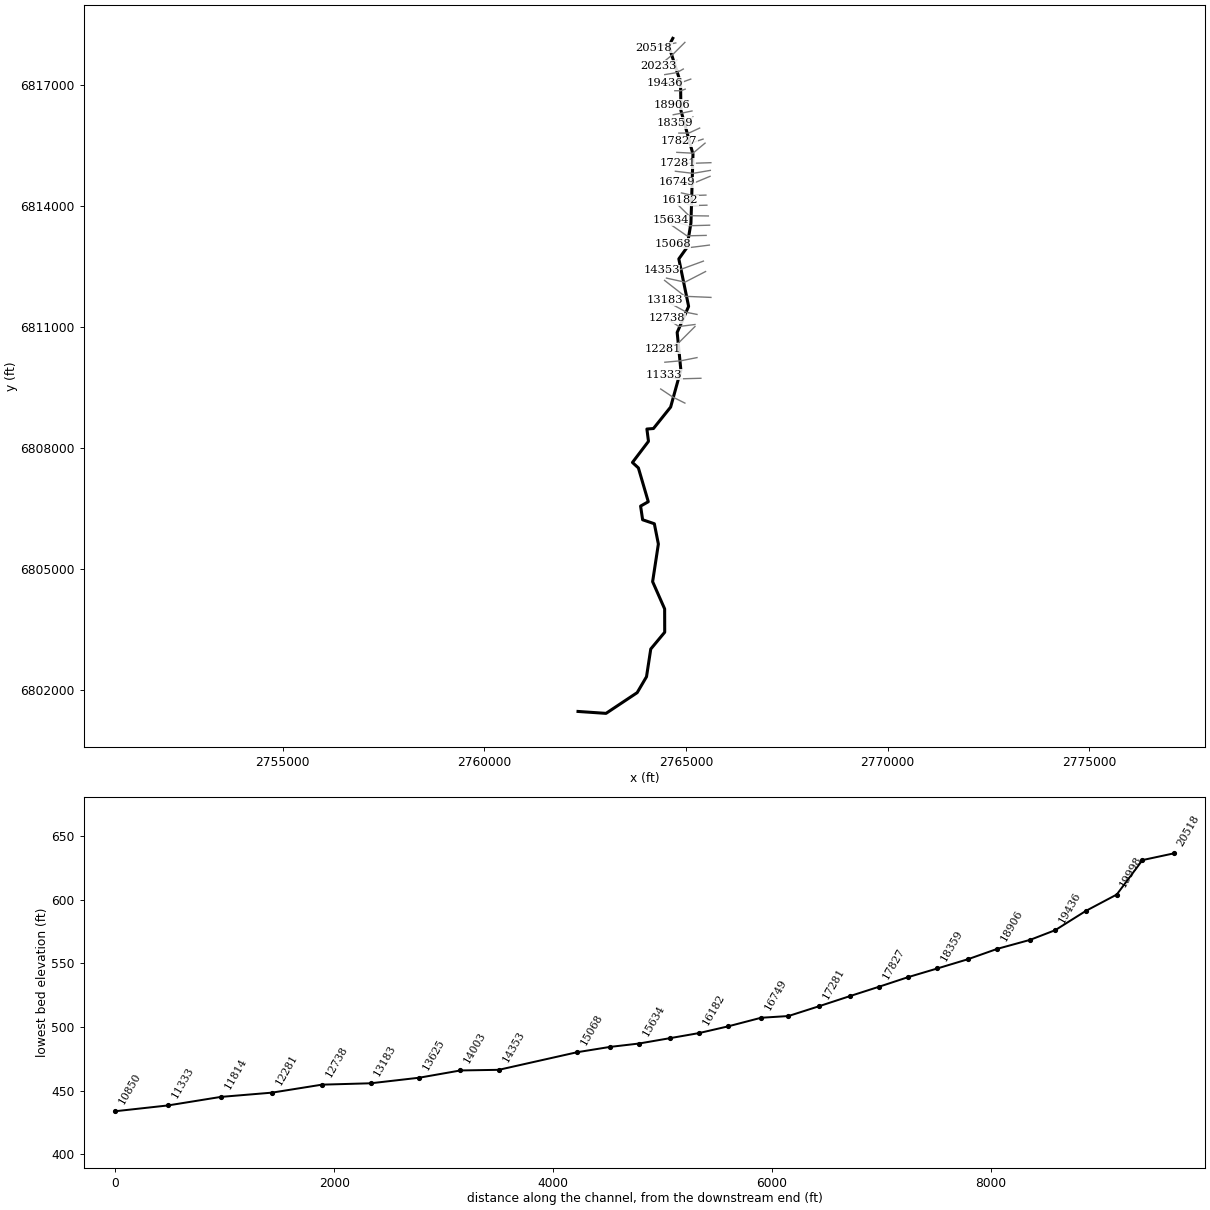
--- Helms Branch.prj (project) ---

Proj Title=Helms Branch Base Level Engineering
Current Plan=p01
Default Exp/Contr=0.3,0.1
English Units
Geom File=g01
Flow File=f01
Plan File=p01
BEGIN DESCRIPTION:
Helms Branch
END DESCRIPTION:

--- Helms Branch.p01 (plan) ---

Plan Title=Multiple Run
Short Identifier=Multiple
Geom File=g01
Flow File=f01
Subcritical Flow
K Sum by GR= 0
Std Step Tol= 0.01
Critical Tol= 0.01
Num of Std Step Trials= 20
Max Error Tol= 0.3
Flow Tol Ratio= 0.001
Split Flow NTrial= 30
Split Flow Tol= 0.02
Split Flow Ratio= 0.02
Log Output Level= 0
Friction Slope Method= 1
Unsteady Friction Slope Method= 2
Unsteady Bridges Friction Slope Method= 1
Parabolic Critical Depth
Global Vel Dist=  1 , 1 , 1
Global Log Level= 0
CheckData=True
Encroach Param= -1, 0, 0, 0
BEGIN DESCRIPTION:
Multiple Run
END DESCRIPTION:

--- Helms Branch.f01 (steady flow) ---

Flow Title=Multiple
Number of Profiles=7
Profile Names=10-year,25-year,50-year,1pct_min,100-year,1pct_plu,500-year
River Rch & RM= Helms Branch,Reach-1,20518
     434     587     713     433     864    1724    1269
River Rch & RM= Helms Branch,Reach-1,14353
     945    1344    1689    1057    2109    4207    3294
River Rch & RM= Helms Branch,Reach-1,13183
    1118    1592    2002    1251    2496    4981    3892
River Rch & RM= Helms Branch,Reach-1,5961
    1225    1745    2194    1371    2735    5457    4260
Boundary for River Rch & Prof#=Helms Branch,Reach-1,1
Up Type=0
Dn Type=3
Dn Slope=0.005
Boundary for River Rch & Prof#=Helms Branch,Reach-1,2
Up Type=0
Dn Type=3
Dn Slope=0.005
Boundary for River Rch & Prof#=Helms Branch,Reach-1,3
Up Type=0
Dn Type=3
Dn Slope=0.005
Boundary for River Rch & Prof#=Helms Branch,Reach-1,4
Up Type=0
Dn Type=3
Dn Slope=0.005
Boundary for River Rch & Prof#=Helms Branch,Reach-1,5
Up Type=0
Dn Type=3
Dn Slope=0.005
Boundary for River Rch & Prof#=Helms Branch,Reach-1,6
Up Type=0
Dn Type=3
Dn Slope=0.005
Boundary for River Rch & Prof#=Helms Branch,Reach-1,7
Up Type=0
Dn Type=3
Dn Slope=0.005

--- Helms Branch.g01 (geometry) ---

Geom Title=Existing Conditions

River Reach=Helms Branch,Reach-1
Reach XY= 30
      2764676.00      6818161.00      2764577.10      6817971.55
      2764867.93      6817064.31      2764877.38      6816370.66
      2765176.39      6815286.00      2765125.62      6813576.27
      2765023.76      6812966.93      2764825.49      6812688.38
      2765068.44      6811511.00      2764784.27      6810864.22
      2764875.94      6809931.03      2764622.24      6809012.56
      2764196.03      6808480.30      2764033.74      6808467.55
      2764072.99      6808162.43      2763675.43      6807638.20
      2763822.84      6807502.66      2764068.25      6806664.02
      2763877.65      6806555.58      2763927.97      6806216.65
      2764218.19      6806117.82      2764318.22      6805614.42
      2764175.57      6804681.03      2764473.74      6804005.06
      2764475.49      6803426.21      2764129.45      6803009.75
      2764024.35      6802322.83      2763792.75      6801927.46
      2763020.14      6801413.07      2762326.00      6801461.00

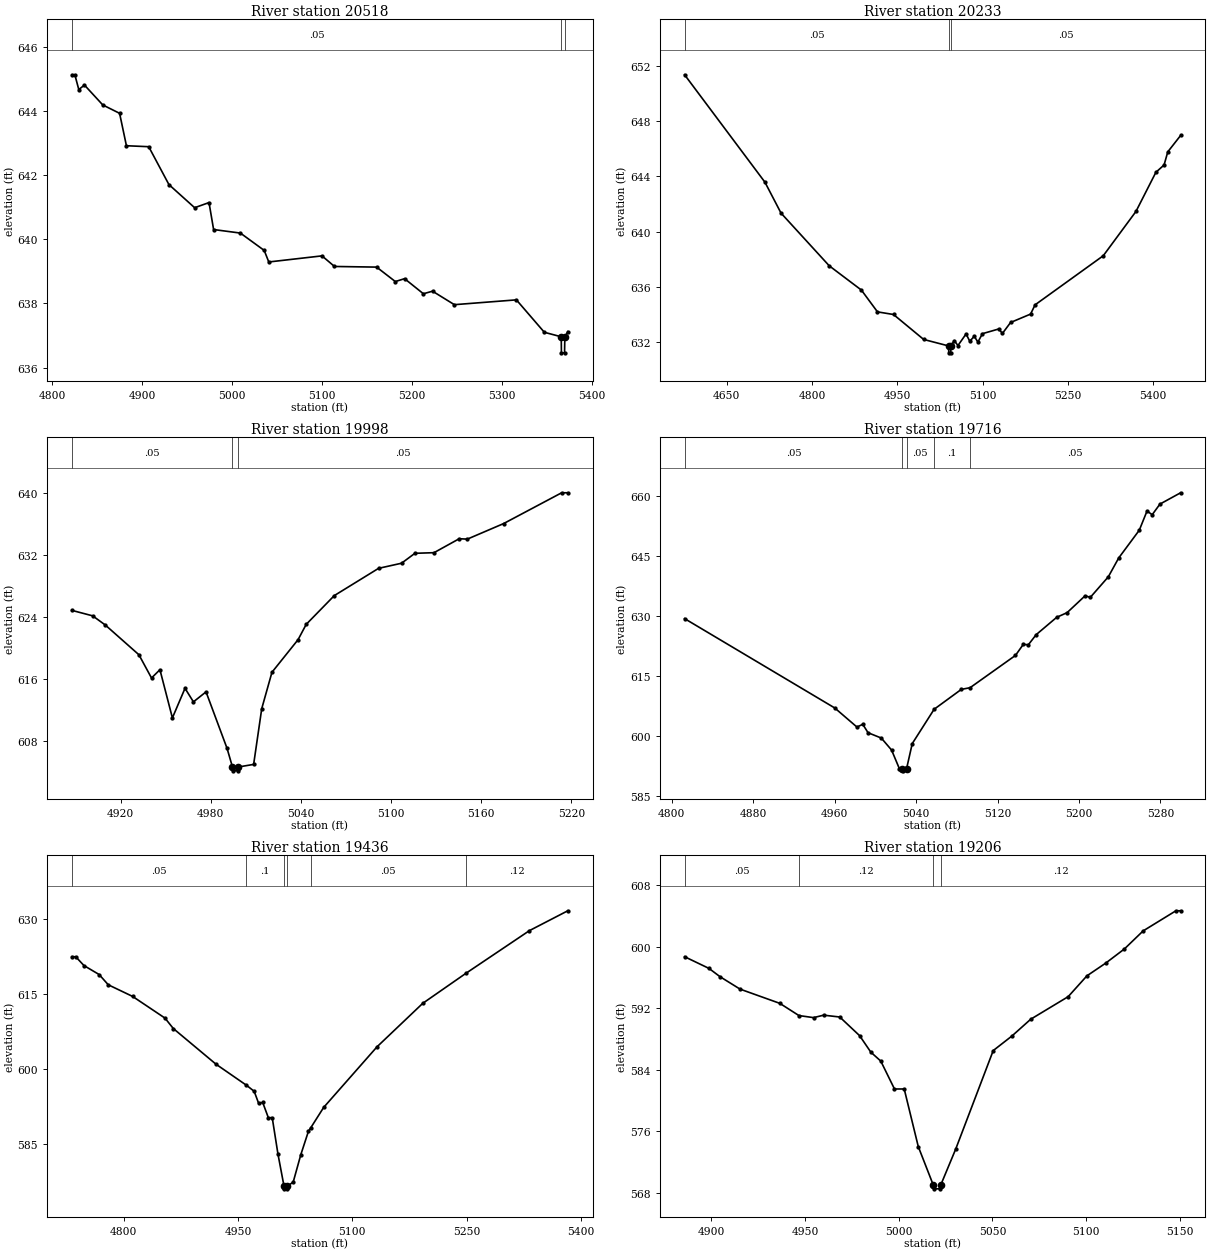
Type RM Length L Ch R = 1,20518,285,285,285
BEGIN DESCRIPTION:
1087
END DESCRIPTION:
XS GIS Cut Line= 5
      2764749.80      6818047.33      2764689.53      6818035.03
      2764576.00      6818011.00      2764425.17      6817990.87
      2764210.85      6817932.33
#Sta/Elev= 30
  4821.6  645.12  4825.0  645.12  4829.4  644.66  4835.7  644.80  4856.1  644.18
  4874.8  643.92  4882.4  642.91  4907.2  642.88  4929.7  641.70  4958.3  640.98
  4974.3  641.14  4979.4  640.30  5009.2  640.19  5035.7  639.65  5040.8  639.29
  5100.0  639.48  5113.9  639.15  5160.8  639.13  5181.6  638.68  5191.9  638.77
  5212.8  638.30  5223.0  638.38  5247.3  637.96  5316.3  638.11  5347.4  637.10
  5366.2  636.96  5366.4  636.46  5369.9  636.46  5370.2  636.96  5373.5  637.12
#Mann=3,-1,0
  4821.6    0.05       0  5366.2    0.04       0  5370.2    0.05       0
Bank Sta=5366.2,5370.2
Exp/Cntr=0.3,0.1

Type RM Length L Ch R = 1,20233,235,235,235
BEGIN DESCRIPTION:
1086
END DESCRIPTION:
XS GIS Cut Line= 3
      2764975.96      6818060.96      2764676.00      6817761.00
      2764327.83      6817478.15
#Sta/Elev= 30
  4575.8  651.37  4717.2  643.58  4745.5  641.34  4830.3  637.52  4886.9  635.76
  4915.2  634.18  4943.4  633.99  4996.5  632.18  5040.4  631.71  5040.6  631.21
  5044.1  631.21  5044.4  631.71  5050.3  632.10  5056.8  631.74  5071.1  632.58
  5077.6  632.05  5085.5  632.41  5091.9  631.99  5099.9  632.60  5128.6  632.94
  5135.1  632.62  5149.4  633.41  5184.6  634.02  5192.5  634.69  5312.5  638.25
  5370.0  641.46  5405.1  644.30  5419.5  644.83  5426.0  645.78  5448.6  646.97
#Mann=3,-1,0
  4575.8    0.05       0  5040.4    0.04       0  5044.4    0.05       0
Bank Sta=5040.4,5044.4
Exp/Cntr=0.3,0.1

Type RM Length L Ch R = 1,19998,282,282,282
BEGIN DESCRIPTION:
1085
END DESCRIPTION:
XS GIS Cut Line= 3
      2764775.96      6817610.98      2764676.00      6817561.00
      2764473.37      6817479.14
#Sta/Elev= 30
  4887.4  624.84  4901.3  624.13  4909.7  622.95  4932.1  619.11  4940.5  616.11
  4946.1  617.18  4954.4  610.96  4962.8  614.78  4968.4  613.03  4976.8  614.32
  4990.8  607.03  4994.4  604.63  4994.6  604.13  4998.1  604.13  4998.4  604.63
  5008.5  604.96  5013.9  612.16  5020.7  616.85  5038.1  621.06  5043.5  623.03
  5062.2  626.74  5091.7  630.26  5107.0  630.92  5115.9  632.20  5128.6  632.28
  5145.4  634.08  5150.8  634.03  5174.9  636.03  5213.6  640.01  5217.7  640.01
#Mann=3,-1,0
  4887.4    0.05       0  4994.4    0.04       0  4998.4    0.05       0
Bank Sta=4994.4,4998.4
Exp/Cntr=0.3,0.1

Type RM Length L Ch R = 1,19716,280,280,280
BEGIN DESCRIPTION:
1084
END DESCRIPTION:
XS GIS Cut Line= 3
      2764936.20      6817399.56      2764776.00      6817311.00
      2764475.98      6817261.00
#Sta/Elev= 30
  4812.6  629.34  4960.1  606.99  4981.9  602.22  4987.6  602.91  4992.8  600.80
  5005.8  599.47  5015.9  596.47  5023.5  591.85  5026.6  591.77  5026.8  591.27
  5030.6  591.77  5036.2  598.08  5057.7  606.67  5084.4  611.64  5093.0  612.06
  5137.6  620.14  5145.2  622.87  5150.3  622.82  5157.9  625.32  5178.1  629.67
  5188.3  630.83  5206.0  635.05  5211.1  634.65  5228.8  639.80  5239.0  644.51
  5259.2  651.45  5266.8  656.24  5271.9  655.33  5279.5  657.98  5299.8  660.81
#Mann=5,-1,0
  4812.6    0.05       0  5026.6    0.04       0  5030.6    0.05       0
  5057.7     0.1       0  5093.0    0.05       0
Bank Sta=5026.6,5030.6
Exp/Cntr=0.3,0.1

Type RM Length L Ch R = 1,19436,230,230,230
BEGIN DESCRIPTION:
1083
END DESCRIPTION:
XS GIS Cut Line= 3
      2765121.02      6817149.55      2764876.00      6817061.00
      2764485.74      6817063.80
#Sta/Elev= 30
  4731.9  622.47  4737.1  622.47  4747.9  620.71  4767.8  618.92  4779.8  616.87
  4811.7  614.55  4854.2  610.22  4865.1  608.14  4921.1  601.02  4961.1  596.81
  4971.2  595.61  4977.1  593.19  4982.4  593.38  4989.8  590.34  4994.9  590.34
  5002.4  583.09  5010.4  576.63  5010.7  576.13  5014.2  576.13  5014.4  576.63
  5022.4  577.47  5032.4  582.95  5042.4  587.62  5045.2  588.26  5062.4  592.39
  5132.4  604.49  5192.4  613.17  5249.0  619.16  5332.4  627.69  5382.7  631.65
#Mann=6,-1,0
  4731.9    0.05       0  4961.1     0.1       0  5010.4    0.07       0
  5014.4     0.1       0  5045.2    0.05       0  5249.0    0.12       0
Bank Sta=5010.4,5014.4
Exp/Cntr=0.3,0.1

Type RM Length L Ch R = 1,19206,300,300,300
BEGIN DESCRIPTION:
1082
END DESCRIPTION:
XS GIS Cut Line= 3
      2764983.78      6816900.25      2764876.00      6816861.00
      2764726.00      6816861.00
#Sta/Elev= 30
  4885.7  598.72  4898.7  597.20  4904.6  596.12  4915.3  594.50  4936.5  592.65
  4946.7  591.06  4954.5  590.79  4959.9  591.11  4968.5  590.87  4979.1  588.44
  4985.1  586.29  4990.4  585.13  4997.7  581.50  5002.9  581.50  5010.4  574.00
  5018.4  569.00  5018.7  568.50  5022.2  568.50  5022.4  569.00  5030.4  573.69
  5050.4  586.50  5060.4  588.40  5070.4  590.58  5090.4  593.52  5100.4  596.23
  5110.4  597.88  5120.4  599.73  5130.4  602.08  5147.9  604.70  5150.4  604.70
#Mann=4,-1,0
  4885.7    0.05       0  4946.7    0.12       0  5018.4    0.07       0
  5022.4    0.12       0
Bank Sta=5018.4,5022.4
Exp/Cntr=0.3,0.1

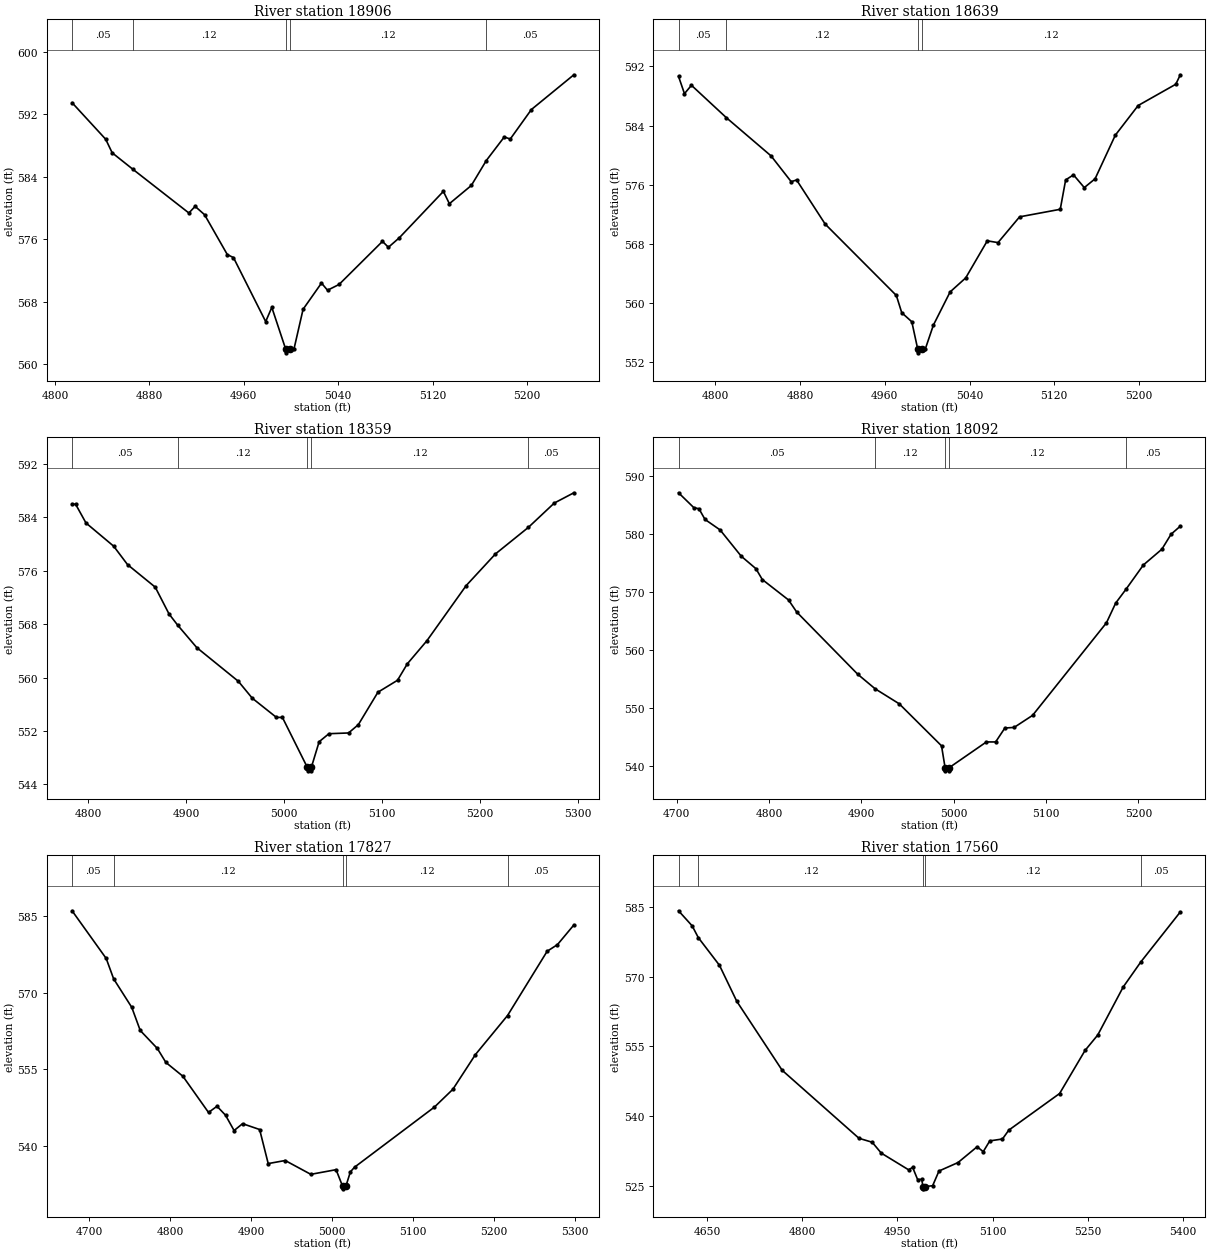
Type RM Length L Ch R = 1,18906,267,267,267
BEGIN DESCRIPTION:
1081
END DESCRIPTION:
XS GIS Cut Line= 3
      2765053.19      6816616.19      2764876.00      6816561.00
      2764640.70      6816515.21
#Sta/Elev= 30
  4814.4  593.51  4842.9  588.82  4848.4  587.08  4866.0  584.96  4913.4  579.36
  4918.7  580.21  4926.7  579.14  4946.0  574.02  4951.2  573.64  4978.5  565.43
  4983.7  567.25  4995.4  561.92  4995.6  561.42  4999.4  561.92  5002.5  561.92
  5010.2  567.01  5025.8  570.37  5030.9  569.45  5040.7  570.19  5077.5  575.72
  5082.5  574.96  5091.7  576.17  5129.1  582.13  5134.2  580.55  5152.8  582.89
  5165.5  586.09  5180.7  589.11  5185.8  588.85  5203.7  592.63  5239.7  597.09
#Mann=5,-1,0
  4814.4    0.05       0  4866.0    0.12       0  4995.4    0.07       0
  4999.4    0.12       0  5165.5    0.05       0
Bank Sta=4995.4,4999.4
Exp/Cntr=0.3,0.1

Type RM Length L Ch R = 1,18639,280,280,280
BEGIN DESCRIPTION:
1080
END DESCRIPTION:
XS GIS Cut Line= 3
      2765151.45      6816358.84      2764926.00      6816311.00
      2764686.93      6816265.17
#Sta/Elev= 30
  4765.2  590.64  4770.8  588.31  4777.4  589.44  4810.4  585.06  4852.6  579.90
  4871.6  576.42  4876.7  576.65  4903.7  570.69  4970.9  561.05  4976.0  558.72
  4985.5  557.50  4991.1  553.80  4991.4  553.30  4995.1  553.80  4998.2  553.80
  5005.9  557.05  5021.7  561.53  5036.4  563.42  5056.8  568.43  5066.9  568.19
  5087.3  571.67  5125.7  572.69  5130.8  576.66  5138.2  577.34  5148.4  575.62
  5158.6  576.81  5177.7  582.70  5199.3  586.71  5234.8  589.58  5239.1  590.86
#Mann=4,-1,0
  4765.2    0.05       0  4810.4    0.12       0  4991.1    0.07       0
  4995.1    0.12       0
Bank Sta=4991.1,4995.1
Exp/Cntr=0.3,0.1

Type RM Length L Ch R = 1,18359,267,267,267
BEGIN DESCRIPTION:
1079
END DESCRIPTION:
XS GIS Cut Line= 3
      2765176.03      6816211.03      2765026.00      6816061.00
      2764725.97      6816061.00
#Sta/Elev= 30
  4783.3  585.96  4786.9  585.96  4797.5  583.15  4825.8  579.67  4839.9  576.92
  4868.2  573.54  4882.3  569.52  4891.2  567.83  4910.6  564.49  4953.0  559.45
  4967.2  556.92  4991.9  554.04  4998.0  554.04  5023.5  546.54  5023.7  546.04
  5027.2  546.04  5027.5  546.54  5035.5  550.40  5045.5  551.60  5065.5  551.71
  5075.5  552.95  5095.5  557.81  5115.5  559.60  5125.5  562.06  5145.5  565.52
  5185.5  573.76  5215.5  578.52  5249.0  582.48  5275.5  586.13  5295.5  587.67
#Mann=5,-1,0
  4783.3    0.05       0  4891.2    0.12       0  5023.5    0.07       0
  5027.5    0.12       0  5249.0    0.05       0
Bank Sta=5023.5,5027.5
Exp/Cntr=0.3,0.1

Type RM Length L Ch R = 1,18092,265,265,265
BEGIN DESCRIPTION:
1078
END DESCRIPTION:
XS GIS Cut Line= 3
      2765341.99      6815934.90      2765076.00      6815811.00
      2764826.03      6815811.00
#Sta/Elev= 30
  4702.0  587.13  4718.6  584.56  4724.1  584.38  4730.7  582.53  4747.0  580.73
  4769.9  576.20  4785.8  574.05  4792.7  572.18  4821.1  568.66  4830.0  566.57
  4896.1  555.85  4914.9  553.35  4941.0  550.76  4986.8  543.52  4990.7  539.71
  4990.9  539.21  4994.4  539.21  4994.7  539.71  5035.4  544.19  5045.4  544.19
  5055.4  546.59  5065.4  546.69  5085.4  548.77  5165.4  564.72  5175.4  568.12
  5186.5  570.49  5205.4  574.69  5225.4  577.40  5235.4  579.99  5245.4  581.38
#Mann=5,-1,0
  4702.0    0.05       0  4914.9    0.12       0  4990.7    0.07       0
  4994.7    0.12       0  5186.5    0.05       0
Bank Sta=4990.7,4994.7
Exp/Cntr=0.3,0.1

Type RM Length L Ch R = 1,17827,267,267,267
BEGIN DESCRIPTION:
1077
END DESCRIPTION:
XS GIS Cut Line= 3
      2765426.01      6815661.00      2765126.00      6815561.00
      2764825.98      6815611.00
#Sta/Elev= 30
  4678.7  585.96  4720.9  576.65  4730.1  572.67  4752.5  567.11  4763.0  562.59
  4784.1  559.09  4794.7  556.35  4815.7  553.66  4847.4  546.59  4857.9  547.80
  4868.4  546.06  4879.0  543.06  4889.5  544.40  4910.6  543.26  4921.2  536.61
  4942.2  537.21  4973.9  534.51  5005.1  535.42  5013.2  532.18  5013.5  531.68
  5017.2  532.18  5022.8  534.99  5027.9  535.90  5126.7  547.64  5149.5  551.11
  5177.4  557.89  5217.1  565.51  5266.1  578.06  5278.8  579.35  5299.1  583.19
#Mann=5,-1,0
  4678.7    0.05       0  4730.1    0.12       0  5013.2    0.07       0
  5017.2    0.12       0  5217.1    0.05       0
Bank Sta=5013.2,5017.2
Exp/Cntr=0.3,0.1

Type RM Length L Ch R = 1,17560,279,279,279
BEGIN DESCRIPTION:
1076
END DESCRIPTION:
XS GIS Cut Line= 3
      2765476.03      6815561.02      2765176.00      6815311.00
      2764776.01      6815332.17
#Sta/Elev= 30
  4604.8  584.20  4626.3  580.95  4636.0  578.41  4669.3  572.46  4696.6  564.70
  4768.2  549.83  4889.3  535.18  4910.1  534.33  4924.4  531.99  4967.4  528.40
  4973.9  528.91  4981.7  526.30  4988.2  526.33  4990.1  524.79  4990.3  524.29
  4994.1  524.79  5005.4  524.96  5015.4  528.13  5045.4  529.95  5075.5  533.35
  5085.2  532.30  5095.5  534.62  5115.5  535.03  5125.5  536.94  5205.6  544.83
  5245.7  554.11  5265.7  557.43  5305.8  567.77  5333.7  573.19  5395.9  583.95
#Mann=5,-1,0
  4604.8    0.05       0  4636.0    0.12       0  4990.1    0.07       0
  4994.1    0.12       0  5333.7    0.05       0
Bank Sta=4990.1,4994.1
Exp/Cntr=0.3,0.1

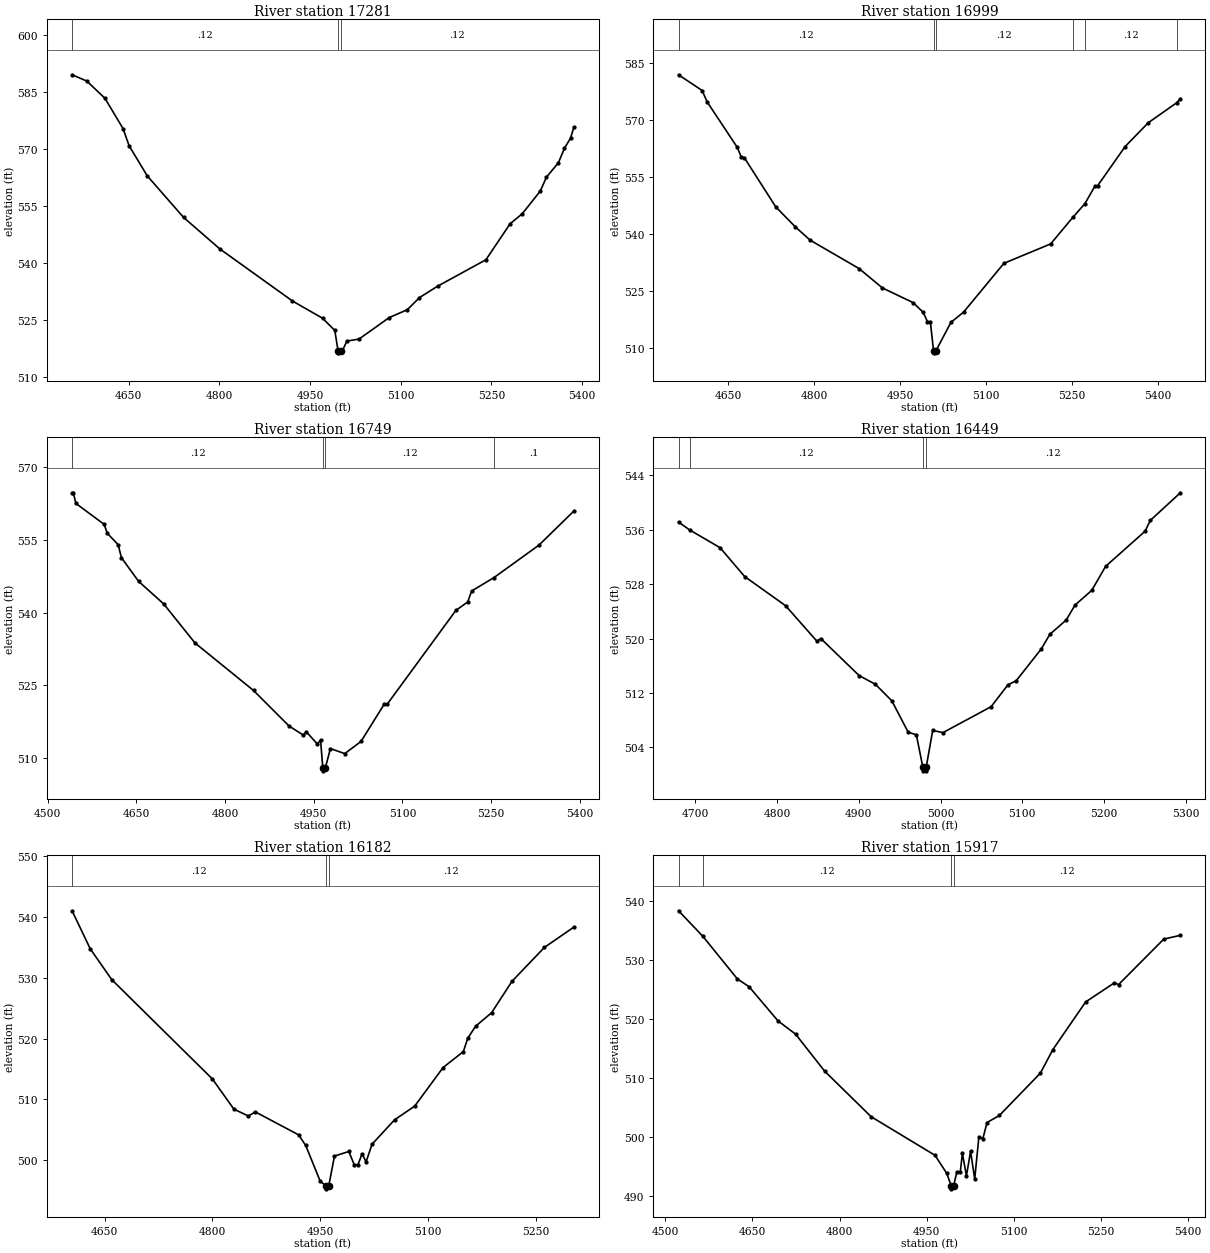
Type RM Length L Ch R = 1,17281,282,282,282
BEGIN DESCRIPTION:
1075
END DESCRIPTION:
XS GIS Cut Line= 3
      2765620.34      6815075.82      2765176.00      6815061.00
      2764790.49      6815059.76
#Sta/Elev= 30
  4556.2  589.47  4580.5  587.83  4610.6  583.29  4640.6  575.31  4650.6  570.81
  4680.6  562.91  4740.6  552.01  4800.7  543.71  4920.7  530.05  4970.8  525.49
  4990.8  522.30  4996.3  516.92  4996.5  516.42  5000.3  516.92  5003.3  516.92
  5010.8  519.51  5030.8  520.03  5080.8  525.68  5110.8  527.75  5130.8  530.92
  5160.8  533.92  5240.8  540.87  5280.8  550.32  5300.8  552.94  5330.8  558.92
  5340.8  562.53  5360.8  566.38  5370.8  570.17  5380.8  572.84  5386.3  575.66
#Mann=3,-1,0
  4556.2    0.12       0  4996.3    0.07       0  5000.3    0.12       0
Bank Sta=4996.3,5000.3
Exp/Cntr=0.3,0.1

Type RM Length L Ch R = 1,16999,250,250,250
BEGIN DESCRIPTION:
1074
END DESCRIPTION:
XS GIS Cut Line= 3
      2765606.68      6814884.98      2765176.00      6814811.00
      2764740.36      6814863.61
#Sta/Elev= 30
  4563.4  581.83  4604.7  577.68  4613.1  574.74  4665.6  562.80  4673.1  560.14
  4678.1  560.04  4733.0  547.08  4767.0  541.84  4793.0  538.31  4878.6  530.82
  4919.2  525.73  4972.9  521.86  4990.2  519.35  4997.9  516.86  5002.9  516.86
  5008.5  509.15  5008.7  508.65  5012.5  509.15  5038.9  516.69  5060.8  519.35
  5131.3  532.21  5212.9  537.32  5251.6  544.31  5272.6  547.90  5289.9  552.45
  5294.9  552.64  5342.9  562.95  5383.2  569.20  5432.6  574.44  5439.2  575.53
#Mann=6,-1,0
  4563.4    0.12       0  5008.5    0.07       0  5012.5    0.12       0
  5251.6     0.1       0  5272.6    0.12       0  5432.6    0.05       0
Bank Sta=5008.5,5012.5
Exp/Cntr=0.3,0.1

Type RM Length L Ch R = 1,16749,300,300,300
BEGIN DESCRIPTION:
1073
END DESCRIPTION:
XS GIS Cut Line= 3
      2765599.25      6814737.58      2765176.00      6814561.00
      2764786.93      6814587.75
#Sta/Elev= 30
  4541.4  564.77  4543.4  564.77  4547.9  562.56  4595.6  558.25  4601.0  556.40
  4619.4  554.03  4624.8  551.36  4654.0  546.45  4696.3  541.80  4749.3  533.72
  4848.3  523.90  4908.5  516.54  4932.3  514.70  4937.7  515.34  4956.2  512.83
  4961.6  513.67  4965.5  507.79  4965.8  507.29  4969.5  507.79  4978.3  511.90
  5002.5  510.85  5030.1  513.37  5069.0  521.02  5074.0  521.01  5190.5  540.46
  5210.5  542.20  5217.1  544.46  5254.9  547.24  5330.8  553.93  5390.0  560.99
#Mann=4,-1,0
  4541.4    0.12       0  4965.5    0.07       0  4969.5    0.12       0
  5254.9     0.1       0
Bank Sta=4965.5,4969.5
Exp/Cntr=0.3,0.1

Type RM Length L Ch R = 1,16449,267,267,267
BEGIN DESCRIPTION:
1072
END DESCRIPTION:
XS GIS Cut Line= 3
      2765496.81      6814271.81      2765176.00      6814261.00
      2764890.25      6814325.85
#Sta/Elev= 30
  4679.4  537.13  4693.0  535.97  4730.2  533.36  4760.3  529.12  4810.3  524.84
  4848.6  519.63  4853.6  520.00  4900.3  514.57  4920.3  513.28  4940.4  510.85
  4960.4  506.24  4970.4  505.85  4978.4  501.06  4978.6  500.56  4982.1  500.56
  4982.4  501.06  4990.4  506.49  5003.0  506.18  5061.9  509.99  5082.4  513.19
  5092.7  513.82  5123.4  518.50  5133.7  520.62  5153.8  522.73  5164.5  524.92
  5185.0  527.08  5202.0  530.62  5250.3  535.78  5256.7  537.37  5293.4  541.43
#Mann=4,-1,0
  4679.4     0.1       0  4693.0    0.12       0  4978.4    0.07       0
  4982.4    0.12       0
Bank Sta=4978.4,4982.4
Exp/Cntr=0.3,0.1

Type RM Length L Ch R = 1,16182,265,265,265
BEGIN DESCRIPTION:
1071
END DESCRIPTION:
XS GIS Cut Line= 3
      2765521.33      6814021.30      2765126.00      6814011.00
      2764852.99      6814143.42
#Sta/Elev= 30
  4604.5  541.04  4629.8  534.78  4659.9  529.68  4799.9  513.35  4829.9  508.37
  4849.9  507.25  4859.9  507.91  4919.9  504.15  4929.9  502.40  4950.0  496.53
  4958.0  495.75  4958.2  495.25  4962.0  495.75  4970.0  500.65  4990.0  501.40
  4997.5  499.22  5002.7  499.22  5008.5  501.04  5014.0  499.67  5022.2  502.58
  5053.6  506.61  5081.7  508.87  5121.3  515.23  5149.5  517.85  5155.6  520.05
  5166.5  522.02  5188.9  524.26  5217.2  529.42  5262.3  535.00  5303.4  538.35
#Mann=3,-1,0
  4604.5    0.12       0  4958.0    0.07       0  4962.0    0.12       0
Bank Sta=4958,4962
Exp/Cntr=0.3,0.1

Type RM Length L Ch R = 1,15917,283,283,283
BEGIN DESCRIPTION:
1070
END DESCRIPTION:
XS GIS Cut Line= 3
      2765557.27      6813753.75      2765076.00      6813761.00
      2764804.32      6814029.64
#Sta/Elev= 30
  4522.9  538.27  4564.7  533.96  4624.2  526.74  4644.2  525.44  4694.2  519.64
  4724.2  517.42  4774.2  511.17  4854.2  503.46  4964.2  496.93  4984.2  493.91
  4992.2  491.76  4992.5  491.26  4996.2  491.76  5001.7  494.10  5007.7  494.10
  5011.3  497.26  5018.3  493.47  5025.4  497.59  5032.5  492.92  5039.6  499.96
  5046.6  499.76  5053.7  502.47  5074.9  503.66  5145.6  510.83  5166.9  514.79
  5223.4  522.86  5272.9  526.09  5280.0  525.79  5357.8  533.48  5386.3  534.12
#Mann=4,-1,0
  4522.9    0.05       0  4564.7    0.12       0  4992.2    0.07       0
  4996.2    0.12       0
Bank Sta=4992.2,4996.2
Exp/Cntr=0.3,0.1

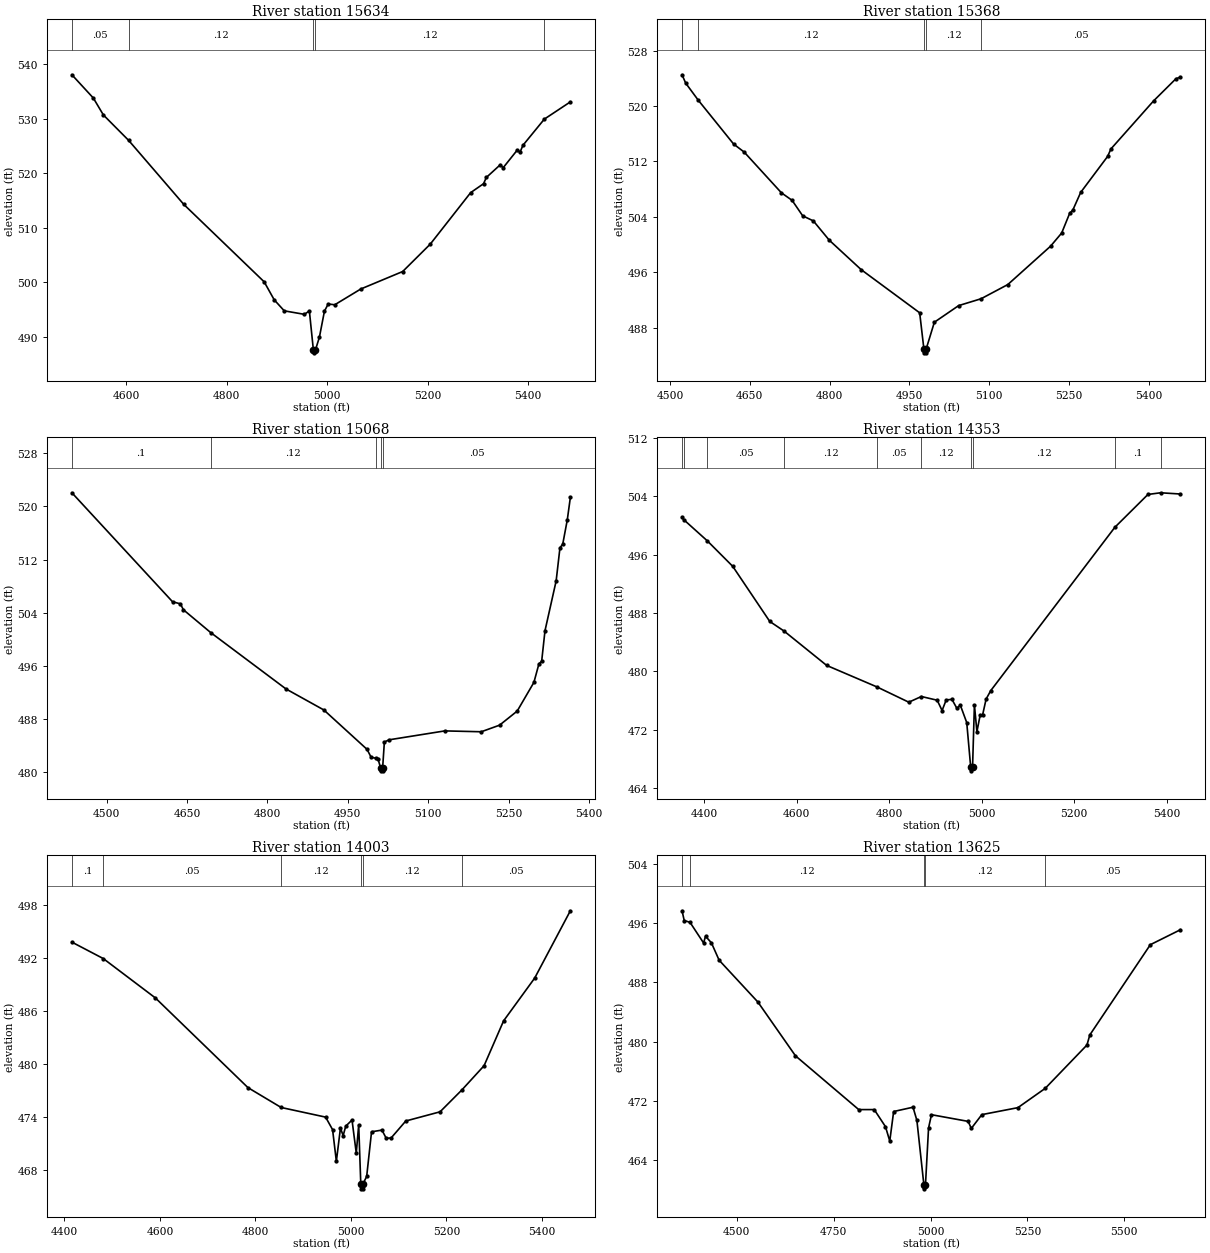
Type RM Length L Ch R = 1,15634,266,266,266
BEGIN DESCRIPTION:
1069
END DESCRIPTION:
XS GIS Cut Line= 3
      2765588.65      6813525.05      2765076.00      6813511.00
      2764615.27      6813644.02
#Sta/Elev= 30
  4491.8  538.02  4534.5  533.75  4554.5  530.65  4604.8  525.99  4714.5  514.26
  4874.6  500.06  4894.6  496.76  4914.6  494.74  4954.6  494.10  4964.6  494.72
  4972.6  487.54  4972.9  487.04  4976.6  487.54  4984.6  489.92  4994.6  494.68
  5002.1  496.00  5015.1  495.85  5067.1  498.75  5150.4  501.95  5205.3  506.97
  5285.7  516.41  5311.4  518.05  5316.9  519.19  5345.0  521.55  5350.2  520.95
  5378.7  524.24  5383.9  523.80  5389.8  525.09  5432.4  529.89  5484.2  533.05
#Mann=5,-1,0
  4491.8    0.05       0  4604.8    0.12       0  4972.6    0.07       0
  4976.6    0.12       0  5432.4    0.05       0
Bank Sta=4972.6,4976.6
Exp/Cntr=0.3,0.1

Type RM Length L Ch R = 1,15368,300,300,300
BEGIN DESCRIPTION:
1068
END DESCRIPTION:
XS GIS Cut Line= 3
      2765502.93      6813271.83      2765026.00      6813261.00
      2764647.64      6813523.58
#Sta/Elev= 30
  4522.5  524.52  4529.4  523.31  4552.9  520.86  4619.5  514.52  4639.5  513.35
  4709.5  507.47  4729.5  506.39  4749.5  504.15  4769.5  503.42  4799.5  500.63
  4859.5  496.38  4969.5  490.15  4977.5  484.87  4977.8  484.37  4981.3  484.37
  4981.5  484.87  4997.1  488.79  5042.8  491.19  5085.0  492.18  5135.3  494.23
  5215.7  499.77  5236.6  501.67  5251.5  504.49  5257.6  504.99  5272.4  507.54
  5323.1  512.74  5329.2  513.81  5409.5  520.75  5451.4  523.94  5460.1  524.19
#Mann=5,-1,0
  4522.5    0.05       0  4552.9    0.12       0  4977.5    0.07       0
  4981.5    0.12       0  5085.0    0.05       0
Bank Sta=4977.5,4981.5
Exp/Cntr=0.3,0.1

Type RM Length L Ch R = 1,15068,715,715,715
BEGIN DESCRIPTION:
1067
END DESCRIPTION:
XS GIS Cut Line= 3
      2765582.35      6813031.32      2765026.00      6812961.00
      2764670.50      6813060.74
#Sta/Elev= 30
  4435.1  522.04  4622.9  505.64  4637.5  505.33  4643.1  504.44  4694.0  501.01
  4834.6  492.52  4905.2  489.36  4985.8  483.43  4993.4  482.24  5002.8  482.09
  5006.3  481.96  5010.9  480.70  5011.2  480.20  5014.7  480.20  5014.9  480.70
  5018.1  484.54  5027.0  484.87  5130.9  486.21  5198.9  486.08  5233.0  487.07
  5265.9  489.19  5297.1  493.51  5306.4  496.28  5311.6  496.70  5317.8  501.29
  5338.6  508.78  5345.7  513.76  5350.9  514.31  5359.4  517.97  5365.1  521.33
#Mann=5,-1,0
  4435.1     0.1       0  4694.0    0.12       0  5002.8    0.05       0
  5010.9    0.07       0  5014.9    0.05       0
Bank Sta=5010.9,5014.9
Exp/Cntr=0.3,0.1

Type RM Length L Ch R = 1,14353,350,350,350
BEGIN DESCRIPTION:
1066
END DESCRIPTION:
XS GIS Cut Line= 3
      2765434.11      6812633.70      2764826.00      6812411.00
      2764395.61      6812409.04
#Sta/Elev= 30
  4352.0  501.09  4355.8  500.77  4406.6  497.88  4461.7  494.38  4541.7  486.84
  4572.7  485.52  4664.7  480.82  4773.6  477.87  4842.4  475.78  4869.6  476.56
  4903.8  476.05  4914.4  474.64  4923.3  476.09  4935.7  476.17  4946.4  474.94
  4953.8  475.38  4967.7  472.99  4976.3  466.88  4976.6  466.38  4980.3  466.88
  4984.3  475.42  4989.7  471.74  4996.9  474.06  5002.1  474.06  5009.6  476.21
  5019.6  477.36  5288.0  499.73  5359.6  504.23  5386.9  504.46  5430.0  504.29
#Mann=10,-1,0
  4352.0    0.05       0  4355.8    0.12       0  4406.6    0.05       0
  4572.7    0.12       0  4773.6    0.05       0  4869.6    0.12       0
  4976.3    0.07       0  4980.3    0.12       0  5288.0     0.1       0
  5386.9    0.12       0
Bank Sta=4976.3,4980.3
Exp/Cntr=0.3,0.1

Type RM Length L Ch R = 1,14003,378,378,378
BEGIN DESCRIPTION:
1065
END DESCRIPTION:
XS GIS Cut Line= 3
      2765488.27      6812375.27      2764976.00      6812111.00
      2764519.57      6812212.54
#Sta/Elev= 30
  4415.6  493.81  4481.3  491.95  4590.5  487.49  4784.3  477.34  4853.9  475.09
  4947.0  474.00  4961.6  472.58  4969.5  469.00  4978.1  472.77  4983.7  471.90
  4989.2  472.98  5002.3  473.67  5011.2  469.93  5016.3  473.13  5020.7  466.38
  5021.0  465.88  5024.5  465.88  5024.7  466.38  5033.0  467.28  5043.2  472.34
  5065.0  472.53  5074.0  471.60  5084.2  471.64  5114.9  473.56  5186.7  474.60
  5232.3  477.07  5278.9  479.82  5319.8  484.90  5384.9  489.74  5459.6  497.36
#Mann=6,-1,0
  4415.6     0.1       0  4481.3    0.05       0  4853.9    0.12       0
  5020.7    0.07       0  5024.7    0.12       0  5232.3    0.05       0
Bank Sta=5020.7,5024.7
Exp/Cntr=0.3,0.1

Type RM Length L Ch R = 1,13625,442,442,442
BEGIN DESCRIPTION:
1064
END DESCRIPTION:
XS GIS Cut Line= 3
      2765621.59      6811733.42      2764976.00      6811761.00
      2764471.71      6812155.43
#Sta/Elev= 30
  4358.5  497.63  4364.1  496.32  4379.1  496.07  4414.1  493.29  4419.1  494.20
  4434.2  493.32  4454.2  490.97  4554.3  485.33  4651.3  478.08  4814.5  470.84
  4854.5  470.84  4883.5  468.54  4894.6  466.60  4904.6  470.58  4954.6  471.16
  4964.6  469.38  4982.7  460.66  4982.9  460.16  4986.7  460.66  4994.7  468.36
  5002.2  470.15  5096.9  469.25  5105.0  468.30  5132.2  470.16  5225.3  471.10
  5295.8  473.70  5403.5  479.54  5410.9  480.90  5567.1  493.06  5644.9  495.08
#Mann=5,-1,0
  4358.5     0.1       0  4379.1    0.12       0  4982.7    0.07       0
  4986.7    0.12       0  5295.8    0.05       0
Bank Sta=4982.7,4986.7
Exp/Cntr=0.3,0.1

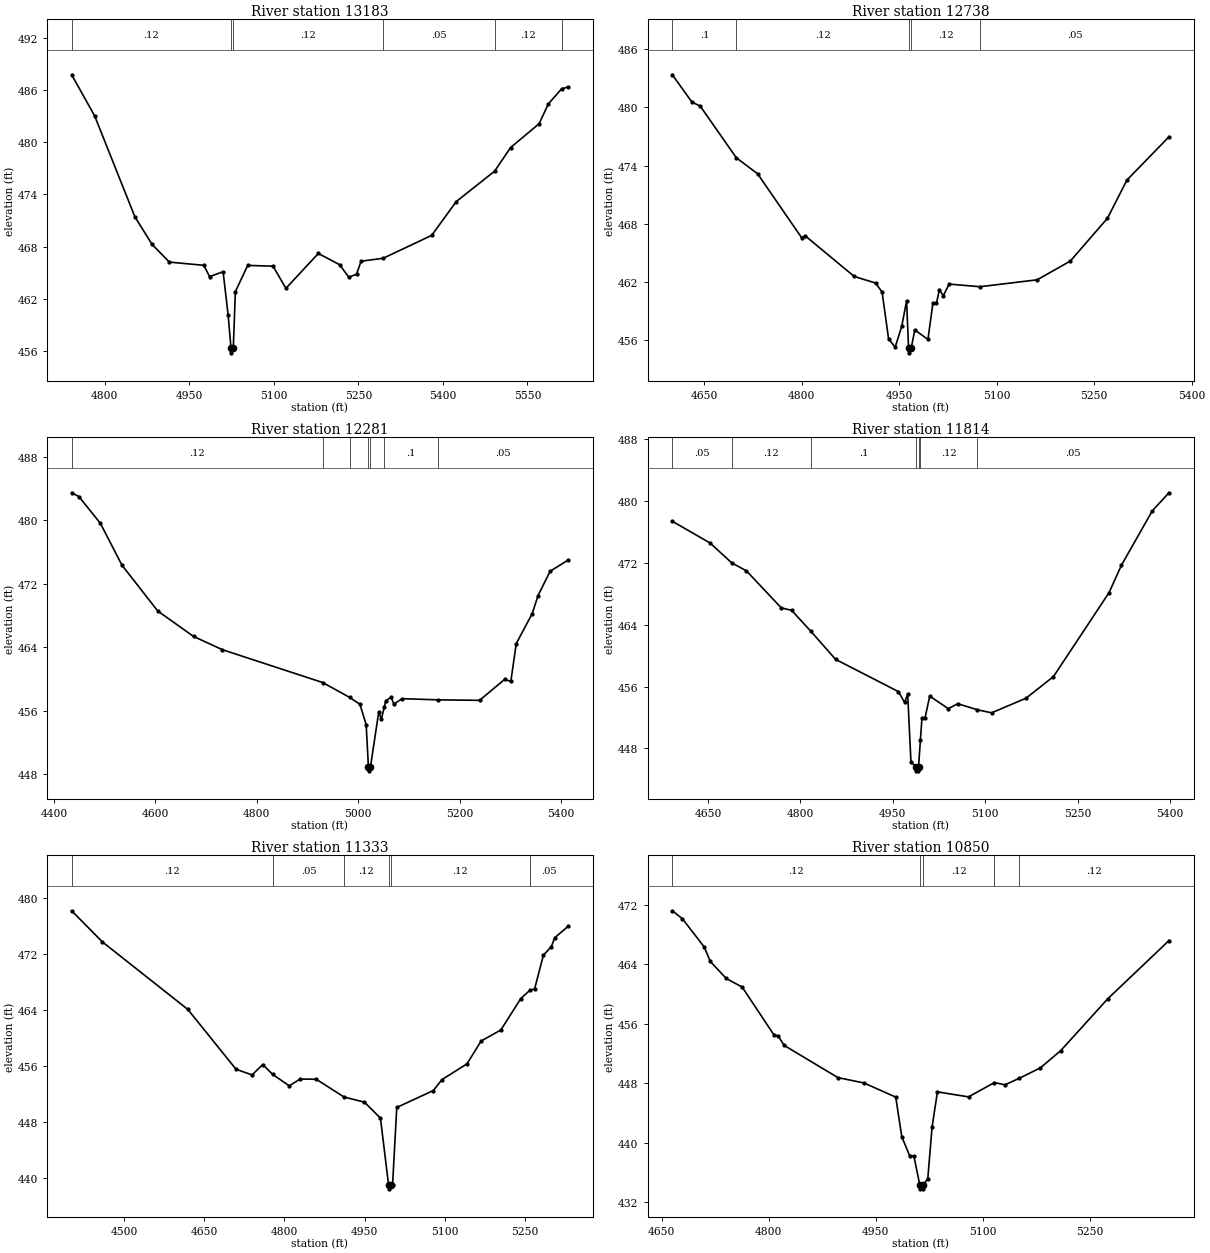
Type RM Length L Ch R = 1,13183,445,445,445
BEGIN DESCRIPTION:
1063
END DESCRIPTION:
XS GIS Cut Line= 3
      2765275.98      6811311.00      2765026.00      6811361.00
      2764476.02      6811660.99
#Sta/Elev= 30
  4741.1  487.76  4781.9  483.03  4853.3  471.43  4883.8  468.26  4914.4  466.23
  4975.6  465.86  4985.8  464.56  5009.8  465.12  5018.8  460.12  5023.9  456.30
  5024.2  455.80  5027.9  456.30  5031.6  462.83  5053.5  465.85  5098.5  465.76
  5121.3  463.21  5178.8  467.22  5216.7  465.93  5232.9  464.49  5246.6  464.83
  5254.7  466.33  5293.9  466.67  5380.0  469.30  5423.7  473.19  5491.7  476.68
  5520.0  479.39  5570.8  482.14  5586.9  484.40  5610.7  486.15  5622.5  486.36
#Mann=6,-1,0
  4741.1    0.12       0  5023.9    0.07       0  5027.9    0.12       0
  5293.9    0.05       0  5491.7    0.12       0  5610.7    0.05       0
Bank Sta=5023.9,5027.9
Exp/Cntr=0.3,0.1

Type RM Length L Ch R = 1,12738,457,457,457
BEGIN DESCRIPTION:
1062
END DESCRIPTION:
XS GIS Cut Line= 3
      2765225.97      6811061.00      2764826.00      6811011.00
      2764526.03      6811210.98
#Sta/Elev= 30
  4601.4  483.36  4631.6  480.54  4644.2  480.14  4699.8  474.81  4732.4  473.17
  4800.4  466.56  4805.4  466.79  4881.0  462.59  4913.8  461.91  4923.9  460.98
  4933.9  456.16  4944.0  455.30  4954.1  457.45  4961.6  460.08  4964.6  455.22
  4964.9  454.72  4968.7  455.22  4974.2  457.08  4994.4  456.10  5002.0  459.82
  5007.5  459.82  5012.0  461.23  5018.0  460.60  5027.0  461.80  5074.4  461.53
  5162.2  462.24  5213.3  464.17  5270.4  468.58  5300.4  472.52  5365.0  476.97
#Mann=5,-1,0
  4601.4     0.1       0  4699.8    0.12       0  4964.6    0.07       0
  4968.7    0.12       0  5074.4    0.05       0
Bank Sta=4964.6,4968.7
Exp/Cntr=0.3,0.1

Type RM Length L Ch R = 1,12281,467,467,467
BEGIN DESCRIPTION:
1061
END DESCRIPTION:
XS GIS Cut Line= 3
      2765225.98      6811010.98      2764826.00      6810611.00
      2764440.32      6810462.05
#Sta/Elev= 30
  4434.9  483.46  4449.0  482.99  4491.4  479.62  4533.9  474.35  4604.6  468.57
  4675.3  465.36  4731.9  463.70  4929.8  459.56  4983.1  457.68  5003.2  456.82
  5015.5  454.24  5019.9  448.94  5020.2  448.44  5024.0  448.94  5040.1  455.80
  5045.5  454.97  5051.3  456.51  5054.2  457.28  5064.7  457.69  5070.1  456.84
  5086.3  457.53  5156.4  457.38  5239.1  457.32  5288.3  459.95  5300.7  459.72
  5311.4  464.47  5342.9  468.25  5354.3  470.51  5378.2  473.58  5414.0  475.00
#Mann=7,-1,0
  4434.9    0.12       0  4929.8     0.1       0  4983.1    0.12       0
  5019.9    0.07       0  5024.0    0.12       0  5051.3     0.1       0
  5156.4    0.05       0
Bank Sta=5019.9,5024
Exp/Cntr=0.3,0.1

Type RM Length L Ch R = 1,11814,481,481,481
BEGIN DESCRIPTION:
1060
END DESCRIPTION:
XS GIS Cut Line= 3
      2765276.01      6810239.88      2764876.00      6810161.00
      2764479.22      6810125.19
#Sta/Elev= 30
  4592.3  477.40  4653.5  474.59  4688.5  472.03  4712.6  470.98  4769.1  466.19
  4786.0  465.87  4817.1  463.16  4857.3  459.52  4959.2  455.35  4969.3  453.95
  4974.3  455.04  4979.6  446.25  4987.7  445.59  4988.0  445.09  4991.6  445.09
  4991.9  445.59  4995.0  449.12  4997.5  451.97  5002.5  451.97  5010.1  454.76
  5040.2  453.14  5055.4  453.78  5087.3  453.00  5110.5  452.60  5166.3  454.49
  5210.9  457.29  5301.2  468.17  5321.3  471.72  5371.5  478.77  5398.4  481.09
#Mann=7,-1,0
  4592.3    0.05       0  4688.5    0.12       0  4817.1     0.1       0
  4987.7    0.07       0  4991.9     0.1       0  4995.0    0.12       0
  5087.3    0.05       0
Bank Sta=4987.7,4991.9
Exp/Cntr=0.3,0.1

Type RM Length L Ch R = 1,11333,483,483,483
BEGIN DESCRIPTION:
1059
END DESCRIPTION:
XS GIS Cut Line= 3
      2765373.16      6809727.05      2764776.00      6809711.00
      2764461.85      6809816.29
#Sta/Elev= 30
  4402.2  478.12  4459.4  473.69  4619.4  464.03  4709.5  455.49  4739.5  454.68
  4759.5  456.16  4778.1  454.75  4809.0  453.12  4829.5  454.09  4859.5  454.06
  4911.6  451.52  4949.6  450.79  4979.6  448.51  4994.9  438.91  4995.3  438.41
  4999.2  438.91  5002.2  438.91  5010.1  450.03  5078.5  452.45  5094.5  454.00
  5141.6  456.27  5167.8  459.52  5204.7  461.09  5242.1  465.59  5258.8  466.75
  5267.8  466.94  5284.3  471.78  5299.3  473.01  5305.4  474.27  5330.9  475.92
#Mann=6,-1,0
  4402.2    0.12       0  4778.1    0.05       0  4911.6    0.12       0
  4994.9    0.07       0  4999.2    0.12       0  5258.8    0.05       0
Bank Sta=4994.9,4999.2
Exp/Cntr=0.3,0.1

Type RM Length L Ch R = 1,10850,450,450,450
BEGIN DESCRIPTION:
1058
END DESCRIPTION:
XS GIS Cut Line= 3
      2764976.04      6809110.98      2764676.00      6809261.00
      2764376.00      6809461.00
#Sta/Elev= 30
  4664.9  471.17  4678.9  470.11  4709.7  466.30  4718.0  464.38  4740.4  462.08
  4762.8  460.92  4807.5  454.47  4813.1  454.39  4821.5  453.10  4896.9  448.77
  4933.3  448.05  4978.0  446.15  4986.4  440.85  4997.6  438.24  5003.4  438.24
  5011.7  434.33  5012.1  433.83  5015.7  433.83  5016.1  434.33  5022.9  435.19
  5028.9  442.12  5036.4  446.85  5080.0  446.18  5116.2  448.10  5131.1  447.80
  5151.2  448.68  5180.6  450.07  5209.2  452.39  5275.3  459.37  5360.9  467.17
#Mann=5,-1,0
  4664.9    0.12       0  5011.7    0.07       0  5016.1    0.12       0
  5116.2    0.05       0  5151.2    0.12       0
Bank Sta=5011.7,5016.1
Exp/Cntr=0.3,0.1