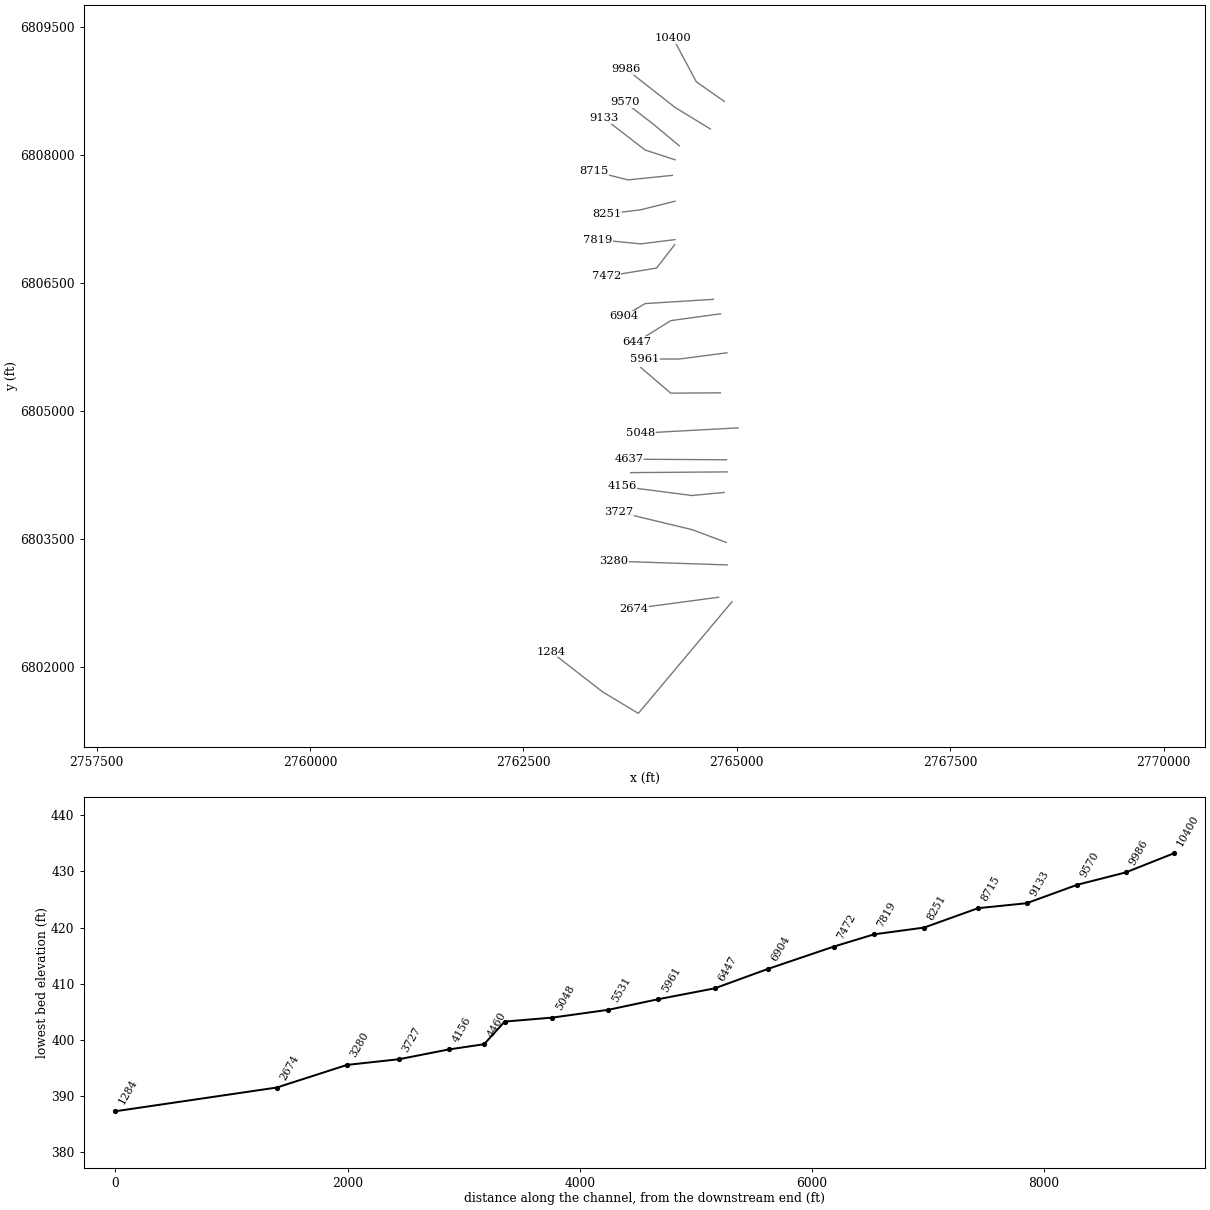
HEC-RAS study Helms Branch.prj: Helms Branch Base Level Engineering

--- Helms Branch.g01 (geometry) --- (continued)

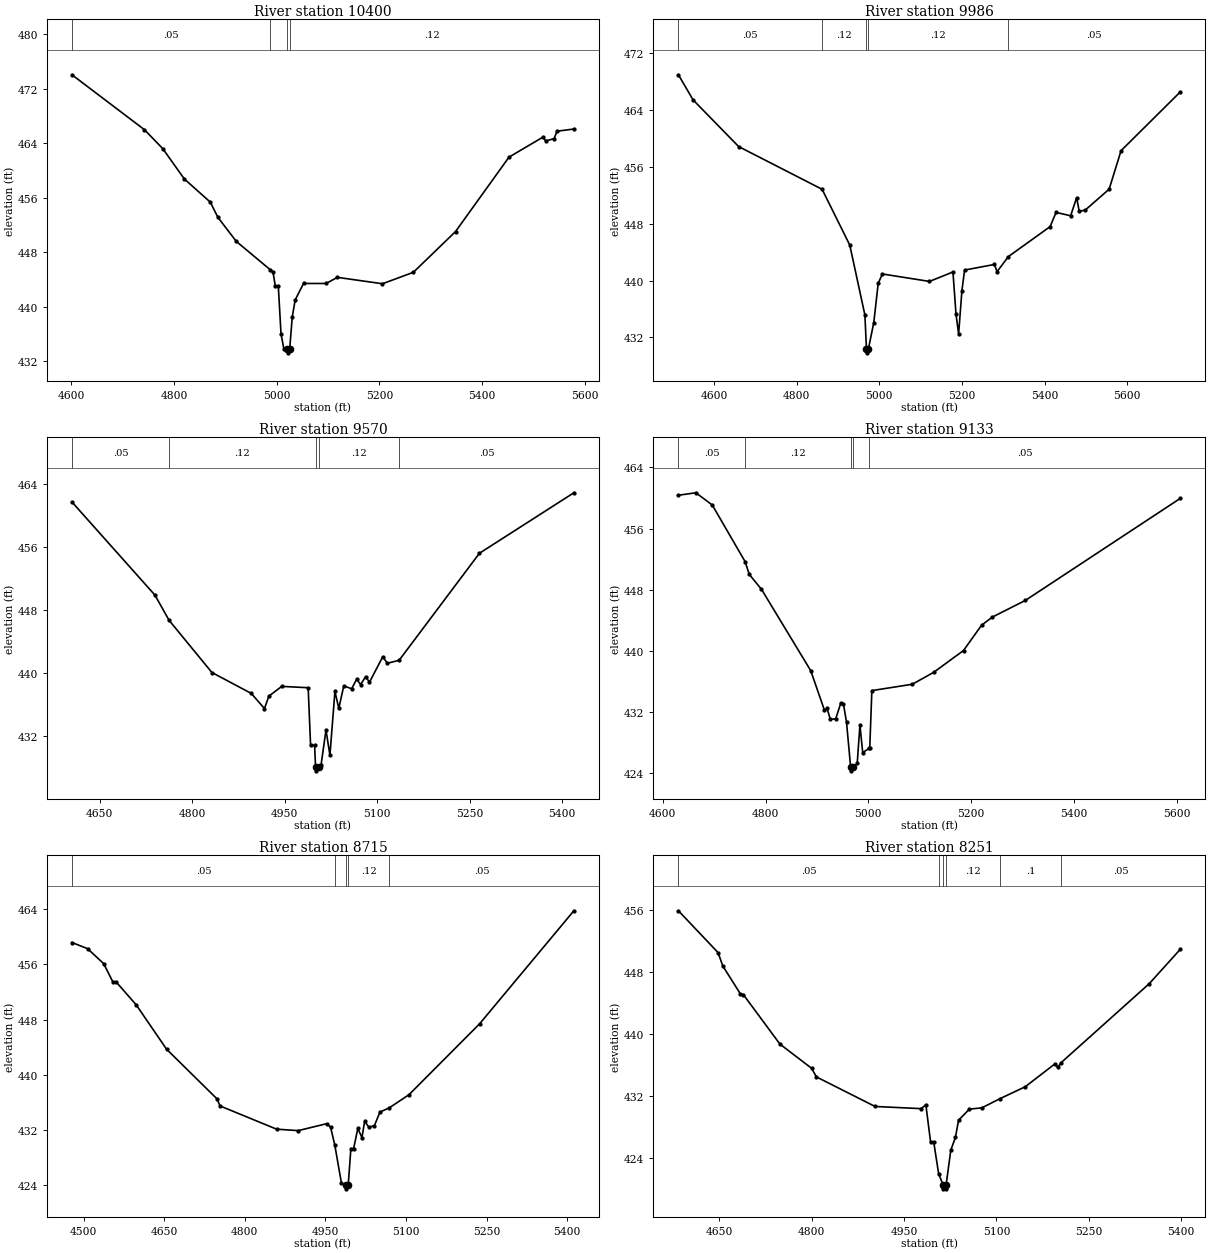
Type RM Length L Ch R = 1,10400,414,414,414
BEGIN DESCRIPTION:
1057
END DESCRIPTION:
XS GIS Cut Line= 3
      2764852.21      6808631.89      2764526.00      6808861.00
      2764253.23      6809370.55
#Sta/Elev= 30
  4601.6  474.06  4742.7  465.99  4778.5  463.19  4820.3  458.75  4870.8  455.35
  4885.6  453.11  4921.4  449.58  4987.1  445.44  4992.8  445.10  4997.2  443.05
  5003.1  443.05  5008.4  436.00  5014.0  433.79  5020.7  433.71  5021.1  433.21
  5025.2  433.71  5030.3  438.50  5036.0  440.99  5052.2  443.40  5096.1  443.40
  5118.1  444.30  5205.8  443.36  5265.9  445.04  5348.0  451.03  5452.0  461.96
  5517.8  464.89  5523.5  464.34  5539.8  464.68  5545.4  465.77  5578.2  466.09
#Mann=4,-1,0
  4601.6    0.05       0  4987.1    0.12       0  5020.7    0.07       0
  5025.2    0.12       0
Bank Sta=5020.7,5025.2
Exp/Cntr=0.3,0.1

Type RM Length L Ch R = 1,9986,416,416,416
BEGIN DESCRIPTION:
1056
END DESCRIPTION:
XS GIS Cut Line= 3
      2764691.12      6808307.50      2764276.00      6808561.00
      2763703.24      6809010.68
#Sta/Elev= 30
  4513.8  468.99  4549.2  465.46  4659.5  458.88  4861.5  452.86  4928.5  445.00
  4965.1  435.14  4968.9  430.32  4969.4  429.82  4973.4  430.32  4986.6  434.09
  4997.3  439.61  5007.4  440.93  5121.3  439.88  5178.2  441.21  5185.5  435.31
  5191.9  432.48  5199.9  438.59  5206.3  441.48  5278.6  442.27  5284.9  441.25
  5312.3  443.38  5413.3  447.60  5427.7  449.60  5463.0  449.13  5477.4  451.67
  5483.8  449.76  5498.3  449.93  5556.1  452.87  5585.0  458.30  5728.4  466.58
#Mann=5,-1,0
  4513.8    0.05       0  4861.5    0.12       0  4968.9    0.07       0
  4973.4    0.12       0  5312.3    0.05       0
Bank Sta=4968.9,4973.4
Exp/Cntr=0.3,0.1

Type RM Length L Ch R = 1,9570,437,437,437
BEGIN DESCRIPTION:
1055
END DESCRIPTION:
XS GIS Cut Line= 3
      2764325.98      6808111.01      2764026.00      6808361.00
      2763690.88      6808620.60
#Sta/Elev= 30
  4604.9  461.72  4739.6  449.91  4762.5  446.72  4832.0  440.10  4895.8  437.45
  4917.3  435.53  4924.4  437.10  4945.3  438.34  4988.2  438.17  4992.1  430.87
  4998.6  430.87  5000.2  428.13  5000.8  427.63  5005.1  428.13  5009.0  428.31
  5017.1  432.80  5023.5  429.61  5031.6  437.70  5037.9  435.56  5046.0  438.40
  5058.8  438.04  5066.9  439.26  5073.2  438.57  5081.4  439.57  5087.7  438.87
  5109.2  442.10  5116.7  441.27  5135.8  441.65  5266.1  455.22  5419.3  462.89
#Mann=5,-1,0
  4604.9    0.05       0  4762.5    0.12       0  5000.2    0.07       0
  5005.1    0.12       0  5135.8    0.05       0
Bank Sta=5000.2,5005.1
Exp/Cntr=0.3,0.1

Type RM Length L Ch R = 1,9133,418,418,418
BEGIN DESCRIPTION:
1054
END DESCRIPTION:
XS GIS Cut Line= 3
      2764277.09      6807946.69      2763926.00      6808061.00
      2763445.37      6808432.83
#Sta/Elev= 30
  4630.3  460.37  4664.3  460.69  4696.2  459.09  4760.1  451.69  4768.2  450.02
  4792.0  448.07  4887.8  437.44  4914.5  432.27  4919.7  432.49  4925.9  431.08
  4936.4  431.13  4946.4  433.21  4951.6  433.06  4957.5  430.69  4965.5  424.84
  4966.1  424.34  4970.4  424.84  4978.3  425.30  4983.6  430.32  4989.0  426.73
  5002.2  427.30  5002.7  427.30  5006.8  434.83  5085.6  435.66  5127.2  437.22
  5185.2  440.07  5220.5  443.39  5241.3  444.44  5305.6  446.62  5607.2  459.96
#Mann=5,-1,0
  4630.3    0.05       0  4760.1    0.12       0  4965.5    0.07       0
  4970.4    0.12       0  5002.2    0.05       0
Bank Sta=4965.5,4970.4
Exp/Cntr=0.3,0.1

Type RM Length L Ch R = 1,8715,464,464,464
BEGIN DESCRIPTION:
1053
END DESCRIPTION:
XS GIS Cut Line= 3
      2764244.84      6807764.03      2763726.00      6807711.00
      2763325.96      6807811.01
#Sta/Elev= 30
  4478.4  459.17  4507.4  458.28  4537.5  456.10  4555.0  453.38  4560.0  453.51
  4597.9  450.14  4654.5  443.70  4748.6  436.48  4753.9  435.48  4859.2  432.11
  4899.4  431.90  4952.7  432.91  4959.7  432.38  4967.5  429.80  4979.8  424.31
  4987.4  423.96  4988.0  423.46  4992.4  423.96  4997.4  429.29  5002.5  429.29
  5010.3  432.21  5018.0  430.89  5023.1  433.27  5030.9  432.39  5041.2  432.62
  5051.5  434.59  5069.0  435.21  5105.6  437.11  5237.0  447.39  5412.3  463.77
#Mann=5,-1,0
  4478.4    0.05       0  4967.5    0.12       0  4987.4    0.07       0
  4992.4    0.12       0  5069.0    0.05       0
Bank Sta=4987.4,4992.4
Exp/Cntr=0.3,0.1

Type RM Length L Ch R = 1,8251,432,432,432
BEGIN DESCRIPTION:
1052
END DESCRIPTION:
XS GIS Cut Line= 3
      2764275.98      6807461.00      2763876.00      6807361.00
      2763476.00      6807311.00
#Sta/Elev= 30
  4583.3  455.93  4647.7  450.53  4655.4  448.80  4683.8  445.22  4688.9  445.09
  4748.2  438.71  4799.7  435.58  4807.5  434.47  4902.8  430.65  4977.6  430.37
  4985.3  430.87  4993.0  426.05  4998.1  426.05  5006.0  421.99  5013.2  420.51
  5013.8  420.01  5017.6  420.01  5018.2  420.51  5025.8  425.01  5033.4  426.67
  5038.4  428.87  5056.1  430.31  5076.2  430.47  5105.5  431.65  5146.8  433.20
  5194.6  436.13  5199.7  435.71  5204.9  436.30  5348.3  446.52  5398.7  450.96
#Mann=6,-1,0
  4583.3    0.05       0  5006.0    0.12       0  5013.2    0.04       0
  5018.2    0.12       0  5105.5     0.1       0  5204.9    0.05       0
Bank Sta=5013.2,5018.2
Exp/Cntr=0.3,0.1

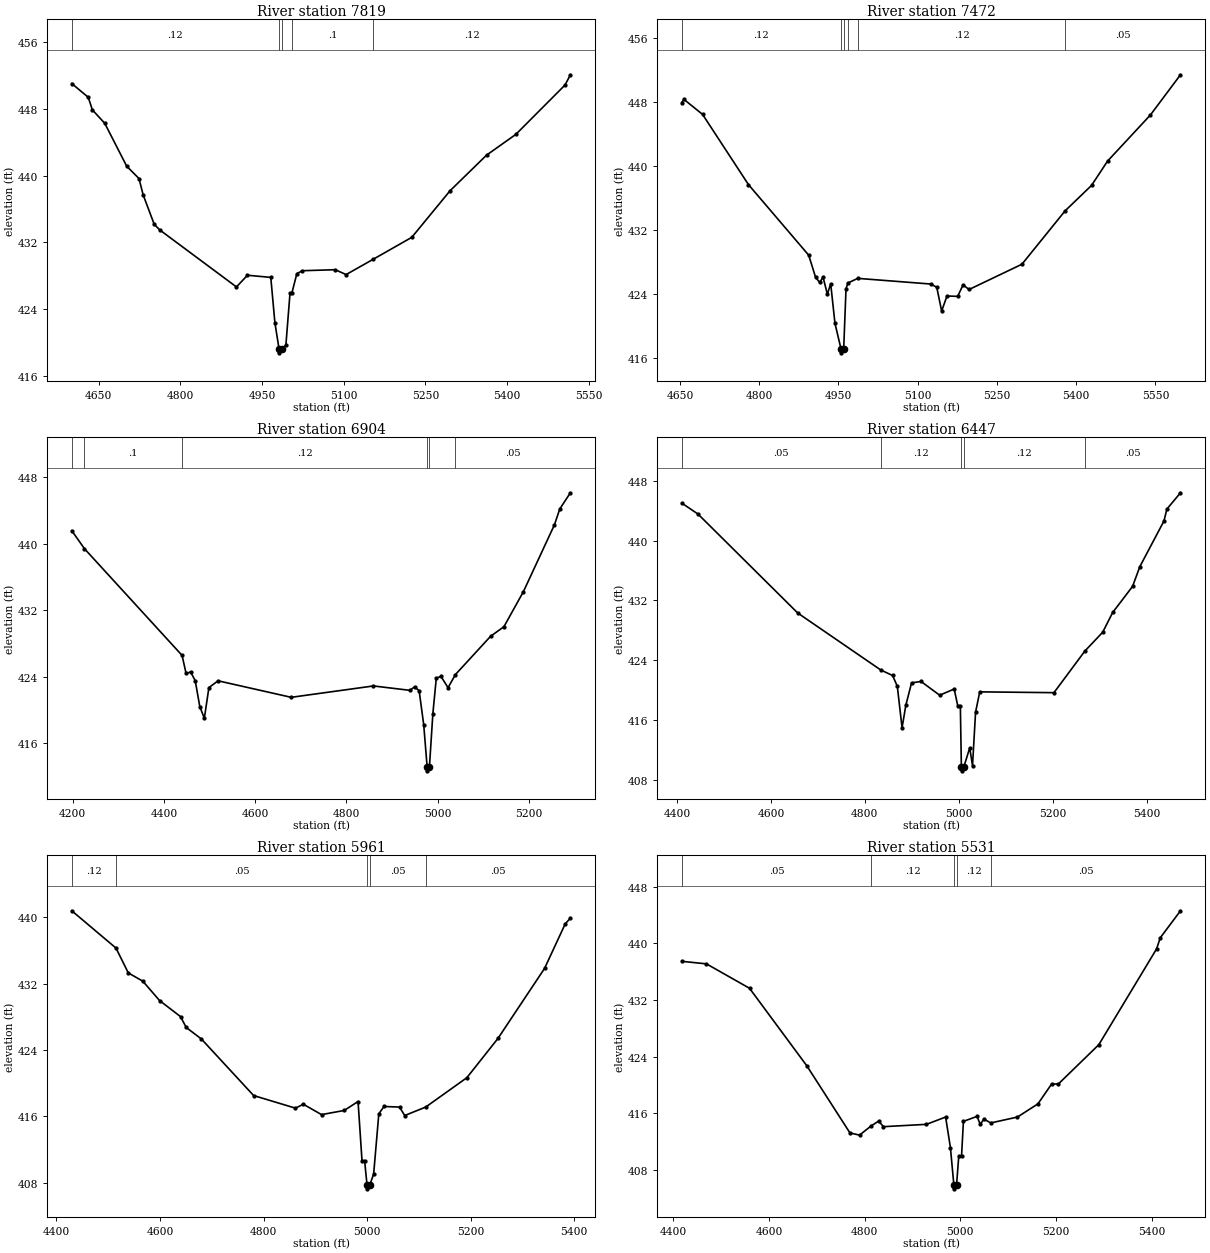
Type RM Length L Ch R = 1,7819,347,347,347
BEGIN DESCRIPTION:
1051
END DESCRIPTION:
XS GIS Cut Line= 3
      2764275.99      6807011.00      2763876.00      6806961.00
      2763366.23      6807010.80
#Sta/Elev= 30
  4600.9  451.00  4631.1  449.36  4638.7  447.85  4661.4  446.25  4701.7  441.12
  4724.3  439.64  4731.9  437.69  4752.1  434.19  4762.1  433.51  4903.2  426.68
  4923.4  428.08  4966.2  427.82  4973.8  422.37  4981.3  419.30  4981.9  418.80
  4986.4  419.30  4993.9  419.70  5001.5  425.94  5004.9  425.94  5014.0  428.26
  5024.1  428.62  5084.4  428.74  5104.5  428.16  5153.7  429.97  5225.0  432.61
  5295.4  438.19  5362.3  442.44  5416.0  444.92  5506.4  450.83  5516.2  452.05
#Mann=5,-1,0
  4600.9    0.12       0  4981.3    0.07       0  4986.4    0.12       0
  5004.9     0.1       0  5153.7    0.12       0
Bank Sta=4981.3,4986.4
Exp/Cntr=0.3,0.1

Type RM Length L Ch R = 1,7472,568,568,568
BEGIN DESCRIPTION:
1050
END DESCRIPTION:
XS GIS Cut Line= 3
      2764272.13      6806950.72      2764059.47      6806677.41
      2763469.87      6806580.55
#Sta/Elev= 30
  4653.7  447.95  4657.6  448.34  4692.9  446.46  4779.8  437.67  4893.8  428.84
  4906.8  426.07  4914.6  425.43  4920.9  426.10  4929.1  423.96  4935.4  425.26
  4943.5  420.30  4954.9  417.12  4955.5  416.62  4960.0  417.12  4964.4  424.62
  4967.9  425.36  4986.7  425.94  5125.1  425.23  5136.2  424.82  5145.4  421.85
  5155.5  423.73  5175.8  423.69  5185.9  425.12  5197.4  424.55  5297.4  427.71
  5379.1  434.39  5429.1  437.57  5459.5  440.62  5540.6  446.39  5597.5  451.42
#Mann=6,-1,0
  4653.7    0.12       0  4954.9    0.07       0  4960.0    0.12       0
  4967.9     0.1       0  4986.7    0.12       0  5379.1    0.05       0
Bank Sta=4954.9,4960
Exp/Cntr=0.3,0.1

Type RM Length L Ch R = 1,6904,457,457,457
BEGIN DESCRIPTION:
1049
END DESCRIPTION:
XS GIS Cut Line= 3
      2764726.03      6806311.00      2763926.00      6806261.00
      2763676.03      6806111.02
#Sta/Elev= 30
  4197.9  441.58  4225.7  439.41  4439.7  426.55  4448.4  424.39  4458.4  424.55
  4468.5  423.51  4478.5  420.39  4488.5  418.97  4498.5  422.67  4518.6  423.49
  4678.9  421.50  4859.2  422.87  4939.4  422.34  4949.4  422.77  4959.4  422.29
  4969.4  418.21  4976.9  413.14  4977.6  412.64  4982.0  413.14  4989.5  419.54
  4997.0  423.81  5007.3  424.02  5022.8  422.66  5038.9  424.24  5116.1  428.86
  5145.3  430.01  5188.0  434.24  5256.1  442.30  5267.7  444.20  5291.0  446.15
#Mann=6,-1,0
  4197.9    0.05       0  4225.7     0.1       0  4439.7    0.12       0
  4976.9    0.07       0  4982.0    0.12       0  5038.9    0.05       0
Bank Sta=4976.9,4982
Exp/Cntr=0.3,0.1

Type RM Length L Ch R = 1,6447,486,486,486
BEGIN DESCRIPTION:
1048
END DESCRIPTION:
XS GIS Cut Line= 3
      2764810.44      6806141.33      2764226.00      6806061.00
      2763826.03      6805811.02
#Sta/Elev= 30
  4410.5  445.01  4444.9  443.55  4657.2  430.31  4834.1  422.68  4859.1  421.95
  4869.2  420.51  4879.3  414.95  4887.3  417.95  4899.5  420.96  4919.7  421.15
  4959.4  419.31  4990.3  420.14  4997.9  417.89  5003.4  417.89  5005.6  409.69
  5006.2  409.19  5010.7  409.69  5023.4  412.27  5029.3  409.87  5035.8  417.03
  5044.7  419.76  5202.7  419.65  5268.4  425.21  5306.5  427.74  5327.7  430.38
  5370.1  433.87  5385.5  436.51  5436.8  442.61  5443.2  444.22  5472.1  446.40
#Mann=5,-1,0
  4410.5    0.05       0  4834.1    0.12       0  5005.6    0.07       0
  5010.7    0.12       0  5268.4    0.05       0
Bank Sta=5005.6,5010.7
Exp/Cntr=0.3,0.1

Type RM Length L Ch R = 1,5961,430,430,430
BEGIN DESCRIPTION:
1047
END DESCRIPTION:
XS GIS Cut Line= 3
      2764884.19      6805684.21      2764326.00      6805611.00
      2763925.97      6805611.00
#Sta/Elev= 30
  4429.7  440.79  4515.1  436.29  4538.8  433.30  4566.9  432.30  4599.3  429.96
  4639.7  428.03  4650.7  426.72  4680.0  425.33  4780.9  418.51  4861.6  416.99
  4877.0  417.46  4912.0  416.21  4955.8  416.71  4982.6  417.79  4990.2  410.67
  4995.2  410.67  4999.9  407.76  5000.7  407.26  5005.4  407.76  5012.7  409.04
  5022.7  416.31  5032.7  417.19  5062.7  417.12  5072.7  416.10  5113.2  417.12
  5192.7  420.66  5252.7  425.39  5342.7  433.83  5382.7  439.21  5392.7  439.91
#Mann=5,-1,0
  4429.7    0.12       0  4515.1    0.05       0  4999.9    0.05       0
  5005.4    0.05       0  5113.2    0.05       0
Bank Sta=4999.9,5005.4
Exp/Cntr=0.3,0.1

Type RM Length L Ch R = 1,5531,483,483,483
BEGIN DESCRIPTION:
1046
END DESCRIPTION:
XS GIS Cut Line= 3
      2764807.40      6805214.73      2764226.00      6805211.00
      2763876.00      6805511.00
#Sta/Elev= 30
  4418.0  437.47  4469.4  437.11  4559.4  433.67  4679.4  422.71  4769.4  413.26
  4789.4  412.95  4814.0  414.26  4829.4  414.93  4839.4  414.14  4929.4  414.47
  4969.4  415.50  4979.4  411.20  4986.7  405.87  4987.5  405.37  4992.2  405.87
  4996.9  410.01  5002.7  410.01  5006.6  414.89  5035.1  415.59  5041.7  414.47
  5049.4  415.20  5063.9  414.67  5119.6  415.50  5162.4  417.36  5190.9  420.15
  5205.2  420.17  5289.7  425.71  5410.5  439.23  5418.1  440.79  5460.4  444.60
#Mann=5,-1,0
  4418.0    0.05       0  4814.0    0.12       0  4986.7    0.07       0
  4992.2    0.12       0  5063.9    0.05       0
Bank Sta=4986.7,4992.2
Exp/Cntr=0.3,0.1

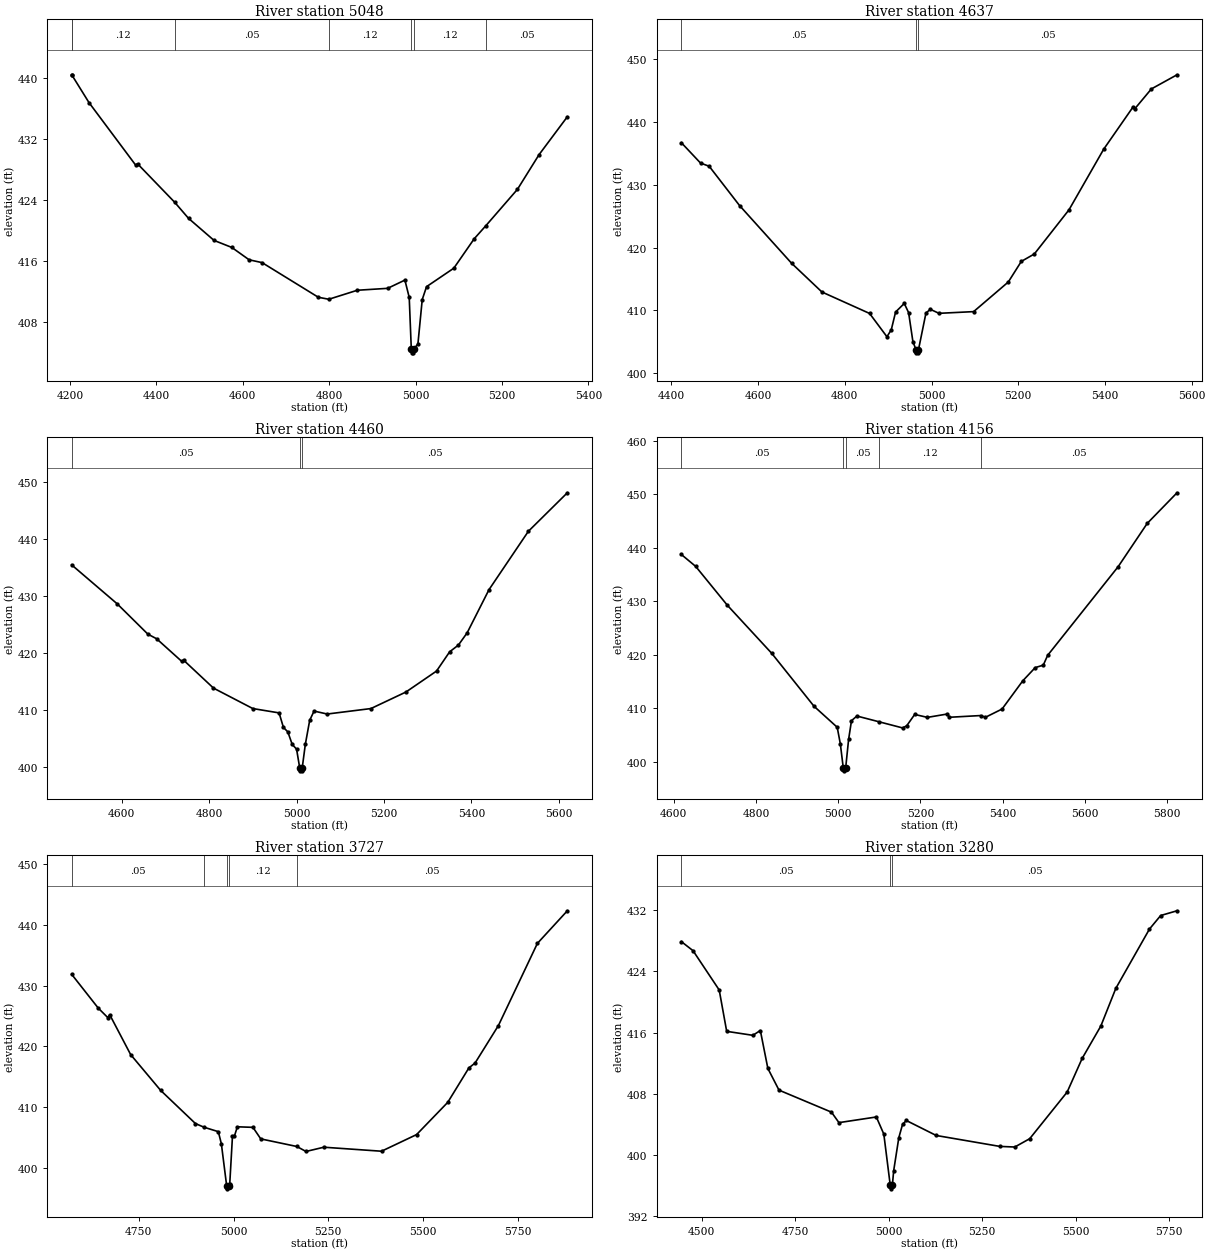
Type RM Length L Ch R = 1,5048,411,411,411
BEGIN DESCRIPTION:
1045
END DESCRIPTION:
XS GIS Cut Line= 3
      2765016.08      6804804.21      2764226.00      6804761.00
      2763870.70      6804741.49
#Sta/Elev= 30
  4204.0  440.41  4204.2  440.41  4244.1  436.77  4351.8  428.60  4356.8  428.73
  4442.4  423.71  4474.5  421.60  4533.5  418.71  4574.6  417.79  4614.7  416.17
  4644.7  415.80  4774.9  411.26  4799.1  411.00  4865.1  412.18  4935.2  412.43
  4975.2  413.51  4985.2  411.24  4990.0  404.48  4990.8  403.98  4994.7  403.98
  4995.6  404.48  5005.3  405.13  5015.3  410.96  5025.3  412.65  5088.4  415.07
  5135.5  418.92  5162.6  420.64  5235.6  425.40  5285.7  429.95  5351.1  434.91
#Mann=7,-1,0
  4204.0    0.05       0  4204.2    0.12       0  4442.4    0.05       0
  4799.1    0.12       0  4990.0    0.07       0  4995.6    0.12       0
  5162.6    0.05       0
Bank Sta=4990,4995.6
Exp/Cntr=0.3,0.1

Type RM Length L Ch R = 1,4637,177,177,177
BEGIN DESCRIPTION:
2504
END DESCRIPTION:
XS GIS Cut Line= 2
      2764880.27      6804430.00      2763736.79      6804436.57
#Sta/Elev= 30
  4422.8  436.67  4467.1  433.43  4487.1  432.92  4557.1  426.68  4677.1  417.51
  4747.1  412.94  4857.1  409.53  4897.1  405.83  4907.1  406.93  4917.1  409.76
  4937.1  411.12  4947.1  409.66  4957.1  405.01  4964.3  403.77  4965.1  403.27
  4969.0  403.27  4969.9  403.77  4987.1  409.59  4997.1  410.19  5017.1  409.55
  5097.1  409.82  5177.1  414.53  5207.1  417.80  5237.1  418.98  5317.1  426.00
  5397.1  435.63  5464.3  442.29  5469.3  442.09  5507.1  445.21  5566.3  447.46
#Mann=3,-1,0
  4422.8    0.05       0  4964.3    0.05       0  4969.9    0.05       0
Bank Sta=4964.3,4969.9
Exp/Cntr=0.3,0.1

Type RM Length L Ch R = 1,4460,304,304,304
BEGIN DESCRIPTION:
2505
END DESCRIPTION:
XS GIS Cut Line= 2
      2764890.29      6804287.92      2763756.92      6804279.35
#Sta/Elev= 30
  4485.8  435.39  4590.1  428.54  4660.1  423.23  4680.1  422.42  4737.4  418.46
  4742.4  418.62  4810.1  413.76  4900.1  410.17  4960.1  409.41  4970.1  406.85
  4980.1  406.08  4990.1  403.88  5000.1  403.05  5007.3  399.74  5008.2  399.24
  5012.1  399.24  5013.0  399.74  5020.1  403.88  5030.1  408.11  5040.1  409.73
  5070.1  409.21  5170.1  410.17  5250.1  413.07  5320.1  416.75  5350.1  420.13
  5370.1  421.31  5390.1  423.46  5440.1  431.04  5530.1  441.28  5619.2  448.04
#Mann=3,-1,0
  4485.8    0.05       0  5007.3    0.04       0  5013.0    0.05       0
Bank Sta=5007.3,5013
Exp/Cntr=0.3,0.1

Type RM Length L Ch R = 1,4156,429,429,429
BEGIN DESCRIPTION:
1044
END DESCRIPTION:
XS GIS Cut Line= 3
      2764850.76      6804046.80      2764476.00      6804011.00
      2763654.08      6804117.04
#Sta/Elev= 30
  4618.6  438.78  4653.5  436.55  4730.5  429.28  4838.4  420.29  4941.2  410.39
  4997.6  406.46  5005.2  403.36  5012.4  398.81  5013.3  398.31  5018.1  398.81
  5025.3  404.18  5032.3  407.69  5045.5  408.56  5100.1  407.47  5156.4  406.34
  5166.5  406.73  5186.0  408.86  5216.9  408.31  5265.4  408.94  5270.5  408.33
  5346.1  408.65  5358.1  408.33  5398.4  409.87  5448.8  415.15  5479.0  417.62
  5498.6  418.08  5509.3  419.92  5680.7  436.50  5751.3  444.59  5823.8  450.32
#Mann=5,-1,0
  4618.6    0.05       0  5012.4    0.04       0  5018.1    0.05       0
  5100.1    0.12       0  5346.1    0.05       0
Bank Sta=5012.4,5018.1
Exp/Cntr=0.3,0.1

Type RM Length L Ch R = 1,3727,447,447,447
BEGIN DESCRIPTION:
1043
END DESCRIPTION:
XS GIS Cut Line= 3
      2764876.02      6803460.99      2764476.00      6803611.00
      2763619.13      6803816.95
#Sta/Elev= 30
  4572.7  431.88  4643.0  426.31  4668.0  424.76  4673.3  425.22  4728.5  418.66
  4807.7  412.77  4899.4  407.32  4922.0  406.71  4959.9  405.98  4967.9  403.99
  4981.9  397.07  4982.8  396.57  4987.7  397.07  4990.1  397.43  4997.3  405.28
  5002.5  405.28  5010.2  406.78  5051.3  406.69  5071.9  404.79  5167.1  403.54
  5191.3  402.72  5238.4  403.42  5390.7  402.76  5483.3  405.50  5565.6  410.81
  5621.3  416.47  5637.6  417.27  5699.3  423.45  5802.1  436.96  5881.2  442.33
#Mann=5,-1,0
  4572.7    0.05       0  4922.0    0.12       0  4981.9    0.07       0
  4987.7    0.12       0  5167.1    0.05       0
Bank Sta=4981.9,4987.7
Exp/Cntr=0.3,0.1

Type RM Length L Ch R = 1,3280,606,606,606
BEGIN DESCRIPTION:
2273
END DESCRIPTION:
XS GIS Cut Line= 2
      2764887.23      6803197.23      2763562.36      6803240.94
#Sta/Elev= 30
  4445.7  427.90  4477.0  426.71  4547.0  421.57  4567.0  416.16  4637.0  415.64
  4657.0  416.27  4677.1  411.31  4706.9  408.47  4847.2  405.59  4867.2  404.22
  4967.2  404.96  4987.2  402.72  5004.3  396.06  5005.3  395.56  5010.1  396.06
  5013.6  397.94  5027.3  402.25  5037.3  403.99  5047.3  404.50  5127.3  402.54
  5297.4  401.11  5337.4  401.03  5377.4  402.12  5477.5  408.22  5517.5  412.61
  5567.5  416.85  5607.6  421.78  5697.6  429.54  5727.6  431.31  5771.3  431.93
#Mann=3,-1,0
  4445.7    0.05       0  5004.3    0.04       0  5010.1    0.05       0
Bank Sta=5004.3,5010.1
Exp/Cntr=0.3,0.1

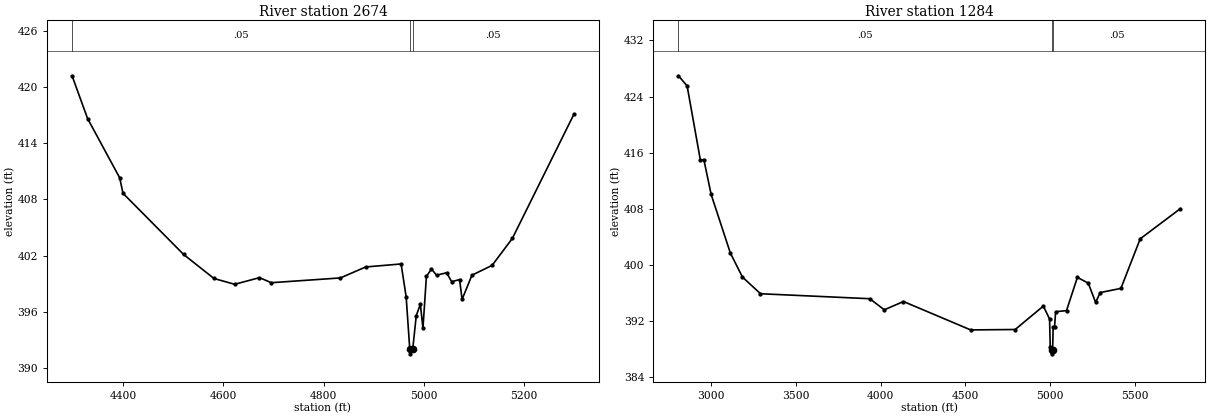
Type RM Length L Ch R = 1,2674,1390,1390,1390
BEGIN DESCRIPTION:
2394
END DESCRIPTION:
XS GIS Cut Line= 2
      2764786.66      6802818.37      2763794.26      6802685.89
#Sta/Elev= 30
  4298.2  421.20  4329.1  416.64  4393.2  410.31  4399.8  408.66  4520.8  402.13
  4581.3  399.57  4622.6  398.95  4672.1  399.66  4695.7  399.12  4833.6  399.63
  4884.0  400.80  4954.6  401.12  4964.7  397.63  4971.9  392.03  4972.8  391.53
  4977.8  392.03  4984.9  395.62  4993.1  396.82  4998.2  394.24  5005.1  399.79
  5015.2  400.59  5025.3  399.92  5045.4  400.18  5055.5  399.23  5071.3  399.45
  5076.3  397.34  5095.9  399.92  5136.2  400.97  5176.6  403.85  5299.4  417.10
#Mann=3,-1,0
  4298.2    0.05       0  4971.9    0.04       0  4977.8    0.05       0
Bank Sta=4971.9,4977.8
Exp/Cntr=0.3,0.1

Type RM Length L Ch R = 1,1284,0,0,0
BEGIN DESCRIPTION:
1042
END DESCRIPTION:
XS GIS Cut Line= 4
      2764943.63      6802765.39      2763846.06      6801456.89
      2763426.83      6801709.82      2762822.22      6802179.99
#Sta/Elev= 30
  2806.7  426.96  2857.8  425.51  2935.8  414.96  2956.7  414.99  2999.6  410.04
  3112.8  401.70  3184.3  398.26  3291.0  395.88  3936.3  395.17  4022.1  393.59
  4135.3  394.77  4532.2  390.72  4794.9  390.78  4961.2  394.12  4998.1  392.27
  5001.8  388.32  5010.0  387.81  5010.9  387.31  5015.9  387.81  5019.3  391.09
  5027.4  391.11  5033.7  393.32  5098.0  393.47  5162.2  398.21  5226.5  397.39
  5269.9  394.64  5297.1  396.05  5419.2  396.64  5533.2  403.71  5770.1  408.01
#Mann=3,-1,0
  2806.7    0.05       0  5010.0    0.04       0  5015.9    0.05       0
Bank Sta=5010,5015.9
Exp/Cntr=0.3,0.1

Chan Stop Cuts=-1