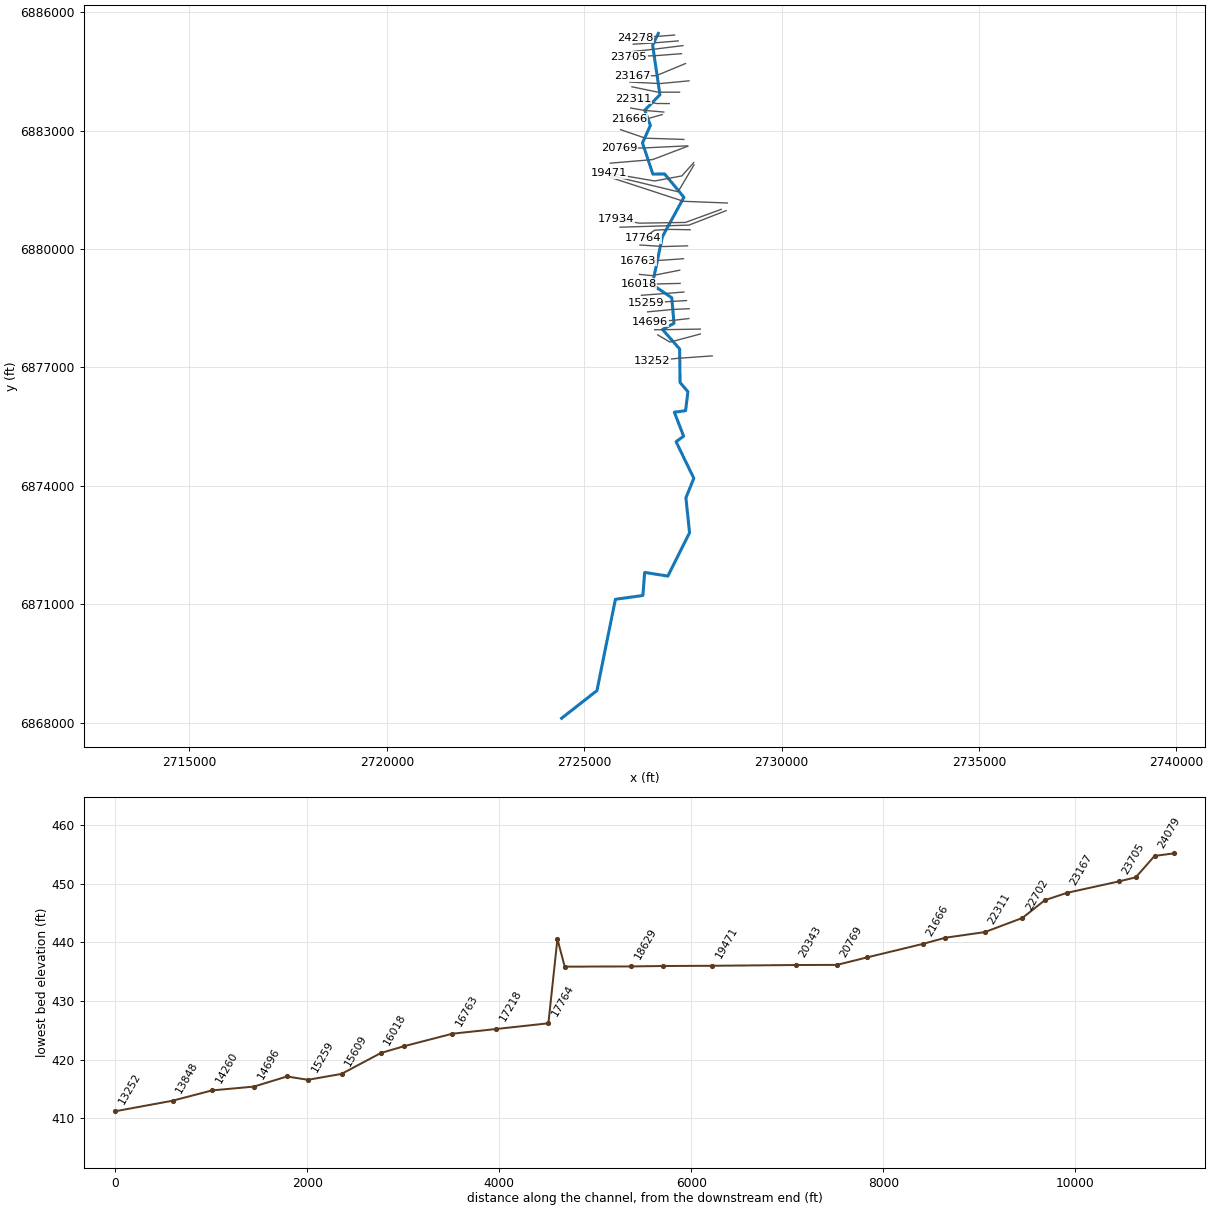
--- Knudson Branch.prj (project) ---

Proj Title=Knudson Branch Base Level Engineering
Current Plan=p01
Default Exp/Contr=0.3,0.1
English Units
Geom File=g01
Flow File=f01
Plan File=p01
Y Axis Title=Elevation
X Axis Title(PF)=Main Channel Distance
X Axis Title(XS)=Station
BEGIN DESCRIPTION:
Knudson Branch
END DESCRIPTION:
DSS Export Rating Curves= 0
DSS Export Rating Curve Sorted= 0
DSS Export Volume Flow Curves= 0
DXF OffsetX= 0
DXF OffsetY= 0
DXF ScaleX= 1
DXF ScaleY= 10

--- Knudson Branch.p01 (plan) ---

Plan Title=Multiple Run
Short Identifier=Multiple
Geom File=g01
Flow File=f01
Subcritical Flow
K Sum by GR= 0
Std Step Tol= 0.01
Critical Tol= 0.01
Num of Std Step Trials= 20
Max Error Tol= 0.3
Flow Tol Ratio= 0.001
Split Flow NTrial= 30
Split Flow Tol= 0.02
Split Flow Ratio= 0.02
Log Output Level= 0
Friction Slope Method= 1
Unsteady Friction Slope Method= 2
Unsteady Bridges Friction Slope Method= 1
Parabolic Critical Depth
Global Vel Dist=  1 , 1 , 1
Global Log Level= 0
CheckData=True
Encroach Param= -1, 0, 0, 0
BEGIN DESCRIPTION:
Multiple Run
END DESCRIPTION:

--- Knudson Branch.f01 (steady flow) ---

Flow Title=Multiple
Number of Profiles=7
Profile Names=10-year,25-year,50-year,1pct_min,100-year,1pct_plu,500-year
River Rch & RM= Knudson Branch,Reach-1,24278
     355     458     537     313     625    1246     844
River Rch & RM= Knudson Branch,Reach-1,21087
     495     649     771     454     907    1809    1252
River Rch & RM= Knudson Branch,Reach-1,18629
     577     763     912     540    1078    2151    1505
River Rch & RM= Knudson Branch,Reach-1,17934
     849    1148    1392     835    1667    3325    2389
River Rch & RM= Knudson Branch,Reach-1,13252
    1025    1401    1710    1032    2060    4110    2991
River Rch & RM= Knudson Branch,Reach-1,10777
    1199    1641    2003    1209    2411    4811    3496
Boundary for River Rch & Prof#=Knudson Branch,Reach-1,1
Up Type=0
Dn Type=3
Dn Slope=0.005
Boundary for River Rch & Prof#=Knudson Branch,Reach-1,2
Up Type=0
Dn Type=3
Dn Slope=0.005
Boundary for River Rch & Prof#=Knudson Branch,Reach-1,3
Up Type=0
Dn Type=3
Dn Slope=0.005
Boundary for River Rch & Prof#=Knudson Branch,Reach-1,4
Up Type=0
Dn Type=3
Dn Slope=0.005
Boundary for River Rch & Prof#=Knudson Branch,Reach-1,5
Up Type=0
Dn Type=3
Dn Slope=0.005
Boundary for River Rch & Prof#=Knudson Branch,Reach-1,6
Up Type=0
Dn Type=3
Dn Slope=0.005
Boundary for River Rch & Prof#=Knudson Branch,Reach-1,7
Up Type=0
Dn Type=3
Dn Slope=0.005

--- Knudson Branch.g01 (geometry) ---

Geom Title=Existing Conditions
Program Version=4.10

River Reach=Knudson Branch  ,Reach-1
Reach XY= 30
        2726876.        6885461.      2726733.29      6885161.09
      2726918.19      6883907.58      2726533.69      6883514.74
      2726676.21      6883131.05      2726475.51      6882686.19
      2726739.22      6881897.19      2727036.12      6881900.66
        2727526.        6881311.      2726979.53      6880309.54
      2726725.22      6879095.86       2727218.3      6878764.69
      2727274.03      6878116.68      2726982.97      6877961.23
      2727417.01      6877468.07      2727427.97      6876616.89
      2727626.54      6876386.11      2727568.53       6875904.3
      2727283.48      6875864.62      2727518.51      6875257.41
      2727327.43      6875117.44      2727776.28      6874190.82
      2727576.37      6873695.73      2727668.68      6872810.87
      2727118.09       6871713.9      2726531.08      6871805.98
      2726486.06      6871222.11      2725789.48      6871124.76
      2725322.38       6868812.5        2724426.        6868111.

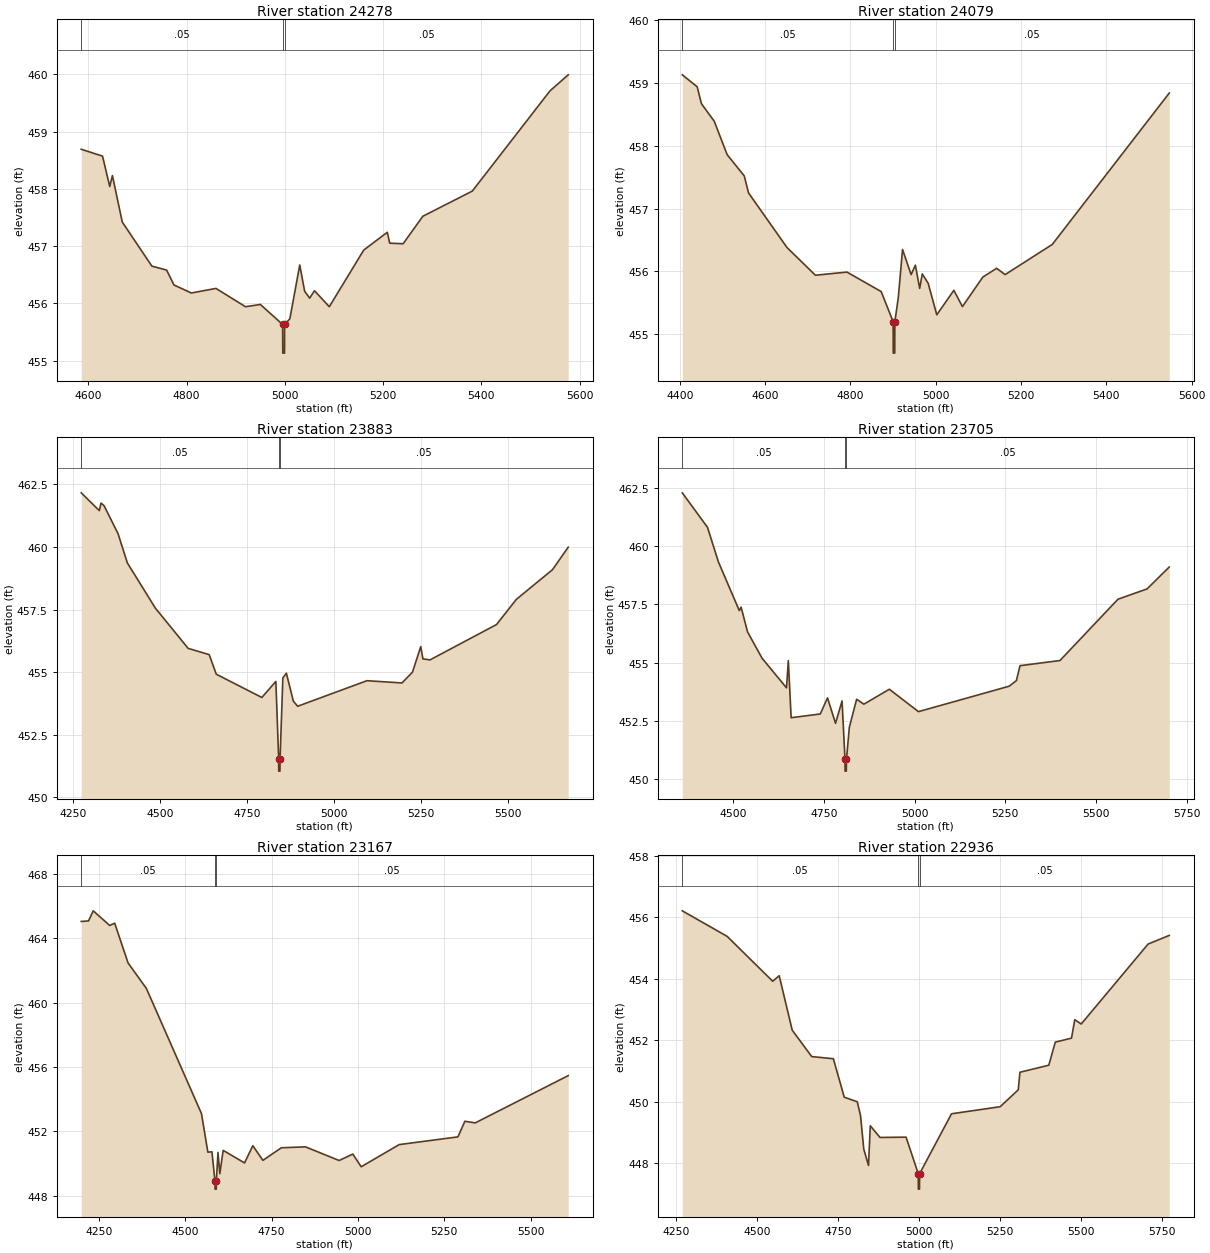
Type RM Length L Ch R = 1 ,24278   ,199,199,199
BEGIN DESCRIPTION:
Knudson Branch 1520
END DESCRIPTION:
XS GIS Cut Line= 3
       2727289.2      6885420.39      2726876.31      6885388.76
      2726300.76      6885353.95
#Sta/Elev= 30
  4585.9  458.69  4629.2  458.57  4643.8  458.04  4649.3  458.23  4669.3  457.42
  4729.5  456.65  4759.6  456.58  4774.5  456.32  4809.8  456.18  4859.9  456.26
  4920.1  455.94  4950.2  455.98  4995.6  455.63  4995.9  455.13  4999.4  455.13
  4999.6  455.63  5010.3  455.73  5030.4  456.67  5040.4  456.21  5050.6  456.09
  5060.4  456.22  5090.5  455.94  5160.6  456.93  5208.5  457.24  5213.5  457.05
  5240.7  457.04  5280.8  457.52  5381.5  457.96  5539.5  459.71  5576.6  459.99
#Mann= 3 ,-1 , 0
  4585.9     .05       0  4995.6     .04       0  4999.6     .05       0
Bank Sta=4995.6,4999.6
XS Rating Curve= 0 ,0
Exp/Cntr=0.3,0.1

Type RM Length L Ch R = 1 ,24079   ,196,196,196
BEGIN DESCRIPTION:
Knudson Branch 1519
END DESCRIPTION:
XS GIS Cut Line= 3
      2727380.79      6885271.01      2726769.42      6885222.05
      2726242.04      6885188.05
#Sta/Elev= 30
  4405.7  459.13  4440.6  458.94  4450.6  458.67  4480.7  458.39  4510.8  457.86
    4551  457.52    4561  457.25  4651.3  456.38  4717.8  455.94  4791.7  455.99
    4872  455.68  4900.1   455.2  4900.3   454.7  4903.8   454.7  4904.1   455.2
  4912.1  455.58  4922.1  456.35  4942.2  455.95  4952.2   456.1  4962.3  455.73
  4968.4  455.96  4982.3  455.81  5002.4  455.31  5042.5   455.7  5062.5  455.44
  5110.3  455.91  5142.7  456.05  5162.7  455.95  5273.2  456.43  5547.5  458.84
#Mann= 3 ,-1 , 0
  4405.7     .05       0  4900.1     .04       0  4904.1     .05       0
Bank Sta=4900.1,4904.1
XS Rating Curve= 0 ,0
Exp/Cntr=0.3,0.1

Type RM Length L Ch R = 1 ,23883   ,178,178,178
BEGIN DESCRIPTION:
Knudson Branch 1518
END DESCRIPTION:
XS GIS Cut Line= 3
      2727500.88       6885152.6      2726780.16      6885062.75
      2726110.98      6884990.16
#Sta/Elev= 30
  4273.7  462.16  4325.5  461.45  4330.6  461.75  4339.1  461.65  4379.4  460.53
  4406.2  459.36    4487  457.55  4580.9  455.95  4641.4   455.7  4661.6  454.92
  4792.6  453.99  4832.9  454.63    4841  451.55  4841.2  451.05  4844.7  451.05
    4845  451.55    4853  454.77  4863.1  454.96  4883.3  453.84  4895.6  453.64
  5094.7  454.66  5195.3  454.57  5225.5     455  5249.3  456.02  5255.6  455.53
  5275.8  455.49  5466.9   456.9  5524.2  457.91  5627.8  459.09  5673.1  459.99
#Mann= 3 ,-1 , 0
  4273.7     .05       0    4841     .04       0    4845     .05       0
Bank Sta=4841,4845
XS Rating Curve= 0 ,0
Exp/Cntr=0.3,0.1

Type RM Length L Ch R = 1 ,23705   ,538,538,538
BEGIN DESCRIPTION:
Knudson Branch 1514
END DESCRIPTION:
XS GIS Cut Line= 3
      2727465.34      6884948.29      2726821.01      6884898.55
       2726124.7      6884873.59
#Sta/Elev= 30
  4359.2  462.28  4428.7   460.8  4458.8  459.32  4516.4  457.23  4521.4  457.38
  4539.1  456.32  4579.2  455.19  4646.6  453.92  4651.6  455.09  4659.4  452.64
  4739.7   452.8  4759.7  453.49  4781.8   452.4  4799.8  453.36  4807.9  450.85
  4808.1  450.35  4811.6  450.35  4811.9  450.85  4819.9  452.23    4840  453.43
    4860  453.22  4930.2  453.86  5010.5   452.9  5260.6  453.99  5280.6  454.23
  5290.6  454.87  5400.7  455.09  5560.8  457.72  5640.9  458.16  5702.2   459.1
#Mann= 3 ,-1 , 0
  4359.2     .05       0  4807.9     .04       0  4811.9     .05       0
Bank Sta=4807.9,4811.9
XS Rating Curve= 0 ,0
Exp/Cntr=0.3,0.1

Type RM Length L Ch R = 1 ,23167   ,231,231,231
BEGIN DESCRIPTION:
Knudson Branch 1515
END DESCRIPTION:
XS GIS Cut Line= 3
      2727565.37      6884698.26       2726828.2      6884392.11
      2726216.89      6884373.78
#Sta/Elev= 30
  4198.9  465.06  4219.9  465.09  4233.5  465.72  4281.2  464.81  4295.7  464.95
  4334.4  462.48  4387.5  460.89  4546.9  453.11  4565.4  450.71  4577.2  450.73
    4586  448.91  4586.3  448.41  4589.8  448.41    4590  448.91  4594.7  450.69
  4600.1  449.37  4609.7  450.82  4671.7  450.04  4695.5  451.11  4724.8   450.2
    4778  450.98  4847.9  451.04  4945.4  450.19  4985.1  450.59  5009.3   449.8
  5119.4  451.18  5289.4  451.66  5309.5  452.63  5339.5  452.53  5608.7  455.47
#Mann= 3 ,-1 , 0
  4198.9     .05       0    4586     .04       0    4590     .05       0
Bank Sta=4586,4590
XS Rating Curve= 0 ,0
Exp/Cntr=0.3,0.1

Type RM Length L Ch R = 1 ,22936   ,234,234,234
BEGIN DESCRIPTION:
Knudson Branch 1517
END DESCRIPTION:
XS GIS Cut Line= 3
      2727653.83        6884260.      2726921.95      6884190.89
      2726154.54       6884229.2
#Sta/Elev= 30
    4268  456.21  4406.4  455.38  4547.1  453.92  4567.2   454.1  4607.3  452.33
  4667.6  451.47  4734.4   451.4    4768  450.15  4808.2     450  4818.3  449.55
  4828.3  448.46  4842.9  447.93  4848.4  449.22  4878.5  448.84  4958.9  448.85
  4996.6  447.66  4996.8  447.16  5000.3  447.16  5000.6  447.66  5099.2  449.61
  5249.4  449.84  5305.3  450.39  5310.4  450.96  5399.6  451.19  5419.6  451.94
  5469.7  452.07  5479.7  452.67  5499.7  452.53  5706.2  455.13  5771.5  455.41
#Mann= 3 ,-1 , 0
    4268     .05       0  4996.6     .04       0  5000.6     .05       0
Bank Sta=4996.6,5000.6
XS Rating Curve= 0 ,0
Exp/Cntr=0.3,0.1

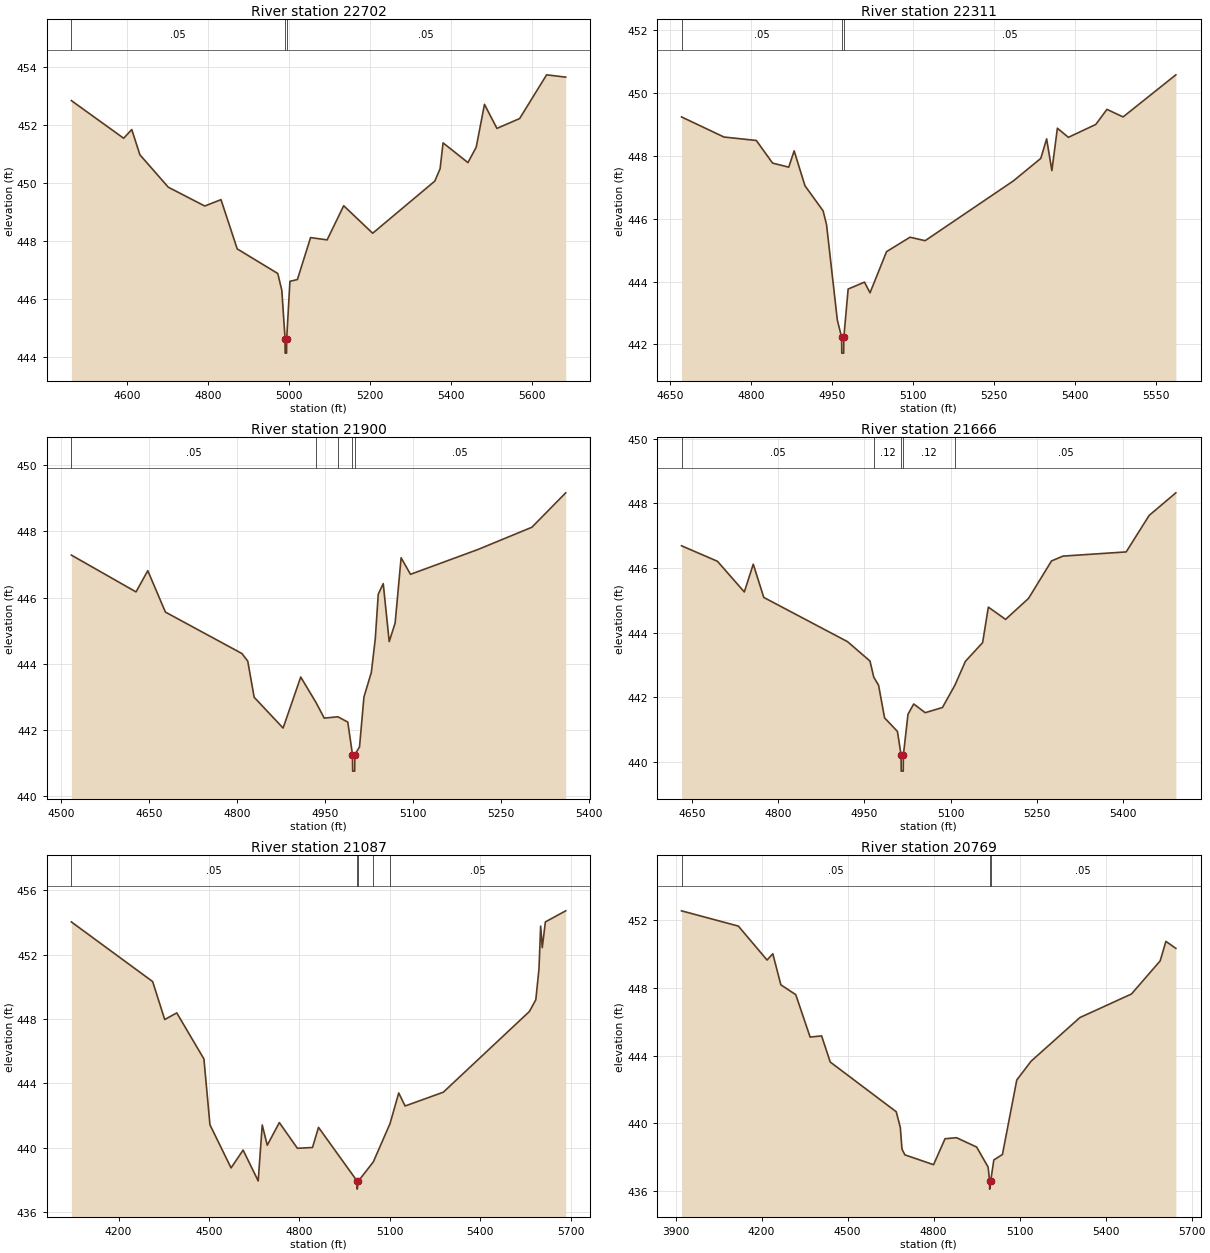
Type RM Length L Ch R = 1 ,22702   ,391,391,391
BEGIN DESCRIPTION:
Knudson Branch 1516
END DESCRIPTION:
XS GIS Cut Line= 3
       2727414.9      6883972.98      2726868.37      6883973.16
      2726209.86      6884108.99
#Sta/Elev= 30
  4463.6  452.85  4592.5  451.55  4612.5  451.85  4632.5  450.98  4702.5  449.86
  4792.5  449.21  4832.5  449.43  4872.5  447.73  4972.5  446.88  4982.5   446.3
  4990.5  444.63  4990.7  444.13  4994.2  444.13  4994.5  444.63  5002.5  446.61
  5020.9  446.67  5053.4  448.12  5094.2  448.04  5135.1  449.22  5206.5  448.27
  5359.7  450.07  5372.8   450.5  5380.1  451.39  5441.4  450.71  5461.8  451.24
  5482.2  452.72  5512.9  451.89  5568.9  452.23  5635.4  453.74  5682.5  453.66
#Mann= 3 ,-1 , 0
  4463.6     .05       0  4990.5     .04       0  4994.5     .05       0
Bank Sta=4990.5,4994.5
XS Rating Curve= 0 ,0
Exp/Cntr=0.3,0.1

Type RM Length L Ch R = 1 ,22311   ,411,411,411
BEGIN DESCRIPTION:
Knudson Branch 1484
END DESCRIPTION:
XS GIS Cut Line= 3
      2727154.57      6883683.72      2726831.78      6883686.54
      2726250.95      6883804.56
#Sta/Elev= 30
  4671.3  449.24  4749.9   448.6  4809.9  448.49  4839.9  447.77  4869.9  447.64
  4879.9  448.16  4899.9  447.05  4933.5  446.25  4939.9  445.81  4959.9  442.77
  4967.9  442.22  4968.1  441.72  4971.6  441.72  4971.9  442.22  4979.9  443.76
  5010.2  443.98  5020.4  443.64    5051  444.95  5094.4  445.41  5122.5   445.3
  5285.7   447.2  5336.7  447.92  5347.5  448.54  5357.2  447.53  5367.4  448.88
  5387.8  448.59  5438.5     449  5459.2  449.48  5489.1  449.24  5586.8  450.58
#Mann= 3 ,-1 , 0
  4671.3     .05       0  4967.9     .04       0  4971.9     .05       0
Bank Sta=4967.9,4971.9
XS Rating Curve= 0 ,0
Exp/Cntr=0.3,0.1

Type RM Length L Ch R = 1 ,21900   ,234,234,234
BEGIN DESCRIPTION:
Knudson Branch 1485
END DESCRIPTION:
XS GIS Cut Line= 3
      2727015.88      6883469.19      2726516.01       6883512.9
      2726179.07      6883570.46
#Sta/Elev= 30
  4516.9  447.28  4627.2  446.17  4647.3  446.81  4677.4  445.56  4807.9  444.31
  4817.9  444.08  4828.8  442.99  4878.2  442.06  4908.3   443.6  4934.4  442.83
  4948.4  442.36  4971.7   442.4  4988.6  442.24  4996.6  441.26  4996.9  440.76
  5000.4  440.76  5000.6  441.26  5008.6  441.49  5016.2     443  5028.8  443.74
  5035.5  444.75  5040.6   446.1  5049.1  446.42  5059.3  444.67  5069.4  445.23
  5079.6   447.2  5095.6   446.7  5210.8  447.45  5302.7  448.12  5360.5  449.16
#Mann= 5 ,-1 , 0
  4516.9     .05       0  4934.4     .12       0  4971.7     .05       0
  4996.6     .04       0  5000.6     .05       0
Bank Sta=4996.6,5000.6
XS Rating Curve= 0 ,0
Exp/Cntr=0.3,0.1

Type RM Length L Ch R = 1 ,21666   ,579,579,579
BEGIN DESCRIPTION:
Knudson Branch 1486
END DESCRIPTION:
XS GIS Cut Line= 3
      2726976.25      6883405.91      2726617.74        6883304.
      2726129.49      6883292.57
#Sta/Elev= 30
  4631.4  446.69    4694  446.21  4740.8  445.26  4756.4  446.12  4774.7  445.09
  4920.6  443.72  4959.7  443.12  4966.3  442.62  4974.7  442.37  4985.1  441.36
  5007.5  440.94  5013.9  440.21  5014.1  439.71  5017.6  439.71  5017.9  440.21
  5025.9  441.47  5035.9  441.79  5055.9  441.52  5085.9  441.68  5107.6  442.37
  5125.9  443.11  5155.9  443.69  5165.9  444.79  5195.9  444.41  5235.9  445.06
  5275.9  446.22  5295.9  446.37    5406   446.5    5446  447.63  5492.5  448.33
#Mann= 5 ,-1 , 0
  4631.4     .05       0  4966.3     .12       0  5013.9     .07       0
  5017.9     .12       0  5107.6     .05       0
Bank Sta=5013.9,5017.9
XS Rating Curve= 0 ,0
Exp/Cntr=0.3,0.1

Type RM Length L Ch R = 1 ,21087   ,318,318,318
BEGIN DESCRIPTION:
Knudson Branch 1487
END DESCRIPTION:
XS GIS Cut Line= 3
      2727525.42      6882775.59      2726550.15      6882807.13
      2725922.16      6883022.89
#Sta/Elev= 30
  4043.4  454.04    4313  450.33    4353  447.97    4393  448.38    4483  445.52
  4503.1  441.42  4573.1  438.74  4613.1  439.85  4663.1  437.93  4676.5  441.41
  4693.2  440.15  4733.2  441.56  4793.2  439.96  4843.2  440.01  4863.2  441.26
  4991.3  437.92  4991.6  437.42  4995.3  437.92  5044.9  439.11  5100.5   441.5
  5129.3   443.4  5150.4  442.59  5277.3  443.45  5562.8  448.47    5584   449.2
  5594.5  451.11  5600.1  453.78  5605.4  452.44  5615.7  454.04  5683.2  454.73
#Mann= 5 ,-1 , 0
  4043.4     .05       0  4991.3     .04       0  4995.3     .05       0
  5044.9     .12       0  5100.5     .05       0
Bank Sta=4991.3,4995.3
XS Rating Curve= 0 ,0
Exp/Cntr=0.3,0.1

Type RM Length L Ch R = 1 ,20769   ,426,426,426
BEGIN DESCRIPTION:
Knudson Branch 1489
END DESCRIPTION:
XS GIS Cut Line= 3
      2727604.04      6882612.94      2726526.58      6882560.67
      2725881.31      6882549.03
#Sta/Elev= 30
  3920.8  452.53  4119.1  451.63  4219.2  449.63  4239.2     450  4267.3  448.17
  4319.3  447.59  4369.4  445.09  4409.4  445.16  4439.5  443.62  4669.7  440.69
    4684  439.76  4689.7  438.49  4699.8  438.15  4799.9  437.57  4839.9   439.1
    4880  439.16  4950.1  438.61  4990.1  437.43  4995.3  436.63  4995.6  436.13
  4999.3  436.63  5010.1  437.85  5040.1  438.17  5090.1  442.56  5140.1  443.67
  5310.2  446.24  5490.2  447.63  5590.2  449.58  5610.2  450.73  5644.9  450.32
#Mann= 3 ,-1 , 0
  3920.8     .05       0  4995.3     .05       0  4999.3     .05       0
Bank Sta=4995.3,4999.3
XS Rating Curve= 0 ,0
Exp/Cntr=0.3,0.1

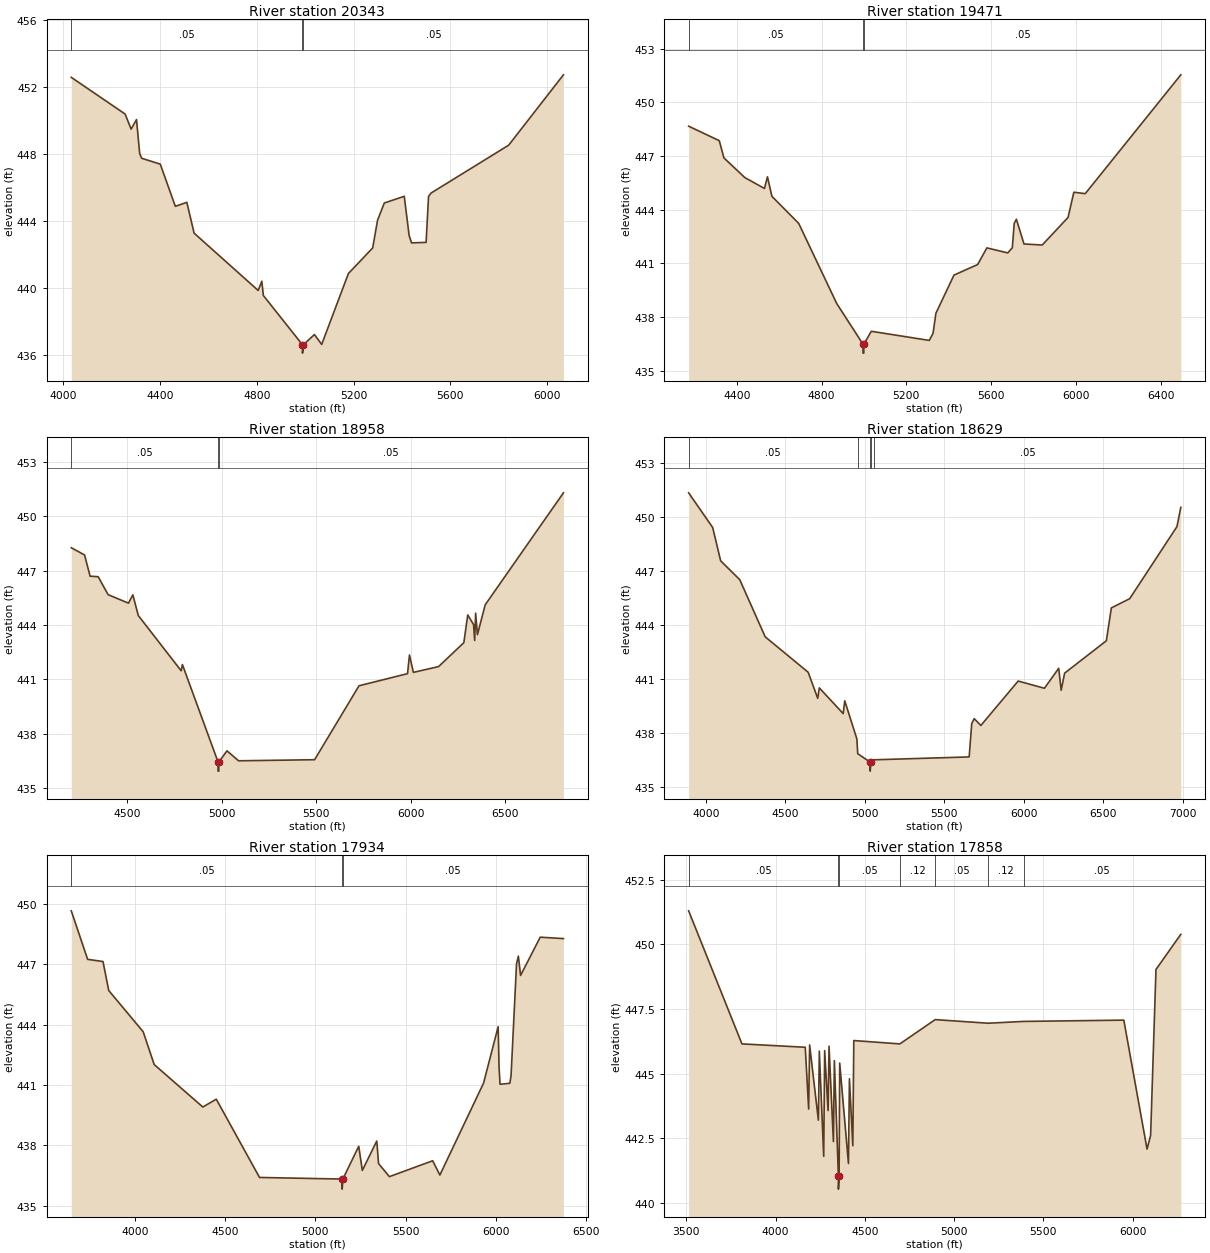
Type RM Length L Ch R = 1 ,20343   ,872,872,872
BEGIN DESCRIPTION:
Knudson Branch 1488
END DESCRIPTION:
XS GIS Cut Line= 3
      2727628.05      6882605.49      2726730.12      6882264.11
      2725660.42      6882174.28
#Sta/Elev= 30
    4033  452.57  4255.6  450.38  4280.4  449.48  4302.6  450.05  4315.8  448.02
    4324  447.74  4400.8  447.39  4463.1  444.87  4510.6  445.11  4540.7  443.27
  4805.5  439.85  4820.5   440.4  4826.9  439.55  4988.5  436.61  4988.7  436.11
  4992.5  436.61  5037.9  437.22    5068  436.63  5178.4  440.86  5278.8  442.39
  5298.8  444.04  5326.7  445.07  5409.2  445.47  5429.3  443.14  5439.3  442.69
  5499.5  442.72  5509.6  445.46  5519.6  445.66  5840.7  448.52  6067.1  452.72
#Mann= 3 ,-1 , 0
    4033     .05       0  4988.5     .05       0  4992.5     .05       0
Bank Sta=4988.5,4992.5
XS Rating Curve= 0 ,0
Exp/Cntr=0.3,0.1

Type RM Length L Ch R = 1 ,19471   ,513,513,513
BEGIN DESCRIPTION:
Knudson Branch 1455
END DESCRIPTION:
XS GIS Cut Line= 4
      2727773.78      6882187.65      2727472.35       6881851.6
      2726785.36      6881723.16       2725631.9      6881920.83
#Sta/Elev= 30
  4173.4  448.66  4317.9  447.85  4339.6  446.89  4438.2  445.79  4530.9  445.18
    4545  445.83  4566.1  444.74  4692.3  443.23  4871.7  438.75  4995.5  436.48
  4995.8  435.98  4999.3  435.98  4999.5  436.48  5034.7   437.2    5308  436.69
  5325.9  437.09  5339.4  438.21  5424.5  440.34  5536.1  440.93  5579.6  441.86
  5678.2  441.58  5699.6  441.87  5708.6  443.23  5718.8  443.46  5754.6  442.08
  5840.5  442.02  5962.3  443.56  5989.7  444.97  6043.4  444.89    6494  451.53
#Mann= 3 ,-1 , 0
  4173.4     .05       0  4995.5     .05       0  4999.5     .05       0
Bank Sta=4995.5,4999.5
XS Rating Curve= 0 ,0
Exp/Cntr=0.3,0.1

Type RM Length L Ch R = 1 ,18958   ,329,329,329
BEGIN DESCRIPTION:
Knudson Branch 1453
END DESCRIPTION:
XS GIS Cut Line= 3
      2727781.89      6882131.67      2727377.69      6881450.24
      2725613.05      6881876.12
#Sta/Elev= 30
  4202.4  448.27  4272.9  447.87  4302.1   446.7  4344.9  446.67  4397.6  445.68
  4505.5  445.21  4528.7  445.67  4557.4  444.53  4784.5  441.48  4791.3  441.82
  4980.2  436.44  4980.4  435.94  4983.9  435.94  4984.2  436.44  5027.3  437.06
    5089  436.51  5491.7  436.57  5726.8  440.65    5984  441.32  5994.3  442.35
  6014.9  441.39  6148.6  441.71  6282.3  443.03    6303  444.56  6333.8  444.03
  6339.8  443.15  6344.9  444.66  6354.3  443.47  6395.5  445.12    6810   451.3
#Mann= 3 ,-1 , 0
  4202.4     .05       0  4980.2     .03       0  4984.2     .05       0
Bank Sta=4980.2,4984.2
XS Rating Curve= 0 ,0
Exp/Cntr=0.3,0.1

Type RM Length L Ch R = 1 ,18629   ,695,695,695
BEGIN DESCRIPTION:
Knudson Branch 1454
END DESCRIPTION:
XS GIS Cut Line= 3
      2728627.13      6881164.57      2727516.89      6881208.02
      2725630.87      6881824.47
#Sta/Elev= 30
  3891.4  451.35  4042.6  449.42  4092.7  447.57  4212.8  446.52  4372.9  443.34
  4643.1  441.37  4703.2  439.92  4713.2   440.5  4863.3  439.07  4873.3  439.78
  4949.5  437.66  4954.8  436.84    5033  436.37  5033.2  435.87    5037  436.37
    5057   436.5  5655.7  436.66  5671.7  438.51  5687.3  438.79  5729.3  438.41
  5963.8  440.88  6129.1  440.48  6218.8  441.59  6234.3  440.37    6256  441.32
  6518.4  443.12    6550  444.95  6665.1  445.46  6962.5  449.47  6986.7  450.54
#Mann= 5 ,-1 , 0
  3891.4     .05       0  4954.8     .12       0    5033     .07       0
    5037     .12       0    5057     .05       0
Bank Sta=5033,5037
XS Rating Curve= 0 ,0
Exp/Cntr=0.3,0.1

Type RM Length L Ch R = 1 ,17934   ,76,76,76
BEGIN DESCRIPTION:
Knudson Branch 1452
END DESCRIPTION:
XS GIS Cut Line= 4
       2728471.2      6881004.45      2727562.82      6880672.68
      2726400.08      6880654.53      2725809.81      6880757.29
#Sta/Elev= 30
  3646.6  449.66  3737.3  447.25  3822.5  447.14  3854.4   445.7  4045.4  443.65
  4106.5  442.02  4376.1  439.91  4450.6   440.3  4690.5  436.41  5148.5  436.33
  5148.8  435.83  5152.6  436.33  5240.6  437.96  5260.6  436.76  5340.6  438.22
  5350.6   437.1  5410.6  436.45  5650.6  437.24  5690.6  436.53  5932.9   441.1
  6013.7   443.9  6018.8  441.87  6024.3  441.04  6078.4  441.09  6085.2  441.46
  6115.7  447.03  6125.8  447.41    6138  446.45  6247.1  448.35  6375.7  448.28
#Mann= 3 ,-1 , 0
  3646.6     .05       0  5148.5     .03       0  5152.6     .05       0
Bank Sta=5148.5,5152.6
XS Rating Curve= 0 ,0
Exp/Cntr=0.3,0.1

Type RM Length L Ch R = 1 ,17858   ,94,94,94
BEGIN DESCRIPTION:
Knudson Branch 1450
END DESCRIPTION:
XS GIS Cut Line= 3
      2728594.29      6880971.22      2727654.27      6880605.13
      2725906.97      6880552.07
#Sta/Elev= 30
  3513.3   451.3  3811.9  446.15  4166.5  446.02  4185.6  443.63    4191  446.11
    4240   443.2  4245.3  445.87  4269.9   441.8  4275.2  445.89  4294.4  443.57
  4299.7  446.06  4324.2  442.37  4329.6   445.5  4352.1  441.03  4352.4  440.53
  4356.2  441.03  4359.5  445.41  4408.5  441.52  4413.9   444.8    4433  442.21
  4438.4  446.28  4696.4  446.15  4894.4  447.09  5191.3  446.95  5389.2  447.02
    5951  447.07  6081.1  442.08  6101.1  442.61  6131.1  449.03  6270.2  450.39
#Mann= 7 ,-1 , 0
  3513.3     .05       0  4352.1     .04       0  4356.2     .05       0
  4696.4     .12       0  4894.4     .05       0  5191.3     .12       0
  5389.2     .05       0
Bank Sta=4352.1,4356.2
XS Rating Curve= 0 ,0
Exp/Cntr=0.3,0.1

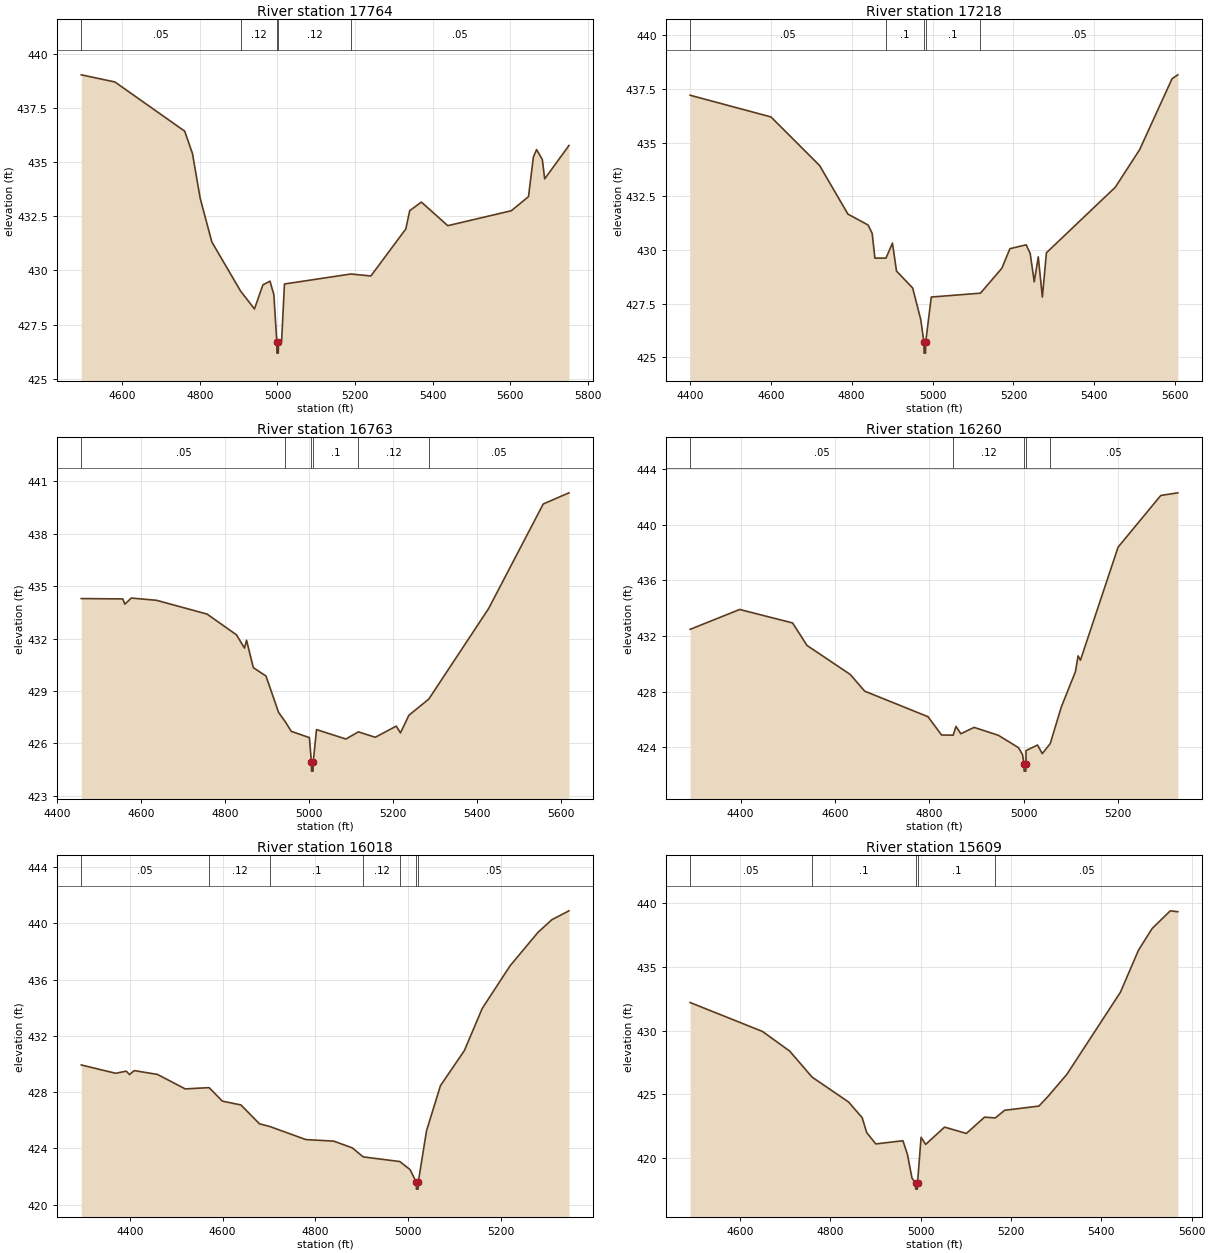
Type RM Length L Ch R = 1 ,17764   ,546,546,546
BEGIN DESCRIPTION:
Knudson Branch 1451
END DESCRIPTION:
XS GIS Cut Line= 4
      2727682.75       6880487.6      2727171.52      6880496.83
      2726781.72      6880475.57      2726491.32      6880268.78
#Sta/Elev= 30
  4493.8  439.02  4580.6  438.69  4760.6  436.42  4780.6  435.39  4800.6  433.32
  4830.6  431.31  4904.9  429.04  4940.6  428.22  4962.4  429.33  4980.6   429.5
  4990.6  428.88  4998.3  426.68  4998.6  426.18  5002.1  426.18  5002.5  426.68
  5010.6  426.73    5018  429.37  5189.2  429.83    5241  429.74  5331.1  431.91
  5341.1  432.75  5371.2  433.15  5439.3  432.06  5603.4  432.75  5647.6   433.4
  5660.3  435.23  5668.5  435.57  5683.3  435.11  5689.4  434.22    5752  435.76
#Mann= 5 ,-1 , 0
  4493.8     .05       0  4904.9     .12       0  4998.3     .07       0
  5002.5     .12       0  5189.2     .05       0
Bank Sta=4998.3,5002.5
XS Rating Curve= 0 ,0
Exp/Cntr=0.3,0.1

Type RM Length L Ch R = 1 ,17218   ,455,455,455
BEGIN DESCRIPTION:
Knudson Branch 1521
END DESCRIPTION:
XS GIS Cut Line= 3
      2727615.84      6880079.47      2727019.02      6880061.92
      2726411.86       6880101.1
#Sta/Elev= 30
  4400.9   437.2  4600.8  436.19  4720.9  433.93  4790.9  431.67  4840.9  431.16
  4850.9  430.77  4857.6  429.62    4885  429.62    4901  430.32    4911  429.02
    4951  428.23    4971  426.76  4978.9   425.7  4979.2   425.2  4982.7   425.2
  4983.1   425.7    4997  427.81  5118.6  427.99  5171.4  429.15  5191.4  430.06
  5231.5  430.24  5241.5  429.84  5251.5  428.52  5261.5  429.68  5271.6  427.81
  5281.6  429.87  5451.9  432.92  5512.1  434.67  5592.2  437.97  5606.4  438.15
#Mann= 5 ,-1 , 0
  4400.9     .05       0    4885      .1       0  4978.9     .07       0
  4983.1      .1       0  5118.6     .05       0
Bank Sta=4978.9,4983.1
XS Rating Curve= 0 ,0
Exp/Cntr=0.3,0.1

Type RM Length L Ch R = 1 ,16763   ,503,503,503
BEGIN DESCRIPTION:
Knudson Branch 1522
END DESCRIPTION:
XS GIS Cut Line= 3
      2727514.86      6879753.17      2726972.85      6879715.55
      2726354.71      6879708.19
#Sta/Elev= 30
  4457.2  434.29    4556  434.27    4561  433.97  4576.3  434.32  4636.5  434.19
  4756.8   433.4  4826.9  432.21  4845.8  431.45  4850.8   431.9    4867  430.33
  4897.1  429.85  4927.2  427.76  4943.4  427.22  4957.3  426.68  5000.5  426.32
  5005.3   424.9  5005.6   424.4  5009.2   424.4  5009.5   424.9  5017.4  426.78
  5087.4  426.24  5117.2  426.65  5157.4  426.34  5207.4  426.98  5217.4  426.59
  5237.4   427.6  5284.9  428.53  5427.4  433.72  5557.4  439.71  5618.7  440.35
#Mann= 6 ,-1 , 0
  4457.2     .05       0  4943.4      .1       0  5005.3     .07       0
  5009.5      .1       0  5117.2     .12       0  5284.9     .05       0
Bank Sta=5005.3,5009.5
XS Rating Curve= 0 ,0
Exp/Cntr=0.3,0.1

Type RM Length L Ch R = 1 ,16260   ,242,242,242
BEGIN DESCRIPTION:
Knudson Branch 1523
END DESCRIPTION:
XS GIS Cut Line= 3
      2727419.11      6879462.58      2726719.59      6879325.16
      2726400.03      6879356.72
#Sta/Elev= 30
  4292.9  432.48    4398  433.91  4510.1  432.94  4540.7  431.32  4632.4  429.23
  4662.9  428.03  4797.2  426.19    4826  424.87  4850.7  424.86  4856.6  425.49
  4866.8  424.96    4895  425.42  4946.4  424.85  4989.1  423.96  4997.8  423.45
  5000.7  422.77  5001.1  422.27  5004.7  422.27    5005  422.77  5005.1  423.75
  5029.5  424.15  5039.5  423.53  5056.4  424.25  5079.7  426.87  5109.9  429.44
  5115.5  430.57  5120.5  430.26  5200.3   438.4  5290.8  442.12  5326.9  442.31
#Mann= 5 ,-1 , 0
  4292.9     .05       0  4850.7     .12       0  5000.7     .07       0
    5005     .12       0  5056.4     .05       0
Bank Sta=5000.7,5005
XS Rating Curve= 0 ,0
Exp/Cntr=0.3,0.1

Type RM Length L Ch R = 1 ,16018   ,409,409,409
BEGIN DESCRIPTION:
Knudson Branch 1524
END DESCRIPTION:
XS GIS Cut Line= 3
        2727430.      6879128.22      2726721.58      6879111.62
      2726379.25      6879124.85
#Sta/Elev= 30
  4295.3  429.93  4369.3  429.34  4392.2  429.49  4399.3  429.25  4409.3  429.53
  4459.3  429.26  4519.4  428.23  4570.8  428.32  4599.4  427.36  4639.4  427.09
  4679.4  425.75  4701.5  425.56  4779.4  424.63  4839.5  424.52  4879.5  424.04
    4903   423.4  4981.8  423.07  5003.9   422.5  5017.4  421.61  5017.7  421.11
  5021.3  421.11  5021.7  421.61  5039.5  425.26  5069.5  428.46    5121  430.95
  5159.6  433.95  5219.7  436.98  5279.7  439.35  5309.7  440.25  5346.5  440.88
#Mann= 7 ,-1 , 0
  4295.3     .05       0  4570.8     .12       0  4701.5      .1       0
    4903     .12       0  4981.8     .05       0  5017.4     .04       0
  5021.7     .05       0
Bank Sta=5017.4,5021.7
XS Rating Curve= 0 ,0
Exp/Cntr=0.3,0.1

Type RM Length L Ch R = 1 ,15609   ,350,350,350
BEGIN DESCRIPTION:
Knudson Branch 1525
END DESCRIPTION:
XS GIS Cut Line= 3
      2727525.59      6878909.76      2727010.77      6878869.21
      2726449.32      6878827.67
#Sta/Elev= 30
    4490   432.2  4650.1  429.93  4710.3  428.39  4759.8  426.35  4840.7  424.39
  4870.8  423.16  4880.8  421.99  4900.9   421.1    4961  421.35  4971.1  420.26
  4981.1   418.4    4989  418.05  4989.3  417.55  4992.9  417.55  4993.3  418.05
  5001.2  421.62  5011.3  421.06  5053.1  422.42  5101.4  421.92  5141.6   423.2
  5165.5  423.14  5186.1  423.74  5261.9  424.07  5281.9  424.82    5324  426.57
  5442.4  433.01  5482.5  436.32  5512.6  438.01  5552.7   439.4  5569.4  439.33
#Mann= 5 ,-1 , 0
    4490     .05       0  4759.8      .1       0    4989     .07       0
  4993.3      .1       0  5165.5     .05       0
Bank Sta=4989,4993.3
XS Rating Curve= 0 ,0
Exp/Cntr=0.3,0.1

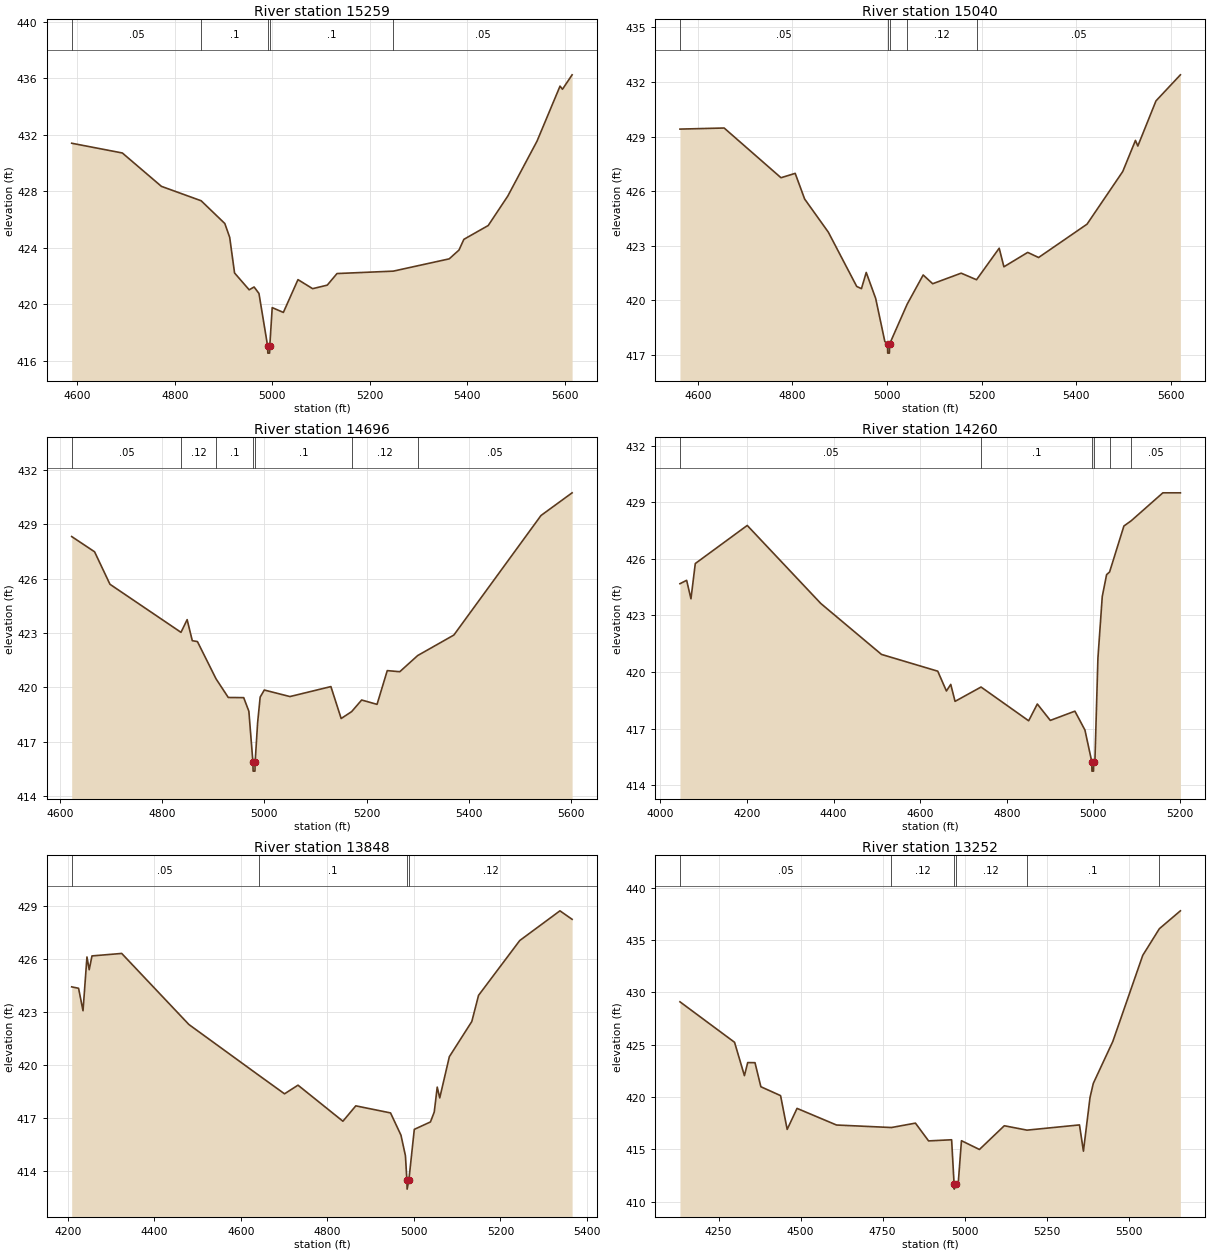
Type RM Length L Ch R = 1 ,15259   ,219,219,219
BEGIN DESCRIPTION:
Knudson Branch 1431
END DESCRIPTION:
XS GIS Cut Line= 3
      2727589.85      6878693.37      2727176.65      6878669.83
      2726564.13       6878634.7
#Sta/Elev= 30
  4588.1   431.4  4692.1  430.71  4772.3  428.35  4853.9  427.33  4902.5  425.72
  4912.5  424.74  4922.5  422.22  4952.5  421.03  4962.6  421.23  4972.6  420.77
  4990.4  417.05  4990.8  416.55  4994.4  416.55  4994.8  417.05  4999.8  419.77
  5022.7  419.43  5052.7  421.75  5082.8  421.11  5112.8  421.36  5132.8  422.18
  5248.3  422.35  5363.2  423.22  5383.2  423.84  5393.3   424.6  5443.3  425.58
  5483.4  427.66  5543.5  431.55  5590.7  435.44  5595.7  435.22  5615.5  436.24
#Mann= 5 ,-1 , 0
  4588.1     .05       0  4853.9      .1       0  4990.4     .07       0
  4994.8      .1       0  5248.3     .05       0
Bank Sta=4990.4,4994.8
XS Rating Curve= 0 ,0
Exp/Cntr=0.3,0.1

Type RM Length L Ch R = 1 ,15040   ,344,344,344
BEGIN DESCRIPTION:
Knudson Branch 1430
END DESCRIPTION:
XS GIS Cut Line= 3
      2727659.32      6878487.19       2727222.5      6878466.56
      2726604.66      6878407.06
#Sta/Elev= 30
  4562.2  429.41  4655.6  429.47  4775.8  426.74  4805.8  426.98  4825.8  425.57
  4875.9  423.75  4935.9  420.77  4945.9  420.65    4956  421.54    4976  420.11
  4995.3  417.75    5001  417.61  5001.4  417.11    5005  417.11  5005.4  417.61
  5042.4  419.79  5076.4   421.4  5096.5  420.92  5156.7   421.5  5189.2  421.14
  5237.1  422.87  5247.1  421.85  5297.4  422.64  5320.4  422.36  5422.8  424.19
  5498.3  427.08  5525.2  428.79  5530.2  428.48  5568.6  430.96  5620.2  432.39
#Mann= 5 ,-1 , 0
  4562.2     .05       0    5001     .05       0  5005.4     .05       0
  5042.4     .12       0  5189.2     .05       0
Bank Sta=5001,5005.4
XS Rating Curve= 0 ,0
Exp/Cntr=0.3,0.1

Type RM Length L Ch R = 1 ,14696   ,436,436,436
BEGIN DESCRIPTION:
Knudson Branch 1432
END DESCRIPTION:
XS GIS Cut Line= 3
      2727650.46       6878237.6      2727269.97      6878194.05
       2726675.2      6878152.41
#Sta/Elev= 30
    4623  428.32  4667.8  427.48  4697.9  425.69  4836.9  423.04  4848.9  423.74
    4859  422.58  4869.1  422.53  4905.4  420.48  4929.4  419.45  4959.6  419.44
  4969.7  418.69  4977.6  415.89    4978  415.39  4981.6  415.39    4982  415.89
  4986.8  418.05  4991.8  419.47  4999.9  419.86  5050.1   419.5  5130.2  420.05
  5150.3  418.29  5170.8  418.67  5190.4  419.31  5220.5  419.07  5240.5  420.93
    5265  420.87    5300  421.76  5370.8  422.89  5541.3  429.48  5602.2  430.73
#Mann= 7 ,-1 , 0
    4623     .05       0  4836.9     .12       0  4905.4      .1       0
  4977.6     .07       0    4982      .1       0  5170.8     .12       0
    5300     .05       0
Bank Sta=4977.6,4982
XS Rating Curve= 0 ,0
Exp/Cntr=0.3,0.1

Type RM Length L Ch R = 1 ,14260   ,412,412,412
BEGIN DESCRIPTION:
Knudson Branch 1429
END DESCRIPTION:
XS GIS Cut Line= 3
       2727941.4      6877970.81      2726985.03      6877955.31
      2726785.53       6877954.1
#Sta/Elev= 30
    4045  424.68  4060.4  424.86  4070.4  423.88  4080.4  425.75  4200.4  427.77
  4370.4  423.63  4510.5  420.93  4640.5  420.04  4660.5  418.99  4670.5  419.34
  4680.5  418.44  4740.5   419.2  4850.5  417.41  4870.5   418.3  4900.5  417.43
  4957.3  417.92  4980.5  416.92  4996.3  415.24  4996.7  414.74  5000.3  414.74
  5000.8  415.24  5003.5  415.24  5010.5  420.73  5020.5     424  5030.5  425.16
  5037.4   425.3  5070.5  427.74  5087.5  428.02  5160.5   429.5    5201   429.5
#Mann= 6 ,-1 , 0
    4045     .05       0  4740.5      .1       0  4996.3     .07       0
  5000.8      .1       0  5037.4     .12       0  5087.5     .05       0
Bank Sta=4996.3,5000.8
XS Rating Curve= 0 ,0
Exp/Cntr=0.3,0.1

Type RM Length L Ch R = 1 ,13848   ,596,596,596
BEGIN DESCRIPTION:
Knudson Branch 1428
END DESCRIPTION:
XS GIS Cut Line= 3
      2727941.34      6877846.11      2727171.41      6877641.03
      2726861.86       6877824.3
#Sta/Elev= 30
  4209.1  424.42    4225  424.34  4235.3  423.07  4244.4  426.11  4249.6  425.39
    4256  426.17  4324.7  426.31    4480  422.29  4640.9  419.43    4701  418.37
  4732.1  418.86  4835.9  416.82  4865.7  417.69    4946  417.29  4970.1  416.03
  4980.4  414.87  4983.8  413.48  4984.3  412.98  4988.3  413.48  5000.9  416.36
  5038.2  416.78    5047  417.34  5053.9  418.75  5059.7  418.14  5081.9  420.47
  5133.8  422.46  5149.4  423.94  5244.6  427.04  5337.5  428.72  5365.6  428.24
#Mann= 4 ,-1 , 0
  4209.1     .05       0  4640.9      .1       0  4983.8     .07       0
  4988.3     .12       0
Bank Sta=4983.8,4988.3
XS Rating Curve= 0 ,0
Exp/Cntr=0.3,0.1

Type RM Length L Ch R = 1 ,13252   ,344,344,344
BEGIN DESCRIPTION:
Knudson Branch 1433
END DESCRIPTION:
XS GIS Cut Line= 3
      2728241.96      6877292.08      2727374.74      6877230.17
      2726721.78      6877166.39
#Sta/Elev= 30
  4132.5   429.1  4298.9  425.23    4329  422.04    4339  423.29  4361.2  423.28
  4379.1  420.98  4439.2  420.13  4459.3   416.9  4489.4  418.91  4609.7  417.32
  4777.1  417.08  4850.3   417.5  4890.4   415.8  4960.6  415.91  4968.1  411.69
  4968.7  411.19  4973.1  411.69  4980.6   411.7  4990.6  415.82  5045.4  414.98
  5121.2  417.25  5190.4  416.83  5350.4  417.33  5362.4  414.82  5382.5  419.95
  5392.5   421.3    5452  425.31  5543.2  433.54  5593.9  436.09    5658   437.8
#Mann= 6 ,-1 , 0
  4132.5     .05       0  4777.1     .12       0  4968.1     .07       0
  4973.1     .12       0  5190.4      .1       0  5593.9     .05       0
Bank Sta=4968.1,4973.1
XS Rating Curve= 0 ,0
Exp/Cntr=0.3,0.1