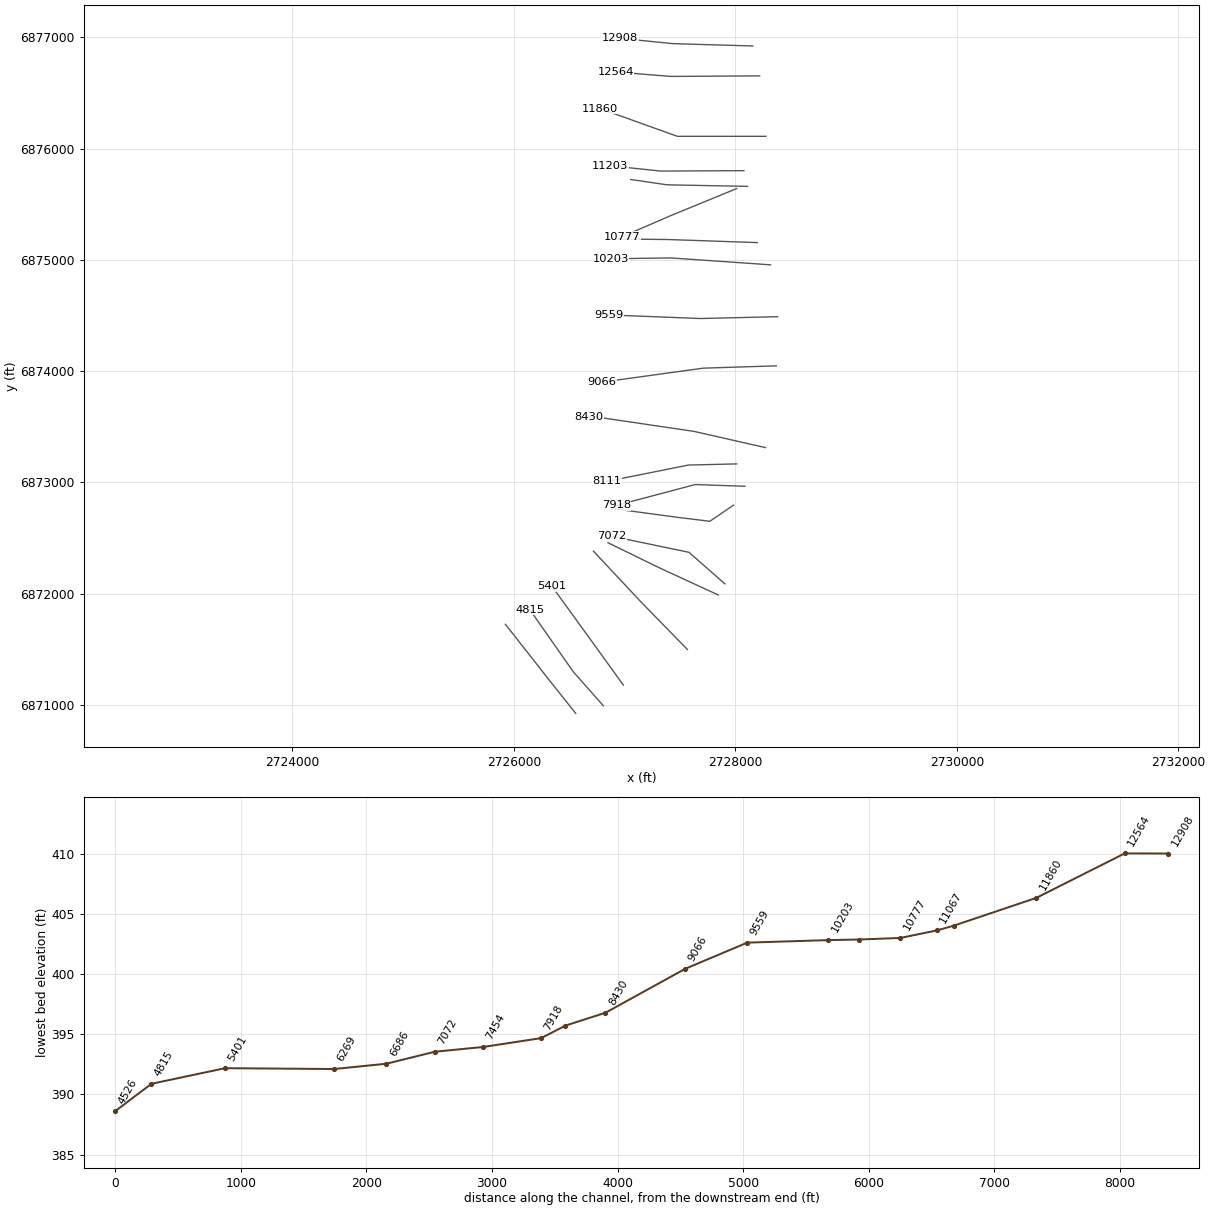
HEC-RAS study Knudson Branch.prj: Knudson Branch Base Level Engineering

--- Knudson Branch.g01 (geometry) --- (continued)

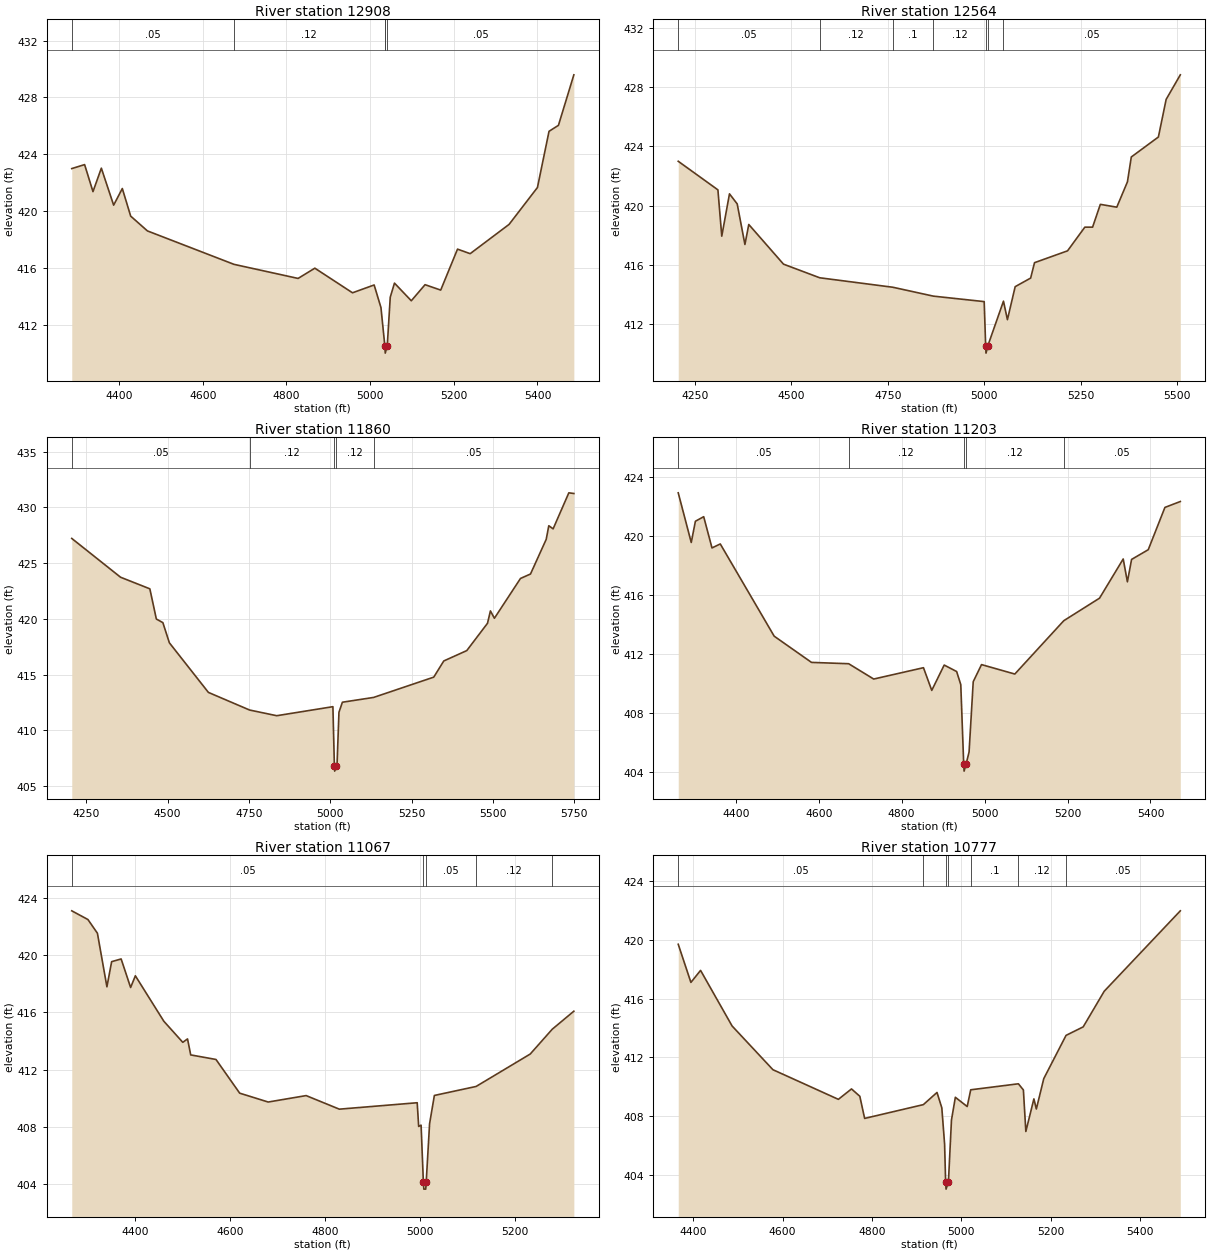
Type RM Length L Ch R = 1 ,12908   ,344,344,344
BEGIN DESCRIPTION:
Knudson Branch 1426
END DESCRIPTION:
XS GIS Cut Line= 3
      2728156.71      6876922.94      2727434.27       6876944.1
      2726959.39      6876991.64
#Sta/Elev= 30
  4286.9     423  4317.6  423.28  4337.6  421.38  4357.6  423.03    4387  420.43
  4407.7   421.6  4427.7  419.66  4467.7  418.62  4674.6  416.27  4827.8  415.28
  4867.9     416  4957.9  414.27  5009.6  414.82  5025.9  413.23  5034.9  410.62
  5035.2  410.53  5036.1  410.03  5040.9  410.53  5048.1  413.96  5058.2  414.95
  5098.4  413.71  5131.3  414.84  5168.7  414.46  5208.9  417.34  5239.1  417.02
  5332.2  419.08  5399.9  421.67  5427.6  425.62  5450.1  426.04  5486.9  429.59
#Mann= 5 ,-1 , 0
  4286.9     .05       0  4674.6     .12       0  5034.9     .05       0
  5035.2     .07       0  5040.9     .05       0
Bank Sta=5035.2,5040.9
XS Rating Curve= 0 ,0
Exp/Cntr=0.3,0.1

Type RM Length L Ch R = 1 ,12564   ,704,704,704
BEGIN DESCRIPTION:
Knudson Branch 1427
END DESCRIPTION:
XS GIS Cut Line= 3
      2728218.81      6876654.24       2727417.7      6876649.31
      2726919.43      6876689.42
#Sta/Elev= 30
  4207.1     423  4309.9  421.07  4319.9  417.94  4339.9   420.8  4359.9  420.12
  4379.9  417.38  4389.9  418.73  4479.9  416.05  4573.7  415.13  4763.2  414.49
  4868.1  413.89  4999.9  413.52  5003.7  410.54  5004.6  410.04  5009.4  410.54
  5049.9  413.55  5060.1   412.3  5080.2  414.53  5120.3  415.11  5130.3  416.15
  5215.9  416.95  5260.7  418.55  5280.8  418.55  5300.9  420.09  5343.5   419.9
  5371.1  421.61  5381.1  423.29  5451.3  424.64  5471.4  427.18  5508.1  428.84
#Mann= 7 ,-1 , 0
  4207.1     .05       0  4573.7     .12       0  4763.2      .1       0
  4868.1     .12       0  5003.7     .07       0  5009.4     .12       0
  5049.9     .05       0
Bank Sta=5003.7,5009.4
XS Rating Curve= 0 ,0
Exp/Cntr=0.3,0.1

Type RM Length L Ch R = 1 ,11860   ,657,657,657
BEGIN DESCRIPTION:
Knudson Branch 42
END DESCRIPTION:
XS GIS Cut Line= 3
      2728276.03        6876111.        2727476.        6876111.
      2726776.03      6876360.99
#Sta/Elev= 30
  4205.4  427.21  4355.4  423.73  4445.4  422.69  4465.4  419.98  4485.4  419.66
  4505.4  417.85  4625.4   413.4    4752  411.82  4835.4  411.31  5008.1  412.12
  5012.6  406.84  5013.5  406.34  5018.5  406.84  5020.8  406.91  5026.7  411.62
  5037.3  412.52  5133.3  412.95  5318.1  414.77  5348.9  416.22  5419.6  417.15
  5483.3   419.6  5492.3  420.71  5504.5  420.05  5584.7  423.62  5615.5  424.02
  5663.8  427.13  5671.7  428.35    5685  428.07  5733.3   431.3  5748.7  431.24
#Mann= 5 ,-1 , 0
  4205.4     .05       0    4752     .12       0  5012.6     .07       0
  5018.5     .12       0  5133.3     .05       0
Bank Sta=5012.6,5018.5
XS Rating Curve= 0 ,0
Exp/Cntr=0.3,0.1

Type RM Length L Ch R = 1 ,11203   ,136,136,136
BEGIN DESCRIPTION:
Knudson Branch 1425
END DESCRIPTION:
XS GIS Cut Line= 3
      2728077.38      6875802.35      2727326.11      6875798.59
      2726869.09      6875846.51
#Sta/Elev= 30
  4261.2  422.92  4292.6  419.55  4302.6  420.99  4322.6   421.3  4342.6  419.18
  4362.6  419.45  4492.6  413.19  4582.6  411.41  4672.2  411.32  4732.6  410.28
  4852.6  411.05  4872.6  409.51  4902.6  411.23  4932.6  410.79  4942.6   409.9
  4949.6  404.53  4950.6  404.03  4955.6  404.53  4962.6  405.33  4972.6   410.1
  4992.6  411.26  5072.9  410.62    5191  414.24  5277.2  415.77  5334.3  418.43
  5344.4  416.88  5354.5   418.4  5394.7  419.06  5434.9  421.93    5472  422.33
#Mann= 5 ,-1 , 0
  4261.2     .05       0  4672.2     .12       0  4949.6     .07       0
  4955.6     .12       0    5191     .05       0
Bank Sta=4949.6,4955.6
XS Rating Curve= 0 ,0
Exp/Cntr=0.3,0.1

Type RM Length L Ch R = 1 ,11067   ,290,290,290
BEGIN DESCRIPTION:
Knudson Branch 1424
END DESCRIPTION:
XS GIS Cut Line= 3
      2728110.07      6875661.11      2727381.84      6875675.21
      2727054.98      6875722.96
#Sta/Elev= 30
  4266.4  423.12  4300.5  422.51  4320.5  421.55  4340.5   417.8  4350.5  419.56
  4370.5  419.75  4390.5  417.75  4400.5  418.57  4460.5  415.39  4500.5  413.91
  4510.5  414.15  4517.2  413.03  4570.5  412.71  4620.5  410.35  4680.6  409.73
  4760.6  410.18  4830.6  409.23  4994.8  409.68  4997.9  408.02    5003  408.11
  5007.8  404.13  5008.8  403.63  5012.8  403.63  5013.8  404.13  5020.9  408.21
    5031  410.19    5119  410.82  5233.1  413.09  5279.6  414.83  5325.1  416.09
#Mann= 5 ,-1 , 0
  4266.4     .05       0  5007.8     .04       0  5013.8     .05       0
    5119     .12       0  5279.6     .05       0
Bank Sta=5007.8,5013.8
XS Rating Curve= 0 ,0
Exp/Cntr=0.3,0.1

Type RM Length L Ch R = 1 ,10777   ,327,327,327
BEGIN DESCRIPTION:
Knudson Branch 1412
END DESCRIPTION:
XS GIS Cut Line= 3
      2728012.31      6875641.73      2727413.42       6875397.2
      2726975.35      6875208.19
#Sta/Elev= 30
  4366.2   419.7  4394.6   417.1  4416.2  417.92  4486.8  414.13  4578.2  411.15
  4724.7  409.13  4754.1  409.84  4772.7  409.34  4783.5  407.83    4915  408.77
  4945.5   409.6  4956.3  408.55  4962.5  406.08  4964.8  403.51  4965.8  403.01
  4971.1  403.51  4977.9  407.72  4986.6  409.27  5013.1  408.64    5021  409.78
  5127.7  410.19  5138.9  409.77  5144.4  406.94  5162.4  409.16  5167.9  408.47
  5184.5  410.54  5234.4  413.49  5272.8  414.07  5319.9   416.5  5490.2  421.98
#Mann= 7 ,-1 , 0
  4366.2     .05       0    4915     .12       0  4964.8     .07       0
  4971.1     .12       0    5021      .1       0  5127.7     .12       0
  5234.4     .05       0
Bank Sta=4964.8,4971.1
XS Rating Curve= 0 ,0
Exp/Cntr=0.3,0.1

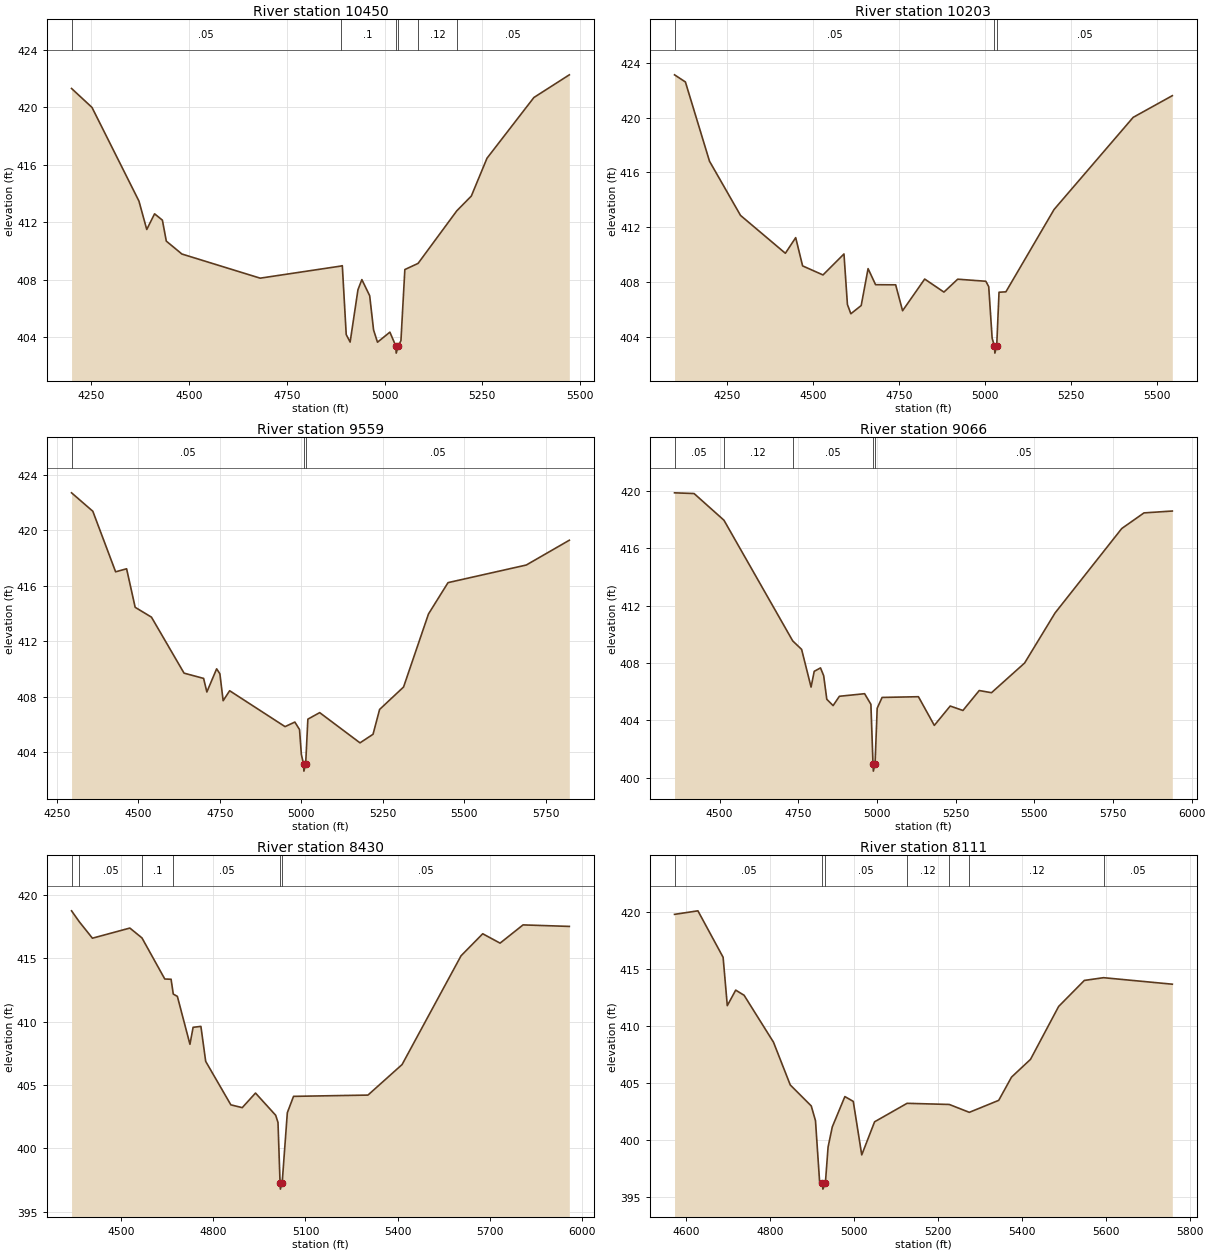
Type RM Length L Ch R = 1 ,10450   ,247,247,247
BEGIN DESCRIPTION:
Knudson Branch 1411
END DESCRIPTION:
XS GIS Cut Line= 3
      2728198.27      6875155.84      2727387.61      6875183.58
      2726925.27      6875188.33
#Sta/Elev= 30
  4199.2  421.31  4251.5  419.99  4371.6  413.47  4391.6  411.49  4411.6  412.58
  4431.6  412.14  4441.6  410.68  4481.6  409.78  4681.8   408.1  4887.6  408.94
  4891.9  408.97  4901.9  404.17  4911.9  403.65  4931.9  407.29  4941.9     408
  4961.9  406.88  4971.9  404.49  4981.9  403.64  5013.6  404.34  5028.7  403.38
  5029.8  402.88  5035.1  403.38  5041.9  403.75  5051.9   408.7  5085.8  409.13
  5184.8  412.79    5222  413.82    5262  416.45    5382  420.68  5472.7  422.26
#Mann= 6 ,-1 , 0
  4199.2     .05       0  4887.6      .1       0  5028.7     .07       0
  5035.1      .1       0  5085.8     .12       0  5184.8     .05       0
Bank Sta=5028.7,5035.1
XS Rating Curve= 0 ,0
Exp/Cntr=0.3,0.1

Type RM Length L Ch R = 1 ,10203   ,644,644,644
BEGIN DESCRIPTION:
Knudson Branch 1410
END DESCRIPTION:
XS GIS Cut Line= 3
      2728317.49      6874956.01       2727417.9      6875018.04
      2726872.18      6875010.45
#Sta/Elev= 30
  4096.8  423.12  4128.4   422.6  4198.5  416.82  4288.7  412.87  4419.1  410.11
  4449.1  411.25  4469.2  409.19  4528.5  408.53  4589.5  410.06  4599.5  406.38
  4609.5   405.7  4639.6   406.3  4659.6  408.99  4681.4  407.82  4739.8  407.81
  4759.9  405.92  4824.2  408.23  4880.2  407.28  4920.2  408.22    5002  408.07
  5010.4  407.68  5020.4  403.91  5027.2  403.33  5028.3  402.83  5033.6  403.33
  5040.4  407.27  5060.4   407.3  5200.4   413.3  5430.5  420.02  5544.3   421.6
#Mann= 3 ,-1 , 0
  4096.8     .05       0  5027.2     .04       0  5033.6     .05       0
Bank Sta=5027.2,5033.6
XS Rating Curve= 0 ,0
Exp/Cntr=0.3,0.1

Type RM Length L Ch R = 1 ,9559    ,493,493,493
BEGIN DESCRIPTION:
Knudson Branch 1413
END DESCRIPTION:
XS GIS Cut Line= 3
      2728381.27      6874489.93      2727681.62      6874473.52
      2726853.91      6874506.03
#Sta/Elev= 30
  4294.9   422.7  4360.2  421.37  4430.2     417  4463.9  417.22  4490.2  414.44
  4540.2  413.73  4640.3  409.69  4700.3  409.31  4710.3  408.33  4740.3     410
  4750.3  409.64  4760.3   407.7  4780.3  408.42  4950.4  405.83  4980.4  406.16
  4994.8  405.62  5000.4  403.83  5007.1  403.12  5008.2  402.62  5013.6  403.12
  5020.4  406.37  5056.7  406.84  5180.5  404.66  5220.5  405.28  5240.6  407.07
  5314.2  408.69  5390.7  413.96  5450.7  416.22  5690.9  417.49  5823.1  419.28
#Mann= 3 ,-1 , 0
  4294.9     .05       0  5007.1    .035       0  5013.6     .05       0
Bank Sta=5007.1,5013.6
XS Rating Curve= 0 ,0
Exp/Cntr=0.3,0.1

Type RM Length L Ch R = 1 ,9066    ,636,636,636
BEGIN DESCRIPTION:
Knudson Branch 1409
END DESCRIPTION:
XS GIS Cut Line= 3
      2728369.55      6874048.06      2727709.69      6874027.38
      2726796.84      6873902.08
#Sta/Elev= 30
    4357  419.86  4419.1  419.81    4514  417.95  4732.6  409.53  4760.8  408.94
  4790.8  406.31  4800.8  407.41  4820.8  407.65  4830.8  407.11  4840.8  405.46
  4860.8  405.02  4880.8  405.67  4960.9  405.85  4980.9  405.11  4987.6  400.95
  4988.7  400.45  4994.1  400.95  5000.9  404.84  5016.5  405.59  5131.9  405.64
  5182.4  403.64  5232.9  404.99  5273.3  404.68  5325.1  406.07  5364.1  405.92
  5469.3  407.99    5566  411.48  5777.9  417.37  5848.6  418.46  5938.6  418.59
#Mann= 5 ,-1 , 0
    4357     .05       0    4514     .12       0  4732.6     .05       0
  4987.6     .03       0  4994.1     .05       0
Bank Sta=4987.6,4994.1
XS Rating Curve= 0 ,0
Exp/Cntr=0.3,0.1

Type RM Length L Ch R = 1 ,8430    ,319,319,319
BEGIN DESCRIPTION:
Knudson Branch 1408
END DESCRIPTION:
XS GIS Cut Line= 4
      2728272.36      6873313.24      2727626.15      6873459.13
      2726711.64      6873593.56      2726676.46      6873592.74
#Sta/Elev= 30
  4337.8  418.75  4363.2  417.88  4405.8  416.59  4527.8  417.39  4567.3  416.61
  4641.6  413.37  4662.1  413.35  4669.3  412.18  4682.6     412  4723.6  408.22
  4733.9  409.56  4759.3  409.63  4774.9  406.87  4856.9  403.44    4894  403.22
  4937.2  404.37  5002.9  402.62  5010.5  402.05  5017.2  397.29  5018.3  396.79
  5024.1  397.29  5040.9  402.82  5061.1  404.11  5303.6  404.21  5414.8  406.62
  5606.9   415.2  5677.6  416.94  5734.1   416.2    5809  417.64  5959.8  417.52
#Mann= 6 ,-1 , 0
  4337.8     .12       0  4363.2     .05       0  4567.3      .1       0
  4669.3     .05       0  5017.2     .05       0  5024.1     .05       0
Bank Sta=5017.2,5024.1
XS Rating Curve= 0 ,0
Exp/Cntr=0.3,0.1

Type RM Length L Ch R = 1 ,8111    ,193,193,193
BEGIN DESCRIPTION:
Knudson Branch 1407
END DESCRIPTION:
XS GIS Cut Line= 3
      2728011.66      6873166.84      2727576.01      6873156.63
      2726840.42      6873009.62
#Sta/Elev= 30
  4571.7   419.8  4627.4  420.11  4687.4  416.04  4697.4   411.8  4717.4  413.16
  4737.4  412.71  4807.4   408.6  4847.4  404.85  4897.4  403.01  4907.5  401.72
  4917.5  396.26    4924  396.22  4925.1  395.72    4931  396.22  4937.5  399.41
  4947.5  401.17  4977.5  403.83  4997.5  403.41  5017.7  398.72  5048.3  401.62
  5125.7  403.24  5226.2  403.14    5274  402.45    5344   403.5  5374.6  405.54
  5419.7  407.09  5486.8  411.73    5548  414.01  5593.7  414.25  5757.6  413.68
#Mann= 7 ,-1 , 0
  4571.7     .05       0    4924     .05       0    4931     .05       0
  5125.7     .12       0  5226.2     .05       0    5274     .12       0
  5593.7     .05       0
Bank Sta=4924,4931
XS Rating Curve= 0 ,0
Exp/Cntr=0.3,0.1

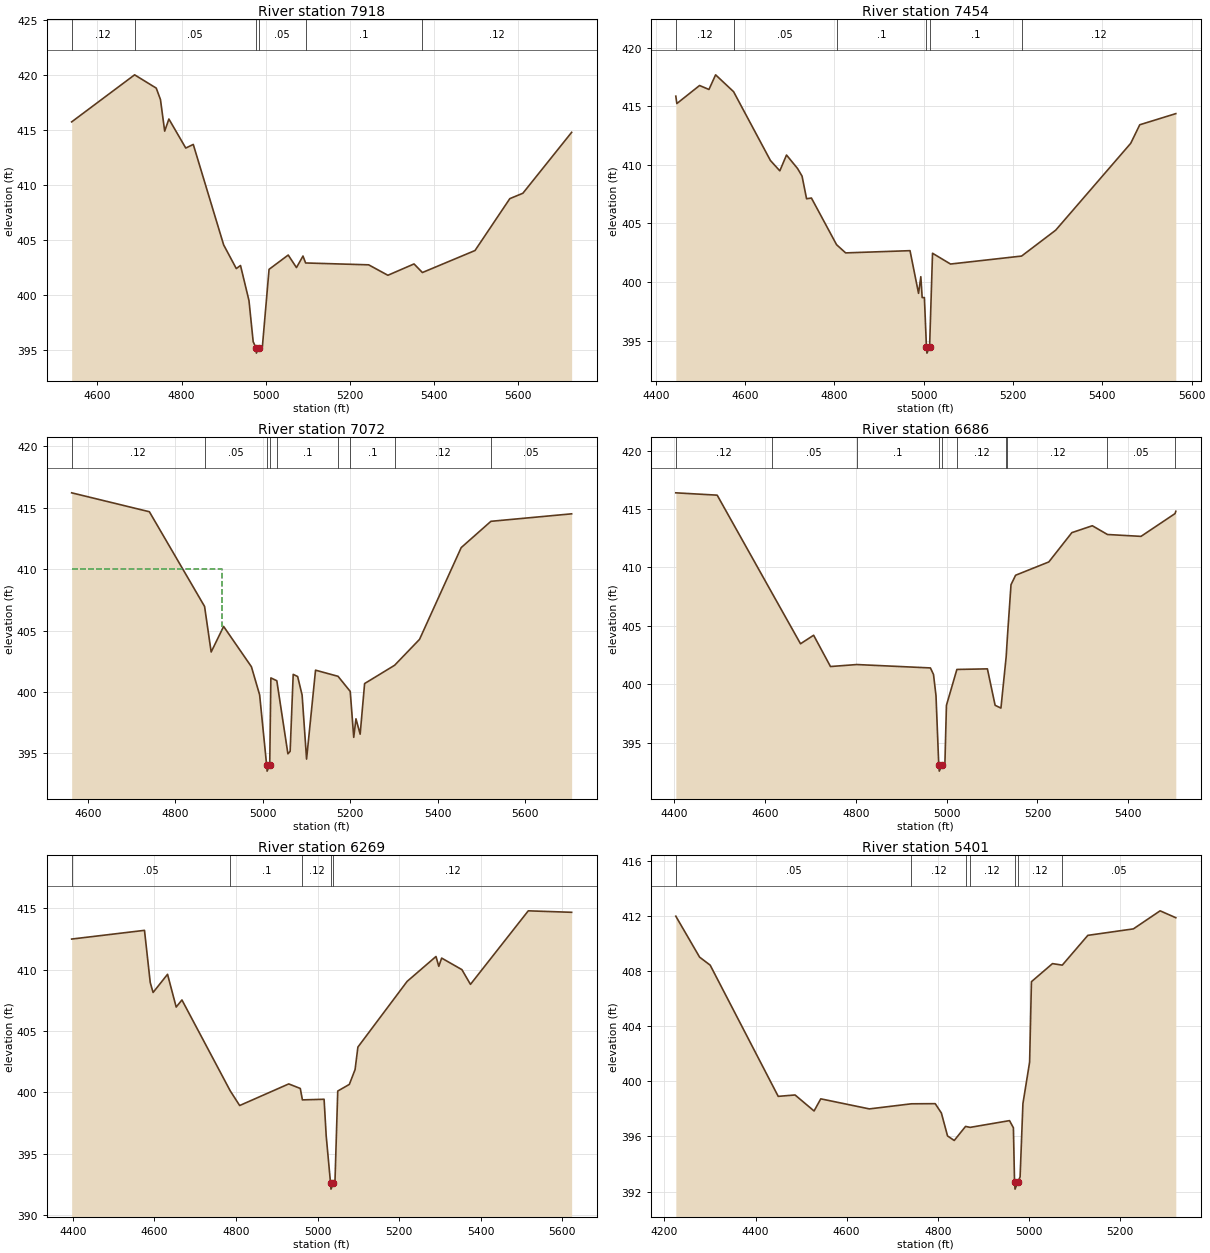
Type RM Length L Ch R = 1 ,7918    ,464,464,464
BEGIN DESCRIPTION:
Knudson Branch 1406
END DESCRIPTION:
XS GIS Cut Line= 3
      2728086.81      6872965.99      2727637.35      6872981.43
      2726924.08      6872793.26
#Sta/Elev= 30
  4539.1  415.71  4688.6  419.99    4740  418.78    4750  417.74    4760  414.87
    4770  415.97  4810.1  413.33  4827.9  413.66  4900.1  404.52  4930.1  402.37
  4940.1  402.65  4960.2  399.46  4970.2  395.72  4976.7  395.18  4977.8  394.68
  4983.7  395.18  4992.1  395.29  5007.9   402.3  5053.4   403.6    5073  402.46
  5088.5  403.51  5094.7  402.88  5244.5  402.71  5290.1  401.76  5352.2  402.79
  5372.1  402.01    5497  404.01  5579.7  408.73  5610.7  409.22  5726.5  414.76
#Mann= 6 ,-1 , 0
  4539.1     .12       0  4688.6     .05       0  4976.7     .05       0
  4983.7     .05       0  5094.7      .1       0  5372.1     .12       0
Bank Sta=4976.7,4983.7
XS Rating Curve= 0 ,0
Exp/Cntr=0.3,0.1

Type RM Length L Ch R = 1 ,7454    ,382,382,382
BEGIN DESCRIPTION:
Knudson Branch 1405
END DESCRIPTION:
XS GIS Cut Line= 4
      2727983.88       6872796.6      2727769.25      6872651.15
      2727476.95      6872686.73        2726916.      6872761.91
#Sta/Elev= 30
  4444.8  415.86  4447.1  415.23    4498  416.77    4519  416.43  4533.9  417.68
  4574.2  416.24  4656.7  410.37  4677.7  409.49  4692.7  410.84  4717.4  409.69
  4727.5  409.04  4737.6  407.11  4748.5  407.17  4804.8  403.19  4825.1  402.49
  4969.3  402.68  4988.4  399.04  4993.5  400.46  4996.5  398.68  5001.5  398.68
  5006.1  394.44  5007.2  393.94  5013.1  394.44  5019.7  402.46    5060  401.54
  5219.2  402.22  5295.6  404.43  5463.6  411.84  5483.8  413.42  5564.5  414.37
#Mann= 6 ,-1 , 0
  4444.8     .12       0  4574.2     .05       0  4804.8      .1       0
  5006.1     .07       0  5013.1      .1       0  5219.2     .12       0
Bank Sta=5006.1,5013.1
XS Rating Curve= 0 ,0
Exp/Cntr=0.3,0.1

Type RM Length L Ch R = 1 ,7072    ,386,386,386
BEGIN DESCRIPTION:
Knudson Branch 1404
END DESCRIPTION:
XS GIS Cut Line= 3
      2727904.81      6872088.94      2727581.19      6872372.26
      2726882.12      6872516.94
#Sta/Elev= 30
  4562.9  416.21  4740.7  414.67    4867  406.96  4882.1  403.25  4910.6  405.33
  4974.2  402.05    4993  399.76    5009  394.05  5010.1  393.55  5016.1  394.05
  5018.7  401.14  5032.3  400.91  5057.7  394.96  5062.8  395.16  5069.8  401.43
    5080  401.25  5090.2  399.74  5100.4  394.53  5120.9  401.77  5172.4  401.27
  5200.3  400.04  5208.3   396.3  5213.4  397.81    5223  396.56  5233.2  400.68
  5301.9  402.17  5358.9  404.28  5454.2  411.75  5522.2  413.89  5706.9   414.5
#Mann= 9 ,-1 , 0
  4562.9     .12       0    4867     .05       0    5009     .03       0
  5016.1     .05       0  5032.3      .1       0  5172.4     .12       0
  5200.3      .1       0  5301.9     .12       0  5522.2     .05       0
#XS Ineff= 2 , 0
       0    4906     410               0
Permanent Ineff=
       F       F
Bank Sta=5009,5016.1
XS Rating Curve= 0 ,0
Exp/Cntr=0.3,0.1

Type RM Length L Ch R = 1 ,6686    ,417,417,417
BEGIN DESCRIPTION:
Knudson Branch 1402
END DESCRIPTION:
XS GIS Cut Line= 3
      2727845.57      6871988.79        2727307.      6872235.95
      2726849.67      6872458.31
#Sta/Elev= 30
  4403.5  416.39  4494.6  416.19  4614.3  407.88  4678.1  403.46    4707  404.19
  4744.1  401.51    4802  401.68  4964.2  401.39    4971  400.83  4976.5  399.01
  4982.6  393.05  4983.7  392.55  4989.8  393.05  4996.1  393.17  4999.5  398.19
  5022.5  401.26  5089.7  401.31  5106.7  398.19  5119.5  397.95    5131  402.34
  5133.9  404.13  5141.7  408.52  5151.8  409.33    5225  410.47  5275.7  412.98
  5320.8  413.57  5354.1  412.82    5428  412.66  5502.9  414.61  5504.6  414.81
#Mann= 10 ,-1 , 0
  4403.5     .12       0  4614.3     .05       0    4802      .1       0
  4982.6     .07       0  4989.8      .1       0  5022.5     .12       0
    5131      .1       0  5133.9     .12       0  5354.1     .05       0
  5502.9     .12       0
Bank Sta=4982.6,4989.8
XS Rating Curve= 0 ,0
Exp/Cntr=0.3,0.1

Type RM Length L Ch R = 1 ,6269    ,868,868,868
BEGIN DESCRIPTION:
Knudson Branch 1403
END DESCRIPTION:
XS GIS Cut Line= 3
      2727566.45      6871499.08      2727133.39      6871940.94
      2726717.94      6872383.23
#Sta/Elev= 30
  4397.4  412.48  4575.9  413.19    4590  408.94    4597  408.13  4632.4  409.61
  4653.6  406.94  4667.7  407.52    4786  400.12  4809.2  398.92  4929.5  400.68
  4957.8  400.31    4963  399.38  5016.1  399.43  5021.3  396.45  5031.9  392.61
    5033  392.11  5039.1  392.61  5042.8  392.72  5049.6   400.1    5078  400.64
  5092.1  401.85    5099  403.68  5219.6  409.03  5290.4  411.06  5297.3  410.26
  5304.3  410.93  5353.9  409.99  5374.9  408.79  5516.6  414.78  5622.9  414.66
#Mann= 5 ,-1 , 0
  4397.4     .05       0    4786      .1       0    4963     .12       0
  5031.9     .07       0  5039.1     .12       0
Bank Sta=5031.9,5039.1
XS Rating Curve= 0 ,0
Exp/Cntr=0.3,0.1

Type RM Length L Ch R = 1 ,5401    ,586,586,586
BEGIN DESCRIPTION:
Knudson Branch 1401
END DESCRIPTION:
XS GIS Cut Line= 3
       2726988.3      6871179.06      2726528.79      6871812.49
        2726343.      6872066.93
#Sta/Elev= 30
  4224.9  411.98  4277.1  409.01  4300.3  408.43  4449.7  398.91  4486.7  399.01
  4528.4  397.85  4543.1  398.73  4649.8     398  4742.1  398.37  4794.4  398.38
  4807.9   397.7  4821.4  396.04  4836.1  395.71    4861  396.73  4870.9  396.66
  4957.5  397.15    4966  396.63  4968.5  392.68  4969.6  392.18  4975.8  392.68
  4980.7  393.07  4986.9  398.38  5001.6   401.4  5005.6  407.23  5051.8  408.54
  5073.3  408.43  5129.4  410.59  5229.4  411.06  5288.1  412.37  5322.5  411.87
#Mann= 7 ,-1 , 0
  4224.9     .05       0  4742.1     .12       0    4861      .1       0
  4870.9     .12       0  4968.5     .07       0  4975.8     .12       0
  5073.3     .05       0
Bank Sta=4968.5,4975.8
XS Rating Curve= 0 ,0
Exp/Cntr=0.3,0.1

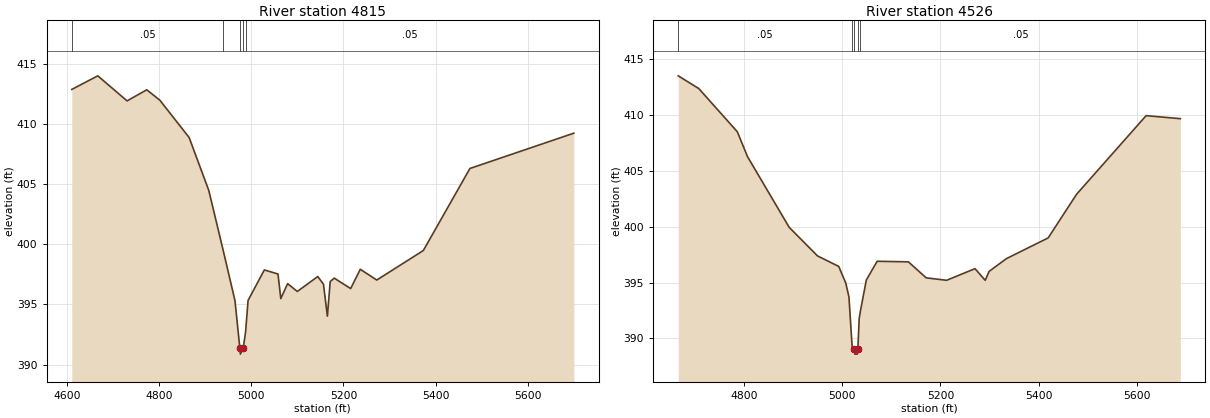
Type RM Length L Ch R = 1 ,4815    ,289,289,289
BEGIN DESCRIPTION:
Knudson Branch 1400
END DESCRIPTION:
XS GIS Cut Line= 3
      2726807.77      6870992.95      2726536.43      6871298.33
      2726144.76      6871855.41
#Sta/Elev= 30
  4610.5  412.85    4667  413.98  4730.5   411.9  4773.2  412.82  4801.6  411.96
  4865.2  408.86  4907.8  404.47  4939.4  399.44  4964.7  395.31  4975.2  391.38
  4976.3  390.88  4982.6  391.38  4987.7  392.73  4993.1  395.34  5028.4  397.87
    5058  397.53  5064.1  395.49  5078.9  396.73  5099.9  396.08  5144.3  397.32
  5156.7  396.68  5165.2  394.03  5171.3   396.9    5180  397.19  5215.7  396.32
  5236.6  397.92  5272.4  397.03  5373.4  399.48  5474.5  406.29    5700  409.22
#Mann= 5 ,-1 , 0
  4610.5     .05       0  4939.4      .1       0  4975.2     .04       0
  4982.6      .1       0  4987.7     .05       0
Bank Sta=4975.2,4982.6
XS Rating Curve= 0 ,0
Exp/Cntr=0.3,0.1

Type RM Length L Ch R = 1 ,4526    ,569,569,569
BEGIN DESCRIPTION:
Knudson Branch 1397
END DESCRIPTION:
XS GIS Cut Line= 3
       2726558.4      6870924.75      2726349.75      6871184.86
      2725923.19      6871725.62
#Sta/Elev= 30
  4666.2  413.48  4708.1  412.34  4786.5  408.48  4807.3  406.25  4892.2  399.93
  4949.8  397.38    4993  396.44  5007.4  394.94  5013.8   393.7  5019.3  389.91
  5020.2  389.29  5024.6   389.1  5025.7   388.6  5030.8   388.6    5032   389.1
  5034.6  391.78  5036.9   392.4  5049.1  395.22  5071.2   396.9  5134.8  396.85
    5171  395.42  5212.6   395.2  5270.4  396.24  5291.2   395.2  5299.2     396
  5334.5  397.14  5419.4  398.99  5477.2  402.89  5618.8  409.92  5688.4  409.65
#Mann= 5 ,-1 , 0
  4666.2     .05       0  5019.3      .1       0  5024.6     .04       0
    5032      .1       0  5036.9     .05       0
Bank Sta=5024.6,5032
XS Rating Curve= 0 ,0
Exp/Cntr=0.3,0.1