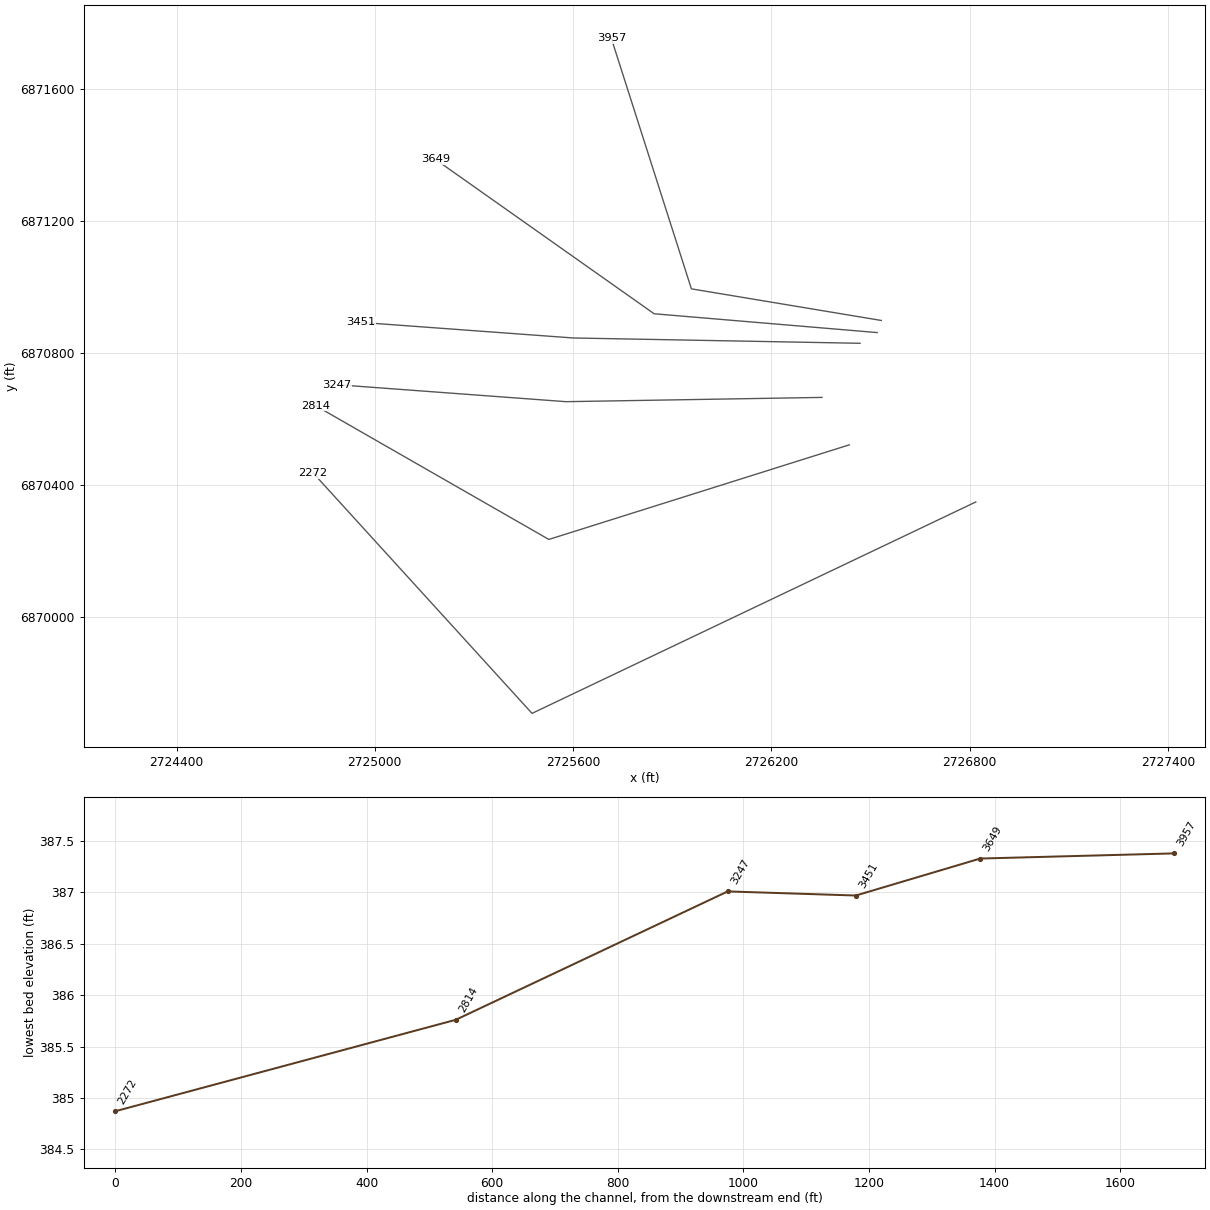
HEC-RAS study Knudson Branch.prj: Knudson Branch Base Level Engineering

--- Knudson Branch.g01 (geometry) --- (continued)

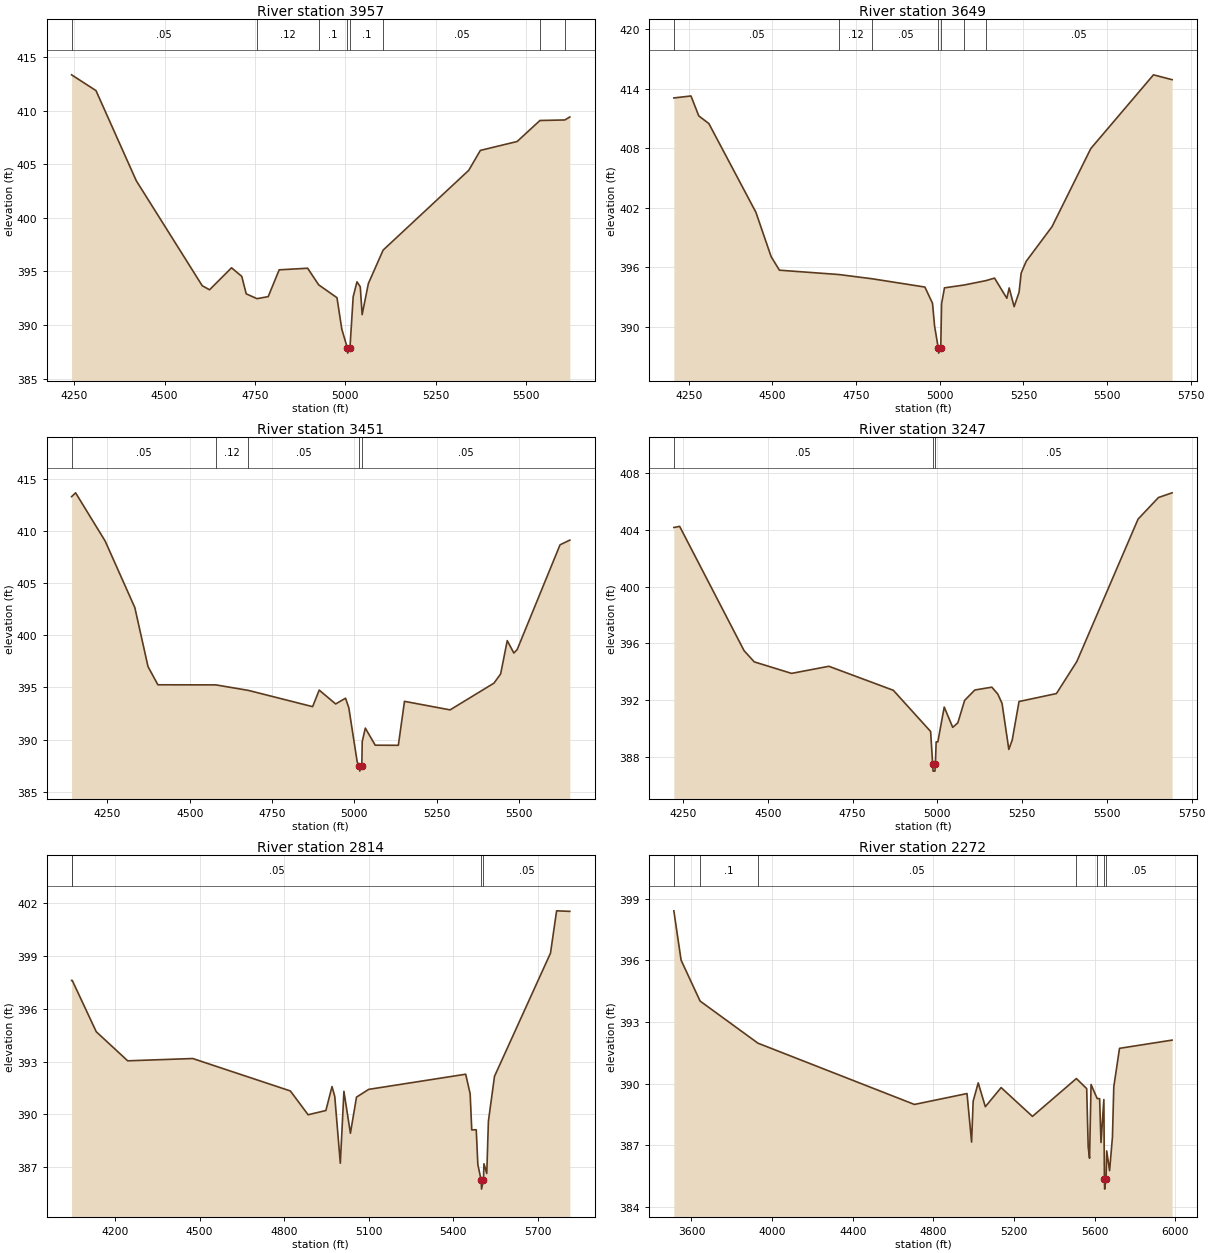
Type RM Length L Ch R = 1 ,3957    ,308,308,308
BEGIN DESCRIPTION:
Knudson Branch 1398
END DESCRIPTION:
XS GIS Cut Line= 3
      2726532.54      6870898.21      2725957.95      6870993.85
      2725715.67      6871751.88
#Sta/Elev= 30
  4242.9  413.34  4310.4  411.87  4421.9  403.46  4604.3  393.67  4624.6  393.29
  4685.4  395.34  4713.7  394.54    4726  392.91  4755.9  392.46  4786.8  392.65
  4817.2  395.15  4895.9   395.3  4926.5  393.75  4977.1  392.55  4990.4  389.62
  5005.6  387.88  5006.7  387.38    5013  387.88  5021.9  392.64  5032.4  394.03
  5041.5  393.57  5046.7  390.97  5063.9  393.87  5104.7  396.99  5341.5  404.43
  5373.7  406.29  5475.4  407.12  5538.5  409.08  5607.4  409.13  5621.2  409.41
#Mann= 8 ,-1 , 0
  4242.9     .05       0  4755.9     .12       0  4926.5      .1       0
  5005.6     .07       0    5013      .1       0  5104.7     .05       0
  5538.5     .12       0  5607.4      .1       0
Bank Sta=5005.6,5013
XS Rating Curve= 0 ,0
Exp/Cntr=0.3,0.1

Type RM Length L Ch R = 1 ,3649    ,198,198,198
BEGIN DESCRIPTION:
Knudson Branch 1399
END DESCRIPTION:
XS GIS Cut Line= 3
      2726520.22      6870861.54      2725845.23      6870918.48
      2725182.73       6871386.1
#Sta/Elev= 30
  4205.8  413.05    4257  413.25  4280.3  411.24  4310.4  410.47  4450.9  401.53
  4496.4  397.06  4521.1  395.69  4699.4  395.25  4798.9  394.82  4955.7  393.99
  4978.5  392.35  4984.6  390.07  4995.7  387.83  4996.8  387.33  5003.1  387.83
  5005.5   392.3  5014.2  393.91    5072  394.19  5138.3  394.64  5163.8  394.89
  5200.5  392.86  5207.5   393.9  5222.3  392.01  5237.1  393.48  5243.2  395.39
    5258  396.57  5335.5  400.08  5451.3  407.95  5638.5  415.38  5694.1  414.89
#Mann= 7 ,-1 , 0
  4205.8     .05       0  4699.4     .12       0  4798.9     .05       0
  4995.7     .04       0  5003.1     .05       0    5072      .1       0
  5138.3     .05       0
Bank Sta=4995.7,5003.1
XS Rating Curve= 0 ,0
Exp/Cntr=0.3,0.1

Type RM Length L Ch R = 1 ,3451    ,204,204,204
BEGIN DESCRIPTION:
Knudson Branch 1396
END DESCRIPTION:
XS GIS Cut Line= 3
       2726468.2      6870829.15      2725600.37      6870845.22
      2724956.38      6870892.51
#Sta/Elev= 30
  4141.1  413.32  4153.3  413.69  4243.3  409.05  4333.3  402.67  4373.3  397.01
  4403.3  395.26  4579.4  395.25  4678.5  394.72  4873.4  393.16  4893.4  394.75
  4943.4  393.42  4973.4  393.97  4983.4  393.05  5008.8  387.86  5015.4  387.47
  5016.6  386.97  5022.8  387.47  5024.1  389.81  5033.5   391.1  5063.6  389.46
  5133.8  389.45  5152.5  393.67    5291  392.85  5424.4  395.42  5444.6   396.3
  5464.7   399.5  5484.7  398.31  5494.8  398.64  5625.1   408.7  5654.8  409.15
#Mann= 5 ,-1 , 0
  4141.1     .05       0  4579.4     .12       0  4678.5     .05       0
  5015.4     .04       0  5022.8     .05       0
Bank Sta=5015.4,5022.8
XS Rating Curve= 0 ,0
Exp/Cntr=0.3,0.1

Type RM Length L Ch R = 1 ,3247    ,433,433,433
BEGIN DESCRIPTION:
Knudson Branch 1393
END DESCRIPTION:
XS GIS Cut Line= 3
      2726353.12       6870665.4      2725578.46      6870652.48
      2724885.93      6870703.84
#Sta/Elev= 30
  4223.1  404.16  4240.2  404.24  4430.2  395.49  4460.3   394.7  4570.3  393.89
  4680.3  394.39  4870.3   392.7  4980.3   389.8  4986.3  387.51  4987.5  387.01
  4993.1  387.01  4994.3  387.51  4996.6  389.07  5001.6  389.07  5020.4  391.52
  5045.5  390.09  5060.5  390.41  5080.6  391.99  5110.6  392.72  5160.8  392.92
  5178.2  392.44  5190.9  391.78  5210.9  388.54  5220.9   389.2    5241  391.91
  5351.3  392.47  5411.5  394.73    5592  404.75  5652.1  406.27  5692.3   406.6
#Mann= 3 ,-1 , 0
  4223.1     .05       0  4986.3     .04       0  4994.3     .05       0
Bank Sta=4986.3,4994.3
XS Rating Curve= 0 ,0
Exp/Cntr=0.3,0.1

Type RM Length L Ch R = 1 ,2814    ,542,542,542
BEGIN DESCRIPTION:
Knudson Branch 1394
END DESCRIPTION:
XS GIS Cut Line= 3
      2726435.71      6870521.86      2725526.56      6870235.64
      2724821.41      6870639.99
#Sta/Elev= 30
  4046.6   397.6    4049   397.6  4134.1  394.69  4245.5  393.04  4476.1  393.17
  4822.1  391.33    4885  389.98  4947.9  390.22  4969.7  391.58  4979.4  391.02
  4999.1  387.23  5011.9  391.31  5034.9  388.93  5056.5  390.98  5099.7  391.42
  5443.5  392.28  5459.3  391.17    5465  389.12  5480.9  389.13  5486.6  387.15
  5498.4  386.26  5499.6  385.76  5506.4  386.26  5508.2   387.2  5518.2  386.65
    5524  389.61  5545.6  392.16  5744.1  399.15  5765.7  401.55  5812.6  401.52
#Mann= 4 ,-1 , 0
  4046.6     .12       0    4049     .05       0  5498.4     .04       0
  5506.4     .05       0
Bank Sta=5498.4,5506.4
XS Rating Curve= 0 ,0
Exp/Cntr=0.3,0.1

Type RM Length L Ch R = 1 ,2272    ,0,0,0
BEGIN DESCRIPTION:
Knudson Branch 1395
END DESCRIPTION:
XS GIS Cut Line= 3
      2726818.46        6870349.      2725475.75      6869709.33
      2724813.49      6870436.57
#Sta/Elev= 30
  3512.7  398.41  3548.7  396.01  3642.9  394.02  3929.9  391.97  4705.8  388.99
  4966.6  389.52  4989.3  387.16  4997.1  389.15  5022.2  390.04  5057.4  388.88
  5135.7  389.81  5291.1  388.41    5509  390.25  5560.1  389.76  5567.5  386.93
  5574.3  386.37  5581.7  389.96    5612  389.28  5624.2  389.27    5631  387.14
  5645.2  389.23    5648  385.37  5649.2  384.87    5656  385.37  5659.4  386.73
  5673.6  385.77  5687.8   387.4  5694.5  389.85  5722.9  391.72  5983.6  392.12
#Mann= 7 ,-1 , 0
  3512.7     .12       0  3642.9      .1       0  3929.9     .05       0
    5509      .1       0    5612     .05       0    5648     .04       0
    5656     .05       0
Bank Sta=5648,5656
XS Rating Curve= 0 ,0
Exp/Cntr=0.3,0.1

Chan Stop Cuts=-1
Use User Specified Reach Order=0
Composite Channel Slope=5