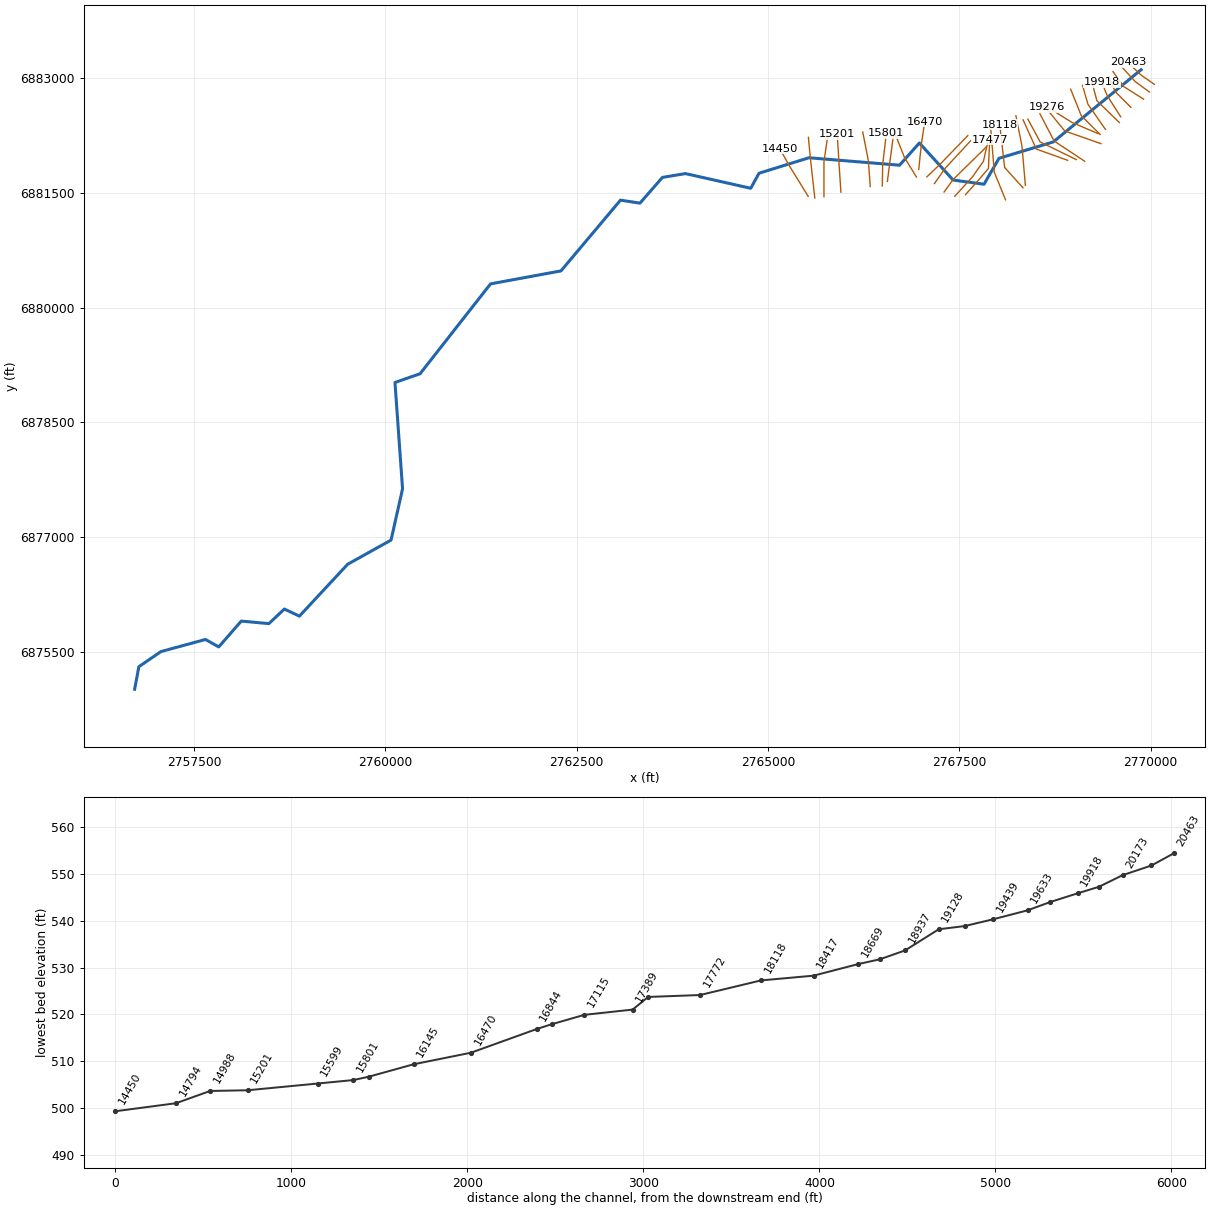
--- Lacy 001.prj (project) ---

Proj Title=Lacy 001 Base Level Engineering
Current Plan=p01
Default Exp/Contr=0.3,0.1
English Units
Geom File=g01
Flow File=f01
Plan File=p01
BEGIN DESCRIPTION:
Lacy 001
END DESCRIPTION:

--- Lacy 001.p01 (plan) ---

Plan Title=Multiple Run
Short Identifier=Multiple
Geom File=g01
Flow File=f01
Subcritical Flow
K Sum by GR= 0
Std Step Tol= 0.01
Critical Tol= 0.01
Num of Std Step Trials= 20
Max Error Tol= 0.3
Flow Tol Ratio= 0.001
Split Flow NTrial= 30
Split Flow Tol= 0.02
Split Flow Ratio= 0.02
Log Output Level= 0
Friction Slope Method= 1
Unsteady Friction Slope Method= 2
Unsteady Bridges Friction Slope Method= 1
Parabolic Critical Depth
Global Vel Dist=  1 , 1 , 1
Global Log Level= 0
CheckData=True
Encroach Param= -1, 0, 0, 0
BEGIN DESCRIPTION:
Multiple Run
END DESCRIPTION:

--- Lacy 001.f01 (steady flow) ---

Flow Title=Multiple
Number of Profiles=7
Profile Names=10-year,25-year,50-year,1pct_min,100-year,1pct_plu,500-year
River Rch & RM= Lacy 001,Reach-1,20463
     171     214     247     142     284     566     374
River Rch & RM= Lacy 001,Reach-1,18669
     343     448     532     315     629    1254     878
River Rch & RM= Lacy 001,Reach-1,15889
     467     621     745     445     889    1773    1265
River Rch & RM= Lacy 001,Reach-1,14099
     621     836    1012     609    1215    2424    1753
River Rch & RM= Lacy 001,Reach-1,9693
     816    1113    1358     823    1642    3276    2405
River Rch & RM= Lacy 001,Reach-1,7681
     804    1094    1332     806    1608    3208    2346
River Rch & RM= Lacy 001,Reach-1,4895
     952    1302    1591     964    1924    3839    2820
River Rch & RM= Lacy 001,Reach-1,2281
    1069    1470    1803    1096    2188    4365    3228
Boundary for River Rch & Prof#=Lacy 001,Reach-1,1
Up Type=0
Dn Type=3
Dn Slope=0.005
Boundary for River Rch & Prof#=Lacy 001,Reach-1,2
Up Type=0
Dn Type=3
Dn Slope=0.005
Boundary for River Rch & Prof#=Lacy 001,Reach-1,3
Up Type=0
Dn Type=3
Dn Slope=0.005
Boundary for River Rch & Prof#=Lacy 001,Reach-1,4
Up Type=0
Dn Type=3
Dn Slope=0.005
Boundary for River Rch & Prof#=Lacy 001,Reach-1,5
Up Type=0
Dn Type=3
Dn Slope=0.005
Boundary for River Rch & Prof#=Lacy 001,Reach-1,6
Up Type=0
Dn Type=3
Dn Slope=0.005
Boundary for River Rch & Prof#=Lacy 001,Reach-1,7
Up Type=0
Dn Type=3
Dn Slope=0.005

--- Lacy 001.g01 (geometry) ---

Geom Title=Existing Conditions

River Reach=Lacy 001,Reach-1
Reach XY= 30
      2769876.00      6883111.00      2768728.43      6882166.52
      2768019.45      6881953.25      2767824.35      6881614.11
      2767419.81      6881668.75      2766979.22      6882153.17
      2766720.12      6881862.60      2765536.48      6881960.06
      2764884.17      6881757.67      2764776.00      6881561.00
      2763922.70      6881752.92      2763622.31      6881703.30
      2763328.38      6881366.68      2763073.62      6881405.63
      2762296.20      6880480.61      2761376.00      6880311.00
      2760455.11      6879135.95      2760127.30      6879021.77
      2760226.47      6877631.45      2760076.00      6876961.00
      2759508.92      6876644.85      2758878.42      6875966.41
      2758682.43      6876059.58      2758479.42      6875868.79
      2758118.94      6875901.99      2757824.65      6875564.34
      2757651.00      6875661.64      2757069.50      6875503.27
      2756781.18      6875305.62      2756726.00      6875011.00

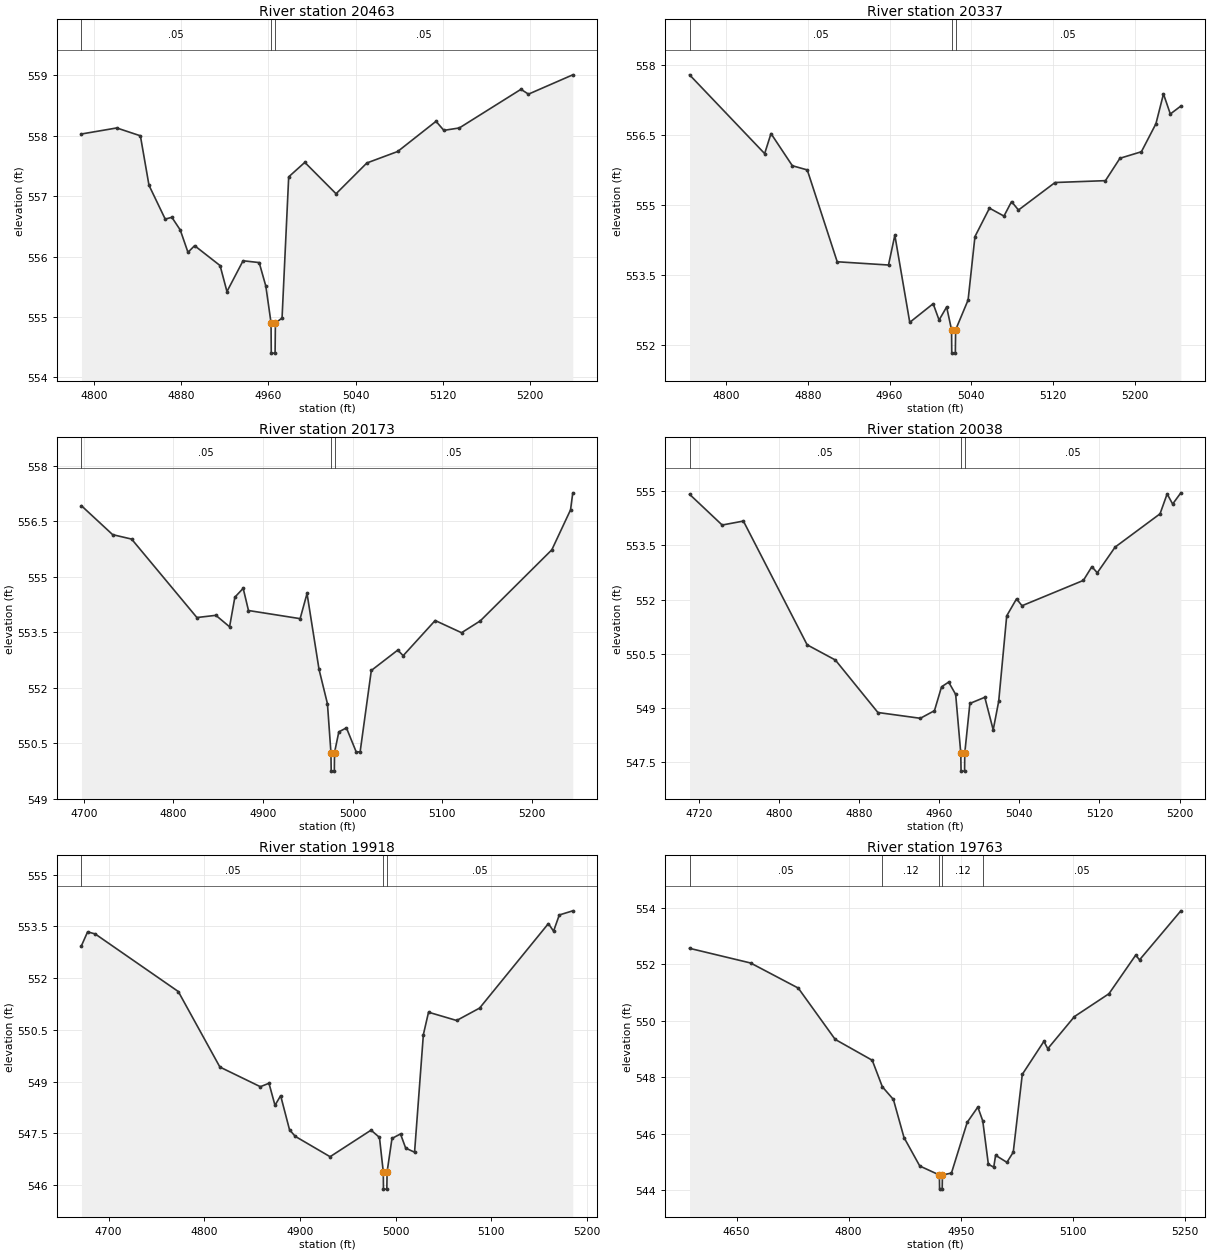
Type RM Length L Ch R = 1,20463,126,126,126
BEGIN DESCRIPTION:
Lacy 001 3449
END DESCRIPTION:
XS GIS Cut Line= 3
      2770050.40      6882919.47      2769876.78      6883040.60
      2769703.28      6883205.71
#Sta/Elev= 30
  4788.3  558.03  4820.7  558.13  4842.4  558.00  4850.3  557.18  4865.2  556.62
  4871.3  556.65  4879.0  556.44  4886.1  556.07  4892.2  556.18  4915.6  555.85
  4921.9  555.42  4936.7  555.93  4951.5  555.90  4957.6  555.51  4962.4  554.90
  4962.6  554.40  4966.1  554.40  4966.4  554.90  4972.5  554.98  4978.6  557.32
  4993.4  557.56  5022.1  557.04  5050.4  557.55  5078.7  557.74  5113.9  558.24
  5121.1  558.09  5135.3  558.13  5191.9  558.77  5198.8  558.69  5239.5  559.01
#Mann=3,-1,0
  4788.3    0.05       0  4962.4    0.05       0  4966.4    0.05       0
Bank Sta=4962.4,4966.4
Exp/Cntr=0.3,0.1

Type RM Length L Ch R = 1,20337,164,164,164
BEGIN DESCRIPTION:
Lacy 001 3450
END DESCRIPTION:
XS GIS Cut Line= 3
      2769985.72      6882819.18      2769797.44      6882957.39
      2769631.13      6883140.33
#Sta/Elev= 30
  4764.3  557.79  4837.8  556.10  4844.0  556.53  4864.9  555.84  4879.5  555.75
  4908.8  553.78  4959.0  553.71  4965.2  554.35  4979.8  552.48  5002.7  552.88
  5008.5  552.53  5015.9  552.81  5020.7  552.32  5020.9  551.82  5024.4  551.82
  5024.7  552.32  5036.9  552.96  5043.6  554.32  5057.8  554.93  5072.0  554.76
  5079.4  555.07  5086.2  554.89  5122.0  555.48  5171.3  555.52  5185.5  556.00
  5206.5  556.14  5220.7  556.74  5228.1  557.38  5234.8  556.95  5245.1  557.12
#Mann=3,-1,0
  4764.3    0.05       0  5020.7    0.05       0  5024.7    0.05       0
Bank Sta=5020.7,5024.7
Exp/Cntr=0.3,0.1

Type RM Length L Ch R = 1,20173,135,135,135
BEGIN DESCRIPTION:
Lacy 001 3448
END DESCRIPTION:
XS GIS Cut Line= 3
      2769908.83      6882726.33      2769648.31      6882891.35
      2769508.75      6883086.99
#Sta/Elev= 30
  4697.3  556.92  4732.1  556.14  4753.3  556.02  4826.2  553.90  4847.4  553.96
  4862.7  553.65  4868.6  554.45  4877.9  554.69  4883.8  554.09  4941.5  553.87
  4949.2  554.55  4962.6  552.50  4972.0  551.57  4975.9  550.25  4976.2  549.75
  4979.7  549.75  4979.9  550.25  4984.7  550.81  4993.2  550.92  5004.1  550.27
  5008.5  550.27  5021.0  552.47  5050.5  553.02  5056.6  552.87  5092.3  553.82
  5121.8  553.49  5142.7  553.81  5222.6  555.73  5243.5  556.81  5246.0  557.27
#Mann=3,-1,0
  4697.3    0.05       0  4975.9    0.04       0  4979.9    0.05       0
Bank Sta=4975.9,4979.9
Exp/Cntr=0.3,0.1

Type RM Length L Ch R = 1,20038,120,120,120
BEGIN DESCRIPTION:
Lacy 001 3447
END DESCRIPTION:
XS GIS Cut Line= 3
      2769741.97      6882620.87      2769538.84      6882823.70
      2769456.10      6883010.00
#Sta/Elev= 30
  4710.4  554.91  4743.0  554.06  4764.2  554.17  4827.9  550.75  4856.1  550.33
  4898.6  548.88  4941.0  548.72  4955.1  548.93  4962.2  549.59  4969.3  549.72
  4976.3  549.38  4981.4  547.76  4981.7  547.26  4985.2  547.26  4985.4  547.76
  4990.5  549.13  5005.4  549.30  5013.8  548.40  5019.3  549.19  5027.3  551.55
  5037.1  552.02  5042.6  551.83  5103.9  552.53  5112.4  552.91  5117.8  552.74
  5135.6  553.45  5180.5  554.37  5187.6  554.92  5193.1  554.64  5201.3  554.95
#Mann=3,-1,0
  4710.4    0.05       0  4981.4    0.05       0  4985.4    0.05       0
Bank Sta=4981.4,4985.4
Exp/Cntr=0.3,0.1

Type RM Length L Ch R = 1,19918,155,155,155
BEGIN DESCRIPTION:
Lacy 001 3445
END DESCRIPTION:
XS GIS Cut Line= 3
      2769609.68      6882495.56      2769433.36      6882773.03
      2769363.11      6882944.01
#Sta/Elev= 30
  4671.7  552.94  4678.1  553.34  4686.0  553.28  4772.9  551.61  4816.4  549.42
  4858.7  548.85  4867.7  548.95  4874.0  548.31  4879.9  548.59  4889.2  547.60
  4895.2  547.41  4931.6  546.82  4974.4  547.59  4983.2  547.38  4987.2  546.38
  4987.4  545.88  4990.9  545.88  4991.2  546.38  4996.3  547.35  5005.2  547.48
  5010.6  547.07  5019.9  546.95  5029.1  550.36  5034.5  551.01  5063.9  550.77
  5087.9  551.13  5159.8  553.58  5165.2  553.36  5171.2  553.83  5185.3  553.95
#Mann=3,-1,0
  4671.7    0.05       0  4987.2    0.05       0  4991.2    0.05       0
Bank Sta=4987.2,4991.2
Exp/Cntr=0.3,0.1

Type RM Length L Ch R = 1,19763,130,130,130
BEGIN DESCRIPTION:
Lacy 001 3446
END DESCRIPTION:
XS GIS Cut Line= 3
      2769591.72      6882421.06      2769297.43      6882707.32
      2769236.65      6882946.67
#Sta/Elev= 30
  4587.1  552.57  4668.8  552.05  4732.6  551.16  4782.0  549.34  4831.6  548.60
  4845.1  547.66  4859.9  547.21  4874.1  545.86  4895.2  544.85  4921.5  544.53
  4921.7  544.03  4925.2  544.03  4925.5  544.53  4937.6  544.60  4958.7  546.40
  4972.9  546.94  4979.5  546.45  4987.0  544.91  4994.2  544.81  4996.7  545.23
  5011.8  544.98  5020.3  545.34  5032.4  548.10  5061.3  549.27  5066.5  549.01
  5102.2  550.15  5148.4  550.96  5184.2  552.33  5189.3  552.16  5244.6  553.90
#Mann=5,-1,0
  4587.1    0.05       0  4845.1    0.12       0  4921.5    0.04       0
  4925.5    0.12       0  4979.5    0.05       0
Bank Sta=4921.5,4925.5
Exp/Cntr=0.3,0.1

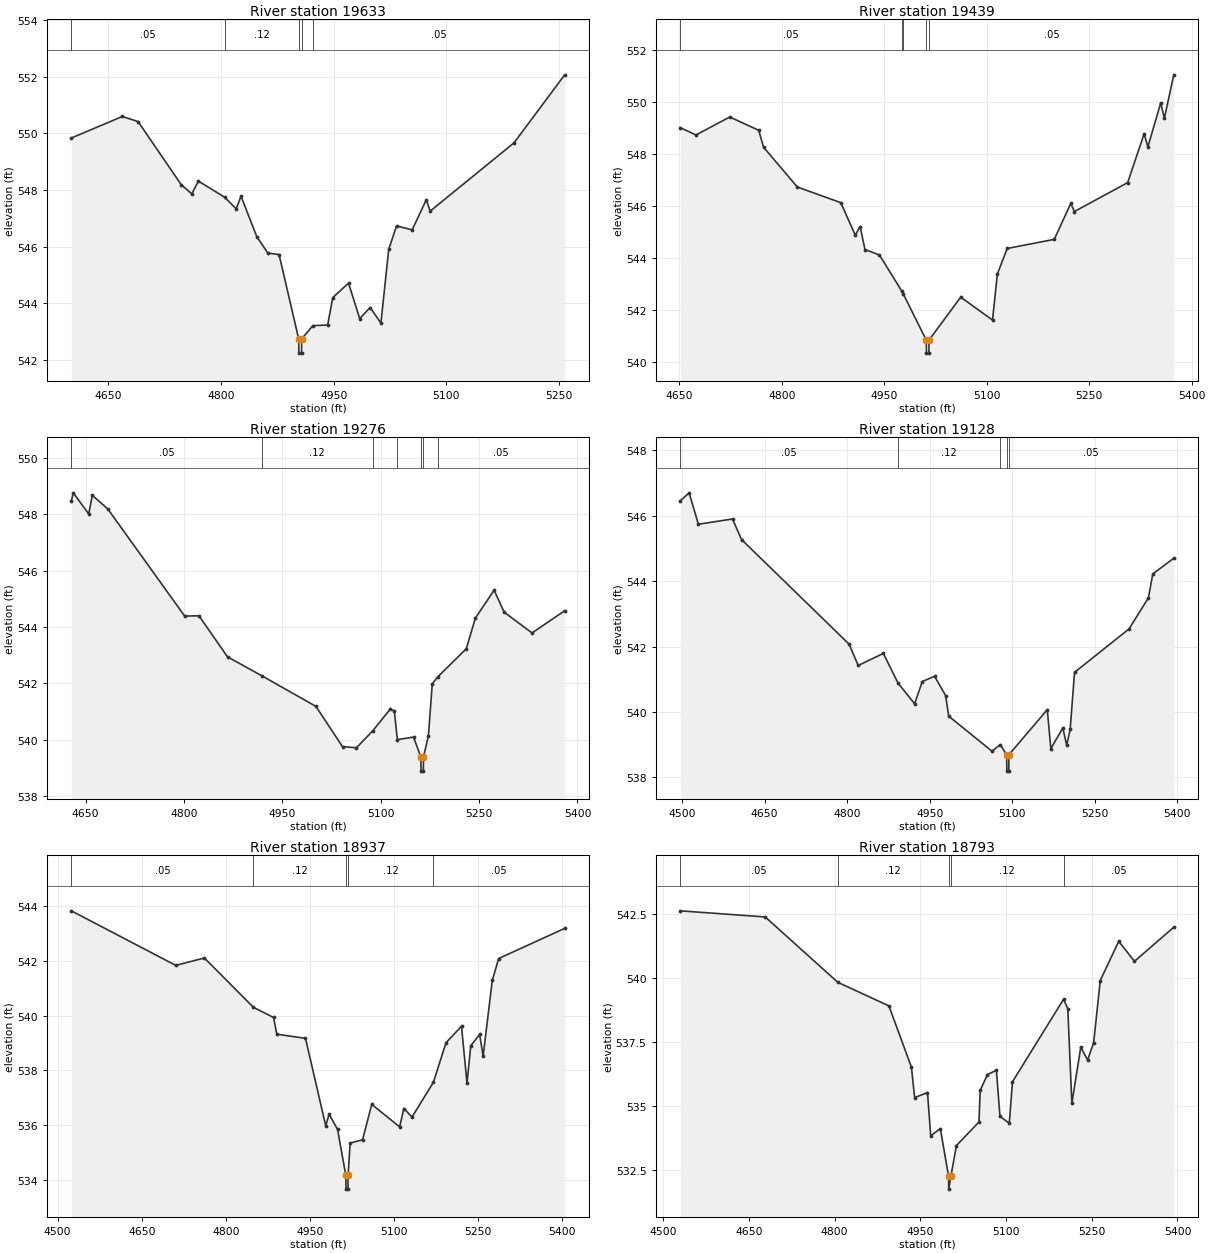
Type RM Length L Ch R = 1,19633,194,194,194
BEGIN DESCRIPTION:
Lacy 001 3444
END DESCRIPTION:
XS GIS Cut Line= 3
      2769410.20      6882330.82      2769181.98      6882659.00
      2769111.05      6882906.19
#Sta/Elev= 30
  4600.7  549.83  4668.6  550.59  4689.6  550.41  4747.1  548.18  4761.1  547.86
  4769.9  548.31  4804.9  547.74  4820.2  547.33  4826.6  547.78  4847.6  546.35
  4862.4  545.77  4877.3  545.72  4903.4  542.74  4903.7  542.24  4907.2  542.24
  4907.4  542.74  4922.2  543.21  4942.0  543.23  4948.8  544.20  4969.8  544.71
  4984.6  543.46  4998.6  543.85  5012.9  543.30  5023.3  545.90  5033.7  546.73
  5054.5  546.59  5073.3  547.65  5078.5  547.25  5190.1  549.66  5257.6  552.06
#Mann=5,-1,0
  4600.7    0.05       0  4804.9    0.12       0  4903.4    0.05       0
  4907.4    0.12       0  4922.2    0.05       0
Bank Sta=4903.4,4907.4
Exp/Cntr=0.3,0.1

Type RM Length L Ch R = 1,19439,163,163,163
BEGIN DESCRIPTION:
Lacy 001 3443
END DESCRIPTION:
XS GIS Cut Line= 3
      2769341.42      6882264.18      2769095.46      6882508.79
      2768955.29      6882857.27
#Sta/Elev= 30
  4651.3  549.00  4674.1  548.72  4723.6  549.41  4766.0  548.90  4773.1  548.25
  4822.6  546.72  4886.2  546.12  4907.4  544.87  4914.5  545.20  4921.6  544.32
  4942.8  544.11  4975.6  542.72  4977.4  542.63  5011.4  540.84  5011.7  540.34
  5015.2  540.34  5015.4  540.84  5061.8  542.49  5108.4  541.61  5115.5  543.38
  5129.9  544.36  5198.8  544.71  5223.0  546.09  5228.4  545.78  5306.3  546.89
  5330.5  548.77  5335.9  548.26  5354.7  549.95  5360.1  549.36  5373.8  551.03
#Mann=5,-1,0
  4651.3    0.05       0  4975.6    0.12       0  4977.4    0.05       0
  5011.4    0.05       0  5015.4    0.05       0
Bank Sta=5011.4,5015.4
Exp/Cntr=0.3,0.1

Type RM Length L Ch R = 1,19276,148,148,148
BEGIN DESCRIPTION:
Lacy 001 3442
END DESCRIPTION:
XS GIS Cut Line= 3
      2769314.72      6882275.22      2768972.14      6882422.61
      2768650.60      6882623.55
#Sta/Elev= 30
  4628.4  548.48  4631.4  548.77  4654.9  548.02  4660.4  548.68  4683.9  548.20
  4801.2  544.39  4823.0  544.40  4866.5  542.94  4918.7  542.27  5001.3  541.18
  5041.8  539.75  5063.0  539.71  5087.8  540.31  5114.7  541.09  5120.8  541.02
  5125.4  540.00  5150.1  540.09  5161.2  539.38  5161.5  538.88  5165.0  538.88
  5165.2  539.38  5172.7  540.13  5178.6  541.98  5187.0  542.23  5230.5  543.23
  5244.4  544.32  5272.9  545.31  5288.2  544.53  5330.7  543.79  5380.5  544.58
#Mann=7,-1,0
  4628.4    0.05       0  4918.7    0.12       0  5087.8    0.05       0
  5125.4    0.12       0  5161.2    0.07       0  5165.2    0.12       0
  5187.0    0.05       0
Bank Sta=5161.2,5165.2
Exp/Cntr=0.3,0.1

Type RM Length L Ch R = 1,19128,191,191,191
BEGIN DESCRIPTION:
Lacy 001 3441
END DESCRIPTION:
XS GIS Cut Line= 3
      2769350.99      6882144.92      2768879.18      6882309.91
      2768628.09      6882617.00
#Sta/Elev= 30
  4497.0  546.46  4512.9  546.70  4529.7  545.74  4591.7  545.90  4608.2  545.27
  4803.7  542.07  4820.1  541.42  4865.8  541.79  4892.6  540.88  4922.6  540.25
  4936.6  540.93  4958.9  541.09  4979.0  540.50  4984.6  539.87  5063.2  538.80
  5078.1  539.00  5089.9  538.69  5090.2  538.19  5093.7  538.19  5093.9  538.69
  5163.7  540.07  5170.2  538.88  5192.0  539.51  5198.9  538.98  5205.3  539.47
  5213.2  541.21  5312.3  542.54  5347.5  543.49  5355.4  544.22  5393.5  544.70
#Mann=5,-1,0
  4497.0    0.05       0  4892.6    0.12       0  5078.1    0.05       0
  5089.9    0.07       0  5093.9    0.05       0
Bank Sta=5089.9,5093.9
Exp/Cntr=0.3,0.1

Type RM Length L Ch R = 1,18937,144,144,144
BEGIN DESCRIPTION:
Lacy 001 3431
END DESCRIPTION:
XS GIS Cut Line= 3
      2769138.58      6881914.55      2768740.30      6882178.32
      2768553.94      6882535.64
#Sta/Elev= 30
  4524.4  543.82  4710.8  541.83  4761.9  542.10  4849.5  540.30  4885.3  539.93
  4891.3  539.32  4942.4  539.17  4978.5  535.98  4984.5  536.40  4999.6  535.85
  5014.4  534.17  5014.7  533.67  5018.2  533.67  5018.4  534.17  5022.1  535.35
  5044.2  535.47  5060.7  536.76  5110.5  535.94  5117.9  536.61  5132.6  536.30
  5170.8  537.57  5193.2  539.01  5220.9  539.61  5230.7  537.53  5237.4  538.90
  5253.3  539.31  5259.5  538.52  5275.8  541.28  5287.2  542.08  5405.1  543.18
#Mann=5,-1,0
  4524.4    0.05       0  4849.5    0.12       0  5014.4    0.07       0
  5018.4    0.12       0  5170.8    0.05       0
Bank Sta=5014.4,5018.4
Exp/Cntr=0.3,0.1

Type RM Length L Ch R = 1,18793,124,124,124
BEGIN DESCRIPTION:
Lacy 001 3432
END DESCRIPTION:
XS GIS Cut Line= 3
      2769029.43      6881936.11      2768557.17      6882166.87
      2768397.22      6882464.26
#Sta/Elev= 30
  4530.2  542.63  4678.7  542.39  4805.7  539.84  4895.1  538.92  4934.5  536.53
  4940.1  535.34  4962.6  535.54  4968.2  533.85  4985.1  534.13  4999.5  532.27
  4999.7  531.77  5003.5  532.27  5013.2  533.47  5052.7  534.39  5054.8  535.62
  5067.5  536.24  5083.2  536.41  5089.4  534.61  5105.7  534.34  5111.3  535.96
  5200.7  539.18  5208.1  538.81  5215.2  535.12  5230.8  537.31  5242.8  536.81
  5253.4  537.49  5264.9  539.91  5297.2  541.44  5324.8  540.66  5393.5  541.99
#Mann=5,-1,0
  4530.2    0.05       0  4805.7    0.12       0  4999.5    0.07       0
  5003.5    0.12       0  5200.7    0.05       0
Bank Sta=4999.5,5003.5
Exp/Cntr=0.3,0.1

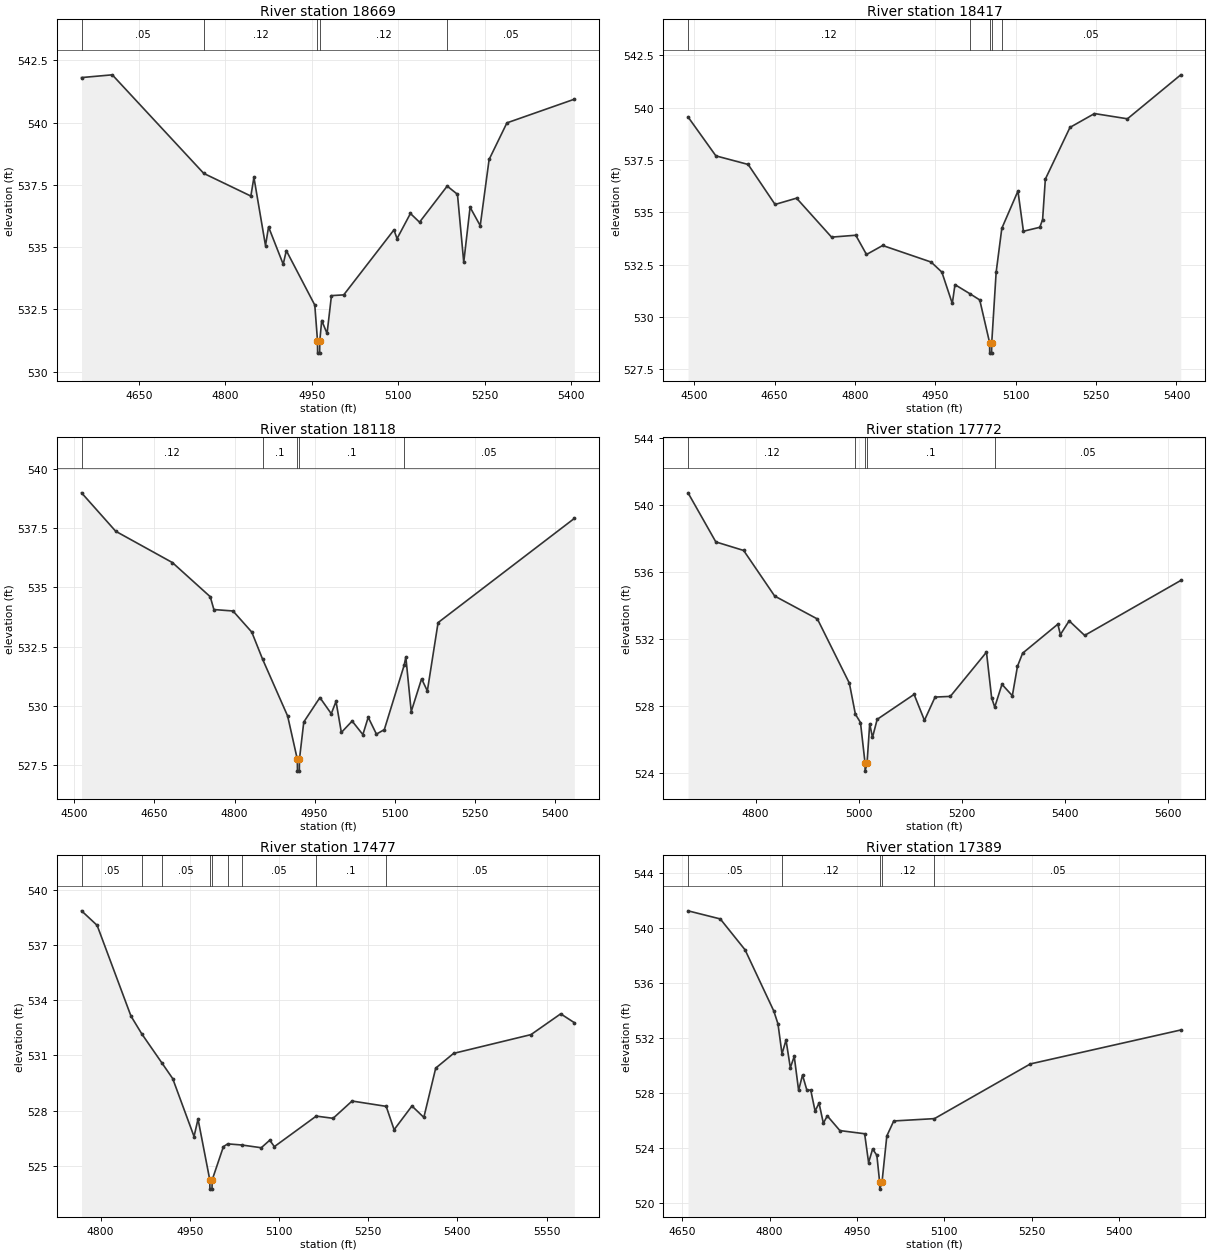
Type RM Length L Ch R = 1,18669,252,252,252
BEGIN DESCRIPTION:
Lacy 001 3430
END DESCRIPTION:
XS GIS Cut Line= 3
      2768916.74      6881926.37      2768506.65      6882073.83
      2768334.34      6882455.77
#Sta/Elev= 30
  4550.3  541.81  4603.6  541.92  4762.3  537.96  4844.0  537.05  4849.3  537.80
  4869.4  535.06  4874.7  535.81  4900.1  534.31  4905.5  534.86  4954.9  532.67
  4959.6  531.24  4959.8  530.74  4963.3  530.74  4963.6  531.24  4966.9  532.05
  4976.2  531.53  4983.8  533.05  5005.1  533.08  5092.2  535.69  5097.6  535.34
  5120.8  536.35  5136.6  536.00  5184.6  537.45  5202.4  537.12  5213.3  534.39
  5224.3  536.60  5241.9  535.86  5257.3  538.52  5288.2  539.99  5405.1  540.94
#Mann=5,-1,0
  4550.3    0.05       0  4762.3    0.12       0  4959.6    0.07       0
  4963.6    0.12       0  5184.6    0.05       0
Bank Sta=4959.6,4963.6
Exp/Cntr=0.3,0.1

Type RM Length L Ch R = 1,18417,299,299,299
BEGIN DESCRIPTION:
Lacy 001 3429
END DESCRIPTION:
XS GIS Cut Line= 3
      2768364.31      6881599.22      2768319.30      6882114.23
      2768240.59      6882508.89
#Sta/Elev= 30
  4488.6  539.56  4540.6  537.70  4600.8  537.29  4651.0  535.38  4691.1  535.68
  4756.4  533.82  4801.6  533.91  4821.6  532.99  4851.8  533.42  4942.1  532.63
  4962.2  532.15  4981.7  530.65  4986.7  531.55  5015.6  531.10  5032.9  530.82
  5051.3  528.78  5051.5  528.28  5055.0  528.28  5055.3  528.78  5063.5  532.14
  5074.1  534.24  5104.2  536.02  5114.4  534.10  5145.0  534.29  5150.2  534.66
  5155.3  536.59  5201.3  539.06  5247.0  539.72  5308.5  539.47  5408.0  541.57
#Mann=5,-1,0
  4488.6    0.12       0  5015.6     0.1       0  5051.3    0.07       0
  5055.3     0.1       0  5074.1    0.05       0
Bank Sta=5051.3,5055.3
Exp/Cntr=0.3,0.1

Type RM Length L Ch R = 1,18118,346,346,346
BEGIN DESCRIPTION:
Lacy 001 3428
END DESCRIPTION:
XS GIS Cut Line= 3
      2768332.83      6881567.29      2768092.95      6881833.28
      2768029.19      6882394.59
#Sta/Elev= 30
  4513.4  538.99  4577.4  537.37  4683.6  536.05  4754.5  534.61  4761.3  534.07
  4797.1  534.01  4832.3  533.12  4852.5  531.98  4899.5  529.58  4917.6  527.76
  4917.9  527.26  4921.4  527.26  4921.6  527.76  4929.7  529.33  4959.9  530.36
  4981.2  529.68  4990.1  530.20  5000.1  528.89  5020.3  529.37  5040.4  528.80
  5050.4  529.53  5065.8  528.82  5080.6  529.01  5117.7  531.72  5120.9  532.07
  5131.0  529.77  5150.4  531.15  5161.2  530.64  5181.3  533.52  5436.5  537.91
#Mann=5,-1,0
  4513.4    0.12       0  4852.5     0.1       0  4917.6    0.07       0
  4921.6     0.1       0  5117.7    0.05       0
Bank Sta=4917.6,4921.6
Exp/Cntr=0.3,0.1

Type RM Length L Ch R = 1,17772,295,295,295
BEGIN DESCRIPTION:
Lacy 001 3427
END DESCRIPTION:
XS GIS Cut Line= 3
      2768104.85      6881411.01      2767958.03      6881771.07
      2767911.83      6882336.94
#Sta/Elev= 30
  4668.8  540.75  4722.8  537.82  4776.8  537.31  4837.0  534.59  4920.0  533.22
  4982.0  529.39  4993.7  527.54  5003.6  527.04  5012.4  524.64  5012.6  524.14
  5016.4  524.64  5021.5  526.97  5026.9  526.15  5036.0  527.23  5107.7  528.72
  5127.8  527.17  5148.4  528.56  5178.0  528.60  5248.2  531.24  5258.2  528.52
  5264.2  527.96  5278.3  529.32  5298.4  528.64  5308.4  530.40  5318.4  531.18
  5386.7  532.91  5391.7  532.29  5408.7  533.11  5438.8  532.24  5625.4  535.52
#Mann=5,-1,0
  4668.8    0.12       0  4993.7     0.1       0  5012.4    0.07       0
  5016.4     0.1       0  5264.2    0.05       0
Bank Sta=5012.4,5016.4
Exp/Cntr=0.3,0.1

Type RM Length L Ch R = 1,17477,88,88,88
BEGIN DESCRIPTION:
Lacy 001 3426
END DESCRIPTION:
XS GIS Cut Line= 4
      2767582.31      6881477.78      2767742.23      6881656.63
      2767881.96      6881821.14      2767897.70      6882193.85
#Sta/Elev= 30
  4767.9  538.86  4794.1  538.07  4851.0  533.14  4869.0  532.18  4903.7  530.56
  4921.2  529.74  4957.1  526.59  4963.8  527.54  4983.6  524.23  4983.8  523.73
  4987.3  523.73  4987.6  524.23  5006.5  526.04  5013.8  526.19  5037.2  526.13
  5070.2  525.98  5084.4  526.39  5092.2  526.04  5162.6  527.70  5191.0  527.58
  5222.9  528.52  5280.3  528.23  5293.6  526.96  5323.6  528.25  5343.6  527.63
  5363.6  530.31  5393.7  531.11  5523.8  532.13  5573.8  533.26  5596.7  532.78
#Mann=9,-1,0
  4767.9    0.05       0  4869.0     0.1       0  4903.7    0.05       0
  4983.6    0.03       0  4987.6    0.05       0  5013.8     0.1       0
  5037.2    0.05       0  5162.6     0.1       0  5280.3    0.05       0
Bank Sta=4983.6,4987.6
Exp/Cntr=0.3,0.1

Type RM Length L Ch R = 1,17389,274,274,274
BEGIN DESCRIPTION:
Lacy 001 3425
END DESCRIPTION:
XS GIS Cut Line= 4
      2767441.92      6881456.95      2767673.40      6881710.35
      2767816.55      6881914.78      2767872.07      6882162.05
#Sta/Elev= 30
  4659.9  541.28  4715.3  540.69  4757.9  538.44  4807.2  533.99  4814.4  533.05
  4821.3  530.87  4828.2  531.88  4835.6  529.86  4842.3  530.69  4849.8  528.22
  4856.5  529.33  4863.9  528.25  4870.7  528.23  4878.1  526.71  4884.9  527.29
  4892.3  525.83  4899.1  526.36  4920.7  525.29  4963.2  525.06  4970.0  522.96
  4976.9  523.95  4984.2  523.49  4989.0  521.53  4989.2  521.03  4993.0  521.53
  5001.3  524.90  5013.2  525.99  5083.1  526.16  5247.8  530.14  5506.1  532.61
#Mann=5,-1,0
  4659.9    0.05       0  4821.3    0.12       0  4989.0    0.07       0
  4993.0    0.12       0  5083.1    0.05       0
Bank Sta=4989,4993
Exp/Cntr=0.3,0.1

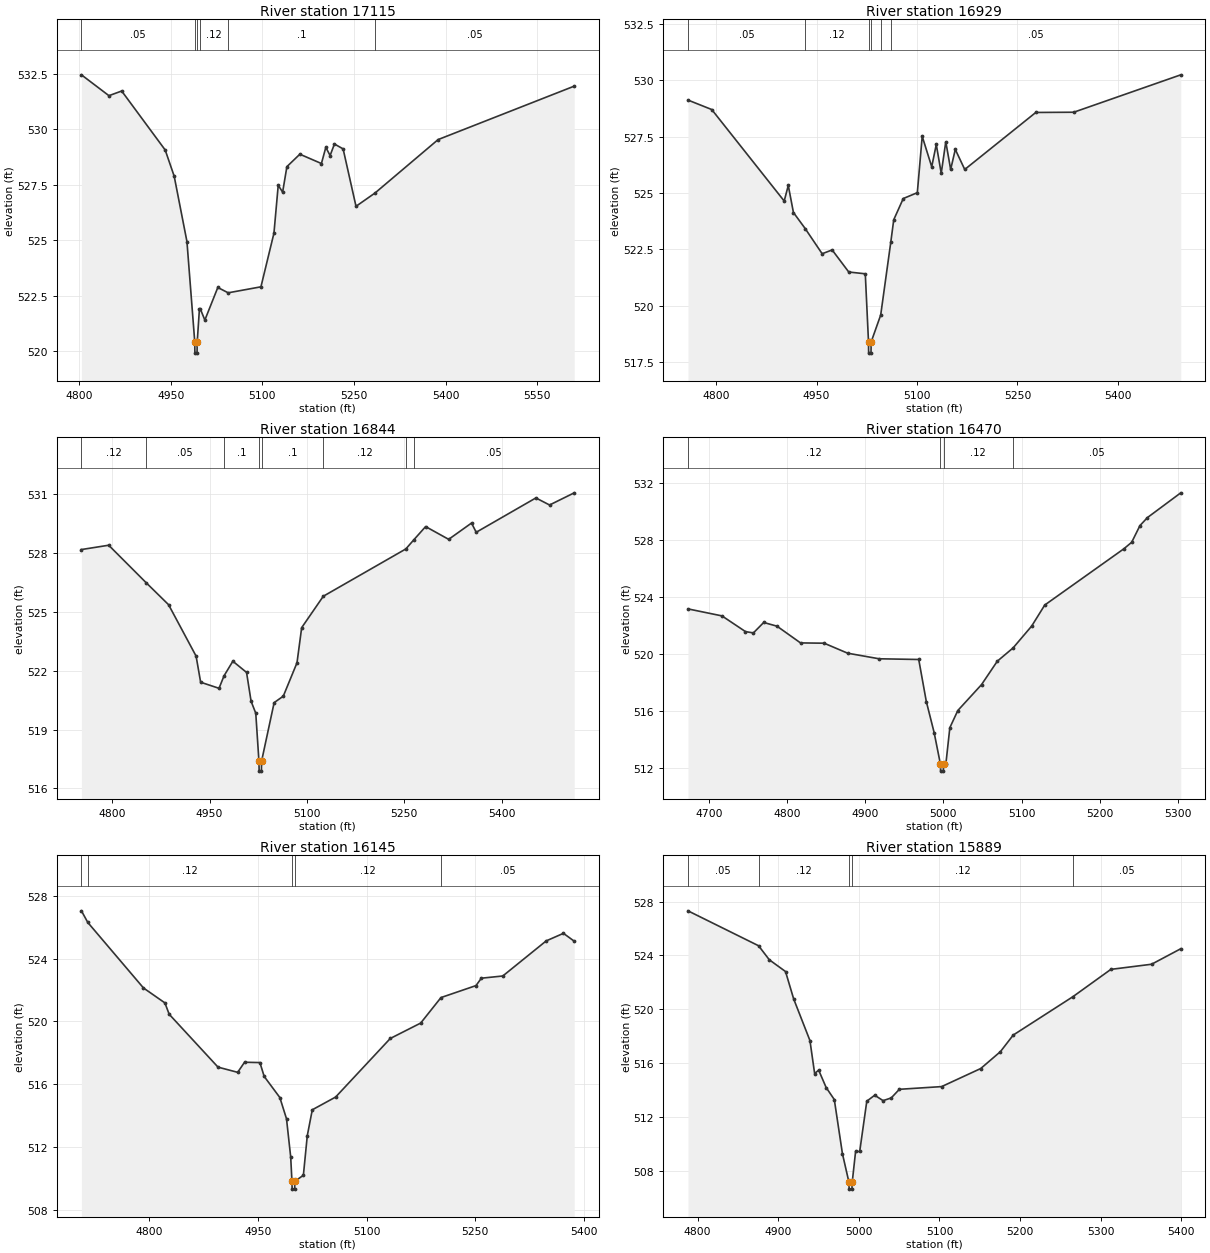
Type RM Length L Ch R = 1,17115,186,186,186
BEGIN DESCRIPTION:
Lacy 001 3424
END DESCRIPTION:
XS GIS Cut Line= 3
      2767302.67      6881512.44      2767417.55      6881672.86
      2767852.04      6882100.00
#Sta/Elev= 30
  4804.0  532.46  4849.0  531.52  4869.9  531.73  4941.1  529.07  4955.8  527.89
  4976.7  524.94  4989.5  520.41  4989.7  519.91  4993.2  519.91  4993.5  520.41
  4997.1  521.89  4998.8  521.89  5006.0  521.40  5027.2  522.87  5044.2  522.63
  5097.8  522.90  5119.1  525.32  5126.1  527.48  5133.3  527.17  5140.3  528.32
  5161.5  528.88  5196.8  528.46  5204.0  529.19  5211.0  528.82  5218.1  529.34
  5232.3  529.12  5253.4  526.53  5284.5  527.13  5387.8  529.54  5610.6  531.95
#Mann=6,-1,0
  4804.0    0.05       0  4989.5    0.07       0  4993.5    0.05       0
  4998.8    0.12       0  5044.2     0.1       0  5284.5    0.05       0
Bank Sta=4989.5,4993.5
Exp/Cntr=0.3,0.1

Type RM Length L Ch R = 1,16929,85,85,85
BEGIN DESCRIPTION:
Lacy 001 3416
END DESCRIPTION:
XS GIS Cut Line= 3
      2767176.14      6881621.85      2767315.40      6881821.44
      2767649.84      6882183.01
#Sta/Elev= 30
  4758.0  529.13  4793.5  528.71  4901.7  524.65  4907.8  525.34  4915.5  524.14
  4933.0  523.43  4958.4  522.31  4973.3  522.48  4998.1  521.50  5022.8  521.42
  5027.6  518.40  5027.8  517.90  5031.3  517.90  5031.6  518.40  5045.8  519.59
  5060.9  522.83  5065.3  523.82  5079.5  524.76  5100.5  525.02  5107.8  527.52
  5122.0  526.17  5128.8  527.16  5136.2  525.88  5143.0  527.28  5150.3  526.05
  5157.2  526.94  5171.3  526.05  5277.4  528.58  5334.1  528.59  5493.9  530.25
#Mann=6,-1,0
  4758.0    0.05       0  4933.0    0.12       0  5027.6    0.07       0
  5031.6    0.12       0  5045.8     0.1       0  5060.9    0.05       0
Bank Sta=5027.6,5031.6
Exp/Cntr=0.3,0.1

Type RM Length L Ch R = 1,16844,374,374,374
BEGIN DESCRIPTION:
Lacy 001 3415
END DESCRIPTION:
XS GIS Cut Line= 3
      2767077.10      6881710.32      2767256.67      6881882.34
      2767611.45      6882249.18
#Sta/Elev= 30
  4752.7  528.17  4794.7  528.39  4852.7  526.47  4886.9  525.36  4929.3  522.74
  4936.3  521.41  4964.6  521.10  4972.4  521.74  4985.9  522.48  5007.0  521.91
  5014.0  520.44  5021.2  519.83  5026.1  517.38  5026.4  516.88  5029.9  516.88
  5030.1  517.38  5049.5  520.37  5063.6  520.70  5084.7  522.40  5091.9  524.19
  5125.2  525.79  5252.3  528.20  5264.2  528.65  5282.8  529.34  5318.3  528.69
  5353.5  529.52  5360.7  529.05  5452.6  530.80  5473.7  530.44  5511.7  531.06
#Mann=8,-1,0
  4752.7    0.12       0  4852.7    0.05       0  4972.4     0.1       0
  5026.1    0.07       0  5030.1     0.1       0  5125.2    0.12       0
  5252.3     0.1       0  5264.2    0.05       0
Bank Sta=5026.1,5030.1
Exp/Cntr=0.3,0.1

Type RM Length L Ch R = 1,16470,325,325,325
BEGIN DESCRIPTION:
Lacy 001 3413
END DESCRIPTION:
XS GIS Cut Line= 3
      2766971.29      6881807.74      2767005.01      6882135.90
      2767049.40      6882433.12
#Sta/Elev= 30
  4673.3  523.16  4716.8  522.67  4746.9  521.57  4757.0  521.48  4770.2  522.21
  4787.2  521.95  4817.3  520.78  4847.5  520.76  4877.6  520.06  4917.8  519.67
  4968.5  519.62  4978.2  516.68  4988.2  514.51  4996.2  512.31  4996.5  511.81
  5000.0  511.81  5000.2  512.31  5003.2  512.31  5008.3  514.85  5018.5  516.05
  5048.8  517.86  5069.0  519.50  5089.2  520.43  5113.0  521.96  5129.7  523.43
  5230.8  527.36  5240.9  527.82  5251.5  528.99  5261.1  529.55  5303.7  531.28
#Mann=4,-1,0
  4673.3    0.12       0  4996.2    0.07       0  5000.2    0.12       0
  5089.2    0.05       0
Bank Sta=4996.2,5000.2
Exp/Cntr=0.3,0.1

Type RM Length L Ch R = 1,16145,256,256,256
BEGIN DESCRIPTION:
Lacy 001 3414
END DESCRIPTION:
XS GIS Cut Line= 3
      2766941.84      6881708.29      2766787.11      6881957.78
      2766644.36      6882316.98
#Sta/Elev= 30
  4706.5  527.03  4715.3  526.29  4792.1  522.13  4821.7  521.18  4827.6  520.46
  4895.0  517.10  4922.1  516.77  4931.6  517.41  4952.8  517.39  4958.7  516.51
  4980.3  515.17  4989.5  513.82  4995.3  511.39  4997.0  509.85  4997.3  509.35
  5000.8  509.35  5001.0  509.85  5012.8  510.23  5018.2  512.75  5025.1  514.39
  5057.3  515.20  5132.7  518.92  5174.7  519.90  5202.7  521.52  5251.0  522.28
  5258.4  522.75  5288.0  522.89  5347.9  525.12  5371.7  525.60  5386.6  525.10
#Mann=5,-1,0
  4706.5     0.1       0  4715.3    0.12       0  4997.0    0.07       0
  5001.0    0.12       0  5202.7    0.05       0
Bank Sta=4997,5001
Exp/Cntr=0.3,0.1

Type RM Length L Ch R = 1,15889,88,88,88
BEGIN DESCRIPTION:
Lacy 001 3412
END DESCRIPTION:
XS GIS Cut Line= 3
      2766561.39      6881650.91      2766587.37      6881858.41
      2766640.89      6882256.91
#Sta/Elev= 30
  4788.1  527.31  4875.7  524.72  4889.0  523.68  4909.1  522.81  4919.2  520.78
  4939.4  517.69  4945.2  515.25  4950.2  515.50  4959.5  514.21  4969.6  513.32
  4979.7  509.30  4987.8  507.18  4988.0  506.68  4991.5  506.68  4991.8  507.18
  4996.0  509.47  5001.1  509.47  5009.9  513.20  5019.7  513.64  5030.1  513.24
  5040.2  513.44  5050.3  514.08  5102.7  514.28  5151.2  515.62  5175.6  516.87
  5191.5  518.10  5265.4  520.94  5312.6  522.97  5363.1  523.35  5399.3  524.50
#Mann=5,-1,0
  4788.1    0.05       0  4875.7    0.12       0  4987.8    0.07       0
  4991.8    0.12       0  5265.4    0.05       0
Bank Sta=4987.8,4991.8
Exp/Cntr=0.3,0.1

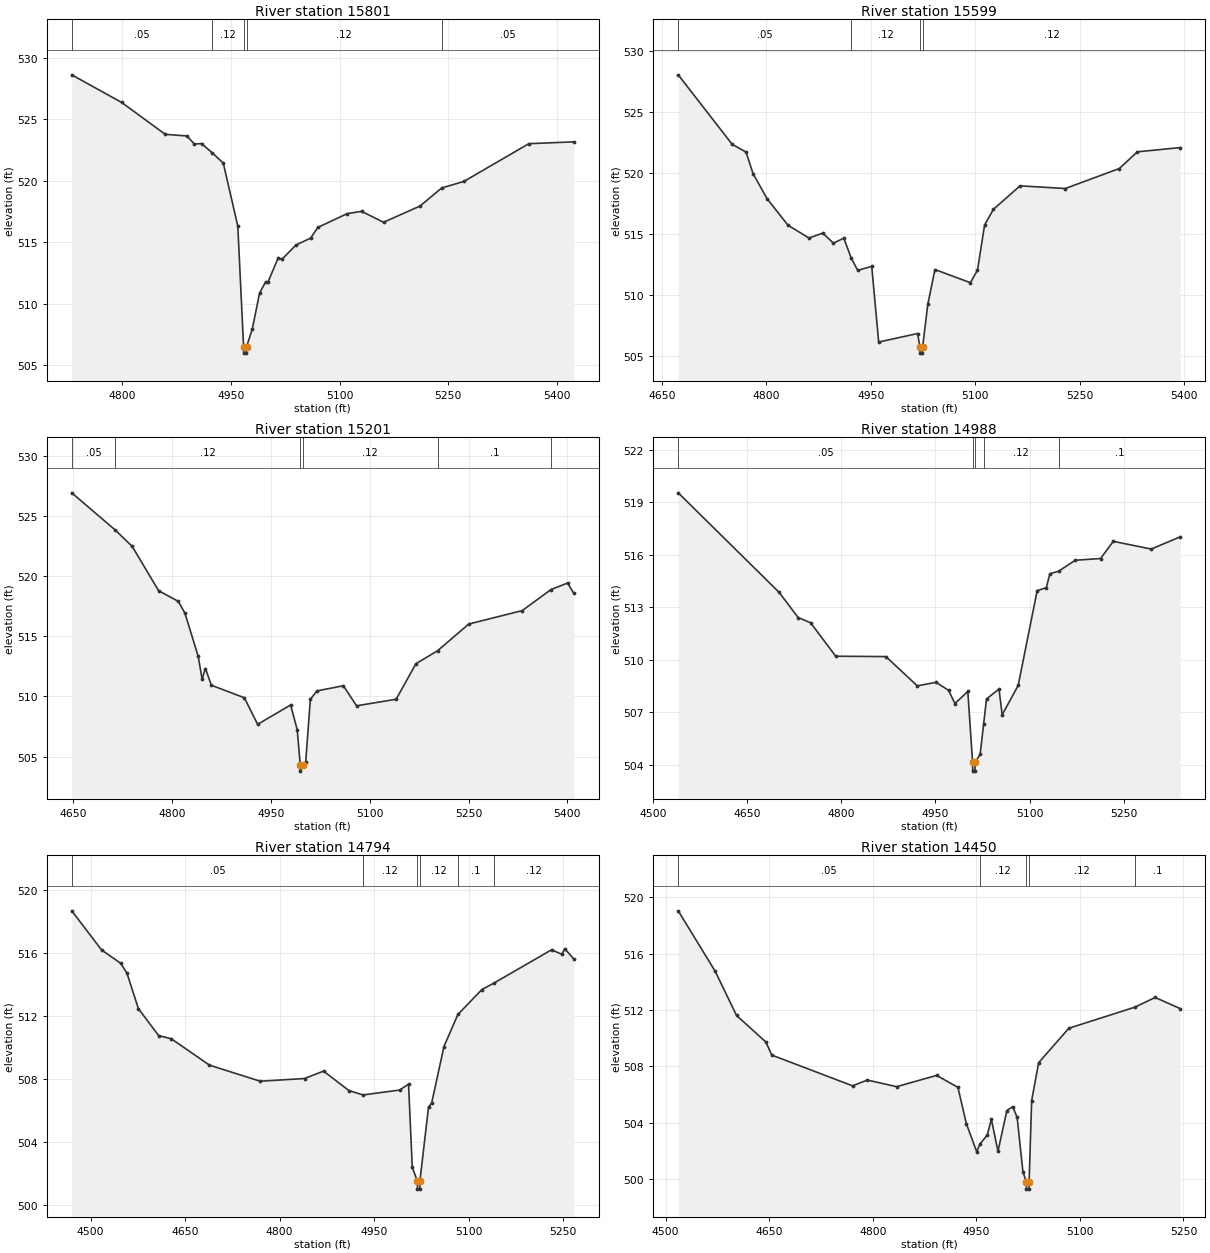
Type RM Length L Ch R = 1,15801,202,202,202
BEGIN DESCRIPTION:
Lacy 001 3402
END DESCRIPTION:
XS GIS Cut Line= 3
      2766494.97      6881592.06      2766499.30      6881862.79
      2766547.66      6882281.74
#Sta/Elev= 30
  4730.7  528.60  4799.6  526.35  4859.7  523.76  4889.7  523.63  4899.7  522.97
  4909.7  523.01  4924.6  522.25  4939.7  521.42  4959.7  516.30  4967.7  506.47
  4967.9  505.97  4971.4  505.97  4971.7  506.47  4979.7  507.93  4989.7  510.84
  4998.1  511.77  5001.5  511.77  5015.5  513.73  5020.6  513.60  5039.9  514.76
  5060.1  515.32  5070.1  516.19  5110.4  517.31  5130.5  517.50  5160.7  516.61
  5211.1  517.93  5240.9  519.40  5271.5  519.93  5361.1  523.00  5423.2  523.15
#Mann=5,-1,0
  4730.7    0.05       0  4924.6    0.12       0  4967.7    0.07       0
  4971.7    0.12       0  5240.9    0.05       0
Bank Sta=4967.7,4971.7
Exp/Cntr=0.3,0.1

Type RM Length L Ch R = 1,15599,398,398,398
BEGIN DESCRIPTION:
Lacy 001 3401
END DESCRIPTION:
XS GIS Cut Line= 3
      2766337.44      6881583.85      2766312.67      6881918.81
      2766239.33      6882296.99
#Sta/Elev= 30
  4673.4  528.07  4750.8  522.37  4770.8  521.73  4780.8  519.97  4800.9  517.91
  4831.0  515.73  4861.1  514.68  4881.1  515.08  4896.3  514.25  4911.2  514.67
  4921.7  513.05  4931.2  512.02  4951.3  512.35  4961.3  506.14  5017.3  506.84
  5020.4  505.73  5020.7  505.23  5024.2  505.23  5024.4  505.73  5031.9  509.26
  5042.1  512.09  5093.0  511.01  5103.2  512.04  5113.4  515.74  5125.9  517.02
  5164.3  518.96  5229.3  518.74  5306.9  520.38  5332.8  521.75  5394.5  522.10
#Mann=4,-1,0
  4673.4    0.05       0  4921.7    0.12       0  5020.4    0.07       0
  5024.4    0.12       0
Bank Sta=5020.4,5024.4
Exp/Cntr=0.3,0.1

Type RM Length L Ch R = 1,15201,213,213,213
BEGIN DESCRIPTION:
Lacy 001 3400
END DESCRIPTION:
XS GIS Cut Line= 3
      2765954.11      6881509.46      2765930.70      6881863.94
      2765906.01      6882270.34
#Sta/Elev= 30
  4647.5  526.93  4713.2  523.85  4739.2  522.48  4779.3  518.80  4809.4  517.90
  4819.4  516.91  4839.5  513.33  4845.4  511.45  4850.5  512.32  4859.5  510.93
  4909.6  509.89  4929.7  507.68  4979.8  509.29  4989.8  507.24  4994.5  504.29
  4994.7  503.79  4998.5  504.29  5002.7  504.54  5009.8  509.76  5019.8  510.46
  5059.9  510.89  5080.0  509.22  5140.1  509.77  5170.1  512.72  5203.0  513.80
  5250.3  516.02  5331.6  517.14  5375.2  518.89  5400.5  519.43  5409.9  518.56
#Mann=6,-1,0
  4647.5    0.05       0  4713.2    0.12       0  4994.5    0.07       0
  4998.5    0.12       0  5203.0     0.1       0  5375.2    0.12       0
Bank Sta=4994.5,4998.5
Exp/Cntr=0.3,0.1

Type RM Length L Ch R = 1,14988,194,194,194
BEGIN DESCRIPTION:
Lacy 001 3399
END DESCRIPTION:
XS GIS Cut Line= 3
      2765732.86      6881449.88      2765732.55      6881907.10
      2765781.72      6882246.84
#Sta/Elev= 30
  4539.9  519.53  4701.0  513.84  4731.0  512.41  4751.0  512.11  4791.0  510.20
  4871.0  510.18  4921.0  508.51  4951.0  508.71  4971.0  508.25  4981.0  507.50
  5001.6  508.19  5009.2  504.14  5009.4  503.64  5012.9  503.64  5013.2  504.14
  5021.3  504.60  5026.8  506.32  5031.4  507.76  5051.3  508.33  5056.4  506.86
  5081.9  508.53  5112.2  513.95  5126.7  514.11  5132.4  514.91  5146.2  515.05
  5172.8  515.68  5213.3  515.78  5233.5  516.76  5294.1  516.32  5340.4  517.02
#Mann=5,-1,0
  4539.9    0.05       0  5009.2    0.04       0  5013.2    0.05       0
  5026.8    0.12       0  5146.2     0.1       0
Bank Sta=5009.2,5013.2
Exp/Cntr=0.3,0.1

Type RM Length L Ch R = 1,14794,344,344,344
BEGIN DESCRIPTION:
Lacy 001 3398
END DESCRIPTION:
XS GIS Cut Line= 3
      2765612.99      6881433.94      2765554.05      6881965.06
      2765529.30      6882226.21
#Sta/Elev= 30
  4470.1  518.66  4517.4  516.18  4547.6  515.34  4557.7  514.71  4575.8  512.46
  4608.0  510.75  4628.1  510.55  4688.5  508.88  4769.0  507.86  4839.4  508.03
  4869.6  508.50  4909.8  507.27  4932.3  506.99  4990.3  507.30  5004.5  507.67
  5010.4  502.41  5018.5  501.52  5018.7  501.02  5022.2  501.02  5022.5  501.52
  5036.2  506.22  5041.2  506.48  5060.7  510.06  5082.8  512.09  5120.9  513.67
  5140.0  514.08  5231.4  516.19  5247.6  515.91  5252.6  516.25  5266.8  515.60
#Mann=6,-1,0
  4470.1    0.05       0  4932.3    0.12       0  5018.5    0.07       0
  5022.5    0.12       0  5082.8     0.1       0  5140.0    0.12       0
Bank Sta=5018.5,5022.5
Exp/Cntr=0.3,0.1

Type RM Length L Ch R = 1,14450,351,351,351
BEGIN DESCRIPTION:
Lacy 001 3396
END DESCRIPTION:
XS GIS Cut Line= 3
      2765526.24      6881455.66      2765270.24      6881871.48
      2765155.06      6882080.77
#Sta/Elev= 30
  4518.3  519.03  4571.9  514.74  4602.7  511.62  4645.3  509.73  4653.7  508.81
  4770.8  506.63  4792.1  507.04  4834.6  506.57  4892.6  507.37  4923.4  506.52
  4935.6  503.95  4950.6  501.96  4955.5  502.52  4966.0  503.15  4971.8  504.27
  4981.4  501.99  4994.3  504.88  5002.7  505.15  5009.2  504.39  5017.5  500.55
  5022.5  499.81  5022.7  499.31  5026.2  499.31  5026.5  499.81  5030.2  505.59
  5040.3  508.27  5084.1  510.71  5179.5  512.20  5209.1  512.89  5245.5  512.10
#Mann=5,-1,0
  4518.3    0.05       0  4955.5    0.12       0  5022.5    0.07       0
  5026.5    0.12       0  5179.5     0.1       0
Bank Sta=5022.5,5026.5
Exp/Cntr=0.3,0.1