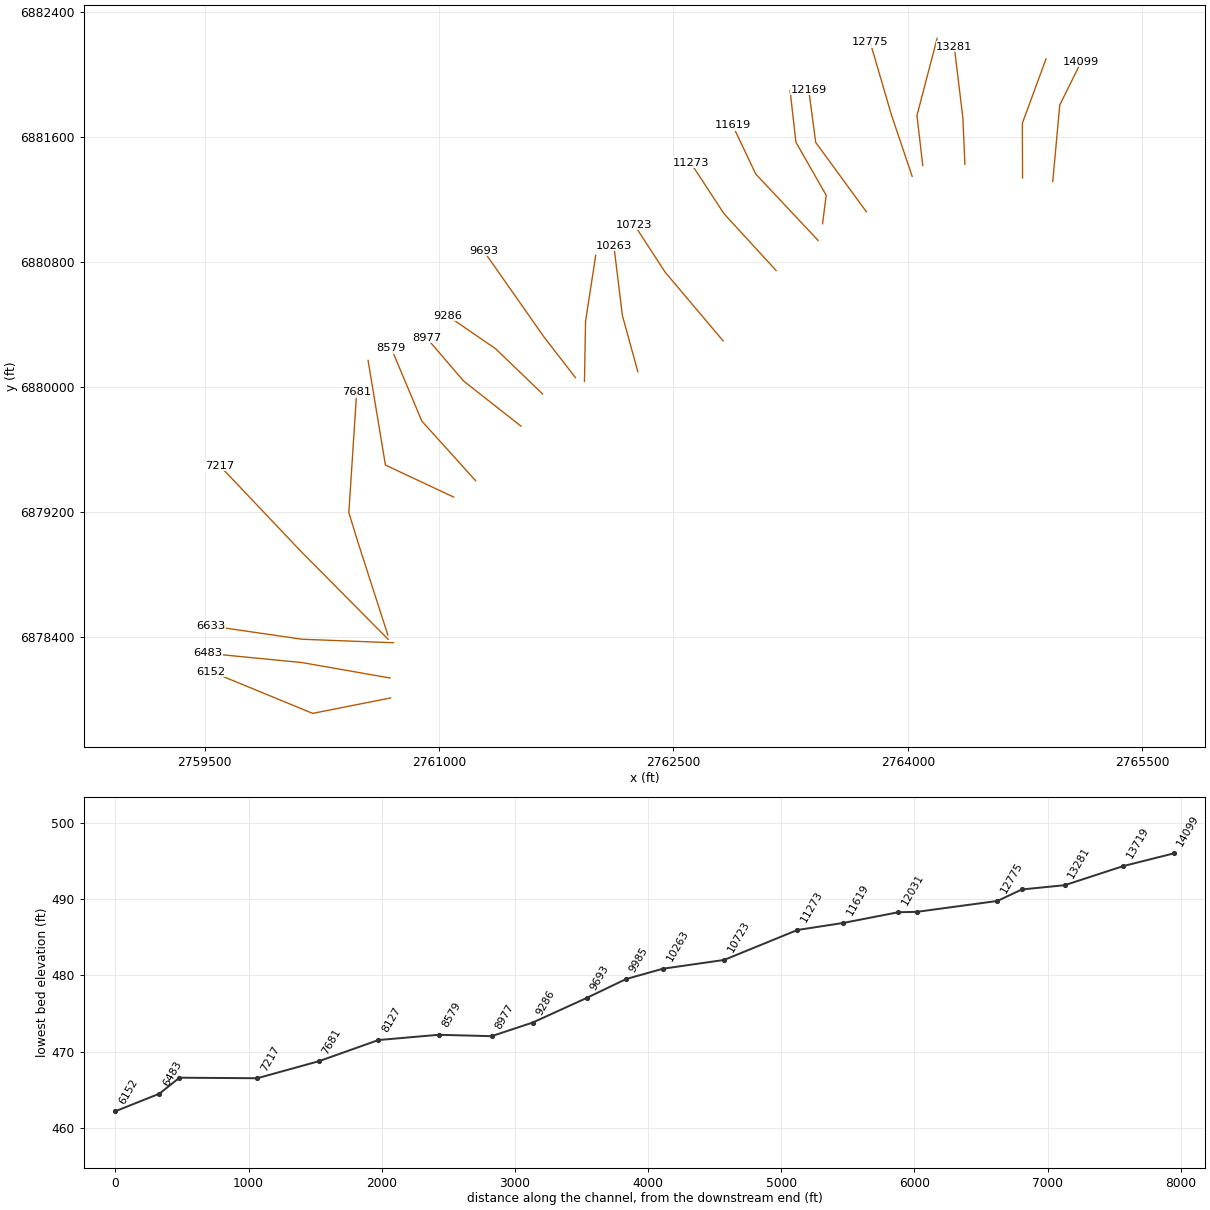
HEC-RAS study Lacy 001.prj: Lacy 001 Base Level Engineering

--- Lacy 001.g01 (geometry) --- (continued)

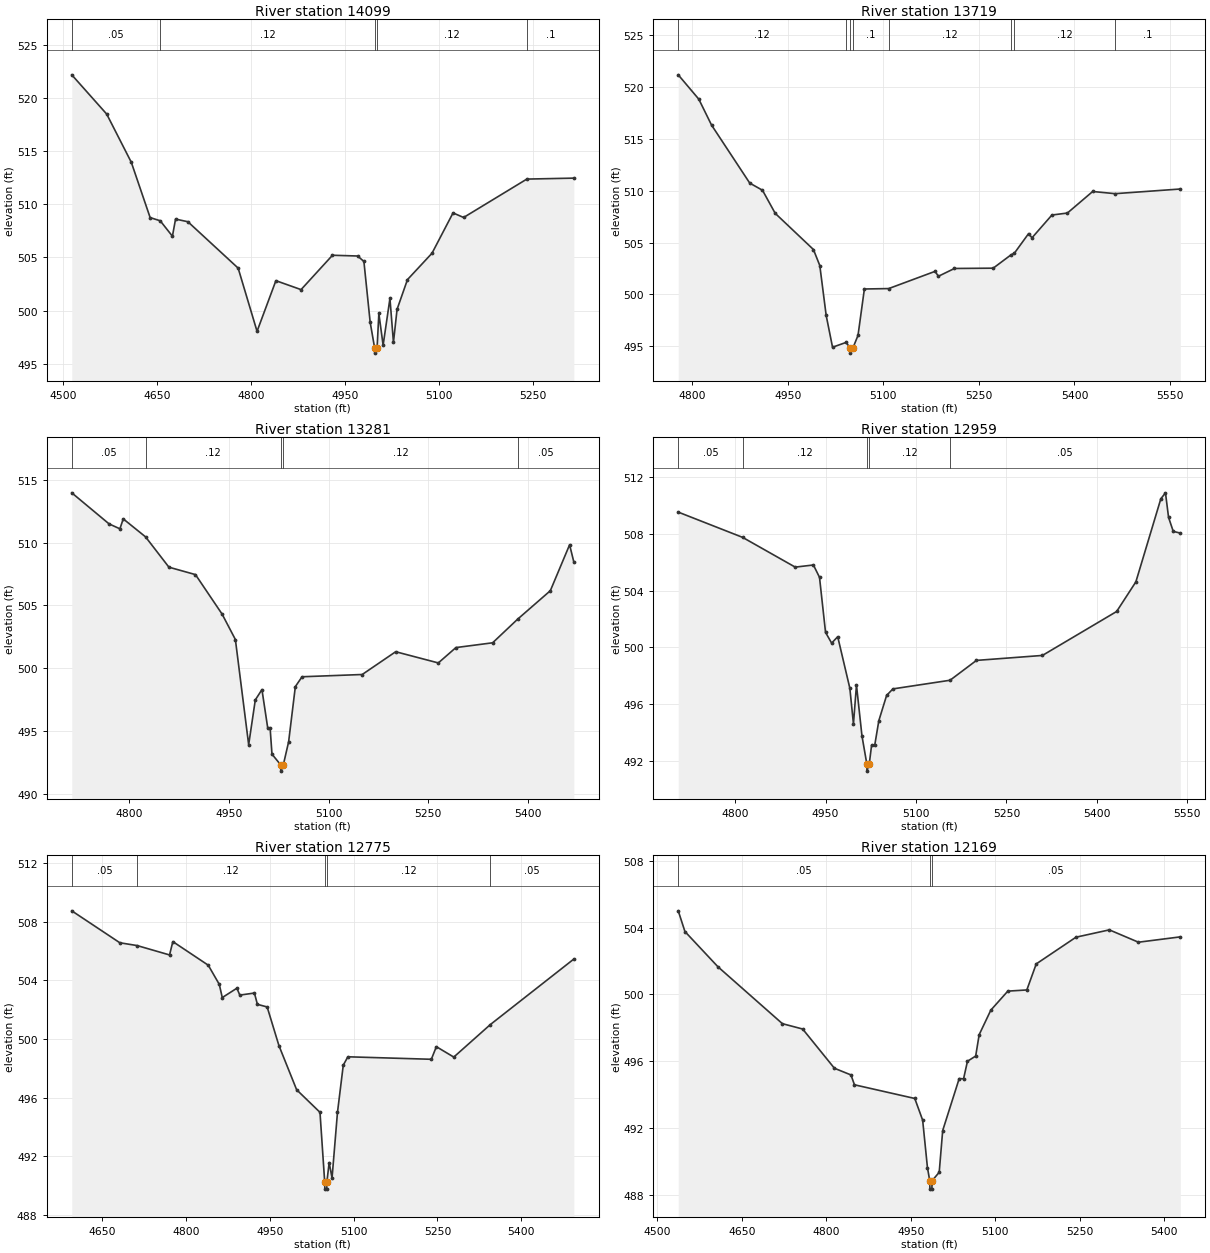
Type RM Length L Ch R = 1,14099,380,380,380
BEGIN DESCRIPTION:
Lacy 001 3397
END DESCRIPTION:
XS GIS Cut Line= 3
      2764926.28      6881316.27      2764971.15      6881805.69
      2765109.11      6882084.00
#Sta/Elev= 30
  4513.5  522.16  4569.3  518.47  4608.6  513.94  4638.7  508.74  4654.8  508.44
  4674.3  506.99  4679.3  508.60  4699.0  508.35  4779.3  503.99  4809.5  498.05
  4839.6  502.81  4879.8  501.97  4930.0  505.20  4970.1  505.13  4980.2  504.62
  4990.2  498.91  4997.3  496.50  4997.5  496.00  5001.3  496.50  5004.1  499.73
  5010.9  496.74  5021.8  501.14  5027.4  497.01  5033.2  500.12  5049.8  502.91
  5089.0  505.39  5122.6  509.18  5139.5  508.75  5240.5  512.36  5315.6  512.45
#Mann=5,-1,0
  4513.5    0.05       0  4654.8    0.12       0  4997.3    0.07       0
  5001.3    0.12       0  5240.5     0.1       0
Bank Sta=4997.3,5001.3
Exp/Cntr=0.3,0.1

Type RM Length L Ch R = 1,13719,438,438,438
BEGIN DESCRIPTION:
Lacy 001 3395
END DESCRIPTION:
XS GIS Cut Line= 3
      2764733.11      6881338.72      2764731.82      6881689.38
      2764883.14      6882100.13
#Sta/Elev= 30
  4777.8  521.19  4810.1  518.84  4830.1  516.34  4890.1  510.74  4910.1  510.05
  4930.1  507.82  4990.1  504.33  5000.1  502.78  5010.1  497.97  5020.1  494.90
  5041.2  495.36  5048.1  494.83  5048.3  494.33  5052.1  494.83  5060.1  496.04
  5070.1  500.52  5108.3  500.56  5181.0  502.22  5186.4  501.75  5211.5  502.50
  5272.4  502.53  5299.6  503.78  5305.8  503.99  5328.0  505.87  5333.3  505.46
  5364.6  507.66  5388.9  507.85  5428.6  509.93  5463.8  509.72  5566.2  510.17
#Mann=8,-1,0
  4777.8    0.12       0  5041.2     0.1       0  5048.1    0.07       0
  5052.1     0.1       0  5108.3    0.12       0  5299.6    0.05       0
  5305.8    0.12       0  5463.8     0.1       0
Bank Sta=5048.1,5052.1
Exp/Cntr=0.3,0.1

Type RM Length L Ch R = 1,13281,322,322,322
BEGIN DESCRIPTION:
Lacy 001 3394
END DESCRIPTION:
XS GIS Cut Line= 3
      2764364.17      6881424.85      2764351.33      6881723.32
      2764296.28      6882177.35
#Sta/Elev= 30
  4713.2  513.95  4769.4  511.48  4785.7  511.09  4790.7  511.88  4824.3  510.45
  4859.5  508.04  4899.5  507.45  4939.6  504.31  4959.6  502.29  4979.6  493.93
  4989.6  497.49  4999.6  498.31  5008.3  495.26  5011.9  495.26  5014.7  493.18
  5027.8  492.33  5028.0  491.83  5031.8  492.33  5039.8  494.17  5049.9  498.55
  5060.0  499.33  5150.6  499.51  5201.0  501.32  5265.2  500.43  5291.7  501.65
  5347.0  502.03  5384.7  503.91  5433.9  506.17  5462.9  509.82  5469.3  508.45
#Mann=5,-1,0
  4713.2    0.05       0  4824.3    0.12       0  5027.8    0.07       0
  5031.8    0.12       0  5384.7    0.05       0
Bank Sta=5027.8,5031.8
Exp/Cntr=0.3,0.1

Type RM Length L Ch R = 1,12959,184,184,184
BEGIN DESCRIPTION:
Lacy 001 3393
END DESCRIPTION:
XS GIS Cut Line= 3
      2764094.71      6881418.32      2764057.52      6881737.75
      2764186.58      6882232.30
#Sta/Elev= 30
  4705.7  509.54  4812.4  507.76  4899.7  505.66  4929.9  505.81  4940.0  504.94
  4950.0  501.06  4960.1  500.30  4970.2  500.75  4990.3  497.12  4996.3  494.60
  5001.3  497.34  5010.4  493.76  5018.5  491.77  5018.7  491.27  5022.5  491.77
  5026.4  493.10  5031.6  493.10  5038.4  494.83  5051.3  496.61  5061.7  497.07
  5156.5  497.68  5200.3  499.08  5309.7  499.43  5432.8  502.53  5464.7  504.62
  5506.1  510.48  5513.8  510.90  5518.9  509.17  5526.7  508.18  5538.4  508.06
#Mann=5,-1,0
  4705.7    0.05       0  4812.4    0.12       0  5018.5    0.07       0
  5022.5    0.12       0  5156.5    0.05       0
Bank Sta=5018.5,5022.5
Exp/Cntr=0.3,0.1

Type RM Length L Ch R = 1,12775,606,606,606
BEGIN DESCRIPTION:
Lacy 001 3392
END DESCRIPTION:
XS GIS Cut Line= 3
      2764026.73      6881349.45      2763894.17      6881742.39
      2763758.41      6882207.38
#Sta/Elev= 30
  4595.2  508.75  4681.3  506.57  4712.2  506.38  4770.3  505.74  4776.2  506.65
  4839.6  505.04  4859.4  503.73  4864.7  502.83  4890.9  503.47  4896.1  503.00
  4922.3  503.14  4927.6  502.37  4945.1  502.19  4966.2  499.55  4997.9  496.54
  5039.7  495.00  5048.1  490.26  5048.4  489.76  5051.9  489.76  5052.1  490.26
  5056.1  491.57  5061.3  490.52  5071.0  494.99  5081.4  498.22  5089.6  498.79
  5239.1  498.62  5248.1  499.48  5279.3  498.77  5344.8  500.99  5494.3  505.46
#Mann=5,-1,0
  4595.2    0.05       0  4712.2    0.12       0  5048.1    0.07       0
  5052.1    0.12       0  5344.8    0.05       0
Bank Sta=5048.1,5052.1
Exp/Cntr=0.3,0.1

Type RM Length L Ch R = 1,12169,138,138,138
BEGIN DESCRIPTION:
Lacy 001 3374
END DESCRIPTION:
XS GIS Cut Line= 3
      2763734.43      6881121.54      2763409.90      6881565.98
      2763364.89      6881904.79
#Sta/Elev= 30
  4537.0  505.00  4548.9  503.76  4607.5  501.65  4722.1  498.24  4758.1  497.92
  4814.5  495.57  4843.9  495.17  4850.1  494.58  4957.3  493.76  4971.3  492.46
  4979.8  489.62  4983.9  488.83  4984.2  488.33  4987.7  488.33  4988.0  488.83
  5000.7  489.34  5006.9  491.84  5036.2  494.95  5044.0  494.94  5050.9  495.99
  5065.5  496.30  5071.7  497.58  5092.4  499.05  5122.6  500.19  5156.4  500.26
  5173.1  501.82  5243.7  503.42  5303.0  503.86  5354.7  503.12  5429.1  503.44
#Mann=3,-1,0
  4537.0    0.05       0  4983.9    0.05       0  4988.0    0.05       0
Bank Sta=4983.9,4988
Exp/Cntr=0.3,0.1

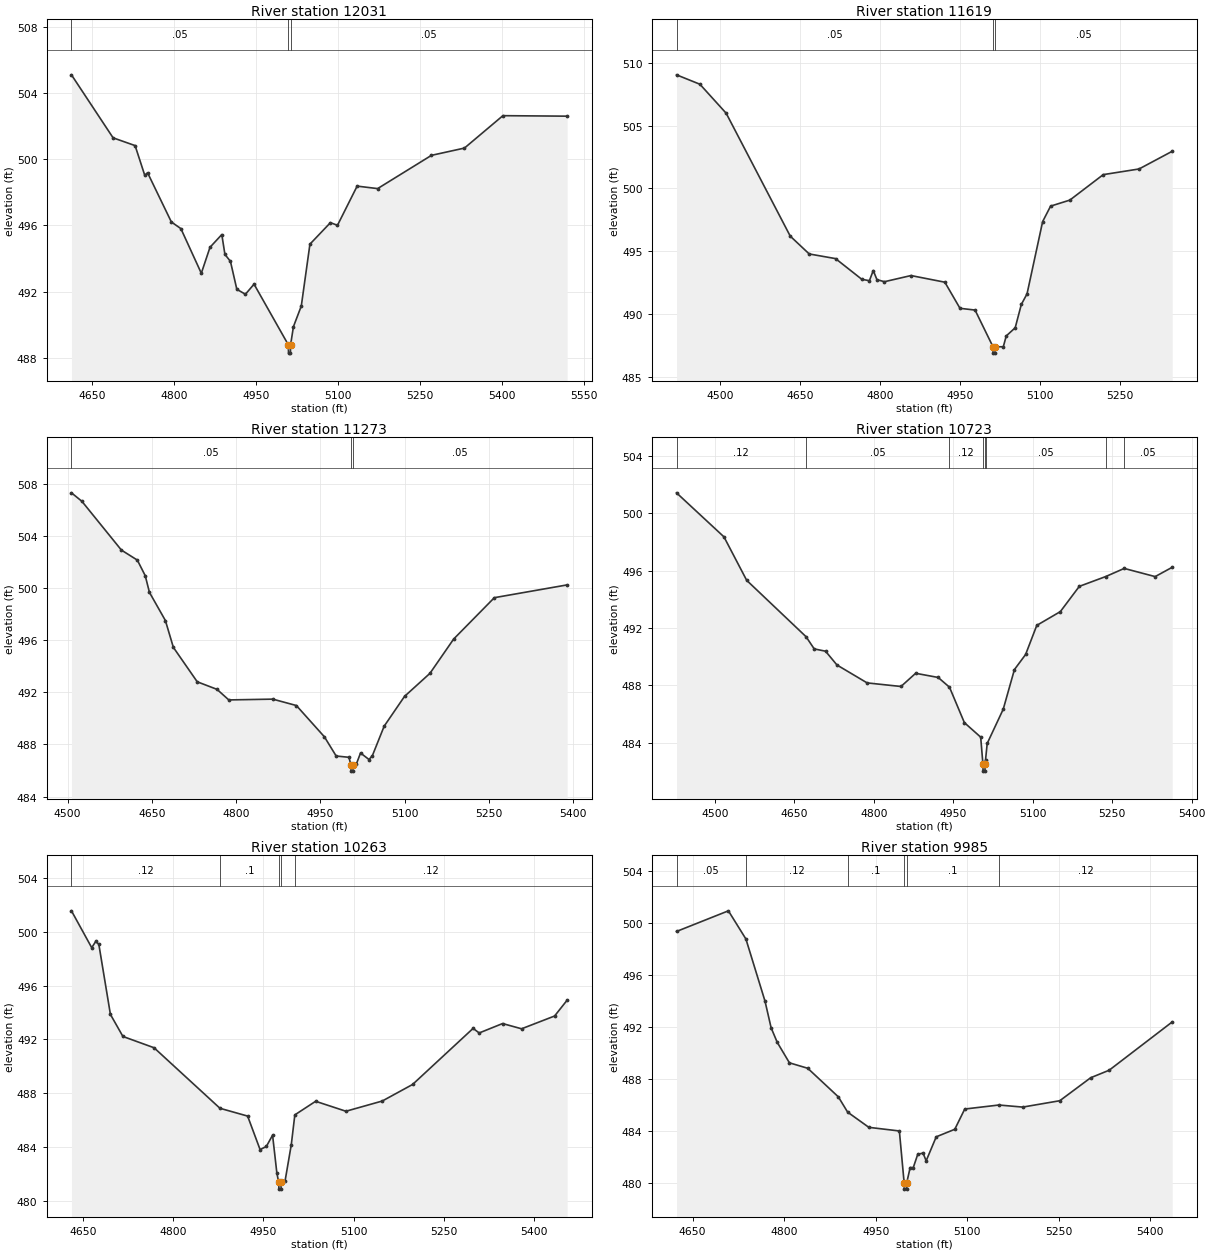
Type RM Length L Ch R = 1,12031,412,412,412
BEGIN DESCRIPTION:
Lacy 001 3375
END DESCRIPTION:
XS GIS Cut Line= 4
      2763453.87      6881045.38      2763476.90      6881227.75
      2763283.31      6881567.20      2763246.01      6881897.81
#Sta/Elev= 30
  4612.3  505.11  4688.5  501.30  4728.8  500.83  4746.5  499.03  4751.6  499.19
  4795.2  496.21  4812.6  495.81  4850.0  493.11  4865.9  494.68  4887.5  495.45
  4893.2  494.25  4903.3  493.83  4915.0  492.14  4930.7  491.84  4946.5  492.45
  5009.3  488.78  5009.6  488.28  5013.1  488.28  5013.4  488.78  5018.6  489.88
  5033.0  491.13  5048.8  494.87  5086.3  496.17  5099.2  496.01  5135.2  498.38
  5172.7  498.23  5271.2  500.24  5331.6  500.68  5402.0  502.64  5519.6  502.61
#Mann=3,-1,0
  4612.3    0.05       0  5009.3    0.04       0  5013.4    0.05       0
Bank Sta=5009.3,5013.4
Exp/Cntr=0.3,0.1

Type RM Length L Ch R = 1,11619,346,346,346
BEGIN DESCRIPTION:
Lacy 001 3376
END DESCRIPTION:
XS GIS Cut Line= 3
      2763425.32      6880938.55      2763026.03      6881363.89
      2762877.65      6881677.24
#Sta/Elev= 30
  4418.3  509.05  4462.2  508.30  4511.5  505.99  4631.7  496.20  4667.3  494.78
  4716.7  494.41  4766.0  492.76  4780.2  492.65  4787.5  493.46  4794.4  492.73
  4808.5  492.57  4858.3  493.06  4921.8  492.53  4950.2  490.45  4978.5  490.31
  5012.2  487.38  5012.5  486.88  5016.0  486.88  5016.3  487.38  5031.5  487.39
  5037.0  488.25  5053.8  488.90  5065.3  490.76  5076.0  491.60  5105.3  497.36
  5120.2  498.59  5156.3  499.07  5219.0  501.10  5286.2  501.55  5348.4  502.96
#Mann=3,-1,0
  4418.3    0.05       0  5012.2    0.05       0  5016.3    0.05       0
Bank Sta=5012.2,5016.3
Exp/Cntr=0.3,0.1

Type RM Length L Ch R = 1,11273,550,550,550
BEGIN DESCRIPTION:
Lacy 001 3373
END DESCRIPTION:
XS GIS Cut Line= 3
      2763156.77      6880745.78      2762823.17      6881109.96
      2762610.35      6881435.01
#Sta/Elev= 30
  4507.0  507.29  4525.6  506.64  4595.9  502.90  4624.3  502.13  4638.4  500.93
  4645.8  499.66  4674.2  497.50  4688.4  495.44  4730.9  492.80  4766.1  492.22
  4787.1  491.41  4865.4  491.47  4907.4  490.98  4957.3  488.58  4978.2  487.11
  5000.9  487.01  5004.4  486.45  5004.7  485.95  5008.2  485.95  5008.6  486.45
  5014.1  486.49  5021.6  487.34  5036.7  486.84  5042.7  487.14  5063.7  489.40
  5099.9  491.68  5145.2  493.45  5187.4  496.08  5259.8  499.25  5389.4  500.23
#Mann=3,-1,0
  4507.0    0.05       0  5004.4    0.05       0  5008.6    0.05       0
Bank Sta=5004.4,5008.6
Exp/Cntr=0.3,0.1

Type RM Length L Ch R = 1,10723,460,460,460
BEGIN DESCRIPTION:
Lacy 001 3372
END DESCRIPTION:
XS GIS Cut Line= 3
      2762817.45      6880295.89      2762447.20      6880734.89
      2762250.01      6881038.00
#Sta/Elev= 30
  4427.4  501.42  4517.0  498.35  4559.9  495.32  4672.0  491.39  4687.4  490.54
  4708.8  490.38  4730.3  489.42  4787.3  488.17  4851.2  487.92  4878.9  488.84
  4921.4  488.55  4942.8  487.87  4970.9  485.40  5001.7  484.39  5005.9  482.52
  5006.2  482.02  5009.8  482.02  5010.1  482.52  5010.8  482.78  5014.0  483.95
  5044.3  486.34  5065.4  489.10  5086.5  490.15  5107.6  492.18  5152.1  493.14
  5187.9  494.90  5237.5  495.58  5272.7  496.15  5331.1  495.58  5363.3  496.23
#Mann=8,-1,0
  4427.4    0.12       0  4672.0    0.05       0  4942.8    0.12       0
  5005.9    0.07       0  5010.1    0.12       0  5010.8    0.05       0
  5237.5    0.12       0  5272.7    0.05       0
Bank Sta=5005.9,5010.1
Exp/Cntr=0.3,0.1

Type RM Length L Ch R = 1,10263,278,278,278
BEGIN DESCRIPTION:
Lacy 001 3371
END DESCRIPTION:
XS GIS Cut Line= 3
      2762272.05      6880098.48      2762173.37      6880457.58
      2762118.38      6880906.21
#Sta/Elev= 30
  4630.9  501.56  4664.6  498.82  4671.2  499.28  4676.4  499.08  4695.7  493.86
  4716.5  492.22  4768.3  491.38  4877.9  486.88  4923.9  486.30  4944.6  483.81
  4955.0  484.04  4965.4  484.88  4972.5  482.07  4975.6  481.37  4975.9  480.87
  4979.5  480.87  4979.8  481.37  4986.1  481.46  4996.5  484.17  5002.4  486.39
  5037.0  487.40  5087.4  486.66  5147.8  487.42  5198.2  488.65  5298.9  492.82
  5309.0  492.48  5347.9  493.18  5379.5  492.79  5434.4  493.74  5455.3  494.92
#Mann=5,-1,0
  4630.9    0.12       0  4877.9     0.1       0  4975.6    0.07       0
  4979.8     0.1       0  5002.4    0.12       0
Bank Sta=4975.6,4979.8
Exp/Cntr=0.3,0.1

Type RM Length L Ch R = 1,9985,292,292,292
BEGIN DESCRIPTION:
Lacy 001 3370
END DESCRIPTION:
XS GIS Cut Line= 3
      2761930.59      6880035.99      2761937.65      6880421.49
      2762002.52      6880843.06
#Sta/Elev= 30
  4623.6  499.35  4708.6  500.94  4737.3  498.77  4768.6  493.98  4778.6  491.93
  4788.6  490.81  4808.6  489.23  4838.6  488.81  4888.7  486.61  4904.0  485.43
  4938.7  484.26  4988.7  483.98  4996.5  480.00  4996.9  479.50  5000.5  479.50
  5000.8  480.00  5006.4  481.16  5011.5  481.16  5018.8  482.18  5027.5  482.28
  5032.6  481.68  5049.1  483.53  5079.5  484.11  5095.8  485.67  5151.7  485.98
  5190.8  485.82  5251.5  486.31  5302.1  488.08  5332.4  488.66  5435.7  492.38
#Mann=6,-1,0
  4623.6    0.05       0  4737.3    0.12       0  4904.0     0.1       0
  4996.5    0.07       0  5000.8     0.1       0  5151.7    0.12       0
Bank Sta=4996.5,5000.8
Exp/Cntr=0.3,0.1

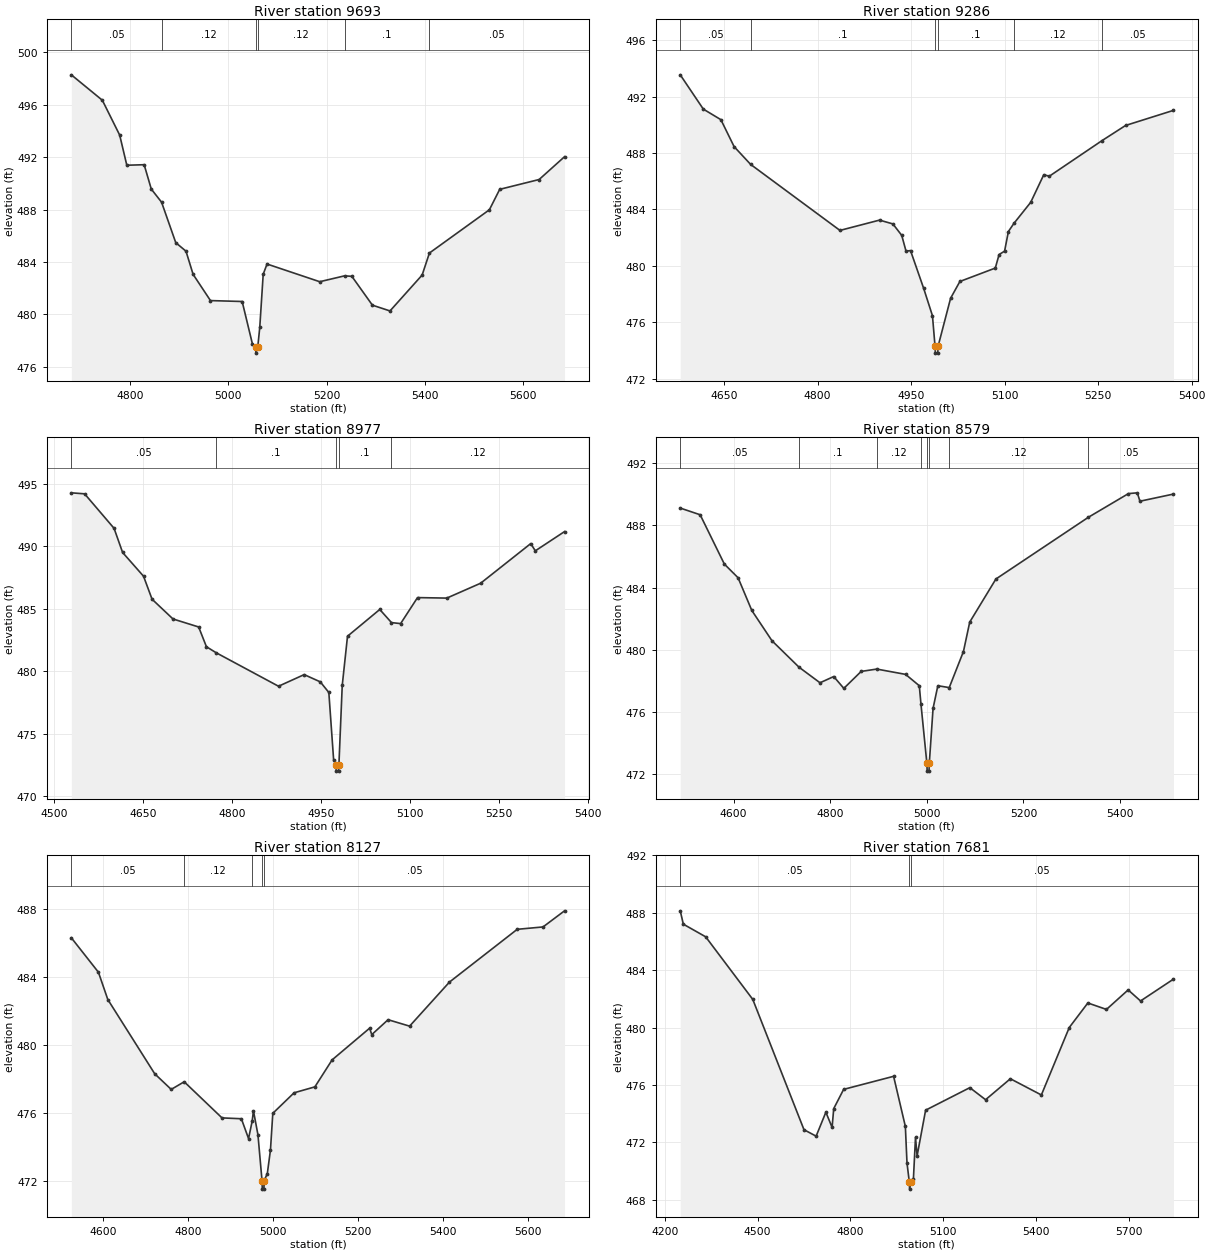
Type RM Length L Ch R = 1,9693,407,407,407
BEGIN DESCRIPTION:
Lacy 001 3369
END DESCRIPTION:
XS GIS Cut Line= 3
      2761873.11      6880060.59      2761672.35      6880319.74
      2761284.62      6880873.10
#Sta/Elev= 30
  4680.8  498.29  4743.9  496.35  4779.2  493.69  4793.7  491.39  4829.0  491.43
  4843.5  489.57  4864.4  488.57  4893.3  485.48  4914.1  484.83  4928.6  483.06
  4963.9  481.06  5028.4  480.99  5049.4  477.73  5055.9  477.55  5056.3  477.05
  5060.2  477.55  5064.2  479.01  5071.2  483.07  5079.0  483.85  5186.2  482.50
  5236.9  482.95  5251.6  482.91  5293.4  480.71  5329.2  480.27  5394.6  483.01
  5409.4  484.69  5531.4  487.99  5552.4  489.55  5632.6  490.30  5684.3  492.04
#Mann=6,-1,0
  4680.8    0.05       0  4864.4    0.12       0  5055.9    0.07       0
  5060.2    0.12       0  5236.9     0.1       0  5409.4    0.05       0
Bank Sta=5055.9,5060.2
Exp/Cntr=0.3,0.1

Type RM Length L Ch R = 1,9286,309,309,309
BEGIN DESCRIPTION:
Lacy 001 3368
END DESCRIPTION:
XS GIS Cut Line= 3
      2761662.96      6879955.80      2761362.37      6880245.04
      2761054.28      6880457.16
#Sta/Elev= 30
  4579.6  493.54  4616.6  491.11  4644.8  490.36  4666.0  488.45  4692.5  487.19
  4835.8  482.51  4899.3  483.24  4920.7  482.97  4934.9  482.16  4941.8  481.04
  4949.0  481.08  4970.1  478.40  4984.2  476.46  4988.3  474.31  4988.9  473.81
  4992.6  473.81  4993.3  474.31  5013.3  477.70  5028.2  478.89  5085.0  479.84
  5091.1  480.80  5099.9  481.04  5106.0  482.43  5114.9  483.01  5141.8  484.50
  5162.8  486.46  5171.6  486.35  5256.0  488.87  5294.0  489.95  5370.8  491.02
#Mann=6,-1,0
  4579.6    0.05       0  4692.5     0.1       0  4988.3    0.07       0
  4993.3     0.1       0  5114.9    0.12       0  5256.0    0.05       0
Bank Sta=4988.3,4993.3
Exp/Cntr=0.3,0.1

Type RM Length L Ch R = 1,8977,398,398,398
BEGIN DESCRIPTION:
Lacy 001 3347
END DESCRIPTION:
XS GIS Cut Line= 3
      2761525.07      6879749.42      2761157.03      6880039.12
      2760920.29      6880315.11
#Sta/Elev= 30
  4529.0  494.28  4551.4  494.20  4601.1  491.44  4615.5  489.51  4650.8  487.61
  4665.2  485.77  4700.5  484.19  4743.8  483.55  4756.9  481.97  4773.3  481.49
  4878.5  478.81  4921.8  479.74  4949.0  479.16  4963.4  478.31  4971.5  472.91
  4975.4  472.52  4976.0  472.02  4979.8  472.02  4980.4  472.52  4986.0  478.87
  4994.9  482.81  5049.3  484.95  5069.1  483.90  5084.5  483.82  5113.0  485.90
  5162.4  485.86  5219.5  487.05  5304.0  490.22  5311.7  489.64  5361.0  491.18
#Mann=5,-1,0
  4529.0    0.05       0  4773.3     0.1       0  4975.4    0.07       0
  4980.4     0.1       0  5069.1    0.12       0
Bank Sta=4975.4,4980.4
Exp/Cntr=0.3,0.1

Type RM Length L Ch R = 1,8579,452,452,452
BEGIN DESCRIPTION:
Lacy 001 3345
END DESCRIPTION:
XS GIS Cut Line= 3
      2761234.31      6879400.66      2760890.40      6879781.91
      2760694.08      6880249.85
#Sta/Elev= 30
  4489.6  489.11  4530.8  488.68  4580.9  485.51  4609.3  484.63  4637.7  482.53
  4679.5  480.58  4735.5  478.88  4778.9  477.88  4807.3  478.28  4828.2  477.52
  4864.1  478.61  4896.4  478.76  4956.0  478.42  4984.4  477.69  4987.8  476.53
  5000.1  472.70  5000.7  472.20  5004.5  472.20  5005.1  472.70  5012.9  476.23
  5022.8  477.69  5046.4  477.57  5075.8  479.89  5088.8  481.78  5143.0  484.55
  5334.5  488.52  5417.3  490.04  5435.7  490.09  5441.1  489.55  5510.5  490.01
#Mann=8,-1,0
  4489.6    0.05       0  4735.5     0.1       0  4896.4    0.12       0
  4987.8     0.1       0  5000.1    0.07       0  5005.1     0.1       0
  5046.4    0.12       0  5334.5    0.05       0
Bank Sta=5000.1,5005.1
Exp/Cntr=0.3,0.1

Type RM Length L Ch R = 1,8127,446,446,446
BEGIN DESCRIPTION:
Lacy 001 3344
END DESCRIPTION:
XS GIS Cut Line= 3
      2761093.76      6879295.94      2760657.37      6879500.85
      2760546.33      6880170.91
#Sta/Elev= 30
  4524.9  486.33  4588.7  484.30  4610.8  482.69  4721.3  478.31  4760.1  477.39
  4790.7  477.84  4879.7  475.71  4925.3  475.66  4942.2  474.49  4950.8  475.53
  4953.7  476.13  4964.3  474.72  4973.9  472.01  4974.6  471.51  4978.4  471.51
  4979.0  472.01  4986.4  472.43  4993.8  473.82  4999.3  475.98  5049.4  477.19
  5098.4  477.54  5138.9  479.13  5227.3  481.00  5232.3  480.62  5270.7  481.50
  5321.4  481.12  5415.3  483.72  5574.8  486.83  5635.6  486.97  5686.2  487.92
#Mann=5,-1,0
  4524.9    0.05       0  4790.7    0.12       0  4950.8    0.05       0
  4973.9    0.04       0  4979.0    0.05       0
Bank Sta=4973.9,4979
Exp/Cntr=0.3,0.1

Type RM Length L Ch R = 1,7681,464,464,464
BEGIN DESCRIPTION:
Lacy 001 3343
END DESCRIPTION:
XS GIS Cut Line= 4
      2760672.91      6878412.81      2760479.16      6879014.23
      2760423.35      6879196.44      2760473.36      6879967.19
#Sta/Elev= 30
  4250.0  488.13  4260.0  487.20  4332.2  486.32  4484.5  481.96  4650.1  472.88
  4689.4  472.43  4720.9  474.10  4741.0  473.04  4746.3  474.35  4778.3  475.69
  4939.9  476.60  4977.9  473.11  4983.2  470.56  4990.7  469.24  4991.6  468.74
  4996.3  469.24  5004.0  469.47  5010.7  472.34  5015.9  471.06  5043.4  474.24
  5186.4  475.81  5237.3  474.97  5317.5  476.43  5417.7  475.30  5507.9  480.00
  5568.0  481.71  5628.2  481.26  5698.3  482.62  5738.4  481.85  5844.8  483.37
#Mann=3,-1,0
  4250.0    0.05       0  4990.7    0.04       0  4996.3    0.05       0
Bank Sta=4990.7,4996.3
Exp/Cntr=0.3,0.1

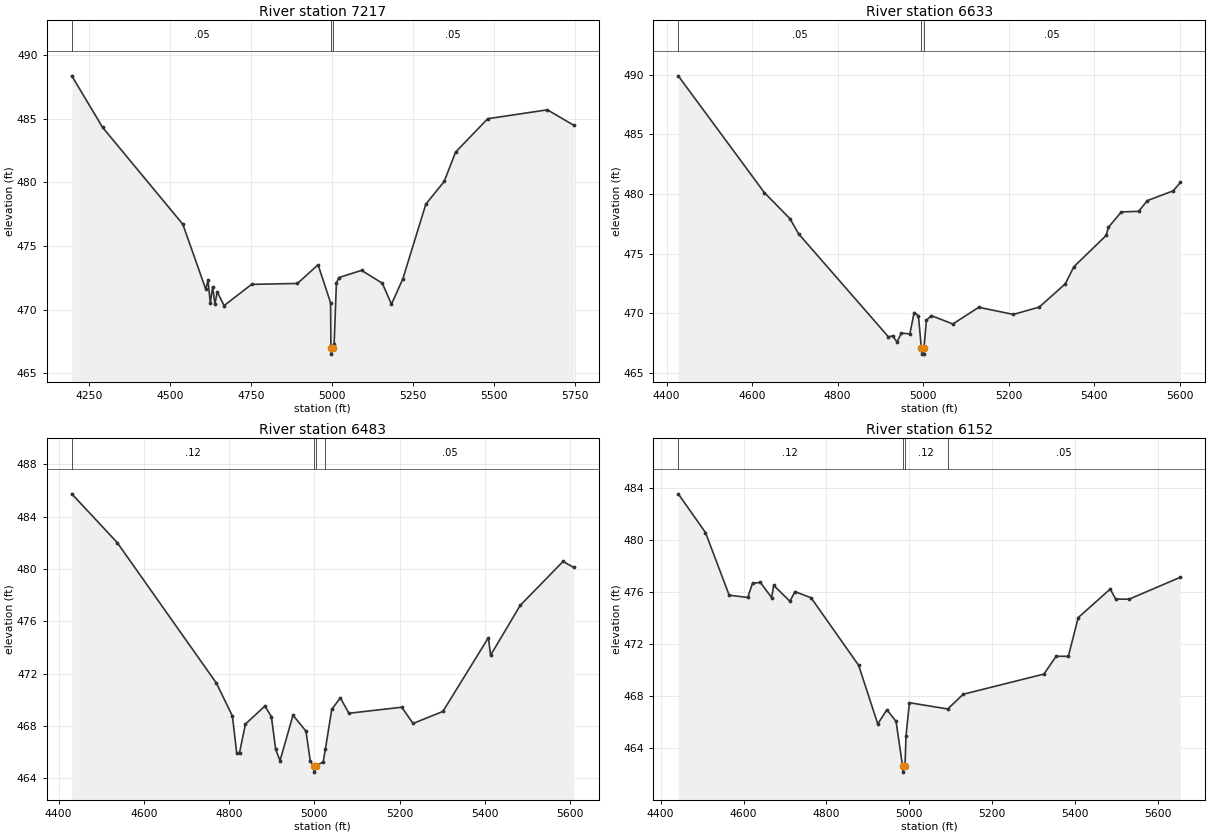
Type RM Length L Ch R = 1,7217,584,584,584
BEGIN DESCRIPTION:
Lacy 001 3342
END DESCRIPTION:
XS GIS Cut Line= 3
      2760674.75      6878385.30      2760113.01      6878952.63
      2759596.87      6879497.35
#Sta/Elev= 30
  4196.5  488.36  4291.6  484.31  4539.1  476.70  4609.8  471.60  4616.8  472.30
  4623.9  470.51  4631.0  471.80  4638.1  470.43  4645.1  471.39  4666.4  470.31
  4751.2  471.98  4892.6  472.05  4956.3  473.52  4994.9  470.53  4995.9  467.00
  4996.7  466.50  5001.5  467.00  5005.9  467.29  5012.8  472.06  5020.1  472.51
  5090.5  473.08  5154.4  472.07  5182.7  470.42  5217.9  472.42  5288.7  478.28
  5345.3  480.06  5380.5  482.37  5479.6  484.99  5663.7  485.69  5745.3  484.47
#Mann=3,-1,0
  4196.5    0.05       0  4995.9    0.04       0  5001.5    0.05       0
Bank Sta=4995.9,5001.5
Exp/Cntr=0.3,0.1

Type RM Length L Ch R = 1,6633,150,150,150
BEGIN DESCRIPTION:
Lacy 001 3339
END DESCRIPTION:
XS GIS Cut Line= 3
      2760707.37      6878363.41      2760123.54      6878385.93
      2759539.57      6878470.99
#Sta/Elev= 30
  4427.2  489.92  4628.7  480.12  4688.8  477.92  4708.8  476.66  4918.9  468.02
  4928.9  468.10  4939.0  467.58  4949.0  468.33  4969.0  468.27  4979.0  470.06
  4989.0  469.79  4996.0  467.07  4997.0  466.57  5001.0  466.57  5002.0  467.07
  5007.7  469.41  5019.1  469.80  5069.6  469.10  5130.2  470.50  5211.1  469.90
  5271.7  470.52  5332.4  472.46  5352.6  473.90  5428.3  476.53  5433.4  477.21
  5463.7  478.50  5504.2  478.55  5524.4  479.45  5585.0  480.27  5601.6  480.97
#Mann=3,-1,0
  4427.2    0.05       0  4996.0    0.04       0  5002.0    0.05       0
Bank Sta=4996,5002
Exp/Cntr=0.3,0.1

Type RM Length L Ch R = 1,6483,331,331,331
BEGIN DESCRIPTION:
Lacy 001 3338
END DESCRIPTION:
XS GIS Cut Line= 3
      2760687.26      6878137.77      2760123.52      6878236.56
      2759520.72      6878295.39
#Sta/Elev= 30
  4430.7  485.75  4537.4  482.02  4770.1  471.28  4807.6  468.77  4817.8  465.91
  4824.4  465.98  4838.1  468.15  4883.8  469.53  4899.0  468.73  4909.1  466.22
  4919.3  465.35  4949.8  468.83  4980.2  467.61  4990.4  465.31  4998.4  464.98
  4999.4  464.48  5004.4  464.98  5020.6  465.26  5025.8  466.24  5040.7  469.28
  5060.8  470.16  5080.9  468.98  5204.9  469.44  5231.6  468.20  5301.5  469.12
  5408.3  474.76  5413.3  473.41  5482.8  477.22  5583.3  480.58  5608.7  480.12
#Mann=4,-1,0
  4430.7    0.12       0  4998.4    0.07       0  5004.4    0.12       0
  5025.8    0.05       0
Bank Sta=4998.4,5004.4
Exp/Cntr=0.3,0.1

Type RM Length L Ch R = 1,6152,164,164,164
BEGIN DESCRIPTION:
Lacy 001 3341
END DESCRIPTION:
XS GIS Cut Line= 3
      2760690.40      6878010.14      2760192.01      6877911.35
      2759541.63      6878179.03
#Sta/Elev= 30
  4442.4  483.54  4508.1  480.57  4565.3  475.76  4610.0  475.58  4621.6  476.67
  4640.6  476.74  4667.7  475.57  4672.8  476.51  4711.9  475.29  4724.0  476.03
  4762.9  475.56  4877.7  470.37  4923.8  465.87  4945.9  466.96  4968.0  466.06
  4983.5  462.67  4984.5  462.17  4989.6  462.67  4991.9  464.93  5000.2  467.50
  5092.6  467.02  5130.0  468.15  5324.7  469.70  5354.3  471.07  5383.6  471.06
  5407.6  474.04  5484.8  476.23  5497.7  475.46  5530.1  475.45  5653.8  477.13
#Mann=4,-1,0
  4442.4    0.12       0  4983.5    0.07       0  4989.6    0.12       0
  5092.6    0.05       0
Bank Sta=4983.5,4989.6
Exp/Cntr=0.3,0.1