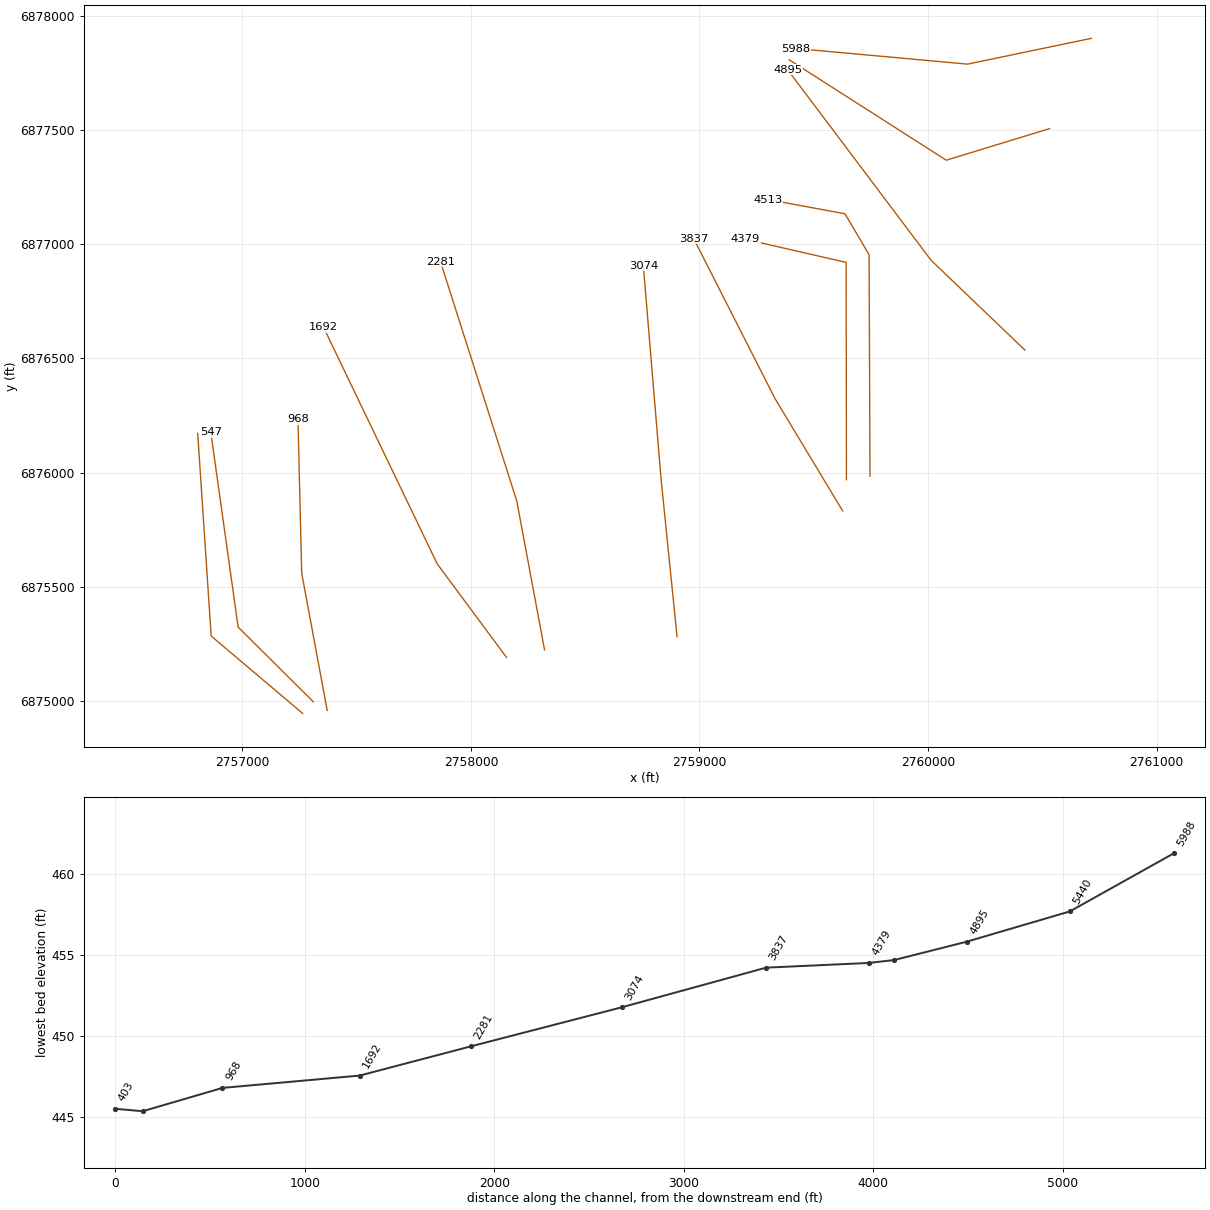
HEC-RAS study Lacy 001.prj: Lacy 001 Base Level Engineering

--- Lacy 001.g01 (geometry) --- (continued)

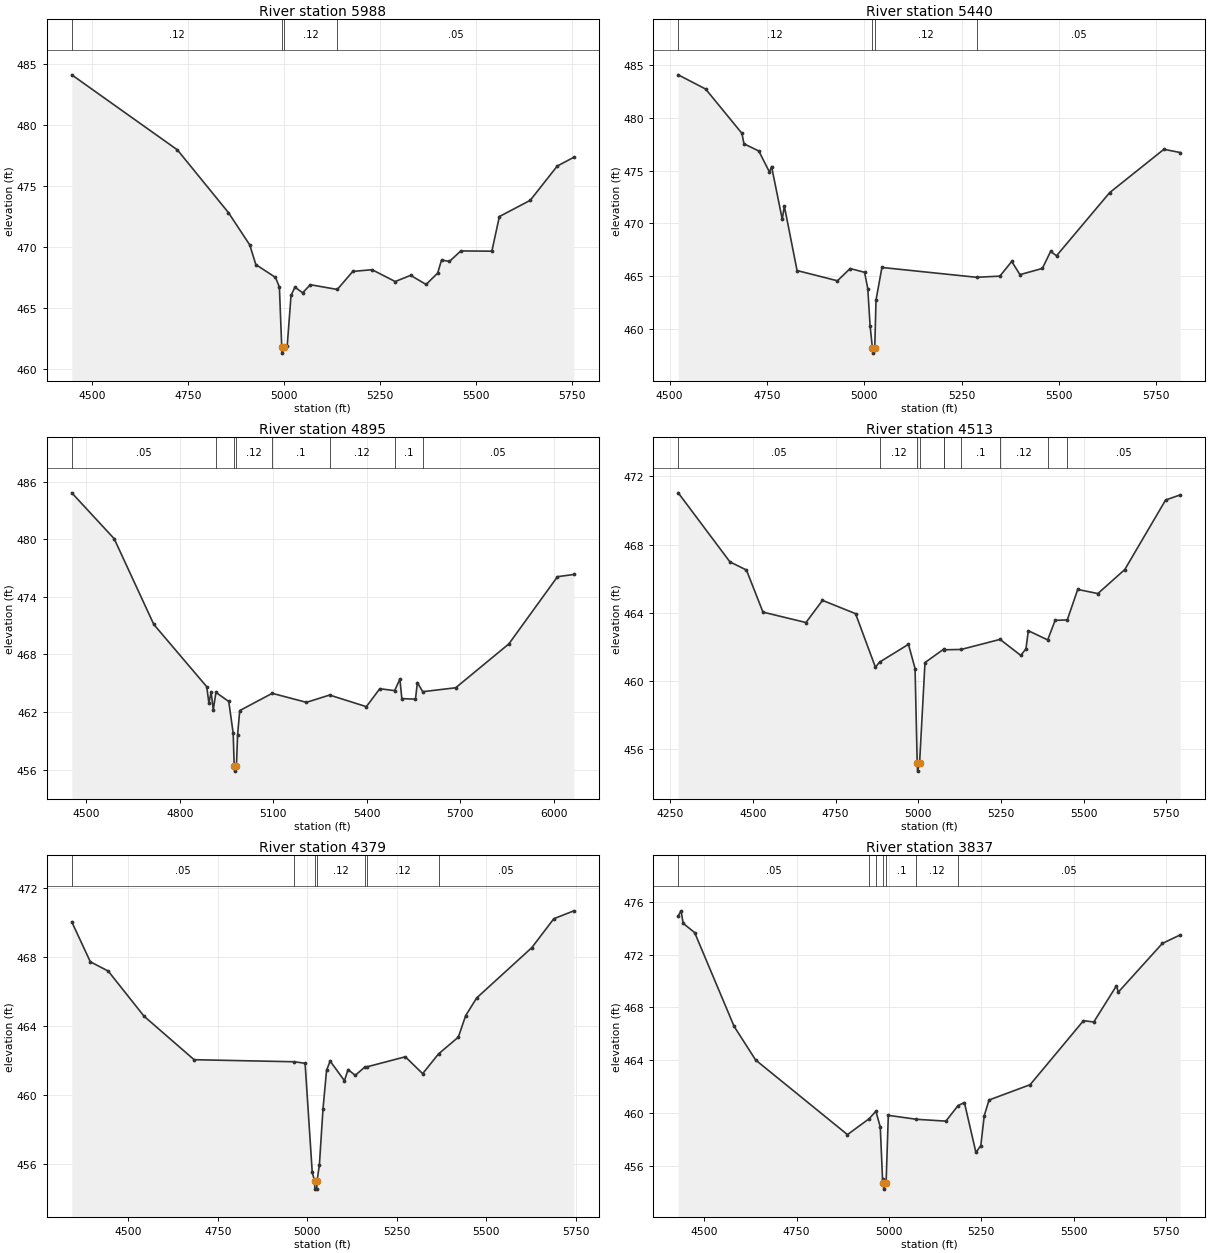
Type RM Length L Ch R = 1,5988,548,548,548
BEGIN DESCRIPTION:
Lacy 001 3340
END DESCRIPTION:
XS GIS Cut Line= 3
      2760715.06      6877900.33      2760173.03      6877787.49
      2759422.98      6877855.75
#Sta/Elev= 30
  4448.0  484.11  4722.8  477.96  4855.6  472.82  4911.3  470.16  4927.1  468.55
  4978.2  467.50  4988.4  466.71  4994.5  461.79  4995.5  461.29  5000.6  461.79
  5008.7  461.86  5018.7  466.02  5028.8  466.70  5048.9  466.24  5069.0  466.90
  5139.1  466.51  5179.4  467.99  5229.6  468.13  5289.9  467.16  5330.0  467.67
  5370.2  466.92  5400.3  467.85  5410.4  468.92  5431.0  468.81  5460.6  469.67
  5541.4  469.65  5561.0  472.49  5641.3  473.82  5711.6  476.63  5754.8  477.35
#Mann=4,-1,0
  4448.0    0.12       0  4994.5    0.07       0  5000.6    0.12       0
  5139.1    0.05       0
Bank Sta=4994.5,5000.6
Exp/Cntr=0.3,0.1

Type RM Length L Ch R = 1,5440,545,545,545
BEGIN DESCRIPTION:
Lacy 001 3298
END DESCRIPTION:
XS GIS Cut Line= 3
      2760532.35      6877505.39      2760080.07      6877367.04
      2759392.48      6877806.68
#Sta/Elev= 30
  4522.4  484.06  4592.9  482.71  4685.9  478.52  4691.2  477.53  4729.2  476.85
  4756.7  474.85  4762.0  475.38  4789.5  470.38  4794.8  471.64  4827.5  465.53
  4931.1  464.56  4963.9  465.72  5000.8  465.36  5009.1  463.82  5015.0  460.30
  5020.9  458.21  5021.9  457.71  5027.0  458.21  5030.2  462.74  5045.4  465.82
  5288.4  464.89  5348.2  465.00  5378.7  466.39  5399.8  465.14  5457.3  465.73
  5478.5  467.34  5493.7  466.93  5629.9  472.90  5769.4  477.01  5811.5  476.70
#Mann=4,-1,0
  4522.4    0.12       0  5020.9    0.07       0  5027.0    0.12       0
  5288.4    0.05       0
Bank Sta=5020.9,5027
Exp/Cntr=0.3,0.1

Type RM Length L Ch R = 1,4895,382,382,382
BEGIN DESCRIPTION:
Lacy 001 3297
END DESCRIPTION:
XS GIS Cut Line= 3
      2760423.96      6876536.39      2760013.74      6876929.00
      2759385.80      6877763.14
#Sta/Elev= 30
  4453.4  484.85  4589.5  480.07  4716.8  471.13  4886.7  464.64  4893.6  462.94
  4900.8  464.08  4907.7  462.24  4916.2  464.05  4957.4  463.10  4971.6  459.80
  4974.9  456.34  4976.0  455.84  4982.0  456.34  4985.7  459.59  4992.6  462.15
  5096.9  463.95  5206.9  463.01  5281.1  463.77  5399.2  462.56  5442.2  464.43
  5489.9  464.23  5506.8  465.43  5513.1  463.40  5556.8  463.34  5563.0  465.07
  5580.1  464.12  5685.9  464.53  5856.6  469.10  6012.8  476.11  6065.3  476.34
#Mann=8,-1,0
  4453.4    0.05       0  4916.2    0.12       0  4974.9    0.07       0
  4982.0    0.12       0  5096.9     0.1       0  5281.1    0.12       0
  5489.9     0.1       0  5580.1    0.05       0
Bank Sta=4974.9,4982
Exp/Cntr=0.3,0.1

Type RM Length L Ch R = 1,4513,134,134,134
BEGIN DESCRIPTION:
Lacy 001 3296
END DESCRIPTION:
XS GIS Cut Line= 4
      2759746.26      6875984.69      2759742.39      6876953.54
      2759636.75      6877132.80      2759300.83      6877194.69
#Sta/Elev= 30
  4274.2  471.04  4430.5  466.99  4480.5  466.51  4530.5  464.04  4660.5  463.43
  4710.5  464.73  4810.5  463.95  4870.5  460.81  4883.4  461.11  4970.5  462.15
  4990.5  460.73  4996.9  455.21  4998.0  454.71  5004.2  455.21  5020.5  461.08
  5076.5  461.86  5079.2  461.83  5129.8  461.85  5247.6  462.44  5310.2  461.50
  5325.9  461.89  5333.0  462.95  5391.6  462.41  5414.2  463.56  5450.8  463.58
  5482.4  465.37  5543.4  465.13  5624.8  466.54  5748.3  470.62  5792.7  470.92
#Mann=10,-1,0
  4274.2    0.05       0  4883.4    0.12       0  4996.9    0.07       0
  5004.2    0.12       0  5076.5     0.1       0  5079.2    0.12       0
  5129.8     0.1       0  5247.6    0.12       0  5391.6     0.1       0
  5450.8    0.05       0
Bank Sta=4996.9,5004.2
Exp/Cntr=0.3,0.1

Type RM Length L Ch R = 1,4379,542,542,542
BEGIN DESCRIPTION:
Lacy 001 3295
END DESCRIPTION:
XS GIS Cut Line= 3
      2759643.17      6875969.22      2759641.95      6876919.91
      2759201.46      6877020.85
#Sta/Elev= 30
  4341.9  470.06  4393.7  467.74  4443.7  467.20  4543.7  464.58  4683.7  462.05
  4964.1  461.93  4993.7  461.84  5013.7  455.50  5020.0  455.03  5021.2  454.53
  5026.2  454.53  5027.3  455.03  5033.7  455.95  5043.7  459.18  5053.7  461.44
  5063.7  461.97  5103.7  460.83  5113.7  461.48  5133.7  461.14  5159.9  461.61
  5165.6  461.63  5273.7  462.22  5322.1  461.24  5366.6  462.39  5421.8  463.36
  5442.3  464.61  5473.1  465.64  5627.0  468.56  5688.5  470.24  5744.5  470.70
#Mann=7,-1,0
  4341.9    0.05       0  4964.1    0.12       0  5020.0    0.07       0
  5027.3    0.12       0  5159.9    0.05       0  5165.6    0.12       0
  5366.6    0.05       0
Bank Sta=5020,5027.3
Exp/Cntr=0.3,0.1

Type RM Length L Ch R = 1,3837,763,763,763
BEGIN DESCRIPTION:
Lacy 001 3346
END DESCRIPTION:
XS GIS Cut Line= 3
      2759626.66      6875832.34      2759330.69      6876323.87
      2758974.57      6877024.39
#Sta/Elev= 30
  4429.6  474.94  4437.2  475.32  4443.1  474.37  4474.1  473.67  4580.9  466.57
  4639.2  464.02  4887.8  458.37  4946.0  459.56  4964.8  460.14  4976.7  458.95
  4982.9  454.97  4985.1  454.74  4986.2  454.24  4992.5  454.74  4998.5  459.83
  5074.7  459.53  5154.4  459.39  5187.4  460.57  5204.5  460.80  5235.7  457.02
  5249.0  457.54  5258.2  459.79  5271.2  460.99  5382.5  462.15  5527.0  467.00
  5554.9  466.90  5616.0  469.63  5621.6  469.17  5740.5  472.85  5789.2  473.50
#Mann=7,-1,0
  4429.6    0.05       0  4946.0    0.12       0  4964.8     0.1       0
  4985.1    0.07       0  4992.5     0.1       0  5074.7    0.12       0
  5187.4    0.05       0
Bank Sta=4985.1,4992.5
Exp/Cntr=0.3,0.1

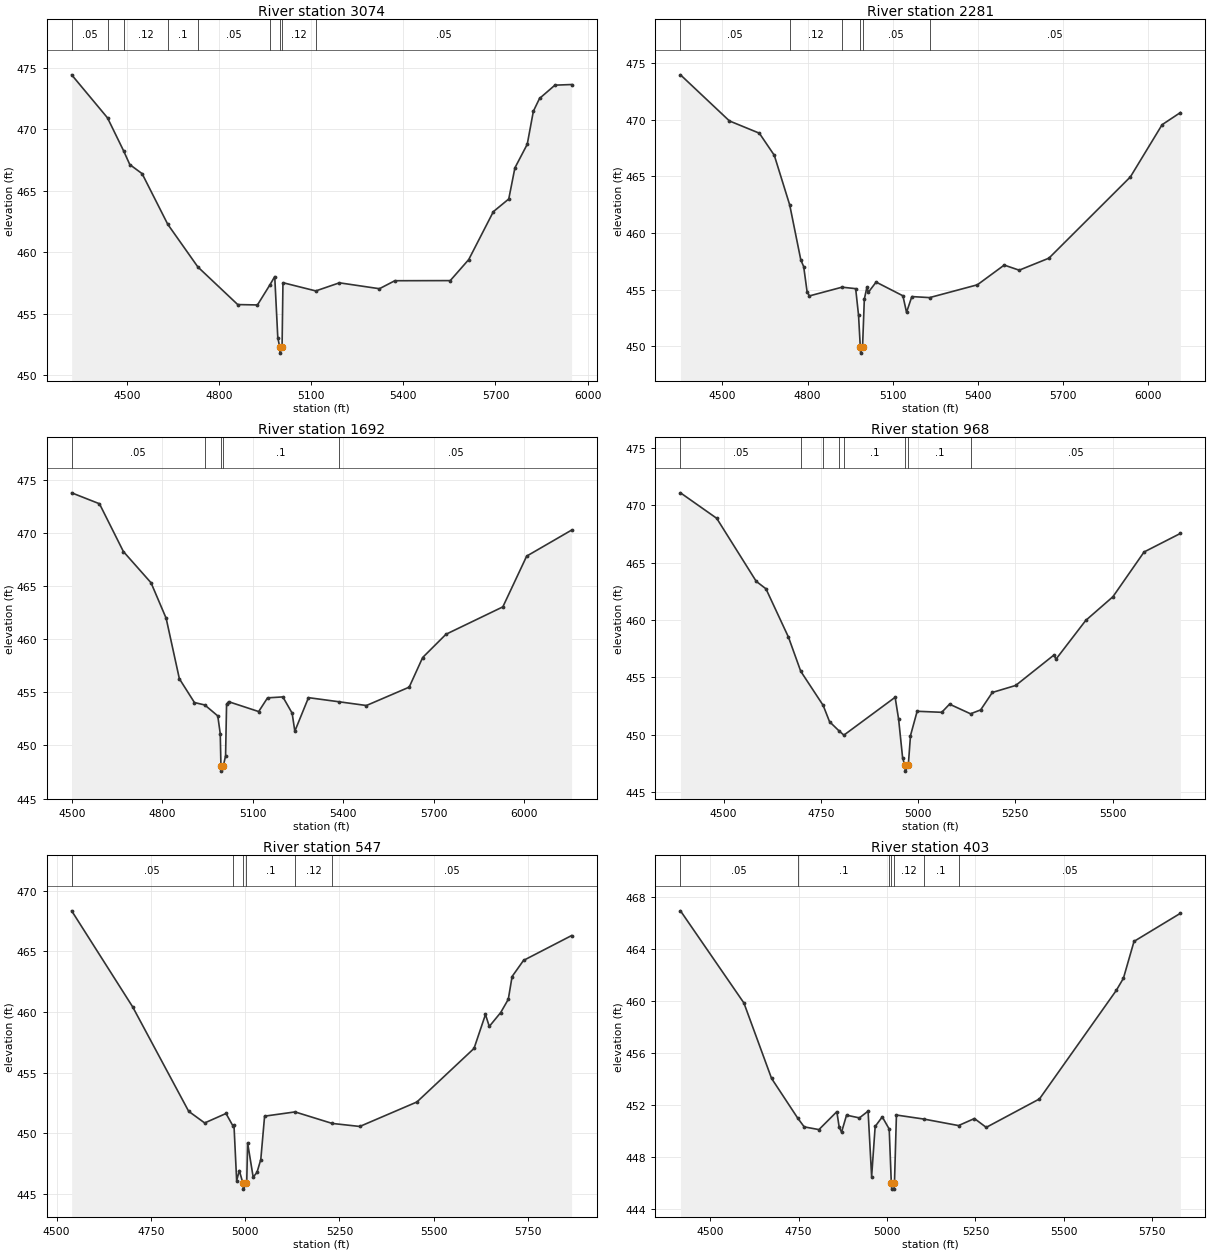
Type RM Length L Ch R = 1,3074,793,793,793
BEGIN DESCRIPTION:
Lacy 001 3281
END DESCRIPTION:
XS GIS Cut Line= 3
      2758901.96      6875282.58      2758832.36      6875969.29
      2758754.49      6876905.12
#Sta/Elev= 30
  4318.8  474.43  4435.6  470.93  4488.4  468.23  4508.2  467.13  4548.4  466.39
  4632.0  462.27  4730.1  458.80  4860.0  455.74  4924.3  455.71  4965.5  457.37
  4980.6  458.02  4990.6  453.05  4996.8  452.29  4998.0  451.79  5004.5  452.29
  5007.4  457.52  5114.4  456.85  5191.4  457.51  5321.8  457.03  5372.0  457.68
  5552.6  457.69  5612.8  459.40  5693.1  463.30  5743.3  464.33  5763.3  466.86
  5803.5  468.78  5823.5  471.47  5843.6  472.51  5893.8  473.59  5948.1  473.64
#Mann=9,-1,0
  4318.8    0.05       0  4435.6     0.1       0  4488.4    0.12       0
  4632.0     0.1       0  4730.1    0.05       0  4965.5    0.12       0
  4996.8    0.07       0  5004.5    0.12       0  5114.4    0.05       0
Bank Sta=4996.8,5004.5
Exp/Cntr=0.3,0.1

Type RM Length L Ch R = 1,2281,589,589,589
BEGIN DESCRIPTION:
Lacy 001 3280
END DESCRIPTION:
XS GIS Cut Line= 3
      2758322.22      6875224.30      2758200.66      6875875.94
      2757866.97      6876922.45
#Sta/Elev= 30
  4352.2  473.95  4524.7  469.88  4630.0  468.80  4682.7  466.85  4737.1  462.46
  4776.1  457.62  4786.3  457.02  4798.3  454.80  4806.6  454.44  4921.4  455.21
  4969.4  455.08  4979.5  452.74  4985.8  449.89  4987.0  449.39  4993.6  449.89
  4999.9  454.15  5009.1  455.22  5014.2  454.76  5041.4  455.66  5135.8  454.45
  5148.6  452.99  5167.3  454.38  5229.9  454.29  5398.2  455.42  5492.7  457.16
  5545.5  456.71  5650.2  457.77  5937.2  464.94  6049.0  469.55  6113.5  470.62
#Mann=6,-1,0
  4352.2    0.05       0  4737.1    0.12       0  4921.4    0.05       0
  4985.8    0.07       0  4993.6    0.05       0  5229.9    0.05       0
Bank Sta=4985.8,4993.6
Exp/Cntr=0.3,0.1

Type RM Length L Ch R = 1,1692,724,724,724
BEGIN DESCRIPTION:
Lacy 001 3279
END DESCRIPTION:
XS GIS Cut Line= 3
      2758155.73      6875191.63      2757852.98      6875599.90
      2757354.72      6876636.60
#Sta/Elev= 30
  4499.6  473.79  4591.8  472.76  4671.2  468.26  4762.9  465.32  4813.0  461.98
  4856.9  456.28  4906.9  454.04  4941.3  453.81  4984.3  452.78  4992.5  451.11
  4994.8  448.08  4996.0  447.58  5002.7  448.08  5010.2  449.02  5013.5  453.89
  5020.2  454.12  5120.0  453.19  5149.4  454.48  5200.2  454.57  5231.0  453.04
  5239.9  451.34  5285.2  454.50  5386.9  454.11  5477.4  453.76  5619.3  455.49
  5664.0  458.28  5741.4  460.47  5930.0  463.05  6009.1  467.83  6158.1  470.28
#Mann=5,-1,0
  4499.6    0.05       0  4941.3     0.1       0  4994.8    0.07       0
  5002.7     0.1       0  5386.9    0.05       0
Bank Sta=4994.8,5002.7
Exp/Cntr=0.3,0.1

Type RM Length L Ch R = 1,968,421,421,421
BEGIN DESCRIPTION:
Lacy 001 3278
END DESCRIPTION:
XS GIS Cut Line= 3
      2757371.09      6874959.51      2757259.61      6875559.46
      2757243.17      6876234.44
#Sta/Elev= 30
  4389.0  471.09  4482.1  468.87  4583.8  463.37  4608.8  462.72  4666.7  458.50
  4698.2  455.53  4755.9  452.55  4772.3  451.13  4797.3  450.31  4809.2  449.96
  4940.9  453.26  4949.9  451.34  4960.1  447.99  4965.8  447.32  4967.1  446.82
  4974.7  447.32  4980.4  449.92  4997.5  452.04  5060.8  451.95  5080.8  452.66
  5134.8  451.82  5160.8  452.16  5190.8  453.68  5250.8  454.29  5349.4  456.95
  5354.4  456.58  5430.9  459.96  5500.9  462.03  5580.9  465.93  5674.4  467.55
#Mann=8,-1,0
  4389.0    0.05       0  4698.2    0.12       0  4755.9    0.05       0
  4797.3    0.12       0  4809.2     0.1       0  4965.8    0.07       0
  4974.7     0.1       0  5134.8    0.05       0
Bank Sta=4965.8,4974.7
Exp/Cntr=0.3,0.1

Type RM Length L Ch R = 1,547,144,144,144
BEGIN DESCRIPTION:
Lacy 001 3277
END DESCRIPTION:
XS GIS Cut Line= 3
      2757310.76      6874996.99      2756981.37      6875324.09
      2756861.68      6876177.22
#Sta/Elev= 30
  4539.9  468.34  4701.6  460.42  4850.2  451.80  4892.6  450.84  4949.2  451.62
  4967.1  450.62  4970.3  450.67  4977.4  446.08  4984.5  446.91  4993.9  445.88
  4995.2  445.38  5002.9  445.88  5004.1  445.88  5006.4  449.21  5021.2  446.37
  5031.3  446.76  5041.4  447.82  5051.5  451.40  5132.2  451.75  5230.8  450.80
  5303.9  450.55  5455.4  452.57  5606.9  456.99  5637.2  459.79  5647.3  458.80
  5677.6  459.95  5697.7  461.04  5707.8  462.92  5738.1  464.25  5865.6  466.30
#Mann=6,-1,0
  4539.9    0.05       0  4967.1     0.1       0  4993.9    0.07       0
  5002.9     0.1       0  5132.2    0.12       0  5230.8    0.05       0
Bank Sta=4993.9,5002.9
Exp/Cntr=0.3,0.1

Type RM Length L Ch R = 1,403,0,0,0
BEGIN DESCRIPTION:
Lacy 001 3276
END DESCRIPTION:
XS GIS Cut Line= 3
      2757263.56      6874946.48      2756863.46      6875284.85
      2756804.44      6876171.79
#Sta/Elev= 30
  4416.3  466.94  4595.6  459.85  4673.7  454.05  4747.2  451.01  4765.9  450.32
  4807.6  450.11  4858.2  451.49  4864.8  450.30  4871.5  449.91  4885.6  451.22
  4922.0  451.01  4946.5  451.53  4956.5  446.49  4966.5  450.35  4986.6  451.09
  5006.2  450.15  5012.1  446.03  5013.4  445.53  5019.8  445.53  5021.1  446.03
  5026.6  451.23  5104.1  450.92  5202.1  450.42  5247.1  450.96  5280.4  450.28
  5430.9  452.47  5648.0  460.82  5668.1  461.75  5698.1  464.59  5829.2  466.75
#Mann=7,-1,0
  4416.3    0.05       0  4747.2     0.1       0  5006.2    0.12       0
  5012.1    0.07       0  5021.1    0.12       0  5104.1     0.1       0
  5202.1    0.05       0
Bank Sta=5012.1,5021.1
Exp/Cntr=0.3,0.1

Chan Stop Cuts=-1