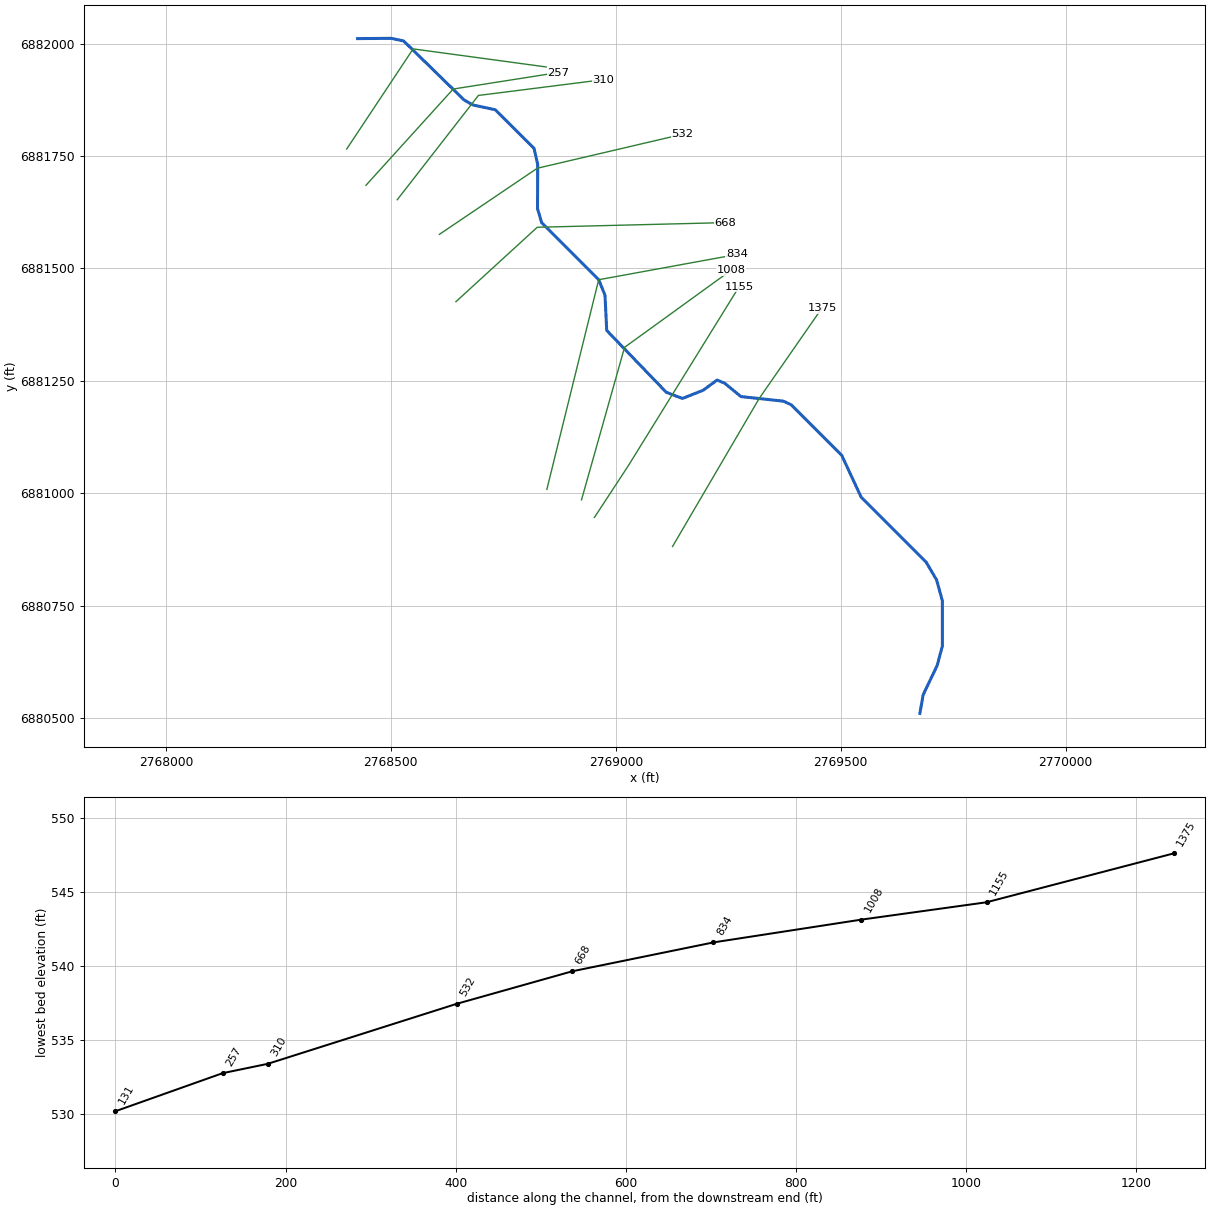
--- Lacy 002.prj (project) ---

Proj Title=Lacy 002 Base Level Engineering
Current Plan=p01
Default Exp/Contr=0.3,0.1
English Units
Geom File=g01
Flow File=f01
Plan File=p01
Y Axis Title=Elevation
X Axis Title(PF)=Main Channel Distance
X Axis Title(XS)=Station
BEGIN DESCRIPTION:
Lacy 002
END DESCRIPTION:
DSS Export Rating Curves= 0
DSS Export Rating Curve Sorted= 0
DSS Export Volume Flow Curves= 0
DXF OffsetX= 0
DXF OffsetY= 0
DXF ScaleX= 1
DXF ScaleY= 10

--- Lacy 002.p01 (plan) ---

Plan Title=Multiple Run
Short Identifier=Multiple
Geom File=g01
Flow File=f01
Subcritical Flow
K Sum by GR= 0
Std Step Tol= 0.01
Critical Tol= 0.01
Num of Std Step Trials= 20
Max Error Tol= 0.3
Flow Tol Ratio= 0.001
Split Flow NTrial= 30
Split Flow Tol= 0.02
Split Flow Ratio= 0.02
Log Output Level= 0
Friction Slope Method= 1
Unsteady Friction Slope Method= 2
Unsteady Bridges Friction Slope Method= 1
Parabolic Critical Depth
Global Vel Dist=  1 , 1 , 1
Global Log Level= 0
CheckData=True
Encroach Param= -1, 0, 0, 0
BEGIN DESCRIPTION:
Multiple Run
END DESCRIPTION:

--- Lacy 002.f01 (steady flow) ---

Flow Title=Multiple
Number of Profiles=7
Profile Names=10-year,25-year,50-year,1pct_min,100-year,1pct_plu,500-year
River Rch & RM= Lacy 002,Reach-1,1375
     117     142     160      90     181     360     229
Boundary for River Rch & Prof#=Lacy 002,Reach-1,1
Up Type=0
Dn Type=3
Dn Slope=0.005
Boundary for River Rch & Prof#=Lacy 002,Reach-1,2
Up Type=0
Dn Type=3
Dn Slope=0.005
Boundary for River Rch & Prof#=Lacy 002,Reach-1,3
Up Type=0
Dn Type=3
Dn Slope=0.005
Boundary for River Rch & Prof#=Lacy 002,Reach-1,4
Up Type=0
Dn Type=3
Dn Slope=0.005
Boundary for River Rch & Prof#=Lacy 002,Reach-1,5
Up Type=0
Dn Type=3
Dn Slope=0.005
Boundary for River Rch & Prof#=Lacy 002,Reach-1,6
Up Type=0
Dn Type=3
Dn Slope=0.005
Boundary for River Rch & Prof#=Lacy 002,Reach-1,7
Up Type=0
Dn Type=3
Dn Slope=0.005

--- Lacy 002.g01 (geometry) ---

Geom Title=Existing Conditions
Program Version=4.10

River Reach=Lacy 002        ,Reach-1
Reach XY= 30
        2769676.        6880511.      2769683.23      6880552.18
      2769714.62       6880617.9        2769726.        6880661.
        2769726.        6880761.      2769713.23       6880807.5
      2769690.06      6880846.94      2769545.52      6880991.48
      2769502.13      6881084.87        2769390.        6881197.
      2769372.44      6881205.07      2769278.28      6881215.21
      2769242.21      6881244.79      2769225.14      6881251.99
      2769194.44      6881229.44      2769148.07        6881211.
      2769112.25      6881224.75      2768979.83      6881362.26
        2768976.      6881440.64      2768962.01      6881474.99
      2768835.21      6881601.79        2768826.      6881633.29
      2768826.43      6881731.18       2768818.2      6881767.21
      2768732.07      6881852.85      2768682.05      6881863.54
      2768662.79      6881874.63       2768528.5      6882005.65
      2768501.25      6882011.59        2768426.        6882011.

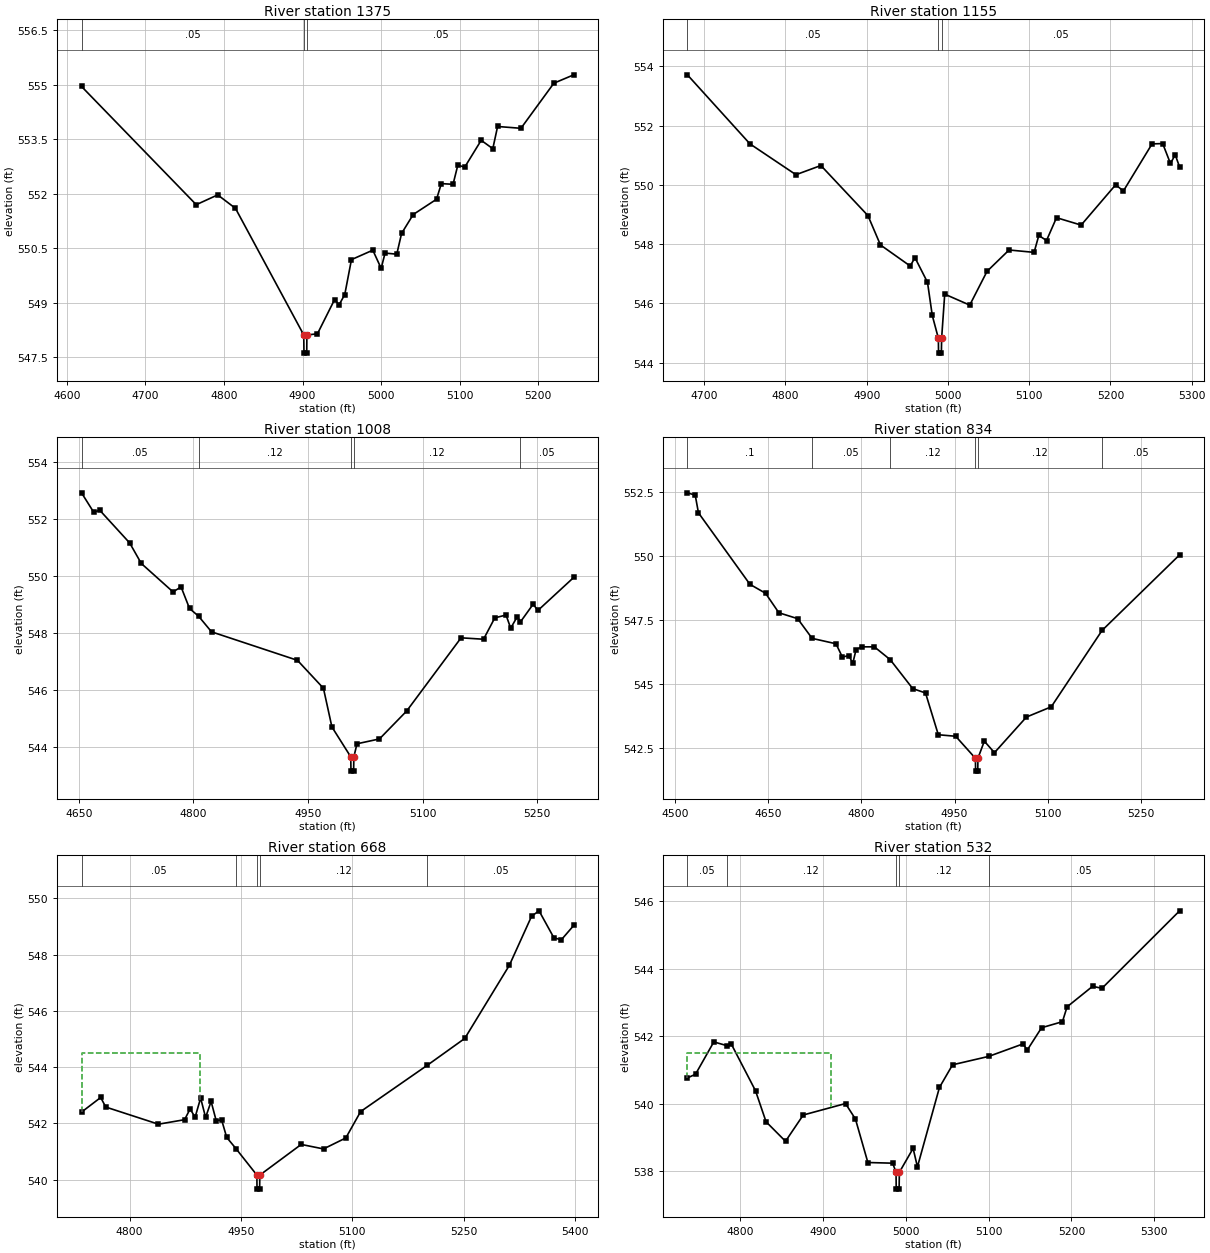
Type RM Length L Ch R = 1 ,1375    ,220,220,220
BEGIN DESCRIPTION:
Lacy 002 3453
END DESCRIPTION:
XS GIS Cut Line= 3
      2769126.14      6880881.91      2769318.73        6881211.
      2769458.58      6881412.29
#Sta/Elev= 30
  4618.7  554.95  4764.7   551.7    4792  551.97  4814.6   551.6  4901.5  548.12
  4901.8  547.62  4905.3  547.62  4905.5  548.12  4918.9  548.15  4940.7  549.09
  4946.5  548.95  4953.7  549.23  4962.2  550.19  4989.4  550.45    5000  549.95
    5005  550.37  5019.9  550.34    5026  550.91  5040.8  551.43  5070.5  551.85
  5076.6  552.28  5091.5  552.26  5097.6  552.79  5106.3  552.73  5127.3  553.47
  5142.1  553.24  5148.2  553.85  5177.9   553.8  5219.8  555.04  5245.1  555.27
#Mann= 3 ,-1 , 0
  4618.7     .05       0  4901.5     .05       0  4905.5     .05       0
Bank Sta=4901.5,4905.5
XS Rating Curve= 0 ,0
Exp/Cntr=0.3,0.1

Type RM Length L Ch R = 1 ,1155    ,147,147,147
BEGIN DESCRIPTION:
Lacy 002 3440
END DESCRIPTION:
XS GIS Cut Line= 3
      2768952.51      6880946.61      2769027.35      6881060.73
      2769274.35      6881459.81
#Sta/Elev= 30
  4679.4  553.71  4756.4  551.38    4813  550.34  4843.7  550.65  4901.6  548.96
    4917  547.97  4953.6  547.26  4959.5  547.54  4974.9  546.71  4980.8  545.59
  4988.3  544.82  4988.5  544.32    4992  544.32  4992.3  544.82  4996.1  546.31
  5026.9  545.94  5048.2  547.08  5075.3   547.8  5106.1  547.72  5111.9  548.29
  5121.4  548.12  5133.7  548.89    5164  548.64  5206.5     550    5216  549.79
  5251.3  551.38  5264.4  551.39  5273.9  550.72  5279.8  551.01  5285.2   550.6
#Mann= 3 ,-1 , 0
  4679.4     .05       0  4988.3     .05       0  4992.3     .05       0
Bank Sta=4988.3,4992.3
XS Rating Curve= 0 ,0
Exp/Cntr=0.3,0.1

Type RM Length L Ch R = 1 ,1008    ,174,174,174
BEGIN DESCRIPTION:
Lacy 002 3439
END DESCRIPTION:
XS GIS Cut Line= 3
      2768923.81      6880985.71       2769019.5       6881324.7
      2769255.87      6881495.75
#Sta/Elev= 30
  4653.6  552.92  4669.5  552.24  4677.4  552.31  4716.6  551.16  4731.8  550.44
  4773.4  549.44  4783.8  549.62  4794.9  548.86  4806.7  548.59  4823.7  548.04
  4936.1  547.04  4970.1  546.06  4981.2   544.7  5005.9  543.65  5006.1  543.15
  5009.6  543.15  5009.9  543.65    5014  544.11  5043.4  544.28    5079  545.26
  5150.2  547.83  5179.6  547.78  5194.3  548.53    5209  548.63  5215.1  548.17
  5223.7  548.57  5227.9  548.39  5244.5  549.01  5250.7  548.79  5297.6  549.95
#Mann= 5 ,-1 , 0
  4653.6     .05       0  4806.7     .12       0  5005.9     .07       0
  5009.9     .12       0  5227.9     .05       0
Bank Sta=5005.9,5009.9
XS Rating Curve= 0 ,0
Exp/Cntr=0.3,0.1

Type RM Length L Ch R = 1 ,834     ,166,166,166
BEGIN DESCRIPTION:
Lacy 002 3438
END DESCRIPTION:
XS GIS Cut Line= 3
      2768846.71      6881008.74      2768962.01      6881474.99
      2769269.32      6881531.15
#Sta/Elev= 30
  4519.7  552.47  4532.3  552.38  4537.5  551.69  4620.4   548.9  4645.6  548.55
    4667  547.79  4697.2  547.56  4720.6  546.79    4759  546.58  4769.3  546.06
  4779.6  546.12  4786.1  545.82  4791.3  546.35  4800.2  546.46  4820.8  546.46
  4846.3  545.96  4882.6  544.83  4903.2  544.66  4923.8  543.03  4951.8  542.97
  4983.6  542.11  4983.8  541.61  4987.3  541.61  4987.6  542.11  4997.9  542.78
  5014.2  542.33  5065.7  543.72  5105.7  544.12  5187.5   547.1  5312.4  550.05
#Mann= 6 ,-1 , 0
  4519.7      .1       0  4720.6     .05       0  4846.3     .12       0
  4983.6     .07       0  4987.6     .12       0  5187.5     .05       0
Bank Sta=4983.6,4987.6
XS Rating Curve= 0 ,0
Exp/Cntr=0.3,0.1

Type RM Length L Ch R = 1 ,668     ,136,136,136
BEGIN DESCRIPTION:
Lacy 002 3437
END DESCRIPTION:
XS GIS Cut Line= 3
      2768644.61      6881426.13      2768825.41      6881591.61
      2769242.69      6881601.93
#Sta/Elev= 30
  4735.4   542.4  4761.2  542.92    4768  542.58  4838.9  541.97  4874.1  542.13
  4881.5  542.51  4888.3  542.22  4895.7   542.9  4902.4  542.21  4909.8  542.78
  4916.6   542.1    4924  542.12  4930.8   541.5  4943.3   541.1  4971.4  540.16
  4971.6  539.66  4975.1  539.66  4975.4  540.16  5031.1  541.25  5061.1  541.09
  5091.1  541.48  5111.1  542.42    5201  544.07  5251.2  545.02  5311.2  547.62
  5341.2  549.37  5351.2  549.56  5371.2   548.6  5381.2  548.53  5397.9  549.04
#Mann= 5 ,-1 , 0
  4735.4     .05       0  4943.3     .12       0  4971.4     .07       0
  4975.4     .12       0    5201     .05       0
#XS Ineff= 2 , 0
       0    4895   544.5               0
Permanent Ineff=
       F       F
Bank Sta=4971.4,4975.4
XS Rating Curve= 0 ,0
Exp/Cntr=0.3,0.1

Type RM Length L Ch R = 1 ,532     ,222,222,222
BEGIN DESCRIPTION:
Lacy 002 3436
END DESCRIPTION:
XS GIS Cut Line= 3
       2768607.9      6881575.84      2768825.47      6881722.79
      2769148.21      6881798.31
#Sta/Elev= 30
  4736.5  540.76  4746.3  540.87  4768.4  541.83  4783.9  541.72  4789.4  541.77
  4818.7  540.38  4831.4  539.46  4854.9  538.88  4876.3  539.66  4927.3     540
  4939.3  539.54  4954.3  538.25  4984.2  538.23  4988.3  537.96  4988.5  537.46
    4992  537.46  4992.3  537.96  5008.9  538.67  5014.1  538.12  5040.7  540.48
  5056.5  541.15  5100.2   541.4  5141.5  541.77  5146.7  541.59  5163.9  542.25
  5189.1  542.43  5194.7  542.87  5225.5  543.48  5236.8  543.42  5330.5  545.72
#Mann= 5 ,-1 , 0
  4736.5     .05       0  4783.9     .12       0  4988.3     .07       0
  4992.3     .12       0  5100.2     .05       0
#XS Ineff= 2 , 0
       0    4910   541.5               0
Permanent Ineff=
       F       F
Bank Sta=4988.3,4992.3
XS Rating Curve= 0 ,0
Exp/Cntr=0.3,0.1

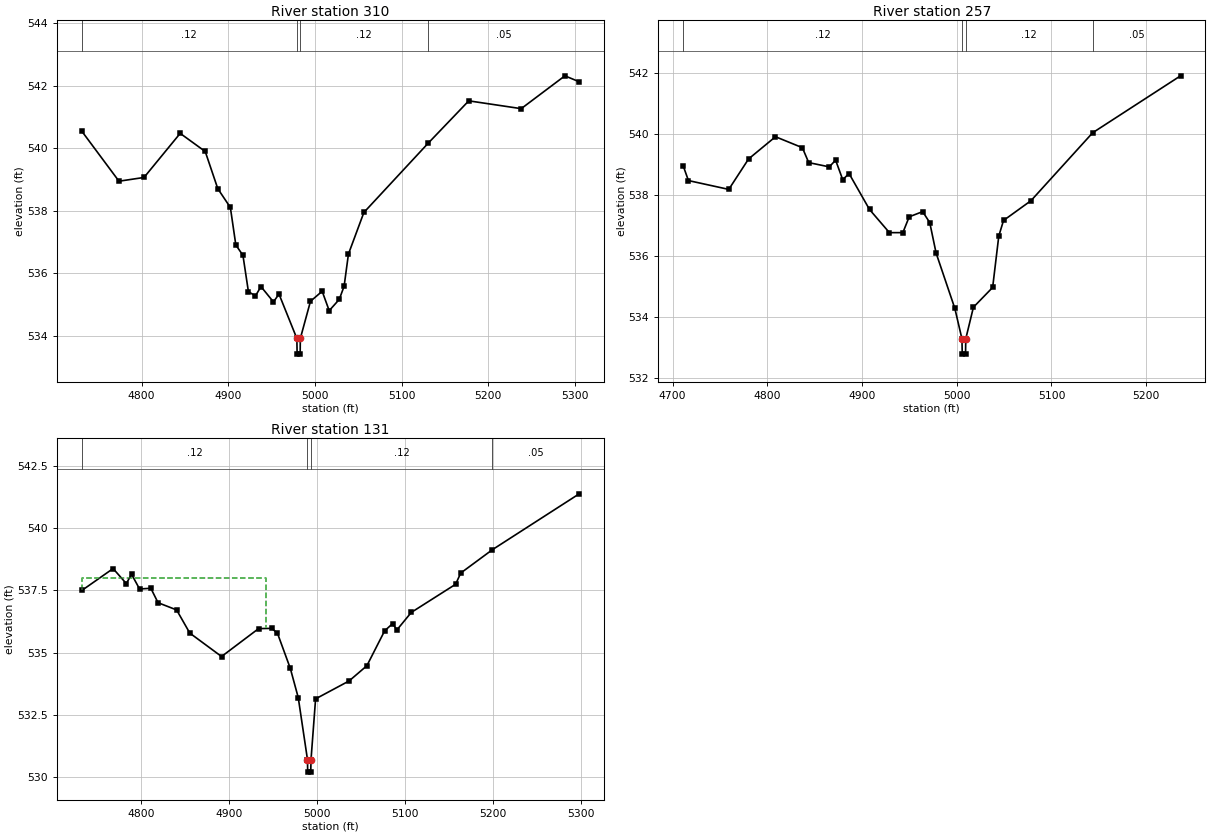
Type RM Length L Ch R = 1 ,310     ,53,53,53
BEGIN DESCRIPTION:
Lacy 002 3514
END DESCRIPTION:
XS GIS Cut Line= 3
      2768514.19      6881652.77      2768694.54       6881884.6
       2768972.4      6881919.74
#Sta/Elev= 30
    4731  540.54  4773.9  538.94  4802.8  539.06  4844.5  540.47  4873.4  539.89
  4887.9   538.7  4902.4   538.1  4908.7   536.9  4916.9  536.57  4923.2  535.41
  4931.3  535.27  4937.7  535.57  4952.1  535.08  4958.5  535.33  4979.1  533.91
  4979.4  533.41  4982.9  533.41  4983.1  533.91  4994.8   535.1  5008.3  535.42
  5016.4   534.8    5028  535.16  5033.6  535.58  5038.6  536.61  5056.4  537.94
  5130.4  540.15  5177.4  541.51  5237.9  541.26  5288.3  542.31  5304.8  542.12
#Mann= 4 ,-1 , 0
    4731     .12       0  4979.1     .07       0  4983.1     .12       0
  5130.4     .05       0
Bank Sta=4979.1,4983.1
XS Rating Curve= 0 ,0
Exp/Cntr=0.3,0.1

Type RM Length L Ch R = 1 ,257     ,126,126,126
BEGIN DESCRIPTION:
Lacy 002 3434
END DESCRIPTION:
XS GIS Cut Line= 3
      2768444.57      6881684.83      2768638.58      6881898.89
      2768872.02      6881935.53
#Sta/Elev= 30
  4711.1  538.97  4716.7  538.48  4759.3  538.19  4780.2  539.19  4808.6  539.92
    4837  539.56  4843.7  539.07  4865.4  538.93  4872.1  539.15  4879.6  538.51
  4886.3  538.71  4907.9  537.53  4928.9  536.77  4943.1  536.77  4949.8  537.29
    4964  537.46  4971.5   537.1  4978.2   536.1    4998  534.28  5005.5  533.28
  5005.8  532.78  5009.3  532.78  5009.5  533.28  5017.6  534.32  5037.9  534.97
  5044.4  536.66  5049.4  537.17  5078.4  537.82  5143.5  540.05  5236.3  541.92
#Mann= 4 ,-1 , 0
  4711.1     .12       0  5005.5     .07       0  5009.5     .12       0
  5143.5     .05       0
Bank Sta=5005.5,5009.5
XS Rating Curve= 0 ,0
Exp/Cntr=0.3,0.1

Type RM Length L Ch R = 1 ,131     ,0,0,0
BEGIN DESCRIPTION:
Lacy 002 3433
END DESCRIPTION:
XS GIS Cut Line= 3
      2768401.83      6881765.57      2768549.52      6881988.12
      2768845.21      6881947.99
#Sta/Elev= 30
  4732.9   537.5  4768.5  538.38  4783.5  537.78  4789.5  538.15  4798.6  537.56
  4811.4  537.59  4819.6  537.01  4840.7  536.72  4855.7  535.79  4891.8  534.85
  4933.9  535.97  4948.9  535.98  4955.4  535.78    4970  534.37    4979   533.2
  4989.5  530.71  4989.7  530.21  4993.2  530.21  4993.5  530.71  4998.7  533.15
  5036.8  533.87    5057  534.48  5077.2  535.88  5086.2  536.17  5091.2  535.92
  5107.5  536.62  5157.9  537.75  5163.7   538.2  5199.8  539.14  5298.4  541.38
#Mann= 4 ,-1 , 0
  4732.9     .12       0  4989.5     .07       0  4993.5     .12       0
  5199.8     .05       0
#XS Ineff= 2 , 0
       0    4942     538               0
Permanent Ineff=
       F       F
Bank Sta=4989.5,4993.5
XS Rating Curve= 0 ,0
Exp/Cntr=0.3,0.1

Chan Stop Cuts=-1
Use User Specified Reach Order=0
Composite Channel Slope=5