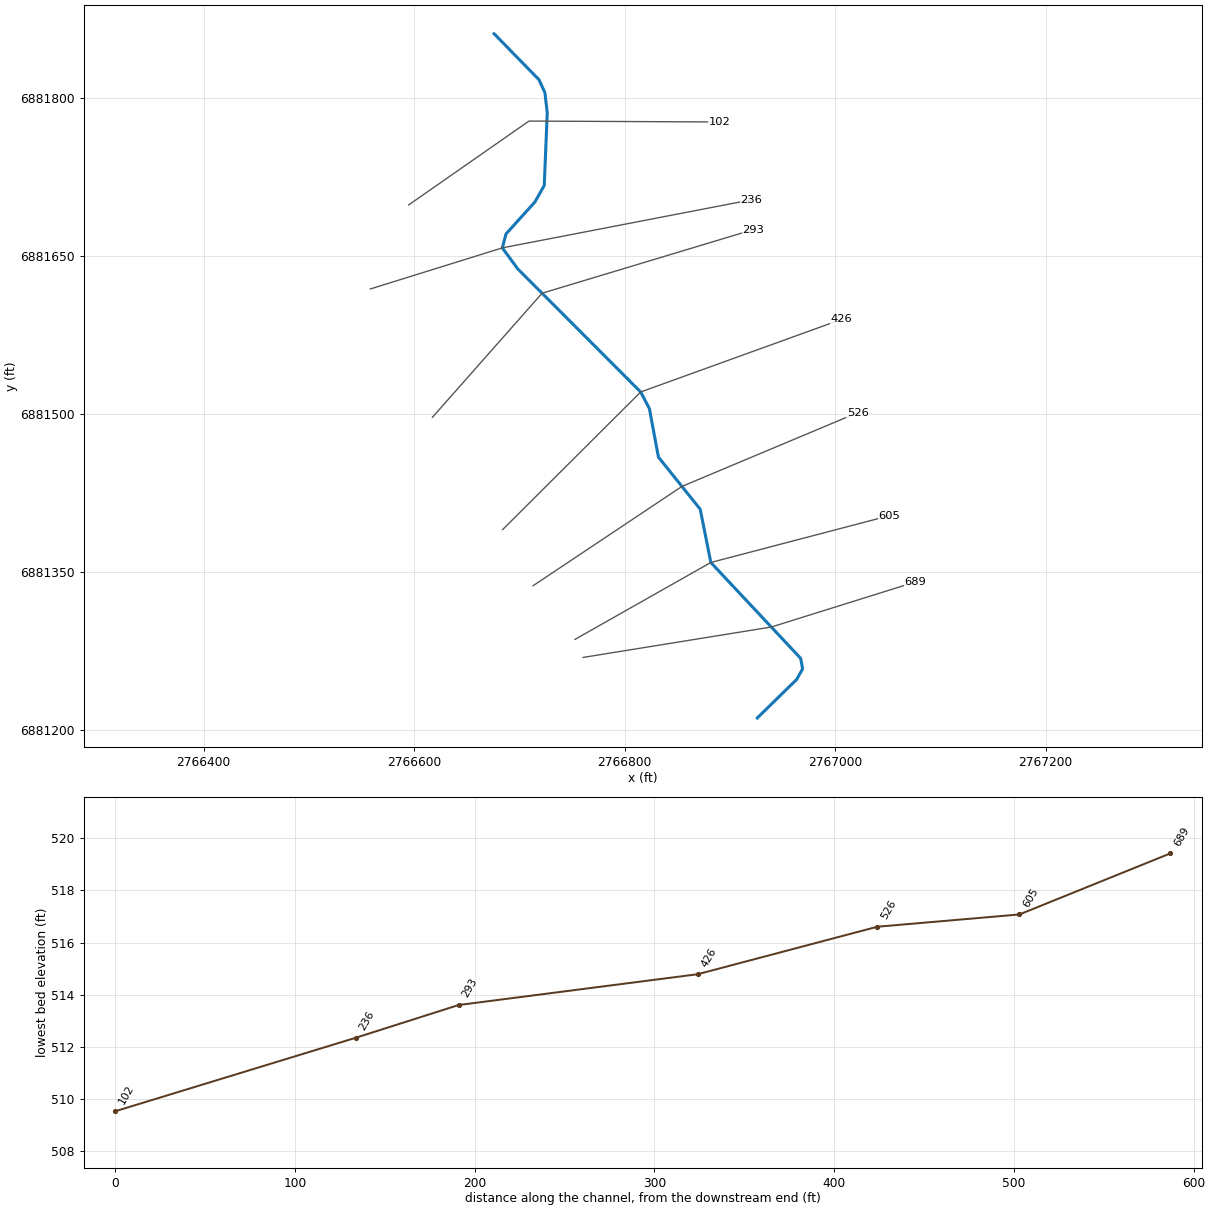
--- Lacy 003.prj (project) ---

Proj Title=Lacy 003 Base Level Engineering
Current Plan=p01
Default Exp/Contr=0.3,0.1
English Units
Geom File=g01
Flow File=f01
Plan File=p01
BEGIN DESCRIPTION:
Lacy 003
END DESCRIPTION:

--- Lacy 003.p01 (plan) ---

Plan Title=Multiple Run
Short Identifier=Multiple
Geom File=g01
Flow File=f01
Subcritical Flow
K Sum by GR= 0
Std Step Tol= 0.01
Critical Tol= 0.01
Num of Std Step Trials= 20
Max Error Tol= 0.3
Flow Tol Ratio= 0.001
Split Flow NTrial= 30
Split Flow Tol= 0.02
Split Flow Ratio= 0.02
Log Output Level= 0
Friction Slope Method= 1
Unsteady Friction Slope Method= 2
Unsteady Bridges Friction Slope Method= 1
Parabolic Critical Depth
Global Vel Dist=  1 , 1 , 1
Global Log Level= 0
CheckData=True
Encroach Param= -1, 0, 0, 0
BEGIN DESCRIPTION:
Multiple Run
END DESCRIPTION:

--- Lacy 003.f01 (steady flow) ---

Flow Title=Multiple
Number of Profiles=7
Profile Names=10-year,25-year,50-year,1pct_min,100-year,1pct_plu,500-year
River Rch & RM= Lacy 003,Reach-1,689
     174     217     249     143     285     569     373
Boundary for River Rch & Prof#=Lacy 003,Reach-1,1
Up Type=0
Dn Type=3
Dn Slope=0.005
Boundary for River Rch & Prof#=Lacy 003,Reach-1,2
Up Type=0
Dn Type=3
Dn Slope=0.005
Boundary for River Rch & Prof#=Lacy 003,Reach-1,3
Up Type=0
Dn Type=3
Dn Slope=0.005
Boundary for River Rch & Prof#=Lacy 003,Reach-1,4
Up Type=0
Dn Type=3
Dn Slope=0.005
Boundary for River Rch & Prof#=Lacy 003,Reach-1,5
Up Type=0
Dn Type=3
Dn Slope=0.005
Boundary for River Rch & Prof#=Lacy 003,Reach-1,6
Up Type=0
Dn Type=3
Dn Slope=0.005
Boundary for River Rch & Prof#=Lacy 003,Reach-1,7
Up Type=0
Dn Type=3
Dn Slope=0.005

--- Lacy 003.g01 (geometry) ---

Geom Title=Existing Conditions

River Reach=Lacy 003,Reach-1
Reach XY= 18
      2766926.00      6881211.00      2766963.49      6881247.66
      2766969.04      6881257.66      2766967.21      6881267.66
      2766881.86      6881358.70      2766871.81      6881409.27
      2766832.10      6881458.81      2766823.50      6881504.96
      2766815.23      6881520.68      2766698.45      6881637.64
      2766683.79      6881657.58      2766687.33      6881670.85
      2766714.80      6881701.21      2766723.63      6881716.88
      2766726.47      6881786.00      2766724.22      6881805.16
      2766718.64      6881817.32      2766676.00      6881861.00

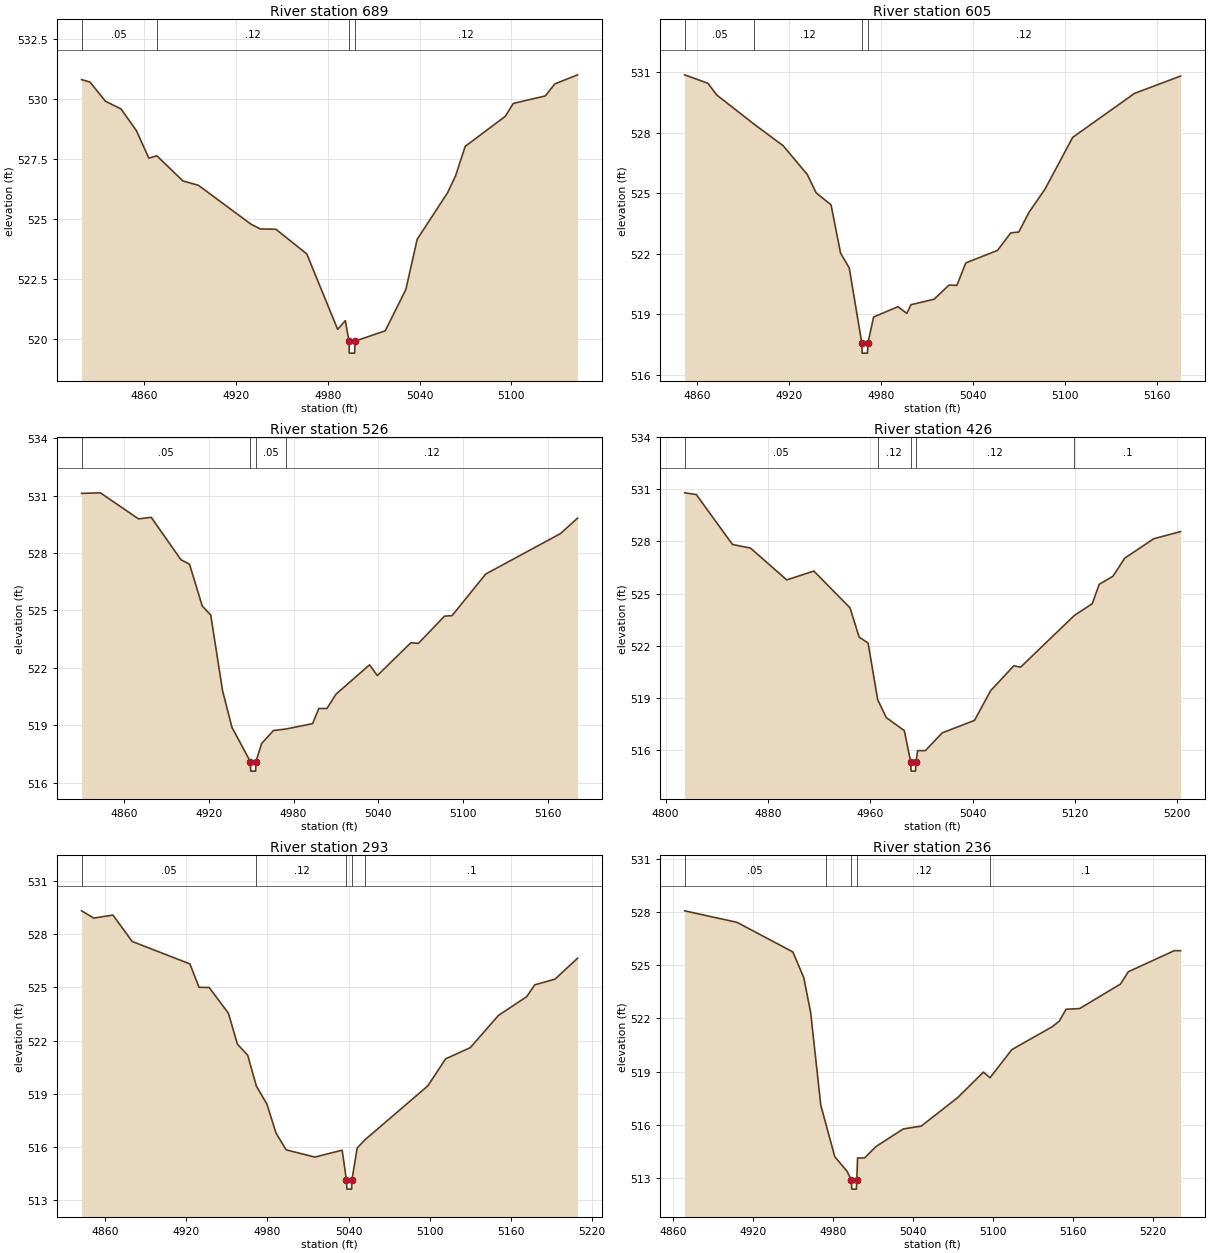
Type RM Length L Ch R = 1,689,84,84,84
BEGIN DESCRIPTION:
Lacy 003 3423
END DESCRIPTION:
XS GIS Cut Line= 3
      2766760.55      6881268.51      2766939.34      6881297.39
      2767076.10      6881340.16
#Sta/Elev= 30
  4818.9  530.81  4824.4  530.71  4834.5  529.91  4844.7  529.59  4854.8  528.68
  4862.9  527.54  4868.1  527.64  4885.2  526.59  4895.3  526.41  4929.7  524.79
  4935.8  524.59  4946.0  524.58  4966.2  523.55  4986.4  520.41  4991.4  520.77
  4993.8  519.92  4994.0  519.42  4997.5  519.42  4997.8  519.92  5017.5  520.35
  5031.0  522.07  5038.4  524.16  5058.2  526.09  5063.5  526.80  5069.8  528.03
  5096.0  529.28  5101.3  529.82  5122.2  530.13  5128.4  530.63  5143.3  531.01
#Mann=4,-1,0
  4818.9    0.05       0  4868.1    0.12       0  4993.8    0.07       0
  4997.8    0.12       0
Bank Sta=4993.8,4997.8
Exp/Cntr=0.3,0.1

Type RM Length L Ch R = 1,605,79,79,79
BEGIN DESCRIPTION:
Lacy 003 3422
END DESCRIPTION:
XS GIS Cut Line= 3
      2766752.80      6881285.64      2766881.86      6881358.70
      2767051.72      6881403.22
#Sta/Elev= 30
  4851.7  530.87  4866.9  530.45  4872.7  529.87  4897.3  528.41  4916.0  527.36
  4931.8  525.93  4937.6  525.02  4947.3  524.43  4953.5  522.04  4959.2  521.30
  4967.4  517.58  4967.6  517.08  4971.1  517.08  4971.4  517.58  4975.1  518.87
  4991.0  519.38  4996.8  519.05  4999.5  519.48  5014.6  519.75  5024.3  520.45
  5029.5  520.44  5035.3  521.55  5056.0  522.17  5064.7  523.04  5069.9  523.08
  5076.6  524.06  5087.0  525.20  5105.1  527.77  5145.5  529.95  5175.6  530.81
#Mann=4,-1,0
  4851.7    0.05       0  4897.3    0.12       0  4967.4    0.07       0
  4971.4    0.12       0
Bank Sta=4967.4,4971.4
Exp/Cntr=0.3,0.1

Type RM Length L Ch R = 1,526,100,100,100
BEGIN DESCRIPTION:
Lacy 003 3421
END DESCRIPTION:
XS GIS Cut Line= 3
      2766713.01      6881336.61      2766854.42      6881430.97
      2767021.31      6881501.02
#Sta/Elev= 30
  4830.0  531.11  4843.3  531.14  4870.3  529.78  4879.3  529.86  4900.3  527.65
  4906.4  527.41  4915.4  525.23  4921.4  524.76  4929.8  520.80  4936.4  518.90
  4949.4  517.11  4949.7  516.61  4953.2  516.61  4953.4  517.11  4957.4  518.05
  4965.8  518.73  4974.7  518.81  4993.5  519.09  4997.9  519.88  5003.6  519.88
  5010.1  520.63  5033.8  522.16  5039.3  521.60  5063.0  523.31  5068.4  523.28
  5086.8  524.70  5092.2  524.73  5116.0  526.90  5168.9  529.01  5181.0  529.82
#Mann=4,-1,0
  4830.0    0.05       0  4949.4    0.07       0  4953.4    0.05       0
  4974.7    0.12       0
Bank Sta=4949.4,4953.4
Exp/Cntr=0.3,0.1

Type RM Length L Ch R = 1,426,133,133,133
BEGIN DESCRIPTION:
Lacy 003 3420
END DESCRIPTION:
XS GIS Cut Line= 3
      2766684.16      6881389.99      2766815.23      6881520.68
      2767005.77      6881589.54
#Sta/Elev= 30
  4814.9  530.80  4824.0  530.70  4852.3  527.83  4866.4  527.62  4894.7  525.79
  4915.9  526.30  4944.2  524.18  4951.3  522.50  4958.3  522.16  4965.8  518.90
  4972.5  517.87  4986.6  517.12  4991.7  515.29  4991.9  514.79  4995.4  514.79
  4995.7  515.29  4997.0  515.97  5003.1  515.97  5016.2  516.99  5041.5  517.71
  5054.0  519.41  5072.2  520.85  5077.5  520.77  5119.6  523.75  5133.5  524.42
  5139.0  525.54  5149.7  526.00  5158.9  527.04  5181.6  528.16  5202.6  528.57
#Mann=5,-1,0
  4814.9    0.05       0  4965.8    0.12       0  4991.7    0.07       0
  4995.7    0.12       0  5119.6     0.1       0
Bank Sta=4991.7,4995.7
Exp/Cntr=0.3,0.1

Type RM Length L Ch R = 1,293,57,57,57
BEGIN DESCRIPTION:
Lacy 003 3419
END DESCRIPTION:
XS GIS Cut Line= 3
      2766617.39      6881496.63      2766721.57      6881614.49
      2766921.97      6881674.87
#Sta/Elev= 30
  4842.7  529.33  4851.7  528.92  4865.9  529.09  4880.1  527.60  4922.8  526.33
  4929.5  525.01  4937.0  525.00  4951.2  523.55  4957.9  521.80  4965.5  521.17
  4971.9  519.43  4979.7  518.41  4986.4  516.78  4993.9  515.83  5015.1  515.42
  5035.3  515.81  5038.5  514.11  5038.8  513.61  5042.3  513.61  5042.5  514.11
  5046.4  515.93  5052.2  516.40  5098.6  519.44  5111.8  520.97  5130.0  521.60
  5150.8  523.42  5171.7  524.48  5177.7  525.15  5192.6  525.47  5209.3  526.65
#Mann=5,-1,0
  4842.7    0.05       0  4971.9    0.12       0  5038.5    0.07       0
  5042.5    0.12       0  5052.2     0.1       0
Bank Sta=5038.5,5042.5
Exp/Cntr=0.3,0.1

Type RM Length L Ch R = 1,236,134,134,134
BEGIN DESCRIPTION:
Lacy 003 3418
END DESCRIPTION:
XS GIS Cut Line= 3
      2766558.43      6881618.55      2766683.79      6881657.58
      2766920.43      6881703.25
#Sta/Elev= 30
  4868.7  528.08  4908.0  527.43  4949.9  525.76  4958.1  524.31  4963.3  522.33
  4970.9  517.10  4974.5  516.10  4981.4  514.19  4990.6  513.37  4993.9  512.86
  4994.1  512.36  4997.6  512.36  4997.9  512.86  4998.5  514.12  5003.7  514.12
  5012.4  514.77  5032.8  515.76  5046.3  515.92  5073.5  517.52  5093.0  518.97
  5097.9  518.65  5114.3  520.24  5144.8  521.54  5149.9  521.85  5155.0  522.52
  5165.2  522.56  5195.8  523.94  5201.8  524.64  5236.2  525.83  5241.0  525.83
#Mann=5,-1,0
  4868.7    0.05       0  4974.5    0.12       0  4993.9    0.07       0
  4997.9    0.12       0  5097.9     0.1       0
Bank Sta=4993.9,4997.9
Exp/Cntr=0.3,0.1

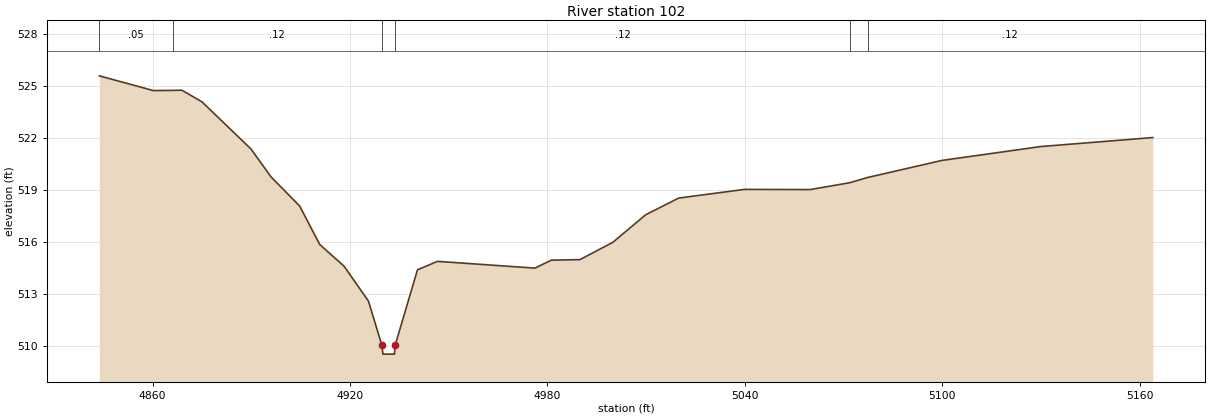
Type RM Length L Ch R = 1,102,0,0,0
BEGIN DESCRIPTION:
Lacy 003 3417
END DESCRIPTION:
XS GIS Cut Line= 3
      2766594.94      6881698.45      2766709.11      6881778.04
      2766890.14      6881777.18
#Sta/Elev= 30
  4843.8  525.59  4860.2  524.74  4866.1  524.75  4868.9  524.76  4875.0  524.09
  4889.9  521.37  4896.0  519.76  4904.7  518.08  4910.8  515.86  4918.2  514.61
  4925.6  512.60  4929.7  510.04  4930.0  509.54  4933.5  509.54  4933.7  510.04
  4940.5  514.40  4946.6  514.89  4976.2  514.50  4981.2  514.96  4989.9  514.99
  4999.9  515.99  5009.9  517.58  5019.9  518.54  5039.9  519.04  5059.9  519.03
  5072.0  519.43  5077.4  519.73  5099.9  520.71  5129.9  521.51  5164.0  522.03
#Mann=6,-1,0
  4843.8    0.05       0  4866.1    0.12       0  4929.7    0.07       0
  4933.7    0.12       0  5072.0     0.1       0  5077.4    0.12       0
Bank Sta=4929.7,4933.7
Exp/Cntr=0.3,0.1

Chan Stop Cuts=-1