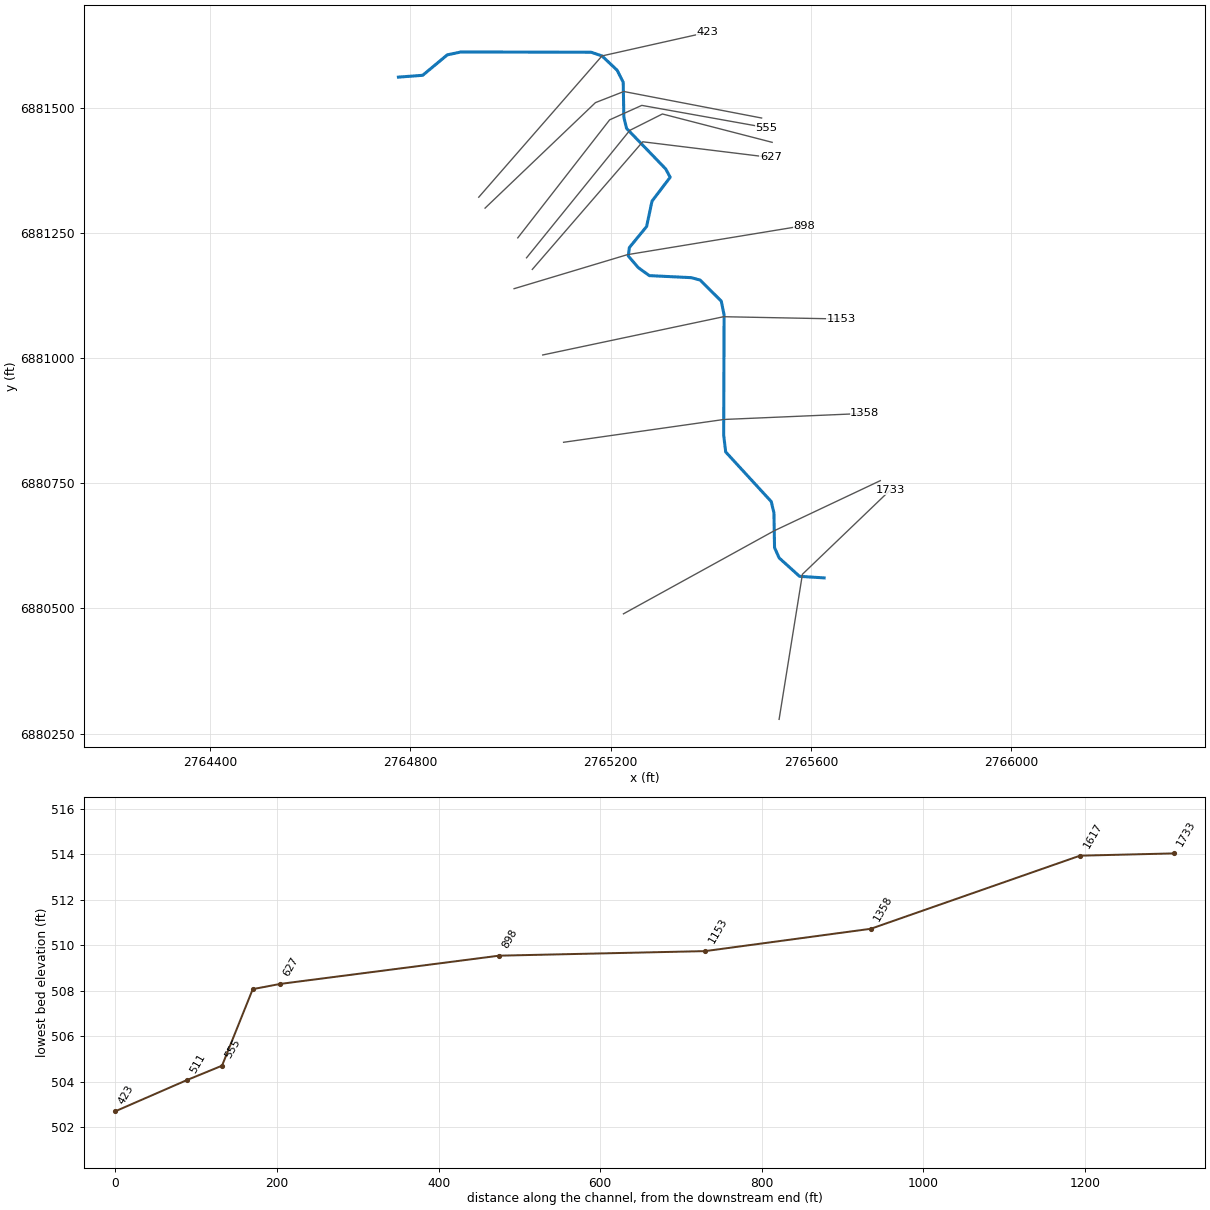
--- Lacy 004.prj (project) ---

Proj Title=Lacy 004 Base Level Engineering
Current Plan=p01
Default Exp/Contr=0.3,0.1
English Units
Geom File=g01
Flow File=f01
Plan File=p01
BEGIN DESCRIPTION:
Lacy 004
END DESCRIPTION:

--- Lacy 004.p01 (plan) ---

Plan Title=Multiple Run
Short Identifier=Multiple
Geom File=g01
Flow File=f01
Subcritical Flow
K Sum by GR= 0
Std Step Tol= 0.01
Critical Tol= 0.01
Num of Std Step Trials= 20
Max Error Tol= 0.3
Flow Tol Ratio= 0.001
Split Flow NTrial= 30
Split Flow Tol= 0.02
Split Flow Ratio= 0.02
Log Output Level= 0
Friction Slope Method= 1
Unsteady Friction Slope Method= 2
Unsteady Bridges Friction Slope Method= 1
Parabolic Critical Depth
Global Vel Dist=  1 , 1 , 1
Global Log Level= 0
CheckData=True
Encroach Param= -1, 0, 0, 0
BEGIN DESCRIPTION:
Multiple Run
END DESCRIPTION:

--- Lacy 004.f01 (steady flow) ---

Flow Title=Multiple
Number of Profiles=7
Profile Names=10-year,25-year,50-year,1pct_min,100-year,1pct_plu,500-year
River Rch & RM= Lacy 004,Reach-1,1733
     166     205     234     133     266     531     344
Boundary for River Rch & Prof#=Lacy 004,Reach-1,1
Up Type=0
Dn Type=3
Dn Slope=0.005
Boundary for River Rch & Prof#=Lacy 004,Reach-1,2
Up Type=0
Dn Type=3
Dn Slope=0.005
Boundary for River Rch & Prof#=Lacy 004,Reach-1,3
Up Type=0
Dn Type=3
Dn Slope=0.005
Boundary for River Rch & Prof#=Lacy 004,Reach-1,4
Up Type=0
Dn Type=3
Dn Slope=0.005
Boundary for River Rch & Prof#=Lacy 004,Reach-1,5
Up Type=0
Dn Type=3
Dn Slope=0.005
Boundary for River Rch & Prof#=Lacy 004,Reach-1,6
Up Type=0
Dn Type=3
Dn Slope=0.005
Boundary for River Rch & Prof#=Lacy 004,Reach-1,7
Up Type=0
Dn Type=3
Dn Slope=0.005

--- Lacy 004.g01 (geometry) ---

Geom Title=Existing Conditions

River Reach=Lacy 004,Reach-1
Reach XY= 30
      2765626.00      6880561.00      2765576.99      6880564.12
      2765536.26      6880600.90      2765527.08      6880621.35
      2765525.87      6880690.94      2765520.46      6880713.42
      2765429.55      6880812.47      2765425.51      6880845.80
      2765426.33      6881086.22      2765420.66      6881113.74
      2765378.71      6881155.59      2765360.91      6881160.53
      2765277.02      6881164.61      2765254.90      6881180.61
      2765234.97      6881203.94      2765237.21      6881220.72
      2765271.59      6881262.63      2765282.38      6881313.29
      2765318.70      6881361.08      2765309.68      6881377.69
      2765231.56      6881458.58      2765226.15      6881481.06
      2765224.90      6881550.69      2765212.77      6881574.73
      2765182.52      6881603.32      2765160.98      6881610.68
      2764900.90      6881611.24      2764873.58      6881605.47
      2764824.49      6881564.65      2764776.00      6881561.00

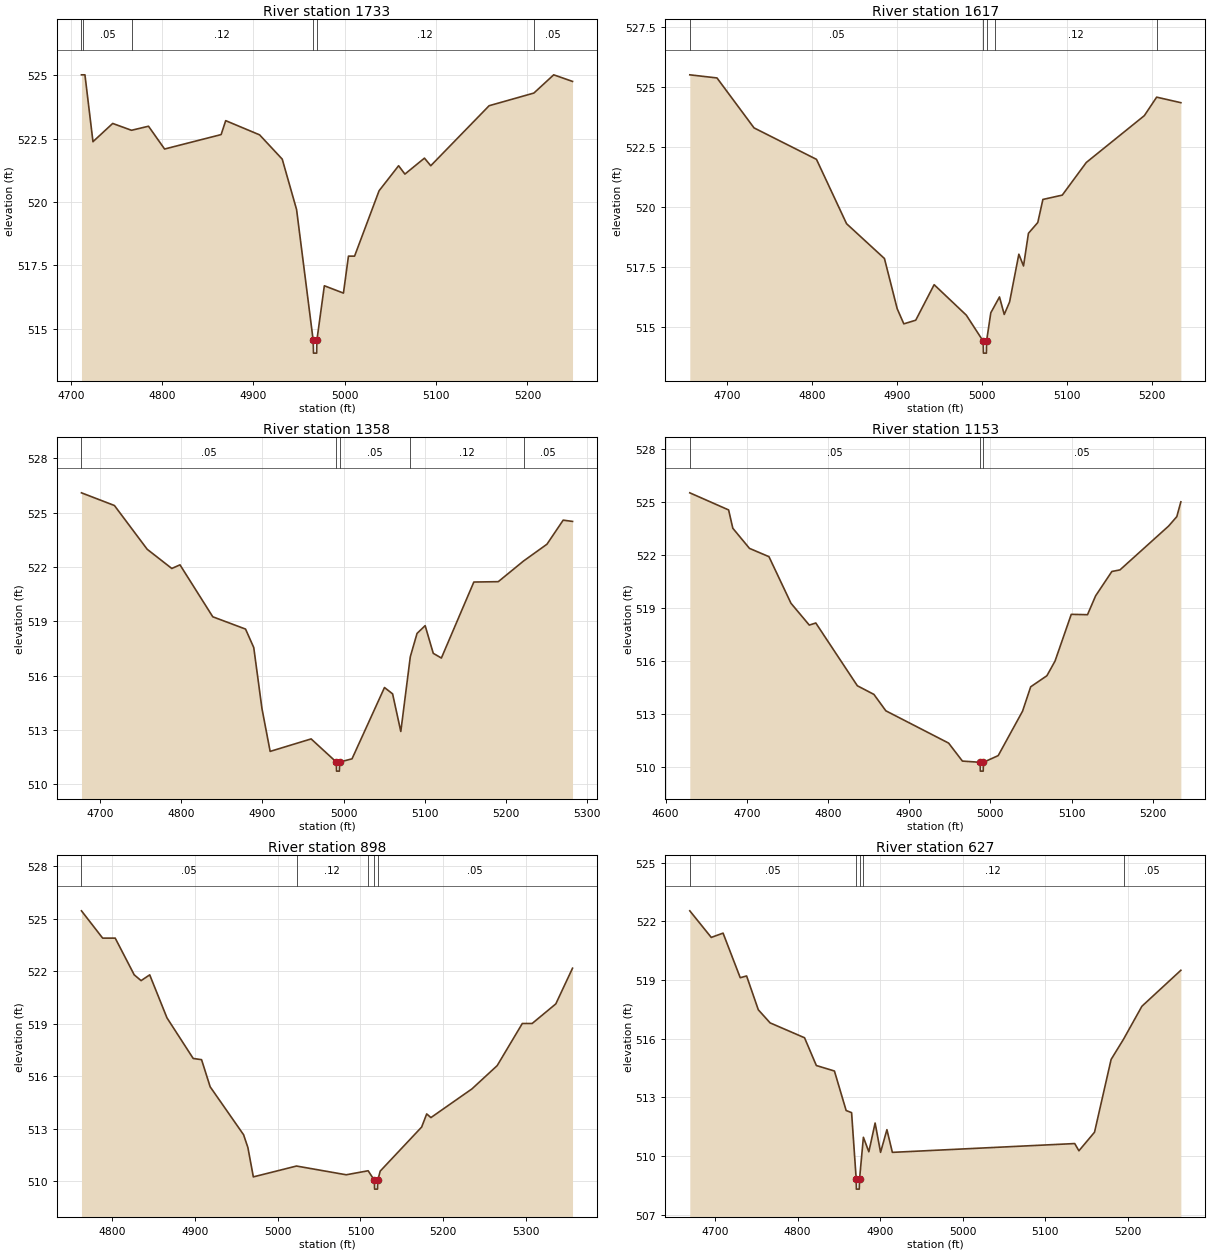
Type RM Length L Ch R = 1,1733,116,116,116
BEGIN DESCRIPTION:
Lacy 004 3429
END DESCRIPTION:
XS GIS Cut Line= 3
      2765536.18      6880278.52      2765582.75      6880568.24
      2765758.95      6880737.25
#Sta/Elev= 30
  4711.7  525.02  4713.7  525.02  4715.5  525.02  4724.3  522.38  4745.9  523.10
  4766.5  522.83  4785.1  522.99  4802.7  522.09  4864.6  522.66  4869.6  523.21
  4906.7  522.65  4931.5  521.69  4947.2  519.70  4965.4  514.53  4965.7  514.03
  4969.2  514.03  4969.4  514.53  4977.6  516.69  4998.5  516.40  5004.0  517.86
  5010.7  517.86  5037.5  520.44  5058.9  521.43  5065.8  521.10  5087.2  521.73
  5094.1  521.43  5158.0  523.80  5207.0  524.30  5228.7  525.02  5249.3  524.76
#Mann=6,-1,0
  4711.7    0.12       0  4713.7    0.05       0  4766.5    0.12       0
  4965.4    0.07       0  4969.4    0.12       0  5207.0    0.05       0
Bank Sta=4965.4,4969.4
Exp/Cntr=0.3,0.1

Type RM Length L Ch R = 1,1617,259,259,259
BEGIN DESCRIPTION:
Lacy 004 3411
END DESCRIPTION:
XS GIS Cut Line= 3
      2765225.37      6880489.24      2765526.49      6880655.13
      2765738.26      6880755.15
#Sta/Elev= 30
  4656.2  525.52  4688.2  525.39  4731.8  523.31  4805.3  522.00  4840.7  519.32
  4885.3  517.87  4900.3  515.78  4908.1  515.15  4922.1  515.30  4943.8  516.78
  4981.7  515.51  5001.5  514.43  5001.8  513.93  5005.3  513.93  5005.5  514.43
  5010.5  515.61  5015.6  515.94  5020.7  516.27  5026.3  515.54  5032.6  516.06
  5043.5  518.05  5049.0  517.56  5054.8  518.92  5065.8  519.37  5071.8  520.33
  5094.6  520.51  5122.9  521.87  5191.2  523.82  5205.7  524.59  5234.2  524.36
#Mann=5,-1,0
  4656.2    0.05       0  5001.5    0.04       0  5005.5    0.05       0
  5015.6    0.12       0  5205.7    0.05       0
Bank Sta=5001.5,5005.5
Exp/Cntr=0.3,0.1

Type RM Length L Ch R = 1,1358,205,205,205
BEGIN DESCRIPTION:
Lacy 004 3407
END DESCRIPTION:
XS GIS Cut Line= 3
      2765105.84      6880831.81      2765426.03      6880877.36
      2765707.45      6880889.48
#Sta/Elev= 30
  4677.0  526.10  4717.6  525.40  4758.0  522.98  4788.3  521.92  4798.4  522.12
  4838.8  519.25  4879.2  518.57  4889.3  517.55  4899.4  514.18  4909.5  511.81
  4960.0  512.50  4991.1  511.22  4991.3  510.72  4994.8  510.72  4995.1  511.22
  5010.4  511.40  5050.4  515.34  5060.4  514.99  5070.5  512.91  5082.2  517.04
  5090.5  518.33  5100.5  518.76  5110.5  517.23  5120.5  516.97  5160.5  521.17
  5190.6  521.19  5221.7  522.33  5250.6  523.26  5270.6  524.59  5282.1  524.52
#Mann=5,-1,0
  4677.0    0.05       0  4991.1    0.04       0  4995.1    0.05       0
  5082.2    0.12       0  5221.7    0.05       0
Bank Sta=4991.1,4995.1
Exp/Cntr=0.3,0.1

Type RM Length L Ch R = 1,1153,255,255,255
BEGIN DESCRIPTION:
Lacy 004 3406
END DESCRIPTION:
XS GIS Cut Line= 3
      2765064.12      6881006.13      2765425.38      6881082.56
      2765660.98      6881077.97
#Sta/Elev= 30
  4629.8  525.52  4677.6  524.55  4682.8  523.51  4703.3  522.37  4727.3  521.90
  4754.4  519.26  4777.0  518.02  4785.0  518.14  4836.2  514.58  4856.6  514.09
  4871.3  513.16  4948.6  511.33  4965.6  510.31  4987.5  510.24  4987.7  509.74
  4991.2  509.74  4991.5  510.24  5009.7  510.62  5039.7  513.14  5049.7  514.52
  5069.7  515.15  5079.7  515.98  5099.7  518.63  5119.7  518.61  5129.7  519.68
  5149.7  521.06  5159.7  521.15  5219.7  523.64  5229.7  524.17  5234.7  525.01
#Mann=3,-1,0
  4629.8    0.05       0  4987.5    0.04       0  4991.5    0.05       0
Bank Sta=4987.5,4991.5
Exp/Cntr=0.3,0.1

Type RM Length L Ch R = 1,898,271,271,271
BEGIN DESCRIPTION:
Lacy 004 3405
END DESCRIPTION:
XS GIS Cut Line= 3
      2765006.96      6881138.52      2765233.05      6881206.42
      2765585.94      6881264.45
#Sta/Elev= 30
  4762.7  525.45  4788.3  523.89  4803.5  523.89  4826.5  521.79  4834.8  521.46
  4845.2  521.79  4866.1  519.33  4897.8  517.01  4907.9  516.94  4918.3  515.39
  4958.7  512.65  4963.9  511.92  4970.5  510.24  5022.7  510.86  5082.8  510.36
  5109.3  510.59  5116.9  510.04  5117.1  509.54  5120.6  509.54  5120.9  510.04
  5123.9  510.57  5174.0  513.09  5180.1  513.84  5185.2  513.63  5234.8  515.27
  5265.3  516.60  5295.7  519.01  5307.6  519.01  5336.2  520.13  5356.4  522.17
#Mann=5,-1,0
  4762.7    0.05       0  5022.7    0.12       0  5109.3    0.05       0
  5116.9    0.04       0  5120.9    0.05       0
Bank Sta=5116.9,5120.9
Exp/Cntr=0.3,0.1

Type RM Length L Ch R = 1,627,34,34,34
BEGIN DESCRIPTION:
Lacy 004 3404
END DESCRIPTION:
XS GIS Cut Line= 3
      2765043.37      6881177.05      2765263.82      6881431.88
      2765519.85      6881400.52
#Sta/Elev= 30
  4669.4  522.53  4695.4  521.17  4709.7  521.39  4730.5  519.11  4738.2  519.20
  4752.4  517.47  4766.7  516.80  4808.4  516.04  4822.7  514.62  4844.6  514.34
  4858.8  512.32  4865.4  512.21  4871.0  508.80  4871.2  508.30  4874.7  508.30
  4875.0  508.80  4878.8  510.54  4879.7  510.95  4886.3  510.21  4893.9  511.68
  4900.5  510.18  4908.2  511.34  4914.8  510.18  5135.7  510.63  5140.8  510.26
  5159.7  511.21  5179.8  514.93  5194.9  515.97  5217.1  517.65  5264.3  519.49
#Mann=5,-1,0
  4669.4    0.05       0  4871.0    0.07       0  4875.0    0.05       0
  4878.8    0.12       0  5194.9    0.05       0
Bank Sta=4871,4875
Exp/Cntr=0.3,0.1

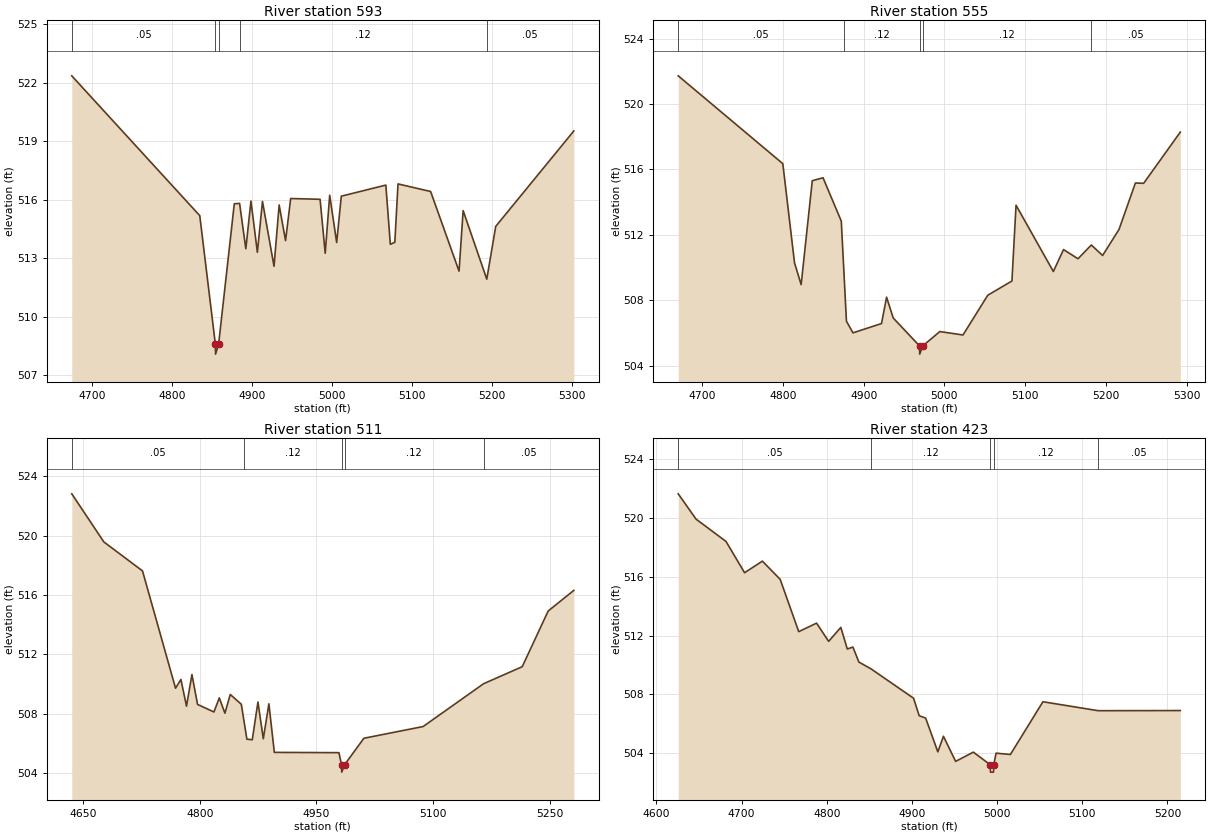
Type RM Length L Ch R = 1,593,38,38,38
BEGIN DESCRIPTION:
Lacy 004 3403
END DESCRIPTION:
XS GIS Cut Line= 4
      2765031.81      6881200.15      2765237.95      6881454.62
      2765303.17      6881487.40      2765522.30      6881430.80
#Sta/Elev= 30
  4675.1  522.36  4834.9  515.18  4854.4  508.57  4854.6  508.07  4858.4  508.57
  4878.0  515.79  4884.6  515.81  4892.4  513.48  4898.8  515.93  4906.8  513.30
  4913.2  515.91  4927.6  512.58  4934.0  515.73  4942.0  513.90  4948.4  516.06
  4985.1  516.02  4991.5  513.25  4997.1  516.23  5005.8  513.80  5011.6  516.18
  5067.2  516.75  5072.8  513.71  5078.4  513.81  5082.4  516.81  5123.1  516.42
  5158.6  512.33  5163.7  515.44  5193.2  511.92  5204.4  514.63  5301.9  519.53
#Mann=5,-1,0
  4675.1    0.05       0  4854.4    0.07       0  4858.4    0.05       0
  4884.6    0.12       0  5193.2    0.05       0
Bank Sta=4854.4,4858.4
Exp/Cntr=0.3,0.1

Type RM Length L Ch R = 1,555,44,44,44
BEGIN DESCRIPTION:
Lacy 004 3410
END DESCRIPTION:
XS GIS Cut Line= 4
      2765014.35      6881240.02      2765197.81      6881475.71
      2765262.03      6881504.57      2765510.69      6881460.04
#Sta/Elev= 30
  4670.4  521.72  4799.9  516.35  4814.4  510.29  4822.6  508.96  4836.4  515.31
  4849.7  515.49  4872.3  512.84  4875.1  510.16  4878.7  506.72  4886.8  506.01
  4922.1  506.58  4928.4  508.19  4936.6  506.92  4969.2  505.21  4969.4  504.71
  4973.2  505.21  4994.3  506.09  5023.0  505.88  5053.7  508.31  5083.6  509.18
  5088.7  513.81  5134.9  509.76  5147.5  511.10  5165.4  510.54  5181.9  511.38
  5195.9  510.74  5216.2  512.33  5236.5  515.17  5246.7  515.15  5292.1  518.28
#Mann=5,-1,0
  4670.4    0.05       0  4875.1    0.12       0  4969.2    0.07       0
  4973.2    0.12       0  5181.9    0.05       0
Bank Sta=4969.2,4973.2
Exp/Cntr=0.3,0.1

Type RM Length L Ch R = 1,511,88,88,88
BEGIN DESCRIPTION:
Lacy 004 3409
END DESCRIPTION:
XS GIS Cut Line= 4
      2764949.03      6881299.43      2765169.45      6881510.08
      2765226.13      6881532.26      2765501.23      6881479.33
#Sta/Elev= 30
  4635.2  522.81  4676.5  519.57  4726.2  517.62  4768.7  509.72  4775.6  510.31
  4782.8  508.51  4789.8  510.64  4797.0  508.63  4818.1  508.12  4825.0  509.07
  4832.2  508.04  4839.1  509.30  4853.3  508.64  4856.6  507.56  4860.5  506.29
  4867.4  506.25  4874.7  508.79  4881.6  506.32  4888.8  508.67  4895.8  505.40
  4978.9  505.38  4982.2  504.57  4982.5  504.07  4986.2  504.57  5011.0  506.35
  5087.2  507.14  5164.9  510.02  5214.7  511.17  5248.1  514.92  5281.1  516.31
#Mann=5,-1,0
  4635.2    0.05       0  4856.6    0.12       0  4982.2    0.07       0
  4986.2    0.12       0  5164.9    0.05       0
Bank Sta=4982.2,4986.2
Exp/Cntr=0.3,0.1

Type RM Length L Ch R = 1,423,0,0,0
BEGIN DESCRIPTION:
Lacy 004 3408
END DESCRIPTION:
XS GIS Cut Line= 3
      2764936.39      6881321.20      2765182.52      6881603.32
      2765392.41      6881650.38
#Sta/Elev= 30
  4625.6  521.65  4646.5  519.93  4681.7  518.41  4703.5  516.28  4724.4  517.07
  4745.3  515.83  4767.1  512.27  4788.0  512.85  4802.2  511.61  4816.5  512.56
  4824.1  511.09  4830.7  511.22  4837.7  510.20  4851.9  509.74  4901.9  507.74
  4908.5  506.55  4916.1  506.39  4930.4  504.09  4937.0  505.15  4951.3  503.44
  4972.1  504.07  4992.0  503.21  4992.2  502.71  4995.7  502.71  4996.0  503.21
  4998.8  504.00  5015.6  503.91  5053.8  507.50  5118.8  506.89  5215.1  506.90
#Mann=5,-1,0
  4625.6    0.05       0  4851.9    0.12       0  4992.0    0.07       0
  4996.0    0.12       0  5118.8    0.05       0
Bank Sta=4992,4996
Exp/Cntr=0.3,0.1

Chan Stop Cuts=-1