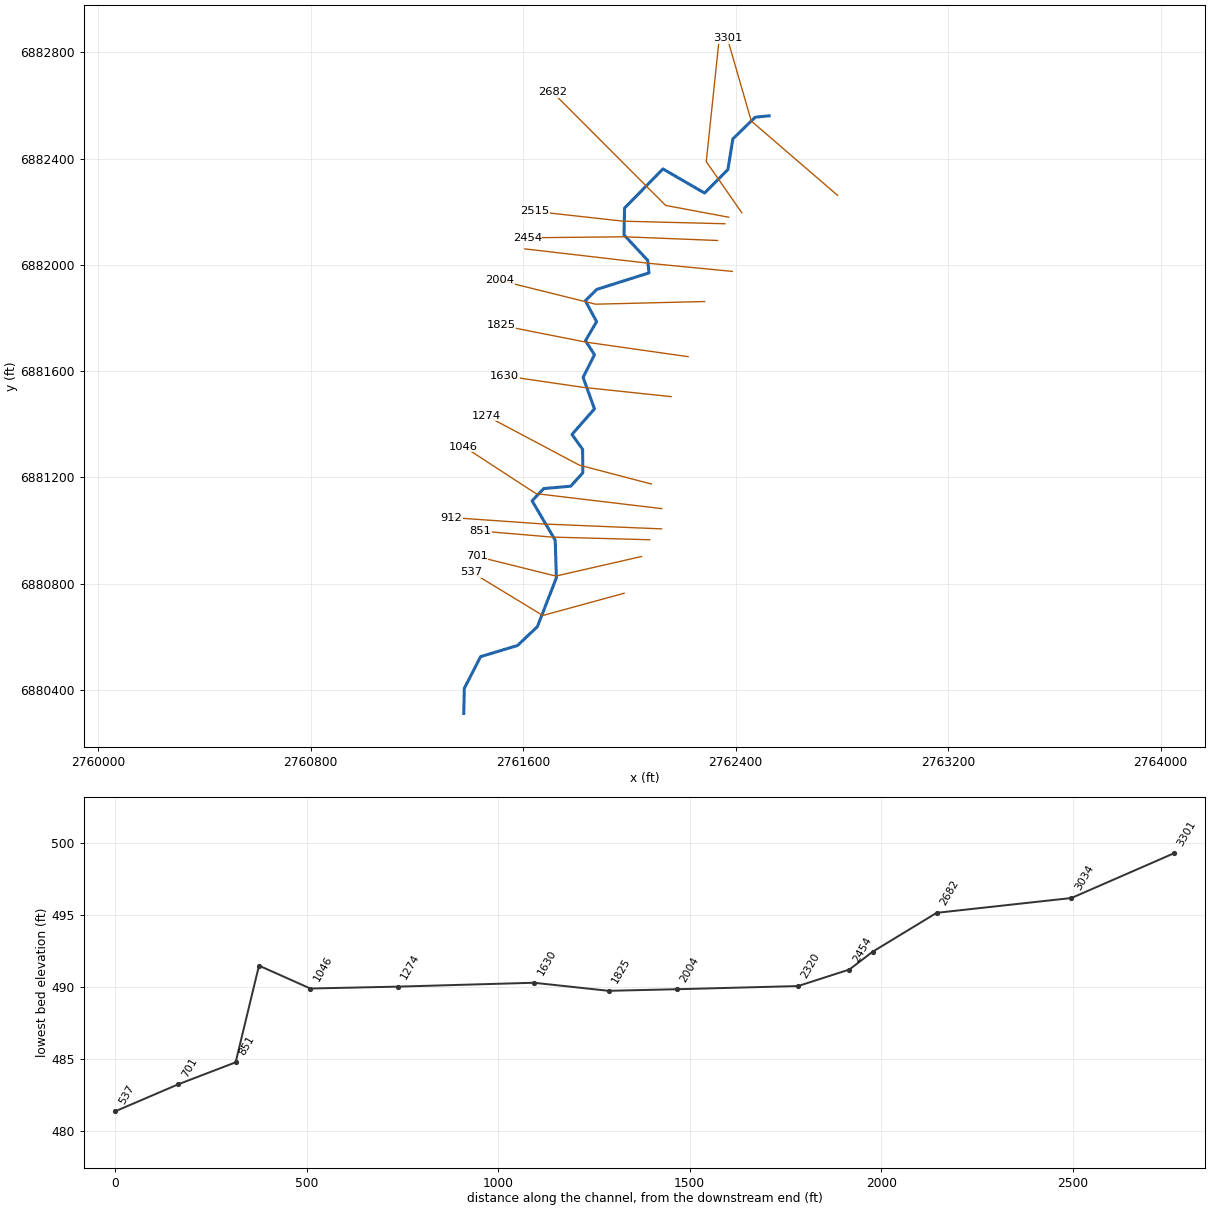
--- Lacy 005.prj (project) ---

Proj Title=Lacy 005 Base Level Engineering
Current Plan=p01
Default Exp/Contr=0.3,0.1
English Units
Geom File=g01
Flow File=f01
Plan File=p01
BEGIN DESCRIPTION:
Lacy 005
END DESCRIPTION:

--- Lacy 005.p01 (plan) ---

Plan Title=Multiple Run
Short Identifier=Multiple
Geom File=g01
Flow File=f01
Subcritical Flow
K Sum by GR= 0
Std Step Tol= 0.01
Critical Tol= 0.01
Num of Std Step Trials= 20
Max Error Tol= 0.3
Flow Tol Ratio= 0.001
Split Flow NTrial= 30
Split Flow Tol= 0.02
Split Flow Ratio= 0.02
Log Output Level= 0
Friction Slope Method= 1
Unsteady Friction Slope Method= 2
Unsteady Bridges Friction Slope Method= 1
Parabolic Critical Depth
Global Vel Dist=  1 , 1 , 1
Global Log Level= 0
CheckData=True
Encroach Param= -1, 0, 0, 0
BEGIN DESCRIPTION:
Multiple Run
END DESCRIPTION:

--- Lacy 005.f01 (steady flow) ---

Flow Title=Multiple
Number of Profiles=7
Profile Names=10-year,25-year,50-year,1pct_min,100-year,1pct_plu,500-year
River Rch & RM= Lacy 005,Reach-1,3301
     221     277     320     184     367     733     484
Boundary for River Rch & Prof#=Lacy 005,Reach-1,1
Up Type=0
Dn Type=3
Dn Slope=0.005
Boundary for River Rch & Prof#=Lacy 005,Reach-1,2
Up Type=0
Dn Type=3
Dn Slope=0.005
Boundary for River Rch & Prof#=Lacy 005,Reach-1,3
Up Type=0
Dn Type=3
Dn Slope=0.005
Boundary for River Rch & Prof#=Lacy 005,Reach-1,4
Up Type=0
Dn Type=3
Dn Slope=0.005
Boundary for River Rch & Prof#=Lacy 005,Reach-1,5
Up Type=0
Dn Type=3
Dn Slope=0.005
Boundary for River Rch & Prof#=Lacy 005,Reach-1,6
Up Type=0
Dn Type=3
Dn Slope=0.005
Boundary for River Rch & Prof#=Lacy 005,Reach-1,7
Up Type=0
Dn Type=3
Dn Slope=0.005

--- Lacy 005.g01 (geometry) ---

Geom Title=Existing Conditions

River Reach=Lacy 005,Reach-1
Reach XY= 30
      2762526.00      6882561.00      2762473.46      6882555.70
      2762389.38      6882474.33      2762370.48      6882358.54
      2762282.75      6882270.09      2762126.00      6882361.00
      2761981.39      6882213.43      2761979.47      6882112.50
      2762068.64      6882016.74      2762073.42      6881969.47
      2761877.02      6881907.39      2761833.70      6881864.69
      2761876.22      6881786.00      2761834.32      6881714.23
      2761868.20      6881661.10      2761825.36      6881576.08
      2761868.17      6881457.58      2761783.34      6881361.10
      2761823.63      6881305.10      2761824.12      6881216.69
      2761778.71      6881166.41      2761677.02      6881157.39
      2761633.19      6881111.33      2761720.30      6880963.35
      2761724.80      6880821.51      2761653.15      6880637.42
      2761578.44      6880566.52      2761439.45      6880524.63
      2761378.07      6880405.14      2761376.00      6880311.00

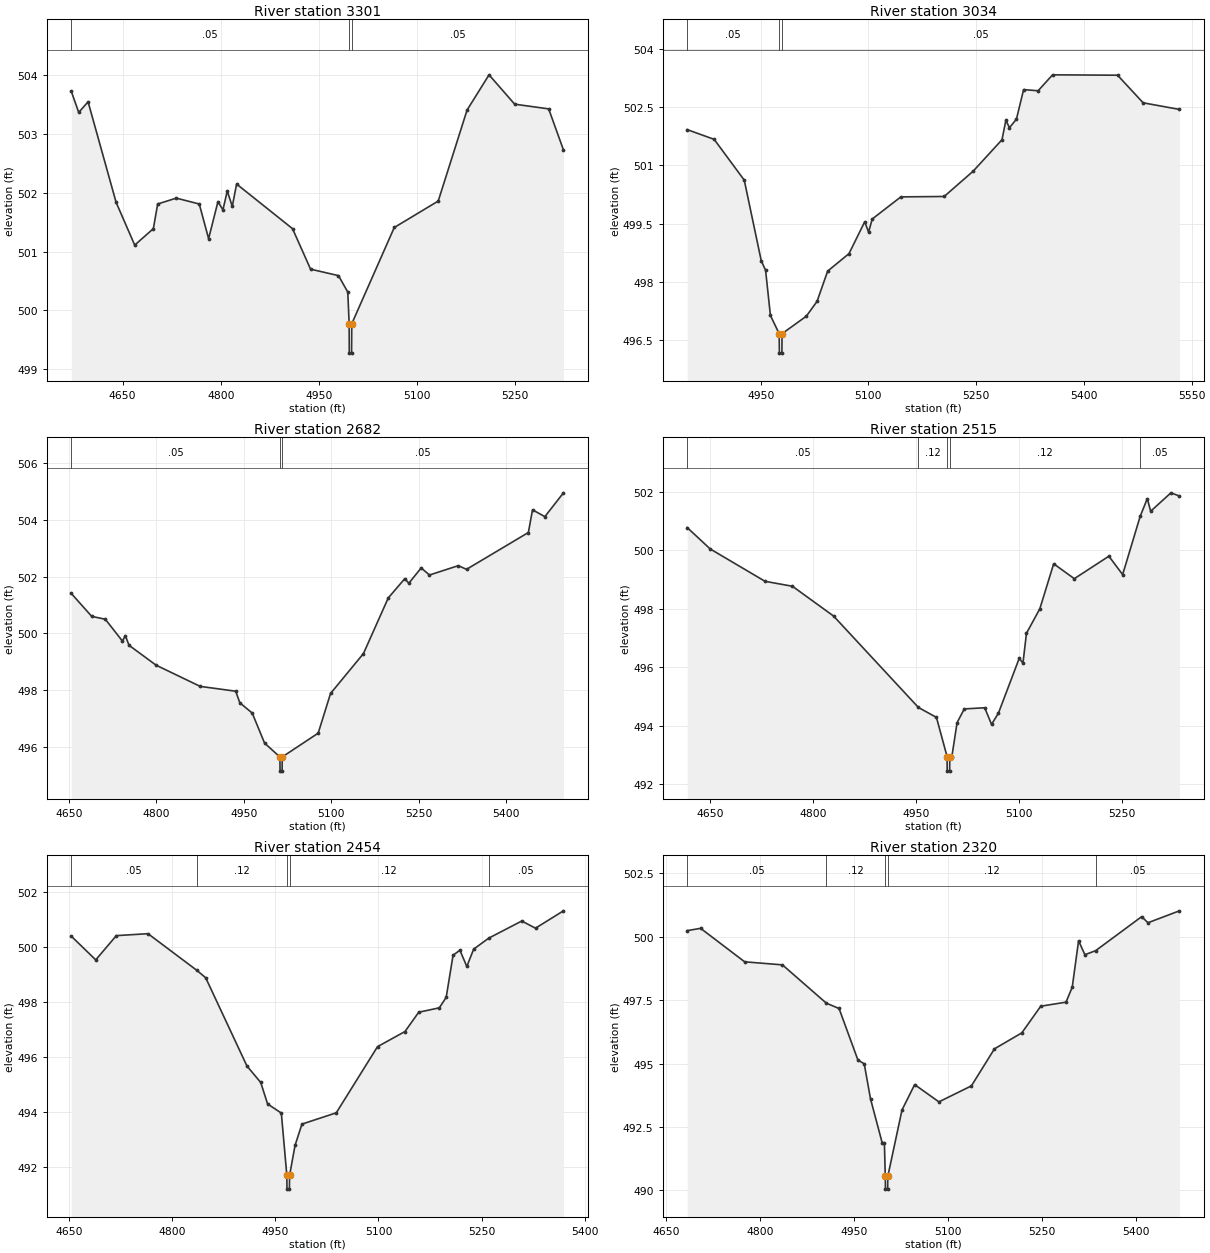
Type RM Length L Ch R = 1,3301,267,267,267
BEGIN DESCRIPTION:
Lacy 005 3391
END DESCRIPTION:
XS GIS Cut Line= 3
      2762783.25      6882261.65      2762458.57      6882541.29
      2762368.67      6882852.68
#Sta/Elev= 30
  4571.5  503.73  4582.9  503.37  4597.2  503.55  4640.0  501.84  4668.5  501.11
  4697.0  501.39  4703.6  501.81  4732.1  501.91  4767.2  501.81  4781.5  501.22
  4795.8  501.85  4803.4  501.71  4810.0  502.03  4817.7  501.77  4824.3  502.15
  4909.8  501.39  4937.4  500.70  4980.1  500.59  4994.3  500.31  4996.4  499.77
  4996.6  499.27  5000.1  499.27  5000.4  499.77  5065.4  501.41  5132.6  501.86
  5176.7  503.41  5210.3  504.01  5249.5  503.51  5301.5  503.43  5324.1  502.73
#Mann=3,-1,0
  4571.5    0.05       0  4996.4    0.04       0  5000.4    0.05       0
Bank Sta=4996.4,5000.4
Exp/Cntr=0.3,0.1

Type RM Length L Ch R = 1,3034,352,352,352
BEGIN DESCRIPTION:
Lacy 005 3390
END DESCRIPTION:
XS GIS Cut Line= 3
      2762422.94      6882195.92      2762289.08      6882388.36
      2762336.24      6882836.67
#Sta/Elev= 30
  4847.8  501.92  4885.3  501.67  4927.2  500.62  4950.8  498.55  4956.9  498.30
  4963.6  497.14  4975.8  496.67  4976.1  496.17  4979.6  496.17  4979.8  496.67
  5013.6  497.12  5028.5  497.50  5043.3  498.28  5073.0  498.73  5094.9  499.55
  5100.3  499.28  5105.3  499.62  5145.2  500.19  5205.5  500.20  5245.8  500.85
  5286.0  501.66  5291.4  502.16  5296.4  501.97  5306.1  502.19  5316.1  502.95
  5336.3  502.92  5356.4  503.33  5446.9  503.32  5482.5  502.61  5533.0  502.44
#Mann=3,-1,0
  4847.8    0.05       0  4975.8    0.04       0  4979.8    0.05       0
Bank Sta=4975.8,4979.8
Exp/Cntr=0.3,0.1

Type RM Length L Ch R = 1,2682,167,167,167
BEGIN DESCRIPTION:
Lacy 005 3389
END DESCRIPTION:
XS GIS Cut Line= 3
      2762373.43      6882179.15      2762136.13      6882223.55
      2761710.01      6882650.17
#Sta/Elev= 30
  4654.1  501.41  4689.2  500.60  4712.5  500.50  4741.8  499.73  4746.9  499.92
  4753.2  499.58  4799.5  498.88  4875.3  498.13  4936.2  497.96  4943.3  497.55
  4964.5  497.19  4985.7  496.13  5012.0  495.64  5012.3  495.14  5015.8  495.14
  5016.0  495.64  5077.7  496.48  5098.9  497.88  5155.4  499.29  5197.9  501.25
  5226.2  501.93  5233.2  501.77  5254.4  502.31  5268.6  502.06  5318.1  502.39
  5332.2  502.26  5438.3  503.56  5445.4  504.36  5466.6  504.12  5498.5  504.96
#Mann=3,-1,0
  4654.1    0.05       0  5012.0    0.04       0  5016.0    0.05       0
Bank Sta=5012,5016
Exp/Cntr=0.3,0.1

Type RM Length L Ch R = 1,2515,61,61,61
BEGIN DESCRIPTION:
Lacy 005 3388
END DESCRIPTION:
XS GIS Cut Line= 3
      2762359.42      6882154.56      2761976.18      6882164.21
      2761643.68      6882201.09
#Sta/Elev= 30
  4616.3  500.78  4649.7  500.05  4729.8  498.94  4769.8  498.77  4829.8  497.75
  4953.5  494.62  4979.8  494.28  4995.3  492.94  4995.5  492.44  4999.0  492.44
  4999.3  492.94  5002.3  492.94  5009.9  494.10  5020.4  494.57  5050.2  494.61
  5060.2  494.04  5070.3  494.43  5100.5  496.30  5106.0  496.14  5111.1  497.16
  5130.6  498.00  5150.8  499.54  5180.9  499.03  5231.3  499.80  5251.4  499.17
  5276.9  501.16  5287.3  501.77  5292.3  501.34  5321.8  501.97  5334.2  501.86
#Mann=5,-1,0
  4616.3    0.05       0  4953.5    0.12       0  4995.3    0.07       0
  4999.3    0.12       0  5276.9    0.05       0
Bank Sta=4995.3,4999.3
Exp/Cntr=0.3,0.1

Type RM Length L Ch R = 1,2454,134,134,134
BEGIN DESCRIPTION:
Lacy 005 3387
END DESCRIPTION:
XS GIS Cut Line= 3
      2762331.53      6882091.53      2761980.56      6882105.44
      2761615.33      6882101.68
#Sta/Elev= 30
  4652.8  500.38  4688.4  499.52  4718.4  500.40  4764.5  500.47  4835.6  499.14
  4848.5  498.87  4908.5  495.67  4928.6  495.07  4938.6  494.29  4958.6  493.96
  4966.6  491.70  4966.8  491.20  4970.3  491.20  4970.6  491.70  4978.6  492.79
  4988.6  493.56  5038.6  493.97  5098.6  496.37  5138.6  496.92  5158.6  497.62
  5188.6  497.78  5198.6  498.16  5208.6  499.69  5218.6  499.87  5228.6  499.28
  5238.6  499.91  5260.6  500.31  5308.6  500.93  5328.6  500.67  5369.3  501.30
#Mann=5,-1,0
  4652.8    0.05       0  4835.6    0.12       0  4966.6    0.07       0
  4970.6    0.12       0  5260.6    0.05       0
Bank Sta=4966.6,4970.6
Exp/Cntr=0.3,0.1

Type RM Length L Ch R = 1,2320,316,316,316
BEGIN DESCRIPTION:
Lacy 005 3386
END DESCRIPTION:
XS GIS Cut Line= 3
      2762387.27      6881975.13      2762073.98      6882005.55
      2761606.09      6882059.89
#Sta/Elev= 30
  4683.8  500.24  4705.2  500.33  4775.5  499.01  4835.8  498.89  4905.9  497.38
  4926.2  497.17  4956.3  495.14  4966.4  494.99  4976.4  493.61  4995.0  491.88
  4998.6  491.88  5000.0  490.55  5000.3  490.05  5003.8  490.05  5004.0  490.55
  5026.7  493.17  5046.9  494.17  5085.6  493.49  5137.5  494.12  5174.3  495.58
  5218.0  496.21  5248.2  497.26  5288.5  497.42  5298.5  498.01  5308.6  499.84
  5318.7  499.29  5335.9  499.45  5409.3  500.79  5419.4  500.55  5469.6  501.02
#Mann=5,-1,0
  4683.8    0.05       0  4905.9    0.12       0  5000.0    0.07       0
  5004.0    0.12       0  5335.9    0.05       0
Bank Sta=5000,5004
Exp/Cntr=0.3,0.1

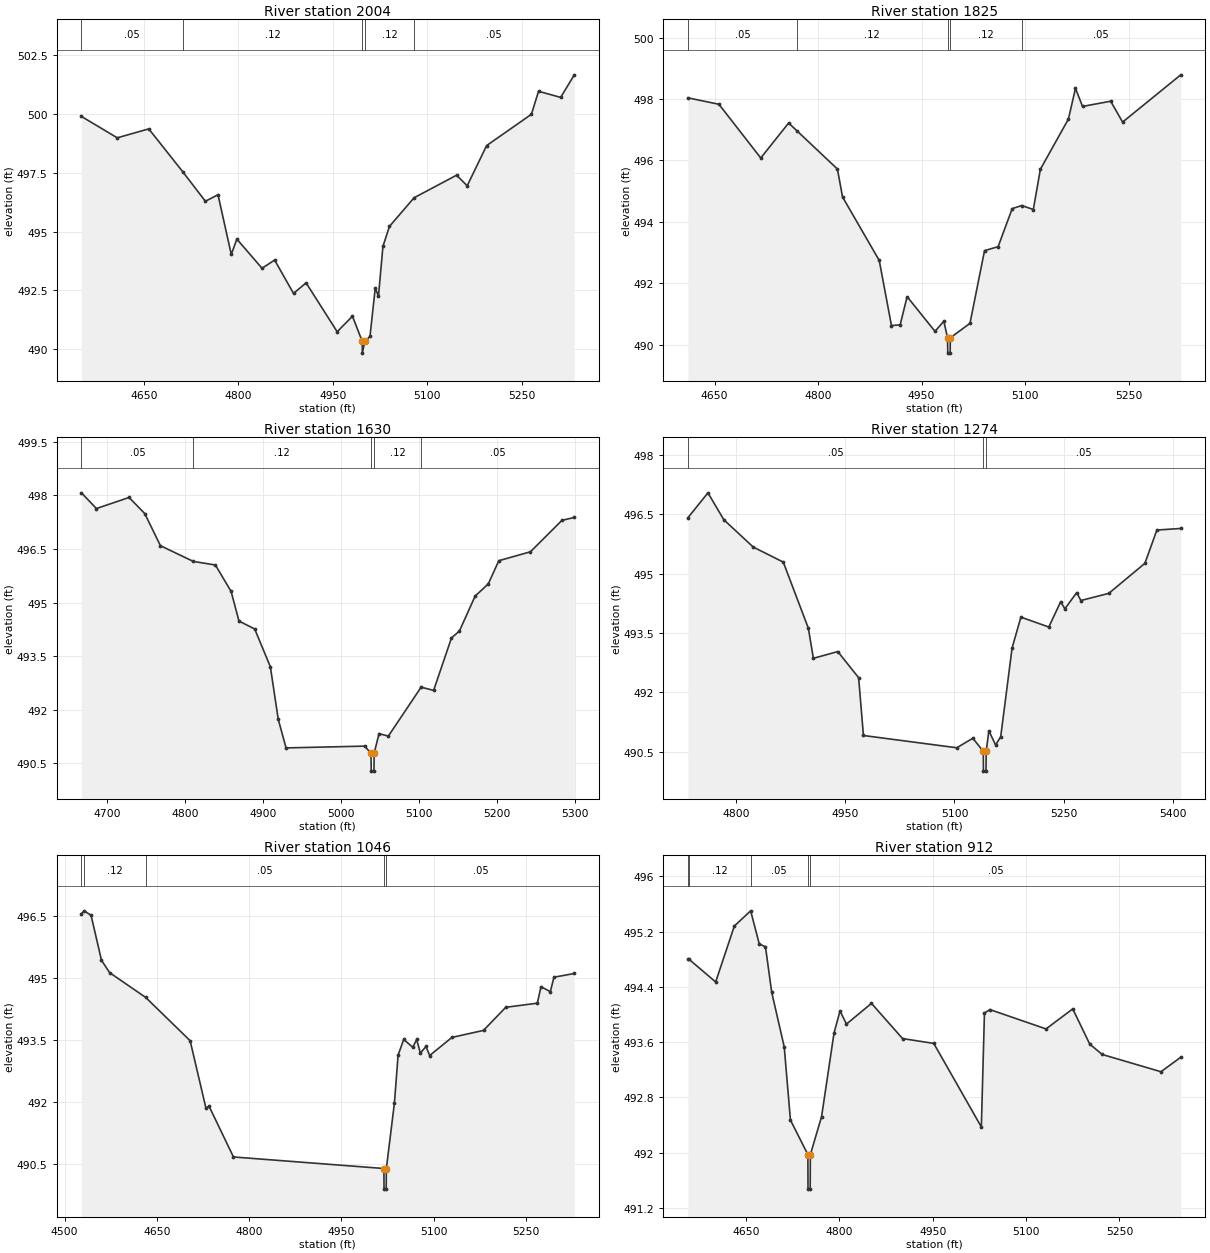
Type RM Length L Ch R = 1,2004,179,179,179
BEGIN DESCRIPTION:
Lacy 005 3385
END DESCRIPTION:
XS GIS Cut Line= 3
      2762282.92      6881861.74      2761872.33      6881851.67
      2761510.84      6881941.48
#Sta/Elev= 30
  4550.5  499.90  4607.4  498.99  4657.5  499.37  4711.4  497.55  4747.5  496.29
  4767.5  496.57  4788.6  494.03  4797.5  494.68  4837.5  493.44  4857.5  493.79
  4887.5  492.37  4907.5  492.82  4956.9  490.74  4981.2  491.40  4996.7  490.33
  4996.9  489.83  5000.7  490.33  5009.0  490.54  5017.4  492.60  5022.5  492.25
  5029.6  494.37  5039.9  495.22  5079.1  496.44  5146.6  497.40  5163.5  496.95
  5194.4  498.66  5265.5  499.99  5276.9  500.97  5312.0  500.71  5333.7  501.67
#Mann=5,-1,0
  4550.5    0.05       0  4711.4    0.12       0  4996.7    0.07       0
  5000.7    0.12       0  5079.1    0.05       0
Bank Sta=4996.7,5000.7
Exp/Cntr=0.3,0.1

Type RM Length L Ch R = 1,1825,195,195,195
BEGIN DESCRIPTION:
Lacy 005 3384
END DESCRIPTION:
XS GIS Cut Line= 3
      2762220.56      6881654.11      2761836.22      6881708.78
      2761516.31      6881771.94
#Sta/Elev= 30
  4611.3  498.04  4656.3  497.83  4716.9  496.08  4757.3  497.22  4769.1  496.97
  4828.0  495.72  4835.4  494.81  4888.6  492.74  4906.3  490.62  4918.9  490.64
  4929.0  491.56  4969.4  490.43  4982.2  490.76  4987.6  490.22  4987.9  489.72
  4991.4  489.72  4991.6  490.22  5020.1  490.69  5041.2  493.06  5060.9  493.19
  5081.3  494.43  5095.2  494.53  5111.9  494.40  5122.1  495.71  5162.8  497.35
  5173.0  498.35  5183.2  497.76  5224.0  497.93  5241.3  497.25  5325.6  498.79
#Mann=5,-1,0
  4611.3    0.05       0  4769.1    0.12       0  4987.6    0.07       0
  4991.6    0.12       0  5095.2    0.05       0
Bank Sta=4987.6,4991.6
Exp/Cntr=0.3,0.1

Type RM Length L Ch R = 1,1630,356,356,356
BEGIN DESCRIPTION:
Lacy 005 3383
END DESCRIPTION:
XS GIS Cut Line= 3
      2762156.67      6881503.62      2761824.24      6881538.77
      2761530.34      6881581.68
#Sta/Elev= 30
  4667.4  498.07  4686.6  497.63  4728.4  497.94  4748.5  497.49  4768.6  496.59
  4810.7  496.15  4839.0  496.05  4859.1  495.31  4869.2  494.48  4889.3  494.26
  4909.4  493.20  4919.5  491.73  4929.5  490.93  5030.2  490.98  5038.3  490.78
  5038.6  490.28  5042.1  490.28  5042.3  490.78  5048.6  491.33  5060.5  491.26
  5102.5  492.63  5118.5  492.54  5141.4  494.01  5151.5  494.20  5171.7  495.18
  5188.5  495.52  5202.0  496.17  5242.5  496.42  5282.9  497.30  5298.7  497.38
#Mann=5,-1,0
  4667.4    0.05       0  4810.7    0.12       0  5038.3    0.07       0
  5042.3    0.12       0  5102.5    0.05       0
Bank Sta=5038.3,5042.3
Exp/Cntr=0.3,0.1

Type RM Length L Ch R = 1,1274,228,228,228
BEGIN DESCRIPTION:
Lacy 005 3382
END DESCRIPTION:
XS GIS Cut Line= 3
      2762082.60      6881174.49      2761810.88      6881245.76
      2761461.53      6881431.16
#Sta/Elev= 30
  4734.2  496.41  4761.7  497.04  4783.5  496.36  4823.9  495.67  4865.1  495.29
  4899.5  493.62  4906.4  492.86  4939.9  493.03  4968.5  492.37  4975.1  490.91
  5103.2  490.60  5125.2  490.84  5139.6  490.51  5139.8  490.01  5143.3  490.01
  5143.6  490.51  5147.2  491.03  5156.5  490.67  5163.5  490.88  5179.1  493.12
  5191.2  493.90  5229.5  493.65  5245.8  494.29  5251.5  494.11  5267.8  494.52
  5273.5  494.32  5311.8  494.50  5361.4  495.26  5377.8  496.10  5410.6  496.14
#Mann=3,-1,0
  4734.2    0.05       0  5139.6    0.03       0  5143.6    0.05       0
Bank Sta=5139.6,5143.6
Exp/Cntr=0.3,0.1

Type RM Length L Ch R = 1,1046,134,134,134
BEGIN DESCRIPTION:
Lacy 005 3381
END DESCRIPTION:
XS GIS Cut Line= 3
      2762121.54      6881081.93      2761647.99      6881138.42
      2761375.88      6881315.75
#Sta/Elev= 30
  4527.3  496.56  4531.8  496.63  4543.0  496.52  4559.9  495.43  4573.2  495.13
  4631.8  494.53  4704.1  493.48  4729.9  491.84  4734.9  491.89  4774.6  490.66
  5019.3  490.38  5019.5  489.88  5023.0  489.88  5023.3  490.38  5036.4  491.97
  5042.4  493.13  5051.5  493.51  5066.3  493.32  5072.6  493.51  5078.6  493.18
  5087.8  493.34  5093.7  493.12  5130.0  493.56  5181.3  493.73  5217.5  494.29
  5268.9  494.39  5274.8  494.79  5290.0  494.67  5295.9  495.02  5329.0  495.11
#Mann=5,-1,0
  4527.3    0.05       0  4531.8    0.12       0  4631.8    0.05       0
  5019.3    0.03       0  5023.3    0.05       0
Bank Sta=5019.3,5023.3
Exp/Cntr=0.3,0.1

Type RM Length L Ch R = 1,912,61,61,61
BEGIN DESCRIPTION:
Lacy 005 3380
END DESCRIPTION:
XS GIS Cut Line= 3
      2762120.52      6881005.70      2761673.98      6881024.20
      2761330.14      6881048.29
#Sta/Elev= 30
  4556.9  494.80  4558.5  494.80  4601.5  494.47  4631.5  495.28  4657.7  495.50
  4671.5  495.02  4681.5  494.98  4691.5  494.32  4711.6  493.53  4721.6  492.47
  4749.6  491.97  4749.8  491.47  4753.3  491.47  4753.6  491.97  4771.6  492.52
  4791.6  493.73  4801.2  494.05  4811.6  493.86  4851.7  494.16  4901.7  493.65
  4951.8  493.58  5028.2  492.37  5033.2  494.02  5041.9  494.07  5132.1  493.79
  5175.0  494.08  5202.3  493.57  5222.3  493.42  5316.7  493.17  5348.5  493.38
#Mann=5,-1,0
  4556.9    0.05       0  4558.5    0.12       0  4657.7    0.05       0
  4749.6    0.03       0  4753.6    0.05       0
Bank Sta=4749.6,4753.6
Exp/Cntr=0.3,0.1

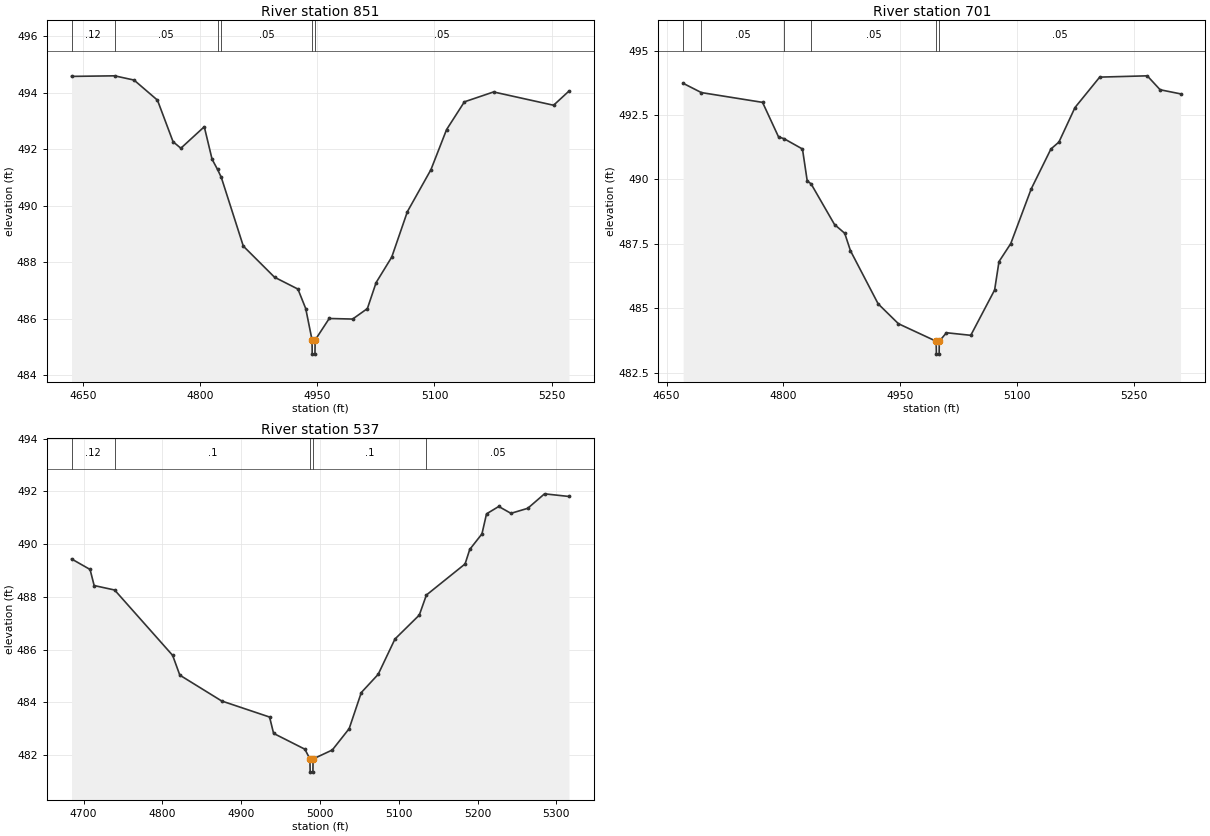
Type RM Length L Ch R = 1,851,150,150,150
BEGIN DESCRIPTION:
Lacy 005 3379
END DESCRIPTION:
XS GIS Cut Line= 3
      2762076.04      6880964.78      2761707.47      6880974.80
      2761439.74      6880997.53
#Sta/Elev= 30
  4634.9  494.57  4690.1  494.59  4715.0  494.44  4745.0  493.73  4765.0  492.26
  4775.0  492.03  4805.0  492.79  4815.0  491.64  4822.0  491.28  4826.8  491.00
  4855.0  488.57  4895.0  487.47  4925.0  487.05  4935.0  486.36  4943.1  485.25
  4943.3  484.75  4946.8  484.75  4947.1  485.25  4965.1  486.01  4995.1  485.99
  5014.0  486.36  5025.2  487.28  5045.2  488.18  5065.3  489.79  5095.4  491.27
  5115.5  492.69  5138.3  493.67  5175.7  494.02  5252.6  493.55  5272.3  494.05
#Mann=6,-1,0
  4634.9    0.12       0  4690.1    0.05       0  4822.0    0.12       0
  4826.8    0.05       0  4943.1    0.03       0  4947.1    0.05       0
Bank Sta=4943.1,4947.1
Exp/Cntr=0.3,0.1

Type RM Length L Ch R = 1,701,164,164,164
BEGIN DESCRIPTION:
Lacy 005 3378
END DESCRIPTION:
XS GIS Cut Line= 3
      2762045.30      6880901.68      2761722.81      6880827.97
      2761424.58      6880902.06
#Sta/Elev= 30
  4671.3  493.73  4694.7  493.37  4773.2  492.99  4793.7  491.65  4800.8  491.58
  4824.4  491.18  4830.5  489.94  4835.4  489.83  4865.5  488.25  4878.6  487.91
  4886.0  487.23  4921.5  485.17  4947.5  484.40  4995.9  483.72  4996.2  483.22
  4999.7  483.22  4999.9  483.72  5009.1  484.05  5040.3  483.95  5070.9  485.71
  5076.5  486.81  5091.6  487.51  5117.8  489.63  5143.1  491.18  5153.4  491.45
  5174.0  492.79  5205.7  493.97  5266.7  494.02  5283.2  493.48  5309.4  493.32
#Mann=6,-1,0
  4671.3    0.12       0  4694.7    0.05       0  4800.8    0.12       0
  4835.4    0.05       0  4995.9    0.03       0  4999.9    0.05       0
Bank Sta=4995.9,4999.9
Exp/Cntr=0.3,0.1

Type RM Length L Ch R = 1,537,0,0,0
BEGIN DESCRIPTION:
Lacy 005 3377
END DESCRIPTION:
XS GIS Cut Line= 3
      2761979.74      6880763.27      2761673.62      6880679.56
      2761405.52      6880842.70
#Sta/Elev= 30
  4684.8  489.44  4708.3  489.04  4713.5  488.43  4739.5  488.26  4813.1  485.78
  4822.2  485.03  4875.3  484.05  4936.1  483.44  4941.2  482.82  4980.9  482.22
  4987.3  481.85  4987.6  481.35  4991.1  481.35  4991.3  481.85  5015.7  482.19
  5037.1  483.00  5052.5  484.37  5073.9  485.06  5095.2  486.40  5126.1  487.31
  5135.1  488.07  5184.2  489.25  5190.1  489.80  5205.6  490.39  5211.4  491.15
  5226.9  491.43  5242.4  491.17  5263.7  491.36  5285.0  491.91  5316.0  491.81
#Mann=5,-1,0
  4684.8    0.12       0  4739.5     0.1       0  4987.3    0.07       0
  4991.3     0.1       0  5135.1    0.05       0
Bank Sta=4987.3,4991.3
Exp/Cntr=0.3,0.1

Chan Stop Cuts=-1