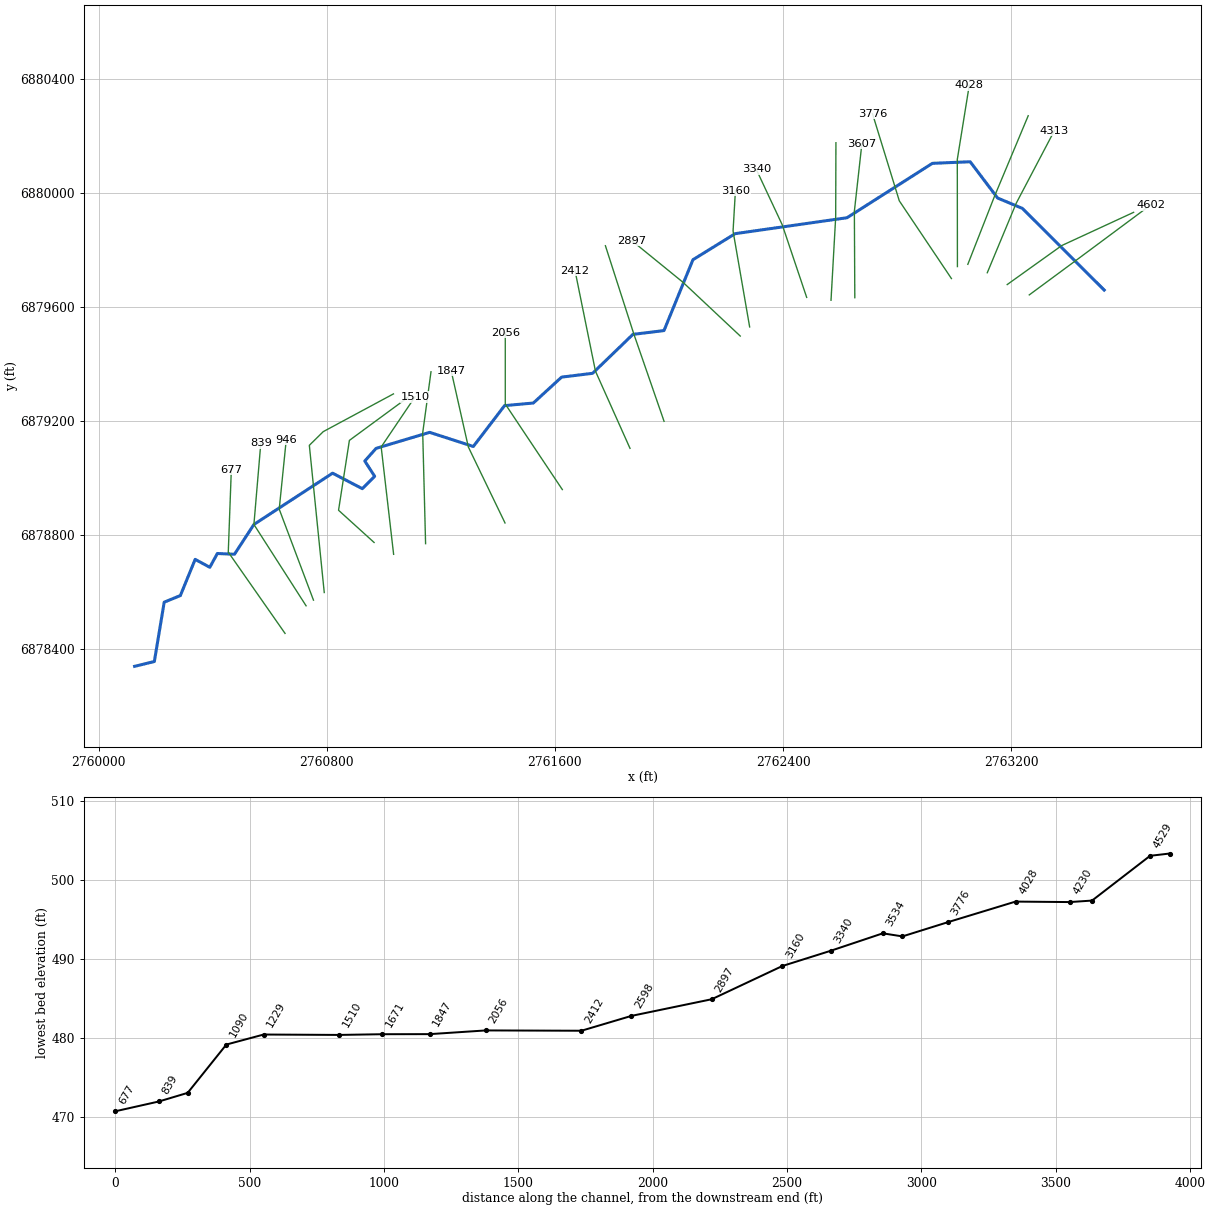
--- Lacy 007.prj (project) ---

Proj Title=Lacy 007 Base Level Engineering
Current Plan=p01
Default Exp/Contr=0.3,0.1
English Units
Geom File=g01
Flow File=f01
Plan File=p01
BEGIN DESCRIPTION:
Lacy 007
END DESCRIPTION:

--- Lacy 007.p01 (plan) ---

Plan Title=Multiple Run
Short Identifier=Multiple
Geom File=g01
Flow File=f01
Subcritical Flow
K Sum by GR= 0
Std Step Tol= 0.01
Critical Tol= 0.01
Num of Std Step Trials= 20
Max Error Tol= 0.3
Flow Tol Ratio= 0.001
Split Flow NTrial= 30
Split Flow Tol= 0.02
Split Flow Ratio= 0.02
Log Output Level= 0
Friction Slope Method= 1
Unsteady Friction Slope Method= 2
Unsteady Bridges Friction Slope Method= 1
Parabolic Critical Depth
Global Vel Dist=  1 , 1 , 1
Global Log Level= 0
CheckData=True
Encroach Param= -1, 0, 0, 0
BEGIN DESCRIPTION:
Multiple Run
END DESCRIPTION:

--- Lacy 007.f01 (steady flow) ---

Flow Title=Multiple
Number of Profiles=7
Profile Names=10-year,25-year,50-year,1pct_min,100-year,1pct_plu,500-year
River Rch & RM= Lacy 007,Reach-1,4602
     210     265     306     177     353     704     469
Boundary for River Rch & Prof#=Lacy 007,Reach-1,1
Up Type=0
Dn Type=3
Dn Slope=0.005
Boundary for River Rch & Prof#=Lacy 007,Reach-1,2
Up Type=0
Dn Type=3
Dn Slope=0.005
Boundary for River Rch & Prof#=Lacy 007,Reach-1,3
Up Type=0
Dn Type=3
Dn Slope=0.005
Boundary for River Rch & Prof#=Lacy 007,Reach-1,4
Up Type=0
Dn Type=3
Dn Slope=0.005
Boundary for River Rch & Prof#=Lacy 007,Reach-1,5
Up Type=0
Dn Type=3
Dn Slope=0.005
Boundary for River Rch & Prof#=Lacy 007,Reach-1,6
Up Type=0
Dn Type=3
Dn Slope=0.005
Boundary for River Rch & Prof#=Lacy 007,Reach-1,7
Up Type=0
Dn Type=3
Dn Slope=0.005

--- Lacy 007.g01 (geometry) ---

Geom Title=Existing Conditions

River Reach=Lacy 007,Reach-1
Reach XY= 30
      2763526.00      6879661.00      2763239.20      6879947.36
      2763152.17      6879983.87      2763056.11      6880111.11
      2762923.56      6880105.53      2762624.45      6879914.75
      2762231.93      6879858.75      2762084.02      6879767.34
      2761982.50      6879518.73      2761873.58      6879505.47
      2761732.17      6879368.86      2761623.58      6879355.46
      2761524.50      6879264.63      2761423.56      6879255.48
      2761313.99      6879112.17      2761160.94      6879161.71
      2760973.03      6879105.48      2760933.47      6879061.23
      2760968.09      6879007.35      2760924.79      6878964.08
      2760820.58      6879018.47      2760544.70      6878838.54
      2760476.53      6878734.00      2760416.60      6878736.69
      2760390.05      6878688.24      2760338.74      6878716.08
      2760286.82      6878589.08      2760230.16      6878565.87
      2760195.63      6878357.73      2760126.34      6878340.79

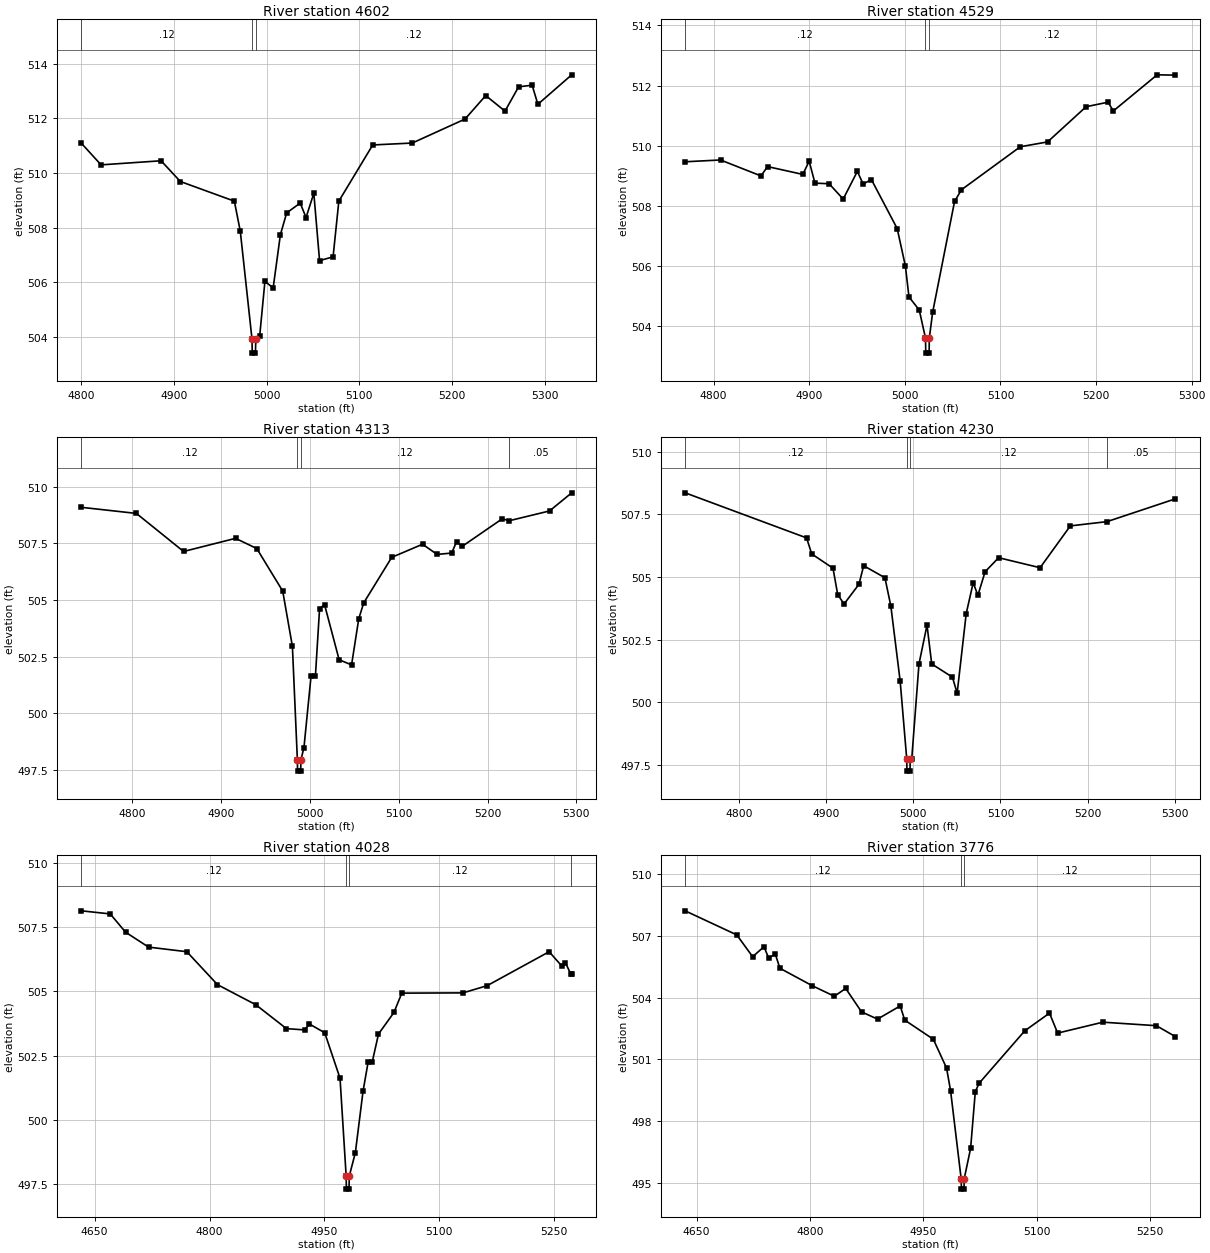
Type RM Length L Ch R = 1,4602,73,73,73
BEGIN DESCRIPTION:
Lacy 007 3367
END DESCRIPTION:
XS GIS Cut Line= 3
      2763263.21      6879643.94      2763424.09      6879762.76
      2763688.37      6879959.21
#Sta/Elev= 30
  4800.0  511.09  4821.2  510.30  4886.0  510.45  4906.8  509.69  4965.1  508.97
  4971.5  507.87  4984.2  503.90  4984.4  503.40  4987.9  503.40  4988.2  503.90
  4992.4  504.01  4998.1  506.03  5007.0  505.79  5014.8  507.74  5021.6  508.54
  5036.2  508.90  5042.5  508.37  5050.9  509.26  5057.1  506.79  5071.7  506.93
  5077.9  508.97  5114.5  511.03  5157.2  511.10  5214.2  511.98  5236.5  512.84
  5257.3  512.27  5272.0  513.16  5286.6  513.22  5292.8  512.52  5329.3  513.60
#Mann=3,-1,0
  4800.0    0.12       0  4984.2    0.07       0  4988.2    0.12       0
Bank Sta=4984.2,4988.2
Exp/Cntr=0.3,0.1

Type RM Length L Ch R = 1,4529,216,216,216
BEGIN DESCRIPTION:
Lacy 007 3366
END DESCRIPTION:
XS GIS Cut Line= 3
      2763185.90      6879680.26      2763377.00      6879817.02
      2763629.14      6879933.64
#Sta/Elev= 30
  4770.2  509.47  4807.2  509.53  4849.5  509.00  4856.4  509.31  4893.3  509.05
  4899.9  509.49  4906.0  508.76  4920.8  508.74  4935.5  508.23  4950.3  509.15
  4956.4  508.73  4965.0  508.88  4992.0  507.25  5000.6  506.00  5004.3  504.98
  5015.1  504.54  5021.6  503.61  5021.9  503.11  5025.4  503.11  5025.6  503.61
  5029.1  504.47  5052.0  508.15  5059.2  508.54  5120.8  509.97  5149.3  510.13
  5189.6  511.30  5212.5  511.45  5218.1  511.16  5263.9  512.36  5283.0  512.35
#Mann=3,-1,0
  4770.2    0.12       0  5021.6    0.07       0  5025.6    0.12       0
Bank Sta=5021.6,5025.6
Exp/Cntr=0.3,0.1

Type RM Length L Ch R = 1,4313,83,83,83
BEGIN DESCRIPTION:
Lacy 007 3360
END DESCRIPTION:
XS GIS Cut Line= 3
      2763116.04      6879721.74      2763217.19      6879964.94
      2763351.37      6880220.34
#Sta/Elev= 30
  4742.8  509.09  4804.7  508.82  4857.8  507.14  4916.3  507.72  4940.2  507.27
  4969.4  505.39  4980.3  502.95  4985.9  497.94  4986.1  497.44  4989.6  497.44
  4989.9  497.94  4993.3  498.48  5001.3  501.64  5006.2  501.64  5010.9  504.62
  5016.5  504.79  5032.9  502.36  5046.9  502.13  5055.0  504.17  5060.6  504.87
  5092.1  506.88  5126.8  507.46  5143.2  507.01  5159.6  507.07  5165.2  507.58
  5171.2  507.36  5216.4  508.58  5224.6  508.50  5269.8  508.93  5294.7  509.73
#Mann=4,-1,0
  4742.8    0.12       0  4985.9    0.07       0  4989.9    0.12       0
  5224.6    0.05       0
Bank Sta=4985.9,4989.9
Exp/Cntr=0.3,0.1

Type RM Length L Ch R = 1,4230,202,202,202
BEGIN DESCRIPTION:
Lacy 007 3359
END DESCRIPTION:
XS GIS Cut Line= 3
      2763047.81      6879751.22      2763141.72      6879990.80
      2763259.53      6880272.53
#Sta/Elev= 30
  4738.1  508.36  4877.5  506.56  4883.4  505.92  4907.8  505.35  4913.2  504.30
  4920.5  503.92  4937.6  504.71  4943.0  505.45  4967.4  504.97  4974.2  503.84
  4984.9  500.84  4992.4  497.75  4992.7  497.25  4996.2  497.25  4996.4  497.75
  4998.2  497.75  5006.5  501.53  5015.7  503.08  5021.1  501.53  5044.9  501.00
  5050.3  500.36  5060.7  503.54  5068.7  504.77  5074.1  504.27  5082.4  505.21
  5097.9  505.77  5145.5  505.37  5180.2  507.04  5222.3  507.21  5300.8  508.12
#Mann=4,-1,0
  4738.1    0.12       0  4992.4    0.07       0  4996.4    0.12       0
  5222.3    0.05       0
Bank Sta=4992.4,4996.4
Exp/Cntr=0.3,0.1

Type RM Length L Ch R = 1,4028,252,252,252
BEGIN DESCRIPTION:
Lacy 007 3358
END DESCRIPTION:
XS GIS Cut Line= 3
      2763011.32      6879743.37      2763010.90      6880119.20
      2763052.93      6880380.01
#Sta/Elev= 30
  4632.7  508.13  4670.3  508.01  4690.3  507.30  4720.3  506.72  4770.3  506.54
  4810.3  505.26  4860.3  504.48  4900.3  503.55  4924.3  503.50  4930.3  503.73
  4950.3  503.39  4970.3  501.62  4978.3  497.81  4978.6  497.31  4982.1  497.31
  4982.3  497.81  4990.3  498.73  5000.3  501.11  5006.9  502.24  5012.3  502.25
  5020.5  503.34  5040.7  504.18  5050.9  504.93  5130.8  504.94  5162.3  505.22
  5243.3  506.54  5259.6  505.99  5264.6  506.11  5271.2  505.69  5272.7  505.69
#Mann=4,-1,0
  4632.7    0.12       0  4978.3    0.07       0  4982.3    0.12       0
  5271.2    0.05       0
Bank Sta=4978.3,4982.3
Exp/Cntr=0.3,0.1

Type RM Length L Ch R = 1,3776,169,169,169
BEGIN DESCRIPTION:
Lacy 007 3357
END DESCRIPTION:
XS GIS Cut Line= 3
      2762990.36      6879701.31      2762807.57      6879973.94
      2762713.50      6880279.87
#Sta/Elev= 30
  4634.9  508.22  4703.2  507.05  4724.2  505.99  4739.2  506.48  4745.2  505.93
  4754.2  506.11  4760.2  505.43  4803.1  504.58  4832.2  504.07  4847.2  504.45
  4868.2  503.31  4889.3  502.96  4919.3  503.60  4925.3  502.91  4963.1  501.98
  4980.6  500.58  4985.9  499.48  4999.9  495.20  5000.2  494.70  5003.7  494.70
  5003.9  495.20  5012.4  496.68  5018.6  499.44  5023.8  499.85  5084.0  502.39
  5116.7  503.25  5127.5  502.28  5187.3  502.81  5258.0  502.64  5283.2  502.11
#Mann=3,-1,0
  4634.9    0.12       0  4999.9    0.07       0  5003.9    0.12       0
Bank Sta=4999.9,5003.9
Exp/Cntr=0.3,0.1

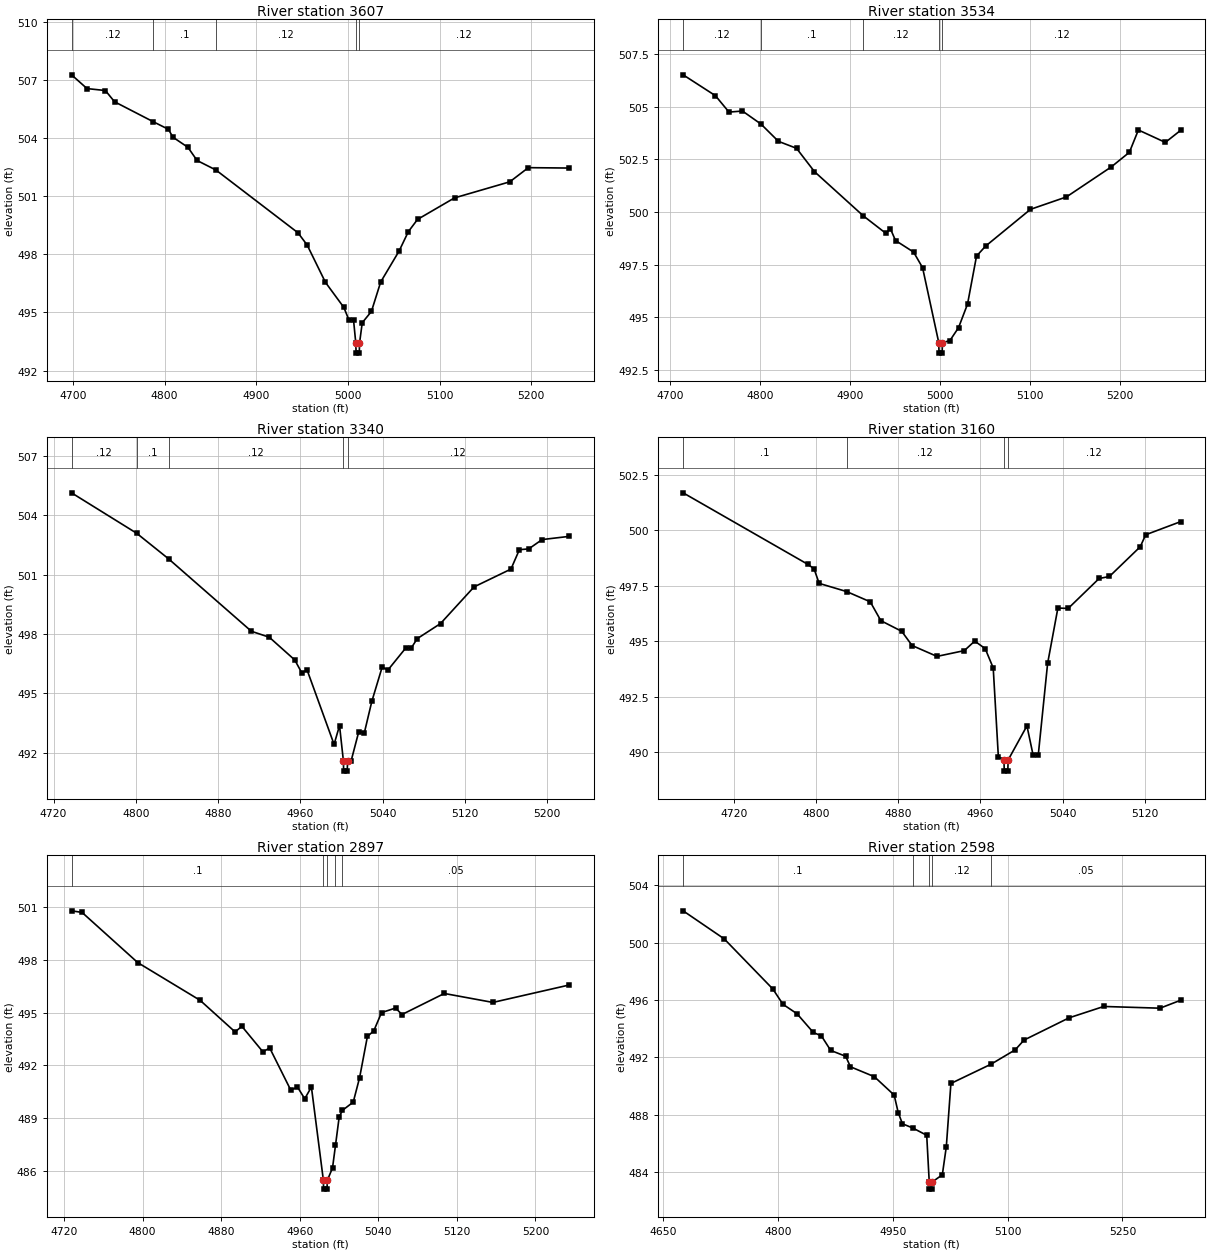
Type RM Length L Ch R = 1,3607,73,73,73
BEGIN DESCRIPTION:
Lacy 007 3355
END DESCRIPTION:
XS GIS Cut Line= 3
      2762651.56      6879634.13      2762650.00      6879937.17
      2762676.44      6880175.06
#Sta/Elev= 30
  4698.6  507.26  4715.5  506.55  4735.5  506.45  4745.5  505.87  4787.7  504.84
  4804.2  504.45  4809.2  504.04  4825.5  503.52  4835.5  502.84  4856.0  502.35
  4945.5  499.11  4955.5  498.48  4975.5  496.55  4995.5  495.26  5001.1  494.61
  5006.1  494.61  5008.6  493.40  5008.9  492.90  5012.4  492.90  5012.6  493.40
  5015.6  494.47  5025.6  495.05  5035.7  496.57  5055.8  498.17  5065.9  499.17
  5075.9  499.80  5116.2  500.91  5176.5  501.74  5196.7  502.47  5241.0  502.45
#Mann=5,-1,0
  4698.6    0.12       0  4787.7     0.1       0  4856.0    0.12       0
  5008.6    0.07       0  5012.6    0.12       0
Bank Sta=5008.6,5012.6
Exp/Cntr=0.3,0.1

Type RM Length L Ch R = 1,3534,194,194,194
BEGIN DESCRIPTION:
Lacy 007 3354
END DESCRIPTION:
XS GIS Cut Line= 3
      2762568.14      6879625.12      2762584.48      6879916.51
      2762585.35      6880177.86
#Sta/Elev= 30
  4714.1  506.51  4750.0  505.52  4765.1  504.74  4780.1  504.79  4800.7  504.17
  4820.1  503.35  4840.2  503.02  4860.2  501.91  4914.5  499.81  4939.6  498.98
  4944.6  499.20  4950.3  498.64  4970.4  498.09  4980.4  497.35  4998.4  493.79
  4998.7  493.29  5002.2  493.29  5002.4  493.79  5010.7  493.88  5020.4  494.50
  5030.4  495.62  5040.4  497.90  5050.4  498.37  5100.4  500.12  5140.4  500.71
  5190.4  502.14  5210.4  502.83  5220.4  503.89  5250.4  503.30  5267.3  503.87
#Mann=5,-1,0
  4714.1    0.12       0  4800.7     0.1       0  4914.5    0.12       0
  4998.4    0.07       0  5002.4    0.12       0
Bank Sta=4998.4,5002.4
Exp/Cntr=0.3,0.1

Type RM Length L Ch R = 1,3340,180,180,180
BEGIN DESCRIPTION:
Lacy 007 3356
END DESCRIPTION:
XS GIS Cut Line= 3
      2762482.78      6879635.23      2762397.32      6879889.40
      2762305.95      6880084.62
#Sta/Elev= 30
  4737.5  505.13  4800.8  503.09  4831.8  501.80  4912.4  498.14  4929.8  497.84
  4954.6  496.69  4961.3  496.05  4966.6  496.18  4992.8  492.43  4998.1  493.38
  5001.9  491.58  5002.1  491.08  5005.6  491.08  5005.9  491.58  5009.3  491.58
  5016.8  493.07  5022.3  493.03  5029.5  494.60  5039.6  496.34  5045.1  496.18
  5062.4  497.29  5067.9  497.30  5073.7  497.77  5096.3  498.53  5128.9  500.38
  5164.8  501.28  5173.0  502.26  5182.1  502.30  5195.1  502.77  5221.2  502.93
#Mann=5,-1,0
  4737.5    0.12       0  4800.8     0.1       0  4831.8    0.12       0
  5001.9    0.07       0  5005.9    0.12       0
Bank Sta=5001.9,5005.9
Exp/Cntr=0.3,0.1

Type RM Length L Ch R = 1,3160,263,263,263
BEGIN DESCRIPTION:
Lacy 007 3352
END DESCRIPTION:
XS GIS Cut Line= 3
      2762282.84      6879531.53      2762224.70      6879867.85
      2762232.95      6880010.10
#Sta/Elev= 30
  4670.8  501.69  4792.0  498.47  4798.1  498.27  4803.1  497.61  4829.9  497.24
  4852.8  496.78  4863.1  495.93  4883.4  495.45  4893.5  494.81  4917.7  494.32
  4944.3  494.58  4954.4  495.01  4964.6  494.67  4972.4  493.80  4977.4  489.80
  4982.9  489.65  4983.1  489.15  4986.6  489.15  4986.9  489.65  5005.2  491.19
  5011.2  489.87  5016.2  489.87  5025.3  494.00  5035.3  496.50  5045.3  496.48
  5075.4  497.83  5085.4  497.92  5115.4  499.26  5120.7  499.80  5154.6  500.39
#Mann=4,-1,0
  4670.8     0.1       0  4829.9    0.12       0  4982.9    0.07       0
  4986.9    0.12       0
Bank Sta=4982.9,4986.9
Exp/Cntr=0.3,0.1

Type RM Length L Ch R = 1,2897,299,299,299
BEGIN DESCRIPTION:
Lacy 007 3353
END DESCRIPTION:
XS GIS Cut Line= 3
      2762249.85      6879499.61      2762048.61      6879688.62
      2761870.00      6879834.02
#Sta/Elev= 30
  4727.7  500.80  4738.4  500.71  4795.1  497.85  4858.6  495.70  4894.2  493.90
  4901.1  494.22  4922.6  492.76  4929.4  492.99  4950.9  490.58  4957.7  490.76
  4965.1  490.09  4971.9  490.76  4984.1  485.44  4984.3  484.94  4987.8  484.94
  4988.1  485.44  4993.4  486.15  4996.4  487.43  5000.2  489.06  5003.5  489.43
  5014.5  489.90  5021.0  491.30  5028.9  493.64  5035.4  493.96  5043.3  495.00
  5057.6  495.26  5064.1  494.89  5107.2  496.09  5156.7  495.58  5234.1  496.57
#Mann=5,-1,0
  4727.7     0.1       0  4984.1    0.07       0  4988.1     0.1       0
  4996.4    0.12       0  5003.5    0.05       0
Bank Sta=4984.1,4988.1
Exp/Cntr=0.3,0.1

Type RM Length L Ch R = 1,2598,186,186,186
BEGIN DESCRIPTION:
Lacy 007 3351
END DESCRIPTION:
XS GIS Cut Line= 3
      2761982.80      6879200.38      2761877.00      6879506.04
      2761777.10      6879816.51
#Sta/Elev= 30
  4676.3  502.21  4729.9  500.26  4793.4  496.77  4806.7  495.70  4825.1  495.04
  4846.3  493.74  4856.9  493.50  4869.0  492.49  4888.6  492.08  4894.8  491.35
  4926.0  490.66  4951.9  489.38  4957.2  488.16  4962.7  487.38  4976.1  487.09
  4994.4  486.58  4997.7  483.33  4998.0  482.83  5001.5  482.83  5001.7  483.33
  5014.8  483.83  5020.0  485.78  5026.0  490.19  5078.4  491.53  5110.0  492.53
  5121.5  493.21  5180.4  494.76  5225.6  495.55  5299.1  495.43  5325.9  495.98
#Mann=5,-1,0
  4676.3     0.1       0  4976.1    0.12       0  4997.7    0.07       0
  5001.7    0.12       0  5078.4    0.05       0
Bank Sta=4997.7,5001.7
Exp/Cntr=0.3,0.1

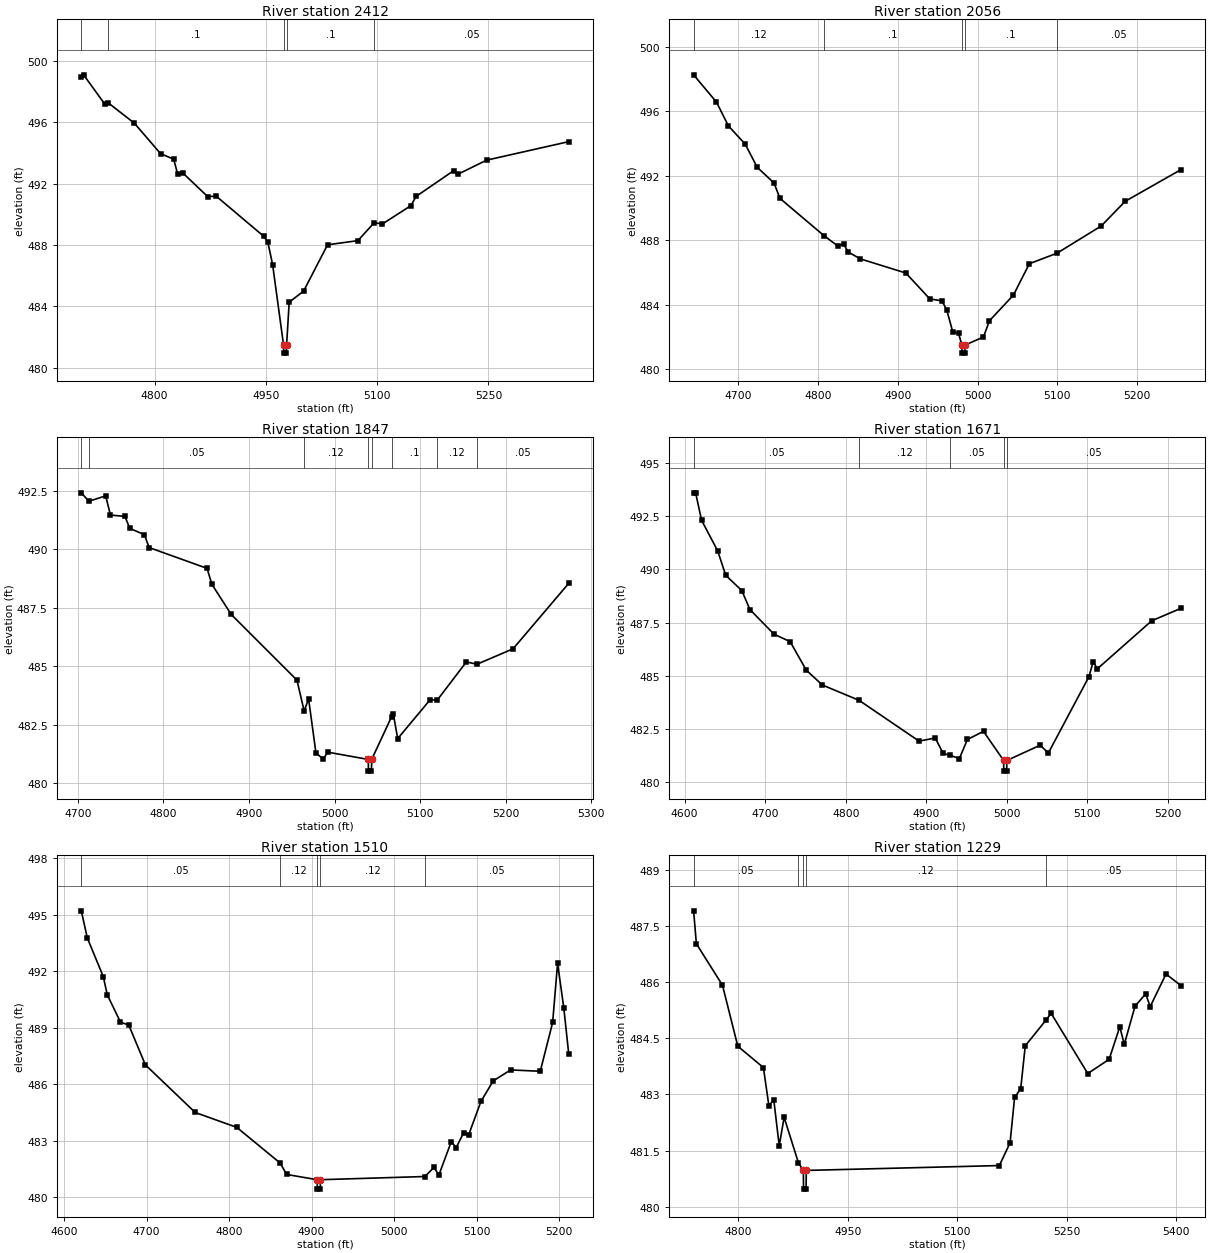
Type RM Length L Ch R = 1,2412,356,356,356
BEGIN DESCRIPTION:
Lacy 007 3350
END DESCRIPTION:
XS GIS Cut Line= 3
      2761863.35      6879105.62      2761742.24      6879376.31
      2761670.49      6879729.55
#Sta/Elev= 30
  4701.3  498.98  4704.4  499.11  4733.1  497.19  4737.4  497.29  4772.9  495.95
  4808.1  493.97  4825.9  493.60  4831.3  492.61  4838.7  492.68  4871.5  491.17
  4883.2  491.19  4947.3  488.57  4952.8  488.18  4959.2  486.72  4974.0  481.45
  4974.2  480.95  4977.7  480.95  4978.0  481.45  4981.5  484.27  5001.0  485.00
  5033.2  488.02  5074.1  488.29  5096.1  489.46  5107.2  489.38  5145.5  490.57
  5152.7  491.18  5203.3  492.86  5208.4  492.61  5247.5  493.54  5358.3  494.75
#Mann=5,-1,0
  4701.3    0.12       0  4737.4     0.1       0  4974.0    0.07       0
  4978.0     0.1       0  5096.1    0.05       0
Bank Sta=4974,4978
Exp/Cntr=0.3,0.1

Type RM Length L Ch R = 1,2056,209,209,209
BEGIN DESCRIPTION:
Lacy 007 73
END DESCRIPTION:
XS GIS Cut Line= 3
      2761626.02      6878960.98      2761426.00      6879261.00
      2761426.00      6879511.02
#Sta/Elev= 30
  4644.3  498.26  4672.9  496.57  4687.9  495.09  4708.9  493.96  4724.0  492.52
  4745.0  491.55  4752.5  490.59  4807.6  488.28  4824.6  487.65  4832.1  487.76
  4838.1  487.26  4853.1  486.84  4910.2  485.96  4940.3  484.35  4955.3  484.24
  4961.3  483.69  4968.8  482.33  4976.3  482.21  4980.3  481.49  4980.6  480.99
  4984.1  480.99  4984.3  481.49  5007.4  481.99  5014.9  483.00  5044.9  484.59
  5064.9  486.54  5099.5  487.19  5154.9  488.88  5184.9  490.41  5254.9  492.38
#Mann=5,-1,0
  4644.3    0.12       0  4807.6     0.1       0  4980.3    0.07       0
  4984.3     0.1       0  5099.5    0.05       0
Bank Sta=4980.3,4984.3
Exp/Cntr=0.3,0.1

Type RM Length L Ch R = 1,1847,176,176,176
BEGIN DESCRIPTION:
Lacy 007 3365
END DESCRIPTION:
XS GIS Cut Line= 3
      2761425.11      6878843.84      2761296.47      6879110.54
      2761236.31      6879377.75
#Sta/Elev= 30
  4703.9  492.42  4712.8  492.06  4732.4  492.29  4738.0  491.47  4755.0  491.41
  4760.6  490.90  4777.7  490.63  4783.2  490.08  4851.0  489.19  4856.6  488.51
  4879.2  487.22  4956.1  484.41  4964.5  483.09  4969.7  483.61  4978.3  481.30
  4986.7  481.04  4992.3  481.33  5039.5  481.02  5039.7  480.52  5043.2  480.52
  5043.5  481.02  5066.8  482.85  5068.8  482.96  5073.9  481.91  5112.0  483.58
  5120.0  483.55  5154.2  485.19  5166.6  485.09  5208.8  485.75  5273.9  488.55
#Mann=8,-1,0
  4703.9    0.12       0  4712.8    0.05       0  4964.5    0.12       0
  5039.5    0.07       0  5043.5    0.12       0  5066.8     0.1       0
  5120.0    0.12       0  5166.6    0.05       0
Bank Sta=5039.5,5043.5
Exp/Cntr=0.3,0.1

Type RM Length L Ch R = 1,1671,161,161,161
BEGIN DESCRIPTION:
Lacy 007 3364
END DESCRIPTION:
XS GIS Cut Line= 3
      2761146.63      6878771.13      2761136.55      6879159.90
      2761165.61      6879374.34
#Sta/Elev= 30
  4611.1  493.60  4613.6  493.60  4621.0  492.31  4641.0  490.87  4651.0  489.72
  4671.0  489.00  4681.0  488.11  4711.0  486.95  4731.0  486.60  4751.0  485.26
  4771.0  484.56  4816.6  483.84  4891.1  481.92  4911.1  482.07  4921.1  481.34
  4930.1  481.25  4941.1  481.10  4951.1  482.00  4971.1  482.38  4996.1  481.01
  4996.3  480.51  4999.8  480.51  5000.1  481.01  5041.5  481.73  5051.6  481.36
  5102.0  484.95  5107.3  485.66  5112.4  485.32  5179.9  487.58  5216.4  488.17
#Mann=5,-1,0
  4611.1    0.05       0  4816.6    0.12       0  4930.1    0.05       0
  4996.1    0.04       0  5000.1    0.05       0
Bank Sta=4996.1,5000.1
Exp/Cntr=0.3,0.1

Type RM Length L Ch R = 1,1510,281,281,281
BEGIN DESCRIPTION:
Lacy 007 3363
END DESCRIPTION:
XS GIS Cut Line= 3
      2761034.55      6878733.80      2760990.94      6879110.48
      2761109.33      6879285.98
#Sta/Elev= 30
  4620.8  495.20  4628.1  493.76  4647.4  491.71  4652.4  490.73  4668.3  489.29
  4678.4  489.13  4698.5  487.02  4758.9  484.49  4809.3  483.70  4862.0  481.80
  4869.7  481.20  4906.7  480.92  4907.0  480.42  4910.5  480.42  4910.7  480.92
  5037.3  481.09  5048.3  481.57  5054.3  481.17  5069.3  482.94  5075.3  482.63
  5084.3  483.41  5090.3  483.29  5105.3  485.08  5120.2  486.17  5141.3  486.75
  5177.2  486.68  5192.2  489.27  5198.2  492.41  5205.7  490.05  5211.7  487.60
#Mann=5,-1,0
  4620.8    0.05       0  4862.0    0.12       0  4906.7    0.07       0
  4910.7    0.12       0  5037.3    0.05       0
Bank Sta=4906.7,4910.7
Exp/Cntr=0.3,0.1

Type RM Length L Ch R = 1,1229,139,139,139
BEGIN DESCRIPTION:
Lacy 007 3362
END DESCRIPTION:
XS GIS Cut Line= 4
      2760966.01      6878775.43      2760841.47      6878888.40
      2760879.49      6879133.51      2761082.61      6879282.85
#Sta/Elev= 30
  4738.7  487.91  4742.5  487.03  4778.3  485.92  4799.3  484.29  4834.4  483.72
  4841.9  482.70  4848.6  482.86  4856.1  481.63  4862.8  482.39  4882.5  481.17
  4889.2  480.97  4889.4  480.47  4892.9  480.47  4893.2  480.97  5157.9  481.10
  5172.6  481.71  5178.8  482.92  5187.2  483.16  5193.4  484.30  5221.9  484.99
  5228.9  485.17  5279.1  483.56  5308.4  483.94  5323.0  484.81  5329.2  484.34
  5343.9  485.36  5358.5  485.69  5364.7  485.35  5386.4  486.22  5407.0  485.91
#Mann=5,-1,0
  4738.7    0.05       0  4882.5    0.12       0  4889.2    0.07       0
  4893.2    0.12       0  5221.9    0.05       0
Bank Sta=4889.2,4893.2
Exp/Cntr=0.3,0.1

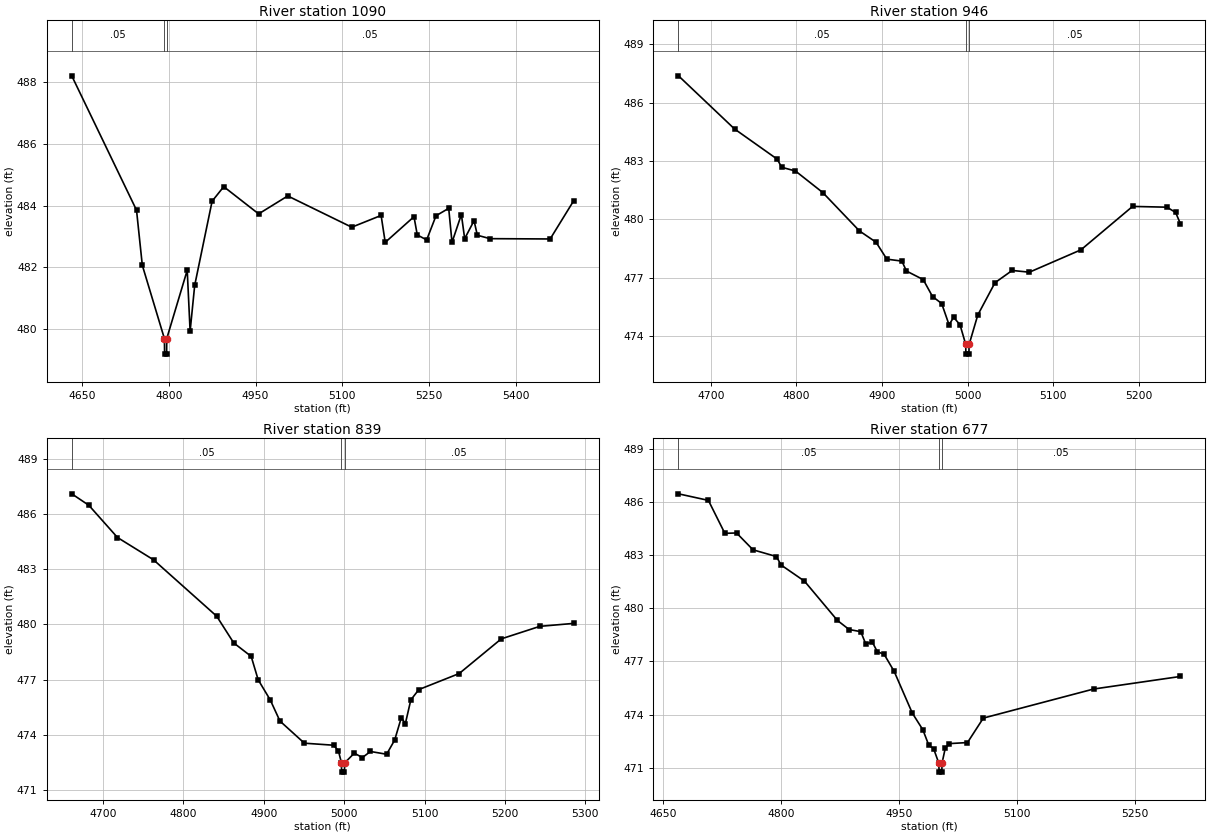
Type RM Length L Ch R = 1,1090,144,144,144
BEGIN DESCRIPTION:
Lacy 007 3361
END DESCRIPTION:
XS GIS Cut Line= 4
      2760791.31      6878599.71      2760739.05      6879116.22
      2760787.76      6879164.17      2761033.99      6879296.63
#Sta/Elev= 30
  4632.4  488.19  4744.3  483.85  4754.3  482.07  4792.5  479.70  4792.8  479.20
  4796.3  479.20  4796.5  479.70  4831.9  481.91  4836.9  479.94  4844.8  481.42
  4874.9  484.14  4895.0  484.61  4955.3  483.73  5005.6  484.31  5116.2  483.30
  5166.9  483.68  5174.0  482.81  5223.7  483.64  5229.4  483.05  5245.6  482.89
  5261.8  483.67  5283.7  483.91  5289.4  482.81  5305.6  483.71  5311.3  482.93
  5327.5  483.51  5333.2  483.04  5355.1  482.93  5459.0  482.92  5499.5  484.15
#Mann=3,-1,0
  4632.4    0.05       0  4792.5    0.05       0  4796.5    0.05       0
Bank Sta=4792.5,4796.5
Exp/Cntr=0.3,0.1

Type RM Length L Ch R = 1,946,107,107,107
BEGIN DESCRIPTION:
Lacy 007 3349
END DESCRIPTION:
XS GIS Cut Line= 3
      2760753.48      6878573.08      2760633.42      6878892.26
      2760658.19      6879136.50
#Sta/Elev= 30
  4662.1  487.38  4727.6  484.65  4777.4  483.10  4782.8  482.68  4798.8  482.49
  4830.8  481.38  4873.6  479.41  4893.0  478.83  4905.6  477.96  4923.2  477.86
  4928.5  477.35  4948.1  476.91  4959.0  476.04  4969.7  475.68  4978.3  474.59
  4983.7  474.97  4991.1  474.59  4997.8  473.58  4998.0  473.08  5001.5  473.08
  5001.8  473.58  5011.9  475.09  5032.0  476.75  5052.1  477.38  5072.2  477.29
  5132.5  478.44  5192.8  480.67  5233.0  480.63  5243.1  480.36  5248.6  479.79
#Mann=3,-1,0
  4662.1    0.05       0  4997.8    0.04       0  5001.8    0.05       0
Bank Sta=4997.8,5001.8
Exp/Cntr=0.3,0.1

Type RM Length L Ch R = 1,839,162,162,162
BEGIN DESCRIPTION:
Lacy 007 3455
END DESCRIPTION:
XS GIS Cut Line= 3
      2760727.62      6878553.12      2760544.70      6878838.54
      2760568.86      6879122.81
#Sta/Elev= 30
  4661.0  487.09  4682.2  486.47  4717.9  484.72  4762.7  483.51  4841.3  480.45
  4862.5  479.00  4884.2  478.27  4892.9  477.00  4907.9  475.91  4920.0  474.76
  4950.4  473.56  4986.7  473.45  4992.7  473.15  4996.5  472.49  4996.7  471.99
  5000.2  471.99  5000.5  472.49  5012.5  473.02  5022.5  472.78  5032.6  473.11
  5052.7  472.96  5062.7  473.73  5071.0  474.95  5076.0  474.62  5082.8  475.91
  5092.8  476.47  5143.0  477.34  5195.3  479.22  5243.3  479.90  5285.3  480.06
#Mann=3,-1,0
  4661.0    0.05       0  4996.5    0.04       0  5000.5    0.05       0
Bank Sta=4996.5,5000.5
Exp/Cntr=0.3,0.1

Type RM Length L Ch R = 1,677,0,0,0
BEGIN DESCRIPTION:
Lacy 007 3456
END DESCRIPTION:
XS GIS Cut Line= 3
      2760653.81      6878456.36      2760454.81      6878741.41
      2760465.54      6879031.18
#Sta/Elev= 30
  4670.0  486.46  4708.0  486.09  4728.9  484.23  4743.8  484.25  4764.7  483.30
  4794.4  482.92  4800.4  482.44  4830.1  481.53  4872.0  479.31  4886.8  478.80
  4901.6  478.68  4907.7  478.01  4916.5  478.07  4922.6  477.55  4931.3  477.40
  4944.0  476.44  4967.1  474.08  4980.5  473.14  4988.0  472.27  4994.1  472.08
  5000.8  471.25  5001.1  470.75  5004.6  470.75  5004.8  471.25  5008.9  472.09
  5014.3  472.36  5037.2  472.42  5057.3  473.80  5197.3  475.44  5307.6  476.15
#Mann=3,-1,0
  4670.0    0.05       0  5000.8    0.04       0  5004.8    0.05       0
Bank Sta=5000.8,5004.8
Exp/Cntr=0.3,0.1

Chan Stop Cuts=-1