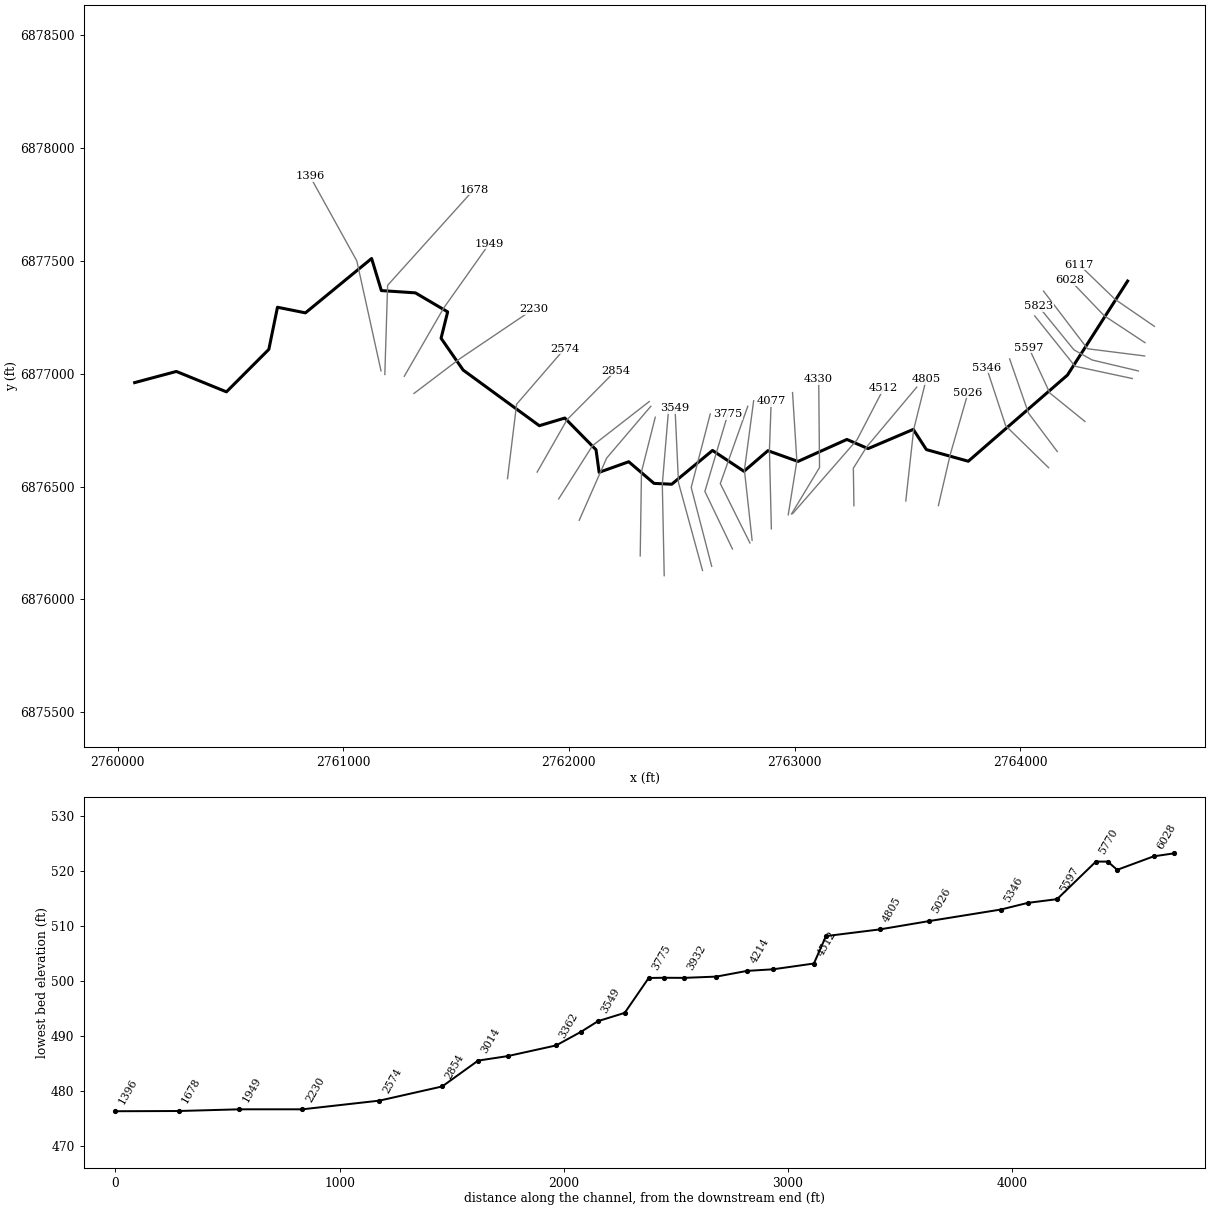
--- Lacy 009.prj (project) ---

Proj Title=Lacy 009 Base Level Engineering
Current Plan=p01
Default Exp/Contr=0.3,0.1
English Units
Geom File=g01
Flow File=f01
Plan File=p01
BEGIN DESCRIPTION:
Lacy 009
END DESCRIPTION:

--- Lacy 009.p01 (plan) ---

Plan Title=Multiple Run
Short Identifier=Multiple
Geom File=g01
Flow File=f01
Subcritical Flow
K Sum by GR= 0
Std Step Tol= 0.01
Critical Tol= 0.01
Num of Std Step Trials= 20
Max Error Tol= 0.3
Flow Tol Ratio= 0.001
Split Flow NTrial= 30
Split Flow Tol= 0.02
Split Flow Ratio= 0.02
Log Output Level= 0
Friction Slope Method= 1
Unsteady Friction Slope Method= 2
Unsteady Bridges Friction Slope Method= 1
Parabolic Critical Depth
Global Vel Dist=  1 , 1 , 1
Global Log Level= 0
CheckData=True
Encroach Param= -1, 0, 0, 0
BEGIN DESCRIPTION:
Multiple Run
END DESCRIPTION:

--- Lacy 009.f01 (steady flow) ---

Flow Title=Multiple
Number of Profiles=7
Profile Names=10-year,25-year,50-year,1pct_min,100-year,1pct_plu,500-year
River Rch & RM= Lacy 009,Reach-1,6117
     275     353     413     241     482     961     654
Boundary for River Rch & Prof#=Lacy 009,Reach-1,1
Up Type=0
Dn Type=3
Dn Slope=0.005
Boundary for River Rch & Prof#=Lacy 009,Reach-1,2
Up Type=0
Dn Type=3
Dn Slope=0.005
Boundary for River Rch & Prof#=Lacy 009,Reach-1,3
Up Type=0
Dn Type=3
Dn Slope=0.005
Boundary for River Rch & Prof#=Lacy 009,Reach-1,4
Up Type=0
Dn Type=3
Dn Slope=0.005
Boundary for River Rch & Prof#=Lacy 009,Reach-1,5
Up Type=0
Dn Type=3
Dn Slope=0.005
Boundary for River Rch & Prof#=Lacy 009,Reach-1,6
Up Type=0
Dn Type=3
Dn Slope=0.005
Boundary for River Rch & Prof#=Lacy 009,Reach-1,7
Up Type=0
Dn Type=3
Dn Slope=0.005

--- Lacy 009.g01 (geometry) ---

Geom Title=Existing Conditions

River Reach=Lacy 009,Reach-1
Reach XY= 30
      2764476.00      6877411.00      2764209.35      6876994.33
      2763769.97      6876612.62      2763584.34      6876664.21
      2763526.30      6876753.74      2763325.99      6876668.59
      2763232.13      6876709.14      2763015.31      6876611.77
      2762882.03      6876659.36      2762776.00      6876568.10
      2762636.64      6876660.45      2762455.94      6876510.78
      2762377.50      6876514.47      2762265.37      6876610.39
      2762134.15      6876563.50      2762120.51      6876663.38
      2761982.14      6876804.02      2761869.27      6876770.13
      2761531.62      6877016.62      2761433.83      6877157.60
      2761463.01      6877274.56      2761320.07      6877358.75
      2761169.18      6877368.81      2761126.00      6877511.00
      2760832.73      6877270.15      2760708.86      6877294.96
      2760670.60      6877108.32      2760482.75      6876920.12
      2760260.78      6877010.50      2760076.00      6876961.00

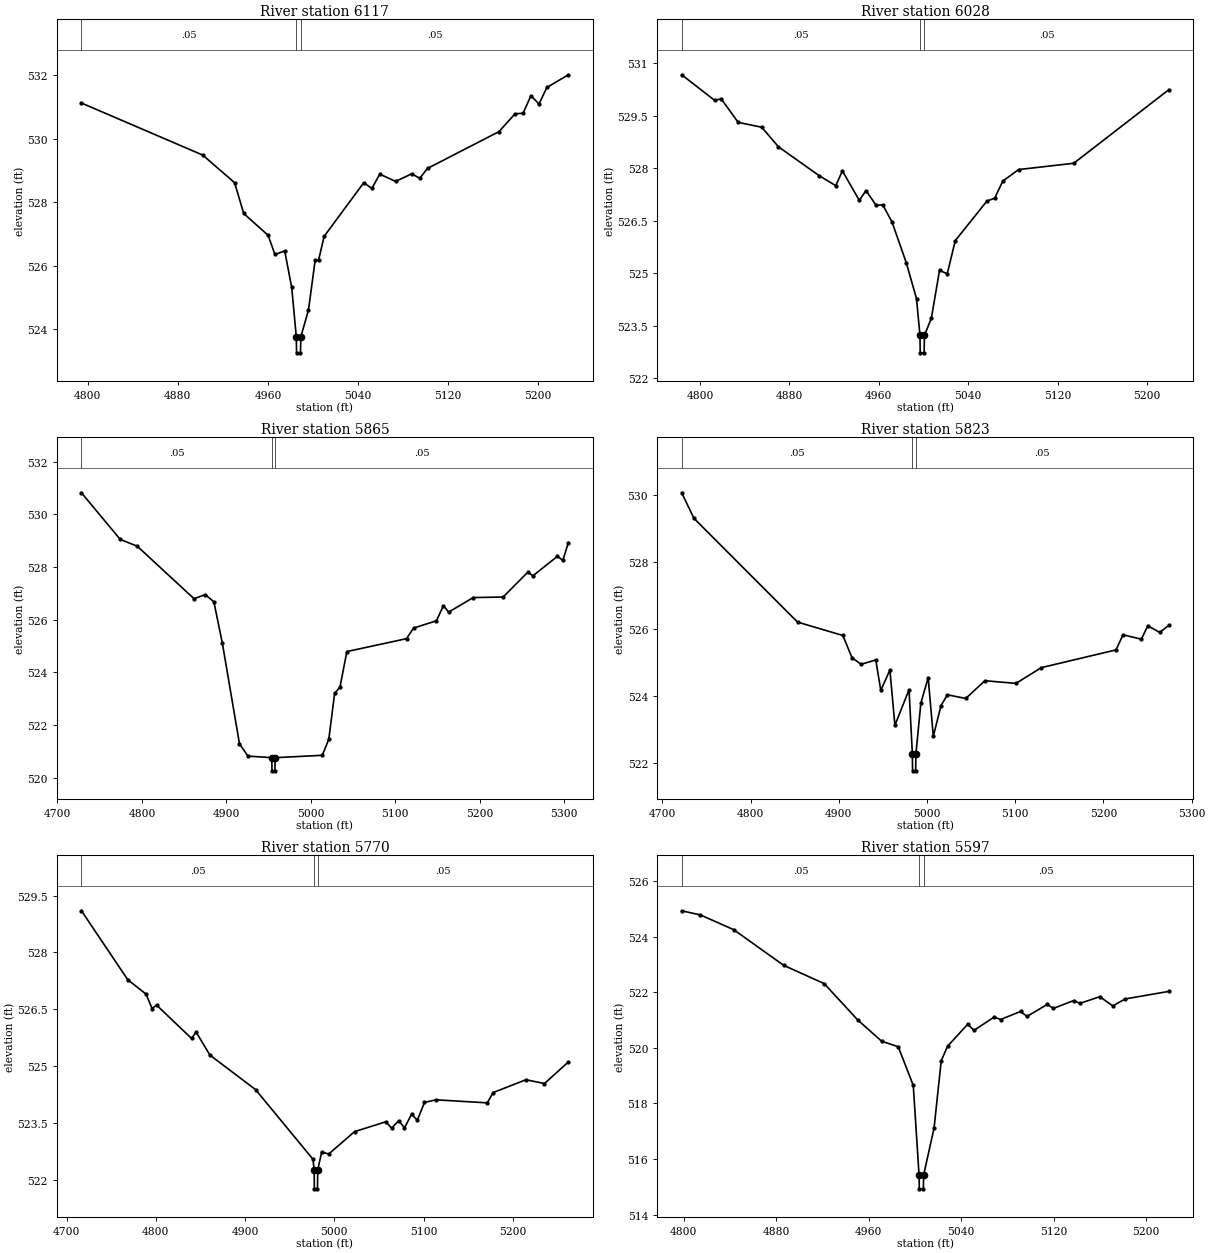
Type RM Length L Ch R = 1,6117,89,89,89
BEGIN DESCRIPTION:
Lacy 009 3515
END DESCRIPTION:
XS GIS Cut Line= 3
      2764594.83      6877210.25      2764421.30      6877329.38
      2764261.60      6877483.47
#Sta/Elev= 30
  4794.4  531.12  4902.1  529.48  4930.4  528.61  4938.5  527.64  4960.2  526.95
  4966.2  526.35  4974.9  526.46  4981.1  525.31  4985.2  523.75  4985.4  523.25
  4988.9  523.25  4989.2  523.75  4996.0  524.60  5001.9  526.16  5004.9  526.16
  5009.9  526.92  5045.1  528.61  5052.3  528.43  5059.3  528.88  5073.4  528.65
  5087.6  528.89  5094.8  528.75  5101.7  529.06  5165.2  530.22  5179.4  530.78
  5186.6  530.80  5193.5  531.35  5200.7  531.09  5207.7  531.61  5226.8  532.01
#Mann=3,-1,0
  4794.4    0.05       0  4985.2    0.05       0  4989.2    0.05       0
Bank Sta=4985.2,4989.2
Exp/Cntr=0.3,0.1

Type RM Length L Ch R = 1,6028,163,163,163
BEGIN DESCRIPTION:
Lacy 009 3336
END DESCRIPTION:
XS GIS Cut Line= 3
      2764553.02      6877138.09      2764372.51      6877257.27
      2764220.62      6877415.58
#Sta/Elev= 30
  4783.7  530.67  4813.1  529.94  4819.1  529.98  4834.2  529.31  4855.3  529.17
  4870.3  528.61  4906.5  527.79  4921.5  527.50  4927.5  527.92  4942.6  527.08
  4948.6  527.36  4957.6  526.94  4963.6  526.95  4971.9  526.46  4984.7  525.29
  4993.8  524.27  4996.9  523.22  4997.1  522.72  5000.6  522.72  5000.9  523.22
  5007.1  523.71  5014.4  525.08  5021.3  524.98  5028.5  525.93  5056.8  527.06
  5063.7  527.14  5071.0  527.63  5085.1  527.96  5134.5  528.14  5219.4  530.24
#Mann=3,-1,0
  4783.7    0.05       0  4996.9    0.04       0  5000.9    0.05       0
Bank Sta=4996.9,5000.9
Exp/Cntr=0.3,0.1

Type RM Length L Ch R = 1,5865,42,42,42
BEGIN DESCRIPTION:
Lacy 009 3335
END DESCRIPTION:
XS GIS Cut Line= 3
      2764551.59      6877079.17      2764298.35      6877111.05
      2764103.40      6877366.53
#Sta/Elev= 30
  4728.4  530.82  4774.3  529.05  4794.5  528.79  4861.6  526.80  4875.1  526.95
  4885.2  526.68  4895.3  525.10  4915.5  521.29  4925.5  520.82  4953.8  520.76
  4954.0  520.26  4957.5  520.26  4957.8  520.76  5013.6  520.85  5021.3  521.46
  5028.2  523.20  5034.5  523.44  5042.7  524.79  5113.4  525.28  5121.6  525.68
  5148.8  525.96  5157.0  526.53  5163.3  526.29  5192.3  526.84  5227.7  526.86
  5256.8  527.80  5263.1  527.67  5292.1  528.41  5298.4  528.25  5305.0  528.93
#Mann=3,-1,0
  4728.4    0.05       0  4953.8    0.04       0  4957.8    0.05       0
Bank Sta=4953.8,4957.8
Exp/Cntr=0.3,0.1

Type RM Length L Ch R = 1,5823,53,53,53
BEGIN DESCRIPTION:
Lacy 009 3334
END DESCRIPTION:
XS GIS Cut Line= 4
      2764523.80      6877012.69      2764318.65      6877061.32
      2764238.30      6877106.11      2764080.91      6877299.29
#Sta/Elev= 30
  4721.9  530.06  4735.7  529.30  4853.2  526.20  4904.6  525.80  4914.9  525.14
  4925.2  524.94  4941.9  525.07  4947.6  524.16  4957.9  524.77  4963.6  523.12
  4979.6  524.18  4983.4  522.26  4983.6  521.76  4987.1  521.76  4987.4  522.26
  4993.0  523.78  5001.3  524.54  5007.1  522.79  5015.9  523.71  5023.1  524.03
  5043.9  523.92  5065.6  524.45  5100.8  524.37  5129.5  524.84  5214.2  525.37
  5222.2  525.82  5243.0  525.69  5250.3  526.09  5263.8  525.89  5273.9  526.10
#Mann=3,-1,0
  4721.9    0.05       0  4983.4    0.04       0  4987.4    0.05       0
Bank Sta=4983.4,4987.4
Exp/Cntr=0.3,0.1

Type RM Length L Ch R = 1,5770,173,173,173
BEGIN DESCRIPTION:
Lacy 009 3333
END DESCRIPTION:
XS GIS Cut Line= 3
      2764496.79      6876979.11      2764243.02      6877033.49
      2764064.23      6877256.93
#Sta/Elev= 30
  4716.6  529.10  4768.5  527.28  4789.0  526.90  4795.7  526.52  4800.8  526.61
  4840.0  525.73  4845.1  525.90  4860.6  525.29  4911.7  524.38  4976.1  522.54
  4977.4  522.26  4977.6  521.76  4981.1  521.76  4981.4  522.26  4985.8  522.73
  4993.8  522.68  5022.6  523.27  5057.8  523.53  5064.2  523.36  5072.2  523.56
  5078.6  523.37  5086.6  523.73  5093.0  523.57  5101.0  524.04  5113.8  524.11
  5171.4  524.03  5177.9  524.30  5214.7  524.64  5235.5  524.54  5262.3  525.11
#Mann=3,-1,0
  4716.6    0.05       0  4977.4    0.04       0  4981.4    0.05       0
Bank Sta=4977.4,4981.4
Exp/Cntr=0.3,0.1

Type RM Length L Ch R = 1,5597,131,131,131
BEGIN DESCRIPTION:
Lacy 009 3332
END DESCRIPTION:
XS GIS Cut Line= 3
      2764287.19      6876788.66      2764131.48      6876914.71
      2764038.50      6877115.06
#Sta/Elev= 30
  4798.2  524.93  4814.4  524.78  4843.2  524.25  4886.3  522.97  4921.5  522.31
  4950.3  521.01  4971.1  520.24  4985.5  520.04  4998.5  518.65  5003.5  515.43
  5003.7  514.93  5007.2  514.93  5007.5  515.43  5016.5  517.12  5022.7  519.54
  5028.2  520.06  5045.6  520.85  5051.1  520.63  5068.5  521.11  5074.0  521.02
  5091.4  521.31  5096.9  521.13  5114.3  521.56  5119.8  521.42  5137.2  521.70
  5142.7  521.60  5159.8  521.84  5171.1  521.51  5181.9  521.76  5219.4  522.03
#Mann=3,-1,0
  4798.2    0.05       0  5003.5    0.04       0  5007.5    0.05       0
Bank Sta=5003.5,5007.5
Exp/Cntr=0.3,0.1

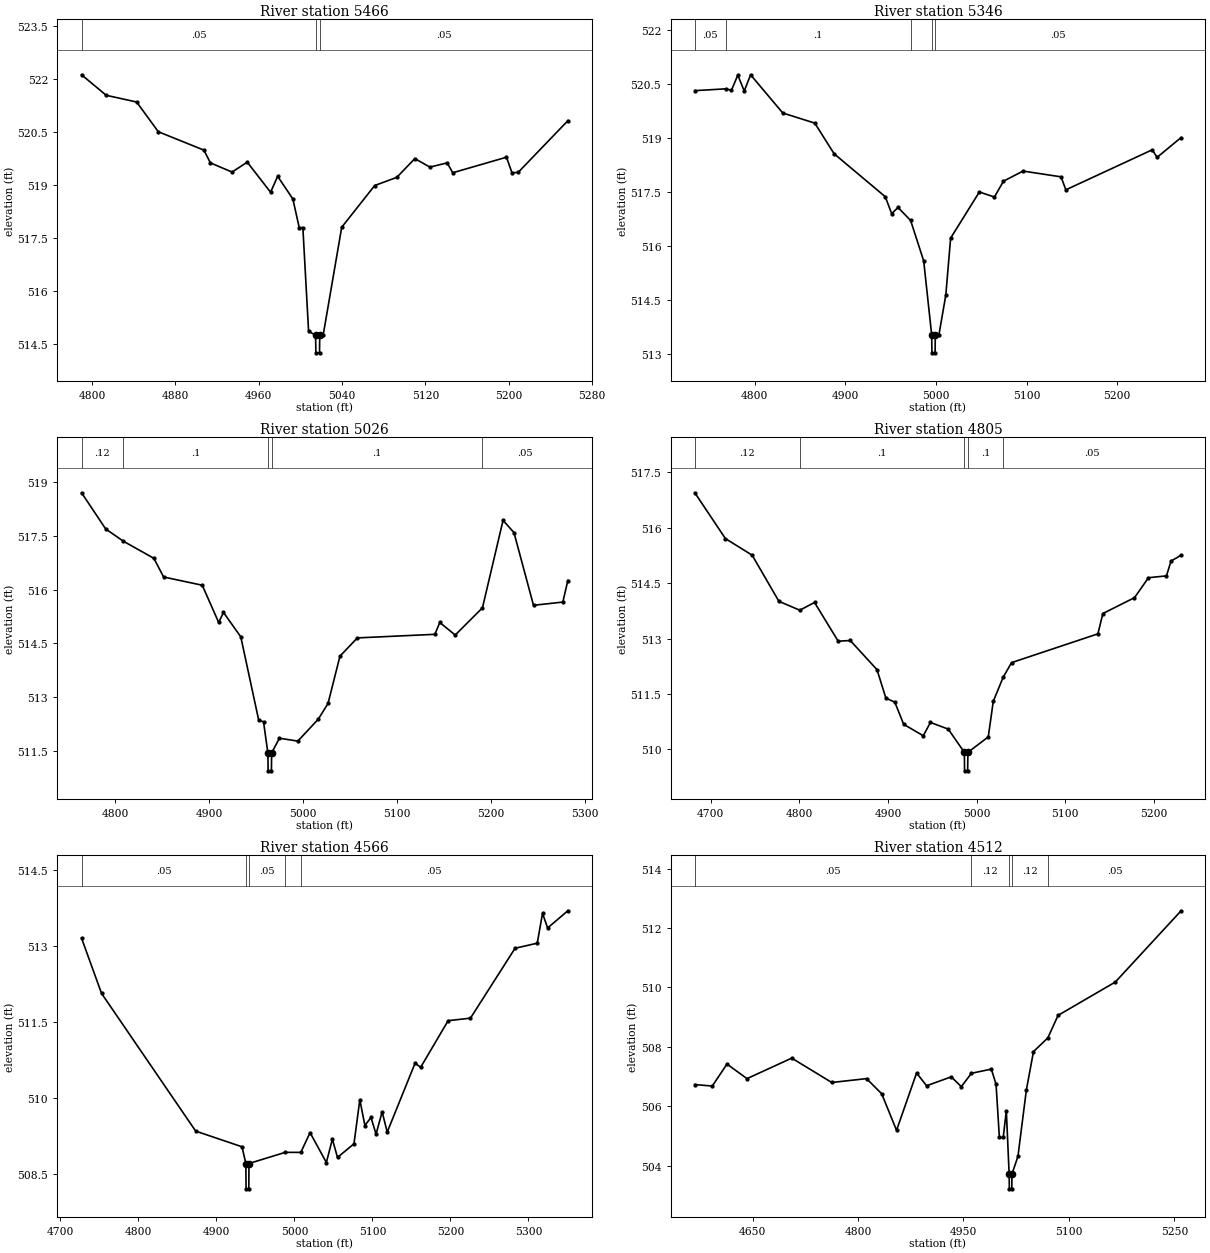
Type RM Length L Ch R = 1,5466,120,120,120
BEGIN DESCRIPTION:
Lacy 009 3331
END DESCRIPTION:
XS GIS Cut Line= 3
      2764164.25      6876655.76      2764036.81      6876825.80
      2763953.17      6877066.06
#Sta/Elev= 30
  4789.8  522.11  4813.5  521.53  4842.7  521.34  4863.5  520.50  4907.3  519.98
  4913.5  519.62  4934.3  519.36  4948.9  519.64  4971.3  518.79  4978.1  519.24
  4992.7  518.60  4998.8  517.79  5002.3  517.79  5007.8  514.86  5014.5  514.75
  5014.8  514.25  5018.3  514.25  5018.5  514.75  5021.8  514.75  5039.6  517.80
  5071.3  518.98  5092.5  519.21  5109.8  519.74  5124.3  519.50  5140.9  519.62
  5146.2  519.34  5197.8  519.78  5203.1  519.34  5209.0  519.35  5256.7  520.81
#Mann=3,-1,0
  4789.8    0.05       0  5014.5    0.04       0  5018.5    0.05       0
Bank Sta=5014.5,5018.5
Exp/Cntr=0.3,0.1

Type RM Length L Ch R = 1,5346,320,320,320
BEGIN DESCRIPTION:
Lacy 009 3330
END DESCRIPTION:
XS GIS Cut Line= 3
      2764125.96      6876583.92      2763935.76      6876769.74
      2763851.18      6877026.57
#Sta/Elev= 30
  4734.1  520.31  4768.1  520.36  4774.5  520.32  4781.5  520.74  4788.6  520.30
  4795.6  520.75  4831.1  519.69  4866.4  519.41  4887.7  518.56  4944.1  517.37
  4951.2  516.90  4958.2  517.07  4972.1  516.71  4986.5  515.59  4995.3  513.54
  4995.6  513.04  4999.1  513.04  4999.3  513.54  5003.3  513.54  5010.9  514.64
  5016.2  516.22  5047.9  517.50  5064.5  517.36  5074.5  517.80  5096.1  518.08
  5138.0  517.92  5143.3  517.56  5238.6  518.67  5243.9  518.46  5270.4  519.01
#Mann=5,-1,0
  4734.1    0.05       0  4768.1     0.1       0  4972.1    0.05       0
  4995.3    0.04       0  4999.3    0.05       0
Bank Sta=4995.3,4999.3
Exp/Cntr=0.3,0.1

Type RM Length L Ch R = 1,5026,221,221,221
BEGIN DESCRIPTION:
Lacy 009 3329
END DESCRIPTION:
XS GIS Cut Line= 3
      2763637.45      6876415.97      2763690.54      6876644.11
      2763768.94      6876916.10
#Sta/Elev= 30
  4764.3  518.70  4790.0  517.69  4808.7  517.35  4841.3  516.87  4851.6  516.35
  4892.7  516.12  4910.2  515.08  4915.3  515.36  4933.7  514.68  4952.8  512.35
  4957.9  512.31  4962.5  511.44  4962.8  510.94  4966.3  510.94  4966.5  511.44
  4974.8  511.85  4994.4  511.77  5016.1  512.38  5026.5  512.82  5039.2  514.14
  5057.7  514.65  5140.2  514.75  5145.4  515.08  5161.8  514.73  5190.8  515.49
  5212.7  517.93  5224.3  517.59  5245.1  515.56  5276.3  515.65  5281.6  516.25
#Mann=5,-1,0
  4764.3    0.12       0  4808.7     0.1       0  4962.5    0.07       0
  4966.5     0.1       0  5190.8    0.05       0
Bank Sta=4962.5,4966.5
Exp/Cntr=0.3,0.1

Type RM Length L Ch R = 1,4805,239,239,239
BEGIN DESCRIPTION:
Lacy 009 3328
END DESCRIPTION:
XS GIS Cut Line= 3
      2763493.12      6876436.67      2763527.91      6876752.68
      2763583.83      6876976.69
#Sta/Elev= 30
  4681.9  516.95  4716.4  515.71  4746.6  515.26  4776.8  514.01  4800.4  513.77
  4817.0  513.98  4843.7  512.93  4857.3  512.95  4887.5  512.16  4897.5  511.39
  4907.6  511.28  4917.6  510.68  4939.7  510.37  4947.8  510.73  4967.9  510.55
  4986.1  509.92  4986.3  509.42  4989.8  509.42  4990.1  509.92  5013.1  510.34
  5018.7  511.30  5029.8  511.95  5039.3  512.35  5136.8  513.13  5142.4  513.68
  5178.1  514.11  5193.9  514.65  5214.2  514.70  5219.3  515.10  5230.7  515.26
#Mann=5,-1,0
  4681.9    0.12       0  4800.4     0.1       0  4986.1    0.07       0
  4990.1     0.1       0  5029.8    0.05       0
Bank Sta=4986.1,4990.1
Exp/Cntr=0.3,0.1

Type RM Length L Ch R = 1,4566,54,54,54
BEGIN DESCRIPTION:
Lacy 009 3327
END DESCRIPTION:
XS GIS Cut Line= 4
      2763263.23      6876415.42      2763260.62      6876581.60
      2763319.93      6876676.57      2763541.69      6876941.03
#Sta/Elev= 30
  4727.1  513.16  4752.7  512.07  4873.4  509.35  4932.8  509.04  4937.7  508.71
  4938.0  508.21  4941.5  508.21  4941.7  508.71  4988.1  508.93  5008.2  508.93
  5020.0  509.32  5040.9  508.73  5048.6  509.19  5055.2  508.83  5076.3  509.10
  5083.8  509.97  5090.3  509.46  5098.1  509.62  5104.6  509.29  5112.4  509.73
  5118.9  509.33  5154.6  510.69  5161.8  510.61  5197.0  511.53  5225.6  511.58
  5282.8  512.96  5311.2  513.06  5318.0  513.65  5324.5  513.36  5350.4  513.70
#Mann=5,-1,0
  4727.1    0.05       0  4937.7    0.07       0  4941.7    0.05       0
  4988.1    0.12       0  5008.2    0.05       0
Bank Sta=4937.7,4941.7
Exp/Cntr=0.3,0.1

Type RM Length L Ch R = 1,4512,182,182,182
BEGIN DESCRIPTION:
Lacy 009 3323
END DESCRIPTION:
XS GIS Cut Line= 3
      2762991.75      6876380.70      2763277.24      6876708.12
      2763395.60      6876936.24
#Sta/Elev= 30
  4568.0  506.73  4592.8  506.68  4613.7  507.42  4642.2  506.93  4705.8  507.62
  4762.7  506.80  4812.1  506.93  4833.7  506.42  4854.8  505.19  4883.3  507.12
  4897.5  506.69  4932.6  506.99  4946.9  506.66  4961.3  507.11  4989.6  507.25
  4996.3  506.74  5001.0  504.95  5006.5  504.95  5010.9  505.85  5014.9  503.72
  5015.2  503.22  5018.7  503.22  5018.9  503.72  5027.4  504.31  5039.4  506.55
  5049.5  507.84  5069.9  508.30  5084.5  509.06  5165.8  510.18  5259.4  512.58
#Mann=5,-1,0
  4568.0    0.05       0  4961.3    0.12       0  5014.9    0.07       0
  5018.9    0.12       0  5069.9    0.05       0
Bank Sta=5014.9,5018.9
Exp/Cntr=0.3,0.1

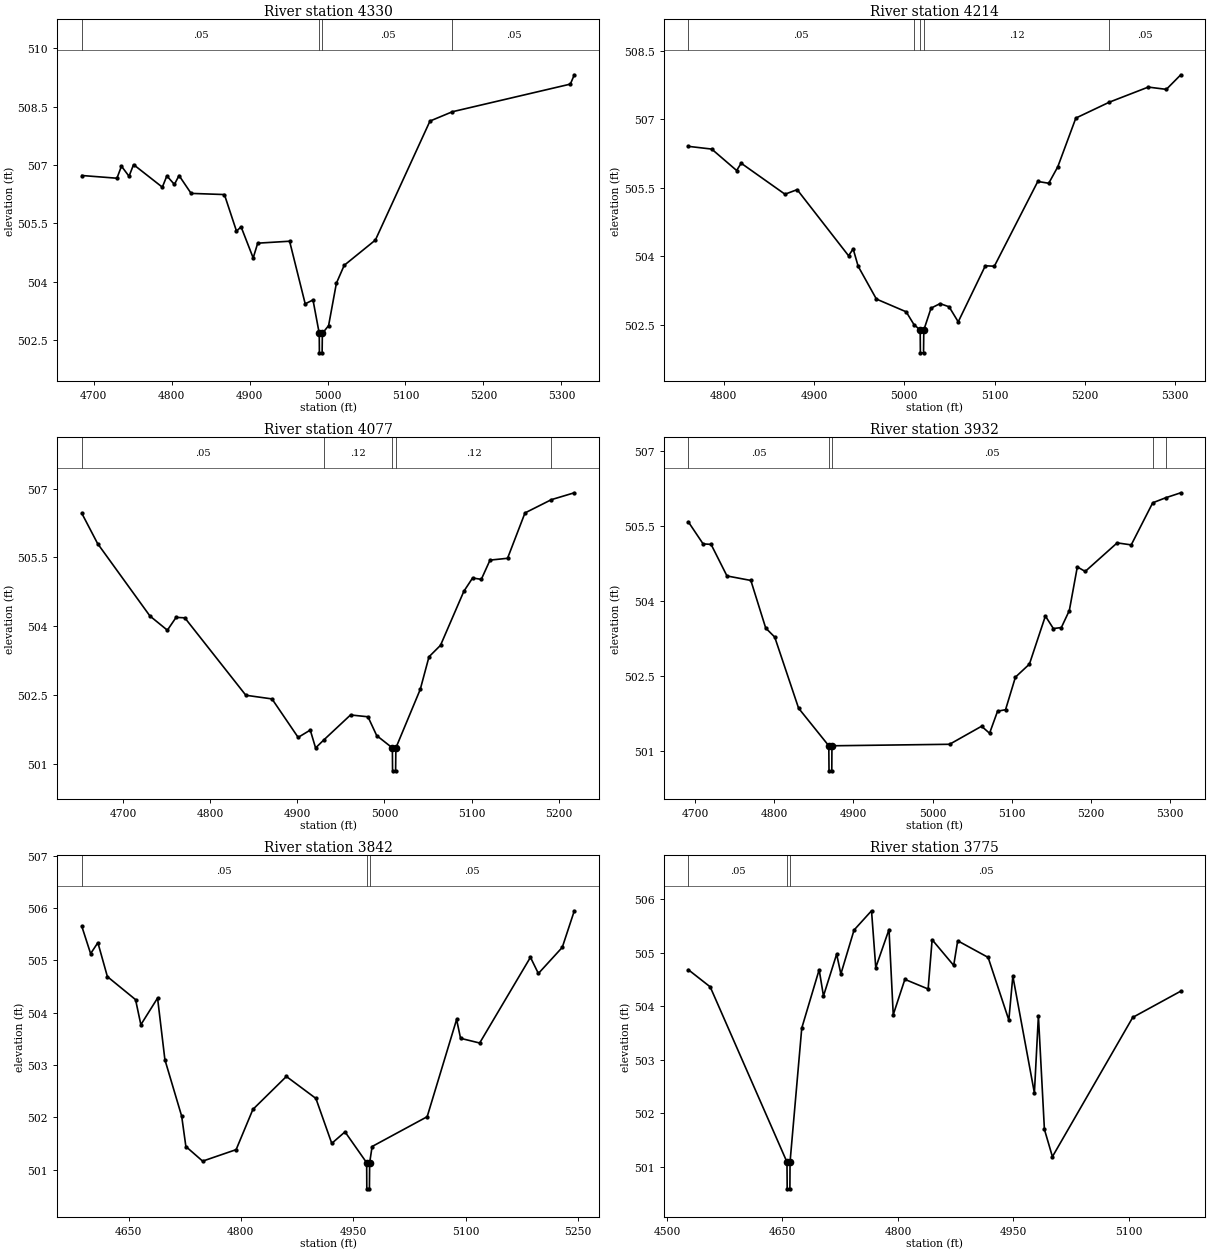
Type RM Length L Ch R = 1,4330,116,116,116
BEGIN DESCRIPTION:
Lacy 009 3326
END DESCRIPTION:
XS GIS Cut Line= 3
      2762986.75      6876379.17      2763110.86      6876584.85
      2763107.12      6876976.11
#Sta/Elev= 30
  4685.0  506.73  4730.0  506.66  4735.8  506.97  4745.5  506.71  4751.3  507.01
  4788.2  506.43  4794.0  506.72  4803.7  506.50  4809.6  506.73  4825.1  506.27
  4867.8  506.24  4883.3  505.30  4889.2  505.41  4904.7  504.61  4910.5  504.99
  4951.4  505.04  4971.4  503.43  4981.4  503.53  4989.4  502.67  4989.6  502.17
  4993.1  502.17  4993.4  502.67  5001.4  502.87  5011.4  503.96  5021.4  504.42
  5061.4  505.07  5131.4  508.13  5160.2  508.37  5311.4  509.08  5316.5  509.32
#Mann=4,-1,0
  4685.0    0.05       0  4989.4    0.07       0  4993.4    0.05       0
  5160.2    0.05       0
Bank Sta=4989.4,4993.4
Exp/Cntr=0.3,0.1

Type RM Length L Ch R = 1,4214,137,137,137
BEGIN DESCRIPTION:
Lacy 009 3325
END DESCRIPTION:
XS GIS Cut Line= 3
      2762972.19      6876375.40      2763010.36      6876613.56
      2762991.21      6876916.95
#Sta/Elev= 30
  4760.9  506.41  4786.8  506.35  4814.4  505.88  4819.4  506.04  4867.9  505.36
  4881.4  505.46  4938.3  504.01  4943.4  504.16  4948.9  503.78  4969.1  503.06
  5002.1  502.78  5010.7  502.50  5017.6  502.38  5017.8  501.88  5021.3  501.88
  5021.6  502.38  5029.6  502.86  5039.6  502.96  5049.6  502.89  5059.7  502.56
  5089.7  503.79  5099.7  503.78  5147.8  505.64  5159.9  505.60  5169.9  505.96
  5189.9  507.03  5227.1  507.38  5270.1  507.71  5290.1  507.66  5306.1  507.98
#Mann=5,-1,0
  4760.9    0.05       0  5010.7    0.12       0  5017.6    0.04       0
  5021.6    0.12       0  5227.1    0.05       0
Bank Sta=5017.6,5021.6
Exp/Cntr=0.3,0.1

Type RM Length L Ch R = 1,4077,145,145,145
BEGIN DESCRIPTION:
Lacy 009 3324
END DESCRIPTION:
XS GIS Cut Line= 3
      2762897.40      6876312.94      2762888.82      6876662.53
      2762896.65      6876877.59
#Sta/Elev= 30
  4652.9  506.46  4671.0  505.80  4731.0  504.22  4751.0  503.91  4761.0  504.19
  4771.0  504.18  4841.0  502.49  4871.0  502.41  4901.0  501.57  4914.9  501.73
  4921.0  501.34  4930.2  501.51  4961.1  502.06  4981.1  502.02  4991.1  501.61
  5009.1  501.34  5009.3  500.84  5012.8  500.84  5013.1  501.34  5041.1  502.62
  5051.1  503.33  5064.3  503.58  5091.1  504.76  5101.1  505.05  5111.1  505.02
  5121.1  505.44  5141.2  505.48  5161.2  506.47  5191.5  506.76  5217.8  506.91
#Mann=5,-1,0
  4652.9    0.05       0  4930.2    0.12       0  5009.1    0.07       0
  5013.1    0.12       0  5191.5    0.05       0
Bank Sta=5009.1,5013.1
Exp/Cntr=0.3,0.1

Type RM Length L Ch R = 1,3932,90,90,90
BEGIN DESCRIPTION:
Lacy 009 3322
END DESCRIPTION:
XS GIS Cut Line= 3
      2762812.05      6876262.37      2762778.02      6876573.22
      2762818.90      6876880.80
#Sta/Elev= 30
  4691.1  505.58  4709.8  505.14  4719.9  505.13  4740.0  504.50  4770.2  504.41
  4789.0  503.46  4800.4  503.28  4830.6  501.86  4868.8  501.11  4869.1  500.61
  4872.6  500.61  4872.8  501.11  5021.6  501.14  5062.1  501.50  5072.2  501.36
  5082.3  501.80  5092.4  501.83  5104.9  502.48  5122.6  502.74  5142.8  503.70
  5152.9  503.45  5163.0  503.47  5173.1  503.81  5183.2  504.68  5193.2  504.59
  5233.6  505.16  5251.4  505.12  5278.6  505.96  5294.9  506.06  5314.1  506.16
#Mann=5,-1,0
  4691.1    0.05       0  4868.8    0.04       0  4872.8    0.05       0
  5278.6    0.12       0  5294.9    0.05       0
Bank Sta=4868.8,4872.8
Exp/Cntr=0.3,0.1

Type RM Length L Ch R = 1,3842,67,67,67
BEGIN DESCRIPTION:
Lacy 009 3321
END DESCRIPTION:
XS GIS Cut Line= 3
      2762802.37      6876250.49      2762671.16      6876513.58
      2762792.91      6876856.20
#Sta/Elev= 30
  4587.7  505.65  4599.4  505.13  4609.1  505.34  4621.8  504.69  4659.4  504.25
  4666.5  503.77  4688.8  504.28  4698.6  503.10  4721.0  502.02  4726.6  501.44
  4749.0  501.16  4793.7  501.38  4816.1  502.15  4860.8  502.78  4900.2  502.36
  4921.4  501.50  4939.1  501.72  4968.0  501.13  4968.2  500.63  4971.7  500.63
  4972.0  501.13  4975.3  501.44  5048.8  502.01  5088.1  503.87  5093.4  503.51
  5118.9  503.42  5186.7  505.06  5197.3  504.75  5229.2  505.25  5245.3  505.95
#Mann=3,-1,0
  4587.7    0.05       0  4968.0    0.04       0  4972.0    0.05       0
Bank Sta=4968,4972
Exp/Cntr=0.3,0.1

Type RM Length L Ch R = 1,3775,107,107,107
BEGIN DESCRIPTION:
Lacy 009 3320
END DESCRIPTION:
XS GIS Cut Line= 3
      2762724.93      6876223.85      2762602.76      6876478.86
      2762704.44      6876820.80
#Sta/Elev= 30
  4527.8  504.68  4556.2  504.36  4655.9  501.09  4656.2  500.59  4659.7  500.59
  4659.9  501.09  4675.1  503.59  4697.7  504.68  4703.3  504.19  4720.4  504.97
  4725.9  504.60  4743.0  505.42  4765.7  505.78  4771.2  504.72  4788.4  505.43
  4793.9  503.84  4809.0  504.50  4839.2  504.32  4844.4  505.24  4872.4  504.76
  4877.6  505.22  4917.1  504.91  4944.0  503.74  4949.2  504.56  4977.2  502.38
  4982.4  503.82  4990.2  501.70  5000.6  501.19  5104.9  503.79  5167.3  504.28
#Mann=3,-1,0
  4527.8    0.05       0  4655.9    0.04       0  4659.9    0.05       0
Bank Sta=4655.9,4659.9
Exp/Cntr=0.3,0.1

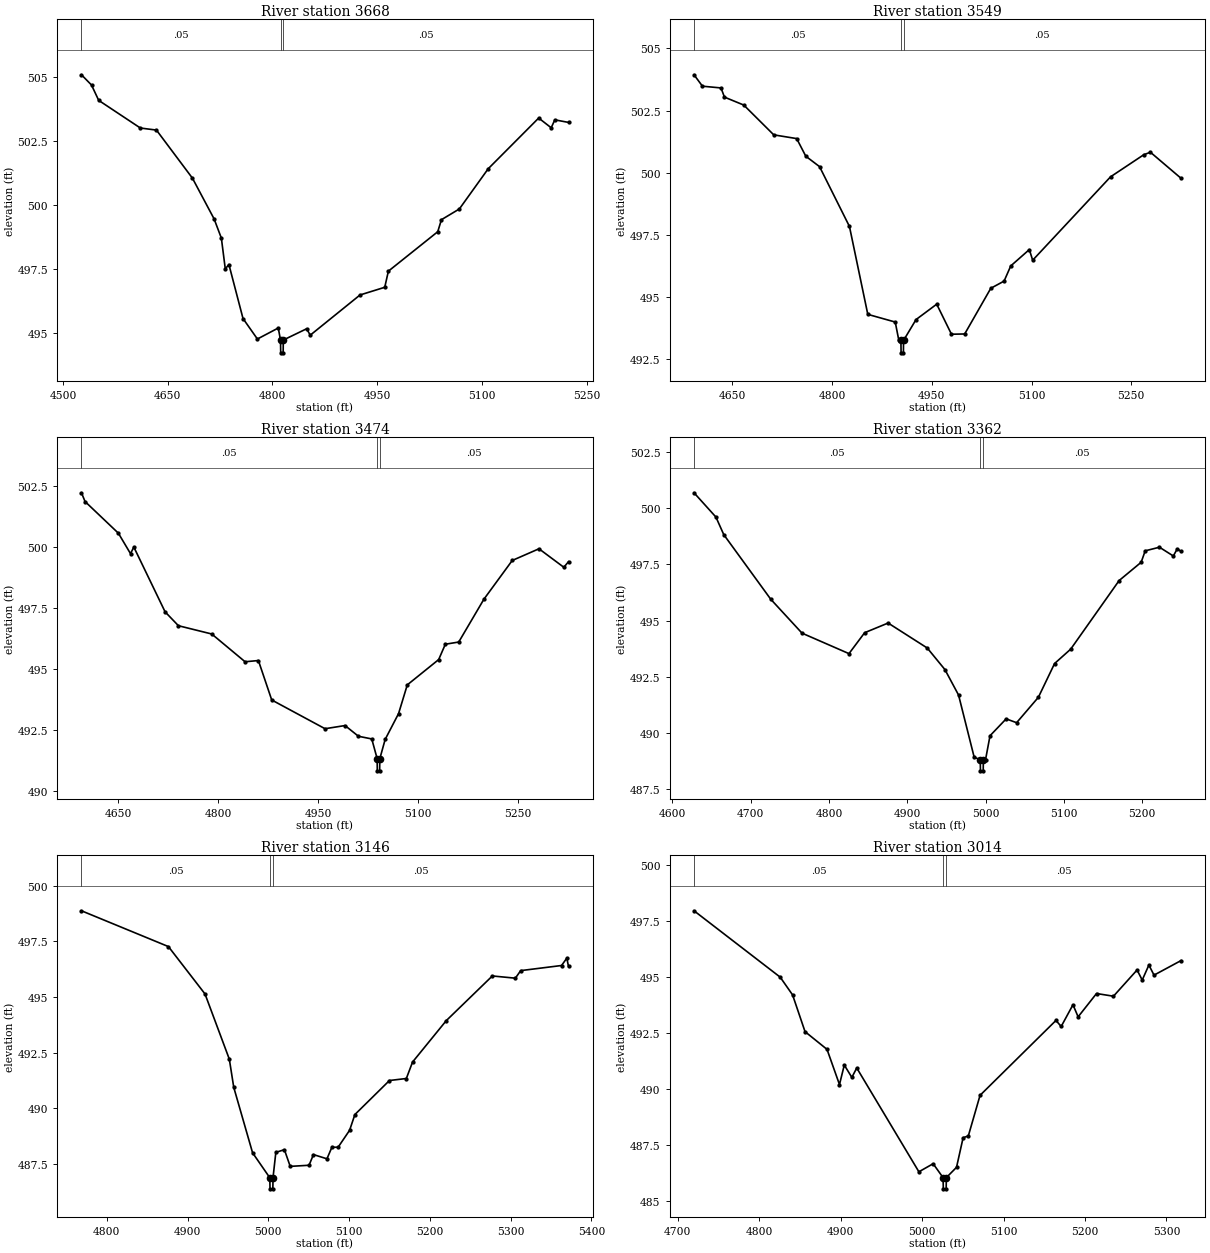
Type RM Length L Ch R = 1,3668,119,119,119
BEGIN DESCRIPTION:
Lacy 009 3319
END DESCRIPTION:
XS GIS Cut Line= 3
      2762632.92      6876147.08      2762542.16      6876496.43
      2762626.61      6876822.32
#Sta/Elev= 30
  4526.4  505.10  4540.8  504.70  4551.1  504.10  4610.8  503.02  4633.8  502.94
  4685.4  501.06  4716.4  499.47  4726.8  498.72  4732.4  497.52  4737.6  497.69
  4757.8  495.58  4778.4  494.78  4808.3  495.21  4811.5  494.74  4811.8  494.24
  4815.3  494.24  4815.5  494.74  4848.9  495.18  4854.1  494.93  4925.4  496.50
  4960.8  496.80  4966.0  497.43  5036.7  498.97  5042.0  499.44  5067.7  499.86
  5109.0  501.43  5181.3  503.41  5199.2  503.03  5204.4  503.34  5224.0  503.24
#Mann=3,-1,0
  4526.4    0.05       0  4811.5    0.04       0  4815.5    0.05       0
Bank Sta=4811.5,4815.5
Exp/Cntr=0.3,0.1

Type RM Length L Ch R = 1,3549,75,75,75
BEGIN DESCRIPTION:
Lacy 009 3318
END DESCRIPTION:
XS GIS Cut Line= 3
      2762592.27      6876128.77      2762485.88      6876517.56
      2762470.48      6876847.02
#Sta/Elev= 30
  4592.1  503.94  4604.8  503.48  4632.7  503.41  4637.9  503.04  4667.0  502.72
  4712.1  501.52  4746.6  501.37  4760.3  500.66  4781.0  500.24  4826.0  497.83
  4853.6  494.29  4894.9  493.98  4900.1  493.27  4903.4  493.24  4903.7  492.74
  4907.2  492.74  4907.4  493.24  4926.2  494.08  4957.3  494.70  4979.5  493.49
  4999.4  493.50  5038.7  495.34  5058.7  495.63  5068.7  496.24  5096.7  496.90
  5101.7  496.47  5218.9  499.83  5268.9  500.72  5278.9  500.82  5325.0  499.77
#Mann=3,-1,0
  4592.1    0.05       0  4903.4    0.04       0  4907.4    0.05       0
Bank Sta=4903.4,4907.4
Exp/Cntr=0.3,0.1

Type RM Length L Ch R = 1,3474,112,112,112
BEGIN DESCRIPTION:
Lacy 009 3316
END DESCRIPTION:
XS GIS Cut Line= 3
      2762422.60      6876105.57      2762414.14      6876510.61
      2762441.40      6876835.14
#Sta/Elev= 30
  4594.7  502.24  4600.1  501.88  4650.1  500.58  4668.3  499.74  4673.3  500.01
  4720.2  497.35  4740.2  496.78  4790.2  496.44  4840.2  495.30  4860.2  495.35
  4880.2  493.73  4960.2  492.55  4990.2  492.68  5010.3  492.24  5030.3  492.13
  5038.4  491.32  5038.6  490.82  5042.1  490.82  5042.4  491.32  5050.4  492.11
  5070.5  493.17  5083.6  494.35  5130.7  495.39  5140.7  496.02  5160.8  496.11
  5198.6  497.87  5241.1  499.46  5281.2  499.94  5318.5  499.18  5325.5  499.41
#Mann=3,-1,0
  4594.7    0.05       0  5038.4    0.04       0  5042.4    0.05       0
Bank Sta=5038.4,5042.4
Exp/Cntr=0.3,0.1

Type RM Length L Ch R = 1,3362,216,216,216
BEGIN DESCRIPTION:
Lacy 009 3317
END DESCRIPTION:
XS GIS Cut Line= 3
      2762316.27      6876193.05      2762321.81      6876565.49
      2762382.89      6876807.72
#Sta/Elev= 30
  4627.5  500.68  4655.5  499.60  4665.5  498.82  4725.5  495.95  4765.5  494.44
  4825.5  493.53  4845.5  494.46  4875.5  494.89  4925.5  493.78  4948.1  492.82
  4965.5  491.69  4985.5  488.92  4993.2  488.82  4993.5  488.32  4997.0  488.32
  4997.2  488.82  5000.0  488.82  5005.7  489.88  5026.3  490.63  5039.7  490.46
  5067.5  491.59  5088.2  493.09  5108.8  493.73  5170.7  496.78  5198.8  497.59
  5204.0  498.10  5222.2  498.26  5239.9  497.87  5245.0  498.19  5249.8  498.07
#Mann=3,-1,0
  4627.5    0.05       0  4993.2   0.035       0  4997.2    0.05       0
Bank Sta=4993.2,4997.2
Exp/Cntr=0.3,0.1

Type RM Length L Ch R = 1,3146,132,132,132
BEGIN DESCRIPTION:
Lacy 009 3315
END DESCRIPTION:
XS GIS Cut Line= 3
      2762045.95      6876351.05      2762167.60      6876626.78
      2762363.41      6876856.34
#Sta/Elev= 30
  4768.6  498.88  4876.3  497.27  4921.6  495.14  4951.7  492.21  4957.2  490.94
  4980.5  488.00  5001.8  486.88  5002.1  486.38  5005.6  486.38  5005.8  486.88
  5009.3  488.02  5019.9  488.14  5027.1  487.39  5050.4  487.44  5055.9  487.92
  5072.6  487.73  5078.7  488.25  5086.4  488.25  5100.6  489.01  5107.2  489.72
  5150.0  491.25  5170.9  491.34  5178.6  492.08  5220.3  493.94  5277.4  495.95
  5305.9  495.85  5312.5  496.19  5363.1  496.42  5369.6  496.75  5371.7  496.38
#Mann=3,-1,0
  4768.6    0.05       0  5001.8   0.035       0  5005.8    0.05       0
Bank Sta=5001.8,5005.8
Exp/Cntr=0.3,0.1

Type RM Length L Ch R = 1,3014,160,160,160
BEGIN DESCRIPTION:
Lacy 009 3314
END DESCRIPTION:
XS GIS Cut Line= 3
      2761954.95      6876445.69      2762104.71      6876681.40
      2762356.28      6876877.12
#Sta/Elev= 30
  4719.9  497.96  4825.7  495.00  4840.9  494.21  4856.2  492.57  4883.2  491.78
  4898.5  490.21  4904.4  491.08  4913.7  490.53  4919.7  490.95  4996.0  486.32
  5013.5  486.68  5025.7  486.06  5026.0  485.56  5029.5  485.56  5029.7  486.06
  5042.2  486.52  5050.3  487.84  5056.7  487.92  5071.1  489.73  5164.3  493.07
  5170.7  492.80  5185.2  493.77  5191.5  493.23  5214.1  494.27  5234.9  494.15
  5263.9  495.32  5270.2  494.87  5278.4  495.54  5284.7  495.09  5317.9  495.74
#Mann=3,-1,0
  4719.9    0.05       0  5025.7    0.04       0  5029.7    0.05       0
Bank Sta=5025.7,5029.7
Exp/Cntr=0.3,0.1

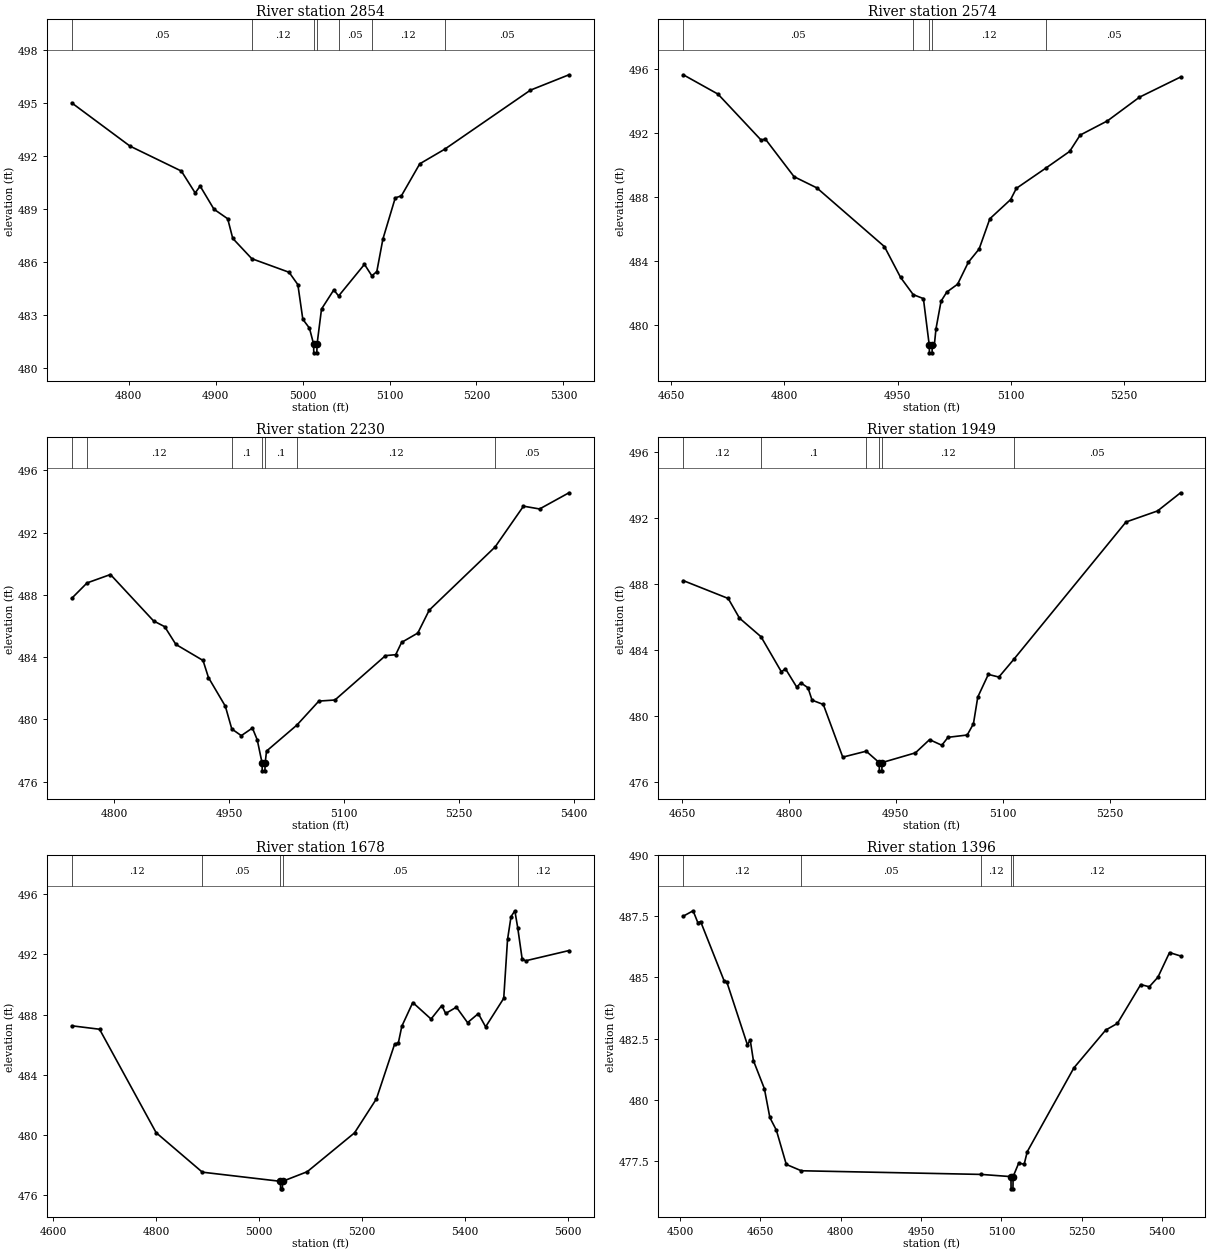
Type RM Length L Ch R = 1,2854,280,280,280
BEGIN DESCRIPTION:
Lacy 009 3312
END DESCRIPTION:
XS GIS Cut Line= 3
      2761859.58      6876564.58      2761991.83      6876796.39
      2762206.64      6877012.94
#Sta/Elev= 30
  4734.5  495.01  4801.6  492.56  4860.6  491.15  4876.5  489.91  4882.2  490.30
  4898.1  488.99  4913.9  488.45  4919.7  487.34  4941.6  486.19  4984.5  485.42
  4994.6  484.72  5000.3  482.76  5007.9  482.26  5012.7  481.36  5012.9  480.86
  5016.4  480.86  5016.7  481.36  5021.8  483.34  5035.9  484.42  5041.5  484.08
  5071.2  485.87  5079.7  485.22  5085.4  485.46  5092.4  487.30  5106.6  489.63
  5113.7  489.75  5134.8  491.56  5163.6  492.39  5262.1  495.73  5306.4  496.60
#Mann=7,-1,0
  4734.5    0.05       0  4941.6    0.12       0  5012.7    0.07       0
  5016.7    0.12       0  5041.5    0.05       0  5079.7    0.12       0
  5163.6    0.05       0
Bank Sta=5012.7,5016.7
Exp/Cntr=0.3,0.1

Type RM Length L Ch R = 1,2574,344,344,344
BEGIN DESCRIPTION:
Lacy 009 3313
END DESCRIPTION:
XS GIS Cut Line= 3
      2761728.21      6876535.38      2761768.55      6876865.39
      2761981.79      6877112.15
#Sta/Elev= 30
  4666.1  495.66  4712.1  494.45  4769.5  491.56  4774.5  491.66  4812.8  489.29
  4843.0  488.59  4932.5  484.92  4953.8  483.00  4970.6  481.92  4984.1  481.67
  4991.8  478.78  4992.1  478.28  4995.6  478.28  4995.8  478.78  4998.6  478.78
  5000.8  479.79  5007.5  481.51  5015.1  482.08  5029.4  482.57  5043.6  483.94
  5057.9  484.77  5072.1  486.66  5099.6  487.86  5107.2  488.56  5147.0  489.85
  5177.8  490.87  5191.7  491.89  5227.9  492.78  5270.3  494.26  5324.7  495.52
#Mann=5,-1,0
  4666.1    0.05       0  4970.6    0.12       0  4991.8    0.07       0
  4995.8    0.12       0  5147.0    0.05       0
Bank Sta=4991.8,4995.8
Exp/Cntr=0.3,0.1

Type RM Length L Ch R = 1,2230,281,281,281
BEGIN DESCRIPTION:
Lacy 009 3311
END DESCRIPTION:
XS GIS Cut Line= 3
      2761313.92      6876913.14      2761517.07      6877067.05
      2761843.24      6877287.06
#Sta/Elev= 30
  4744.9  487.78  4764.9  488.77  4795.4  489.31  4851.6  486.33  4866.1  485.96
  4880.7  484.82  4916.1  483.79  4923.2  482.69  4945.2  480.85  4953.6  479.39
  4966.0  478.96  4980.5  479.45  4986.8  478.69  4993.1  477.20  4993.3  476.70
  4996.8  476.70  4997.1  477.20  4998.9  477.97  5038.5  479.64  5067.1  481.18
  5088.1  481.25  5154.0  484.10  5167.3  484.16  5175.0  484.95  5196.1  485.55
  5211.0  487.02  5296.9  491.08  5333.9  493.70  5354.9  493.52  5393.2  494.56
#Mann=7,-1,0
  4744.9    0.05       0  4764.9    0.12       0  4953.6     0.1       0
  4993.1    0.07       0  4997.1     0.1       0  5038.5    0.12       0
  5296.9    0.05       0
Bank Sta=4993.1,4997.1
Exp/Cntr=0.3,0.1

Type RM Length L Ch R = 1,1949,271,271,271
BEGIN DESCRIPTION:
Lacy 009 3310
END DESCRIPTION:
XS GIS Cut Line= 3
      2761270.80      6876989.18      2761445.00      6877290.85
      2761646.97      6877576.14
#Sta/Elev= 30
  4651.8  488.22  4714.8  487.14  4730.6  485.95  4760.9  484.82  4789.4  482.70
  4795.2  482.88  4811.0  481.77  4816.8  482.03  4826.8  481.73  4832.5  480.98
  4848.3  480.72  4875.6  477.53  4908.5  477.89  4926.7  477.20  4927.0  476.70
  4930.5  476.70  4930.7  477.20  4977.6  477.79  4997.4  478.59  5014.6  478.25
  5023.3  478.73  5050.3  478.87  5059.0  479.55  5065.1  481.17  5079.9  482.54
  5094.7  482.38  5115.8  483.46  5273.1  491.77  5317.4  492.44  5349.7  493.54
#Mann=6,-1,0
  4651.8    0.12       0  4760.9     0.1       0  4908.5    0.12       0
  4926.7    0.07       0  4930.7    0.12       0  5115.8    0.05       0
Bank Sta=4926.7,4930.7
Exp/Cntr=0.3,0.1

Type RM Length L Ch R = 1,1678,282,282,282
BEGIN DESCRIPTION:
Lacy 009 3309
END DESCRIPTION:
XS GIS Cut Line= 3
      2761184.56      6876996.95      2761196.90      6877392.15
      2761579.22      6877816.55
#Sta/Elev= 30
  4635.8  487.25  4689.9  487.02  4799.9  480.13  4889.7  477.50  5041.6  476.89
  5041.8  476.39  5045.3  476.39  5045.6  476.89  5093.6  477.53  5185.6  480.12
  5228.2  482.39  5263.3  486.01  5270.8  486.12  5277.5  487.22  5298.8  488.80
  5334.3  487.70  5355.2  488.60  5362.7  488.07  5383.6  488.49  5405.3  487.46
  5426.2  488.06  5440.4  487.18  5475.6  489.08  5483.0  493.00  5489.8  494.52
  5497.2  494.91  5502.8  493.78  5511.4  491.70  5518.2  491.58  5602.4  492.26
#Mann=5,-1,0
  4635.8    0.12       0  4889.7    0.05       0  5041.6    0.03       0
  5045.6    0.05       0  5502.8    0.12       0
Bank Sta=5041.6,5045.6
Exp/Cntr=0.3,0.1

Type RM Length L Ch R = 1,1396,205,205,205
BEGIN DESCRIPTION:
Lacy 009 3308
END DESCRIPTION:
XS GIS Cut Line= 3
      2761167.67      6877013.17      2761060.45      6877500.26
      2760852.36      6877876.38
#Sta/Elev= 30
  4505.9  487.51  4524.2  487.73  4533.1  487.24  4538.2  487.29  4582.0  484.87
  4587.1  484.82  4625.7  482.24  4630.8  482.45  4636.8  481.60  4657.3  480.45
  4667.5  479.27  4679.7  478.75  4698.2  477.35  4726.2  477.09  5062.4  476.94
  5117.8  476.85  5118.0  476.35  5121.5  476.35  5121.8  476.85  5132.2  477.40
  5142.5  477.36  5148.2  477.87  5235.3  481.30  5294.8  482.85  5316.6  483.12
  5360.1  484.71  5376.1  484.62  5392.2  485.01  5413.9  486.02  5434.5  485.88
#Mann=5,-1,0
  4505.9    0.12       0  4726.2    0.05       0  5062.4    0.12       0
  5117.8    0.03       0  5121.8    0.12       0
Bank Sta=5117.8,5121.8
Exp/Cntr=0.3,0.1