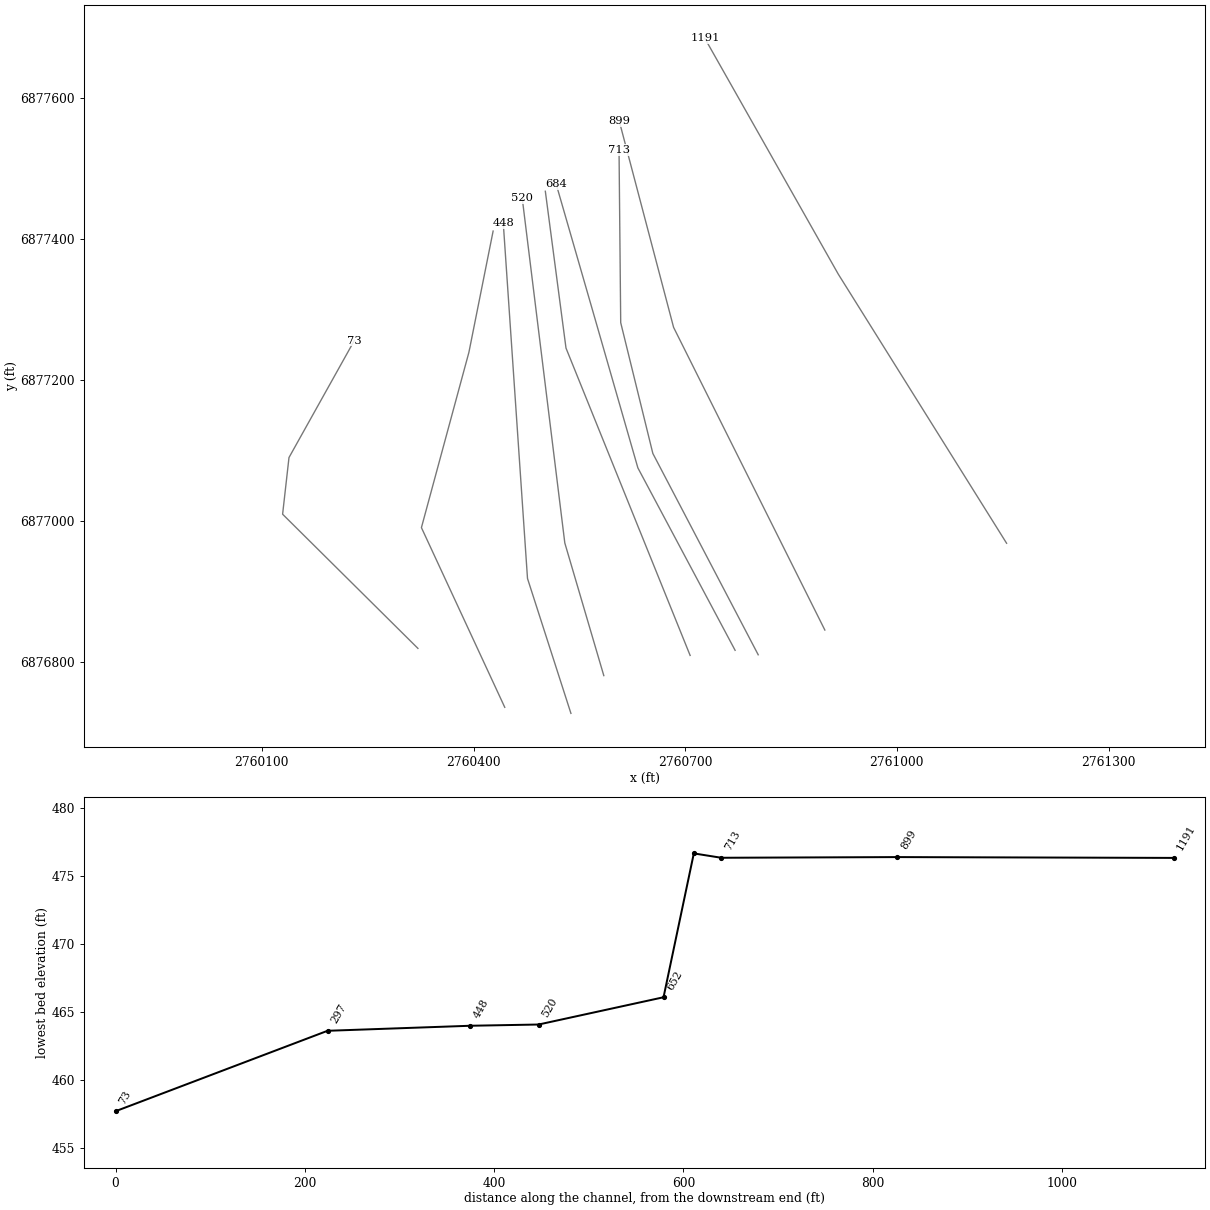
HEC-RAS study Lacy 009.prj: Lacy 009 Base Level Engineering

--- Lacy 009.g01 (geometry) --- (continued)

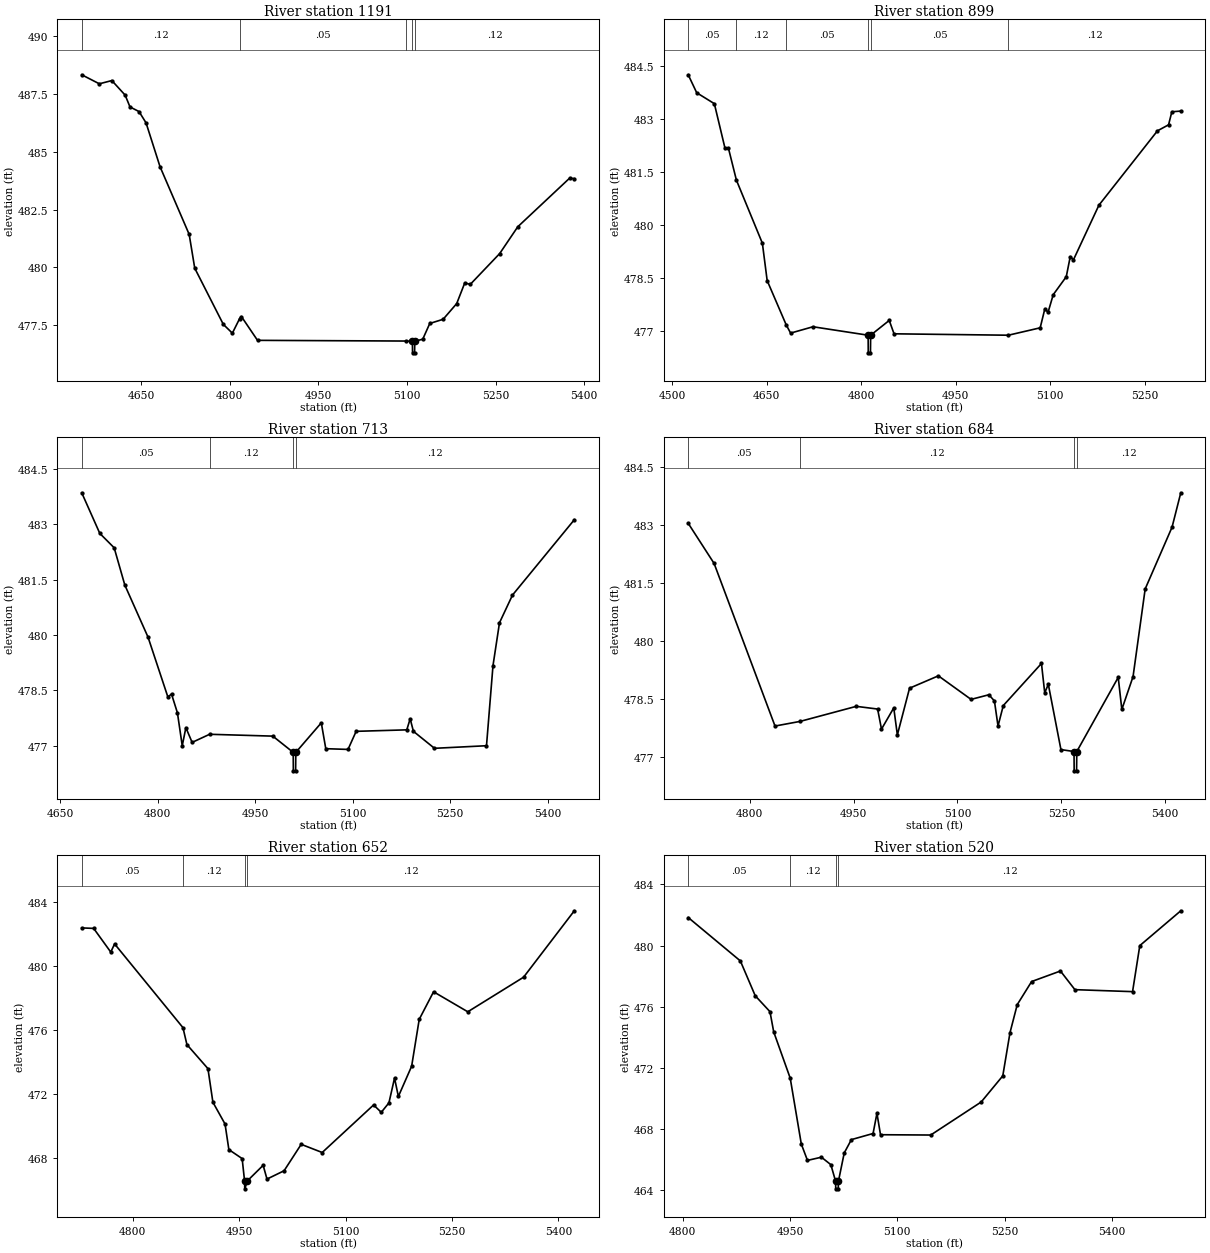
Type RM Length L Ch R = 1,1191,292,292,292
BEGIN DESCRIPTION:
Lacy 009 3307
END DESCRIPTION:
XS GIS Cut Line= 3
      2761155.52      6876968.66      2760916.94      6877350.11
      2760727.82      6877684.30
#Sta/Elev= 30
  4549.4  488.33  4579.2  487.94  4600.4  488.08  4622.9  487.45  4631.1  486.94
  4646.4  486.74  4658.3  486.25  4681.9  484.36  4731.3  481.43  4740.7  479.97
  4789.1  477.54  4804.4  477.16  4816.5  477.78  4819.7  477.88  4847.0  476.85
  5098.2  476.82  5109.2  476.81  5109.4  476.31  5112.9  476.31  5113.2  476.81
  5126.7  476.90  5138.6  477.58  5161.2  477.76  5184.2  478.44  5197.8  479.33
  5207.2  479.27  5256.9  480.60  5287.6  481.76  5375.3  483.86  5383.3  483.84
#Mann=5,-1,0
  4549.4    0.12       0  4816.5    0.05       0  5098.2    0.12       0
  5109.2    0.03       0  5113.2    0.12       0
Bank Sta=5109.2,5113.2
Exp/Cntr=0.3,0.1

Type RM Length L Ch R = 1,899,186,186,186
BEGIN DESCRIPTION:
Lacy 009 3306
END DESCRIPTION:
XS GIS Cut Line= 3
      2760897.91      6876845.68      2760683.55      6877274.64
      2760606.60      6877566.73
#Sta/Elev= 30
  4525.7  484.26  4539.2  483.75  4567.2  483.44  4583.9  482.19  4589.5  482.18
  4602.2  481.27  4643.4  479.48  4651.0  478.42  4681.3  477.16  4688.2  476.93
  4723.7  477.11  4811.2  476.87  4811.4  476.37  4814.9  476.37  4815.2  476.87
  4844.7  477.29  4852.3  476.91  5033.7  476.87  5084.2  477.08  5091.6  477.62
  5096.7  477.52  5104.9  478.02  5125.6  478.53  5131.9  479.10  5137.0  479.01
  5177.4  480.56  5270.3  482.67  5287.9  482.84  5293.1  483.21  5307.3  483.23
#Mann=6,-1,0
  4525.7    0.05       0  4602.2    0.12       0  4681.3    0.05       0
  4811.2    0.03       0  4815.2    0.05       0  5033.7    0.12       0
Bank Sta=4811.2,4815.2
Exp/Cntr=0.3,0.1

Type RM Length L Ch R = 1,713,29,29,29
BEGIN DESCRIPTION:
Lacy 009 3305
END DESCRIPTION:
XS GIS Cut Line= 4
      2760803.48      6876810.60      2760654.14      6877095.95
      2760608.59      6877281.34      2760606.22      6877526.06
#Sta/Elev= 30
  4683.2  483.85  4711.0  482.75  4733.1  482.36  4749.5  481.35  4785.2  479.94
  4815.7  478.32  4821.3  478.40  4830.4  477.89  4837.8  477.00  4843.4  477.49
  4853.0  477.09  4879.9  477.31  4977.1  477.26  5008.5  476.82  5008.7  476.32
  5012.2  476.32  5012.5  476.82  5051.7  477.62  5058.6  476.92  5092.8  476.90
  5105.3  477.39  5183.2  477.43  5188.4  477.73  5193.4  477.39  5225.8  476.93
  5305.8  477.00  5315.8  479.17  5325.8  480.33  5345.8  481.08  5440.9  483.12
#Mann=4,-1,0
  4683.2    0.05       0  4879.9    0.12       0  5008.5    0.07       0
  5012.5    0.12       0
Bank Sta=5008.5,5012.5
Exp/Cntr=0.3,0.1

Type RM Length L Ch R = 1,684,32,32,32
BEGIN DESCRIPTION:
Lacy 009 3303
END DESCRIPTION:
XS GIS Cut Line= 4
      2760770.73      6876816.94      2760632.92      6877075.50
      2760573.59      6877281.91      2760517.26      6877477.19
#Sta/Elev= 30
  4711.4  483.05  4748.8  482.01  4836.7  477.80  4872.9  477.92  4954.0  478.31
  4984.8  478.24  4990.4  477.72  5008.1  478.27  5013.3  477.57  5030.9  478.78
  5072.5  479.10  5119.7  478.49  5145.4  478.61  5153.4  478.45  5158.6  477.80
  5166.2  478.33  5221.3  479.42  5226.0  478.66  5231.2  478.88  5249.4  477.19
  5268.3  477.14  5268.5  476.64  5272.0  476.64  5272.3  477.14  5332.1  479.06
  5337.3  478.23  5353.5  479.08  5371.0  481.35  5409.8  482.95  5422.4  483.84
#Mann=4,-1,0
  4711.4    0.05       0  4872.9    0.12       0  5268.3    0.07       0
  5272.3    0.12       0
Bank Sta=5268.3,5272.3
Exp/Cntr=0.3,0.1

Type RM Length L Ch R = 1,652,132,132,132
BEGIN DESCRIPTION:
Lacy 009 3304
END DESCRIPTION:
XS GIS Cut Line= 3
      2760706.98      6876809.69      2760531.05      6877245.28
      2760501.76      6877467.58
#Sta/Elev= 30
  4728.3  482.39  4745.1  482.36  4769.2  480.88  4774.6  481.39  4870.9  476.16
  4876.5  475.10  4906.1  473.60  4913.1  471.50  4930.2  470.14  4935.6  468.54
  4954.3  467.98  4957.7  466.59  4958.0  466.09  4961.7  466.59  4983.9  467.56
  4989.3  466.70  5013.4  467.22  5037.5  468.87  5067.1  468.36  5139.5  471.33
  5150.3  470.87  5161.1  471.46  5169.0  473.01  5174.4  471.86  5193.1  473.75
  5203.8  476.68  5224.0  478.40  5272.2  477.15  5350.8  479.31  5422.3  483.46
#Mann=4,-1,0
  4728.3    0.05       0  4870.9    0.12       0  4957.7    0.07       0
  4961.7    0.12       0
Bank Sta=4957.7,4961.7
Exp/Cntr=0.3,0.1

Type RM Length L Ch R = 1,520,72,72,72
BEGIN DESCRIPTION:
Lacy 009 3302
END DESCRIPTION:
XS GIS Cut Line= 3
      2760584.63      6876781.07      2760529.37      6876969.04
      2760468.99      6877457.90
#Sta/Elev= 30
  4807.8  481.84  4880.7  479.00  4901.5  476.72  4922.1  475.68  4927.3  474.36
  4950.4  471.33  4965.9  467.02  4974.5  465.95  4994.0  466.16  5007.2  465.67
  5013.8  464.59  5014.0  464.09  5017.5  464.09  5017.8  464.59  5025.9  466.44
  5035.9  467.31  5066.2  467.71  5071.6  469.03  5076.6  467.63  5146.8  467.61
  5217.3  469.77  5247.5  471.48  5257.6  474.31  5267.7  476.14  5287.8  477.65
  5328.1  478.34  5348.3  477.12  5428.9  476.99  5439.0  480.00  5496.3  482.28
#Mann=4,-1,0
  4807.8    0.05       0  4950.4    0.12       0  5013.8    0.07       0
  5017.8    0.12       0
Bank Sta=5013.8,5017.8
Exp/Cntr=0.3,0.1

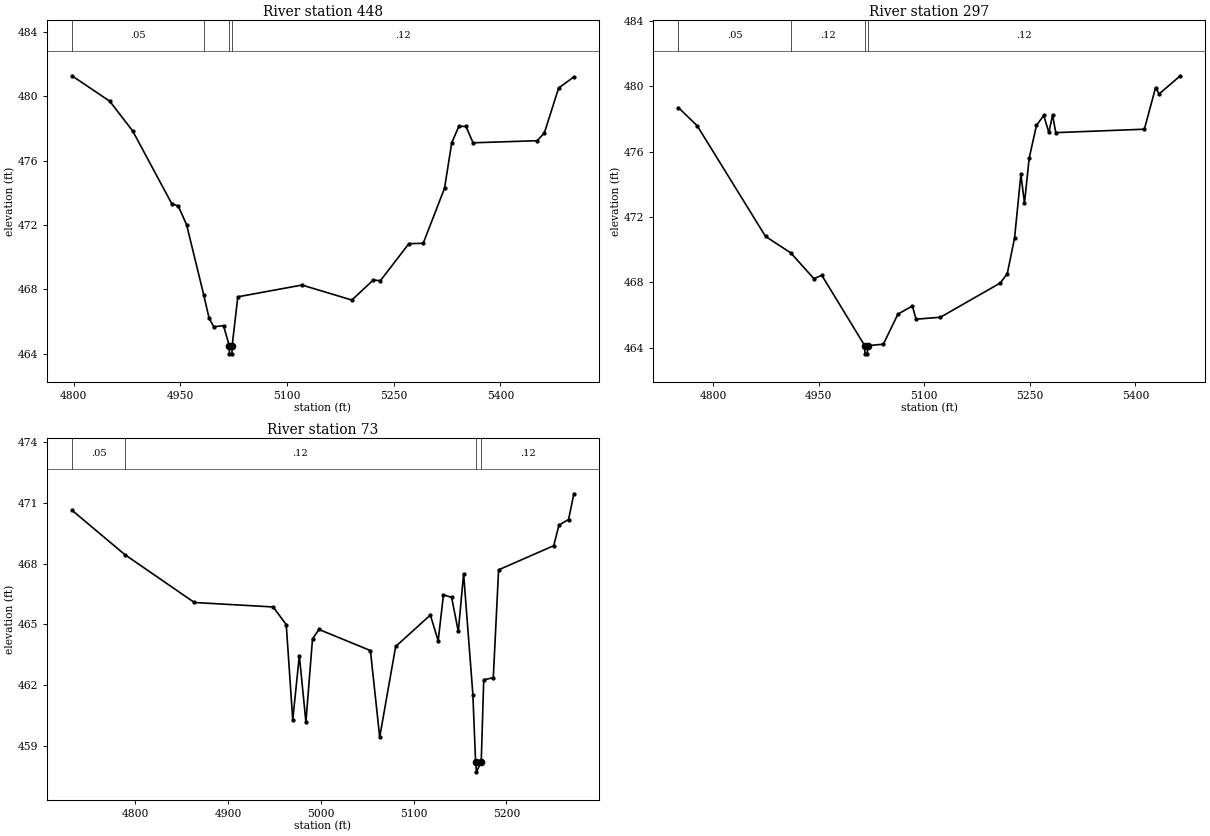
Type RM Length L Ch R = 1,448,151,151,151
BEGIN DESCRIPTION:
Lacy 009 3300
END DESCRIPTION:
XS GIS Cut Line= 3
      2760538.04      6876727.56      2760476.49      6876918.75
      2760442.16      6877422.33
#Sta/Elev= 30
  4797.7  481.26  4850.9  479.68  4883.0  477.84  4937.9  473.33  4947.2  473.17
  4958.9  472.01  4983.0  467.65  4990.4  466.23  4997.1  465.68  5010.8  465.75
  5018.9  464.50  5019.1  464.00  5022.6  464.00  5022.9  464.50  5030.9  467.54
  5121.1  468.27  5191.2  467.34  5221.3  468.58  5231.3  468.54  5271.4  470.84
  5291.5  470.86  5321.5  474.28  5331.6  477.10  5341.6  478.12  5351.6  478.12
  5361.6  477.10  5451.8  477.23  5461.9  477.72  5481.9  480.50  5503.3  481.19
#Mann=4,-1,0
  4797.7    0.05       0  4983.0    0.12       0  5018.9    0.07       0
  5022.9    0.12       0
Bank Sta=5018.9,5022.9
Exp/Cntr=0.3,0.1

Type RM Length L Ch R = 1,297,224,224,224
BEGIN DESCRIPTION:
Lacy 009 3299
END DESCRIPTION:
XS GIS Cut Line= 4
      2760444.26      6876736.14      2760326.14      6876990.84
      2760393.44      6877239.27      2760427.76      6877411.14
#Sta/Elev= 30
  4750.4  478.70  4777.1  477.59  4874.2  470.82  4910.1  469.81  4943.0  468.23
  4954.2  468.44  5015.2  464.13  5015.5  463.63  5019.0  463.63  5019.2  464.13
  5041.7  464.22  5062.4  466.06  5083.0  466.56  5088.1  465.75  5122.8  465.87
  5207.7  467.96  5217.8  468.53  5228.2  470.72  5237.2  474.61  5242.3  472.85
  5248.9  475.59  5259.3  477.61  5269.6  478.22  5277.0  477.18  5282.2  478.25
  5286.8  477.17  5412.7  477.38  5428.6  479.92  5433.7  479.54  5463.8  480.65
#Mann=4,-1,0
  4750.4    0.05       0  4910.1    0.12       0  5015.2    0.07       0
  5019.2    0.12       0
Bank Sta=5015.2,5019.2
Exp/Cntr=0.3,0.1

Type RM Length L Ch R = 1,73,0,0,0
BEGIN DESCRIPTION:
Lacy 009 3301
END DESCRIPTION:
XS GIS Cut Line= 4
      2760321.18      6876819.67      2760129.40      6877009.84
      2760138.45      6877090.16      2760231.03      6877255.96
#Sta/Elev= 30
  4731.8  470.63  4788.8  468.44  4863.7  466.08  4948.6  465.86  4962.7  464.99
  4969.7  460.29  4976.8  463.46  4983.9  460.19  4991.0  464.29  4998.0  464.75
  5053.4  463.71  5063.4  459.44  5080.6  463.91  5118.0  465.46  5126.4  464.19
  5132.1  466.46  5140.9  466.33  5148.1  464.65  5153.8  467.50  5163.8  461.54
  5166.7  458.23  5167.7  457.73  5172.8  458.23  5175.5  462.27  5185.8  462.37
  5191.5  467.69  5250.9  468.88  5256.6  469.90  5266.9  470.17  5272.6  471.44
#Mann=4,-1,0
  4731.8    0.05       0  4788.8    0.12       0  5166.7    0.07       0
  5172.8    0.12       0
Bank Sta=5166.7,5172.8
Exp/Cntr=0.3,0.1

Chan Stop Cuts=-1