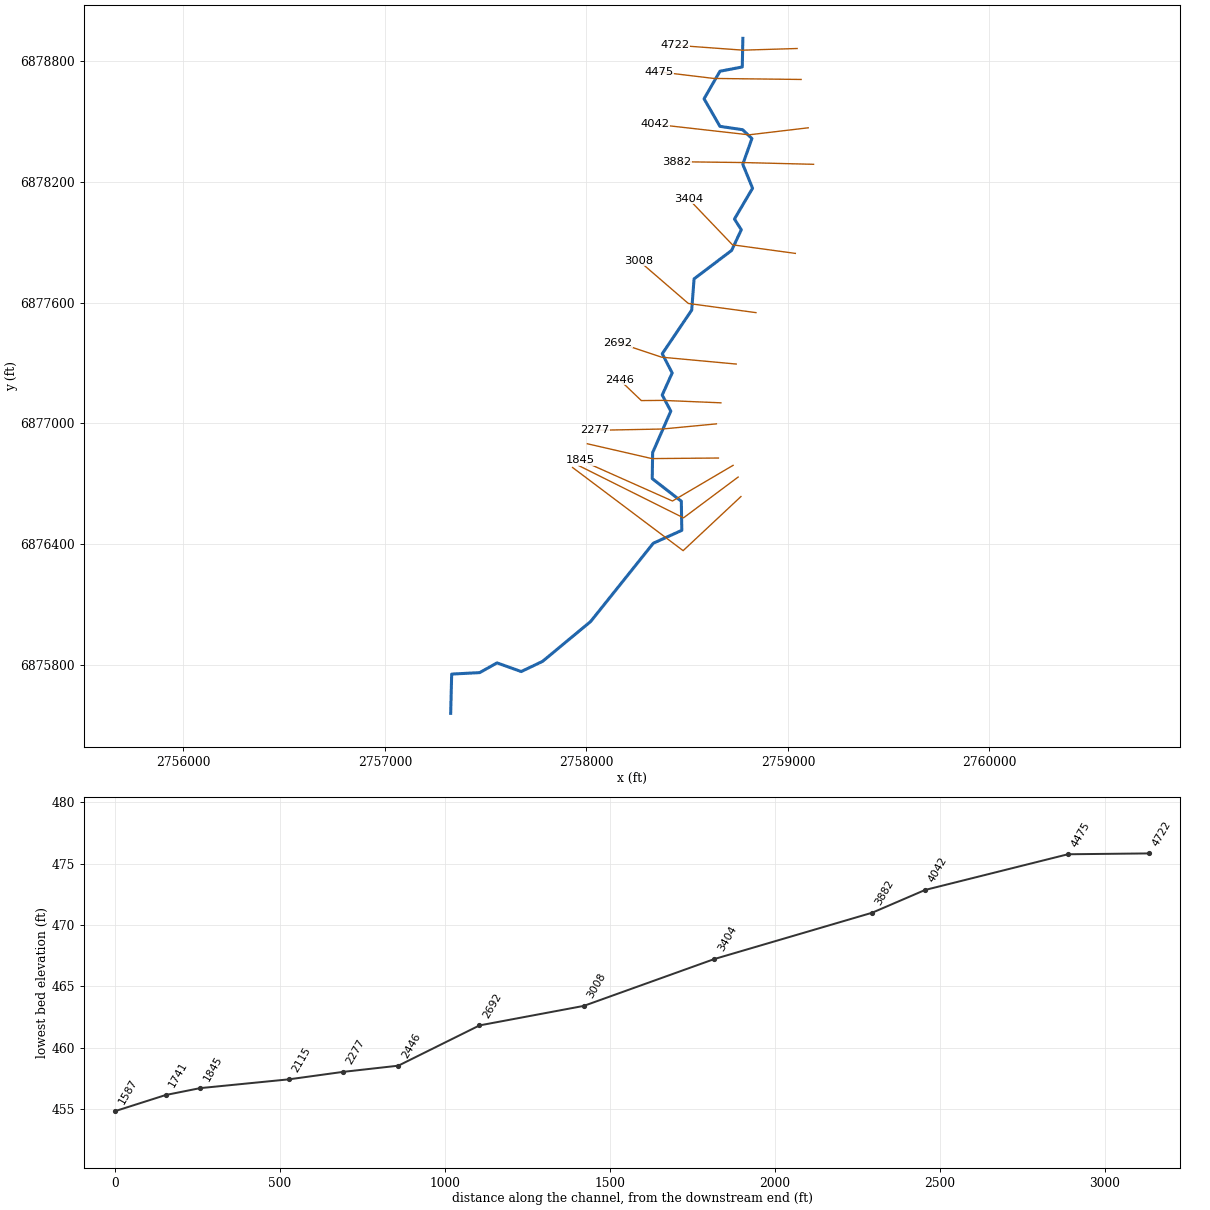
--- Lacy 012.prj (project) ---

Proj Title=Lacy 012 Base Level Engineering
Current Plan=p01
Default Exp/Contr=0.3,0.1
English Units
Geom File=g01
Flow File=f01
Plan File=p01
BEGIN DESCRIPTION:
Lacy 012
END DESCRIPTION:

--- Lacy 012.p01 (plan) ---

Plan Title=Multiple Run
Short Identifier=Multiple
Geom File=g01
Flow File=f01
Subcritical Flow
K Sum by GR= 0
Std Step Tol= 0.01
Critical Tol= 0.01
Num of Std Step Trials= 20
Max Error Tol= 0.3
Flow Tol Ratio= 0.001
Split Flow NTrial= 30
Split Flow Tol= 0.02
Split Flow Ratio= 0.02
Log Output Level= 0
Friction Slope Method= 1
Unsteady Friction Slope Method= 2
Unsteady Bridges Friction Slope Method= 1
Parabolic Critical Depth
Global Vel Dist=  1 , 1 , 1
Global Log Level= 0
CheckData=True
Encroach Param= -1, 0, 0, 0
BEGIN DESCRIPTION:
Multiple Run
END DESCRIPTION:

--- Lacy 012.f01 (steady flow) ---

Flow Title=Multiple
Number of Profiles=7
Profile Names=10-year,25-year,50-year,1pct_min,100-year,1pct_plu,500-year
River Rch & RM= Lacy 012,Reach-1,4722
     241     304     352     203     406     809     539
Boundary for River Rch & Prof#=Lacy 012,Reach-1,1
Up Type=0
Dn Type=3
Dn Slope=0.005
Boundary for River Rch & Prof#=Lacy 012,Reach-1,2
Up Type=0
Dn Type=3
Dn Slope=0.005
Boundary for River Rch & Prof#=Lacy 012,Reach-1,3
Up Type=0
Dn Type=3
Dn Slope=0.005
Boundary for River Rch & Prof#=Lacy 012,Reach-1,4
Up Type=0
Dn Type=3
Dn Slope=0.005
Boundary for River Rch & Prof#=Lacy 012,Reach-1,5
Up Type=0
Dn Type=3
Dn Slope=0.005
Boundary for River Rch & Prof#=Lacy 012,Reach-1,6
Up Type=0
Dn Type=3
Dn Slope=0.005
Boundary for River Rch & Prof#=Lacy 012,Reach-1,7
Up Type=0
Dn Type=3
Dn Slope=0.005

--- Lacy 012.g01 (geometry) ---

Geom Title=Existing Conditions

River Reach=Lacy 012,Reach-1
Reach XY= 30
      2758776.00      6878911.00      2758773.13      6878768.90
      2758662.37      6878747.73      2758583.50      6878611.00
      2758662.34      6878474.26      2758774.78      6878457.47
      2758821.03      6878413.58      2758775.62      6878286.00
      2758824.20      6878167.11      2758734.24      6878014.23
      2758768.24      6877961.08      2758720.30      6877858.46
      2758533.81      6877717.21      2758522.24      6877562.56
      2758375.96      6877345.66      2758425.21      6877250.31
      2758375.80      6877140.80      2758418.41      6877061.01
      2758328.25      6876855.06      2758326.31      6876726.04
      2758470.65      6876613.69      2758472.95      6876469.28
      2758331.61      6876405.41      2758020.38      6876016.62
      2757782.05      6875819.12      2757676.01      6875768.53
      2757555.96      6875811.58      2757470.05      6875763.28
      2757330.99      6875756.00      2757326.00      6875561.00

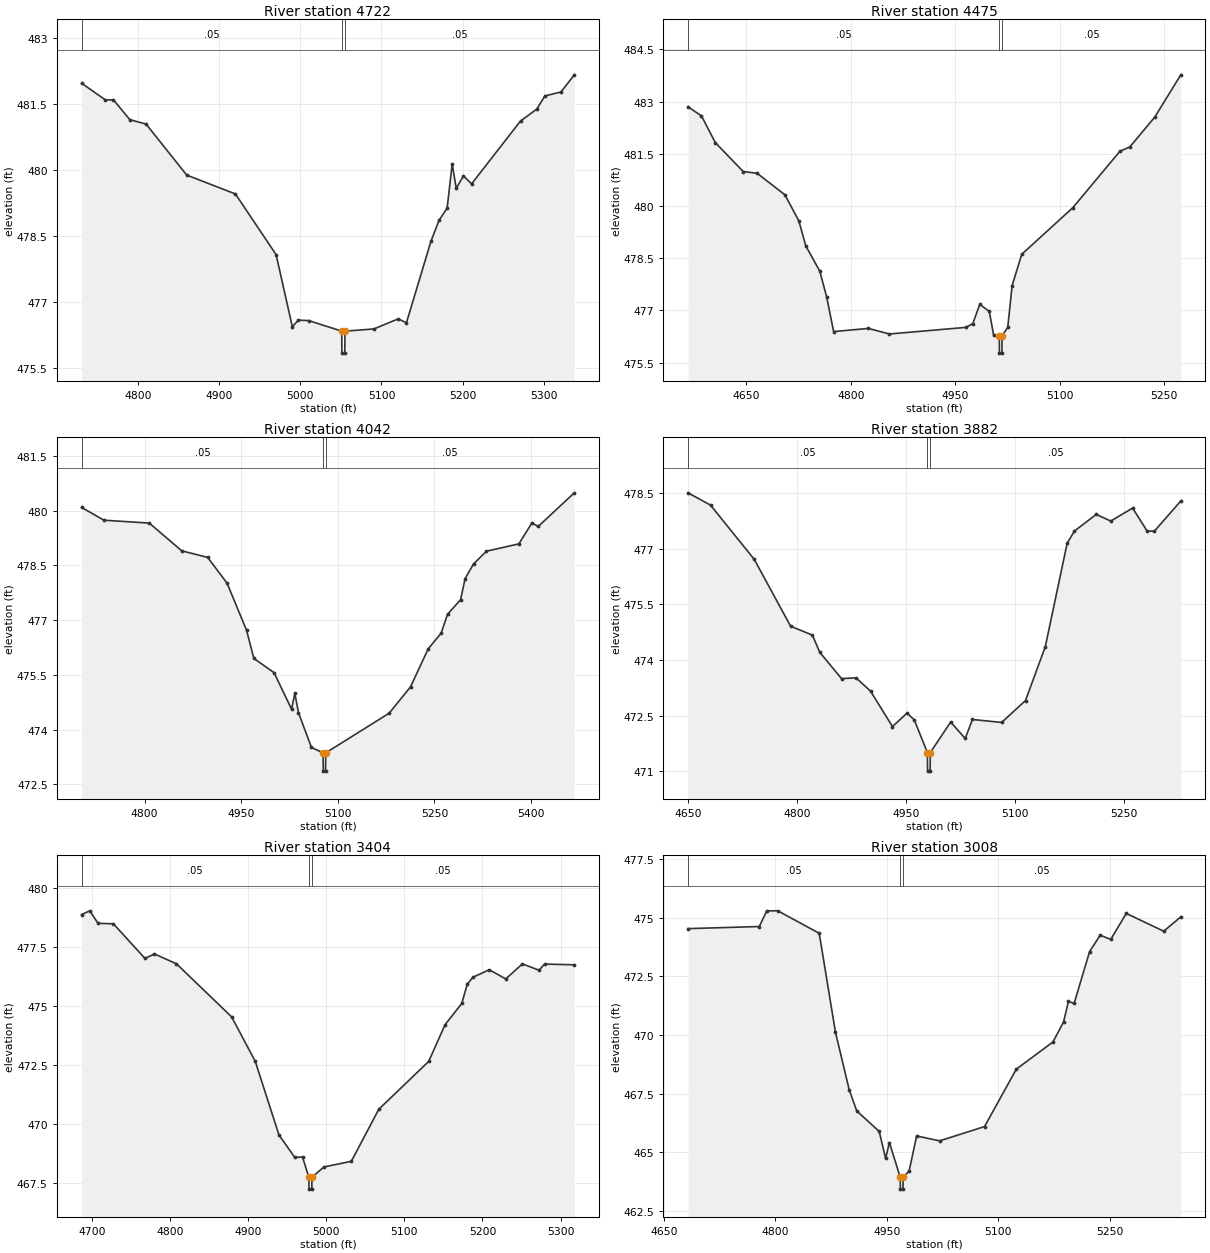
Type RM Length L Ch R = 1,4722,247,247,247
BEGIN DESCRIPTION:
Lacy 012 3294
END DESCRIPTION:
XS GIS Cut Line= 3
      2759045.32      6878860.56      2758776.35      6878852.31
      2758439.94      6878876.85
#Sta/Elev= 30
  4730.9  481.98  4760.2  481.60  4770.2  481.60  4790.3  481.15  4810.3  481.05
  4860.3  479.89  4920.3  479.46  4970.3  478.08  4990.3  476.44  4997.7  476.59
  5010.4  476.58  5051.1  476.34  5051.3  475.84  5054.8  475.84  5055.1  476.34
  5090.6  476.39  5120.7  476.62  5130.7  476.53  5160.8  478.38  5170.8  478.86
  5180.8  479.14  5187.0  480.14  5192.0  479.59  5200.9  479.87  5210.9  479.69
  5271.1  481.12  5291.1  481.39  5301.1  481.69  5320.9  481.78  5337.3  482.17
#Mann=3,-1,0
  4730.9    0.05       0  5051.1    0.03       0  5055.1    0.05       0
Bank Sta=5051.1,5055.1
Exp/Cntr=0.3,0.1

Type RM Length L Ch R = 1,4475,433,433,433
BEGIN DESCRIPTION:
Lacy 012 3291
END DESCRIPTION:
XS GIS Cut Line= 3
      2759065.25      6878706.91      2758632.24      6878711.93
      2758359.05      6878744.80
#Sta/Elev= 30
  4566.1  482.85  4585.4  482.59  4605.4  481.82  4645.4  480.99  4665.4  480.94
  4705.4  480.32  4725.4  479.57  4735.4  478.85  4755.4  478.13  4765.4  477.38
  4775.4  476.39  4825.4  476.48  4855.4  476.32  4965.4  476.51  4975.4  476.62
  4985.4  477.17  4999.1  476.97  5005.4  476.28  5013.5  476.27  5013.7  475.77
  5017.2  475.77  5017.5  476.27  5025.6  476.51  5031.9  477.71  5045.7  478.61
  5119.1  479.95  5186.7  481.57  5201.2  481.70  5237.1  482.56  5274.3  483.77
#Mann=3,-1,0
  4566.1    0.05       0  5013.5    0.04       0  5017.5    0.05       0
Bank Sta=5013.5,5017.5
Exp/Cntr=0.3,0.1

Type RM Length L Ch R = 1,4042,160,160,160
BEGIN DESCRIPTION:
Lacy 012 3290
END DESCRIPTION:
XS GIS Cut Line= 3
      2759100.46      6878467.05      2758806.36      6878432.16
      2758340.49      6878484.79
#Sta/Elev= 30
  4702.2  480.09  4736.9  479.74  4807.4  479.66  4857.7  478.90  4898.0  478.72
  4928.2  478.01  4958.4  476.72  4969.7  475.95  5001.1  475.56  5028.2  474.56
  5033.3  474.99  5039.0  474.46  5059.1  473.51  5077.2  473.36  5077.5  472.86
  5081.0  472.86  5081.2  473.36  5179.9  474.45  5212.9  475.17  5240.3  476.21
  5260.4  476.64  5270.4  477.16  5290.6  477.56  5297.7  478.14  5310.7  478.54
  5330.8  478.89  5381.1  479.09  5401.3  479.66  5411.3  479.57  5467.2  480.49
#Mann=3,-1,0
  4702.2    0.05       0  5077.2    0.05       0  5081.2    0.05       0
Bank Sta=5077.2,5081.2
Exp/Cntr=0.3,0.1

Type RM Length L Ch R = 1,3882,478,478,478
BEGIN DESCRIPTION:
Lacy 012 3289
END DESCRIPTION:
XS GIS Cut Line= 3
      2759126.94      6878285.85      2758775.96      6878294.60
      2758449.77      6878298.72
#Sta/Elev= 30
  4650.4  478.50  4681.3  478.17  4741.4  476.71  4791.4  474.91  4821.4  474.67
  4831.4  474.21  4861.4  473.50  4881.4  473.52  4901.4  473.16  4931.4  472.21
  4951.4  472.57  4961.4  472.39  4979.4  471.51  4979.7  471.01  4983.2  471.01
  4983.4  471.51  5011.4  472.33  5031.4  471.89  5041.4  472.40  5081.5  472.32
  5114.3  472.91  5141.5  474.36  5171.5  477.14  5181.5  477.47  5211.5  477.92
  5231.5  477.74  5261.5  478.09  5281.5  477.47  5291.5  477.47  5327.7  478.28
#Mann=3,-1,0
  4650.4    0.05       0  4979.4    0.05       0  4983.4    0.05       0
Bank Sta=4979.4,4983.4
Exp/Cntr=0.3,0.1

Type RM Length L Ch R = 1,3404,396,396,396
BEGIN DESCRIPTION:
Lacy 012 3288
END DESCRIPTION:
XS GIS Cut Line= 3
      2759036.45      6877843.76      2758724.30      6877886.37
      2758505.93      6878114.85
#Sta/Elev= 30
  4686.5  478.89  4697.0  479.05  4707.6  478.52  4727.3  478.50  4767.7  477.03
  4779.9  477.22  4808.1  476.80  4878.7  474.55  4909.0  472.66  4939.3  469.54
  4959.5  468.59  4969.5  468.60  4977.6  467.74  4977.9  467.24  4981.4  467.24
  4981.6  467.74  4996.8  468.18  5032.0  468.42  5067.2  470.63  5131.1  472.66
  5152.1  474.22  5173.5  475.12  5180.4  475.93  5187.7  476.23  5208.7  476.55
  5229.8  476.16  5251.2  476.80  5272.3  476.53  5279.5  476.79  5317.6  476.76
#Mann=3,-1,0
  4686.5    0.05       0  4977.6   0.035       0  4981.6    0.05       0
Bank Sta=4977.6,4981.6
Exp/Cntr=0.3,0.1

Type RM Length L Ch R = 1,3008,316,316,316
BEGIN DESCRIPTION:
Lacy 012 3287
END DESCRIPTION:
XS GIS Cut Line= 3
      2758841.15      6877549.78      2758505.41      6877595.27
      2758259.55      6877807.51
#Sta/Elev= 30
  4682.3  474.54  4778.3  474.63  4788.4  475.30  4803.3  475.30  4859.0  474.34
  4880.9  470.11  4899.4  467.66  4909.5  466.76  4939.8  465.88  4948.4  464.73
  4953.5  465.41  4968.1  463.92  4968.3  463.42  4971.8  463.42  4972.1  463.92
  4980.1  464.20  4990.2  465.69  5021.1  465.48  5081.6  466.09  5124.4  468.54
  5173.7  469.70  5188.0  470.55  5194.6  471.43  5202.3  471.35  5223.1  473.56
  5237.4  474.26  5251.6  474.08  5272.5  475.19  5322.9  474.43  5345.9  475.04
#Mann=3,-1,0
  4682.3    0.05       0  4968.1   0.035       0  4972.1    0.05       0
Bank Sta=4968.1,4972.1
Exp/Cntr=0.3,0.1

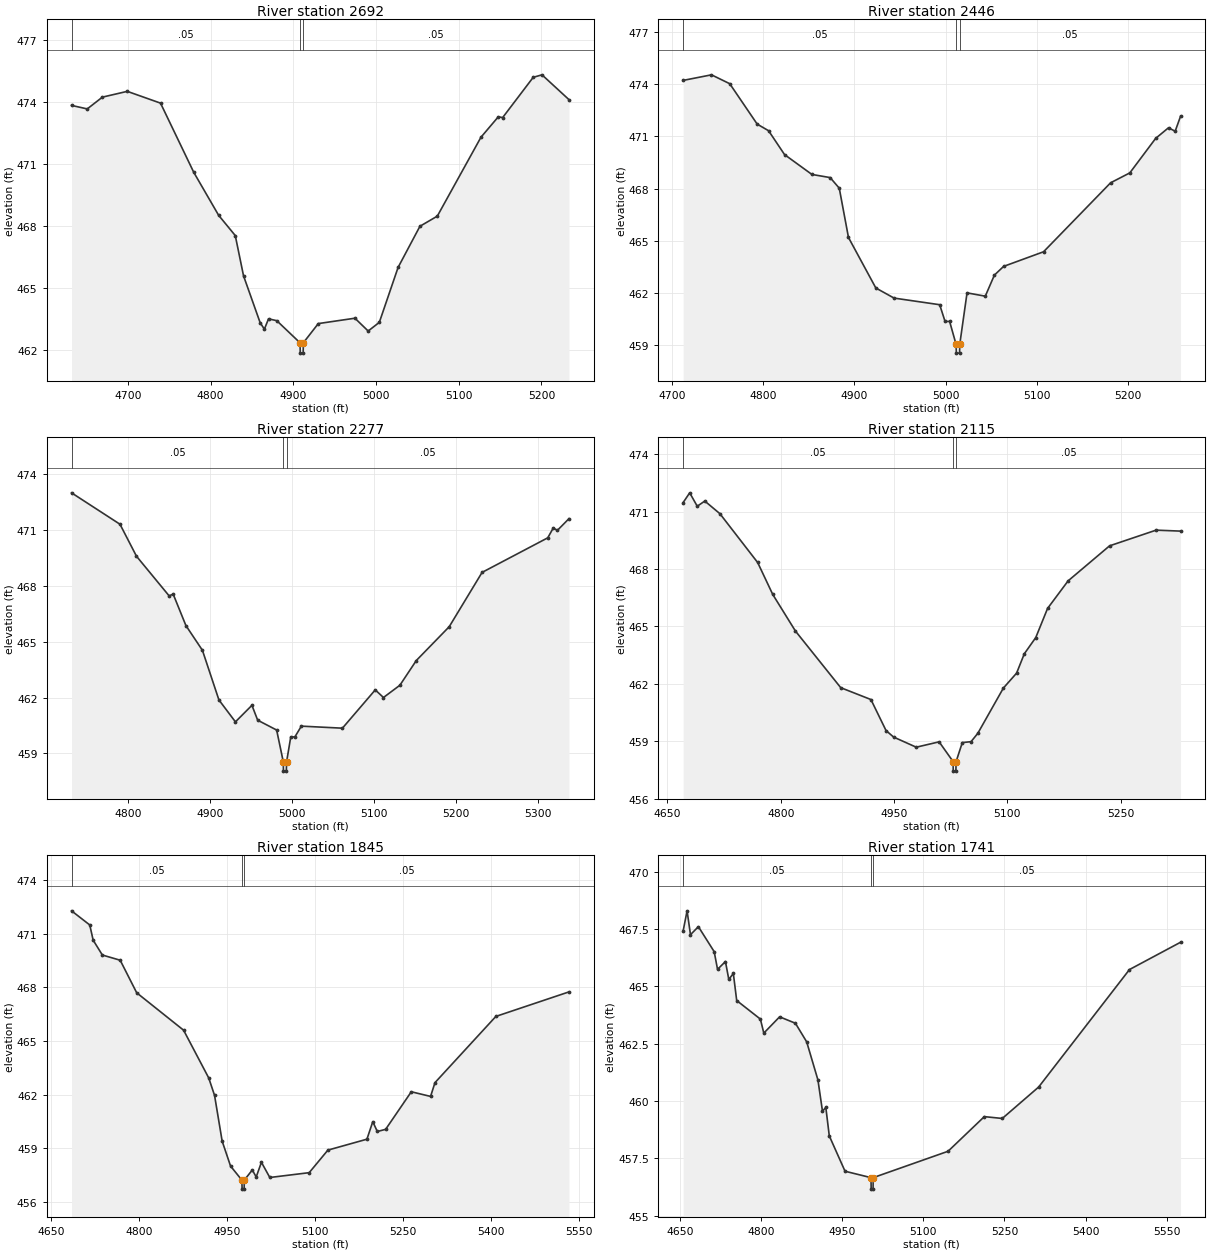
Type RM Length L Ch R = 1,2692,246,246,246
BEGIN DESCRIPTION:
Lacy 012 3286
END DESCRIPTION:
XS GIS Cut Line= 3
      2758743.16      6877294.54      2758372.51      6877328.80
      2758155.04      6877401.41
#Sta/Elev= 30
  4631.8  473.82  4650.8  473.65  4669.1  474.22  4699.2  474.50  4739.4  473.93
  4779.6  470.58  4809.7  468.50  4829.8  467.52  4839.8  465.57  4859.9  463.30
  4865.0  462.99  4870.0  463.49  4880.0  463.40  4908.1  462.33  4908.4  461.83
  4911.9  461.83  4912.1  462.33  4930.2  463.26  4974.5  463.52  4990.5  462.90
  5004.0  463.32  5026.7  465.98  5053.1  467.97  5074.1  468.46  5126.9  472.28
  5147.9  473.27  5153.1  473.23  5190.1  475.18  5200.7  475.30  5233.3  474.10
#Mann=3,-1,0
  4631.8    0.05       0  4908.1   0.035       0  4912.1    0.05       0
Bank Sta=4908.1,4912.1
Exp/Cntr=0.3,0.1

Type RM Length L Ch R = 1,2446,169,169,169
BEGIN DESCRIPTION:
Lacy 012 3284
END DESCRIPTION:
XS GIS Cut Line= 4
      2758667.10      6877102.19      2758379.21      6877114.22
      2758272.10      6877113.33      2758163.49      6877217.01
#Sta/Elev= 30
  4712.3  474.21  4743.4  474.53  4763.4  474.02  4793.5  471.70  4806.0  471.32
  4823.5  469.95  4853.5  468.81  4873.5  468.63  4883.5  468.02  4893.6  465.19
  4923.6  462.29  4943.6  461.71  4993.6  461.33  4999.5  460.37  5004.5  460.37
  5011.6  459.05  5011.9  458.55  5015.4  458.55  5015.6  459.05  5023.6  462.01
  5043.6  461.82  5053.6  463.03  5063.7  463.53  5107.5  464.37  5181.0  468.33
  5202.1  468.90  5230.4  470.88  5244.5  471.49  5251.8  471.29  5257.7  472.15
#Mann=3,-1,0
  4712.3    0.05       0  5011.6    0.04       0  5015.6    0.05       0
Bank Sta=5011.6,5015.6
Exp/Cntr=0.3,0.1

Type RM Length L Ch R = 1,2277,162,162,162
BEGIN DESCRIPTION:
Lacy 012 3285
END DESCRIPTION:
XS GIS Cut Line= 3
      2758644.70      6876997.73      2758376.81      6876972.15
      2758040.18      6876965.66
#Sta/Elev= 30
  4731.4  473.01  4790.4  471.32  4810.5  469.60  4850.2  467.47  4855.2  467.56
  4870.7  465.87  4890.8  464.54  4910.9  461.87  4931.0  460.69  4951.1  461.58
  4958.1  460.78  4981.2  460.25  4989.3  458.54  4989.5  458.04  4993.0  458.04
  4993.3  458.54  4998.4  459.88  5003.4  459.88  5011.3  460.46  5061.3  460.35
  5101.3  462.41  5111.3  462.00  5131.3  462.66  5151.3  463.99  5191.4  465.81
  5231.4  468.73  5311.4  470.59  5318.1  471.12  5323.1  470.99  5337.2  471.62
#Mann=3,-1,0
  4731.4    0.05       0  4989.3    0.04       0  4993.3    0.05       0
Bank Sta=4989.3,4993.3
Exp/Cntr=0.3,0.1

Type RM Length L Ch R = 1,2115,270,270,270
BEGIN DESCRIPTION:
Lacy 012 3282
END DESCRIPTION:
XS GIS Cut Line= 3
      2758654.72      6876828.26      2758324.62      6876825.40
      2758004.38      6876898.99
#Sta/Elev= 30
  4670.8  471.47  4679.5  471.98  4689.5  471.28  4699.5  471.55  4719.5  470.89
  4769.5  468.34  4789.5  466.67  4819.5  464.76  4879.5  461.80  4919.5  461.18
  4939.5  459.56  4949.5  459.22  4979.5  458.69  5009.8  458.97  5028.3  457.94
  5028.5  457.44  5032.0  457.44  5032.3  457.94  5040.5  458.93  5052.1  458.98
  5061.1  459.42  5094.9  461.78  5112.4  462.56  5122.6  463.57  5137.8  464.42
  5153.4  465.94  5180.6  467.38  5235.5  469.21  5297.1  470.03  5329.5  469.98
#Mann=3,-1,0
  4670.8    0.05       0  5028.3    0.04       0  5032.3    0.05       0
Bank Sta=5028.3,5032.3
Exp/Cntr=0.3,0.1

Type RM Length L Ch R = 1,1845,104,104,104
BEGIN DESCRIPTION:
Lacy 012 3283
END DESCRIPTION:
XS GIS Cut Line= 3
      2758727.54      6876791.94      2758426.61      6876614.88
      2757970.31      6876818.18
#Sta/Elev= 30
  4684.2  472.27  4715.3  471.48  4721.1  470.63  4736.8  469.80  4767.2  469.51
  4795.4  467.69  4875.4  465.60  4918.3  462.93  4928.2  461.96  4941.2  459.40
  4955.5  458.01  4974.9  457.22  4975.2  456.72  4978.7  456.72  4978.9  457.22
  4992.6  457.79  4999.3  457.40  5008.2  458.22  5022.5  457.37  5089.7  457.64
  5121.6  458.90  5188.2  459.51  5198.2  460.49  5205.9  459.94  5220.1  460.06
  5263.9  462.16  5296.8  461.90  5304.3  462.67  5408.2  466.37  5532.9  467.74
#Mann=3,-1,0
  4684.2    0.05       0  4974.9    0.04       0  4978.9    0.05       0
Bank Sta=4974.9,4978.9
Exp/Cntr=0.3,0.1

Type RM Length L Ch R = 1,1741,154,154,154
BEGIN DESCRIPTION:
Lacy 012 3293
END DESCRIPTION:
XS GIS Cut Line= 3
      2758752.46      6876733.69      2758481.48      6876531.36
      2757961.50      6876790.59
#Sta/Elev= 30
  4656.3  467.41  4663.6  468.29  4669.9  467.25  4684.5  467.60  4713.7  466.51
  4719.9  465.74  4734.5  466.08  4740.7  465.30  4749.1  465.56  4755.3  464.38
  4799.1  463.57  4805.4  462.96  4834.6  463.67  4863.8  463.39  4884.6  462.58
  4905.4  460.92  4913.8  459.56  4920.0  459.72  4926.4  458.48  4955.5  456.94
  5003.5  456.66  5003.8  456.16  5007.3  456.16  5007.5  456.66  5145.9  457.81
  5212.9  459.32  5246.1  459.24  5313.3  460.61  5481.1  465.73  5575.5  466.92
#Mann=3,-1,0
  4656.3    0.05       0  5003.5    0.04       0  5007.5    0.05       0
Bank Sta=5003.5,5007.5
Exp/Cntr=0.3,0.1

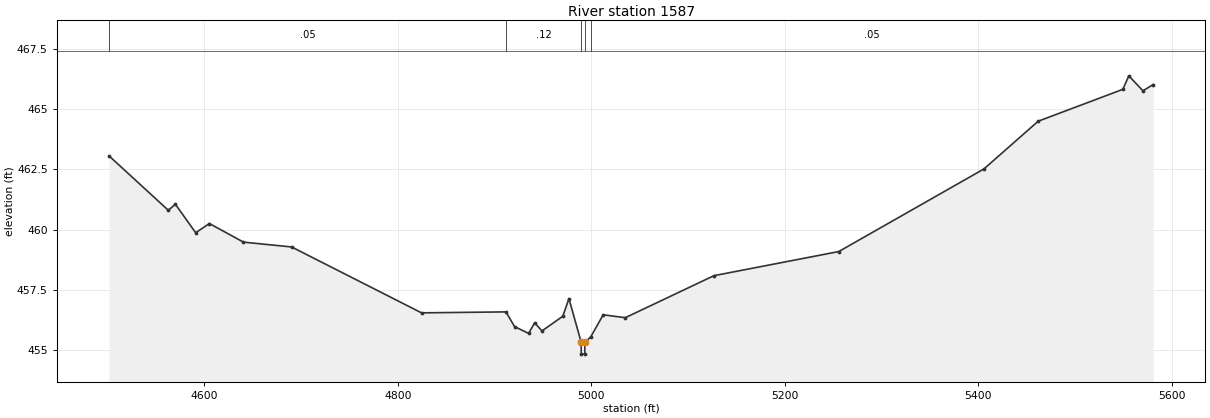
Type RM Length L Ch R = 1,1587,0,0,0
BEGIN DESCRIPTION:
Lacy 012 3292
END DESCRIPTION:
XS GIS Cut Line= 3
      2758766.54      6876637.04      2758479.58      6876368.52
      2757930.94      6876781.17
#Sta/Elev= 30
  4501.4  463.05  4562.6  460.80  4569.9  461.05  4590.9  459.87  4605.1  460.25
  4640.3  459.48  4690.1  459.28  4824.4  456.55  4911.7  456.59  4920.6  455.98
  4935.1  455.70  4941.4  456.14  4948.9  455.80  4970.5  456.41  4976.8  457.14
  4989.4  455.34  4989.6  454.84  4993.1  454.84  4993.4  455.34  4999.3  455.55
  5012.2  456.47  5035.1  456.35  5126.7  458.09  5255.8  459.09  5405.8  462.51
  5462.0  464.49  5549.5  465.81  5555.7  466.37  5570.3  465.75  5580.9  466.01
#Mann=5,-1,0
  4501.4    0.05       0  4911.7    0.12       0  4989.4    0.04       0
  4993.4    0.12       0  4999.3    0.05       0
Bank Sta=4989.4,4993.4
Exp/Cntr=0.3,0.1

Chan Stop Cuts=-1