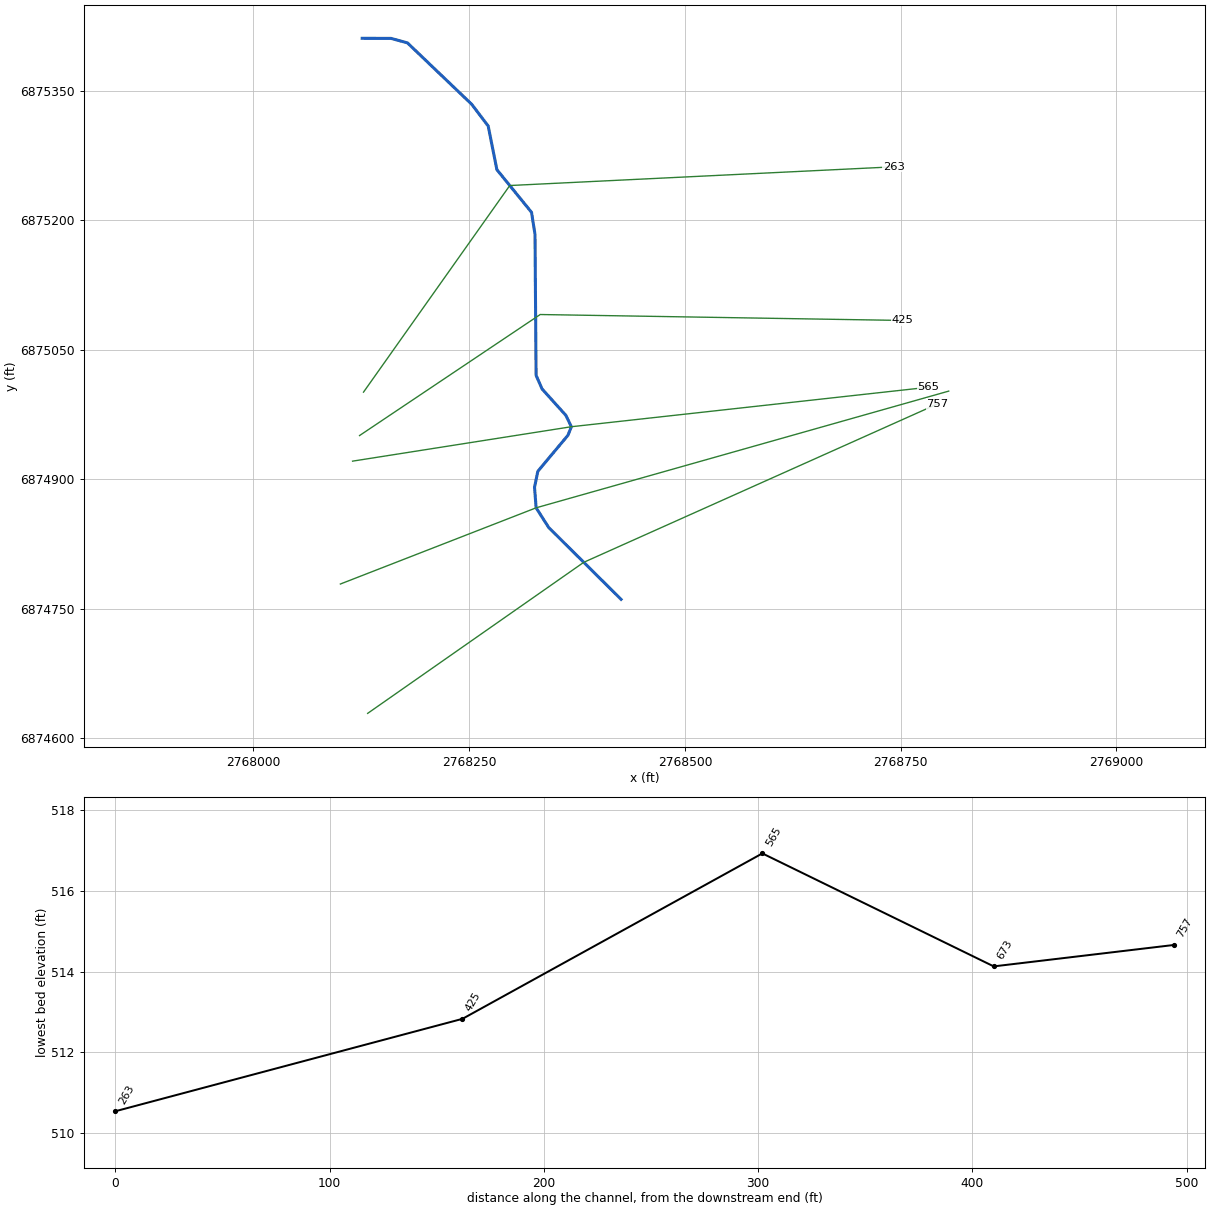
--- Lacy 014.prj (project) ---

Proj Title=Lacy 014 Base Level Engineering
Current Plan=p01
Default Exp/Contr=0.3,0.1
English Units
Geom File=g01
Flow File=f01
Plan File=p01
Y Axis Title=Elevation
X Axis Title(PF)=Main Channel Distance
X Axis Title(XS)=Station
BEGIN DESCRIPTION:
Lacy 014
END DESCRIPTION:
DSS Export Rating Curves= 0
DSS Export Rating Curve Sorted= 0
DSS Export Volume Flow Curves= 0
DXF OffsetX= 0
DXF OffsetY= 0
DXF ScaleX= 1
DXF ScaleY= 10

--- Lacy 014.p01 (plan) ---

Plan Title=Multiple Run
Short Identifier=Multiple
Geom File=g01
Flow File=f01
Subcritical Flow
K Sum by GR= 0
Std Step Tol= 0.01
Critical Tol= 0.01
Num of Std Step Trials= 20
Max Error Tol= 0.3
Flow Tol Ratio= 0.001
Split Flow NTrial= 30
Split Flow Tol= 0.02
Split Flow Ratio= 0.02
Log Output Level= 0
Friction Slope Method= 1
Unsteady Friction Slope Method= 2
Unsteady Bridges Friction Slope Method= 1
Parabolic Critical Depth
Global Vel Dist=  1 , 1 , 1
Global Log Level= 0
CheckData=True
Encroach Param= -1, 0, 0, 0
BEGIN DESCRIPTION:
Multiple Run
END DESCRIPTION:

--- Lacy 014.f01 (steady flow) ---

Flow Title=Multiple
Number of Profiles=7
Profile Names=10-year,25-year,50-year,1pct_min,100-year,1pct_plu,500-year
River Rch & RM= Lacy 014,Reach-1,757
     470     632     764     460     918    1832    1329
Boundary for River Rch & Prof#=Lacy 014,Reach-1,1
Up Type=0
Dn Type=3
Dn Slope=0.005
Boundary for River Rch & Prof#=Lacy 014,Reach-1,2
Up Type=0
Dn Type=3
Dn Slope=0.005
Boundary for River Rch & Prof#=Lacy 014,Reach-1,3
Up Type=0
Dn Type=3
Dn Slope=0.005
Boundary for River Rch & Prof#=Lacy 014,Reach-1,4
Up Type=0
Dn Type=3
Dn Slope=0.005
Boundary for River Rch & Prof#=Lacy 014,Reach-1,5
Up Type=0
Dn Type=3
Dn Slope=0.005
Boundary for River Rch & Prof#=Lacy 014,Reach-1,6
Up Type=0
Dn Type=3
Dn Slope=0.005
Boundary for River Rch & Prof#=Lacy 014,Reach-1,7
Up Type=0
Dn Type=3
Dn Slope=0.005

--- Lacy 014.g01 (geometry) ---

Geom Title=Existing Conditions
Program Version=4.10

River Reach=Lacy 014        ,Reach-1
Reach XY= 18
        2768426.        6874761.      2768342.11      6874844.29
       2768327.6      6874867.04      2768325.74      6874890.84
      2768329.57      6874909.35      2768364.47      6874951.07
      2768368.41      6874960.99      2768362.04       6874974.2
      2768334.45      6875004.81      2768327.55      6875020.59
      2768326.29      6875183.85      2768322.25      6875209.45
      2768282.14      6875258.83      2768272.07      6875309.38
      2768253.03      6875334.51      2768178.54       6875405.7
      2768159.64      6875410.93        2768126.        6875411.

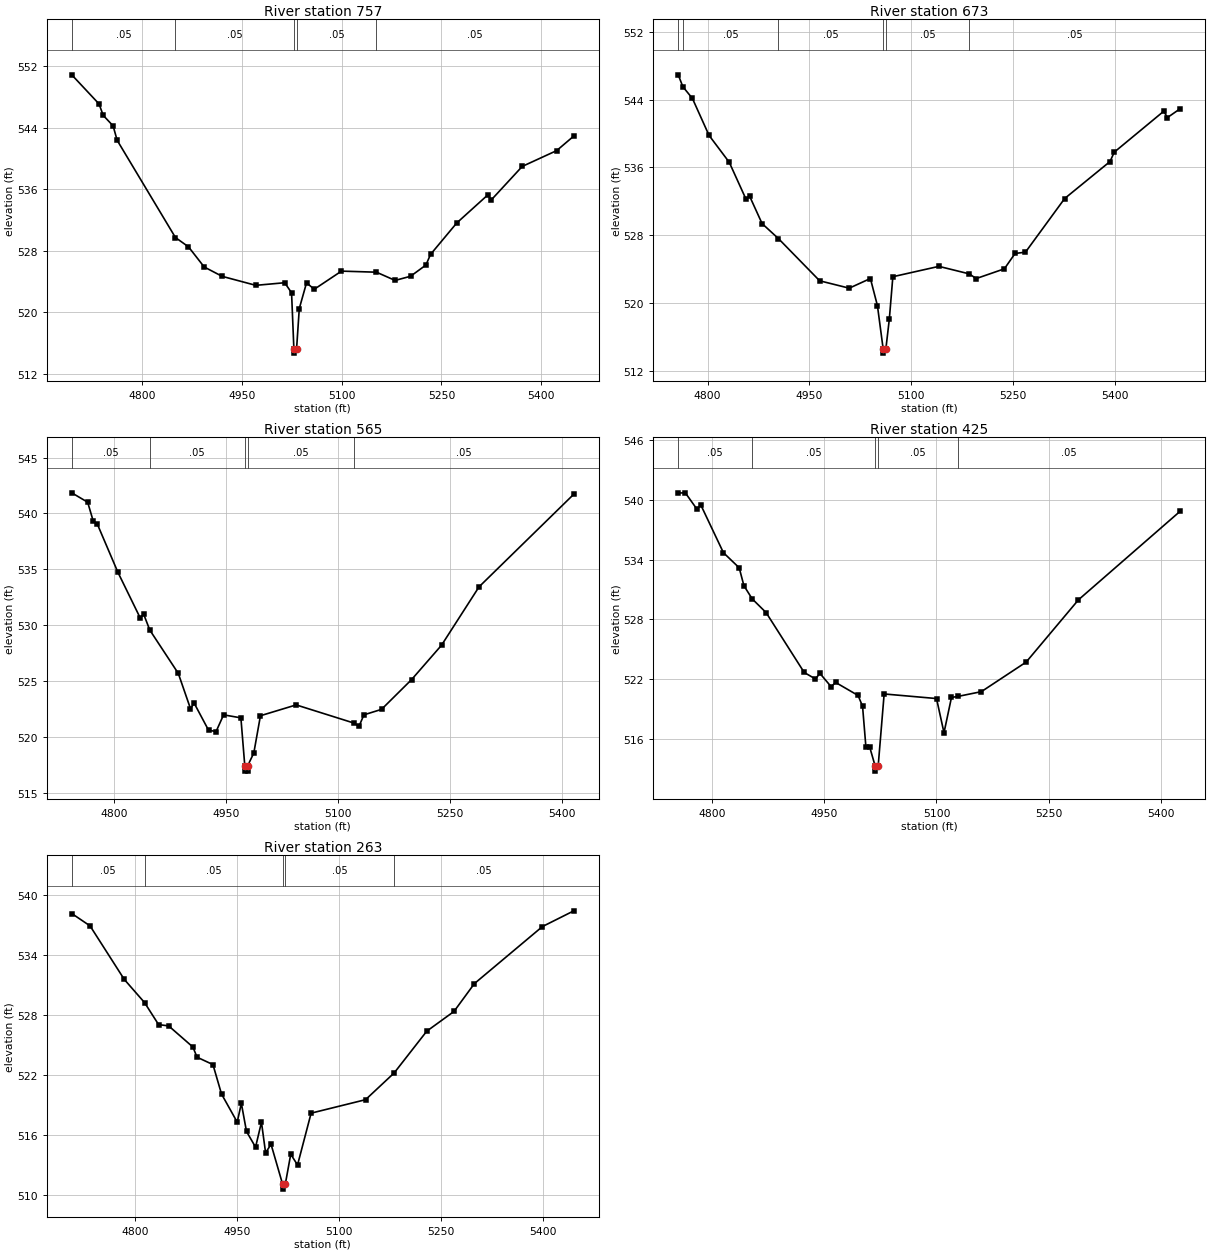
Type RM Length L Ch R = 1 ,757     ,84,84,84
BEGIN DESCRIPTION:
Lacy 014 3517
END DESCRIPTION:
XS GIS Cut Line= 3
       2768132.4      6874628.87      2768382.79       6874803.9
      2768792.59      6874987.39
#Sta/Elev= 30
  4694.5  550.87  4735.5  547.08  4741.7   545.6  4756.6  544.23  4762.7  542.35
  4850.3   529.7  4869.9  528.49  4893.5  525.87  4920.5  524.65  4971.1  523.48
  5014.5  523.82  5024.8  522.51  5028.3  515.16  5028.5  514.66  5032.3  515.16
  5036.4  520.46  5047.3  523.81  5058.9  522.97  5099.8  525.33  5152.4  525.19
  5180.4  524.12  5203.6  524.66  5226.7  526.12  5233.6   527.5  5273.1   531.6
  5319.5  535.23    5325   534.6  5371.4  538.95  5423.2  541.01    5449  542.91
#Mann= 5 ,-1 , 0
  4694.5     .05       0  4850.3     .05       0  5028.3    .005       0
  5032.3     .05       0  5152.4     .05       0
Bank Sta=5028.3,5032.3
XS Rating Curve= 0 ,0
Exp/Cntr=0.3,0.1

Type RM Length L Ch R = 1 ,673     ,108,108,108
BEGIN DESCRIPTION:
Lacy 014 3518
END DESCRIPTION:
XS GIS Cut Line= 3
      2768100.78      6874778.74       2768327.6      6874867.04
      2768805.64      6875002.26
#Sta/Elev= 30
  4756.6  546.91  4763.4  545.51  4777.5  544.13    4802  539.78  4831.8  536.61
  4856.4  532.28  4861.7  532.64  4880.2  529.39  4904.2  527.63  4965.1  522.65
  5008.7  521.78  5039.9  522.92  5050.3  519.71  5058.7  514.63  5058.9  514.13
  5062.7  514.63  5067.8  518.13    5073  523.13  5140.9  524.35  5185.9  523.46
  5195.8  522.91  5237.4  524.06  5253.2  525.87  5268.5  526.02  5326.3  532.34
  5393.2   536.7  5399.4   537.8  5472.5  542.63  5477.7  541.87  5496.8  542.93
#Mann= 6 ,-1 , 0
  4756.6     .05       0  4763.4     .05       0  4904.2     .05       0
  5058.7     .05       0  5062.7     .05       0  5185.9     .05       0
Bank Sta=5058.7,5062.7
XS Rating Curve= 0 ,0
Exp/Cntr=0.3,0.1

Type RM Length L Ch R = 1 ,565     ,140,140,140
BEGIN DESCRIPTION:
Lacy 014 3516
END DESCRIPTION:
XS GIS Cut Line= 3
      2768114.92      6874921.11      2768368.41      6874960.99
      2768782.28      6875006.77
#Sta/Elev= 30
  4743.4  541.85  4764.7  541.01  4772.3  539.29  4777.4  539.09  4805.2  534.74
  4834.9  530.68  4839.9  530.96    4848  529.56  4886.2  525.68  4902.5  522.53
  4907.5  523.01  4926.7   520.6  4936.8  520.47  4946.9  521.97  4970.1   521.7
  4975.3  517.43  4975.6  516.93  4979.1  516.93  4979.3  517.43  4987.4  518.55
  4996.3  521.89  5044.2  522.86  5121.8  521.23  5128.4  520.94    5135  521.97
  5158.6  522.46  5198.8  525.12    5239   528.2  5289.3  533.43  5416.4  541.73
#Mann= 5 ,-1 , 0
  4743.4     .05       0    4848     .05       0  4975.3     .05       0
  4979.3     .05       0  5121.8     .05       0
Bank Sta=4975.3,4979.3
XS Rating Curve= 0 ,0
Exp/Cntr=0.3,0.1

Type RM Length L Ch R = 1 ,425     ,162,162,162
BEGIN DESCRIPTION:
Lacy 014 3515
END DESCRIPTION:
XS GIS Cut Line= 3
        2768123.      6874950.76      2768332.32        6875091.
       2768752.3      6875084.12
#Sta/Elev= 30
  4754.4  540.65  4763.9  540.67  4778.9  539.09  4784.9  539.41  4814.9  534.68
    4836  533.17  4842.3  531.38  4853.4  530.06    4872  528.69    4923   522.7
    4938  522.05    4944  522.61    4959  521.28  4965.1   521.7  4995.1   520.4
  5001.1  519.32  5005.6  515.23  5010.7  515.23    5018  513.33  5018.3  512.83
    5022  513.33    5030  520.55  5100.1  520.09  5110.1  516.67  5120.1   520.2
  5129.2  520.31  5160.1  520.78  5220.1  523.74  5290.1  529.97  5426.4  538.84
#Mann= 5 ,-1 , 0
  4754.4     .05       0  4853.4     .05       0    5018     .05       0
    5022     .05       0  5129.2     .05       0
Bank Sta=5018,5022
XS Rating Curve= 0 ,0
Exp/Cntr=0.3,0.1

Type RM Length L Ch R = 1 ,263     ,0,0,0
BEGIN DESCRIPTION:
Lacy 014 3514
END DESCRIPTION:
XS GIS Cut Line= 3
       2768127.6      6875001.07      2768297.06      6875240.46
      2768742.23      6875262.16
#Sta/Elev= 30
  4706.7  538.18  4733.6  536.94    4784  531.57  4813.8  529.25  4834.5  527.04
  4849.3  526.91    4885  524.79  4891.1  523.77  4914.5  523.03  4927.1  520.08
  4950.2  517.26  4956.3  519.14  4963.9  516.32  4977.2  514.75  4985.9  517.25
    4992  514.18    5000  515.04    5017  511.04  5017.2  510.54    5021  511.04
    5029  514.04    5039  512.96    5059  518.16  5139.1  519.51  5181.2  522.19
  5229.2  526.38  5269.3  528.36  5299.3  531.15  5399.4  536.87  5445.7  538.45
#Mann= 5 ,-1 , 0
  4706.7     .05       0  4813.8     .05       0    5017     .05       0
    5021     .05       0  5181.2     .05       0
Bank Sta=5017,5021
XS Rating Curve= 0 ,0
Exp/Cntr=0.3,0.1

Chan Stop Cuts=-1
Use User Specified Reach Order=0
Composite Channel Slope=5