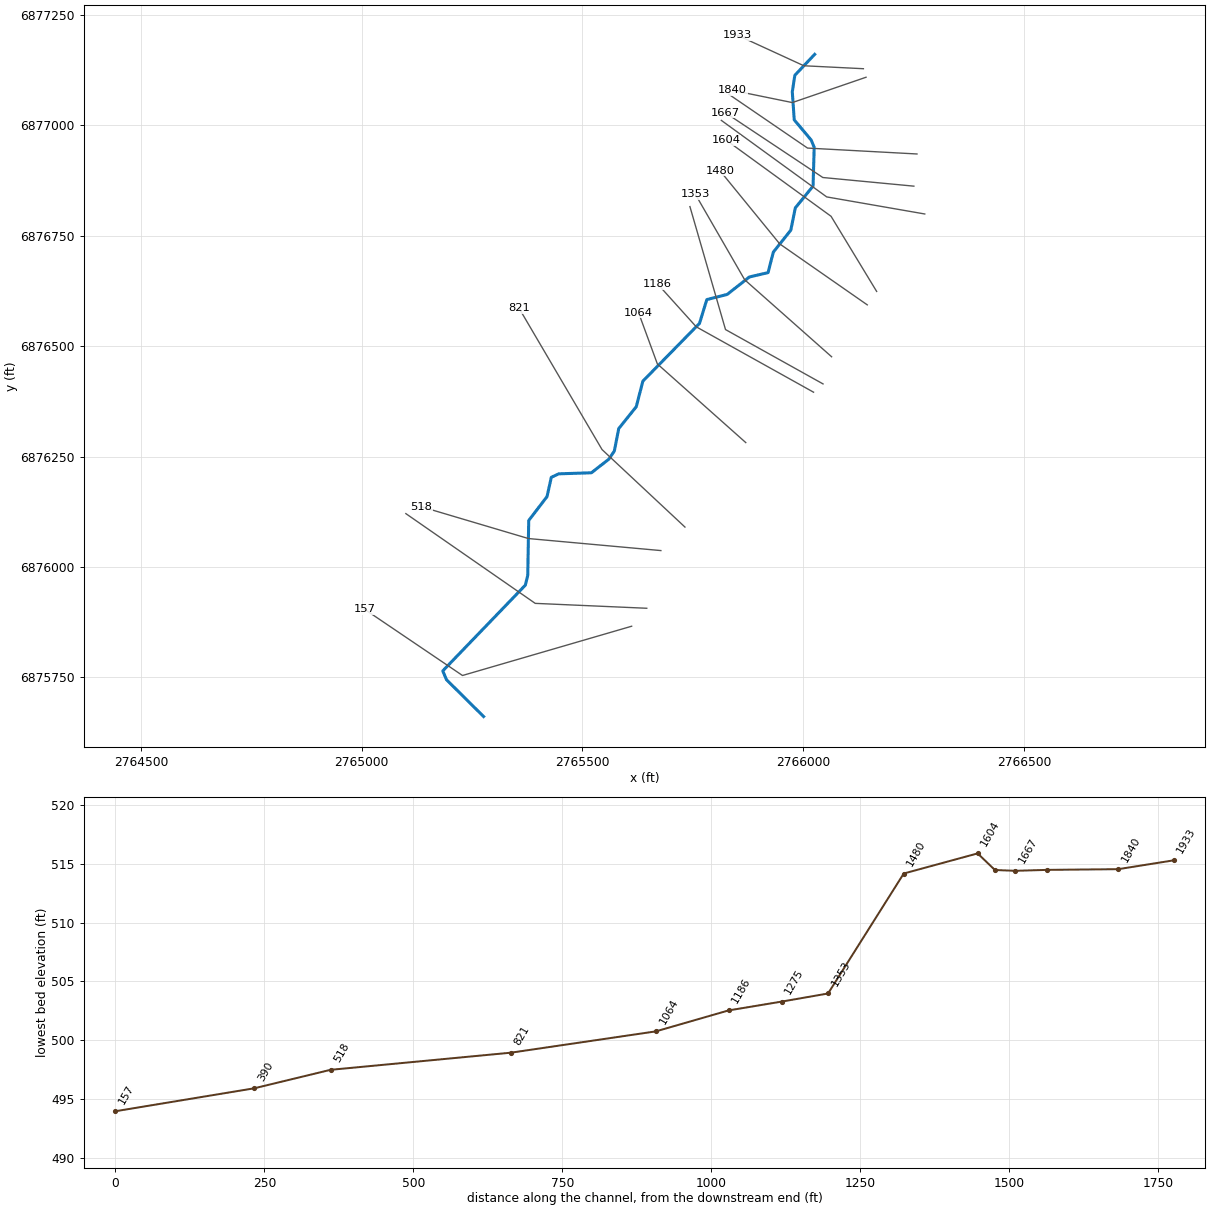
--- Lacy 015.prj (project) ---

Proj Title=Lacy 015 Base Level Engineering
Current Plan=p01
Default Exp/Contr=0.3,0.1
English Units
Geom File=g01
Flow File=f01
Plan File=p01
BEGIN DESCRIPTION:
Lacy 015
END DESCRIPTION:

--- Lacy 015.p01 (plan) ---

Plan Title=Multiple Run
Short Identifier=Multiple
Geom File=g01
Flow File=f01
Subcritical Flow
K Sum by GR= 0
Std Step Tol= 0.01
Critical Tol= 0.01
Num of Std Step Trials= 20
Max Error Tol= 0.3
Flow Tol Ratio= 0.001
Split Flow NTrial= 30
Split Flow Tol= 0.02
Split Flow Ratio= 0.02
Log Output Level= 0
Friction Slope Method= 1
Unsteady Friction Slope Method= 2
Unsteady Bridges Friction Slope Method= 1
Parabolic Critical Depth
Global Vel Dist=  1 , 1 , 1
Global Log Level= 0
CheckData=True
Encroach Param= -1, 0, 0, 0
BEGIN DESCRIPTION:
Multiple Run
END DESCRIPTION:

--- Lacy 015.f01 (steady flow) ---

Flow Title=Multiple
Number of Profiles=7
Profile Names=10-year,25-year,50-year,1pct_min,100-year,1pct_plu,500-year
River Rch & RM= Lacy 015,Reach-1,1933
     214     271     315     183     365     729     490
Boundary for River Rch & Prof#=Lacy 015,Reach-1,1
Up Type=0
Dn Type=3
Dn Slope=0.005
Boundary for River Rch & Prof#=Lacy 015,Reach-1,2
Up Type=0
Dn Type=3
Dn Slope=0.005
Boundary for River Rch & Prof#=Lacy 015,Reach-1,3
Up Type=0
Dn Type=3
Dn Slope=0.005
Boundary for River Rch & Prof#=Lacy 015,Reach-1,4
Up Type=0
Dn Type=3
Dn Slope=0.005
Boundary for River Rch & Prof#=Lacy 015,Reach-1,5
Up Type=0
Dn Type=3
Dn Slope=0.005
Boundary for River Rch & Prof#=Lacy 015,Reach-1,6
Up Type=0
Dn Type=3
Dn Slope=0.005
Boundary for River Rch & Prof#=Lacy 015,Reach-1,7
Up Type=0
Dn Type=3
Dn Slope=0.005

--- Lacy 015.g01 (geometry) ---

Geom Title=Existing Conditions

River Reach=Lacy 015,Reach-1
Reach XY= 30
      2766026.00      6877161.00      2765981.05      6877113.55
      2765975.27      6877076.04      2765979.70      6877012.59
      2766017.91      6876967.04      2766024.90      6876950.45
      2766022.33      6876862.58      2765982.12      6876813.18
      2765971.85      6876762.69      2765932.24      6876712.85
      2765920.42      6876666.58      2765878.07      6876656.67
      2765827.89      6876617.23      2765781.61      6876605.41
      2765765.11      6876551.59      2765636.77      6876420.68
      2765621.81      6876362.73      2765582.11      6876313.16
      2765572.15      6876262.39      2765559.54      6876243.87
      2765520.20      6876213.11      2765446.26      6876210.78
      2765429.38      6876202.85      2765419.70      6876159.22
      2765378.24      6876105.09      2765376.02      6875980.99
      2765370.53      6875958.55      2765183.51      6875764.33
      2765191.99      6875744.33      2765276.00      6875661.00

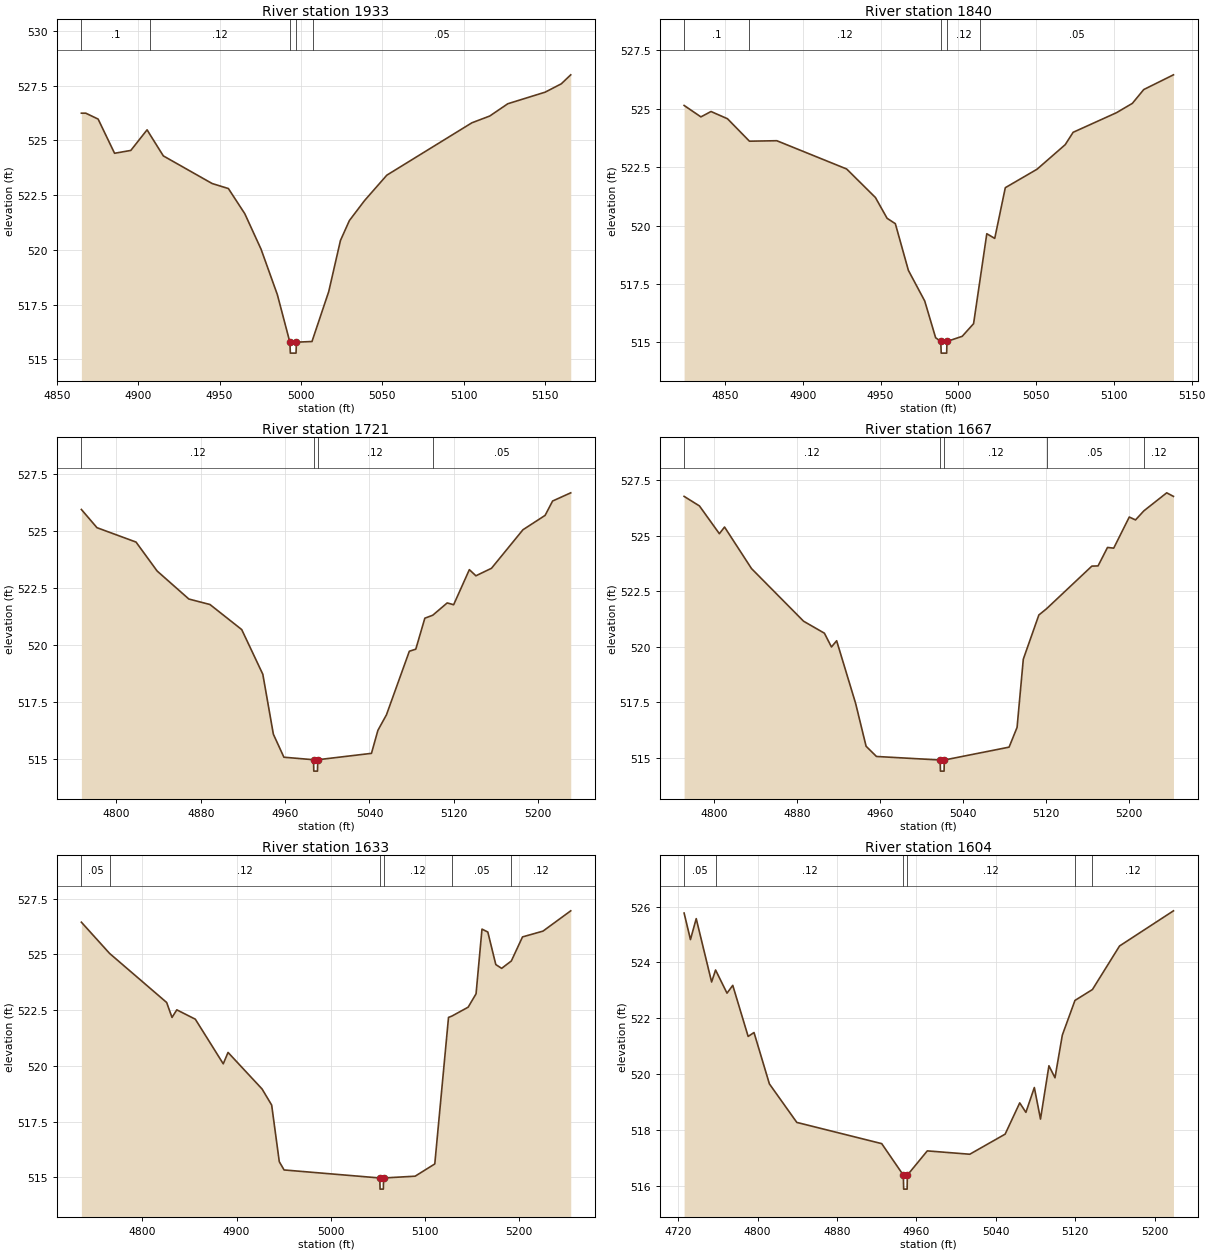
Type RM Length L Ch R = 1,1933,93,93,93
BEGIN DESCRIPTION:
Lacy 015 3503
END DESCRIPTION:
XS GIS Cut Line= 3
      2766136.33      6877128.44      2766001.50      6877135.13
      2765850.75      6877204.40
#Sta/Elev= 30
  4865.0  526.24  4867.7  526.24  4875.3  525.97  4885.4  524.41  4895.4  524.54
  4905.4  525.48  4907.3  525.25  4915.4  524.29  4945.4  523.03  4955.4  522.80
  4965.5  521.65  4975.5  520.03  4985.5  517.96  4993.2  515.79  4993.5  515.29
  4997.0  515.29  4997.2  515.79  5006.8  515.82  5007.7  516.02  5017.1  518.10
  5024.3  520.43  5029.8  521.34  5039.1  522.25  5052.8  523.41  5105.1  525.80
  5116.1  526.11  5127.2  526.67  5150.2  527.20  5160.1  527.58  5165.9  527.99
#Mann=5,-1,0
  4865.0     0.1       0  4907.3    0.12       0  4993.2    0.07       0
  4997.2    0.12       0  5007.7    0.05       0
Bank Sta=4993.2,4997.2
Exp/Cntr=0.3,0.1

Type RM Length L Ch R = 1,1840,119,119,119
BEGIN DESCRIPTION:
Lacy 015 3502
END DESCRIPTION:
XS GIS Cut Line= 3
      2766142.34      6877109.12      2765975.32      6877051.74
      2765840.12      6877079.38
#Sta/Elev= 30
  4823.7  525.14  4834.5  524.65  4841.0  524.88  4851.6  524.57  4865.7  523.61
  4883.3  523.63  4928.2  522.42  4946.7  521.20  4954.2  520.31  4959.5  520.08
  4967.9  518.08  4978.4  516.77  4985.4  515.20  4988.7  515.04  4989.0  514.54
  4992.5  514.54  4992.7  515.04  5002.5  515.26  5009.8  515.80  5013.8  517.61
  5018.3  519.65  5023.4  519.45  5030.2  521.62  5050.6  522.41  5068.7  523.46
  5073.8  523.99  5101.7  524.83  5111.9  525.23  5119.2  525.82  5138.3  526.45
#Mann=5,-1,0
  4823.7     0.1       0  4865.7    0.12       0  4988.7    0.07       0
  4992.7    0.12       0  5013.8    0.05       0
Bank Sta=4988.7,4992.7
Exp/Cntr=0.3,0.1

Type RM Length L Ch R = 1,1721,54,54,54
BEGIN DESCRIPTION:
Lacy 015 3501
END DESCRIPTION:
XS GIS Cut Line= 3
      2766257.73      6876935.30      2766009.78      6876948.68
      2765831.77      6877070.29
#Sta/Elev= 30
  4766.9  525.96  4781.7  525.16  4818.7  524.53  4838.7  523.26  4868.8  522.03
  4888.8  521.79  4918.9  520.69  4938.9  518.73  4948.9  516.10  4958.9  515.09
  4987.0  514.98  4987.2  514.48  4990.7  514.48  4991.0  514.98  5041.9  515.26
  5048.0  516.27  5056.1  516.95  5077.8  519.74  5083.9  519.83  5092.5  521.19
  5100.0  521.32  5113.7  521.86  5119.8  521.78  5134.7  523.32  5140.9  523.05
  5155.7  523.38  5185.5  525.07  5206.5  525.70  5213.6  526.33  5230.8  526.69
#Mann=4,-1,0
  4766.9    0.12       0  4987.0    0.07       0  4991.0    0.12       0
  5100.0    0.05       0
Bank Sta=4987,4991
Exp/Cntr=0.3,0.1

Type RM Length L Ch R = 1,1667,34,34,34
BEGIN DESCRIPTION:
Lacy 015 3500
END DESCRIPTION:
XS GIS Cut Line= 3
      2766250.69      6876862.40      2766044.44      6876881.99
      2765823.99      6877028.54
#Sta/Elev= 30
  4771.3  526.77  4786.1  526.34  4805.3  525.09  4810.3  525.39  4836.3  523.52
  4886.5  521.15  4906.6  520.61  4913.4  519.99  4918.4  520.27  4936.7  517.45
  4946.8  515.52  4956.8  515.06  5018.2  514.90  5018.5  514.40  5022.0  514.40
  5022.2  514.90  5084.7  515.48  5092.4  516.37  5098.4  519.44  5113.4  521.43
  5120.8  521.71  5164.5  523.63  5170.5  523.64  5179.6  524.47  5185.6  524.44
  5200.6  525.84  5206.6  525.71  5214.7  526.12  5236.7  526.93  5243.2  526.77
#Mann=5,-1,0
  4771.3    0.12       0  5018.2    0.07       0  5022.2    0.12       0
  5120.8    0.05       0  5214.7    0.12       0
Bank Sta=5018.2,5022.2
Exp/Cntr=0.3,0.1

Type RM Length L Ch R = 1,1633,29,29,29
BEGIN DESCRIPTION:
Lacy 015 3498
END DESCRIPTION:
XS GIS Cut Line= 3
      2766275.37      6876799.36      2766053.23      6876838.04
      2765814.52      6877011.41
#Sta/Elev= 30
  4735.0  526.44  4765.0  525.04  4825.7  522.84  4831.4  522.17  4836.5  522.51
  4856.2  522.09  4885.9  520.09  4891.0  520.60  4927.2  518.96  4937.4  518.24
  4945.5  515.70  4950.6  515.33  5052.4  514.97  5052.7  514.47  5056.2  514.47
  5056.4  514.97  5090.0  515.05  5110.9  515.60  5125.5  522.17  5129.1  522.23
  5146.4  522.63  5154.8  523.23  5161.1  526.13  5167.3  526.00  5175.8  524.54
  5182.0  524.37  5192.3  524.70  5204.2  525.78  5226.0  526.04  5255.5  526.95
#Mann=6,-1,0
  4735.0    0.05       0  4765.0    0.12       0  5052.4    0.07       0
  5056.4    0.12       0  5129.1    0.05       0  5192.3    0.12       0
Bank Sta=5052.4,5056.4
Exp/Cntr=0.3,0.1

Type RM Length L Ch R = 1,1604,124,124,124
BEGIN DESCRIPTION:
Lacy 015 3499
END DESCRIPTION:
XS GIS Cut Line= 3
      2766166.35      6876623.95      2766063.11      6876794.13
      2765825.43      6876966.75
#Sta/Elev= 30
  4726.0  525.77  4732.4  524.82  4738.2  525.57  4753.7  523.30  4757.7  523.73
  4769.2  522.90  4775.0  523.18  4790.5  521.35  4796.4  521.49  4811.9  519.65
  4839.5  518.27  4925.0  517.51  4946.8  516.38  4947.1  515.88  4950.6  515.88
  4950.8  516.38  4970.9  517.25  5013.7  517.13  5049.3  517.85  5064.0  518.97
  5070.2  518.63  5078.7  519.52  5084.9  518.39  5093.4  520.30  5099.5  519.87
  5106.9  521.40  5119.6  522.64  5137.2  523.03  5164.5  524.59  5218.8  525.85
#Mann=6,-1,0
  4726.0    0.05       0  4757.7    0.12       0  4946.8    0.07       0
  4950.8    0.12       0  5119.6    0.05       0  5137.2    0.12       0
Bank Sta=4946.8,4950.8
Exp/Cntr=0.3,0.1

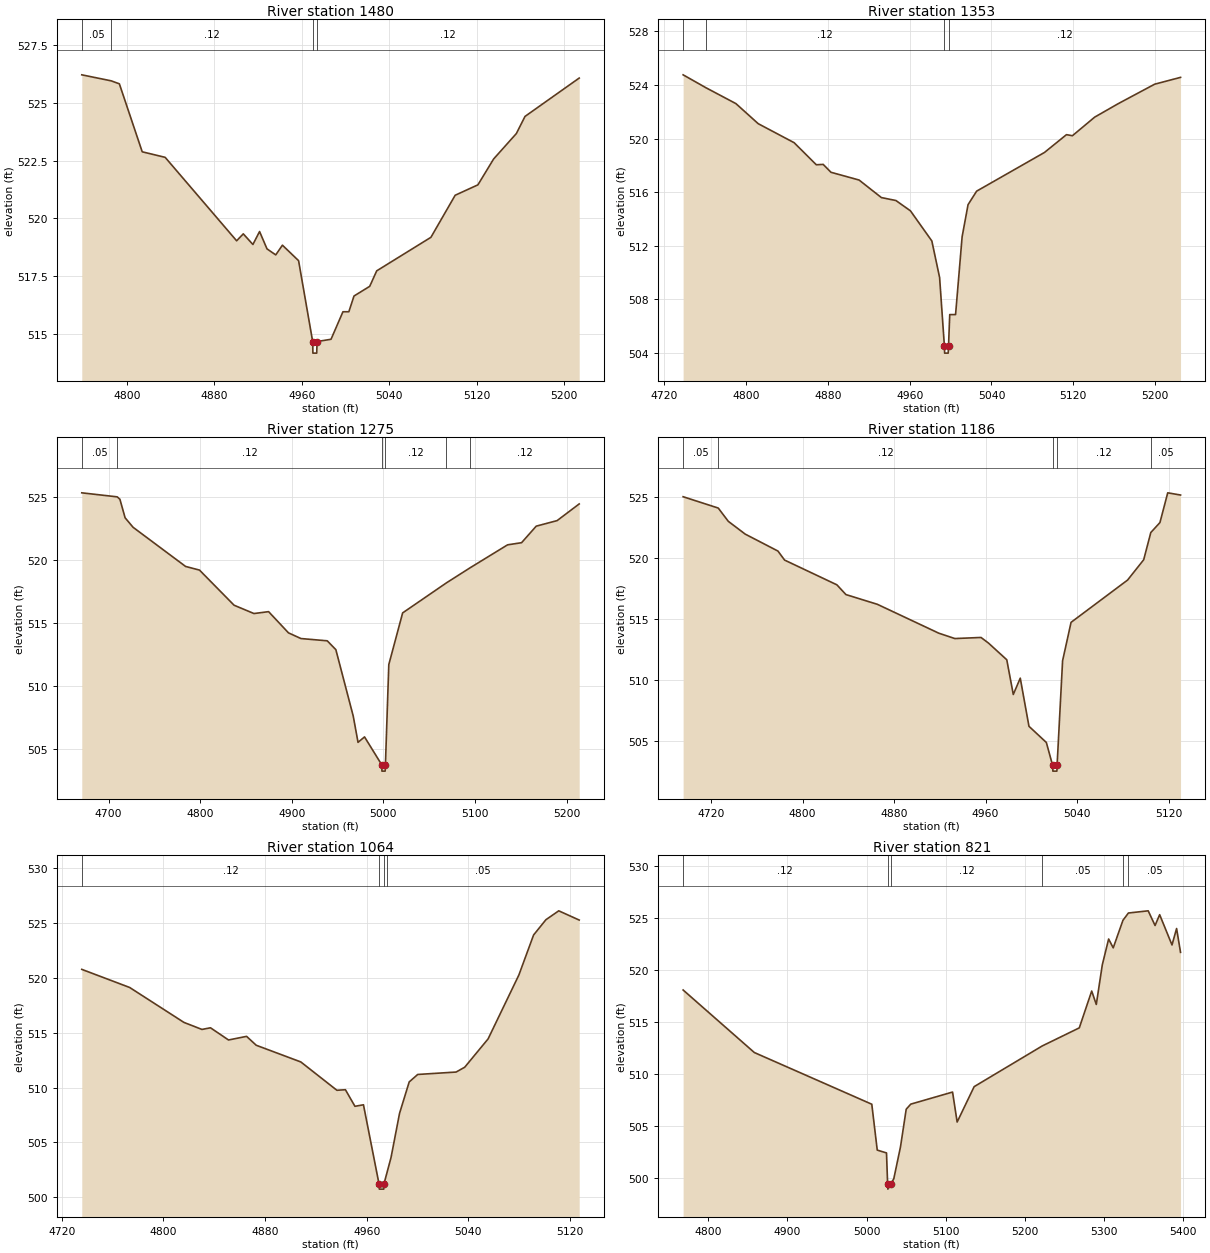
Type RM Length L Ch R = 1,1480,127,127,127
BEGIN DESCRIPTION:
Lacy 015 3497
END DESCRIPTION:
XS GIS Cut Line= 3
      2766145.12      6876593.50      2765946.89      6876731.51
      2765811.76      6876897.01
#Sta/Elev= 30
  4758.6  526.21  4785.5  525.95  4793.0  525.82  4813.9  522.88  4834.9  522.64
  4900.3  519.03  4906.4  519.33  4915.2  518.87  4921.3  519.43  4928.1  518.68
  4936.1  518.42  4942.2  518.84  4957.0  518.17  4969.9  514.67  4970.1  514.17
  4973.6  514.17  4973.9  514.67  4986.7  514.77  4997.6  515.96  5003.0  515.96
  5007.7  516.64  5022.1  517.06  5028.5  517.73  5078.1  519.18  5100.3  521.00
  5121.1  521.45  5135.5  522.57  5156.3  523.67  5164.2  524.41  5213.8  526.07
#Mann=4,-1,0
  4758.6    0.05       0  4785.5    0.12       0  4969.9    0.07       0
  4973.9    0.12       0
Bank Sta=4969.9,4973.9
Exp/Cntr=0.3,0.1

Type RM Length L Ch R = 1,1353,78,78,78
BEGIN DESCRIPTION:
Lacy 015 3494
END DESCRIPTION:
XS GIS Cut Line= 3
      2766064.33      6876475.95      2765867.44      6876650.33
      2765755.94      6876843.67
#Sta/Elev= 30
  4738.6  524.76  4760.8  523.80  4790.2  522.61  4812.0  521.11  4847.1  519.69
  4868.8  518.04  4875.5  518.07  4883.1  517.48  4910.6  516.90  4932.4  515.59
  4946.6  515.37  4960.8  514.60  4981.7  512.35  4989.3  509.62  4994.0  504.47
  4994.2  503.97  4997.7  503.97  4998.0  504.47  4999.2  506.85  5004.9  506.85
  5011.3  512.66  5017.1  515.06  5025.5  516.07  5091.8  518.96  5113.3  520.29
  5119.1  520.21  5140.9  521.60  5164.0  522.61  5199.5  524.06  5224.8  524.57
#Mann=4,-1,0
  4738.6    0.05       0  4760.8    0.12       0  4994.0    0.07       0
  4998.0    0.12       0
Bank Sta=4994,4998
Exp/Cntr=0.3,0.1

Type RM Length L Ch R = 1,1275,89,89,89
BEGIN DESCRIPTION:
Lacy 015 3496
END DESCRIPTION:
XS GIS Cut Line= 3
      2766044.93      6876414.42      2765823.99      6876537.55
      2765743.40      6876816.09
#Sta/Elev= 30
  4670.8  525.32  4709.5  525.00  4712.4  524.81  4718.1  523.34  4726.8  522.59
  4784.1  519.49  4799.3  519.20  4837.0  516.42  4858.7  515.76  4874.7  515.91
  4896.4  514.23  4910.0  513.78  4938.7  513.60  4948.1  512.90  4967.1  507.63
  4972.3  505.56  4979.4  505.99  4998.2  503.78  4998.4  503.28  5001.9  503.28
  5002.2  503.78  5005.9  511.72  5021.0  515.81  5068.8  518.19  5095.0  519.40
  5135.5  521.20  5150.8  521.37  5166.8  522.68  5189.6  523.12  5213.7  524.44
#Mann=6,-1,0
  4670.8    0.05       0  4709.5    0.12       0  4998.2    0.07       0
  5002.2    0.12       0  5068.8    0.05       0  5095.0    0.12       0
Bank Sta=4998.2,5002.2
Exp/Cntr=0.3,0.1

Type RM Length L Ch R = 1,1186,122,122,122
BEGIN DESCRIPTION:
Lacy 015 3495
END DESCRIPTION:
XS GIS Cut Line= 3
      2766023.44      6876395.67      2765757.80      6876543.72
      2765670.26      6876640.76
#Sta/Elev= 30
  4695.6  525.05  4726.3  524.12  4735.1  523.03  4749.9  521.98  4778.5  520.59
  4784.3  519.85  4830.0  517.82  4837.9  517.02  4865.4  516.22  4919.1  513.85
  4933.1  513.41  4956.0  513.50  4962.5  513.04  4978.5  511.67  4984.2  508.82
  4990.3  510.16  4997.9  506.21  5013.1  504.88  5018.5  503.03  5018.8  502.53
  5022.3  502.53  5022.5  503.03  5027.3  511.59  5034.7  514.74  5084.1  518.21
  5098.2  519.88  5104.4  522.11  5112.4  522.93  5119.2  525.37  5130.4  525.19
#Mann=5,-1,0
  4695.6    0.05       0  4726.3    0.12       0  5018.5    0.07       0
  5022.5    0.12       0  5104.4    0.05       0
Bank Sta=5018.5,5022.5
Exp/Cntr=0.3,0.1

Type RM Length L Ch R = 1,1064,243,243,243
BEGIN DESCRIPTION:
Lacy 015 3493
END DESCRIPTION:
XS GIS Cut Line= 3
      2765869.90      6876281.53      2765669.62      6876459.72
      2765627.13      6876575.60
#Sta/Elev= 30
  4735.8  520.76  4773.5  519.11  4816.2  515.93  4830.4  515.29  4837.1  515.44
  4851.3  514.33  4865.5  514.66  4873.1  513.85  4908.2  512.33  4936.6  509.75
  4943.3  509.80  4950.8  508.29  4957.5  508.43  4969.7  501.25  4970.0  500.75
  4973.5  500.75  4973.7  501.25  4976.2  502.33  4979.2  503.63  4985.9  507.65
  4993.5  510.51  5000.2  511.19  5030.4  511.41  5037.2  511.85  5055.6  514.43
  5079.8  520.24  5091.4  523.89  5101.1  525.28  5111.2  526.09  5127.3  525.25
#Mann=4,-1,0
  4735.8    0.12       0  4969.7    0.05       0  4973.7    0.12       0
  4976.2    0.05       0
Bank Sta=4969.7,4973.7
Exp/Cntr=0.3,0.1

Type RM Length L Ch R = 1,821,303,303,303
BEGIN DESCRIPTION:
Lacy 015 3492
END DESCRIPTION:
XS GIS Cut Line= 3
      2765732.13      6876090.18      2765544.33      6876265.70
      2765356.13      6876586.29
#Sta/Elev= 30
  4768.1  518.08  4858.1  512.07  5006.6  507.10  5013.5  502.69  5025.2  502.42
  5026.6  499.44  5026.9  498.94  5030.6  499.44  5034.4  499.93  5042.9  503.01
  5050.1  506.62  5055.9  507.11  5108.7  508.27  5114.5  505.39  5136.0  508.79
  5222.0  512.70  5268.9  514.44  5284.6  517.98  5290.4  516.69  5298.0  520.50
  5306.0  522.98  5311.8  522.13  5324.1  524.78  5331.0  525.48  5356.0  525.69
  5364.7  524.28  5370.5  525.32  5386.1  522.41  5391.9  523.99  5396.9  521.70
#Mann=6,-1,0
  4768.1    0.12       0  5026.6    0.07       0  5030.6    0.12       0
  5222.0    0.05       0  5324.1    0.12       0  5331.0    0.05       0
Bank Sta=5026.6,5030.6
Exp/Cntr=0.3,0.1

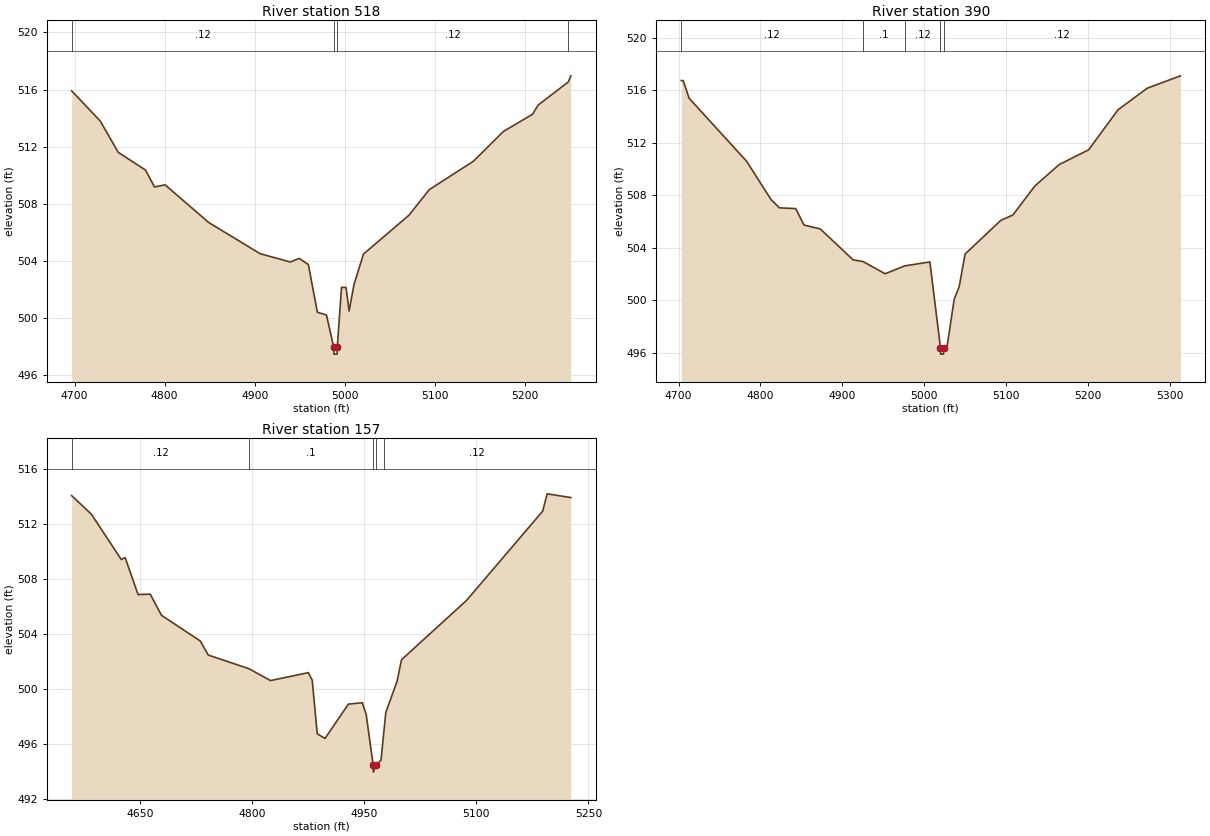
Type RM Length L Ch R = 1,518,128,128,128
BEGIN DESCRIPTION:
Lacy 015 3491
END DESCRIPTION:
XS GIS Cut Line= 3
      2765677.61      6876036.92      2765377.59      6876064.17
      2765135.39      6876136.06
#Sta/Elev= 30
  4696.8  515.91  4728.5  513.80  4748.6  511.60  4778.7  510.37  4788.8  509.18
  4800.5  509.33  4849.0  506.69  4906.0  504.51  4939.4  503.93  4949.4  504.18
  4959.5  503.75  4969.5  500.41  4979.6  500.22  4987.6  497.98  4987.9  497.48
  4991.4  497.48  4991.6  497.98  4996.3  502.15  5001.3  502.15  5004.7  500.50
  5010.1  502.34  5020.6  504.48  5071.1  507.20  5093.6  508.99  5142.8  510.99
  5176.0  513.07  5208.3  514.27  5214.4  514.91  5247.9  516.53  5250.7  516.96
#Mann=4,-1,0
  4696.8    0.12       0  4987.6    0.07       0  4991.6    0.12       0
  5247.9    0.05       0
Bank Sta=4987.6,4991.6
Exp/Cntr=0.3,0.1

Type RM Length L Ch R = 1,390,233,233,233
BEGIN DESCRIPTION:
Lacy 015 3505
END DESCRIPTION:
XS GIS Cut Line= 3
      2765645.64      6875906.24      2765392.95      6875917.34
      2765099.89      6876120.64
#Sta/Elev= 30
  4703.4  516.74  4705.7  516.74  4713.0  515.39  4783.1  510.60  4813.1  507.67
  4823.2  507.05  4843.2  506.99  4853.2  505.74  4873.2  505.44  4913.2  503.09
  4925.4  502.96  4952.3  502.03  4976.4  502.63  5007.0  502.93  5019.9  496.41
  5020.1  495.91  5023.6  495.91  5023.9  496.41  5027.9  496.45  5036.7  500.09
  5042.8  501.05  5050.0  503.53  5093.5  506.09  5108.3  506.50  5135.3  508.72
  5165.1  510.35  5200.9  511.47  5236.7  514.51  5272.5  516.16  5313.0  517.10
#Mann=5,-1,0
  4703.4    0.12       0  4925.4     0.1       0  4976.4    0.12       0
  5019.9    0.07       0  5023.9    0.12       0
Bank Sta=5019.9,5023.9
Exp/Cntr=0.3,0.1

Type RM Length L Ch R = 1,157,0,0,0
BEGIN DESCRIPTION:
Lacy 015 3504
END DESCRIPTION:
XS GIS Cut Line= 3
      2765611.39      6875865.56      2765228.20      6875753.96
      2765005.80      6875904.38
#Sta/Elev= 30
  4558.8  514.08  4585.2  512.73  4625.2  509.43  4630.4  509.57  4647.7  506.88
  4663.9  506.91  4679.0  505.37  4730.9  503.50  4741.5  502.48  4796.2  501.48
  4824.8  500.62  4875.4  501.20  4880.6  500.64  4887.3  496.75  4897.7  496.41
  4929.0  498.91  4947.6  499.01  4952.8  498.14  4962.1  494.46  4962.3  493.96
  4966.1  494.46  4972.6  494.84  4976.2  496.79  4979.0  498.30  4994.0  500.56
  5000.0  502.14  5086.9  506.45  5188.8  512.95  5194.8  514.21  5226.4  513.94
#Mann=5,-1,0
  4558.8    0.12       0  4796.2     0.1       0  4962.1    0.07       0
  4966.1     0.1       0  4976.2    0.12       0
Bank Sta=4962.1,4966.1
Exp/Cntr=0.3,0.1

Chan Stop Cuts=-1