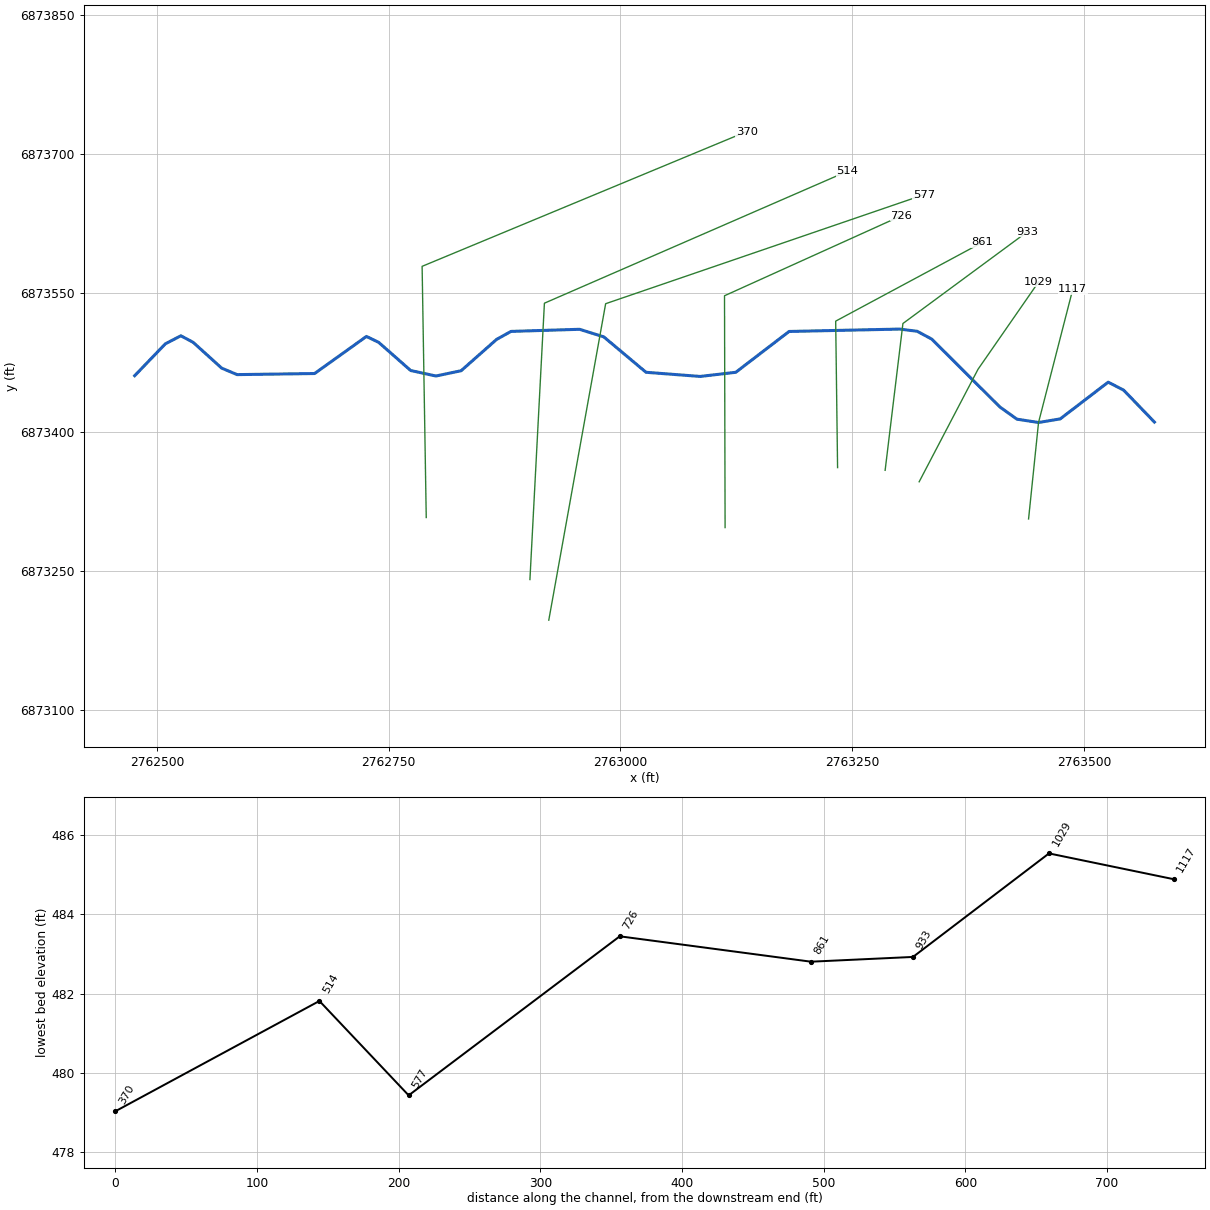
--- Lacy 016.prj (project) ---

Proj Title=Lacy 016 Base Level Engineering
Current Plan=p01
Default Exp/Contr=0.3,0.1
English Units
Geom File=g01
Flow File=f01
Plan File=p01
BEGIN DESCRIPTION:
Lacy 016
END DESCRIPTION:

--- Lacy 016.p01 (plan) ---

Plan Title=Multiple Run
Short Identifier=Multiple
Geom File=g01
Flow File=f01
Subcritical Flow
K Sum by GR= 0
Std Step Tol= 0.01
Critical Tol= 0.01
Num of Std Step Trials= 20
Max Error Tol= 0.3
Flow Tol Ratio= 0.001
Split Flow NTrial= 30
Split Flow Tol= 0.02
Split Flow Ratio= 0.02
Log Output Level= 0
Friction Slope Method= 1
Unsteady Friction Slope Method= 2
Unsteady Bridges Friction Slope Method= 1
Parabolic Critical Depth
Global Vel Dist=  1 , 1 , 1
Global Log Level= 0
CheckData=True
Encroach Param= -1, 0, 0, 0
BEGIN DESCRIPTION:
Multiple Run
END DESCRIPTION:

--- Lacy 016.f01 (steady flow) ---

Flow Title=Multiple
Number of Profiles=7
Profile Names=10-year,25-year,50-year,1pct_min,100-year,1pct_plu,500-year
River Rch & RM= Lacy 016,Reach-1,1117
     283     367     433     255     510    1017     705
Boundary for River Rch & Prof#=Lacy 016,Reach-1,1
Up Type=0
Dn Type=3
Dn Slope=0.005
Boundary for River Rch & Prof#=Lacy 016,Reach-1,2
Up Type=0
Dn Type=3
Dn Slope=0.005
Boundary for River Rch & Prof#=Lacy 016,Reach-1,3
Up Type=0
Dn Type=3
Dn Slope=0.005
Boundary for River Rch & Prof#=Lacy 016,Reach-1,4
Up Type=0
Dn Type=3
Dn Slope=0.005
Boundary for River Rch & Prof#=Lacy 016,Reach-1,5
Up Type=0
Dn Type=3
Dn Slope=0.005
Boundary for River Rch & Prof#=Lacy 016,Reach-1,6
Up Type=0
Dn Type=3
Dn Slope=0.005
Boundary for River Rch & Prof#=Lacy 016,Reach-1,7
Up Type=0
Dn Type=3
Dn Slope=0.005

--- Lacy 016.g01 (geometry) ---

Geom Title=Existing Conditions

River Reach=Lacy 016,Reach-1
Reach XY= 30
      2763576.00      6873411.00      2763542.83      6873445.44
      2763526.12      6873454.05      2763474.37      6873414.43
      2763450.99      6873410.55      2763427.65      6873414.16
      2763409.34      6873427.26      2763335.79      6873500.50
      2763320.14      6873508.94      2763301.11      6873511.32
      2763181.94      6873508.75      2763124.40      6873464.71
      2763086.05      6873460.23      2763027.60      6873464.71
      2762982.04      6873502.90      2762955.90      6873511.09
      2762881.97      6873508.81      2762866.35      6873500.13
      2762828.17      6873466.40      2762800.96      6873460.69
      2762773.71      6873466.65      2762739.24      6873496.98
      2762726.01      6873503.40      2762670.11      6873463.37
      2762586.47      6873462.20      2762569.80      6873469.24
      2762539.12      6873497.02      2762525.86      6873504.09
      2762509.16      6873495.46      2762476.00      6873461.00

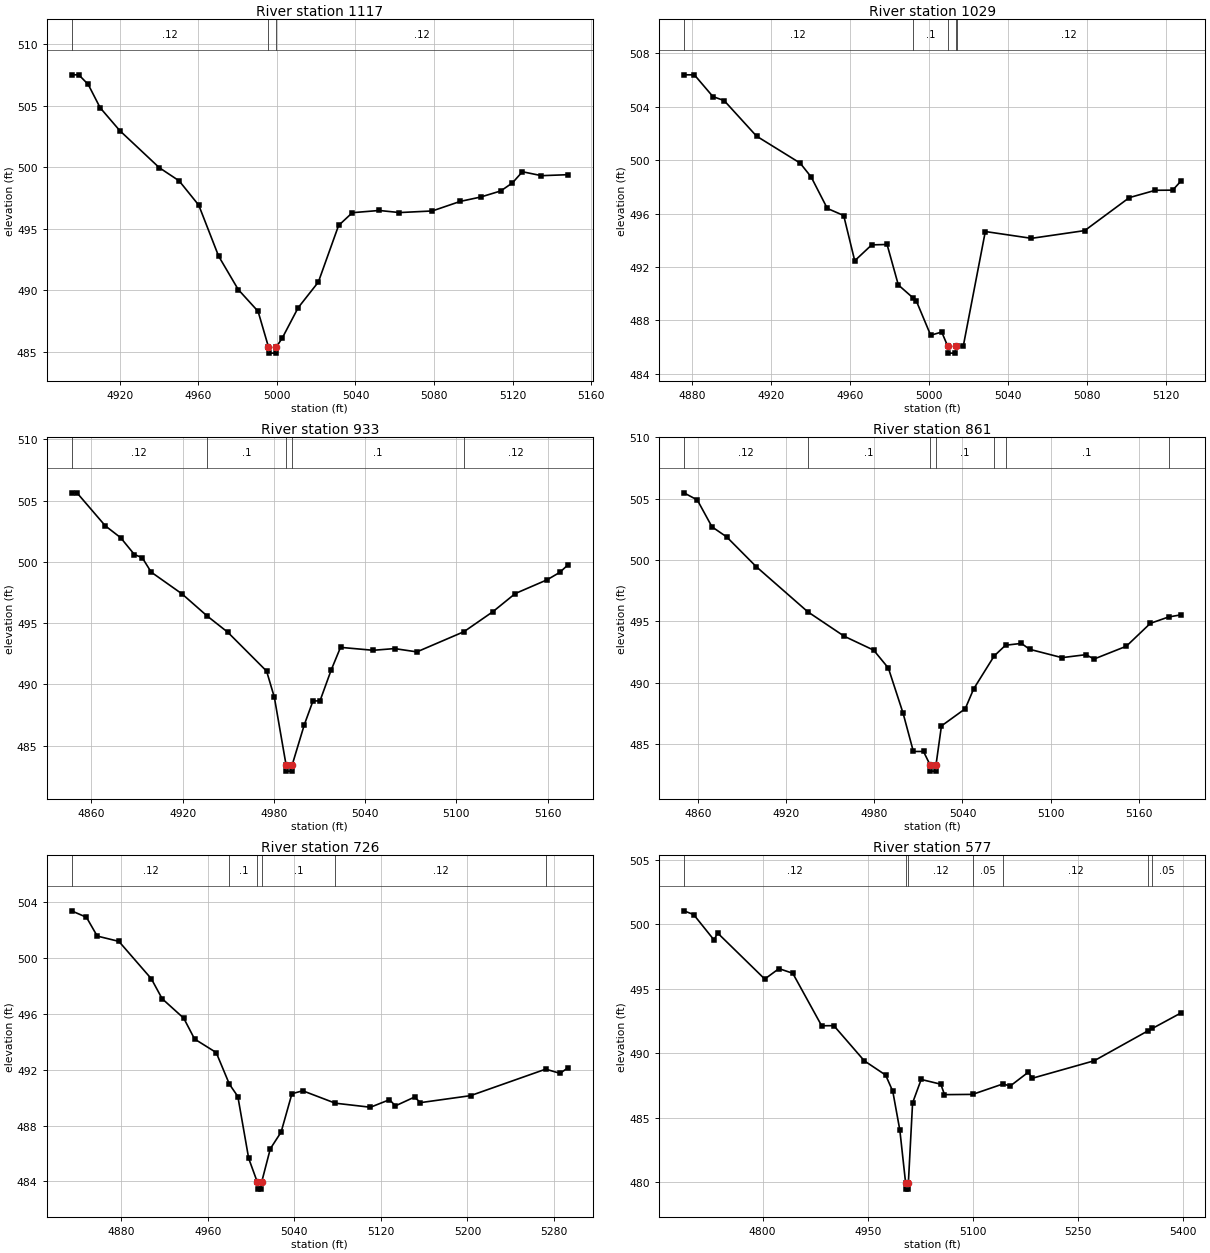
Type RM Length L Ch R = 1,1117,88,88,88
BEGIN DESCRIPTION:
Lacy 016 3477
END DESCRIPTION:
XS GIS Cut Line= 3
      2763440.24      6873306.50      2763450.99      6873410.55
      2763487.90      6873554.18
#Sta/Elev= 30
  4895.4  507.52  4899.1  507.52  4903.9  506.74  4910.0  504.84  4920.0  502.98
  4940.1  499.97  4950.2  498.90  4960.2  496.92  4970.3  492.78  4980.3  490.06
  4990.4  488.29  4995.7  485.39  4996.0  484.89  4999.5  484.89  4999.7  485.39
  5002.8  486.14  5010.8  488.58  5021.1  490.67  5031.4  495.27  5038.4  496.31
  5052.1  496.49  5062.4  496.32  5079.1  496.45  5093.4  497.23  5103.7  497.58
  5114.0  498.08  5119.9  498.73  5125.0  499.64  5134.7  499.32  5148.3  499.40
#Mann=3,-1,0
  4895.4    0.12       0  4995.7    0.07       0  4999.7    0.12       0
Bank Sta=4995.7,4999.7
Exp/Cntr=0.3,0.1

Type RM Length L Ch R = 1,1029,96,96,96
BEGIN DESCRIPTION:
Lacy 016 3476
END DESCRIPTION:
XS GIS Cut Line= 3
      2763322.24      6873346.62      2763385.70      6873467.93
      2763451.17      6873562.35
#Sta/Elev= 30
  4875.8  506.39  4881.1  506.39  4890.5  504.76  4896.2  504.46  4912.6  501.80
  4934.7  499.78  4940.3  498.74  4948.5  496.38  4956.8  495.85  4962.4  492.46
  4971.0  493.65  4978.8  493.68  4984.5  490.65  4991.8  489.70  4993.6  489.46
  5000.9  486.88  5006.5  487.12  5009.6  486.04  5009.9  485.54  5013.4  485.54
  5013.6  486.04  5014.2  486.04  5017.4  486.04  5028.6  494.65  5052.0  494.14
  5079.0  494.72  5101.6  497.19  5114.8  497.74  5123.6  497.75  5127.6  498.40
#Mann=5,-1,0
  4875.8    0.12       0  4991.8     0.1       0  5009.6    0.07       0
  5013.6     0.1       0  5014.2    0.12       0
Bank Sta=5009.6,5013.6
Exp/Cntr=0.3,0.1

Type RM Length L Ch R = 1,933,72,72,72
BEGIN DESCRIPTION:
Lacy 016 3475
END DESCRIPTION:
XS GIS Cut Line= 3
      2763285.52      6873358.98      2763304.71      6873517.34
      2763439.18      6873616.50
#Sta/Elev= 30
  4846.9  505.64  4850.5  505.64  4869.1  502.95  4879.2  501.98  4888.3  500.60
  4893.4  500.35  4899.3  499.17  4919.5  497.40  4936.1  495.59  4949.7  494.26
  4975.2  491.09  4980.3  488.95  4988.0  483.43  4988.2  482.93  4991.7  482.93
  4992.0  483.43  5000.0  486.72  5005.7  488.66  5010.3  488.66  5017.6  491.16
  5023.8  493.03  5045.3  492.79  5059.3  492.93  5074.0  492.66  5105.0  494.31
  5124.1  495.95  5138.7  497.42  5159.6  498.54  5168.0  499.15  5173.5  499.78
#Mann=5,-1,0
  4846.9    0.12       0  4936.1     0.1       0  4988.0    0.07       0
  4992.0     0.1       0  5105.0    0.12       0
Bank Sta=4988,4992
Exp/Cntr=0.3,0.1

Type RM Length L Ch R = 1,861,135,135,135
BEGIN DESCRIPTION:
Lacy 016 3474
END DESCRIPTION:
XS GIS Cut Line= 3
      2763234.22      6873361.88      2763232.18      6873519.89
      2763390.66      6873604.98
#Sta/Elev= 30
  4850.5  505.47  4859.6  504.89  4869.6  502.70  4879.6  501.88  4899.6  499.47
  4934.7  495.79  4959.6  493.79  4979.6  492.66  4989.6  491.20  4999.6  487.53
  5006.6  484.41  5013.5  484.41  5018.0  483.31  5018.2  482.81  5021.7  482.81
  5022.0  483.31  5025.7  486.49  5041.9  487.89  5047.6  489.50  5061.6  492.19
  5069.3  493.06  5080.1  493.21  5085.7  492.73  5107.7  492.05  5123.9  492.29
  5129.6  491.94  5151.5  492.98  5167.8  494.84  5180.2  495.36  5188.4  495.53
#Mann=7,-1,0
  4850.5    0.12       0  4934.7     0.1       0  5018.0    0.07       0
  5022.0     0.1       0  5061.6    0.12       0  5069.3     0.1       0
  5180.2    0.12       0
Bank Sta=5018,5022
Exp/Cntr=0.3,0.1

Type RM Length L Ch R = 1,726,149,149,149
BEGIN DESCRIPTION:
Lacy 016 3472
END DESCRIPTION:
XS GIS Cut Line= 3
      2763112.89      6873297.21      2763112.26      6873547.26
      2763302.83      6873633.44
#Sta/Elev= 30
  4833.9  503.40  4847.7  502.94  4857.7  501.59  4877.7  501.21  4907.7  498.53
  4917.7  497.10  4937.7  495.70  4947.7  494.21  4967.7  493.24  4979.9  490.97
  4987.7  490.09  4997.7  485.66  5005.7  483.95  5005.9  483.45  5009.4  483.45
  5009.7  483.95  5017.7  486.34  5027.7  487.54  5037.7  490.29  5047.7  490.50
  5077.8  489.61  5110.3  489.32  5127.9  489.86  5133.4  489.42  5151.1  490.05
  5156.5  489.65  5202.8  490.15  5272.3  492.05  5285.6  491.75  5293.1  492.16
#Mann=6,-1,0
  4833.9    0.12       0  4979.9     0.1       0  5005.7    0.07       0
  5009.7     0.1       0  5077.8    0.12       0  5272.3     0.1       0
Bank Sta=5005.7,5009.7
Exp/Cntr=0.3,0.1

Type RM Length L Ch R = 1,577,63,63,63
BEGIN DESCRIPTION:
Lacy 016 3473
END DESCRIPTION:
XS GIS Cut Line= 3
      2762922.71      6873197.33      2762984.05      6873538.70
      2763327.25      6873656.24
#Sta/Elev= 30
  4687.5  501.06  4701.4  500.77  4730.6  498.79  4735.6  499.34  4803.0  495.76
  4823.3  496.57  4843.0  496.21  4884.3  492.13  4901.7  492.14  4945.2  489.41
  4975.7  488.30  4985.9  487.04  4996.0  484.02  5004.2  479.94  5004.4  479.44
  5007.9  479.44  5008.2  479.94  5014.2  486.14  5026.5  487.96  5054.6  487.59
  5059.8  486.78  5099.9  486.80  5143.3  487.61  5153.7  487.45  5179.7  488.53
  5185.0  488.05  5273.6  489.41  5350.9  491.75  5356.7  491.92  5397.1  493.11
#Mann=7,-1,0
  4687.5    0.12       0  5004.2    0.07       0  5008.2    0.12       0
  5099.9    0.05       0  5143.3    0.12       0  5350.9     0.1       0
  5356.7    0.05       0
Bank Sta=5004.2,5008.2
Exp/Cntr=0.3,0.1

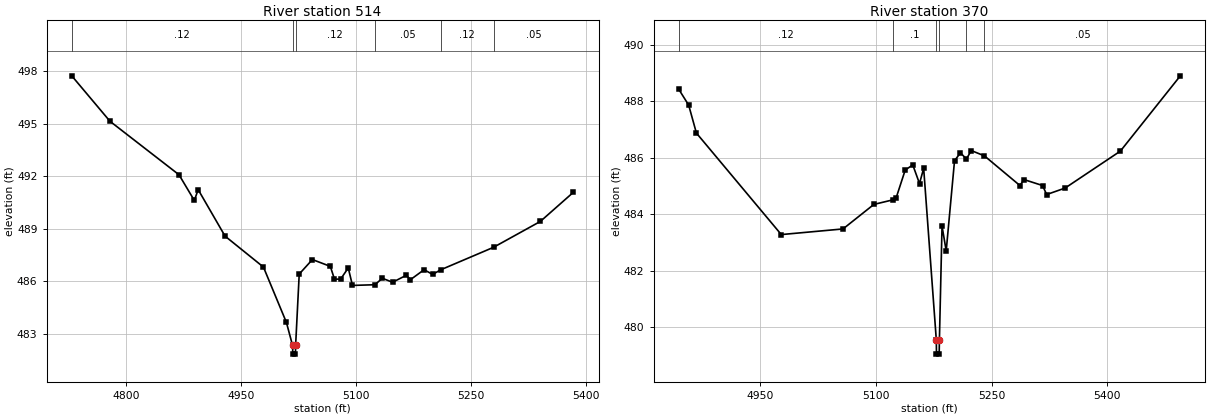
Type RM Length L Ch R = 1,514,144,144,144
BEGIN DESCRIPTION:
Lacy 016 3471
END DESCRIPTION:
XS GIS Cut Line= 3
      2762902.37      6873241.15      2762917.99      6873539.24
      2763244.68      6873681.46
#Sta/Elev= 30
  4729.3  497.74  4779.2  495.14  4869.3  492.08  4889.3  490.61  4894.3  491.23
  4929.4  488.57  4979.5  486.80  5009.5  483.63  5017.5  482.32  5017.8  481.82
  5021.3  481.82  5021.5  482.32  5026.2  486.40  5043.4  487.23  5066.8  486.84
  5072.2  486.11  5080.2  486.11  5090.2  486.75  5095.7  485.75  5125.0  485.79
  5134.7  486.16  5148.0  485.93  5166.0  486.33  5171.4  486.08  5189.2  486.65
  5200.3  486.38  5211.2  486.65  5279.8  487.93  5340.9  489.41  5384.1  491.08
#Mann=6,-1,0
  4729.3    0.12       0  5017.5    0.07       0  5021.5    0.12       0
  5125.0    0.05       0  5211.2    0.12       0  5279.8    0.05       0
Bank Sta=5017.5,5021.5
Exp/Cntr=0.3,0.1

Type RM Length L Ch R = 1,370,0,0,0
BEGIN DESCRIPTION:
Lacy 016 3455
END DESCRIPTION:
XS GIS Cut Line= 3
      2762790.53      6873308.05      2762786.08      6873579.00
      2763136.20      6873724.40
#Sta/Elev= 30
  4844.5  488.44  4857.5  487.87  4867.5  486.88  4977.5  483.28  5057.5  483.48
  5097.5  484.35  5121.9  484.51  5126.2  484.57  5138.1  485.57  5147.9  485.75
  5156.6  485.09  5162.0  485.63  5178.4  479.54  5178.6  479.04  5182.1  479.04
  5182.4  479.54  5185.8  483.58  5191.2  482.70  5202.0  485.90  5209.7  486.18
  5217.4  485.96  5223.7  486.26  5240.8  486.07  5286.7  485.02  5292.1  485.23
  5316.0  485.02  5321.4  484.70  5345.3  484.93  5416.9  486.24  5494.6  488.91
#Mann=6,-1,0
  4844.5    0.12       0  5121.9     0.1       0  5178.4    0.07       0
  5182.4     0.1       0  5217.4    0.12       0  5240.8    0.05       0
Bank Sta=5178.4,5182.4
Exp/Cntr=0.3,0.1

Chan Stop Cuts=-1