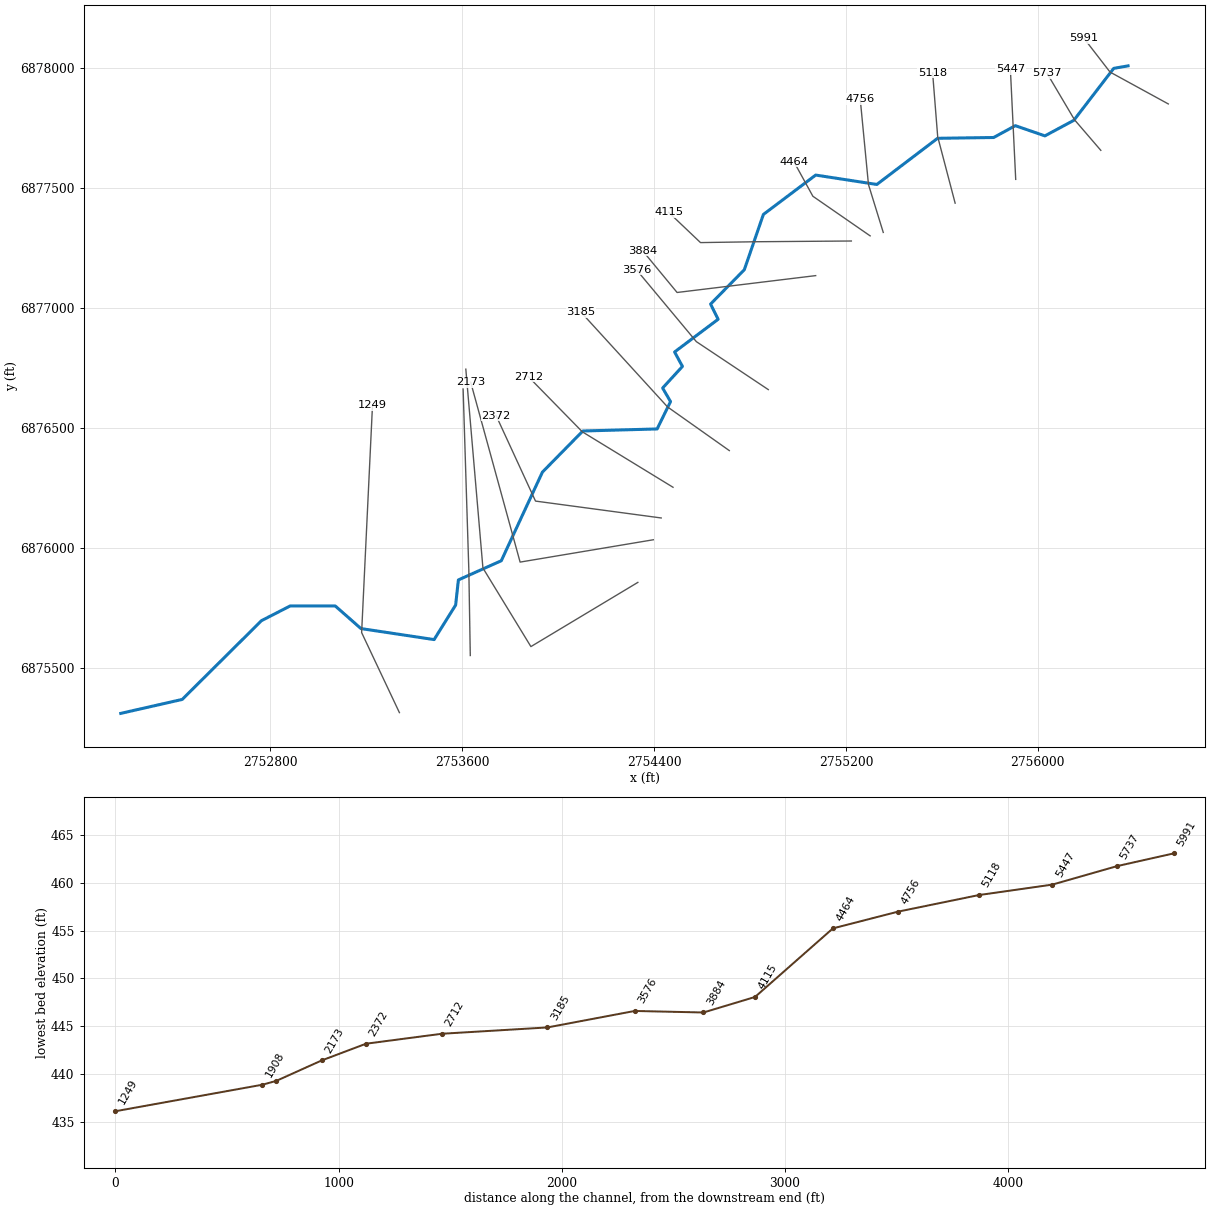
--- Lacy 017.prj (project) ---

Proj Title=Lacy 017 Base Level Engineering
Current Plan=p01
Default Exp/Contr=0.3,0.1
English Units
Geom File=g01
Flow File=f01
Plan File=p01
BEGIN DESCRIPTION:
Lacy 017
END DESCRIPTION:

--- Lacy 017.p01 (plan) ---

Plan Title=Multiple Run
Short Identifier=Multiple
Geom File=g01
Flow File=f01
Subcritical Flow
K Sum by GR= 0
Std Step Tol= 0.01
Critical Tol= 0.01
Num of Std Step Trials= 20
Max Error Tol= 0.3
Flow Tol Ratio= 0.001
Split Flow NTrial= 30
Split Flow Tol= 0.02
Split Flow Ratio= 0.02
Log Output Level= 0
Friction Slope Method= 1
Unsteady Friction Slope Method= 2
Unsteady Bridges Friction Slope Method= 1
Parabolic Critical Depth
Global Vel Dist=  1 , 1 , 1
Global Log Level= 0
CheckData=True
Encroach Param= -1, 0, 0, 0
BEGIN DESCRIPTION:
Multiple Run
END DESCRIPTION:

--- Lacy 017.f01 (steady flow) ---

Flow Title=Multiple
Number of Profiles=7
Profile Names=10-year,25-year,50-year,1pct_min,100-year,1pct_plu,500-year
River Rch & RM= Lacy 017,Reach-1,5991
     173     214     244     139     278     554     359
River Rch & RM= Lacy 017,Reach-1,3884
     356     461     544     319     637    1271     875
Boundary for River Rch & Prof#=Lacy 017,Reach-1,1
Up Type=0
Dn Type=3
Dn Slope=0.005
Boundary for River Rch & Prof#=Lacy 017,Reach-1,2
Up Type=0
Dn Type=3
Dn Slope=0.005
Boundary for River Rch & Prof#=Lacy 017,Reach-1,3
Up Type=0
Dn Type=3
Dn Slope=0.005
Boundary for River Rch & Prof#=Lacy 017,Reach-1,4
Up Type=0
Dn Type=3
Dn Slope=0.005
Boundary for River Rch & Prof#=Lacy 017,Reach-1,5
Up Type=0
Dn Type=3
Dn Slope=0.005
Boundary for River Rch & Prof#=Lacy 017,Reach-1,6
Up Type=0
Dn Type=3
Dn Slope=0.005
Boundary for River Rch & Prof#=Lacy 017,Reach-1,7
Up Type=0
Dn Type=3
Dn Slope=0.005

--- Lacy 017.g01 (geometry) ---

Geom Title=Existing Conditions

River Reach=Lacy 017,Reach-1
Reach XY= 30
      2756376.00      6878011.00      2756316.21      6878000.49
      2756149.84      6877783.85      2756029.32      6877719.04
      2755905.96      6877761.58      2755815.50      6877712.22
      2755581.86      6877708.94      2755328.42      6877516.41
      2755073.57      6877555.60      2754855.43      6877391.41
      2754776.00      6877161.00      2754635.29      6877017.67
      2754666.70      6876954.32      2754485.19      6876817.95
      2754517.96      6876757.68      2754435.33      6876667.67
      2754468.23      6876611.09      2754412.41      6876496.97
      2754102.67      6876488.48      2753934.14      6876317.06
      2753762.55      6875947.37      2753583.73      6875867.50
      2753572.17      6875762.59      2753482.48      6875618.69
      2753177.50      6875664.62      2753070.14      6875758.94
      2752881.93      6875758.76      2752762.46      6875697.46
      2752432.05      6875369.12      2752176.00      6875311.00

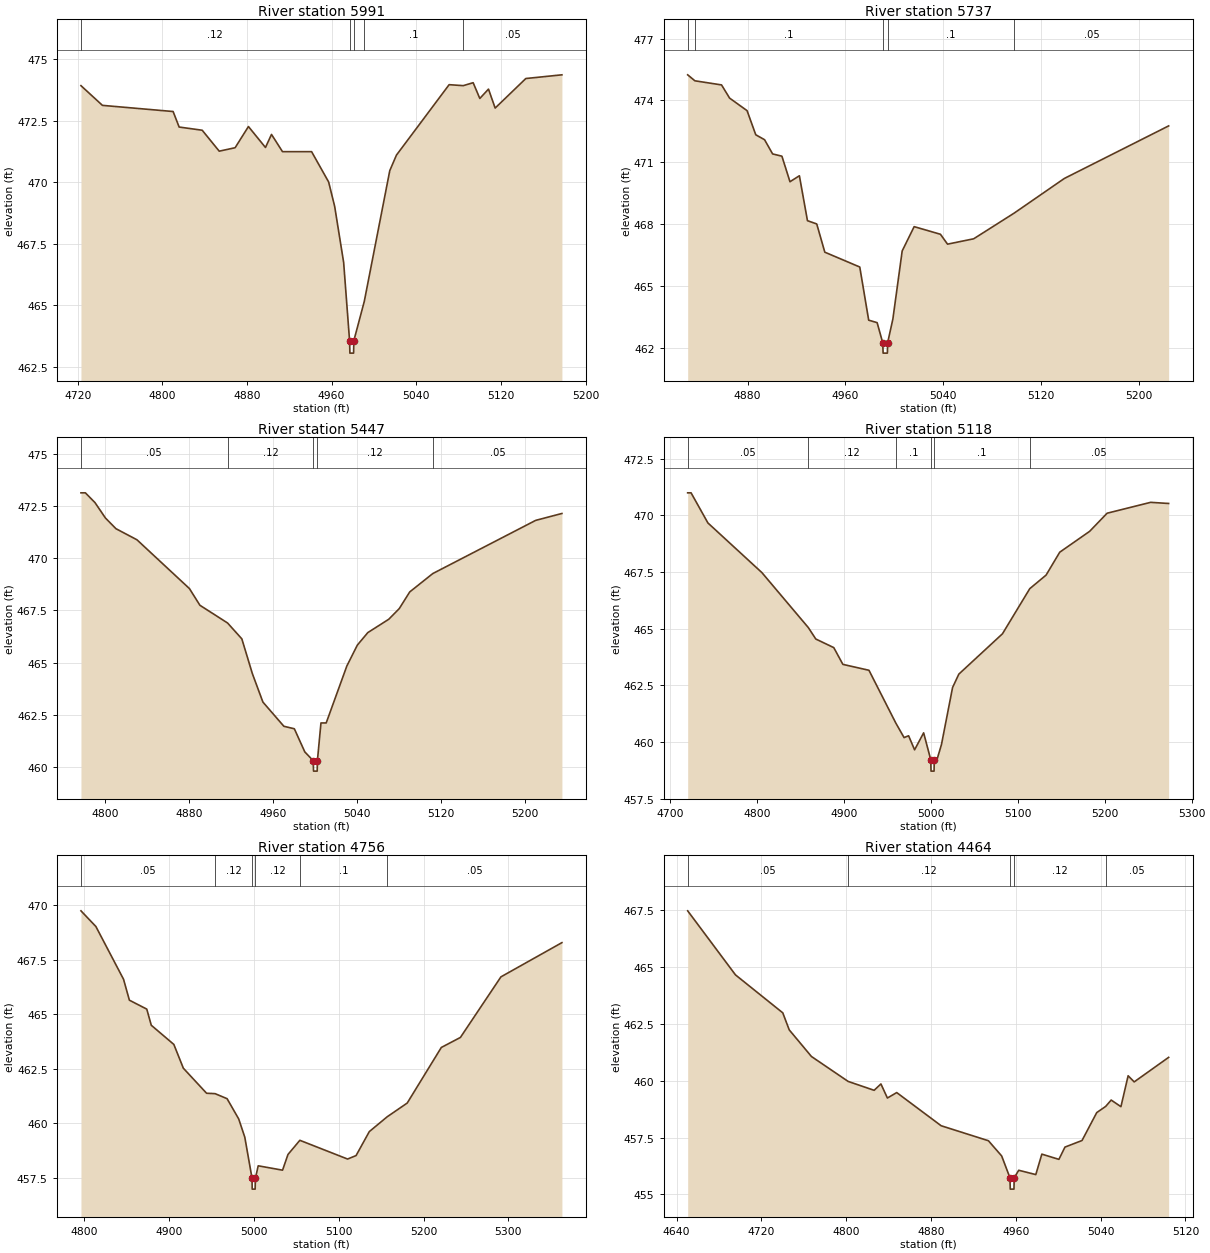
Type RM Length L Ch R = 1,5991,254,254,254
BEGIN DESCRIPTION:
Lacy 017 3259
END DESCRIPTION:
XS GIS Cut Line= 3
      2756543.83      6877852.23      2756300.90      6877985.13
      2756192.27      6878125.75
#Sta/Elev= 30
  4723.1  473.92  4743.4  473.12  4810.2  472.87  4815.9  472.24  4837.7  472.11
  4853.8  471.26  4868.8  471.40  4881.4  472.26  4897.5  471.41  4903.2  471.94
  4913.6  471.24  4941.1  471.24  4957.2  470.01  4962.9  469.02  4971.4  466.74
  4977.0  463.56  4977.3  463.06  4980.8  463.06  4981.0  463.56  4990.9  465.16
  5015.0  470.47  5021.3  471.10  5071.1  473.96  5084.4  473.92  5093.8  474.04
  5100.1  473.40  5108.3  473.78  5114.6  473.01  5143.6  474.21  5177.7  474.36
#Mann=5,-1,0
  4723.1    0.12       0  4977.0    0.07       0  4981.0    0.12       0
  4990.9     0.1       0  5084.4    0.05       0
Bank Sta=4977,4981
Exp/Cntr=0.3,0.1

Type RM Length L Ch R = 1,5737,290,290,290
BEGIN DESCRIPTION:
Lacy 017 3258
END DESCRIPTION:
XS GIS Cut Line= 3
      2756262.36      6877658.78      2756152.85      6877786.04
      2756038.05      6877980.25
#Sta/Elev= 30
  4831.0  475.24  4836.9  474.95  4858.7  474.75  4865.3  474.11  4879.6  473.50
  4886.7  472.33  4893.9  472.09  4900.5  471.40  4908.1  471.29  4914.7  470.05
  4922.4  470.34  4929.0  468.16  4936.6  468.00  4943.2  466.63  4971.8  465.91
  4979.1  463.33  4986.0  463.21  4990.6  462.23  4990.9  461.73  4994.4  461.73
  4994.6  462.23  4998.9  463.39  5006.5  466.69  5016.3  467.87  5037.8  467.50
  5043.6  467.02  5065.0  467.28  5098.2  468.53  5139.2  470.21  5224.5  472.76
#Mann=5,-1,0
  4831.0    0.12       0  4836.9     0.1       0  4990.6    0.07       0
  4994.6     0.1       0  5098.2    0.05       0
Bank Sta=4990.6,4994.6
Exp/Cntr=0.3,0.1

Type RM Length L Ch R = 1,5447,329,329,329
BEGIN DESCRIPTION:
Lacy 017 3256
END DESCRIPTION:
XS GIS Cut Line= 3
      2755907.59      6877537.64      2755896.51      6877766.81
      2755885.43      6877996.01
#Sta/Elev= 30
  4776.6  473.14  4780.8  473.14  4790.0  472.67  4800.0  471.93  4810.0  471.42
  4830.0  470.89  4880.1  468.55  4890.1  467.75  4916.5  466.90  4930.1  466.14
  4940.1  464.48  4950.2  463.11  4970.2  461.95  4980.2  461.83  4990.2  460.72
  4998.2  460.30  4998.5  459.80  5002.0  459.80  5002.2  460.30  5005.6  462.11
  5010.6  462.11  5030.3  464.84  5040.3  465.84  5050.3  466.44  5070.3  467.08
  5080.3  467.59  5090.3  468.39  5112.3  469.27  5210.5  471.82  5235.5  472.15
#Mann=5,-1,0
  4776.6    0.05       0  4916.5    0.12       0  4998.2    0.07       0
  5002.2    0.12       0  5112.3    0.05       0
Bank Sta=4998.2,5002.2
Exp/Cntr=0.3,0.1

Type RM Length L Ch R = 1,5118,362,362,362
BEGIN DESCRIPTION:
Lacy 017 3257
END DESCRIPTION:
XS GIS Cut Line= 3
      2755655.02      6877438.42      2755582.25      6877715.87
      2755561.12      6877981.59
#Sta/Elev= 30
  4720.1  470.99  4724.0  470.99  4743.4  469.66  4805.5  467.47  4859.0  465.04
  4867.5  464.54  4888.2  464.16  4898.7  463.42  4928.7  463.16  4959.6  460.83
  4969.1  460.19  4974.3  460.27  4981.2  459.65  4991.6  460.40  4999.8  459.21
  5000.1  458.71  5003.6  458.71  5003.8  459.21  5006.9  459.21  5012.1  459.88
  5024.9  462.40  5032.1  462.99  5082.3  464.77  5113.7  466.76  5132.5  467.36
  5148.2  468.37  5182.6  469.29  5202.7  470.09  5252.8  470.57  5273.5  470.52
#Mann=6,-1,0
  4720.1    0.05       0  4859.0    0.12       0  4959.6     0.1       0
  4999.8    0.07       0  5003.8     0.1       0  5113.7    0.05       0
Bank Sta=4999.8,5003.8
Exp/Cntr=0.3,0.1

Type RM Length L Ch R = 1,4756,292,292,292
BEGIN DESCRIPTION:
Lacy 017 3254
END DESCRIPTION:
XS GIS Cut Line= 3
      2755355.32      6877316.40      2755293.61      6877516.20
      2755259.27      6877872.54
#Sta/Elev= 30
  4796.0  469.75  4813.6  469.03  4846.2  466.61  4853.1  465.65  4873.6  465.24
  4878.9  464.50  4905.5  463.62  4916.7  462.53  4944.1  461.38  4954.2  461.36
  4968.3  461.13  4982.0  460.20  4989.2  459.36  4997.7  457.48  4997.9  456.98
  5001.4  456.98  5001.7  457.48  5005.0  458.05  5033.7  457.85  5040.1  458.57
  5054.1  459.22  5110.4  458.36  5120.4  458.52  5136.0  459.62  5157.1  460.30
  5180.7  460.93  5220.9  463.48  5243.4  463.94  5291.2  466.72  5363.1  468.29
#Mann=6,-1,0
  4796.0    0.05       0  4954.2    0.12       0  4997.7    0.07       0
  5001.7    0.12       0  5054.1     0.1       0  5157.1    0.05       0
Bank Sta=4997.7,5001.7
Exp/Cntr=0.3,0.1

Type RM Length L Ch R = 1,4464,349,349,349
BEGIN DESCRIPTION:
Lacy 017 3255
END DESCRIPTION:
XS GIS Cut Line= 3
      2755300.62      6877302.08      2755061.84      6877467.27
      2754983.15      6877610.41
#Sta/Elev= 30
  4650.5  467.48  4695.6  464.66  4740.2  462.99  4746.3  462.24  4767.2  461.07
  4801.9  459.97  4826.4  459.58  4832.8  459.86  4838.9  459.24  4847.7  459.48
  4889.6  458.02  4934.2  457.36  4946.7  456.69  4954.5  455.73  4954.8  455.23
  4958.3  455.23  4958.5  455.73  4962.8  456.06  4978.9  455.87  4984.6  456.77
  5000.7  456.54  5006.4  457.08  5022.5  457.37  5036.4  458.60  5044.8  458.87
  5050.0  459.15  5059.2  458.86  5066.0  460.22  5071.7  459.95  5104.2  461.03
#Mann=5,-1,0
  4650.5    0.05       0  4801.9    0.12       0  4954.5    0.07       0
  4958.5    0.12       0  5044.8    0.05       0
Bank Sta=4954.5,4958.5
Exp/Cntr=0.3,0.1

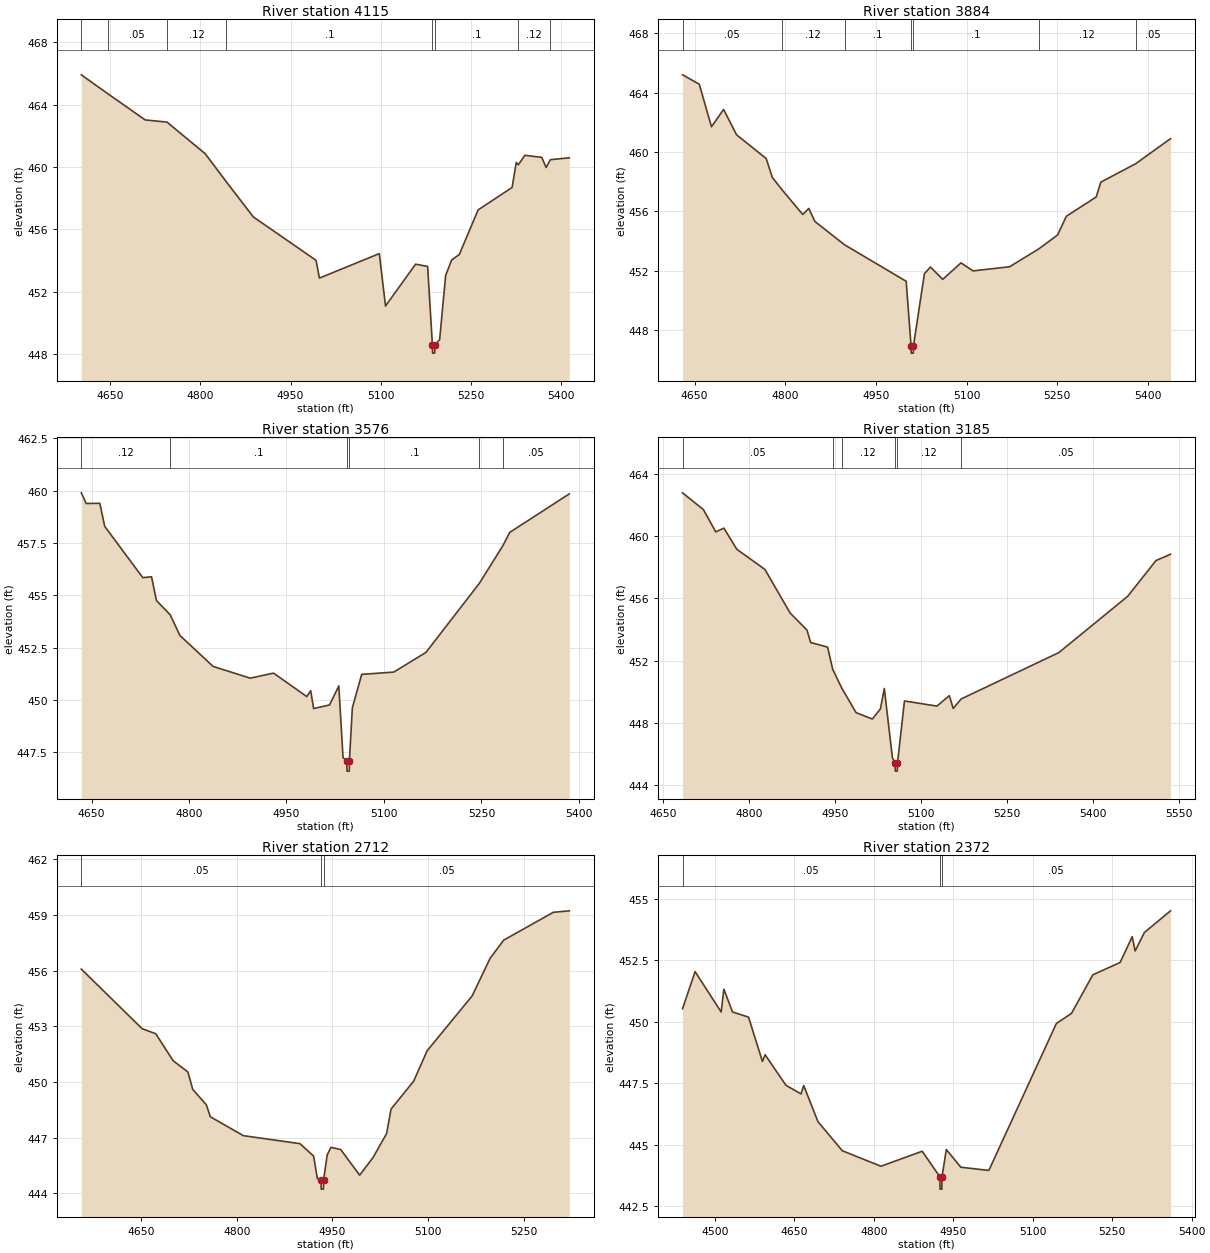
Type RM Length L Ch R = 1,4115,231,231,231
BEGIN DESCRIPTION:
Lacy 017 3252
END DESCRIPTION:
XS GIS Cut Line= 4
      2755222.32      6877280.67      2754831.65      6877277.67
      2754593.28      6877274.05      2754460.52      6877400.17
#Sta/Elev= 30
  4601.8  465.91  4645.5  464.71  4708.1  463.02  4744.4  462.88  4808.1  460.85
  4843.4  459.04  4888.1  456.80  4992.5  454.02  4998.1  452.88  5097.8  454.45
  5108.1  451.09  5158.1  453.77  5178.2  453.63  5186.2  448.57  5186.4  448.07
  5189.9  448.07  5190.2  448.57  5198.2  448.94  5208.2  453.05  5218.2  454.04
  5230.9  454.39  5262.2  457.25  5318.8  458.69  5325.7  460.29  5329.2  460.14
  5339.9  460.75  5368.2  460.62  5375.4  459.97  5382.5  460.47  5414.0  460.59
#Mann=8,-1,0
  4601.8    0.12       0  4645.5    0.05       0  4744.4    0.12       0
  4843.4     0.1       0  5186.2    0.07       0  5190.2     0.1       0
  5329.2    0.12       0  5382.5    0.05       0
Bank Sta=5186.2,5190.2
Exp/Cntr=0.3,0.1

Type RM Length L Ch R = 1,3884,308,308,308
BEGIN DESCRIPTION:
Lacy 017 3251
END DESCRIPTION:
XS GIS Cut Line= 3
      2755073.52      6877136.34      2754495.61      6877066.02
      2754351.98      6877240.04
#Sta/Elev= 30
  4629.9  465.20  4657.6  464.57  4677.8  461.70  4697.9  462.87  4719.3  461.16
  4768.4  459.56  4778.5  458.29  4794.5  457.46  4828.9  455.79  4838.9  456.20
  4849.0  455.32  4898.1  453.75  5000.1  451.29  5008.2  446.95  5008.5  446.45
  5012.0  446.45  5012.2  446.95  5030.3  451.80  5040.4  452.25  5060.6  451.42
  5090.8  452.53  5110.9  451.99  5171.4  452.27  5219.9  453.48  5250.8  454.41
  5265.2  455.67  5314.7  456.97  5322.3  457.97  5380.0  459.21  5437.7  460.90
#Mann=7,-1,0
  4629.9    0.05       0  4794.5    0.12       0  4898.1     0.1       0
  5008.2    0.07       0  5012.2     0.1       0  5219.9    0.12       0
  5380.0    0.05       0
Bank Sta=5008.2,5012.2
Exp/Cntr=0.3,0.1

Type RM Length L Ch R = 1,3576,391,391,391
BEGIN DESCRIPTION:
Lacy 017 61
END DESCRIPTION:
XS GIS Cut Line= 3
      2754875.96      6876661.03      2754576.00      6876861.00
      2754326.01      6877160.98
#Sta/Elev= 30
  4634.3  459.90  4641.8  459.39  4662.8  459.40  4670.3  458.30  4728.9  455.85
  4742.4  455.89  4749.9  454.76  4771.2  454.07  4786.0  453.09  4837.1  451.61
  4894.2  451.05  4930.2  451.29  4981.3  450.17  4987.3  450.45  4991.8  449.60
  5016.3  449.77  5030.6  450.68  5037.1  447.25  5042.9  447.11  5043.2  446.61
  5046.7  446.61  5046.9  447.11  5051.4  449.63  5065.8  451.23  5115.2  451.34
  5164.7  452.28  5246.9  455.58  5283.2  457.38  5293.6  458.01  5385.3  459.85
#Mann=6,-1,0
  4634.3    0.12       0  4771.2     0.1       0  5042.9    0.07       0
  5046.9     0.1       0  5246.9    0.12       0  5283.2    0.05       0
Bank Sta=5042.9,5046.9
Exp/Cntr=0.3,0.1

Type RM Length L Ch R = 1,3185,473,473,473
BEGIN DESCRIPTION:
Lacy 017 3250
END DESCRIPTION:
XS GIS Cut Line= 3
      2754713.38      6876406.74      2754455.83      6876588.81
      2754094.04      6876984.83
#Sta/Elev= 30
  4683.5  462.78  4720.0  461.70  4741.5  460.27  4755.7  460.51  4778.3  459.15
  4827.2  457.86  4871.4  455.05  4900.7  453.96  4907.1  453.16  4936.7  452.86
  4945.7  451.43  4961.0  450.26  4986.4  448.65  5014.8  448.24  5028.9  448.89
  5035.7  450.20  5049.9  445.74  5054.7  445.39  5054.9  444.89  5058.4  444.89
  5058.7  445.39  5070.9  449.40  5127.6  449.07  5149.2  449.74  5156.0  448.92
  5169.9  449.53  5340.4  452.51  5460.6  456.13  5510.0  458.43  5535.3  458.83
#Mann=6,-1,0
  4683.5    0.05       0  4945.7     0.1       0  4961.0    0.12       0
  5054.7    0.07       0  5058.7    0.12       0  5169.9    0.05       0
Bank Sta=5054.7,5058.7
Exp/Cntr=0.3,0.1

Type RM Length L Ch R = 1,2712,340,340,340
BEGIN DESCRIPTION:
Lacy 017 3249
END DESCRIPTION:
XS GIS Cut Line= 3
      2754478.65      6876253.82      2754100.65      6876484.94
      2753874.90      6876715.46
#Sta/Elev= 30
  4555.9  456.08  4651.4  452.87  4672.7  452.60  4699.9  451.15  4723.1  450.54
  4730.8  449.60  4752.1  448.77  4758.3  448.13  4810.1  447.11  4898.9  446.68
  4920.4  446.01  4926.3  444.80  4932.1  444.73  4932.3  444.23  4935.8  444.23
  4936.1  444.73  4941.7  446.07  4947.6  446.48  4963.0  446.36  4992.7  444.98
  5013.6  445.93  5034.9  447.22  5041.9  448.54  5077.3  450.04  5098.5  451.68
  5169.2  454.64  5197.5  456.67  5218.6  457.64  5296.5  459.14  5321.6  459.22
#Mann=3,-1,0
  4555.9    0.05       0  4932.1    0.04       0  4936.1    0.05       0
Bank Sta=4932.1,4936.1
Exp/Cntr=0.3,0.1

Type RM Length L Ch R = 1,2372,199,199,199
BEGIN DESCRIPTION:
Lacy 017 3248
END DESCRIPTION:
XS GIS Cut Line= 3
      2754429.46      6876125.78      2753905.32      6876196.19
      2753741.12      6876552.43
#Sta/Elev= 30
  4439.0  450.52  4462.7  452.03  4511.9  450.39  4517.0  451.32  4533.3  450.39
  4563.6  450.18  4589.8  448.38  4594.9  448.65  4634.2  447.41  4662.7  447.06
  4667.7  447.40  4694.7  445.93  4740.6  444.75  4813.5  444.12  4891.4  444.73
  4924.8  443.69  4925.0  443.19  4928.5  443.19  4928.8  443.69  4936.9  444.80
  4964.3  444.08  5017.2  443.95  5144.6  449.92  5173.1  450.33  5213.5  451.90
  5264.9  452.40  5287.8  453.45  5293.3  452.87  5310.8  453.62  5360.1  454.50
#Mann=3,-1,0
  4439.0    0.05       0  4924.8    0.04       0  4928.8    0.05       0
Bank Sta=4924.8,4928.8
Exp/Cntr=0.3,0.1

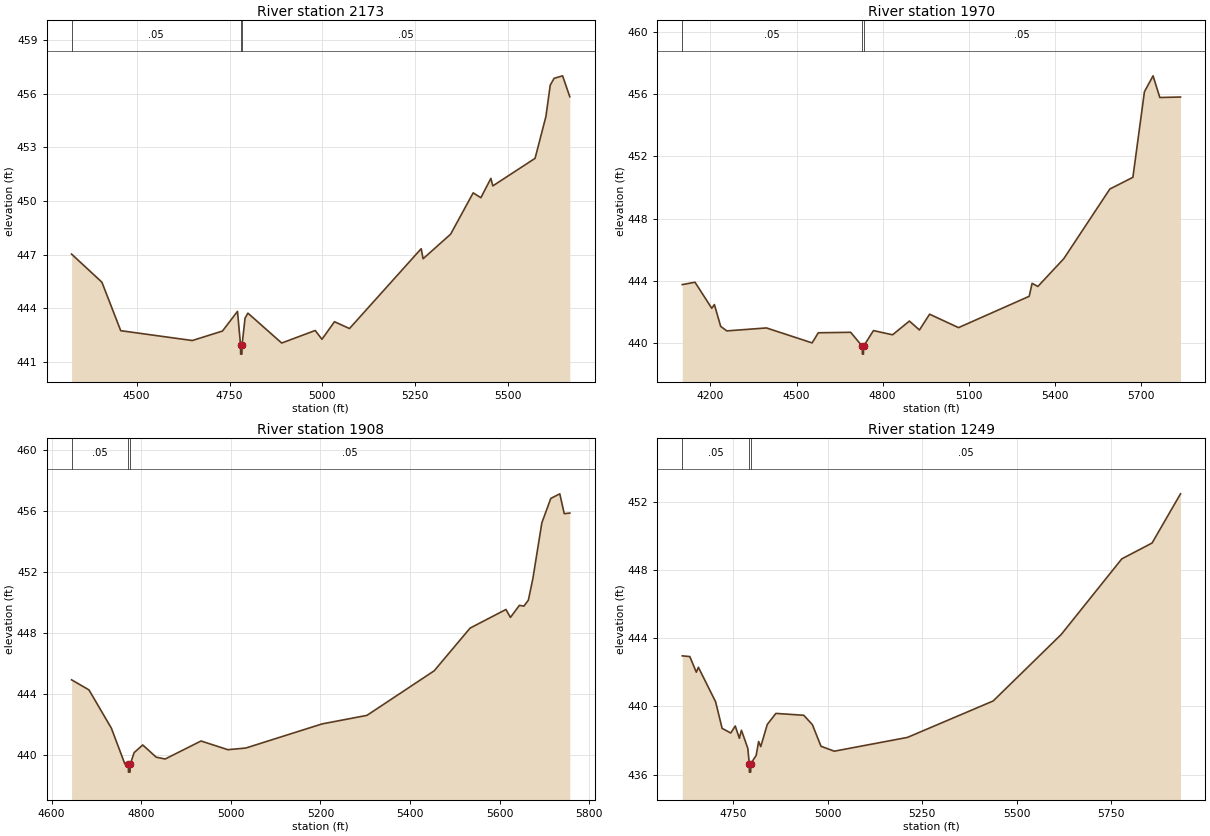
Type RM Length L Ch R = 1,2173,203,203,203
BEGIN DESCRIPTION:
Lacy 017 3247
END DESCRIPTION:
XS GIS Cut Line= 3
      2754396.48      6876034.93      2753841.05      6875941.78
      2753635.03      6876691.82
#Sta/Elev= 30
  4324.9  447.03  4406.5  445.46  4457.2  442.75  4649.9  442.20  4731.0  442.73
  4771.5  443.83  4779.7  441.94  4779.9  441.44  4783.4  441.44  4783.7  441.94
  4791.8  443.45  4799.5  443.73  4890.4  442.06  4980.6  442.76  4998.8  442.27
  5032.5  443.25  5072.9  442.87  5265.8  447.33  5271.0  446.77  5345.0  448.14
  5405.8  450.45  5426.5  450.18  5453.5  451.26  5458.7  450.84  5572.4  452.38
  5601.6  454.72  5613.2  456.47  5623.6  456.85  5646.4  456.99  5665.9  455.82
#Mann=3,-1,0
  4324.9    0.05       0  4779.7    0.04       0  4783.7    0.05       0
Bank Sta=4779.7,4783.7
Exp/Cntr=0.3,0.1

Type RM Length L Ch R = 1,1970,62,62,62
BEGIN DESCRIPTION:
Lacy 017 3429
END DESCRIPTION:
XS GIS Cut Line= 4
      2754332.04      6875857.18      2753886.06      6875589.45
      2753686.00      6875917.10      2753614.69      6876746.26
#Sta/Elev= 30
  4101.7  443.77  4146.2  443.92  4204.5  442.25  4213.7  442.49  4235.6  441.09
  4257.0  440.80  4395.0  440.99  4554.3  440.03  4575.7  440.68  4688.6  440.71
  4729.3  439.81  4729.5  439.31  4733.0  439.31  4733.3  439.81  4768.0  440.82
  4834.6  440.55  4893.2  441.43  4928.3  440.86  4963.6  441.87  5064.5  441.01
  5310.8  443.02  5320.8  443.85  5340.9  443.65  5431.2  445.43  5591.8  449.90
  5672.1  450.65  5712.3  456.14  5742.4  457.16  5765.9  455.77  5838.0  455.80
#Mann=3,-1,0
  4101.7    0.05       0  4729.3    0.04       0  4733.3    0.05       0
Bank Sta=4729.3,4733.3
Exp/Cntr=0.3,0.1

Type RM Length L Ch R = 1,1908,659,659,659
BEGIN DESCRIPTION:
Lacy 017 3246
END DESCRIPTION:
XS GIS Cut Line= 3
      2753633.31      6875552.24      2753627.26      6875907.48
      2753603.43      6876663.41
#Sta/Elev= 30
  4644.7  444.96  4683.5  444.30  4733.5  441.79  4763.5  439.45  4771.5  439.41
  4771.7  438.91  4775.2  438.91  4775.5  439.41  4784.3  440.19  4803.5  440.69
  4833.5  439.89  4853.5  439.77  4933.5  440.95  4993.5  440.38  5033.5  440.49
  5203.6  442.07  5303.7  442.63  5453.7  445.55  5533.8  448.35  5613.8  449.57
  5623.8  449.05  5643.8  449.84  5653.8  449.79  5663.8  450.18  5673.9  451.60
  5693.9  455.25  5713.9  456.85  5733.9  457.15  5743.9  455.85  5756.3  455.89
#Mann=3,-1,0
  4644.7    0.05       0  4771.5    0.04       0  4775.5    0.05       0
Bank Sta=4771.5,4775.5
Exp/Cntr=0.3,0.1

Type RM Length L Ch R = 1,1249,0,0,0
BEGIN DESCRIPTION:
Lacy 017 3430
END DESCRIPTION:
XS GIS Cut Line= 3
      2753337.74      6875314.19      2753180.23      6875647.90
      2753225.56      6876596.10
#Sta/Elev= 30
  4614.9  442.97  4634.9  442.93  4652.1  442.01  4657.6  442.30  4703.2  440.27
  4720.4  438.71  4743.2  438.44  4755.1  438.85  4766.0  438.13  4771.5  438.60
  4788.3  437.54  4792.3  436.64  4792.5  436.14  4796.0  436.14  4796.3  436.64
  4810.4  437.12  4817.0  437.94  4822.6  437.64  4839.8  438.94  4862.6  439.59
  4936.4  439.48  4959.2  438.93  4982.0  437.66  5017.1  437.37  5210.8  438.18
  5437.5  440.32  5617.7  444.23  5777.9  448.67  5858.0  449.60  5933.2  452.49
#Mann=3,-1,0
  4614.9    0.05       0  4792.3    0.04       0  4796.3    0.05       0
Bank Sta=4792.3,4796.3
Exp/Cntr=0.3,0.1

Chan Stop Cuts=-1