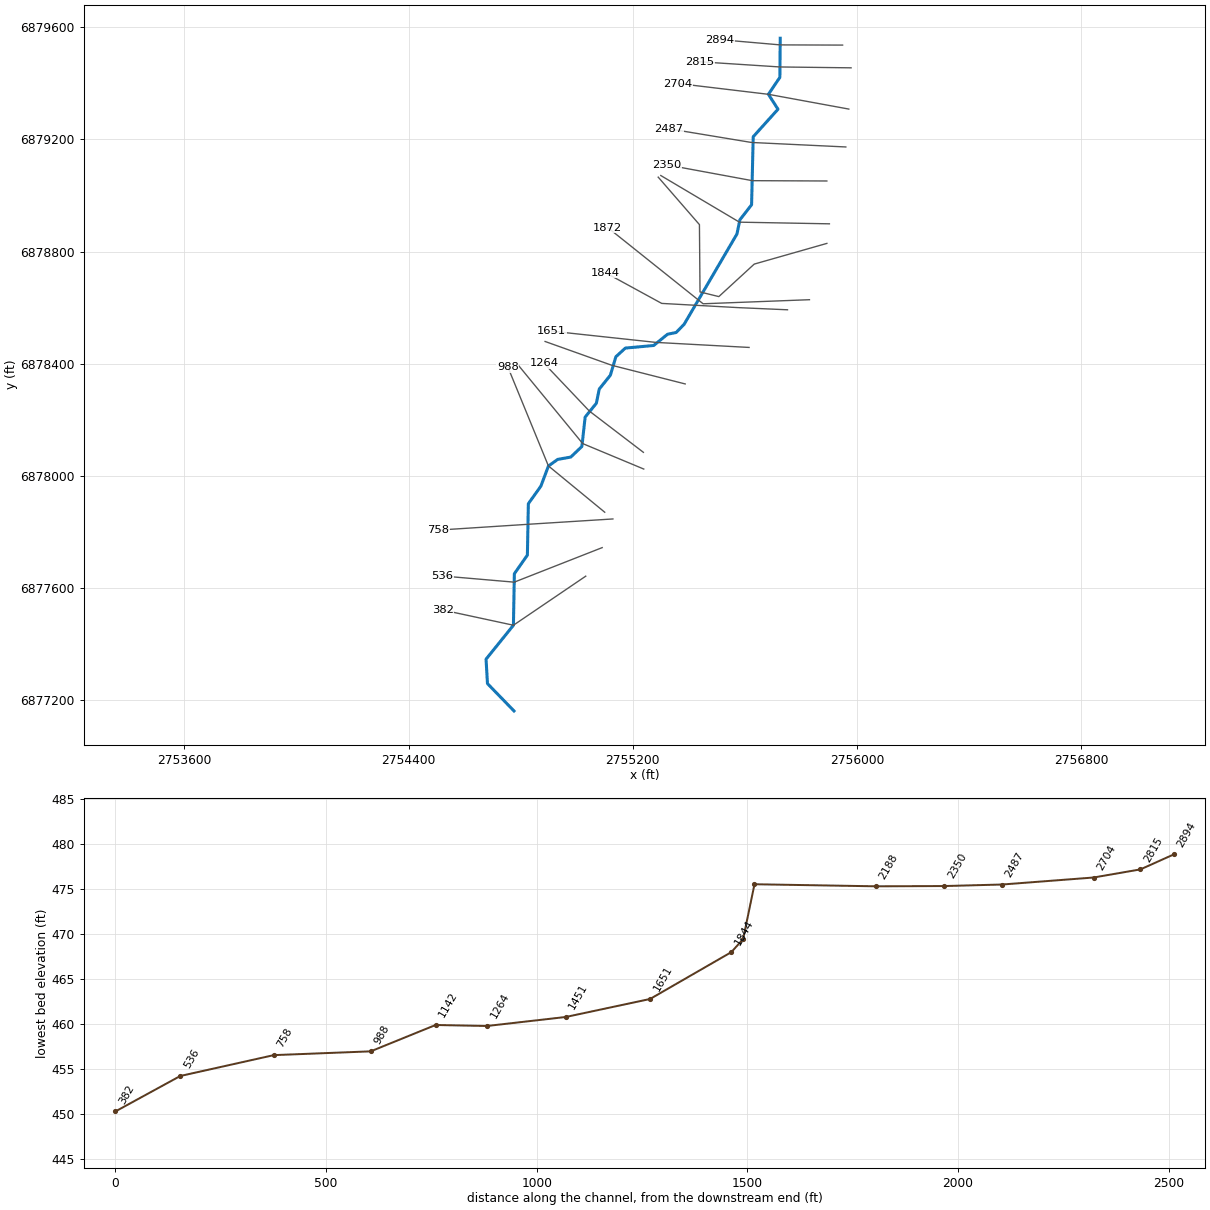
--- Lacy 018.prj (project) ---

Proj Title=Lacy 018 Base Level Engineering
Current Plan=p01
Default Exp/Contr=0.3,0.1
English Units
Geom File=g01
Flow File=f01
Plan File=p01
BEGIN DESCRIPTION:
Lacy 018
END DESCRIPTION:

--- Lacy 018.p01 (plan) ---

Plan Title=Multiple Run
Short Identifier=Multiple
Geom File=g01
Flow File=f01
Subcritical Flow
K Sum by GR= 0
Std Step Tol= 0.01
Critical Tol= 0.01
Num of Std Step Trials= 20
Max Error Tol= 0.3
Flow Tol Ratio= 0.001
Split Flow NTrial= 30
Split Flow Tol= 0.02
Split Flow Ratio= 0.02
Log Output Level= 0
Friction Slope Method= 1
Unsteady Friction Slope Method= 2
Unsteady Bridges Friction Slope Method= 1
Parabolic Critical Depth
Global Vel Dist=  1 , 1 , 1
Global Log Level= 0
CheckData=True
Encroach Param= -1, 0, 0, 0
BEGIN DESCRIPTION:
Multiple Run
END DESCRIPTION:

--- Lacy 018.f01 (steady flow) ---

Flow Title=Multiple
Number of Profiles=7
Profile Names=10-year,25-year,50-year,1pct_min,100-year,1pct_plu,500-year
River Rch & RM= Lacy 018,Reach-1,2894
     180     224     258     149     296     591     390
Boundary for River Rch & Prof#=Lacy 018,Reach-1,1
Up Type=0
Dn Type=3
Dn Slope=0.005
Boundary for River Rch & Prof#=Lacy 018,Reach-1,2
Up Type=0
Dn Type=3
Dn Slope=0.005
Boundary for River Rch & Prof#=Lacy 018,Reach-1,3
Up Type=0
Dn Type=3
Dn Slope=0.005
Boundary for River Rch & Prof#=Lacy 018,Reach-1,4
Up Type=0
Dn Type=3
Dn Slope=0.005
Boundary for River Rch & Prof#=Lacy 018,Reach-1,5
Up Type=0
Dn Type=3
Dn Slope=0.005
Boundary for River Rch & Prof#=Lacy 018,Reach-1,6
Up Type=0
Dn Type=3
Dn Slope=0.005
Boundary for River Rch & Prof#=Lacy 018,Reach-1,7
Up Type=0
Dn Type=3
Dn Slope=0.005

--- Lacy 018.g01 (geometry) ---

Geom Title=Existing Conditions

River Reach=Lacy 018,Reach-1
Reach XY= 30
      2755726.00      6879561.00      2755724.67      6879421.41
      2755683.80      6879360.90      2755717.99      6879307.67
      2755629.56      6879209.54      2755623.76      6878966.93
      2755582.09      6878913.17      2755571.57      6878862.63
      2755383.10      6878540.50      2755354.79      6878511.34
      2755323.83      6878504.91      2755274.41      6878464.83
      2755173.32      6878455.58      2755139.45      6878424.63
      2755119.88      6878358.84      2755080.16      6878309.28
      2755069.88      6878258.82      2755029.83      6878209.41
      2755018.25      6878104.55      2754978.55      6878066.75
      2754931.91      6878058.52      2754898.86      6878034.84
      2754871.77      6877962.78      2754827.20      6877900.50
      2754823.74      6877716.94      2754777.22      6877650.49
      2754773.93      6877466.86      2754676.24      6877345.78
      2754681.33      6877258.55      2754776.00      6877161.00

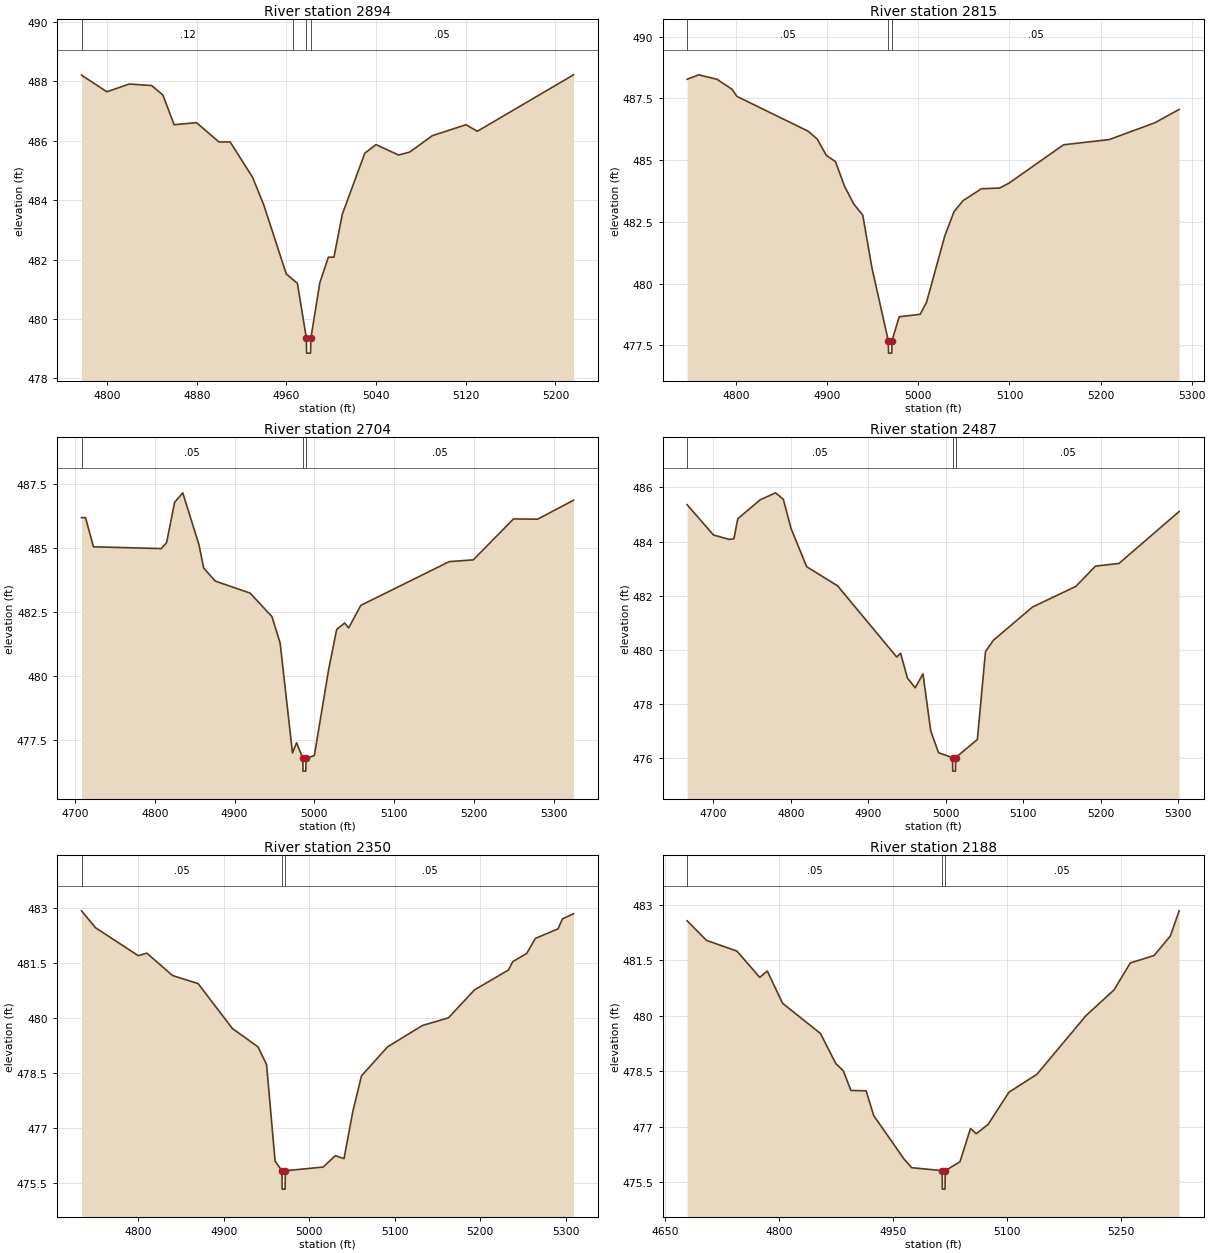
Type RM Length L Ch R = 1,2894,79,79,79
BEGIN DESCRIPTION:
Lacy 018 3274
END DESCRIPTION:
XS GIS Cut Line= 3
      2755948.57      6879536.47      2755725.77      6879537.21
      2755510.49      6879555.96
#Sta/Elev= 30
  4777.2  488.21  4799.8  487.65  4819.8  487.91  4839.8  487.86  4849.8  487.54
  4859.8  486.54  4879.8  486.61  4899.8  485.96  4909.8  485.96  4929.8  484.77
  4939.8  483.84  4959.8  481.52  4966.3  481.31  4969.8  481.20  4977.8  479.35
  4978.0  478.85  4981.5  478.85  4981.8  479.35  4989.8  481.22  4997.4  482.08
  5002.4  482.08  5009.8  483.52  5029.9  485.58  5039.9  485.87  5060.0  485.52
  5070.0  485.62  5090.1  486.17  5120.2  486.54  5130.3  486.32  5216.1  488.22
#Mann=4,-1,0
  4777.2    0.12       0  4966.3    0.05       0  4977.8    0.04       0
  4981.8    0.05       0
Bank Sta=4977.8,4981.8
Exp/Cntr=0.3,0.1

Type RM Length L Ch R = 1,2815,111,111,111
BEGIN DESCRIPTION:
Lacy 018 3273
END DESCRIPTION:
XS GIS Cut Line= 3
      2755978.80      6879455.38      2755725.02      6879458.46
      2755439.32      6879476.97
#Sta/Elev= 30
  4746.2  488.27  4759.0  488.45  4779.0  488.27  4795.7  487.86  4800.7  487.58
  4879.0  486.17  4889.0  485.85  4899.0  485.19  4909.0  484.94  4919.0  483.94
  4929.0  483.23  4939.0  482.77  4949.0  480.65  4967.0  477.69  4967.3  477.19
  4970.8  477.19  4971.0  477.69  4979.0  478.66  5002.0  478.76  5009.0  479.25
  5029.1  481.94  5039.1  482.91  5049.1  483.36  5069.2  483.84  5089.2  483.87
  5099.2  484.06  5159.4  485.62  5209.5  485.83  5259.6  486.51  5286.3  487.05
#Mann=3,-1,0
  4746.2    0.05       0  4967.0    0.04       0  4971.0    0.05       0
Bank Sta=4967,4971
Exp/Cntr=0.3,0.1

Type RM Length L Ch R = 1,2704,217,217,217
BEGIN DESCRIPTION:
Lacy 018 3275
END DESCRIPTION:
XS GIS Cut Line= 3
      2755970.80      6879308.20      2755683.80      6879360.90
      2755361.30      6879399.45
#Sta/Elev= 30
  4708.2  486.20  4713.2  486.20  4723.2  485.06  4808.2  484.99  4814.8  485.22
  4824.9  486.80  4835.1  487.17  4855.4  485.14  4861.3  484.23  4875.8  483.72
  4919.5  483.25  4946.9  482.33  4957.1  481.30  4972.6  477.00  4977.7  477.40
  4985.6  476.79  4985.8  476.29  4989.3  476.29  4989.6  476.79  5000.0  476.90
  5017.9  480.26  5028.0  481.83  5038.0  482.08  5043.0  481.89  5058.2  482.77
  5169.0  484.48  5199.2  484.55  5249.6  486.15  5279.8  486.14  5324.8  486.88
#Mann=3,-1,0
  4708.2    0.05       0  4985.6    0.04       0  4989.6    0.05       0
Bank Sta=4985.6,4989.6
Exp/Cntr=0.3,0.1

Type RM Length L Ch R = 1,2487,137,137,137
BEGIN DESCRIPTION:
Lacy 018 3272
END DESCRIPTION:
XS GIS Cut Line= 3
      2755959.99      6879173.07      2755623.19      6879189.12
      2755329.47      6879237.77
#Sta/Elev= 30
  4666.3  485.36  4700.3  484.24  4720.3  484.08  4726.6  484.10  4731.6  484.84
  4760.4  485.54  4780.4  485.80  4790.4  485.56  4800.4  484.48  4820.5  483.07
  4860.5  482.36  4936.7  479.73  4941.7  479.87  4950.6  478.95  4960.6  478.59
  4970.6  479.11  4980.6  477.00  4990.7  476.19  5008.8  476.01  5009.0  475.51
  5012.5  475.51  5012.8  476.01  5040.8  476.68  5051.3  479.93  5061.5  480.35
  5112.1  481.58  5167.9  482.34  5193.2  483.09  5223.6  483.19  5301.2  485.11
#Mann=3,-1,0
  4666.3    0.05       0  5008.8    0.04       0  5012.8    0.05       0
Bank Sta=5008.8,5012.8
Exp/Cntr=0.3,0.1

Type RM Length L Ch R = 1,2350,162,162,162
BEGIN DESCRIPTION:
Lacy 018 3271
END DESCRIPTION:
XS GIS Cut Line= 3
      2755892.36      6879051.71      2755626.51      6879052.82
      2755322.12      6879109.07
#Sta/Elev= 30
  4733.8  482.91  4750.2  482.45  4800.2  481.69  4810.2  481.76  4840.2  481.15
  4870.2  480.93  4910.2  479.71  4940.2  479.21  4950.2  478.73  4960.2  476.10
  4968.2  475.84  4968.4  475.34  4971.9  475.34  4972.2  475.84  5016.3  475.94
  5030.7  476.25  5040.8  476.17  5051.0  477.44  5061.2  478.42  5091.7  479.21
  5132.4  479.79  5162.9  480.00  5193.4  480.76  5233.1  481.30  5238.2  481.53
  5254.4  481.75  5264.6  482.16  5291.1  482.42  5296.2  482.69  5309.2  482.83
#Mann=3,-1,0
  4733.8    0.05       0  4968.2    0.04       0  4972.2    0.05       0
Bank Sta=4968.2,4972.2
Exp/Cntr=0.3,0.1

Type RM Length L Ch R = 1,2188,289,289,289
BEGIN DESCRIPTION:
Lacy 018 3454
END DESCRIPTION:
XS GIS Cut Line= 3
      2755901.48      6878898.87      2755580.46      6878904.78
      2755299.76      6879071.18
#Sta/Elev= 30
  4678.8  482.57  4704.3  482.04  4744.3  481.75  4774.3  481.04  4784.3  481.21
  4804.3  480.34  4854.3  479.52  4874.3  478.71  4884.3  478.51  4894.3  477.98
  4914.3  477.97  4924.3  477.30  4964.3  476.12  4974.3  475.89  5014.4  475.81
  5014.6  475.31  5018.1  475.31  5018.4  475.81  5037.8  476.05  5051.6  476.95
  5059.2  476.81  5074.8  477.06  5102.1  477.93  5139.2  478.42  5203.4  480.00
  5240.5  480.70  5261.9  481.43  5293.2  481.63  5314.6  482.16  5326.2  482.84
#Mann=3,-1,0
  4678.8    0.05       0  5014.4    0.04       0  5018.4    0.05       0
Bank Sta=5014.4,5018.4
Exp/Cntr=0.3,0.1

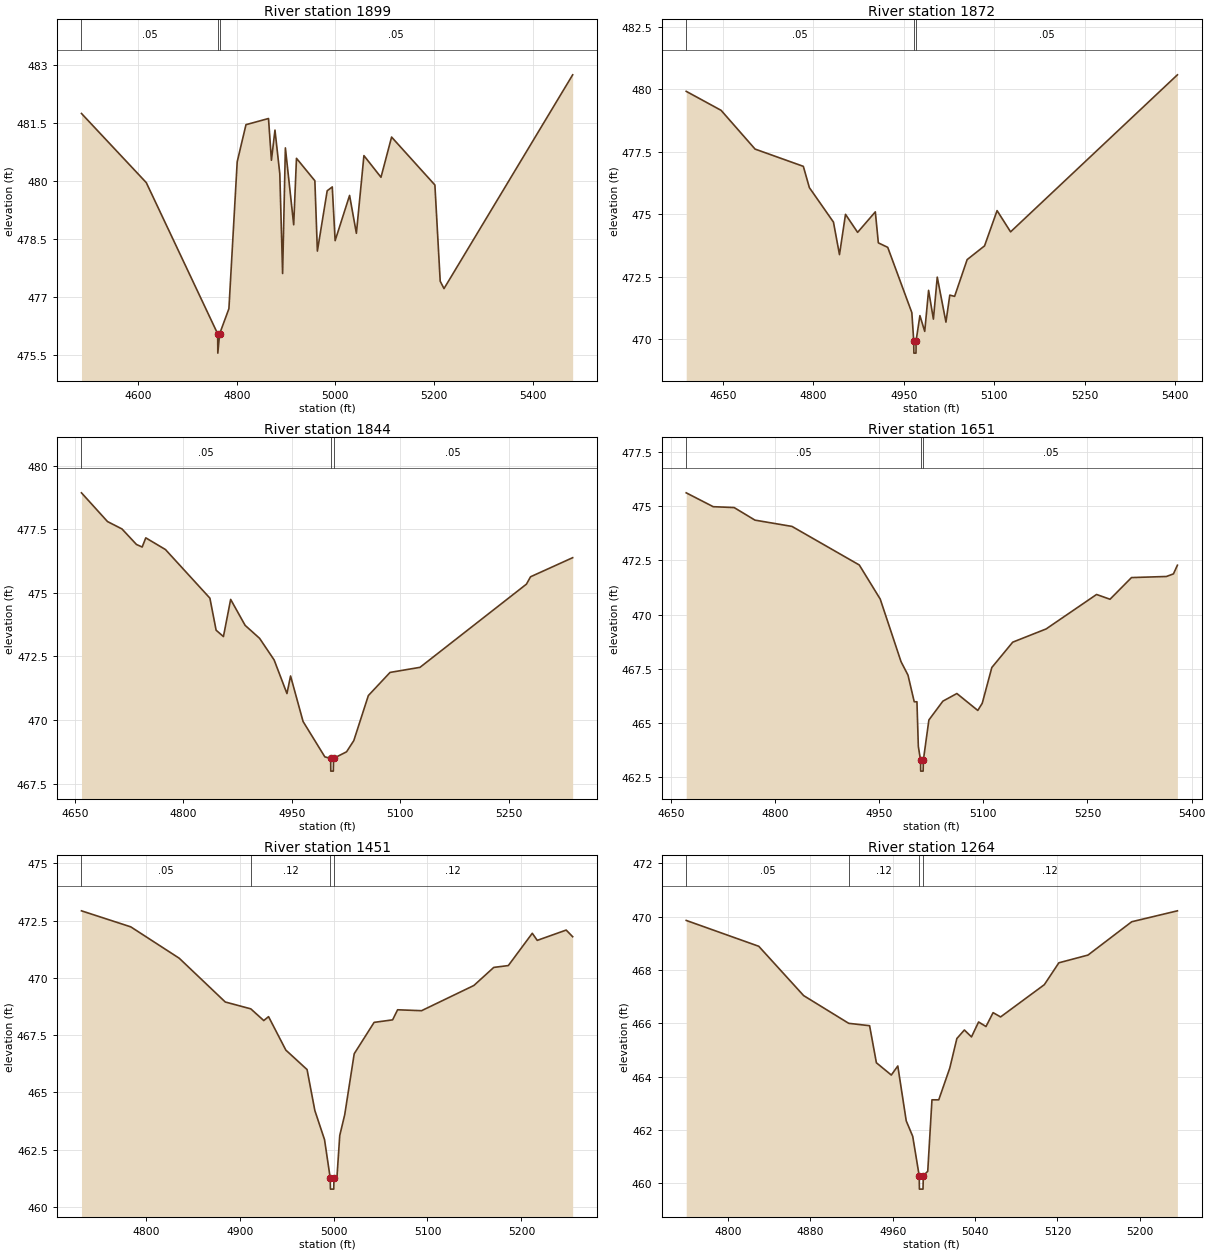
Type RM Length L Ch R = 1,1899,27,27,27
BEGIN DESCRIPTION:
Lacy 018 3268
END DESCRIPTION:
XS GIS Cut Line= 6
      2755892.44      6878829.03      2755633.25      6878755.22
      2755506.88      6878639.26      2755439.71      6878655.81
      2755437.67      6878896.03      2755290.52      6879065.43
#Sta/Elev= 30
  4485.1  481.74  4616.6  479.95  4761.3  476.04  4761.6  475.54  4765.3  476.04
  4784.1  476.69  4800.9  480.49  4818.7  481.45  4864.4  481.61  4870.3  480.53
  4877.5  481.31  4887.3  480.18  4893.0  477.60  4898.6  480.85  4915.5  478.86
  4921.1  480.58  4958.4  480.00  4963.5  478.18  4983.4  479.74  4993.7  479.84
  4999.5  478.45  5028.8  479.62  5042.6  478.64  5057.9  480.65  5092.5  480.09
  5114.0  481.13  5201.8  479.89  5212.6  477.40  5220.3  477.21  5481.2  482.74
#Mann=3,-1,0
  4485.1    0.05       0  4761.3    0.04       0  4765.3    0.05       0
Bank Sta=4761.3,4765.3
Exp/Cntr=0.3,0.1

Type RM Length L Ch R = 1,1872,28,28,28
BEGIN DESCRIPTION:
Lacy 018 3455
END DESCRIPTION:
XS GIS Cut Line= 3
      2755830.25      6878628.15      2755450.79      6878613.66
      2755110.47      6878885.50
#Sta/Elev= 30
  4588.9  479.91  4646.8  479.15  4703.2  477.60  4783.3  476.91  4793.3  476.06
  4833.3  474.68  4843.3  473.38  4853.3  474.99  4873.4  474.27  4902.8  475.09
  4907.8  473.85  4923.4  473.67  4963.4  471.06  4966.5  469.94  4966.8  469.44
  4970.3  469.44  4970.5  469.94  4976.8  470.94  4984.8  470.31  4991.2  471.95
  4999.2  470.80  5005.6  472.48  5020.0  470.68  5026.4  471.76  5034.4  471.71
  5055.2  473.18  5084.1  473.73  5104.9  475.14  5127.3  474.29  5404.2  480.57
#Mann=3,-1,0
  4588.9    0.05       0  4966.5    0.04       0  4970.5    0.05       0
Bank Sta=4966.5,4970.5
Exp/Cntr=0.3,0.1

Type RM Length L Ch R = 1,1844,193,193,193
BEGIN DESCRIPTION:
Lacy 018 3267
END DESCRIPTION:
XS GIS Cut Line= 4
      2755751.95      6878592.19      2755574.60      6878599.99
      2755303.08      6878614.96      2755101.67      6878724.86
#Sta/Elev= 30
  4659.3  478.93  4695.3  477.80  4715.3  477.51  4735.3  476.90  4743.2  476.80
  4748.2  477.16  4775.4  476.70  4836.8  474.79  4845.4  473.53  4855.5  473.28
  4865.5  474.74  4885.5  473.72  4905.5  473.21  4925.6  472.36  4943.3  471.04
  4948.3  471.73  4965.6  469.94  4995.7  468.55  5003.7  468.49  5003.9  467.99
  5007.4  467.99  5007.7  468.49  5025.7  468.75  5035.7  469.19  5055.8  470.96
  5085.8  471.87  5127.2  472.07  5274.3  475.34  5280.0  475.63  5338.2  476.38
#Mann=3,-1,0
  4659.3    0.05       0  5003.7    0.04       0  5007.7    0.05       0
Bank Sta=5003.7,5007.7
Exp/Cntr=0.3,0.1

Type RM Length L Ch R = 1,1651,200,200,200
BEGIN DESCRIPTION:
Lacy 018 3264
END DESCRIPTION:
XS GIS Cut Line= 3
      2755614.85      6878457.88      2755283.13      6878475.80
      2754910.29      6878515.93
#Sta/Elev= 30
  4672.3  475.62  4711.2  474.98  4741.3  474.94  4771.3  474.36  4824.6  474.07
  4921.5  472.29  4951.6  470.72  4981.6  467.83  4991.6  467.21  5000.6  465.98
  5004.5  465.98  5006.5  463.92  5009.7  463.28  5009.9  462.78  5013.4  462.78
  5013.7  463.28  5021.7  465.14  5041.9  466.01  5062.0  466.36  5092.1  465.58
  5098.5  465.91  5112.3  467.56  5142.4  468.73  5190.5  469.34  5263.1  470.93
  5282.5  470.71  5313.4  471.71  5363.7  471.76  5373.8  471.88  5379.5  472.28
#Mann=3,-1,0
  4672.3    0.05       0  5009.7    0.05       0  5013.7    0.05       0
Bank Sta=5009.7,5013.7
Exp/Cntr=0.3,0.1

Type RM Length L Ch R = 1,1451,187,187,187
BEGIN DESCRIPTION:
Lacy 018 3265
END DESCRIPTION:
XS GIS Cut Line= 3
      2755386.87      6878327.65      2755125.54      6878394.03
      2754886.89      6878479.14
#Sta/Elev= 30
  4731.6  472.93  4784.1  472.23  4835.7  470.86  4884.7  468.95  4911.9  468.65
  4925.7  468.14  4930.8  468.31  4949.2  466.85  4971.8  466.00  4980.1  464.21
  4990.4  462.94  4996.4  461.28  4996.7  460.78  5000.2  460.78  5000.4  461.28
  5003.6  461.28  5006.6  463.12  5011.9  464.03  5022.0  466.69  5043.2  468.06
  5062.9  468.17  5068.2  468.61  5093.7  468.57  5149.4  469.67  5170.6  470.46
  5186.1  470.54  5211.6  471.95  5216.9  471.64  5247.7  472.09  5254.6  471.80
#Mann=4,-1,0
  4731.6    0.05       0  4911.9    0.12       0  4996.4    0.07       0
  5000.4    0.12       0
Bank Sta=4996.4,5000.4
Exp/Cntr=0.3,0.1

Type RM Length L Ch R = 1,1264,122,122,122
BEGIN DESCRIPTION:
Lacy 018 3263
END DESCRIPTION:
XS GIS Cut Line= 3
      2755237.66      6878083.71      2755044.75      6878231.01
      2754883.24      6878401.14
#Sta/Elev= 30
  4759.3  469.86  4829.8  468.89  4873.4  467.04  4917.2  466.00  4937.5  465.91
  4944.1  464.52  4958.6  464.06  4964.9  464.40  4973.1  462.34  4979.4  461.76
  4985.7  460.28  4985.9  459.78  4989.4  459.78  4989.7  460.28  4994.0  460.45
  4998.1  463.13  5004.7  463.13  5015.4  464.32  5022.3  465.43  5029.6  465.75
  5036.5  465.49  5043.4  466.05  5050.6  465.88  5057.5  466.40  5064.8  466.24
  5107.3  467.45  5121.4  468.27  5149.7  468.56  5192.2  469.81  5236.6  470.22
#Mann=4,-1,0
  4759.3    0.05       0  4917.2    0.12       0  4985.7    0.07       0
  4989.7    0.12       0
Bank Sta=4985.7,4989.7
Exp/Cntr=0.3,0.1

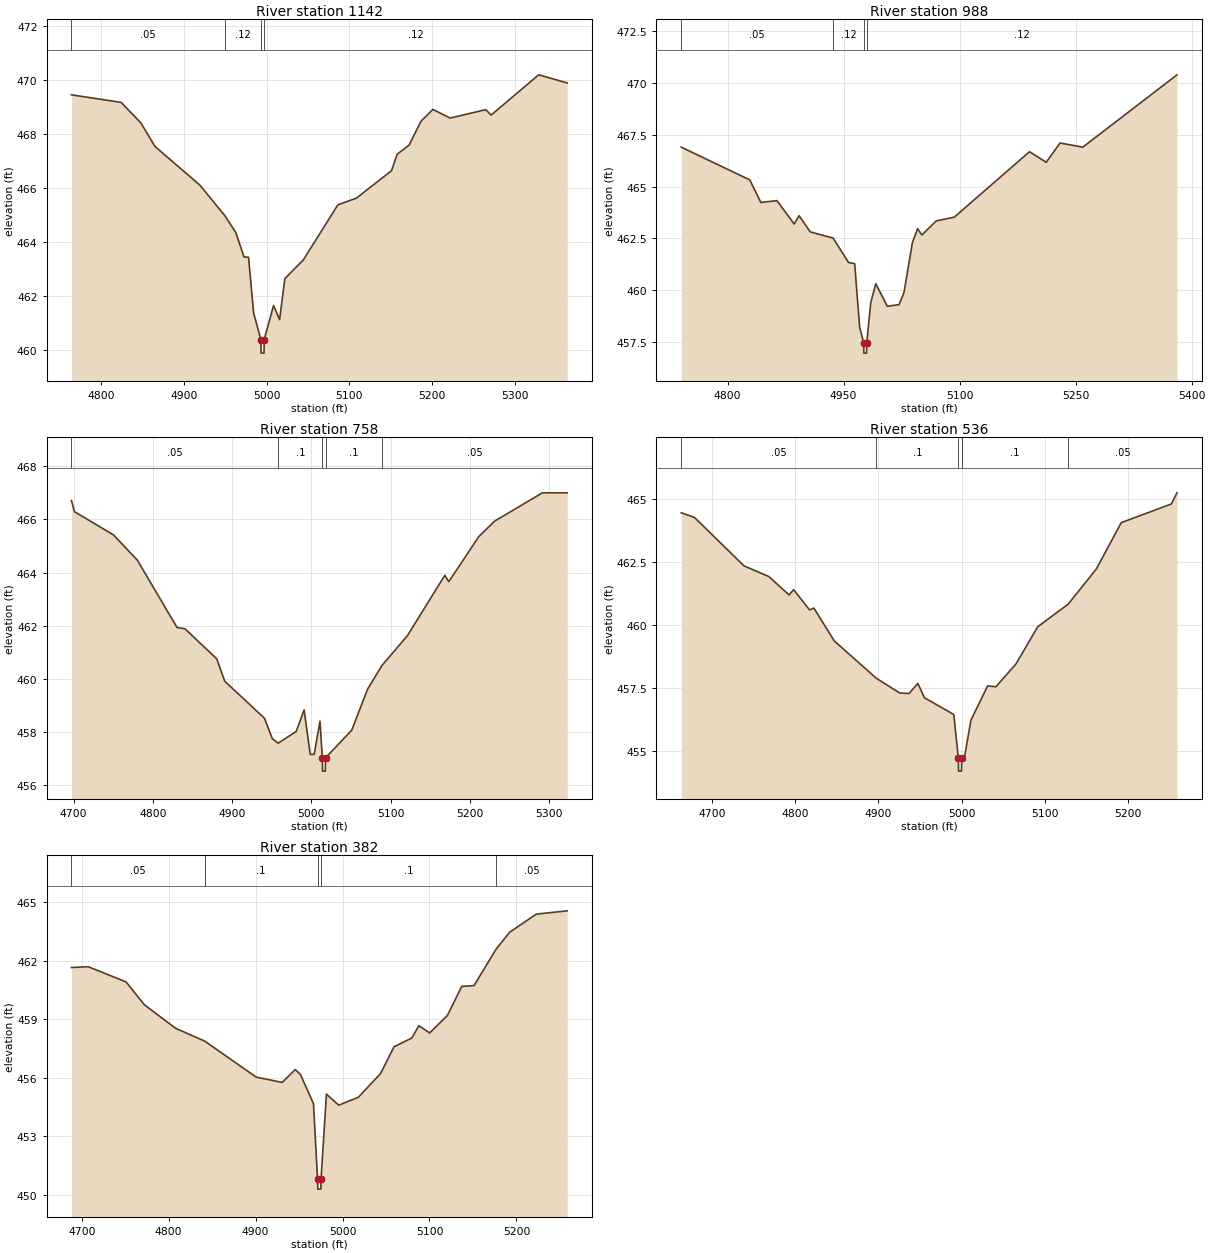
Type RM Length L Ch R = 1,1142,154,154,154
BEGIN DESCRIPTION:
Lacy 018 3266
END DESCRIPTION:
XS GIS Cut Line= 3
      2755239.04      6878024.04      2755021.16      6878114.84
      2754790.98      6878394.96
#Sta/Elev= 30
  4764.5  469.45  4824.5  469.17  4848.3  468.41  4865.3  467.54  4919.5  466.11
  4949.4  464.99  4962.8  464.36  4972.9  463.45  4978.3  463.44  4984.5  461.37
  4993.2  460.39  4993.5  459.89  4997.0  459.89  4997.2  460.39  5008.5  461.65
  5015.8  461.13  5022.2  462.65  5044.5  463.34  5086.2  465.38  5108.3  465.62
  5150.9  466.64  5157.8  467.25  5172.2  467.59  5186.5  468.47  5200.9  468.91
  5221.7  468.59  5264.7  468.90  5271.2  468.70  5328.6  470.19  5363.1  469.89
#Mann=4,-1,0
  4764.5    0.05       0  4949.4    0.12       0  4993.2    0.07       0
  4997.2    0.12       0
Bank Sta=4993.2,4997.2
Exp/Cntr=0.3,0.1

Type RM Length L Ch R = 1,988,230,230,230
BEGIN DESCRIPTION:
Lacy 018 3262
END DESCRIPTION:
XS GIS Cut Line= 3
      2755099.72      6877870.00      2754898.73      6878035.24
      2754754.26      6878387.47
#Sta/Elev= 30
  4740.2  466.90  4828.8  465.32  4843.1  464.23  4863.9  464.32  4886.2  463.19
  4892.6  463.59  4907.0  462.81  4936.6  462.51  4956.5  461.33  4964.4  461.28
  4970.8  458.22  4976.0  457.46  4976.3  456.96  4979.8  456.96  4980.0  457.46
  4985.2  459.40  4991.7  460.31  5006.6  459.22  5021.8  459.30  5028.2  459.89
  5039.0  462.29  5045.8  462.97  5051.2  462.66  5069.8  463.34  5093.1  463.52
  5190.4  466.68  5212.0  466.17  5229.9  467.10  5259.3  466.90  5381.1  470.39
#Mann=4,-1,0
  4740.2    0.05       0  4936.6    0.12       0  4976.0    0.07       0
  4980.0    0.12       0
Bank Sta=4976,4980
Exp/Cntr=0.3,0.1

Type RM Length L Ch R = 1,758,222,222,222
BEGIN DESCRIPTION:
Lacy 018 3261
END DESCRIPTION:
XS GIS Cut Line= 3
      2755128.91      6877846.00      2754825.65      6877826.94
      2754504.78      6877806.16
#Sta/Elev= 30
  4697.3  466.71  4701.2  466.29  4750.3  465.42  4780.4  464.47  4830.5  461.94
  4840.5  461.89  4880.6  460.76  4890.6  459.92  4940.7  458.53  4950.7  457.76
  4958.1  457.59  4980.8  458.03  4990.8  458.84  4998.5  457.17  5003.5  457.17
  5010.8  458.42  5013.8  457.04  5014.0  456.54  5017.5  456.54  5017.8  457.04
  5050.9  458.08  5071.0  459.63  5089.0  460.51  5121.1  461.63  5168.3  463.90
  5173.3  463.66  5211.3  465.36  5231.3  465.94  5291.4  467.00  5322.7  467.00
#Mann=5,-1,0
  4697.3    0.05       0  4958.1     0.1       0  5013.8    0.07       0
  5017.8     0.1       0  5089.0    0.05       0
Bank Sta=5013.8,5017.8
Exp/Cntr=0.3,0.1

Type RM Length L Ch R = 1,536,154,154,154
BEGIN DESCRIPTION:
Lacy 018 3260
END DESCRIPTION:
XS GIS Cut Line= 3
      2755090.68      6877743.75      2754776.74      6877620.53
      2754519.25      6877642.67
#Sta/Elev= 30
  4663.1  464.44  4678.9  464.26  4738.5  462.34  4768.3  461.92  4792.7  461.19
  4798.1  461.40  4817.2  460.60  4822.5  460.67  4847.0  459.37  4897.3  457.90
  4925.6  457.31  4936.7  457.29  4947.4  457.69  4955.4  457.12  4990.6  456.46
  4996.1  454.72  4996.3  454.22  4999.8  454.22  5000.1  454.72  5003.2  454.72
  5011.1  456.23  5031.2  457.59  5041.2  457.56  5065.3  458.46  5091.4  459.93
  5128.1  460.83  5161.7  462.21  5191.8  464.05  5252.0  464.79  5258.8  465.23
#Mann=5,-1,0
  4663.1    0.05       0  4897.3     0.1       0  4996.1    0.07       0
  5000.1     0.1       0  5128.1    0.05       0
Bank Sta=4996.1,5000.1
Exp/Cntr=0.3,0.1

Type RM Length L Ch R = 1,382,0,0,0
BEGIN DESCRIPTION:
Lacy 018 3253
END DESCRIPTION:
XS GIS Cut Line= 3
      2755031.95      6877641.91      2754773.93      6877466.86
      2754521.22      6877521.25
#Sta/Elev= 30
  4688.2  461.66  4707.5  461.70  4751.0  460.92  4772.0  459.75  4807.9  458.54
  4841.5  457.88  4900.8  456.03  4930.7  455.76  4945.6  456.42  4951.6  456.17
  4966.6  454.67  4971.3  450.78  4971.6  450.28  4975.1  450.28  4975.3  450.78
  4981.5  455.16  4995.7  454.59  5018.3  455.00  5043.7  456.21  5059.3  457.59
  5079.7  458.04  5087.9  458.67  5100.2  458.30  5120.6  459.19  5137.2  460.69
  5151.3  460.73  5176.8  462.61  5192.2  463.47  5222.9  464.40  5258.5  464.57
#Mann=5,-1,0
  4688.2    0.05       0  4841.5     0.1       0  4971.3    0.07       0
  4975.3     0.1       0  5176.8    0.05       0
Bank Sta=4971.3,4975.3
Exp/Cntr=0.3,0.1

Chan Stop Cuts=-1