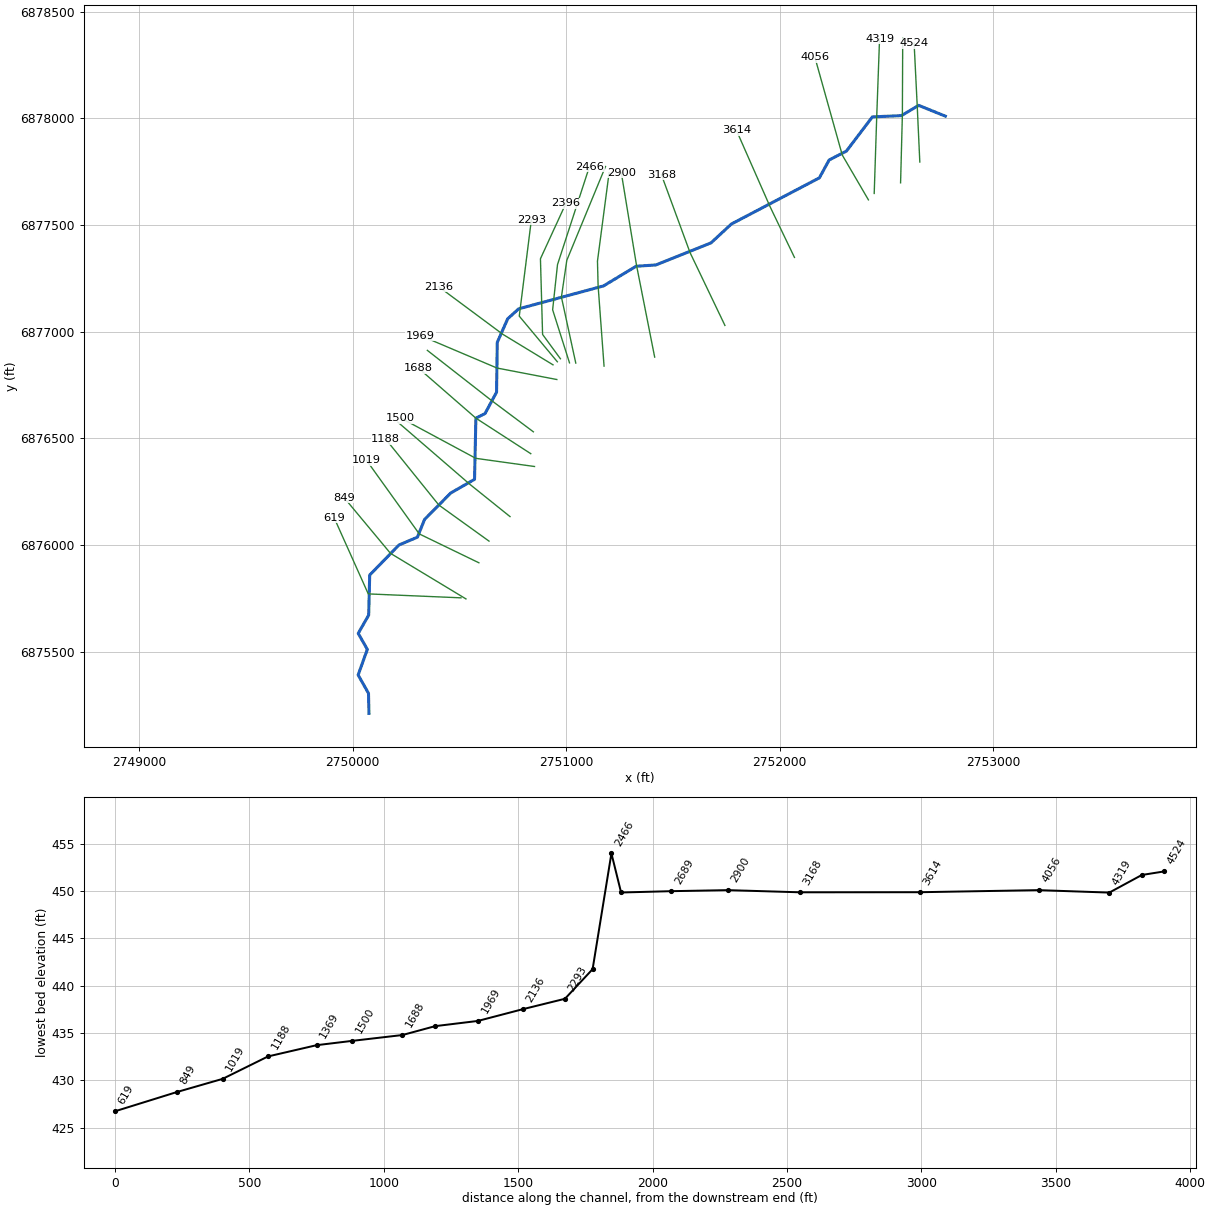
--- Lacy 019.prj (project) ---

Proj Title=Lacy 019 Base Level Engineering
Current Plan=p01
Default Exp/Contr=0.3,0.1
English Units
Geom File=g01
Flow File=f01
Plan File=p01
BEGIN DESCRIPTION:
Lacy 019
END DESCRIPTION:

--- Lacy 019.p01 (plan) ---

Plan Title=Multiple Run
Short Identifier=Multiple
Geom File=g01
Flow File=f01
Subcritical Flow
K Sum by GR= 0
Std Step Tol= 0.01
Critical Tol= 0.01
Num of Std Step Trials= 20
Max Error Tol= 0.3
Flow Tol Ratio= 0.001
Split Flow NTrial= 30
Split Flow Tol= 0.02
Split Flow Ratio= 0.02
Log Output Level= 0
Friction Slope Method= 1
Unsteady Friction Slope Method= 2
Unsteady Bridges Friction Slope Method= 1
Parabolic Critical Depth
Global Vel Dist=  1 , 1 , 1
Global Log Level= 0
CheckData=True
Encroach Param= -1, 0, 0, 0
BEGIN DESCRIPTION:
Multiple Run
END DESCRIPTION:

--- Lacy 019.f01 (steady flow) ---

Flow Title=Multiple
Number of Profiles=7
Profile Names=10-year,25-year,50-year,1pct_min,100-year,1pct_plu,500-year
River Rch & RM= Lacy 019,Reach-1,4524
     242     306     354     205     409     816     544
River Rch & RM= Lacy 019,Reach-1,2136
     336     434     512     300     600    1196     823
Boundary for River Rch & Prof#=Lacy 019,Reach-1,1
Up Type=0
Dn Type=3
Dn Slope=0.005
Boundary for River Rch & Prof#=Lacy 019,Reach-1,2
Up Type=0
Dn Type=3
Dn Slope=0.005
Boundary for River Rch & Prof#=Lacy 019,Reach-1,3
Up Type=0
Dn Type=3
Dn Slope=0.005
Boundary for River Rch & Prof#=Lacy 019,Reach-1,4
Up Type=0
Dn Type=3
Dn Slope=0.005
Boundary for River Rch & Prof#=Lacy 019,Reach-1,5
Up Type=0
Dn Type=3
Dn Slope=0.005
Boundary for River Rch & Prof#=Lacy 019,Reach-1,6
Up Type=0
Dn Type=3
Dn Slope=0.005
Boundary for River Rch & Prof#=Lacy 019,Reach-1,7
Up Type=0
Dn Type=3
Dn Slope=0.005

--- Lacy 019.g01 (geometry) ---

Geom Title=Existing Conditions

River Reach=Lacy 019,Reach-1
Reach XY= 30
      2752776.00      6878011.00      2752651.00      6878061.47
      2752570.06      6878013.30      2752434.38      6878007.61
      2752312.85      6877847.31      2752231.64      6877805.35
      2752185.97      6877721.70      2751773.71      6877505.15
      2751678.29      6877416.84      2751420.03      6877313.35
      2751327.58      6877307.17      2751174.42      6877214.83
      2750777.40      6877107.61      2750726.00      6877061.00
      2750677.12      6876950.54      2750673.77      6876716.90
      2750619.97      6876616.79      2750576.92      6876595.06
      2750570.64      6876308.30      2750459.34      6876244.34
      2750336.79      6876120.66      2750303.14      6876037.16
      2750216.34      6876000.21      2750079.54      6875859.54
      2750074.76      6875671.50      2750025.69      6875585.96
      2750068.40      6875511.01      2750025.41      6875390.96
      2750073.89      6875305.13      2750076.00      6875211.00

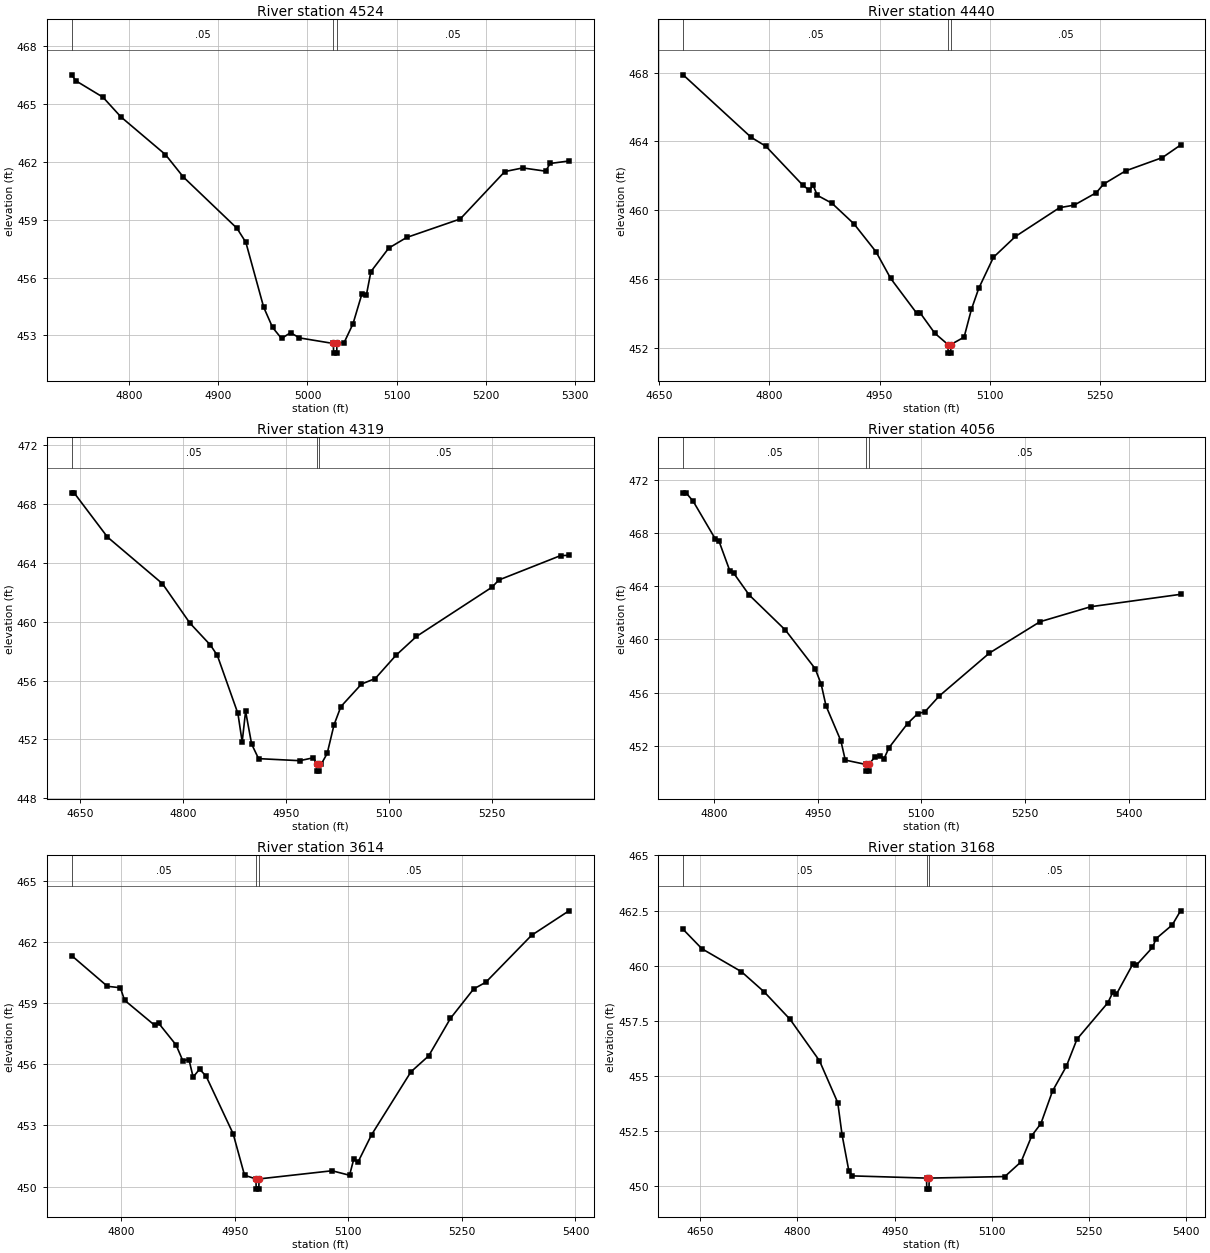
Type RM Length L Ch R = 1,4524,84,84,84
BEGIN DESCRIPTION:
Lacy 019 3095
END DESCRIPTION:
XS GIS Cut Line= 3
      2752656.43      6877795.81      2752644.07      6878063.93
      2752629.74      6878352.76
#Sta/Elev= 30
  4735.5  466.52  4740.7  466.20  4770.7  465.36  4790.8  464.34  4840.8  462.38
  4860.8  461.22  4920.9  458.56  4930.9  457.83  4950.9  454.46  4960.9  453.41
  4970.9  452.84  4981.0  453.14  4991.0  452.87  5029.0  452.58  5029.3  452.08
  5032.8  452.08  5033.0  452.58  5041.0  452.62  5051.0  453.60  5061.0  455.15
  5066.0  455.09  5071.1  456.31  5091.1  457.53  5111.1  458.08  5171.2  459.04
  5221.2  461.50  5241.3  461.69  5267.0  461.52  5272.0  461.92  5293.1  462.05
#Mann=3,-1,0
  4735.5    0.05       0  5029.0    0.04       0  5033.0    0.05       0
Bank Sta=5029,5033
Exp/Cntr=0.3,0.1

Type RM Length L Ch R = 1,4440,121,121,121
BEGIN DESCRIPTION:
Lacy 019 3094
END DESCRIPTION:
XS GIS Cut Line= 3
      2752566.35      6877698.39      2752574.76      6878017.23
      2752576.35      6878375.77
#Sta/Elev= 30
  4682.4  467.87  4775.0  464.24  4795.1  463.72  4845.1  461.47  4854.4  461.16
  4859.4  461.46  4865.1  460.87  4885.1  460.41  4915.1  459.21  4945.1  457.59
  4965.1  456.04  5000.7  454.01  5005.7  454.01  5025.1  452.86  5043.1  452.20
  5043.4  451.70  5046.9  451.70  5047.1  452.20  5065.1  452.63  5075.1  454.25
  5085.1  455.47  5105.1  457.27  5135.1  458.48  5195.1  460.15  5215.1  460.30
  5245.1  461.02  5255.1  461.52  5285.1  462.29  5335.1  463.06  5359.9  463.79
#Mann=3,-1,0
  4682.4    0.05       0  5043.1    0.04       0  5047.1    0.05       0
Bank Sta=5043.1,5047.1
Exp/Cntr=0.3,0.1

Type RM Length L Ch R = 1,4319,263,263,263
BEGIN DESCRIPTION:
Lacy 019 3093
END DESCRIPTION:
XS GIS Cut Line= 3
      2752442.82      6877648.59      2752454.63      6878009.12
      2752467.83      6878373.16
#Sta/Elev= 30
  4637.2  468.77  4640.9  468.77  4689.6  465.76  4769.7  462.59  4809.7  459.91
  4839.7  458.41  4849.7  457.71  4879.7  453.76  4885.9  451.83  4890.9  453.91
  4899.7  451.68  4909.8  450.69  4969.8  450.55  4989.8  450.75  4994.4  450.34
  4994.6  449.84  4998.1  449.84  4998.4  450.34  5001.4  450.34  5009.8  451.04
  5019.8  452.99  5029.8  454.23  5059.8  455.76  5079.9  456.14  5109.9  457.71
  5139.9  459.00  5250.0  462.35  5260.0  462.84  5350.0  464.50  5362.2  464.52
#Mann=3,-1,0
  4637.2    0.05       0  4994.4    0.04       0  4998.4    0.05       0
Bank Sta=4994.4,4998.4
Exp/Cntr=0.3,0.1

Type RM Length L Ch R = 1,4056,442,442,442
BEGIN DESCRIPTION:
Lacy 019 3096
END DESCRIPTION:
XS GIS Cut Line= 3
      2752415.65      6877618.54      2752293.18      6877828.57
      2752164.93      6878286.94
#Sta/Elev= 30
  4755.5  471.02  4759.8  471.02  4770.2  470.37  4801.7  467.58  4807.4  467.38
  4823.2  465.13  4828.9  464.96  4851.0  463.34  4903.4  460.70  4946.4  457.80
  4955.1  456.63  4962.1  455.00  4983.6  452.37  4989.9  450.93  5019.9  450.60
  5020.2  450.10  5023.7  450.10  5023.9  450.60  5032.3  451.14  5040.7  451.27
  5045.9  451.03  5053.1  451.86  5080.0  453.68  5094.6  454.42  5105.0  454.56
  5125.8  455.75  5198.4  458.98  5271.4  461.33  5344.9  462.46  5474.6  463.39
#Mann=3,-1,0
  4755.5    0.05       0  5019.9    0.04       0  5023.9    0.05       0
Bank Sta=5019.9,5023.9
Exp/Cntr=0.3,0.1

Type RM Length L Ch R = 1,3614,446,446,446
BEGIN DESCRIPTION:
Lacy 019 3092
END DESCRIPTION:
XS GIS Cut Line= 3
      2752069.29      6877348.60      2751954.93      6877586.59
      2751796.62      6877946.25
#Sta/Elev= 30
  4734.4  461.33  4781.8  459.82  4798.9  459.75  4804.4  459.14  4844.2  457.91
  4849.7  458.00  4872.4  456.95  4881.3  456.18  4889.5  456.23  4895.0  455.37
  4903.5  455.76  4912.1  455.42  4947.9  452.59  4962.9  450.56  4978.0  450.38
  4978.3  449.88  4981.8  449.88  4982.0  450.38  5078.5  450.78  5101.6  450.56
  5107.3  451.37  5112.7  451.20  5130.6  452.54  5182.7  455.63  5206.1  456.41
  5234.9  458.25  5265.5  459.69  5281.6  460.02  5342.0  462.32  5391.4  463.52
#Mann=3,-1,0
  4734.4    0.05       0  4978.0    0.04       0  4982.0    0.05       0
Bank Sta=4978,4982
Exp/Cntr=0.3,0.1

Type RM Length L Ch R = 1,3168,268,268,268
BEGIN DESCRIPTION:
Lacy 019 3091
END DESCRIPTION:
XS GIS Cut Line= 3
      2751743.50      6877029.79      2751580.06      6877371.43
      2751445.99      6877736.36
#Sta/Elev= 30
  4623.6  461.65  4652.6  460.77  4713.6  459.73  4748.8  458.81  4788.6  457.57
  4834.0  455.69  4862.2  453.79  4868.8  452.34  4879.3  450.70  4884.9  450.47
  4999.2  450.37  4999.5  449.87  5003.0  449.87  5003.2  450.37  5120.0  450.44
  5145.1  451.11  5161.7  452.30  5175.6  452.84  5193.6  454.32  5214.9  455.44
  5231.3  456.67  5278.9  458.32  5286.9  458.81  5292.2  458.71  5317.4  460.07
  5322.7  460.02  5347.8  460.83  5353.4  461.23  5378.3  461.85  5391.1  462.49
#Mann=3,-1,0
  4623.6    0.05       0  4999.2    0.03       0  5003.2    0.05       0
Bank Sta=4999.2,5003.2
Exp/Cntr=0.3,0.1

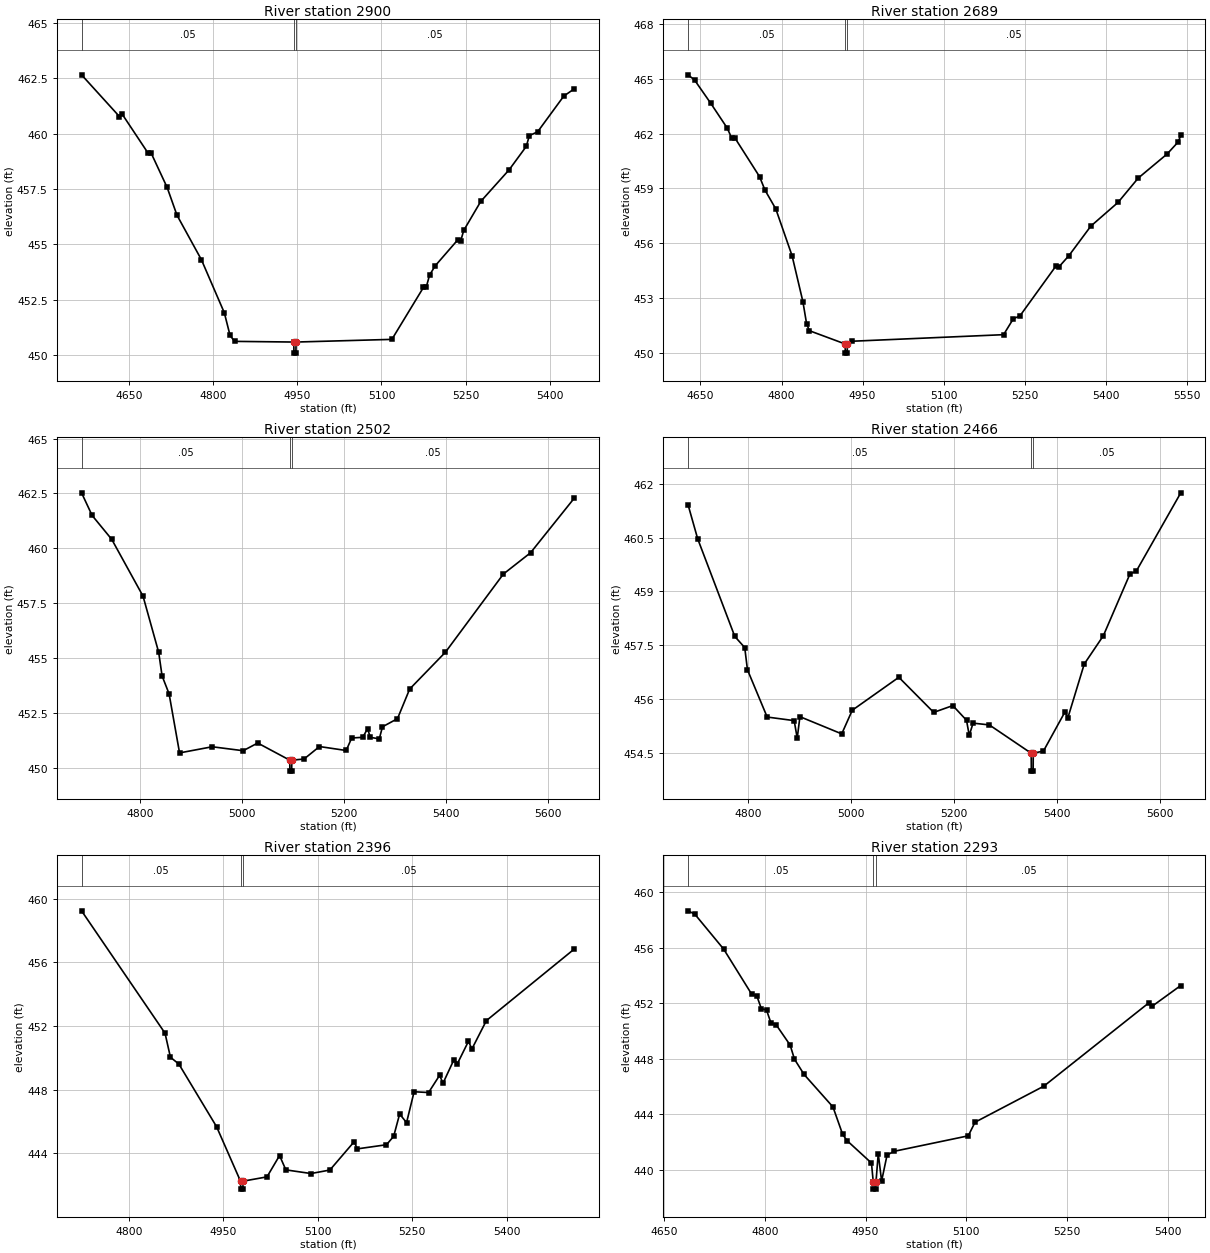
Type RM Length L Ch R = 1,2900,211,211,211
BEGIN DESCRIPTION:
Lacy 019 3090
END DESCRIPTION:
XS GIS Cut Line= 3
      2751414.38      6876881.31      2751329.07      6877313.41
      2751258.11      6877745.58
#Sta/Elev= 30
  4565.4  462.65  4632.9  460.77  4638.0  460.87  4684.2  459.11  4689.3  459.13
  4718.0  457.57  4735.5  456.32  4779.1  454.31  4819.9  451.92  4830.1  450.90
  4838.1  450.63  4943.8  450.60  4944.0  450.10  4947.5  450.10  4947.8  450.60
  5118.6  450.72  5174.8  453.06  5179.9  453.08  5185.8  453.62  5195.9  454.04
  5236.1  455.21  5241.2  455.15  5246.6  455.63  5277.0  456.94  5327.7  458.37
  5358.1  459.42  5363.7  459.91  5378.4  460.08  5425.0  461.69  5443.8  462.02
#Mann=3,-1,0
  4565.4    0.05       0  4943.8    0.03       0  4947.8    0.05       0
Bank Sta=4943.8,4947.8
Exp/Cntr=0.3,0.1

Type RM Length L Ch R = 1,2689,187,187,187
BEGIN DESCRIPTION:
Lacy 019 3089
END DESCRIPTION:
XS GIS Cut Line= 4
      2751177.28      6876839.03      2751149.47      6877215.55
      2751146.46      6877331.04      2751200.99      6877746.00
#Sta/Elev= 30
  4627.0  465.22  4639.0  464.94  4669.1  463.66  4699.2  462.32  4708.2  461.74
  4713.2  461.79  4759.3  459.65  4769.4  458.91  4789.4  457.88  4819.5  455.32
  4839.5  452.81  4846.3  451.61  4851.3  451.22  4917.8  450.49  4918.0  449.99
  4921.5  449.99  4921.8  450.49  4929.8  450.64  5210.8  451.00  5228.8  451.87
  5241.1  452.03  5307.5  454.75  5312.6  454.69  5331.8  455.33  5372.2  456.94
  5422.6  458.24  5459.9  459.57  5513.4  460.89  5533.6  461.54  5538.6  461.90
#Mann=3,-1,0
  4627.0    0.05       0  4917.8    0.03       0  4921.8    0.05       0
Bank Sta=4917.8,4921.8
Exp/Cntr=0.3,0.1

Type RM Length L Ch R = 1,2502,36,36,36
BEGIN DESCRIPTION:
Lacy 019 3088
END DESCRIPTION:
XS GIS Cut Line= 4
      2751044.83      6876853.18      2750977.58      6877162.91
      2751002.77      6877334.96      2751184.02      6877774.64
#Sta/Elev= 30
  4684.9  462.53  4705.6  461.50  4744.1  460.41  4805.5  457.82  4836.2  455.26
  4842.8  454.19  4856.6  453.37  4877.1  450.68  4941.1  450.96  5001.8  450.78
  5030.4  451.13  5093.2  450.35  5093.5  449.85  5097.0  449.85  5097.2  450.35
  5121.2  450.40  5151.5  450.97  5203.9  450.79  5214.7  451.36  5236.3  451.39
  5245.8  451.78  5251.2  451.39  5268.8  451.32  5275.1  451.87  5304.5  452.24
  5328.4  453.59  5398.6  455.27  5512.2  458.83  5565.5  459.80  5651.3  462.29
#Mann=3,-1,0
  4684.9    0.05       0  5093.2    0.04       0  5097.2    0.05       0
Bank Sta=5093.2,5097.2
Exp/Cntr=0.3,0.1

Type RM Length L Ch R = 1,2466,70,70,70
BEGIN DESCRIPTION:
Lacy 019 3085
END DESCRIPTION:
XS GIS Cut Line= 4
      2751015.45      6876854.37      2750936.47      6877103.03
      2750959.23      6877314.86      2751108.99      6877774.74
#Sta/Elev= 30
  4682.6  461.42  4701.3  460.47  4773.5  457.74  4792.8  457.43  4798.1  456.81
  4836.4  455.49  4888.9  455.39  4894.8  454.90  4900.1  455.50  4981.3  455.02
  5001.8  455.68  5092.3  456.60  5160.0  455.62  5197.2  455.81  5223.8  455.40
  5229.1  454.98  5236.6  455.32  5268.2  455.27  5349.5  454.48  5349.8  453.98
  5353.3  453.98  5353.5  454.48  5373.3  454.54  5415.4  455.64  5420.6  455.46
  5452.6  456.97  5489.7  457.76  5541.6  459.49  5553.6  459.56  5640.2  461.75
#Mann=3,-1,0
  4682.6    0.05       0  5349.5    0.04       0  5353.5    0.05       0
Bank Sta=5349.5,5353.5
Exp/Cntr=0.3,0.1

Type RM Length L Ch R = 1,2396,103,103,103
BEGIN DESCRIPTION:
Lacy 019 3086
END DESCRIPTION:
XS GIS Cut Line= 4
      2750972.83      6876873.58      2750889.37      6876987.59
      2750879.32      6877342.37      2750999.23      6877603.33
#Sta/Elev= 30
  4724.4  459.24  4857.1  451.55  4865.7  450.04  4879.1  449.61  4939.1  445.67
  4977.1  442.25  4977.4  441.75  4980.9  441.75  4981.1  442.25  5019.2  442.52
  5039.2  443.86  5049.2  442.96  5089.2  442.73  5119.2  442.95  5157.8  444.73
  5162.8  444.28  5209.2  444.54  5220.6  445.07  5230.1  446.47  5241.1  445.93
  5253.1  447.87  5276.1  447.82  5293.6  448.90  5299.1  448.41  5316.5  449.89
  5322.0  449.64  5339.5  451.04  5345.0  450.56  5368.0  452.34  5507.8  456.84
#Mann=3,-1,0
  4724.4    0.05       0  4977.1    0.04       0  4981.1    0.05       0
Bank Sta=4977.1,4981.1
Exp/Cntr=0.3,0.1

Type RM Length L Ch R = 1,2293,157,157,157
BEGIN DESCRIPTION:
Lacy 019 3087
END DESCRIPTION:
XS GIS Cut Line= 3
      2750958.48      6876859.41      2750780.17      6877073.28
      2750836.76      6877524.90
#Sta/Elev= 30
  4685.7  458.67  4695.8  458.43  4738.8  455.91  4780.4  452.67  4788.2  452.53
  4794.8  451.63  4802.6  451.52  4809.1  450.60  4816.9  450.46  4837.7  449.00
  4844.2  447.98  4858.5  446.88  4901.5  444.54  4915.8  442.58  4922.3  442.12
  4958.8  440.50  4961.5  439.12  4961.8  438.62  4965.3  438.62  4965.5  439.12
  4968.9  441.18  4973.9  439.20  4982.0  441.07  4992.1  441.34  5102.9  442.46
  5113.0  443.44  5215.5  446.04  5371.5  452.03  5376.5  451.79  5419.3  453.29
#Mann=3,-1,0
  4685.7    0.05       0  4961.5    0.04       0  4965.5    0.05       0
Bank Sta=4961.5,4965.5
Exp/Cntr=0.3,0.1

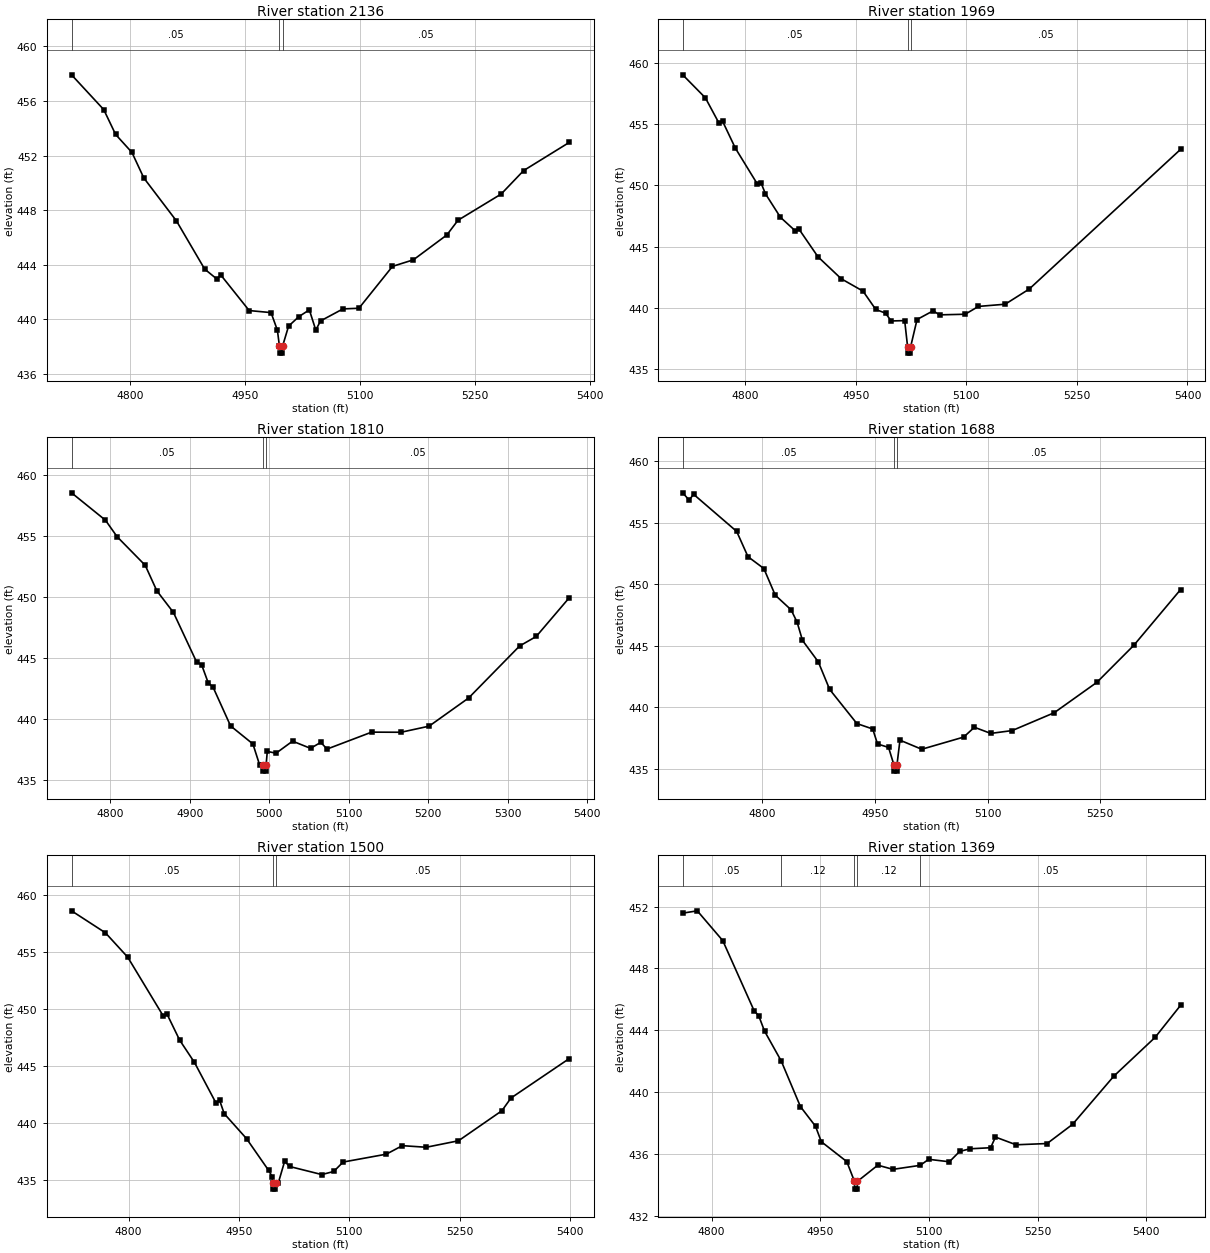
Type RM Length L Ch R = 1,2136,167,167,167
BEGIN DESCRIPTION:
Lacy 019 3083
END DESCRIPTION:
XS GIS Cut Line= 3
      2750938.31      6876845.03      2750702.98      6876988.29
      2750402.66      6877211.34
#Sta/Elev= 30
  4723.6  457.92  4765.6  455.37  4781.1  453.55  4802.4  452.23  4817.9  450.36
  4860.5  447.21  4897.3  443.68  4912.8  442.97  4918.6  443.23  4955.4  440.64
  4983.9  440.49  4992.2  439.20  4994.9  438.02  4995.2  437.52  4998.7  437.52
  4998.9  438.02  5006.8  439.50  5020.3  440.20  5033.9  440.69  5042.3  439.21
  5048.5  439.88  5077.7  440.76  5098.6  440.81  5142.4  443.88  5169.7  444.36
  5213.3  446.18  5227.9  447.26  5284.2  449.18  5313.5  450.90  5373.2  452.97
#Mann=3,-1,0
  4723.6    0.05       0  4994.9    0.04       0  4998.9    0.05       0
Bank Sta=4994.9,4998.9
Exp/Cntr=0.3,0.1

Type RM Length L Ch R = 1,1969,159,159,159
BEGIN DESCRIPTION:
Lacy 019 3084
END DESCRIPTION:
XS GIS Cut Line= 3
      2750956.10      6876776.20      2750675.99      6876830.04
      2750317.15      6876982.44
#Sta/Elev= 30
  4715.5  459.04  4746.2  457.16  4764.4  455.12  4769.5  455.25  4786.9  453.04
  4816.4  450.14  4821.5  450.23  4827.6  449.32  4848.0  447.39  4868.3  446.27
  4873.4  446.40  4898.9  444.16  4930.5  442.36  4960.0  441.35  4977.3  439.85
  4990.5  439.55  4998.2  438.91  5016.5  438.94  5020.5  436.78  5020.7  436.28
  5024.2  436.28  5024.5  436.78  5033.3  439.03  5055.1  439.74  5063.8  439.41
  5098.5  439.46  5116.6  440.10  5152.8  440.28  5185.4  441.52  5390.6  452.94
#Mann=3,-1,0
  4715.5    0.05       0  5020.5    0.04       0  5024.5    0.05       0
Bank Sta=5020.5,5024.5
Exp/Cntr=0.3,0.1

Type RM Length L Ch R = 1,1810,122,122,122
BEGIN DESCRIPTION:
Lacy 019 3104
END DESCRIPTION:
XS GIS Cut Line= 3
      2750846.13      6876531.06      2750647.12      6876680.21
      2750349.56      6876912.83
#Sta/Elev= 30
  4751.3  458.57  4794.0  456.32  4808.6  454.97  4844.0  452.62  4858.6  450.53
  4879.5  448.75  4908.6  444.69  4914.9  444.47  4923.2  442.99  4929.5  442.60
  4951.4  439.44  4979.5  437.96  4987.8  436.27  4992.1  436.23  4992.3  435.73
  4995.8  435.73  4996.1  436.23  4997.6  437.35  5008.6  437.20  5029.4  438.19
  5052.0  437.60  5064.9  438.09  5072.8  437.54  5128.9  438.93  5165.9  438.92
  5201.2  439.42  5250.9  441.73  5315.1  446.00  5336.0  446.78  5377.7  449.97
#Mann=3,-1,0
  4751.3    0.05       0  4992.1    0.04       0  4996.1    0.05       0
Bank Sta=4992.1,4996.1
Exp/Cntr=0.3,0.1

Type RM Length L Ch R = 1,1688,188,188,188
BEGIN DESCRIPTION:
Lacy 019 3103
END DESCRIPTION:
XS GIS Cut Line= 3
      2750833.92      6876428.60      2750576.92      6876595.06
      2750307.67      6876829.79
#Sta/Elev= 30
  4693.8  457.44  4702.3  456.85  4708.3  457.32  4765.7  454.30  4780.8  452.24
  4801.9  451.28  4817.1  449.11  4838.2  447.92  4846.2  446.92  4853.4  445.43
  4874.5  443.68  4889.6  441.44  4925.9  438.66  4947.0  438.22  4953.4  437.00
  4968.1  436.72  4975.3  435.29  4975.5  434.79  4979.0  434.79  4979.3  435.29
  4983.3  437.31  5012.3  436.57  5068.2  437.56  5082.5  438.36  5104.3  437.86
  5132.8  438.09  5188.8  439.54  5245.8  442.02  5295.1  445.04  5357.2  449.56
#Mann=3,-1,0
  4693.8    0.05       0  4975.3    0.04       0  4979.3    0.05       0
Bank Sta=4975.3,4979.3
Exp/Cntr=0.3,0.1

Type RM Length L Ch R = 1,1500,131,131,131
BEGIN DESCRIPTION:
Lacy 019 3102
END DESCRIPTION:
XS GIS Cut Line= 3
      2750851.53      6876368.42      2750576.58      6876406.69
      2750225.23      6876595.77
#Sta/Elev= 30
  4722.4  458.63  4768.4  456.70  4798.7  454.56  4847.0  449.39  4852.1  449.56
  4869.3  447.27  4889.5  445.30  4918.6  441.75  4923.7  441.96  4929.9  440.80
  4960.2  438.61  4990.2  435.82  4995.3  435.25  4995.8  434.67  4996.0  434.17
  4999.5  434.17  4999.8  434.67  5003.2  434.67  5012.0  436.61  5018.7  436.16
  5062.5  435.45  5078.7  435.72  5091.5  436.55  5150.1  437.24  5172.0  437.99
  5204.5  437.85  5248.3  438.42  5307.3  441.06  5319.7  442.18  5399.0  445.65
#Mann=3,-1,0
  4722.4    0.05       0  4995.8    0.05       0  4999.8    0.05       0
Bank Sta=4995.8,4999.8
Exp/Cntr=0.3,0.1

Type RM Length L Ch R = 1,1369,181,181,181
BEGIN DESCRIPTION:
Lacy 019 3101
END DESCRIPTION:
XS GIS Cut Line= 3
      2750736.87      6876133.57      2750549.97      6876283.81
      2750211.48      6876576.38
#Sta/Elev= 30
  4760.2  451.58  4780.3  451.73  4815.5  449.80  4858.7  445.27  4865.1  444.94
  4873.1  443.95  4896.2  442.01  4922.7  439.06  4943.5  437.79  4951.5  436.79
  4986.7  435.50  4997.3  434.22  4997.6  433.72  5001.1  433.72  5001.3  434.22
  5029.5  435.27  5050.4  435.00  5088.1  435.26  5099.7  435.65  5128.3  435.49
  5142.5  436.16  5156.8  436.33  5185.3  436.40  5191.9  437.09  5220.4  436.59
  5263.2  436.67  5298.3  437.91  5355.3  441.03  5412.3  443.54  5447.4  445.61
#Mann=5,-1,0
  4760.2    0.05       0  4896.2    0.12       0  4997.3    0.07       0
  5001.3    0.12       0  5088.1    0.05       0
Bank Sta=4997.3,5001.3
Exp/Cntr=0.3,0.1

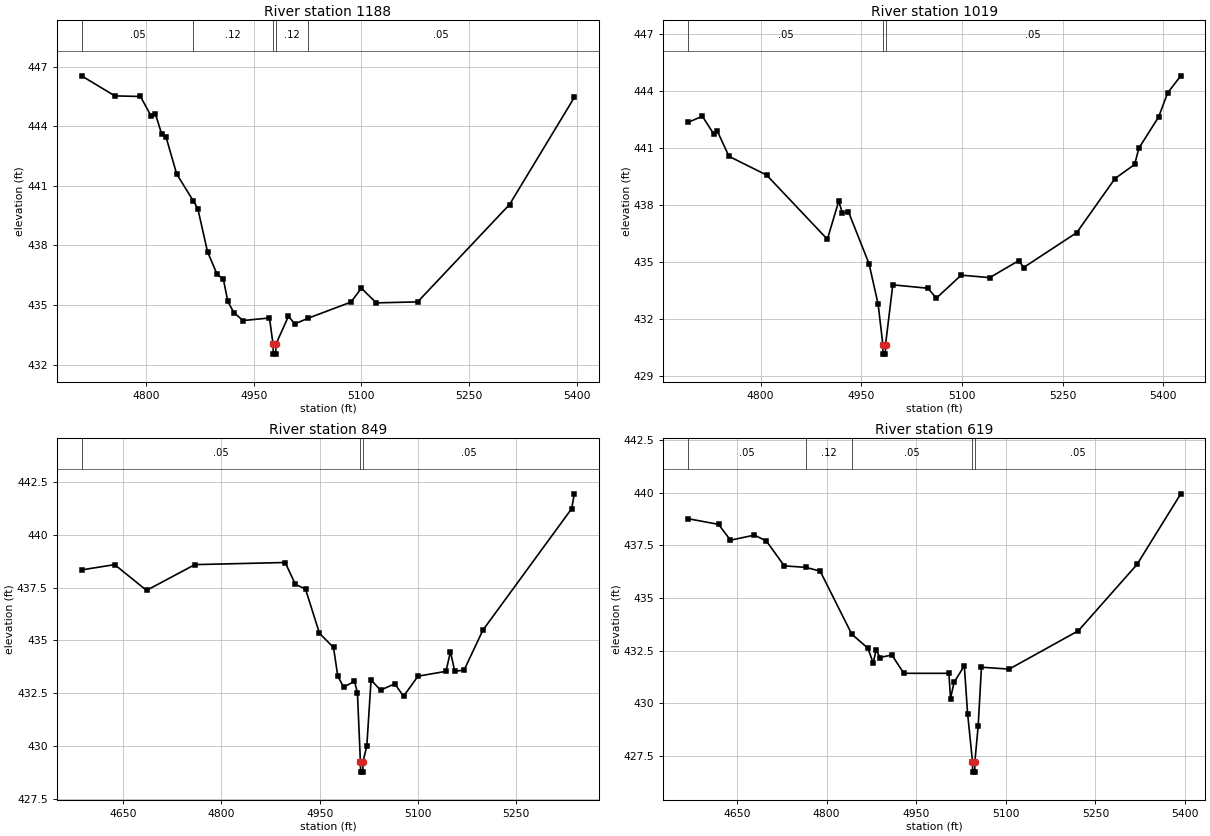
Type RM Length L Ch R = 1,1188,169,169,169
BEGIN DESCRIPTION:
Lacy 019 3100
END DESCRIPTION:
XS GIS Cut Line= 3
      2750638.36      6876018.64      2750403.29      6876187.78
      2750154.69      6876496.54
#Sta/Elev= 30
  4710.4  446.54  4756.8  445.53  4792.4  445.50  4807.2  444.52  4813.3  444.61
  4821.9  443.62  4828.0  443.46  4842.8  441.60  4866.2  440.23  4872.2  439.86
  4885.8  437.68  4899.2  436.54  4907.8  436.31  4914.0  435.18  4922.5  434.62
  4935.1  434.22  4972.0  434.35  4977.0  433.03  4977.3  432.53  4980.8  432.53
  4981.0  433.03  4998.5  434.44  5007.1  434.05  5026.0  434.34  5085.5  435.15
  5099.9  435.85  5120.7  435.11  5178.3  435.16  5306.2  440.06  5396.4  445.45
#Mann=5,-1,0
  4710.4    0.05       0  4866.2    0.12       0  4977.0    0.07       0
  4981.0    0.12       0  5026.0    0.05       0
Bank Sta=4977,4981
Exp/Cntr=0.3,0.1

Type RM Length L Ch R = 1,1019,170,170,170
BEGIN DESCRIPTION:
Lacy 019 3099
END DESCRIPTION:
XS GIS Cut Line= 3
      2750590.96      6875917.04      2750311.76      6876052.32
      2750064.88      6876396.97
#Sta/Elev= 30
  4692.0  442.37  4713.4  442.69  4730.4  441.75  4735.9  441.89  4753.0  440.58
  4809.2  439.59  4899.6  436.21  4916.6  438.22  4922.1  437.57  4930.9  437.67
  4961.7  434.92  4975.3  432.78  4982.3  430.66  4982.6  430.16  4986.1  430.16
  4986.3  430.66  4997.1  433.81  5049.4  433.63  5062.1  433.11  5099.0  434.32
  5141.5  434.19  5185.1  435.09  5191.9  434.72  5271.2  436.56  5328.2  439.41
  5357.4  440.15  5363.8  441.01  5393.3  442.66  5406.6  443.92  5426.2  444.82
#Mann=3,-1,0
  4692.0    0.05       0  4982.3    0.04       0  4986.3    0.05       0
Bank Sta=4982.3,4986.3
Exp/Cntr=0.3,0.1

Type RM Length L Ch R = 1,849,230,230,230
BEGIN DESCRIPTION:
Lacy 019 3098
END DESCRIPTION:
XS GIS Cut Line= 3
      2750530.47      6875747.59      2750176.83      6875961.31
      2749960.45      6876221.49
#Sta/Elev= 30
  4586.8  438.34  4637.3  438.59  4685.9  437.37  4759.6  438.59  4897.4  438.69
  4912.9  437.66  4928.4  437.43  4949.7  435.34  4971.1  434.67  4977.6  433.32
  4986.6  432.79  5003.1  433.07  5007.6  432.53  5012.1  429.27  5012.4  428.77
  5015.9  428.77  5016.1  429.27  5021.9  430.01  5028.4  433.13  5042.8  432.65
  5064.6  432.95  5077.9  432.36  5100.0  433.31  5142.7  433.54  5149.5  434.47
  5156.0  433.54  5170.3  433.60  5199.0  435.49  5334.4  441.24  5338.4  441.94
#Mann=3,-1,0
  4586.8    0.05       0  5012.1    0.04       0  5016.1    0.05       0
Bank Sta=5012.1,5016.1
Exp/Cntr=0.3,0.1

Type RM Length L Ch R = 1,619,0,0,0
BEGIN DESCRIPTION:
Lacy 019 3097
END DESCRIPTION:
XS GIS Cut Line= 3
      2750507.08      6875752.73      2750072.82      6875771.11
      2749913.19      6876127.55
#Sta/Elev= 30
  4567.8  438.77  4618.9  438.50  4638.9  437.75  4679.0  437.99  4699.0  437.71
  4729.0  436.53  4765.1  436.46  4789.1  436.28  4842.0  433.29  4869.1  432.62
  4877.9  431.92  4882.9  432.55  4889.2  432.18  4909.2  432.30  4929.2  431.43
  5004.7  431.43  5007.4  430.23  5013.3  431.00  5030.5  431.79  5036.0  429.52
  5044.2  427.24  5044.4  426.74  5047.9  426.74  5048.2  427.24  5053.7  428.93
  5059.2  431.72  5105.6  431.63  5221.5  433.45  5319.8  436.60  5393.0  439.95
#Mann=5,-1,0
  4567.8    0.05       0  4765.1    0.12       0  4842.0    0.05       0
  5044.2    0.04       0  5048.2    0.05       0
Bank Sta=5044.2,5048.2
Exp/Cntr=0.3,0.1

Chan Stop Cuts=-1