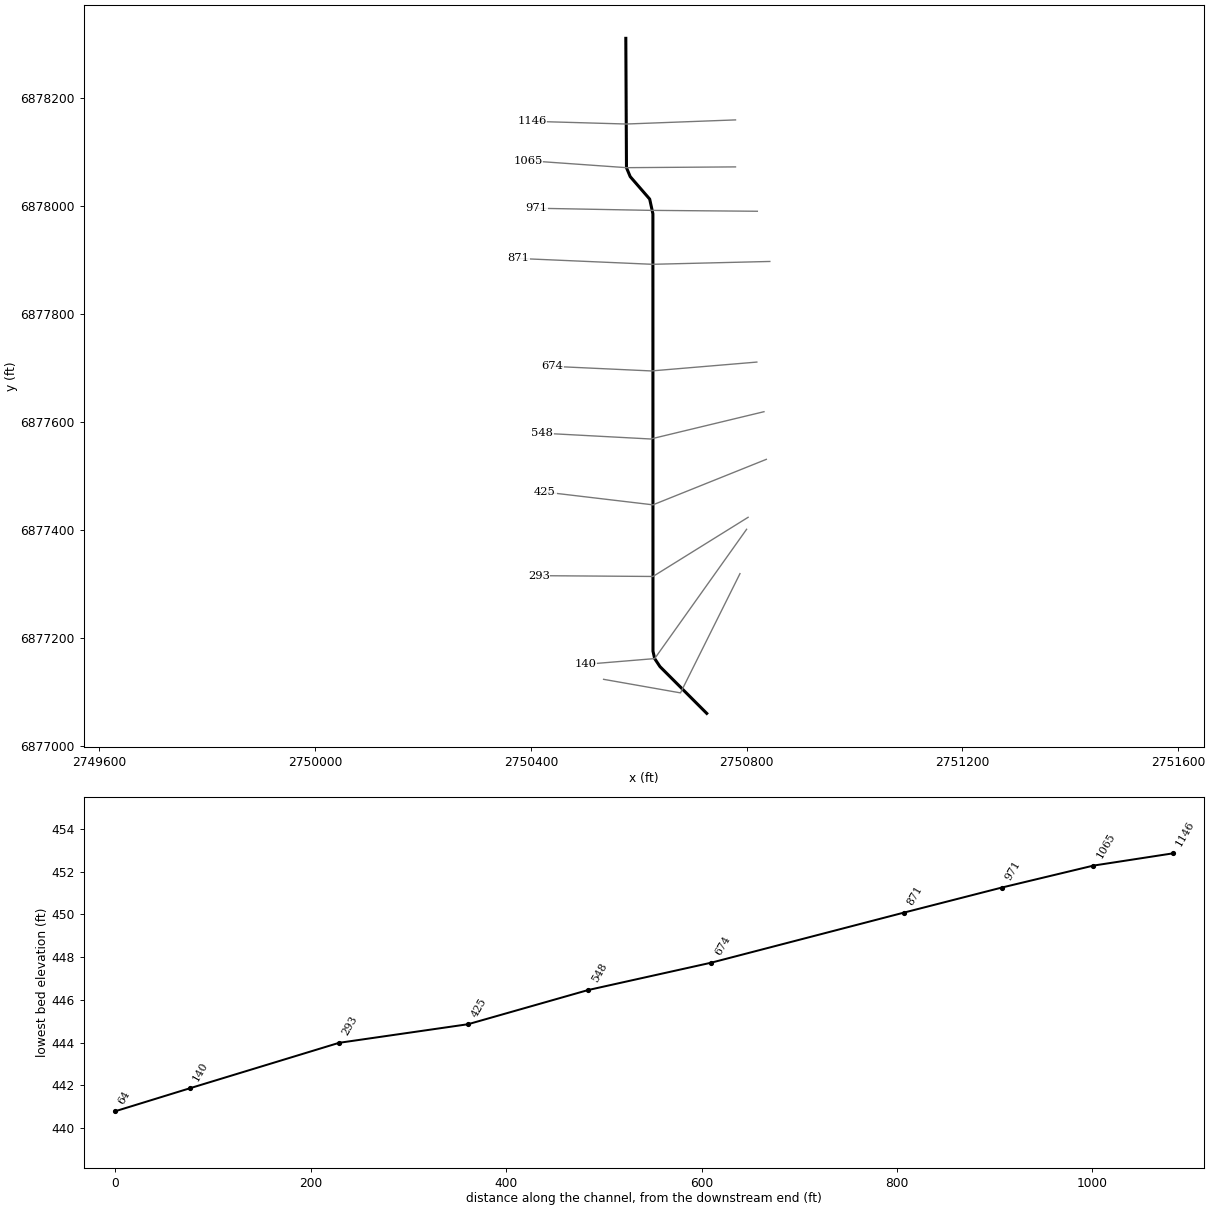
--- Lacy 020.prj (project) ---

Proj Title=Lacy 020 Base Level Engineering
Current Plan=p01
Default Exp/Contr=0.3,0.1
English Units
Geom File=g01
Flow File=f01
Plan File=p01
Y Axis Title=Elevation
X Axis Title(PF)=Main Channel Distance
X Axis Title(XS)=Station
BEGIN DESCRIPTION:
Lacy 020
END DESCRIPTION:
DSS Export Rating Curves= 0
DSS Export Rating Curve Sorted= 0
DSS Export Volume Flow Curves= 0
DXF OffsetX= 0
DXF OffsetY= 0
DXF ScaleX= 1
DXF ScaleY= 10

--- Lacy 020.p01 (plan) ---

Plan Title=Multiple Run
Short Identifier=Multiple
Geom File=g01
Flow File=f01
Subcritical Flow
K Sum by GR= 0
Std Step Tol= 0.01
Critical Tol= 0.01
Num of Std Step Trials= 20
Max Error Tol= 0.3
Flow Tol Ratio= 0.001
Split Flow NTrial= 30
Split Flow Tol= 0.02
Split Flow Ratio= 0.02
Log Output Level= 0
Friction Slope Method= 1
Unsteady Friction Slope Method= 2
Unsteady Bridges Friction Slope Method= 1
Parabolic Critical Depth
Global Vel Dist=  1 , 1 , 1
Global Log Level= 0
CheckData=True
Encroach Param= -1, 0, 0, 0
BEGIN DESCRIPTION:
Multiple Run
END DESCRIPTION:

--- Lacy 020.f01 (steady flow) ---

Flow Title=Multiple
Number of Profiles=7
Profile Names=10-year,25-year,50-year,1pct_min,100-year,1pct_plu,500-year
River Rch & RM= Lacy 020,Reach-1,1146
     103     122     136      76     152     304     189
Boundary for River Rch & Prof#=Lacy 020,Reach-1,1
Up Type=0
Dn Type=3
Dn Slope=0.005
Boundary for River Rch & Prof#=Lacy 020,Reach-1,2
Up Type=0
Dn Type=3
Dn Slope=0.005
Boundary for River Rch & Prof#=Lacy 020,Reach-1,3
Up Type=0
Dn Type=3
Dn Slope=0.005
Boundary for River Rch & Prof#=Lacy 020,Reach-1,4
Up Type=0
Dn Type=3
Dn Slope=0.005
Boundary for River Rch & Prof#=Lacy 020,Reach-1,5
Up Type=0
Dn Type=3
Dn Slope=0.005
Boundary for River Rch & Prof#=Lacy 020,Reach-1,6
Up Type=0
Dn Type=3
Dn Slope=0.005
Boundary for River Rch & Prof#=Lacy 020,Reach-1,7
Up Type=0
Dn Type=3
Dn Slope=0.005

--- Lacy 020.g01 (geometry) ---

Geom Title=Existing Conditions
Program Version=4.10

River Reach=Lacy 020        ,Reach-1
Reach XY= 9
        2750576.        6878311.      2750577.22       6878071.5
      2750584.14      6878054.94      2750620.25      6878013.33
       2750626.2      6877986.08      2750626.37      6877176.15
      2750629.48      6877162.44      2750639.28      6877147.64
        2750726.        6877061.

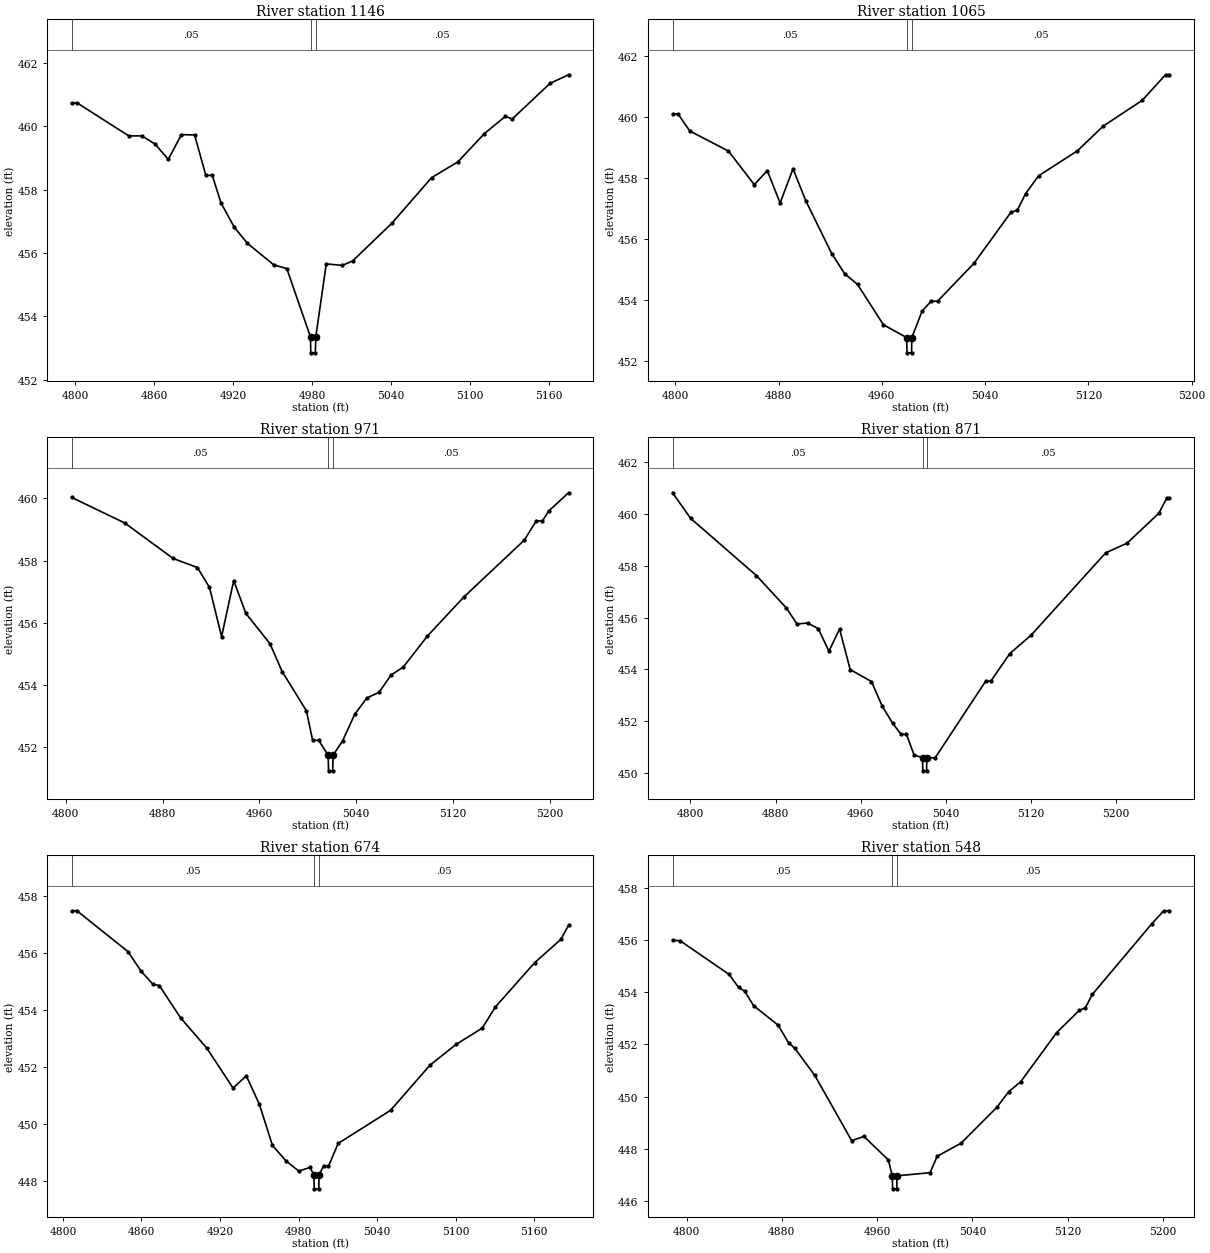
Type RM Length L Ch R = 1 ,1146    ,81,81,81
BEGIN DESCRIPTION:
Lacy 020 3114
END DESCRIPTION:
XS GIS Cut Line= 3
      2750779.36      6878159.96      2750576.81      6878152.33
      2750401.98      6878157.34
#Sta/Elev= 30
  4797.3  460.74  4801.5  460.74  4840.7   459.7  4850.7   459.7  4860.7  459.44
  4870.7  458.96  4880.7  459.74  4890.7  459.73  4899.2  458.46  4904.2  458.45
  4910.7  457.59  4920.8  456.82  4930.8  456.31  4950.8  455.63  4960.8  455.51
  4978.8  453.35    4979  452.85  4982.5  452.85  4982.8  453.35  4990.8  455.66
  5002.9  455.61  5010.8  455.75  5040.8  456.95  5070.8  458.38  5090.8  458.88
  5110.9  459.77    5127  460.32    5132  460.23  5160.9  461.36  5174.9  461.63
#Mann= 3 ,-1 , 0
  4797.3     .05       0  4978.8     .04       0  4982.8     .05       0
Bank Sta=4978.8,4982.8
XS Rating Curve= 0 ,0
Exp/Cntr=0.3,0.1

Type RM Length L Ch R = 1 ,1065    ,94,94,94
BEGIN DESCRIPTION:
Lacy 020 3113
END DESCRIPTION:
XS GIS Cut Line= 3
      2750779.31      6878072.94      2750577.22       6878071.5
      2750394.98      6878084.43
#Sta/Elev= 30
  4797.9  460.11  4802.1  460.11  4811.2  459.55  4841.2  458.89  4861.2  457.79
  4871.2  458.25  4881.2  457.19  4891.2  458.31  4901.2  457.25  4921.2  455.53
  4931.2  454.87  4941.2  454.52  4961.2   453.2  4979.2  452.78  4979.5  452.28
    4983  452.28  4983.2  452.78  4991.2  453.65  4998.1  453.97  5003.1  453.97
  5031.3  455.21  5059.9  456.88    5065  456.96  5071.4   457.5  5081.4  458.08
  5111.5   458.9  5131.5  459.71  5161.6  460.55  5179.7  461.39  5182.7  461.39
#Mann= 3 ,-1 , 0
  4797.9     .05       0  4979.2     .04       0  4983.2     .05       0
Bank Sta=4979.2,4983.2
XS Rating Curve= 0 ,0
Exp/Cntr=0.3,0.1

Type RM Length L Ch R = 1 ,971     ,100,100,100
BEGIN DESCRIPTION:
Lacy 020 3108
END DESCRIPTION:
XS GIS Cut Line= 3
      2750819.81      6877990.79      2750620.57      6877992.47
      2750409.55       6877996.4
#Sta/Elev= 30
    4805  460.03  4848.8  459.21  4888.8  458.07  4908.8  457.78  4918.8  457.14
  4928.8  455.56  4938.8  457.36  4948.8  456.31  4968.8  455.33  4978.8  454.44
  4998.8  453.18    5004  452.23    5009  452.23  5016.8  451.75  5017.1  451.25
  5020.6  451.25  5020.8  451.75  5028.8  452.22  5038.8  453.07  5048.8  453.59
  5058.8  453.77  5068.8  454.33  5078.8  454.58  5098.8  455.58  5128.8  456.83
  5178.8  458.66  5188.7  459.28  5193.7  459.27  5198.8  459.59  5215.3  460.18
#Mann= 3 ,-1 , 0
    4805     .05       0  5016.8     .04       0  5020.8     .05       0
Bank Sta=5016.8,5020.8
XS Rating Curve= 0 ,0
Exp/Cntr=0.3,0.1

Type RM Length L Ch R = 1 ,871     ,197,197,197
BEGIN DESCRIPTION:
Lacy 020 3107
END DESCRIPTION:
XS GIS Cut Line= 3
      2750842.96      6877897.83      2750625.19      6877892.57
      2750376.16      6877903.44
#Sta/Elev= 30
  4783.2  460.82  4800.2  459.83  4862.1  457.62  4890.2  456.37  4900.2  455.75
  4910.2  455.79  4920.2  455.57  4930.2   454.7  4940.2  455.56  4950.2  453.99
  4970.2  453.53  4980.2  452.59  4990.2  451.91  4998.1  451.49  5003.1  451.49
  5010.2   450.7  5018.2  450.58  5018.5  450.08    5022  450.08  5022.2  450.58
  5030.2  450.59  5077.5  453.54  5082.5  453.55  5100.3  454.61  5120.3  455.32
  5190.4   458.5  5210.4  458.87  5240.4  460.03  5247.9  460.62  5250.3  460.62
#Mann= 3 ,-1 , 0
  4783.2     .05       0  5018.2     .04       0  5022.2     .05       0
Bank Sta=5018.2,5022.2
XS Rating Curve= 0 ,0
Exp/Cntr=0.3,0.1

Type RM Length L Ch R = 1 ,674     ,126,126,126
BEGIN DESCRIPTION:
Lacy 020 3106
END DESCRIPTION:
XS GIS Cut Line= 3
      2750818.88      6877711.52      2750623.35       6877695.1
      2750440.17      6877703.61
#Sta/Elev= 30
  4806.7  457.48  4810.7  457.48  4849.7  456.05  4859.8  455.36  4868.7  454.91
  4873.7  454.86  4889.9  453.73  4909.9  452.67    4930  451.27  4940.1   451.7
  4950.1   450.7  4960.1  449.26  4970.2  448.73  4980.2  448.36  4988.7  448.49
  4991.7  448.24    4992  447.74  4995.5  447.74  4995.7  448.24  4999.1  448.53
  5002.9  448.53  5010.3  449.33  5050.3  450.49  5080.4  452.07  5100.4   452.8
  5120.4  453.37  5130.4  454.11  5160.4  455.66  5180.5  456.48  5186.3  456.97
#Mann= 3 ,-1 , 0
  4806.7     .05       0  4991.7     .04       0  4995.7     .05       0
Bank Sta=4991.7,4995.7
XS Rating Curve= 0 ,0
Exp/Cntr=0.3,0.1

Type RM Length L Ch R = 1 ,548     ,123,123,123
BEGIN DESCRIPTION:
Lacy 020 3105
END DESCRIPTION:
XS GIS Cut Line= 3
      2750832.11      6877619.62        2750622.      6877569.08
       2750421.4      6877579.82
#Sta/Elev= 30
  4788.3     456  4794.6  455.98  4835.7  454.69  4843.7  454.19  4848.9  454.04
  4856.3  453.49  4876.9  452.74  4885.7  452.06  4890.8  451.86  4907.7  450.81
  4938.6  448.31  4948.9  448.47  4969.4  447.57  4972.7  446.96    4973  446.46
  4976.5  446.46  4976.7  446.96  5004.4  447.08  5010.4  447.71  5030.4  448.21
  5060.5  449.59  5070.5  450.19  5080.5  450.57  5110.6  452.45  5129.7  453.31
  5134.7   453.4  5140.6  453.92  5190.7  456.64  5200.5  457.13  5205.3  457.13
#Mann= 3 ,-1 , 0
  4788.3     .05       0  4972.7     .04       0  4976.7     .05       0
Bank Sta=4972.7,4976.7
XS Rating Curve= 0 ,0
Exp/Cntr=0.3,0.1

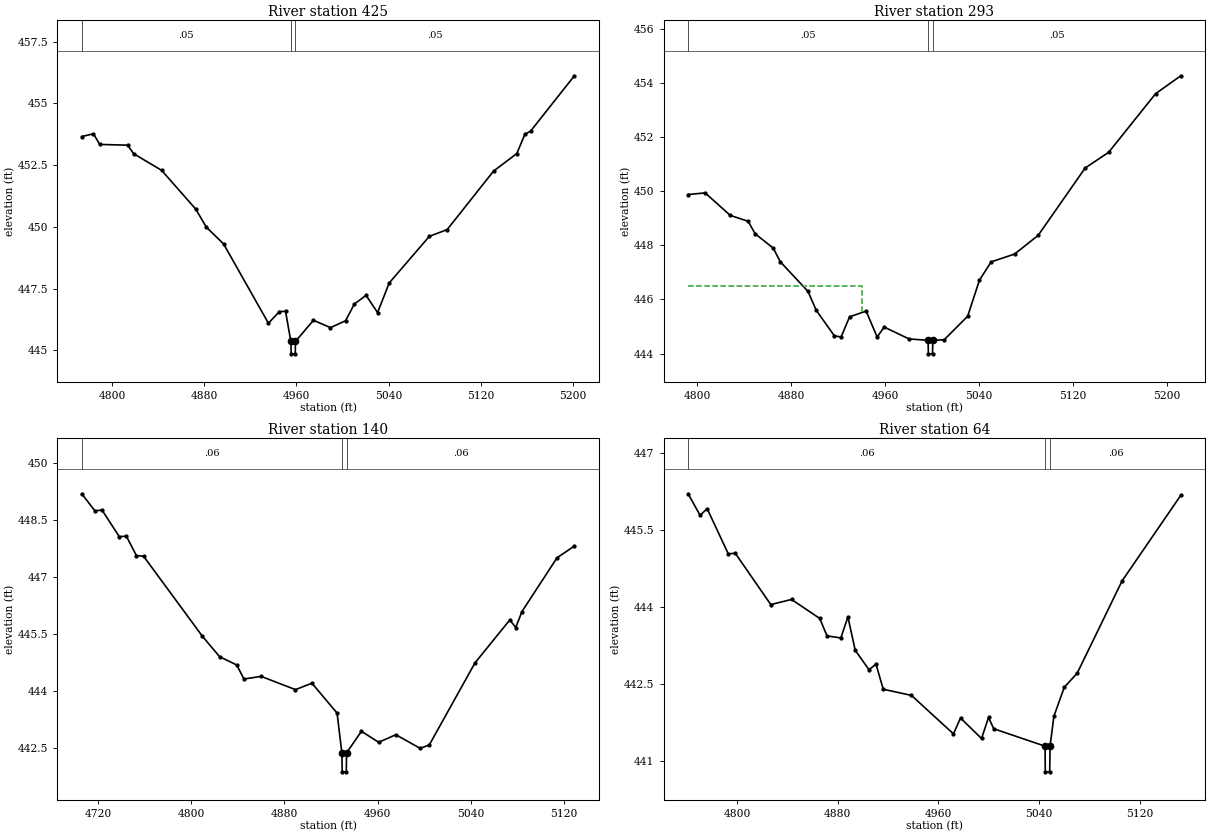
Type RM Length L Ch R = 1 ,425     ,132,132,132
BEGIN DESCRIPTION:
Lacy 020 3112
END DESCRIPTION:
XS GIS Cut Line= 3
      2750836.45      6877531.41      2750626.31      6877447.16
      2750426.31      6877470.83
#Sta/Elev= 30
  4773.6  453.66  4783.8  453.77  4789.2  453.34  4813.4  453.31  4818.8  452.96
    4843  452.29  4872.6  450.72  4881.8  449.99  4896.8  449.31  4935.7   446.1
  4945.2  446.57  4950.6  446.58  4955.2  445.36  4955.5  444.86    4959  444.86
  4959.2  445.36  4974.8  446.22  4989.6  445.92  5002.7   446.2  5010.4  446.88
  5020.5  447.23  5030.5  446.53  5040.6  447.73  5075.5  449.62  5090.9  449.89
  5131.2  452.26  5151.4  452.97  5158.4  453.75  5163.4  453.88  5201.4  456.12
#Mann= 3 ,-1 , 0
  4773.6     .05       0  4955.2     .04       0  4959.2     .05       0
Bank Sta=4955.2,4959.2
XS Rating Curve= 0 ,0
Exp/Cntr=0.3,0.1

Type RM Length L Ch R = 1 ,293     ,153,153,153
BEGIN DESCRIPTION:
Lacy 020 3111
END DESCRIPTION:
XS GIS Cut Line= 3
      2750802.68      6877424.07      2750626.34      6877314.52
      2750414.64      6877315.99
#Sta/Elev= 30
  4792.4  449.88  4806.9  449.94  4828.2  449.11  4843.5  448.89  4849.4  448.43
  4864.8   447.9  4870.9  447.39  4894.4   446.3  4901.4   445.6  4916.8  444.66
  4922.6  444.61  4929.8  445.36  4943.9  445.57  4953.3  444.61  4959.2  444.98
  4980.5  444.54  4996.6  444.49  4996.9  443.99  5000.4  443.99  5000.6  444.49
  5010.3  444.51  5030.3  445.38  5040.3  446.71  5050.3  447.39  5070.3  447.68
  5090.3  448.37  5130.3  450.86  5150.3  451.44  5190.3  453.61  5211.7  454.27
#Mann= 3 ,-1 , 0
  4792.4     .05       0  4996.6     .04       0  5000.6     .05       0
#XS Ineff= 2 , 0
       0    4940   446.5               0
Permanent Ineff=
       F       F
Bank Sta=4996.6,5000.6
XS Rating Curve= 0 ,0
Exp/Cntr=0.3,0.1

Type RM Length L Ch R = 1 ,140     ,76,76,76
BEGIN DESCRIPTION:
Lacy 020 3110
END DESCRIPTION:
XS GIS Cut Line= 3
       2750799.9      6877401.89      2750629.48      6877162.44
      2750501.12      6877151.83
#Sta/Elev= 30
  4706.1   449.2  4717.4  448.75  4723.5  448.77  4738.3  448.07  4744.4  448.08
    4753  447.57  4759.2  447.55  4809.6  445.44  4824.4   444.9  4839.1  444.68
  4845.3  444.31    4860  444.38  4889.5  444.03  4903.6   444.2  4925.2  443.41
  4929.3  442.36  4929.6  441.86  4933.1  441.86  4933.3  442.36  4946.1  442.93
  4960.9  442.64  4975.6  442.84  4996.5  442.48  5004.3  442.57  5043.6  444.74
  5073.4  445.87  5078.5  445.67  5083.8  446.09  5113.9  447.51  5128.8  447.82
#Mann= 3 ,-1 , 0
  4706.1     .06       0  4929.3     .06       0  4933.3     .06       0
Bank Sta=4929.3,4933.3
XS Rating Curve= 0 ,0
Exp/Cntr=0.3,0.1

Type RM Length L Ch R = 1 ,64      ,0,0,0
BEGIN DESCRIPTION:
Lacy 020 3109
END DESCRIPTION:
XS GIS Cut Line= 3
       2750787.6       6877319.8      2750677.38      6877098.94
      2750534.81      6877124.06
#Sta/Elev= 30
  4761.1  446.21  4770.6  445.79  4776.2  445.92    4793  445.04  4798.6  445.05
  4826.8  444.05  4843.3  444.15  4865.7  443.78  4871.5  443.44  4882.5   443.4
  4888.1  443.81  4893.9  443.16  4904.9  442.78  4910.4  442.89  4916.2   442.4
  4938.6  442.28    4972  441.53  4977.6  441.84  4994.3  441.44  4999.9  441.85
    5004  441.63  5044.8  441.29    5045  440.79  5048.5  440.79  5048.8  441.29
  5051.8  441.87  5060.1  442.44  5070.3  442.71    5106  444.51  5152.7  446.18
#Mann= 3 ,-1 , 0
  4761.1     .06       0  5044.8     .06       0  5048.8     .06       0
Bank Sta=5044.8,5048.8
XS Rating Curve= 0 ,0
Exp/Cntr=0.3,0.1

Chan Stop Cuts=-1
Use User Specified Reach Order=0
Composite Channel Slope=5