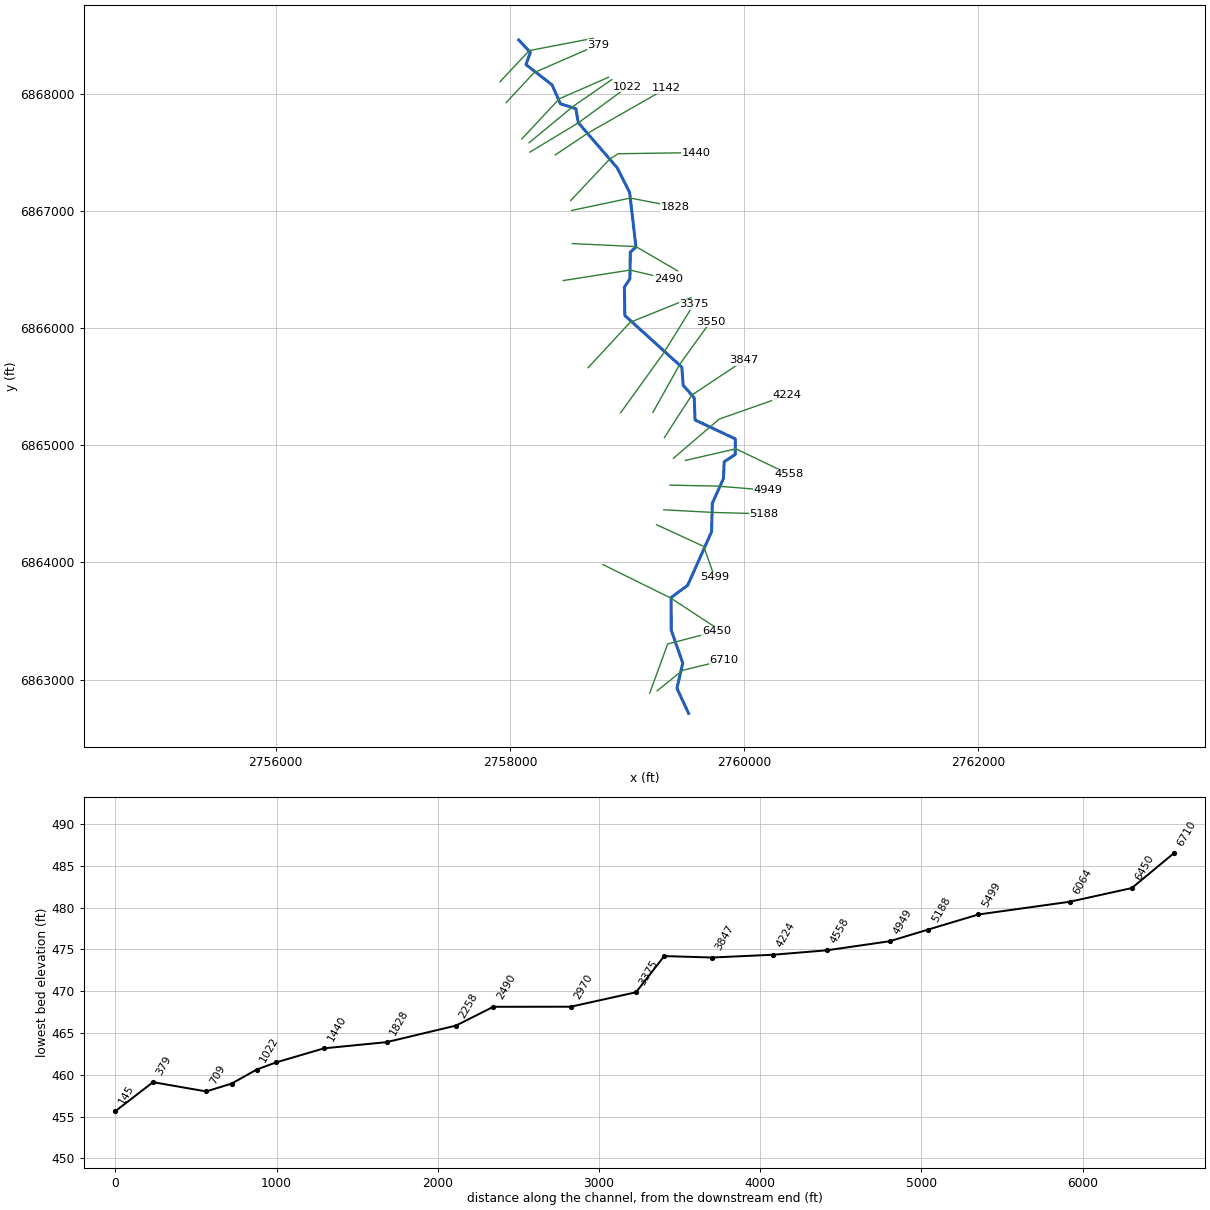
--- Lacy 023.prj (project) ---

Proj Title=Lacy 023 Base Level Engineering
Current Plan=p01
Default Exp/Contr=0.3,0.1
English Units
Geom File=g01
Flow File=f01
Plan File=p01
BEGIN DESCRIPTION:
Lacy 023
END DESCRIPTION:

--- Lacy 023.p01 (plan) ---

Plan Title=Multiple Run
Short Identifier=Multiple
Geom File=g01
Flow File=f01
Subcritical Flow
K Sum by GR= 0
Std Step Tol= 0.01
Critical Tol= 0.01
Num of Std Step Trials= 20
Max Error Tol= 0.3
Flow Tol Ratio= 0.001
Split Flow NTrial= 30
Split Flow Tol= 0.02
Split Flow Ratio= 0.02
Log Output Level= 0
Friction Slope Method= 1
Unsteady Friction Slope Method= 2
Unsteady Bridges Friction Slope Method= 1
Parabolic Critical Depth
Global Vel Dist=  1 , 1 , 1
Global Log Level= 0
CheckData=True
Encroach Param= -1, 0, 0, 0
BEGIN DESCRIPTION:
Multiple Run
END DESCRIPTION:

--- Lacy 023.f01 (steady flow) ---

Flow Title=Multiple
Number of Profiles=7
Profile Names=10-year,25-year,50-year,1pct_min,100-year,1pct_plu,500-year
River Rch & RM= Lacy 023,Reach-1,6710
     581     785     952     574    1146    2286    1664
River Rch & RM= Lacy 023,Reach-1,5188
     919    1264    1552     946    1888    3766    2797
Boundary for River Rch & Prof#=Lacy 023,Reach-1,1
Up Type=0
Dn Type=3
Dn Slope=0.005
Boundary for River Rch & Prof#=Lacy 023,Reach-1,2
Up Type=0
Dn Type=3
Dn Slope=0.005
Boundary for River Rch & Prof#=Lacy 023,Reach-1,3
Up Type=0
Dn Type=3
Dn Slope=0.005
Boundary for River Rch & Prof#=Lacy 023,Reach-1,4
Up Type=0
Dn Type=3
Dn Slope=0.005
Boundary for River Rch & Prof#=Lacy 023,Reach-1,5
Up Type=0
Dn Type=3
Dn Slope=0.005
Boundary for River Rch & Prof#=Lacy 023,Reach-1,6
Up Type=0
Dn Type=3
Dn Slope=0.005
Boundary for River Rch & Prof#=Lacy 023,Reach-1,7
Up Type=0
Dn Type=3
Dn Slope=0.005

--- Lacy 023.g01 (geometry) ---

Geom Title=Existing Conditions

River Reach=Lacy 023,Reach-1
Reach XY= 30
      2759526.00      6862711.00      2759426.24      6862925.10
      2759475.95      6863140.96      2759377.38      6863420.66
      2759376.99      6863700.72      2759517.98      6863804.66
      2759722.25      6864262.55      2759728.26      6864505.06
      2759823.61      6864716.53      2759829.49      6864859.73
      2759924.15      6864922.16      2759924.04      6865055.34
      2759581.03      6865216.08      2759573.82      6865405.55
      2759479.56      6865512.47      2759468.19      6865667.21
      2758981.45      6866108.53      2758977.22      6866350.50
      2759024.78      6866421.50      2759028.20      6866649.71
      2759076.42      6866692.40      2759022.24      6867159.44
      2758915.24      6867370.68      2758583.88      6867754.84
      2758562.76      6867874.72      2758431.45      6867916.25
      2758359.51      6868078.05      2758137.11      6868250.95
      2758174.19      6868354.90      2758076.00      6868461.00

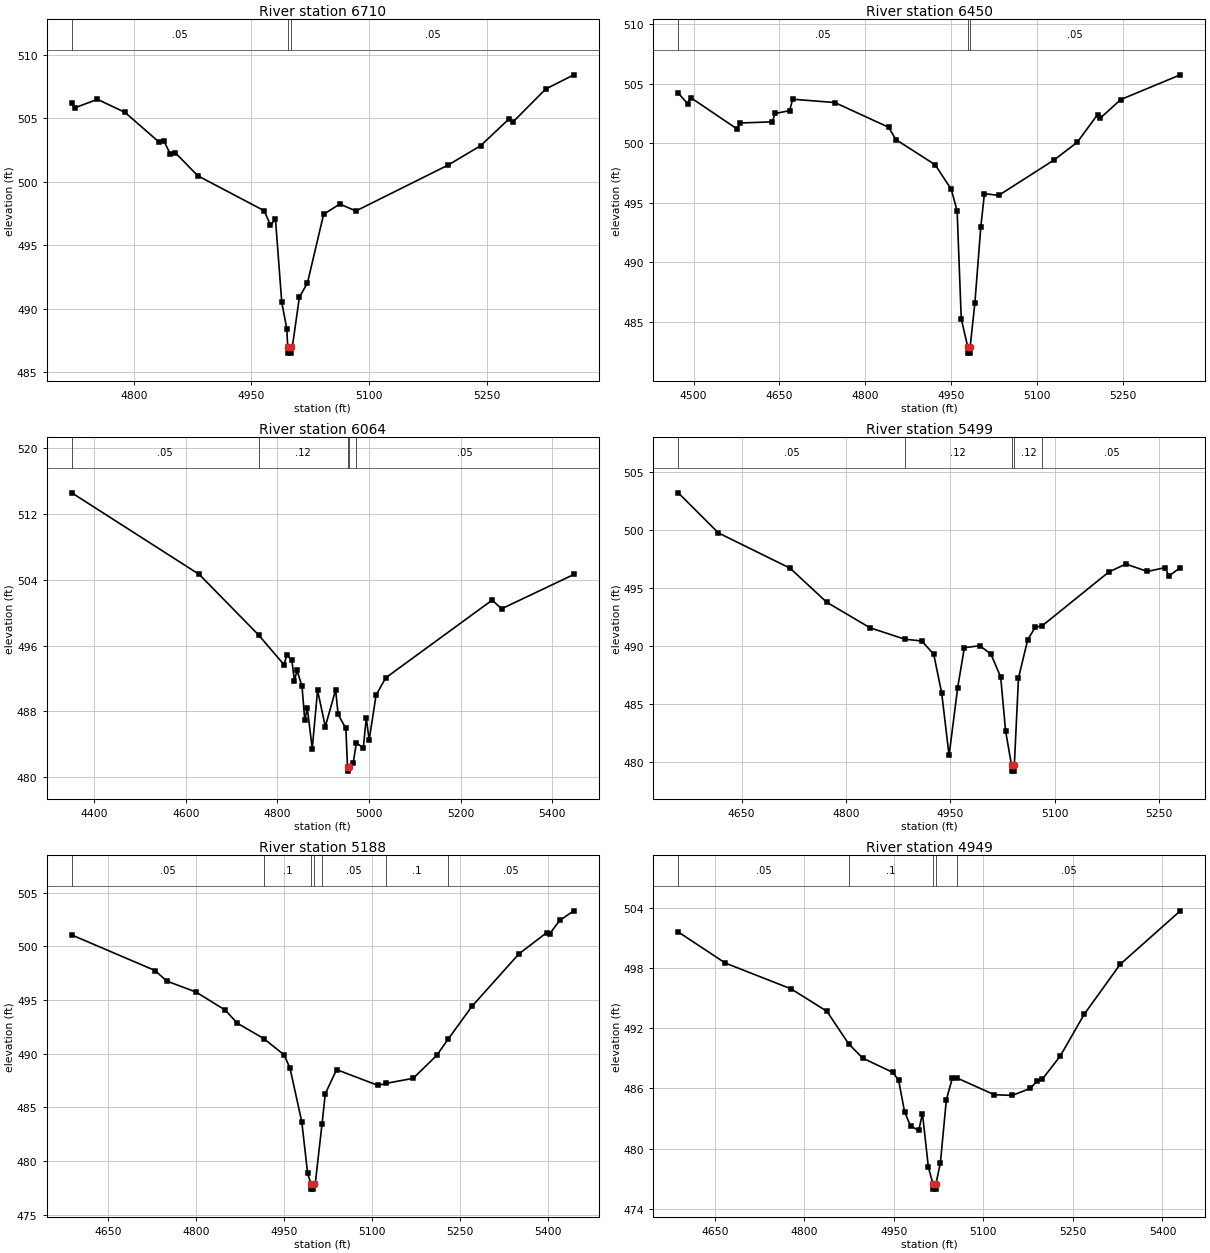
Type RM Length L Ch R = 1,6710,260,260,260
BEGIN DESCRIPTION:
Lacy 023 3203
END DESCRIPTION:
XS GIS Cut Line= 3
      2759257.56      6862903.87      2759473.52      6863077.99
      2759825.94      6863164.53
#Sta/Elev= 30
  4720.8  506.20  4724.7  505.83  4753.5  506.50  4788.7  505.47  4831.9  503.14
  4838.3  503.21  4846.2  502.22  4852.7  502.30  4881.4  500.48  4966.2  497.72
  4974.2  496.59  4980.6  497.04  4988.6  490.50  4995.0  488.43  4996.2  487.00
  4996.5  486.50  5000.0  486.50  5000.2  487.00  5002.1  487.00  5011.1  490.91
  5021.4  492.04  5042.0  497.44  5062.6  498.25  5083.1  497.70  5200.5  501.31
  5242.1  502.84  5278.5  504.96  5283.7  504.73  5325.2  507.31  5361.1  508.43
#Mann=3,-1,0
  4720.8    0.05       0  4996.2    0.04       0  5000.2    0.05       0
Bank Sta=4996.2,5000.2
Exp/Cntr=0.3,0.1

Type RM Length L Ch R = 1,6450,386,386,386
BEGIN DESCRIPTION:
Lacy 023 3202
END DESCRIPTION:
XS GIS Cut Line= 3
      2759194.17      6862884.15      2759346.89      6863303.50
      2759762.91      6863411.92
#Sta/Elev= 30
  4473.3  504.21  4489.6  503.31  4494.9  503.83  4576.0  501.19  4581.3  501.69
  4637.1  501.79  4642.5  502.49  4667.7  502.73  4673.0  503.69  4746.6  503.41
  4840.5  501.33  4853.1  500.30  4921.7  498.18  4949.7  496.12  4960.0  494.31
  4967.2  485.23  4978.7  482.85  4978.9  482.35  4982.4  482.35  4982.7  482.85
  4991.0  486.57  5001.3  492.95  5007.7  495.76  5032.3  495.60  5129.1  498.58
  5169.6  500.07  5205.0  502.39  5210.1  502.11  5245.5  503.66  5349.5  505.74
#Mann=3,-1,0
  4473.3    0.05       0  4978.7    0.04       0  4982.7    0.05       0
Bank Sta=4978.7,4982.7
Exp/Cntr=0.3,0.1

Type RM Length L Ch R = 1,6064,565,565,565
BEGIN DESCRIPTION:
Lacy 023 3200
END DESCRIPTION:
XS GIS Cut Line= 3
      2758795.23      6863981.03      2759372.53      6863696.38
      2759750.75      6863448.45
#Sta/Elev= 30
  4351.0  514.59  4629.4  504.65  4759.2  497.26  4814.6  493.64  4820.2  494.88
  4831.3  494.21  4837.1  491.72  4842.6  492.98  4853.6  491.03  4859.5  486.90
  4865.1  488.37  4875.9  483.46  4887.5  490.55  4904.4  486.13  4926.9  490.60
  4932.4  487.61  4949.3  485.90  4952.9  481.21  4953.2  480.71  4956.9  481.21
  4965.1  481.65  4972.2  484.13  4987.4  483.56  4993.8  487.19  5000.1  484.48
  5015.2  489.96  5036.3  492.07  5268.4  501.52  5289.5  500.48  5446.9  504.65
#Mann=5,-1,0
  4351.0    0.05       0  4759.2    0.12       0  4952.9    0.04       0
  4956.9    0.12       0  4972.2    0.05       0
Bank Sta=4952.9,4956.9
Exp/Cntr=0.3,0.1

Type RM Length L Ch R = 1,5499,311,311,311
BEGIN DESCRIPTION:
Lacy 023 3199
END DESCRIPTION:
XS GIS Cut Line= 3
      2759252.19      6864321.83      2759654.65      6864137.09
      2759747.86      6863874.27
#Sta/Elev= 30
  4558.9  503.19  4616.7  499.73  4719.7  496.69  4772.2  493.76  4834.6  491.55
  4884.5  490.57  4909.1  490.41  4926.2  489.26  4937.6  485.92  4948.2  480.54
  4960.6  486.40  4970.2  489.84  4992.2  490.00  5008.2  489.30  5022.4  487.31
  5029.4  482.68  5038.0  479.69  5038.3  479.19  5041.8  479.19  5042.0  479.69
  5048.0  487.23  5061.3  490.53  5071.9  491.58  5082.4  491.74  5178.0  496.37
  5202.4  497.05  5233.2  496.41  5258.8  496.74  5264.1  496.01  5280.6  496.74
#Mann=5,-1,0
  4558.9    0.05       0  4884.5    0.12       0  5038.0    0.07       0
  5042.0    0.12       0  5082.4    0.05       0
Bank Sta=5038,5042
Exp/Cntr=0.3,0.1

Type RM Length L Ch R = 1,5188,239,239,239
BEGIN DESCRIPTION:
Lacy 023 3197
END DESCRIPTION:
XS GIS Cut Line= 3
      2759314.25      6864449.40      2759726.84      6864427.20
      2760169.88      6864414.76
#Sta/Elev= 30
  4587.9  501.06  4729.9  497.75  4749.9  496.77  4800.0  495.74  4850.0  494.05
  4870.1  492.85  4915.4  491.41  4950.2  489.89  4960.2  488.64  4980.2  483.67
  4990.2  478.86  4995.8  477.89  4996.3  477.39  5000.0  477.39  5000.6  477.89
  5003.2  477.89  5014.7  483.43  5020.3  486.27  5039.6  488.52  5110.3  487.05
  5123.1  487.23  5170.3  487.71  5210.3  489.84  5229.6  491.34  5270.3  494.40
  5350.4  499.29  5397.8  501.27  5402.8  501.15  5420.4  502.43  5444.3  503.31
#Mann=7,-1,0
  4587.9    0.05       0  4915.4     0.1       0  4995.8    0.07       0
  5000.6     0.1       0  5014.7    0.05       0  5123.1     0.1       0
  5229.6    0.05       0
Bank Sta=4995.8,5000.6
Exp/Cntr=0.3,0.1

Type RM Length L Ch R = 1,4949,391,391,391
BEGIN DESCRIPTION:
Lacy 023 3198
END DESCRIPTION:
XS GIS Cut Line= 3
      2759367.02      6864660.06      2759769.80      6864651.66
      2760206.62      6864616.47
#Sta/Elev= 30
  4588.8  501.57  4667.8  498.47  4777.8  495.91  4837.8  493.68  4874.2  490.45
  4897.8  489.02  4947.9  487.61  4957.9  486.85  4967.9  483.70  4977.9  482.27
  4991.7  481.83  4997.9  483.51  5007.9  478.16  5015.6  476.49  5016.1  475.99
  5019.8  475.99  5020.4  476.49  5028.0  478.62  5038.0  484.90  5048.1  487.04
  5056.3  487.03  5118.3  485.38  5148.4  485.31  5178.5  486.01  5190.1  486.74
  5198.5  486.91  5228.6  489.21  5268.8  493.37  5329.0  498.34  5429.9  503.67
#Mann=5,-1,0
  4588.8    0.05       0  4874.2     0.1       0  5015.6    0.07       0
  5020.4     0.1       0  5056.3    0.05       0
Bank Sta=5015.6,5020.4
Exp/Cntr=0.3,0.1

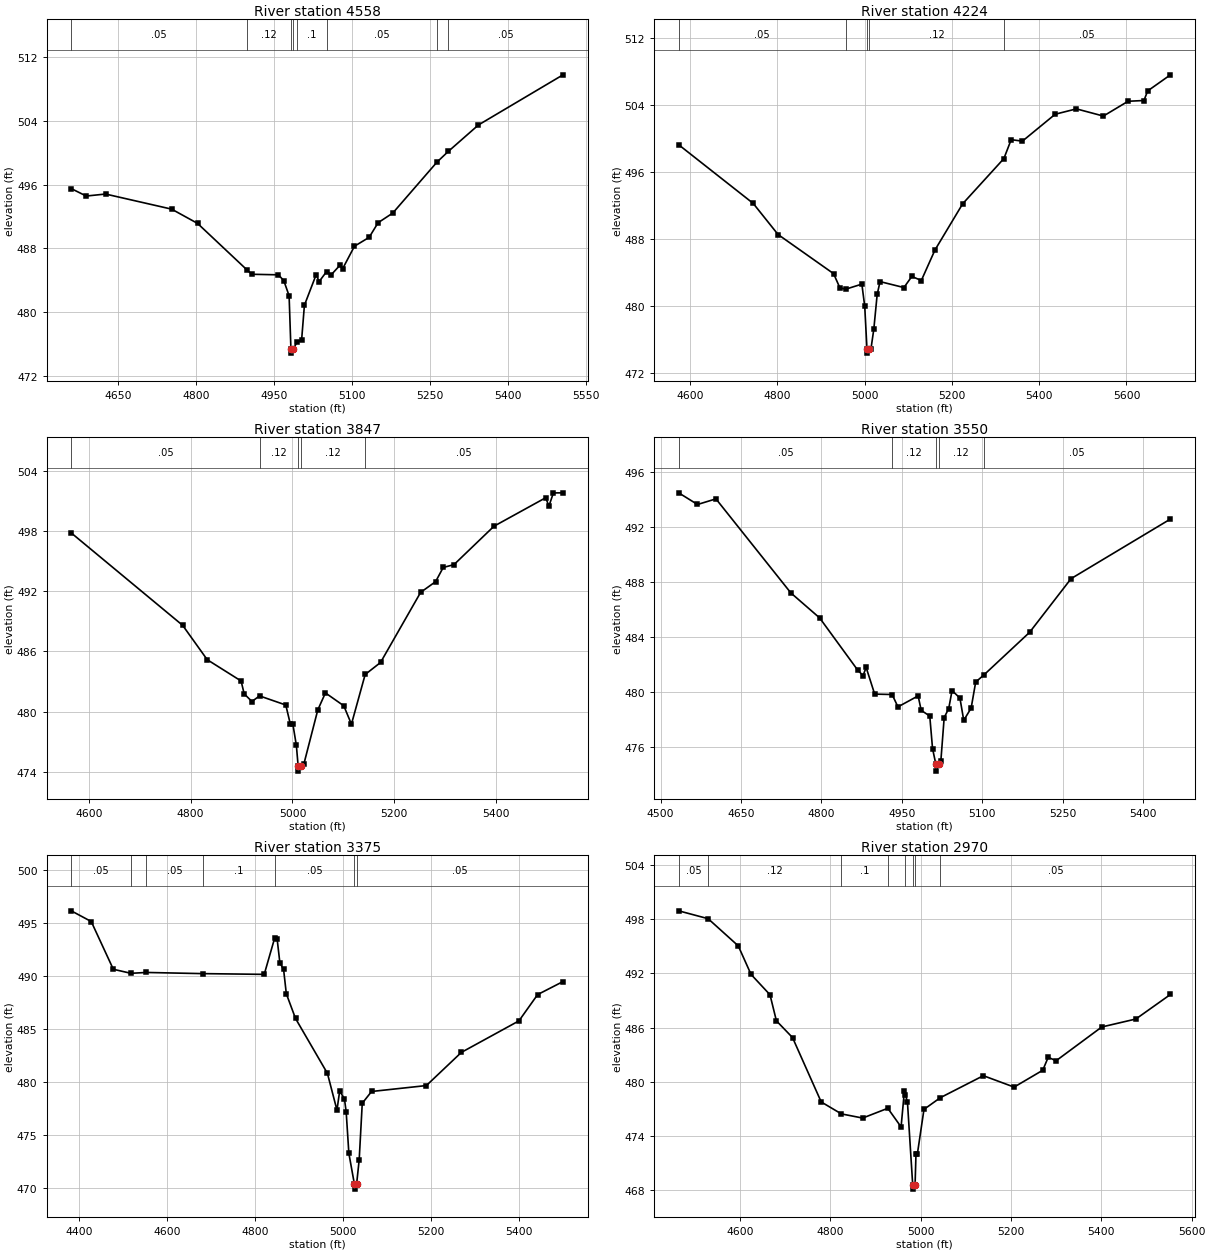
Type RM Length L Ch R = 1,4558,334,334,334
BEGIN DESCRIPTION:
Lacy 023 3196
END DESCRIPTION:
XS GIS Cut Line= 3
      2759497.95      6864871.01      2759929.38      6864969.88
      2760382.47      6864753.08
#Sta/Elev= 30
  4560.6  495.49  4589.4  494.56  4626.5  494.81  4753.5  492.92  4803.2  491.14
  4898.2  485.32  4907.4  484.77  4958.7  484.70  4969.0  483.97  4979.2  482.08
  4982.7  475.40  4983.2  474.90  4987.5  475.40  4994.2  476.29  5003.2  476.52
  5008.6  480.89  5031.3  484.74  5036.8  483.85  5051.3  485.11  5059.5  484.66
  5076.6  485.88  5082.2  485.48  5104.8  488.28  5133.0  489.39  5150.2  491.22
  5178.4  492.43  5263.4  498.81  5285.0  500.14  5343.1  503.46  5505.5  509.73
#Mann=8,-1,0
  4560.6    0.05       0  4898.2    0.12       0  4982.7    0.07       0
  4987.5    0.12       0  4994.2     0.1       0  5051.3    0.05       0
  5263.4     0.1       0  5285.0    0.05       0
Bank Sta=4982.7,4987.5
Exp/Cntr=0.3,0.1

Type RM Length L Ch R = 1,4224,377,377,377
BEGIN DESCRIPTION:
Lacy 023 3195
END DESCRIPTION:
XS GIS Cut Line= 3
      2759396.24      6864889.31      2759786.66      6865223.57
      2760365.17      6865427.33
#Sta/Elev= 30
  4573.5  499.28  4744.3  492.27  4801.3  488.55  4928.6  483.87  4942.9  482.19
  4956.1  482.01  4993.4  482.62  5000.0  479.96  5005.1  474.87  5005.7  474.37
  5010.1  474.87  5014.3  474.89  5020.8  477.23  5028.5  481.38  5035.1  482.92
  5089.8  482.21  5108.0  483.54  5129.7  483.05  5161.0  486.70  5224.6  492.23
  5319.0  497.63  5335.7  499.89  5361.4  499.71  5436.6  502.93  5485.2  503.57
  5547.1  502.71  5603.7  504.48  5640.0  504.57  5648.7  505.72  5700.8  507.64
#Mann=5,-1,0
  4573.5    0.05       0  4956.1    0.12       0  5005.1    0.07       0
  5010.1    0.12       0  5319.0    0.05       0
Bank Sta=5005.1,5010.1
Exp/Cntr=0.3,0.1

Type RM Length L Ch R = 1,3847,297,297,297
BEGIN DESCRIPTION:
Lacy 023 3194
END DESCRIPTION:
XS GIS Cut Line= 3
      2759319.23      6865066.65      2759552.65      6865428.27
      2759999.05      6865724.95
#Sta/Elev= 30
  4565.3  497.85  4784.3  488.61  4832.5  485.18  4899.1  483.05  4905.1  481.77
  4920.3  481.00  4935.3  481.56  4986.9  480.65  4995.7  478.77  5000.7  478.77
  5007.7  476.61  5011.2  474.54  5011.8  474.04  5016.3  474.54  5022.7  474.80
  5049.8  480.16  5064.8  481.86  5100.9  480.57  5115.9  478.73  5142.9  483.70
  5173.1  484.90  5251.9  491.91  5281.3  492.98  5296.3  494.40  5317.4  494.68
  5396.0  498.52  5497.7  501.37  5504.0  500.53  5512.8  501.85  5531.7  501.86
#Mann=5,-1,0
  4565.3    0.05       0  4935.3    0.12       0  5011.2    0.07       0
  5016.3    0.12       0  5142.9    0.05       0
Bank Sta=5011.2,5016.3
Exp/Cntr=0.3,0.1

Type RM Length L Ch R = 1,3550,175,175,175
BEGIN DESCRIPTION:
Lacy 023 3191
END DESCRIPTION:
XS GIS Cut Line= 3
      2759220.46      6865280.33      2759452.54      6865695.12
      2759711.32      6866053.82
#Sta/Elev= 30
  4533.8  494.48  4568.9  493.63  4603.3  494.04  4743.1  487.19  4796.8  485.37
  4867.6  481.58  4877.8  481.17  4883.6  481.76  4899.5  479.82  4932.1  479.79
  4942.9  478.89  4980.6  479.69  4986.3  478.64  5002.3  478.22  5007.5  475.85
  5013.7  474.71  5014.4  474.21  5018.9  474.71  5023.0  474.95  5029.2  478.11
  5037.7  478.77  5043.9  480.08  5058.6  479.53  5065.7  477.91  5079.5  478.80
  5088.0  480.70  5102.9  481.20  5188.6  484.32  5266.0  488.23  5451.4  492.57
#Mann=5,-1,0
  4533.8    0.05       0  4932.1    0.12       0  5013.7    0.07       0
  5018.9    0.12       0  5102.9    0.05       0
Bank Sta=5013.7,5018.9
Exp/Cntr=0.3,0.1

Type RM Length L Ch R = 1,3375,405,405,405
BEGIN DESCRIPTION:
Lacy 023 3192
END DESCRIPTION:
XS GIS Cut Line= 3
      2758945.24      6865277.91      2759309.11      6865782.54
      2759571.32      6866205.40
#Sta/Elev= 30
  4381.4  496.16  4426.9  495.15  4477.2  490.64  4517.2  490.26  4552.4  490.34
  4681.1  490.23  4820.8  490.16  4844.9  493.64  4850.2  493.49  4856.4  491.26
  4864.9  490.62  4871.1  488.33  4892.0  486.00  4964.7  480.81  4986.4  477.34
  4992.6  479.15  5003.5  478.39  5007.4  477.17  5013.5  473.26  5026.0  470.38
  5026.7  469.88  5031.2  470.38  5037.0  472.64  5044.0  477.99  5065.2  479.10
  5190.0  479.66  5269.6  482.79  5400.8  485.77  5443.3  488.25  5501.1  489.48
#Mann=7,-1,0
  4381.4    0.05       0  4517.2     0.1       0  4552.4    0.05       0
  4681.1     0.1       0  4844.9    0.05       0  5026.0    0.05       0
  5031.2    0.05       0
Bank Sta=5026,5031.2
Exp/Cntr=0.3,0.1

Type RM Length L Ch R = 1,2970,480,480,480
BEGIN DESCRIPTION:
Lacy 023 3193
END DESCRIPTION:
XS GIS Cut Line= 3
      2758667.94      6865662.97      2759027.32      6866050.58
      2759547.04      6866260.28
#Sta/Elev= 30
  4464.0  498.89  4529.2  498.02  4595.9  495.02  4624.2  491.87  4666.2  489.62
  4680.4  486.74  4716.1  484.89  4779.6  477.78  4824.3  476.46  4871.4  476.00
  4927.1  477.08  4956.5  475.02  4963.8  478.96  4966.2  478.54  4970.6  477.77
  4982.2  468.65  4982.9  468.15  4987.5  468.65  4989.5  472.04  4992.6  472.04
  5007.2  476.96  5043.4  478.25  5138.7  480.68  5206.8  479.42  5270.2  481.28
  5282.3  482.71  5299.8  482.33  5400.9  486.06  5476.4  486.94  5553.0  489.65
#Mann=8,-1,0
  4464.0    0.05       0  4529.2    0.12       0  4824.3     0.1       0
  4927.1    0.05       0  4966.2    0.12       0  4982.2    0.07       0
  4987.5    0.12       0  5043.4    0.05       0
Bank Sta=4982.2,4987.5
Exp/Cntr=0.3,0.1

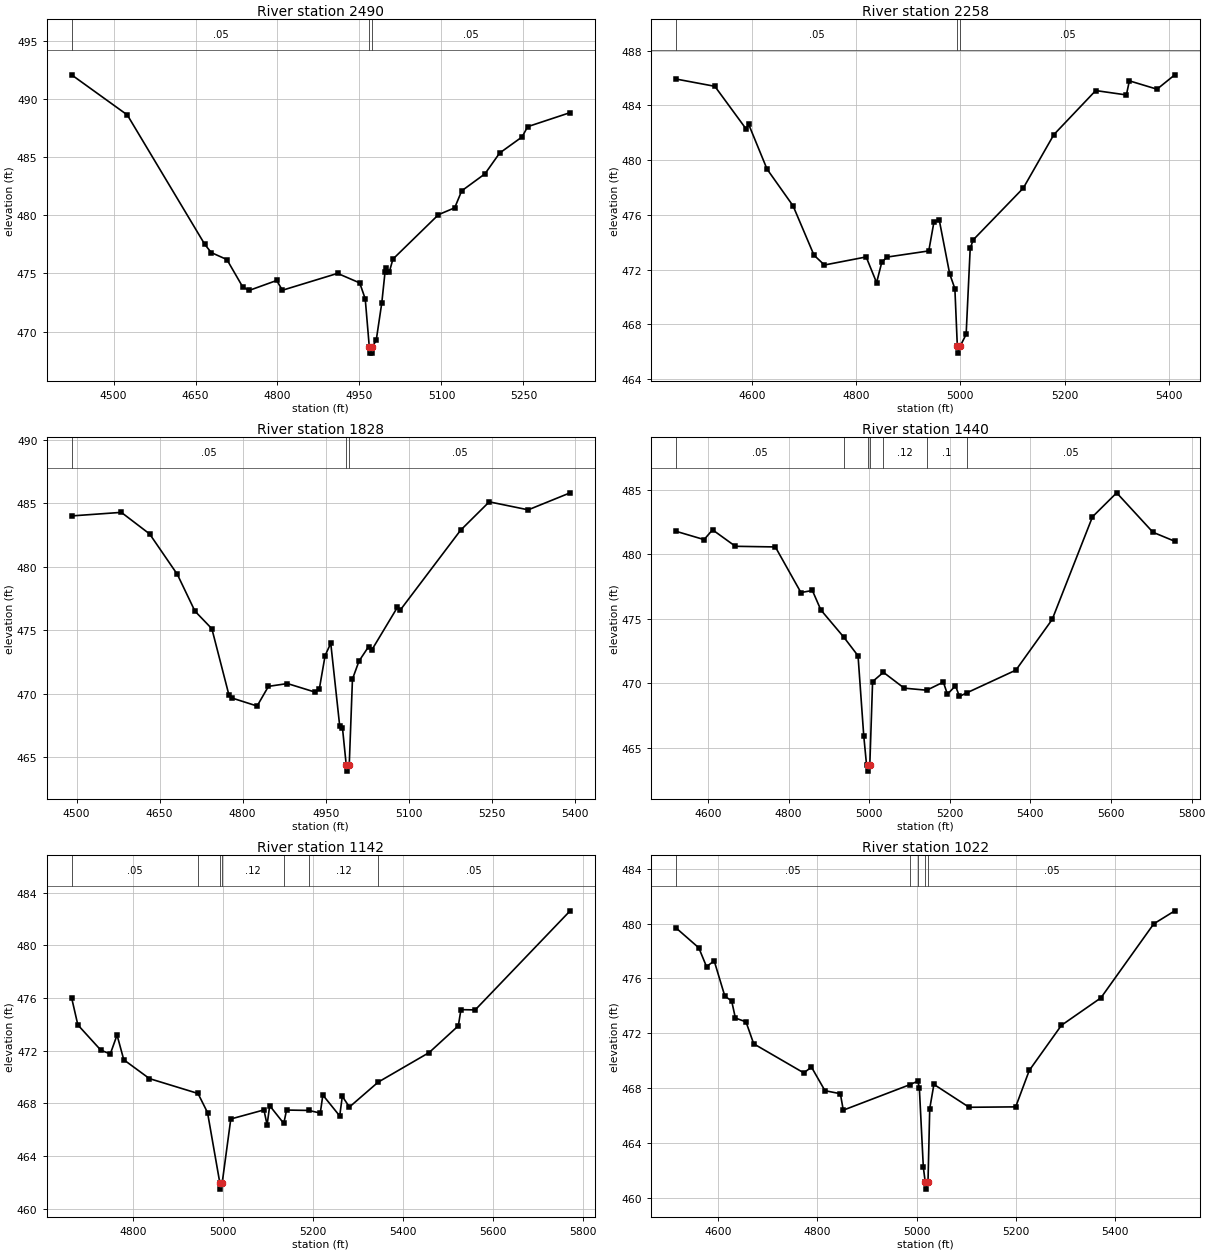
Type RM Length L Ch R = 1,2490,232,232,232
BEGIN DESCRIPTION:
Lacy 023 3190
END DESCRIPTION:
XS GIS Cut Line= 3
      2758455.34      6866406.81      2759025.61      6866496.48
      2759351.63      6866420.18
#Sta/Elev= 30
  4423.3  492.08  4525.2  488.63  4666.9  477.50  4678.8  476.79  4707.4  476.19
  4736.3  473.84  4747.9  473.53  4798.5  474.39  4809.0  473.55  4909.9  475.00
  4950.4  474.18  4960.5  472.81  4968.0  468.64  4968.7  468.14  4972.5  468.14
  4973.3  468.64  4980.7  469.27  4990.8  472.46  4996.7  475.10  4999.0  475.45
  5004.4  475.10  5011.2  476.23  5094.5  480.05  5124.2  480.64  5137.0  482.10
  5179.5  483.56  5206.4  485.35  5247.5  486.74  5257.7  487.62  5335.4  488.83
#Mann=3,-1,0
  4423.3    0.05       0  4968.0    0.04       0  4973.3    0.05       0
Bank Sta=4968,4973.3
Exp/Cntr=0.3,0.1

Type RM Length L Ch R = 1,2258,430,430,430
BEGIN DESCRIPTION:
Lacy 023 3189
END DESCRIPTION:
XS GIS Cut Line= 3
      2758532.01      6866722.56      2759075.77      6866696.87
      2759432.07      6866489.74
#Sta/Elev= 30
  4454.9  485.92  4529.0  485.39  4589.0  482.27  4594.0  482.60  4629.1  479.34
  4679.1  476.65  4719.2  473.05  4739.2  472.33  4819.3  472.92  4839.3  471.04
  4849.3  472.54  4859.3  472.91  4939.4  473.36  4949.4  475.49  4959.5  475.62
  4979.5  471.69  4989.5  470.60  4994.2  466.39  4995.0  465.89  4999.5  466.39
  5011.1  467.26  5018.9  473.55  5024.7  474.17  5120.7  477.95  5179.4  481.86
  5259.7  485.08  5318.5  484.76  5324.3  485.79  5377.3  485.18  5411.4  486.23
#Mann=3,-1,0
  4454.9    0.05       0  4994.2    0.05       0  4999.5    0.05       0
Bank Sta=4994.2,4999.5
Exp/Cntr=0.3,0.1

Type RM Length L Ch R = 1,1828,388,388,388
BEGIN DESCRIPTION:
Lacy 023 3187
END DESCRIPTION:
XS GIS Cut Line= 3
      2758528.17      6867005.61      2759027.67      6867111.33
      2759410.36      6867037.55
#Sta/Elev= 30
  4491.1  484.02  4580.9  484.30  4632.0  482.60  4682.1  479.41  4713.8  476.52
  4744.4  475.13  4775.1  469.93  4781.5  469.66  4826.1  469.04  4846.6  470.59
  4880.9  470.81  4930.6  470.14  4938.6  470.42  4948.9  473.01  4959.1  473.99
  4975.2  467.49  4980.3  467.30  4987.0  464.41  4987.8  463.91  4992.5  464.41
  4998.3  471.16  5010.1  472.58  5027.6  473.73  5032.7  473.42  5079.5  476.82
  5084.6  476.60  5193.5  482.89  5245.3  485.13  5315.7  484.50  5391.4  485.84
#Mann=3,-1,0
  4491.1    0.05       0  4987.0    0.04       0  4992.5    0.05       0
Bank Sta=4987,4992.5
Exp/Cntr=0.3,0.1

Type RM Length L Ch R = 1,1440,298,298,298
BEGIN DESCRIPTION:
Lacy 023 3188
END DESCRIPTION:
XS GIS Cut Line= 4
      2758519.33      6867090.24      2758848.44      6867440.33
      2758924.30      6867489.80      2759590.17      6867499.57
#Sta/Elev= 30
  4521.2  481.78  4590.3  481.14  4611.3  481.90  4668.0  480.62  4767.1  480.57
  4830.6  477.03  4859.0  477.19  4880.0  475.68  4937.4  473.55  4972.3  472.12
  4986.4  465.93  4993.3  463.68  4996.0  463.67  4996.8  463.17  5001.5  463.67
  5008.4  470.12  5035.2  470.84  5086.8  469.61  5142.7  469.45  5184.0  470.08
  5194.0  469.14  5214.0  469.79  5224.0  468.97  5241.7  469.24  5364.0  471.01
  5454.0  474.94  5554.0  482.91  5614.0  484.77  5704.0  481.71  5758.2  481.01
#Mann=7,-1,0
  4521.2    0.05       0  4937.4     0.1       0  4996.0    0.07       0
  5001.5     0.1       0  5035.2    0.12       0  5142.7     0.1       0
  5241.7    0.05       0
Bank Sta=4996,5001.5
Exp/Cntr=0.3,0.1

Type RM Length L Ch R = 1,1142,120,120,120
BEGIN DESCRIPTION:
Lacy 023 3186
END DESCRIPTION:
XS GIS Cut Line= 3
      2758387.33      6867479.63      2758665.30      6867665.89
      2759337.23      6868048.85
#Sta/Elev= 30
  4662.7  476.03  4676.6  473.96  4727.7  472.04  4748.7  471.75  4763.7  473.19
  4778.7  471.31  4835.7  469.88  4943.6  468.75  4964.8  467.30  4992.0  461.98
  4992.8  461.48  4997.5  461.98  5016.5  466.81  5090.2  467.50  5097.2  466.36
  5103.0  467.82  5134.3  466.47  5140.4  467.49  5189.8  467.46  5215.4  467.26
  5221.1  468.63  5258.6  467.04  5264.3  468.53  5280.2  467.72  5344.0  469.61
  5457.4  471.86  5522.2  473.89  5528.0  475.12  5559.7  475.10  5770.7  482.63
#Mann=7,-1,0
  4662.7    0.05       0  4943.6    0.12       0  4992.0    0.07       0
  4997.5    0.12       0  5134.3     0.1       0  5189.8    0.12       0
  5344.0    0.05       0
Bank Sta=4992,4997.5
Exp/Cntr=0.3,0.1

Type RM Length L Ch R = 1,1022,155,155,155
BEGIN DESCRIPTION:
Lacy 023 3185
END DESCRIPTION:
XS GIS Cut Line= 3
      2758170.39      6867503.46      2758586.99      6867755.20
      2759004.50      6868061.54
#Sta/Elev= 30
  4515.8  479.67  4561.3  478.23  4576.8  476.86  4592.3  477.28  4613.7  474.71
  4627.5  474.35  4635.0  473.11  4656.4  472.83  4671.9  471.23  4772.8  469.11
  4788.3  469.53  4815.5  467.81  4846.5  467.59  4852.4  466.39  4985.9  468.24
  5002.9  468.51  5005.7  468.00  5013.7  462.23  5017.6  461.13  5018.4  460.63
  5023.1  461.13  5026.6  466.50  5035.0  468.27  5106.0  466.60  5199.8  466.63
  5227.2  469.29  5292.0  472.58  5371.5  474.58  5478.0  479.98  5520.4  480.93
#Mann=5,-1,0
  4515.8    0.05       0  4985.9    0.12       0  5002.9    0.05       0
  5017.6    0.07       0  5023.1    0.05       0
Bank Sta=5017.6,5023.1
Exp/Cntr=0.3,0.1

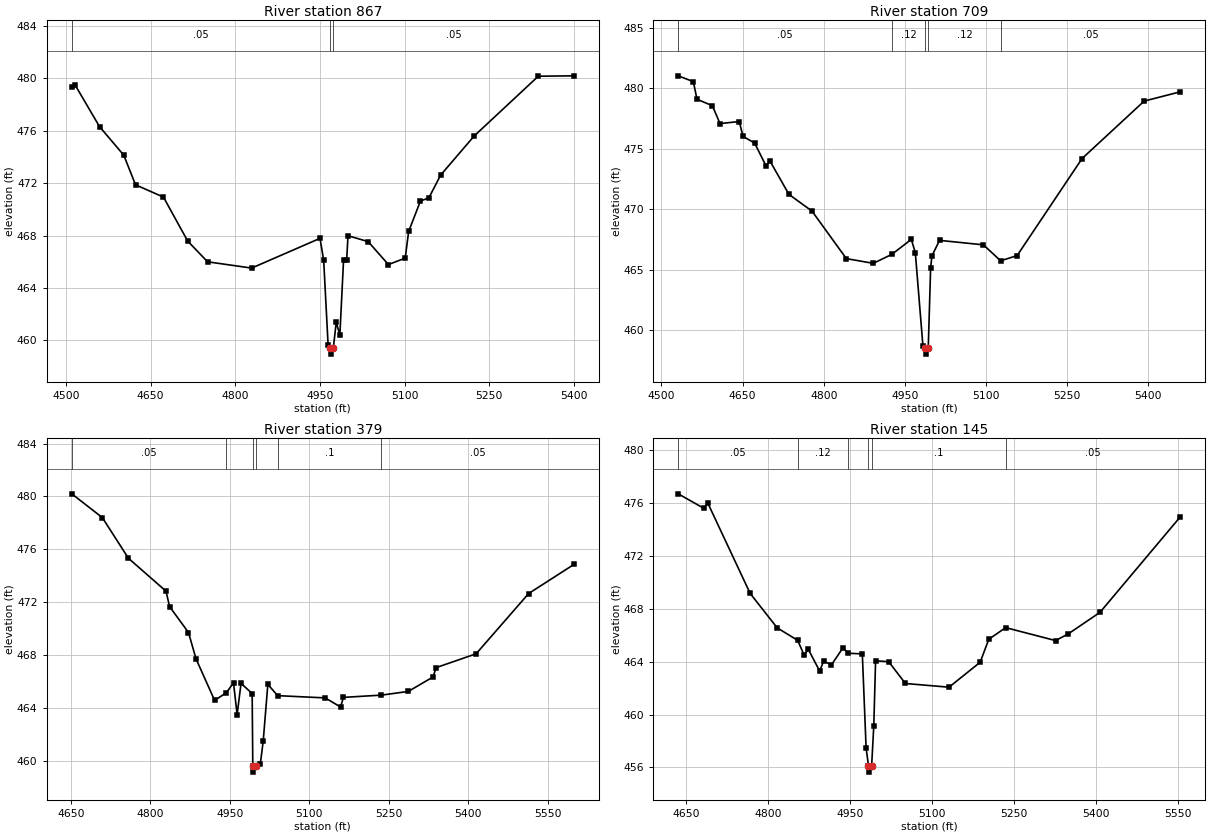
Type RM Length L Ch R = 1,867,158,158,158
BEGIN DESCRIPTION:
Lacy 023 3183
END DESCRIPTION:
XS GIS Cut Line= 3
      2758164.05      6867583.85      2758539.56      6867894.32
      2758870.85      6868123.20
#Sta/Elev= 30
  4510.2  479.32  4516.4  479.48  4559.4  476.32  4602.4  474.14  4623.2  471.88
  4672.7  470.94  4715.7  467.58  4750.9  466.00  4829.0  465.52  4950.2  467.79
  4956.7  466.11  4964.5  459.68  4968.1  459.45  4969.0  458.95  4973.9  459.45
  4978.9  461.37  4985.4  460.43  4991.9  466.10  4997.4  466.10  4999.8  467.99
  5035.6  467.54  5071.4  465.79  5101.2  466.28  5107.3  468.32  5128.2  470.64
  5143.1  470.88  5164.0  472.62  5223.5  475.61  5337.1  480.17  5400.1  480.20
#Mann=3,-1,0
  4510.2    0.05       0  4968.1    0.04       0  4973.9    0.05       0
Bank Sta=4968.1,4973.9
Exp/Cntr=0.3,0.1

Type RM Length L Ch R = 1,709,330,330,330
BEGIN DESCRIPTION:
Lacy 023 3182
END DESCRIPTION:
XS GIS Cut Line= 3
      2758101.55      6867616.04      2758421.63      6867958.83
      2758842.43      6868142.67
#Sta/Elev= 30
  4531.0  481.03  4558.9  480.55  4565.7  479.09  4594.1  478.56  4608.2  477.08
  4643.9  477.25  4650.7  476.02  4672.2  475.47  4693.2  473.59  4700.6  473.98
  4735.7  471.22  4778.3  469.84  4841.8  465.91  4891.6  465.52  4925.8  466.26
  4961.9  467.50  4969.3  466.40  4983.4  458.67  4987.4  458.51  4988.3  458.01
  4993.2  458.51  4997.6  465.14  5000.0  466.14  5014.1  467.42  5095.2  467.05
  5127.0  465.73  5157.5  466.16  5277.6  474.19  5392.4  478.94  5459.2  479.71
#Mann=5,-1,0
  4531.0    0.05       0  4925.8    0.12       0  4987.4    0.07       0
  4993.2    0.12       0  5127.0    0.05       0
Bank Sta=4987.4,4993.2
Exp/Cntr=0.3,0.1

Type RM Length L Ch R = 1,379,234,234,234
BEGIN DESCRIPTION:
Lacy 023 3181
END DESCRIPTION:
XS GIS Cut Line= 3
      2757968.51      6867927.18      2758206.01      6868182.09
      2758755.64      6868421.71
#Sta/Elev= 30
  4651.6  480.19  4709.3  478.39  4758.6  475.31  4829.5  472.82  4836.3  471.65
  4872.0  469.69  4886.2  467.70  4921.3  464.55  4943.4  465.13  4957.0  465.88
  4963.8  463.47  4971.2  465.84  4992.2  465.07  4993.4  459.62  4994.3  459.12
  4999.2  459.62  5007.6  459.73  5013.1  461.48  5021.8  465.76  5040.4  464.91
  5130.2  464.74  5159.1  464.05  5164.5  464.78  5236.4  464.95  5287.1  465.23
  5333.9  466.33  5339.4  467.03  5415.1  468.08  5514.2  472.64  5599.6  474.84
#Mann=6,-1,0
  4651.6    0.05       0  4943.4    0.12       0  4993.4    0.07       0
  4999.2    0.12       0  5040.4     0.1       0  5236.4    0.05       0
Bank Sta=4993.4,4999.2
Exp/Cntr=0.3,0.1

Type RM Length L Ch R = 1,145,0,0,0
BEGIN DESCRIPTION:
Lacy 023 3180
END DESCRIPTION:
XS GIS Cut Line= 3
      2757915.67      6868105.07      2758165.54      6868370.60
      2758710.39      6868475.19
#Sta/Elev= 30
  4635.4  476.71  4682.4  475.61  4689.3  476.03  4767.1  469.17  4816.7  466.56
  4854.0  465.62  4866.1  464.49  4873.4  464.95  4894.4  463.29  4901.7  464.05
  4915.9  463.76  4936.9  465.04  4946.9  464.64  4972.5  464.59  4979.4  457.49
  4983.7  456.14  4984.7  455.64  4989.6  456.14  4993.5  459.17  4996.8  464.07
  5020.8  464.00  5051.4  462.35  5131.3  462.07  5188.3  463.96  5204.1  465.70
  5235.0  466.58  5326.3  465.60  5349.4  466.10  5407.8  467.74  5554.8  474.97
#Mann=6,-1,0
  4635.4    0.05       0  4854.0    0.12       0  4946.9     0.1       0
  4983.7    0.07       0  4989.6     0.1       0  5235.0    0.05       0
Bank Sta=4983.7,4989.6
Exp/Cntr=0.3,0.1

Chan Stop Cuts=-1