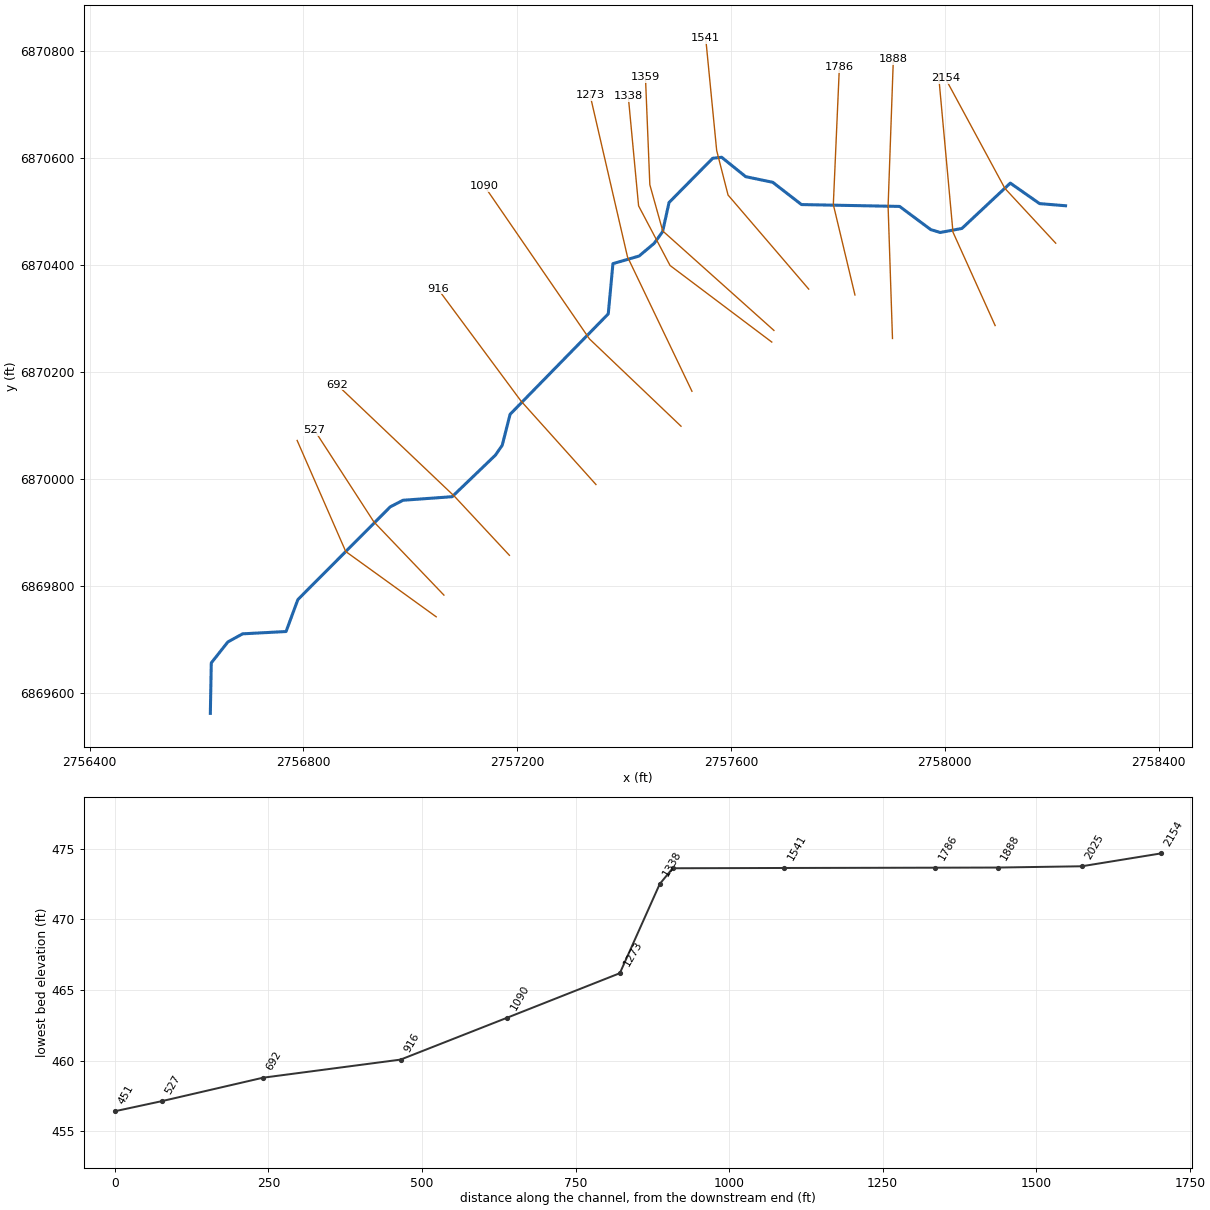
--- Lacy 024.prj (project) ---

Proj Title=Lacy 024 Base Level Engineering
Current Plan=p01
Default Exp/Contr=0.3,0.1
English Units
Geom File=g01
Flow File=f01
Plan File=p01
BEGIN DESCRIPTION:
Lacy 024
END DESCRIPTION:

--- Lacy 024.p01 (plan) ---

Plan Title=Multiple Run
Short Identifier=Multiple
Geom File=g01
Flow File=f01
Subcritical Flow
K Sum by GR= 0
Std Step Tol= 0.01
Critical Tol= 0.01
Num of Std Step Trials= 20
Max Error Tol= 0.3
Flow Tol Ratio= 0.001
Split Flow NTrial= 30
Split Flow Tol= 0.02
Split Flow Ratio= 0.02
Log Output Level= 0
Friction Slope Method= 1
Unsteady Friction Slope Method= 2
Unsteady Bridges Friction Slope Method= 1
Parabolic Critical Depth
Global Vel Dist=  1 , 1 , 1
Global Log Level= 0
CheckData=True
Encroach Param= -1, 0, 0, 0
BEGIN DESCRIPTION:
Multiple Run
END DESCRIPTION:

--- Lacy 024.f01 (steady flow) ---

Flow Title=Multiple
Number of Profiles=7
Profile Names=10-year,25-year,50-year,1pct_min,100-year,1pct_plu,500-year
River Rch & RM= Lacy 024,Reach-1,2154
      94     110     122      68     135     270     165
Boundary for River Rch & Prof#=Lacy 024,Reach-1,1
Up Type=0
Dn Type=3
Dn Slope=0.005
Boundary for River Rch & Prof#=Lacy 024,Reach-1,2
Up Type=0
Dn Type=3
Dn Slope=0.005
Boundary for River Rch & Prof#=Lacy 024,Reach-1,3
Up Type=0
Dn Type=3
Dn Slope=0.005
Boundary for River Rch & Prof#=Lacy 024,Reach-1,4
Up Type=0
Dn Type=3
Dn Slope=0.005
Boundary for River Rch & Prof#=Lacy 024,Reach-1,5
Up Type=0
Dn Type=3
Dn Slope=0.005
Boundary for River Rch & Prof#=Lacy 024,Reach-1,6
Up Type=0
Dn Type=3
Dn Slope=0.005
Boundary for River Rch & Prof#=Lacy 024,Reach-1,7
Up Type=0
Dn Type=3
Dn Slope=0.005

--- Lacy 024.g01 (geometry) ---

Geom Title=Existing Conditions

River Reach=Lacy 024,Reach-1
Reach XY= 30
      2758226.00      6870511.00      2758177.36      6870515.02
      2758122.62      6870553.40      2758032.06      6870468.52
      2757991.42      6870461.03      2757973.83      6870466.35
      2757915.50      6870509.76      2757731.93      6870513.24
      2757678.17      6870554.91      2757627.63      6870565.43
      2757582.54      6870601.76      2757565.92      6870599.93
      2757484.17      6870517.07      2757472.08      6870462.45
      2757456.26      6870440.57      2757428.15      6870416.91
      2757379.19      6870402.65      2757370.45      6870308.63
      2757186.78      6870120.68      2757172.03      6870062.63
      2757159.36      6870044.29      2757078.44      6869966.52
      2756986.48      6869959.83      2756962.70      6869947.60
      2756789.74      6869773.95      2756767.66      6869714.17
      2756686.42      6869709.86      2756658.82      6869694.75
      2756627.76      6869655.47      2756626.00      6869561.00

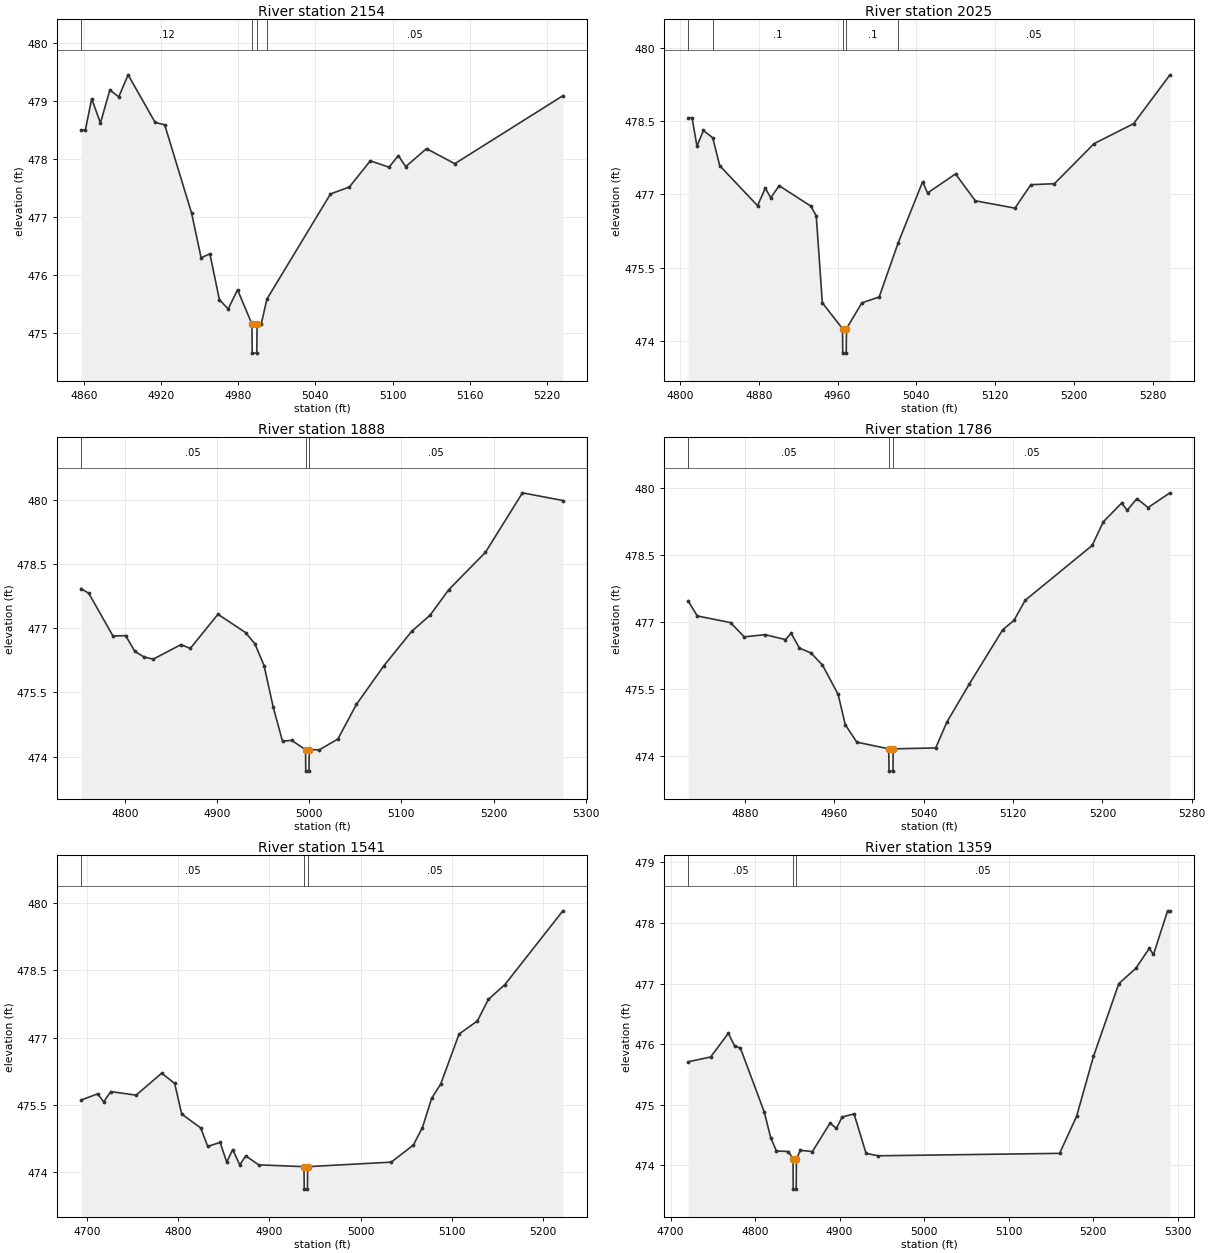
Type RM Length L Ch R = 1,2154,129,129,129
BEGIN DESCRIPTION:
Lacy 024 3177
END DESCRIPTION:
XS GIS Cut Line= 3
      2758207.57      6870440.97      2758112.40      6870543.65
      2758001.00      6870749.77
#Sta/Elev= 30
  4857.9  478.50  4861.3  478.50  4866.2  479.04  4873.0  478.62  4880.3  479.19
  4887.2  479.07  4894.5  479.45  4915.5  478.63  4922.9  478.59  4943.8  477.07
  4951.2  476.30  4958.0  476.37  4965.4  475.58  4972.2  475.42  4979.5  475.75
  4990.7  475.16  4990.9  474.66  4994.4  474.66  4994.7  475.16  4997.9  475.16
  5002.3  475.59  5051.7  477.40  5066.4  477.52  5082.6  477.97  5097.2  477.86
  5104.4  478.06  5110.1  477.87  5126.3  478.18  5148.2  477.92  5232.2  479.09
#Mann=4,-1,0
  4857.9    0.12       0  4990.7    0.07       0  4994.7    0.12       0
  5002.3    0.05       0
Bank Sta=4990.7,4994.7
Exp/Cntr=0.3,0.1

Type RM Length L Ch R = 1,2025,137,137,137
BEGIN DESCRIPTION:
Lacy 024 3176
END DESCRIPTION:
XS GIS Cut Line= 3
      2758094.25      6870286.78      2758015.38      6870461.61
      2757988.22      6870757.77
#Sta/Elev= 30
  4808.2  478.57  4812.2  478.57  4817.2  477.99  4823.8  478.31  4833.2  478.16
  4840.3  477.59  4878.7  476.77  4886.6  477.13  4892.1  476.93  4900.6  477.18
  4932.9  476.76  4938.3  476.56  4944.5  474.78  4965.0  474.25  4965.2  473.75
  4968.7  473.75  4969.0  474.25  4984.6  474.78  5002.2  474.90  5021.5  476.01
  5046.3  477.26  5051.3  477.03  5079.7  477.42  5099.8  476.87  5140.0  476.72
  5156.2  477.20  5180.1  477.22  5220.3  478.04  5260.5  478.45  5297.4  479.45
#Mann=5,-1,0
  4808.2    0.12       0  4833.2     0.1       0  4965.0    0.07       0
  4969.0     0.1       0  5021.5    0.05       0
Bank Sta=4965,4969
Exp/Cntr=0.3,0.1

Type RM Length L Ch R = 1,1888,102,102,102
BEGIN DESCRIPTION:
Lacy 024 3179
END DESCRIPTION:
XS GIS Cut Line= 3
      2757902.19      6870262.61      2757893.98      6870509.88
      2757903.78      6870784.80
#Sta/Elev= 30
  4752.6  477.93  4761.0  477.82  4787.3  476.82  4801.0  476.83  4811.0  476.46
  4821.0  476.33  4831.0  476.28  4861.0  476.62  4871.1  476.53  4901.1  477.33
  4931.1  476.90  4941.1  476.64  4951.1  476.13  4961.1  475.15  4971.1  474.36
  4981.1  474.38  4996.1  474.16  4996.3  473.66  4999.8  473.66  5000.1  474.16
  5011.1  474.16  5031.1  474.41  5051.2  475.22  5081.2  476.13  5111.2  476.93
  5131.2  477.31  5151.2  477.90  5191.2  478.78  5231.3  480.17  5275.1  479.99
#Mann=3,-1,0
  4752.6    0.05       0  4996.1    0.04       0  5000.1    0.05       0
Bank Sta=4996.1,5000.1
Exp/Cntr=0.3,0.1

Type RM Length L Ch R = 1,1786,245,245,245
BEGIN DESCRIPTION:
Lacy 024 3175
END DESCRIPTION:
XS GIS Cut Line= 3
      2757831.96      6870344.03      2757791.51      6870513.20
      2757802.84      6870770.61
#Sta/Elev= 30
  4828.9  477.47  4837.1  477.13  4866.9  476.98  4879.2  476.66  4897.8  476.71
  4916.1  476.60  4921.2  476.74  4928.6  476.41  4938.9  476.30  4949.2  476.03
  4963.3  475.37  4969.7  474.69  4980.0  474.30  5008.6  474.15  5008.9  473.65
  5012.4  473.65  5012.6  474.15  5050.7  474.17  5060.7  474.75  5080.7  475.60
  5110.7  476.82  5120.8  477.03  5130.8  477.48  5190.8  478.71  5200.8  479.24
  5217.2  479.66  5222.2  479.50  5230.9  479.76  5240.9  479.56  5260.5  479.89
#Mann=3,-1,0
  4828.9    0.05       0  5008.6    0.04       0  5012.6    0.05       0
Bank Sta=5008.6,5012.6
Exp/Cntr=0.3,0.1

Type RM Length L Ch R = 1,1541,182,182,182
BEGIN DESCRIPTION:
Lacy 024 3174
END DESCRIPTION:
XS GIS Cut Line= 4
      2757745.46      6870355.05      2757594.56      6870531.08
      2757573.28      6870614.38      2757552.75      6870824.34
#Sta/Elev= 30
  4693.2  475.61  4711.5  475.75  4718.1  475.57  4725.8  475.80  4753.7  475.72
  4781.8  476.21  4796.0  475.98  4803.7  475.30  4824.6  474.99  4832.3  474.58
  4845.9  474.67  4853.1  474.23  4859.7  474.51  4867.4  474.17  4874.0  474.37
  4888.2  474.17  4937.9  474.13  4938.2  473.63  4941.7  473.63  4941.9  474.13
  5033.6  474.23  5057.9  474.61  5067.9  475.00  5078.0  475.65  5088.0  475.97
  5108.1  477.08  5128.2  477.37  5140.2  477.85  5158.4  478.18  5222.0  479.82
#Mann=3,-1,0
  4693.2    0.05       0  4937.9    0.04       0  4941.9    0.05       0
Bank Sta=4937.9,4941.9
Exp/Cntr=0.3,0.1

Type RM Length L Ch R = 1,1359,21,21,21
BEGIN DESCRIPTION:
Lacy 024 3173
END DESCRIPTION:
XS GIS Cut Line= 4
      2757680.36      6870277.71      2757472.37      6870463.85
      2757448.24      6870550.29      2757440.04      6870751.46
#Sta/Elev= 30
  4720.7  475.71  4747.4  475.79  4768.3  476.18  4775.8  475.97  4782.5  475.94
  4810.9  474.88  4818.4  474.46  4825.2  474.24  4839.4  474.23  4844.9  474.11
  4845.1  473.61  4848.6  473.61  4848.9  474.11  4853.6  474.25  4867.8  474.23
  4888.7  474.70  4896.2  474.61  4902.9  474.80  4917.1  474.85  4931.3  474.20
  4945.5  474.16  5160.3  474.20  5180.4  474.81  5200.4  475.80  5230.4  477.00
  5250.4  477.25  5266.4  477.58  5271.4  477.48  5288.1  478.20  5290.9  478.20
#Mann=3,-1,0
  4720.7    0.05       0  4844.9    0.04       0  4848.9    0.05       0
Bank Sta=4844.9,4848.9
Exp/Cntr=0.3,0.1

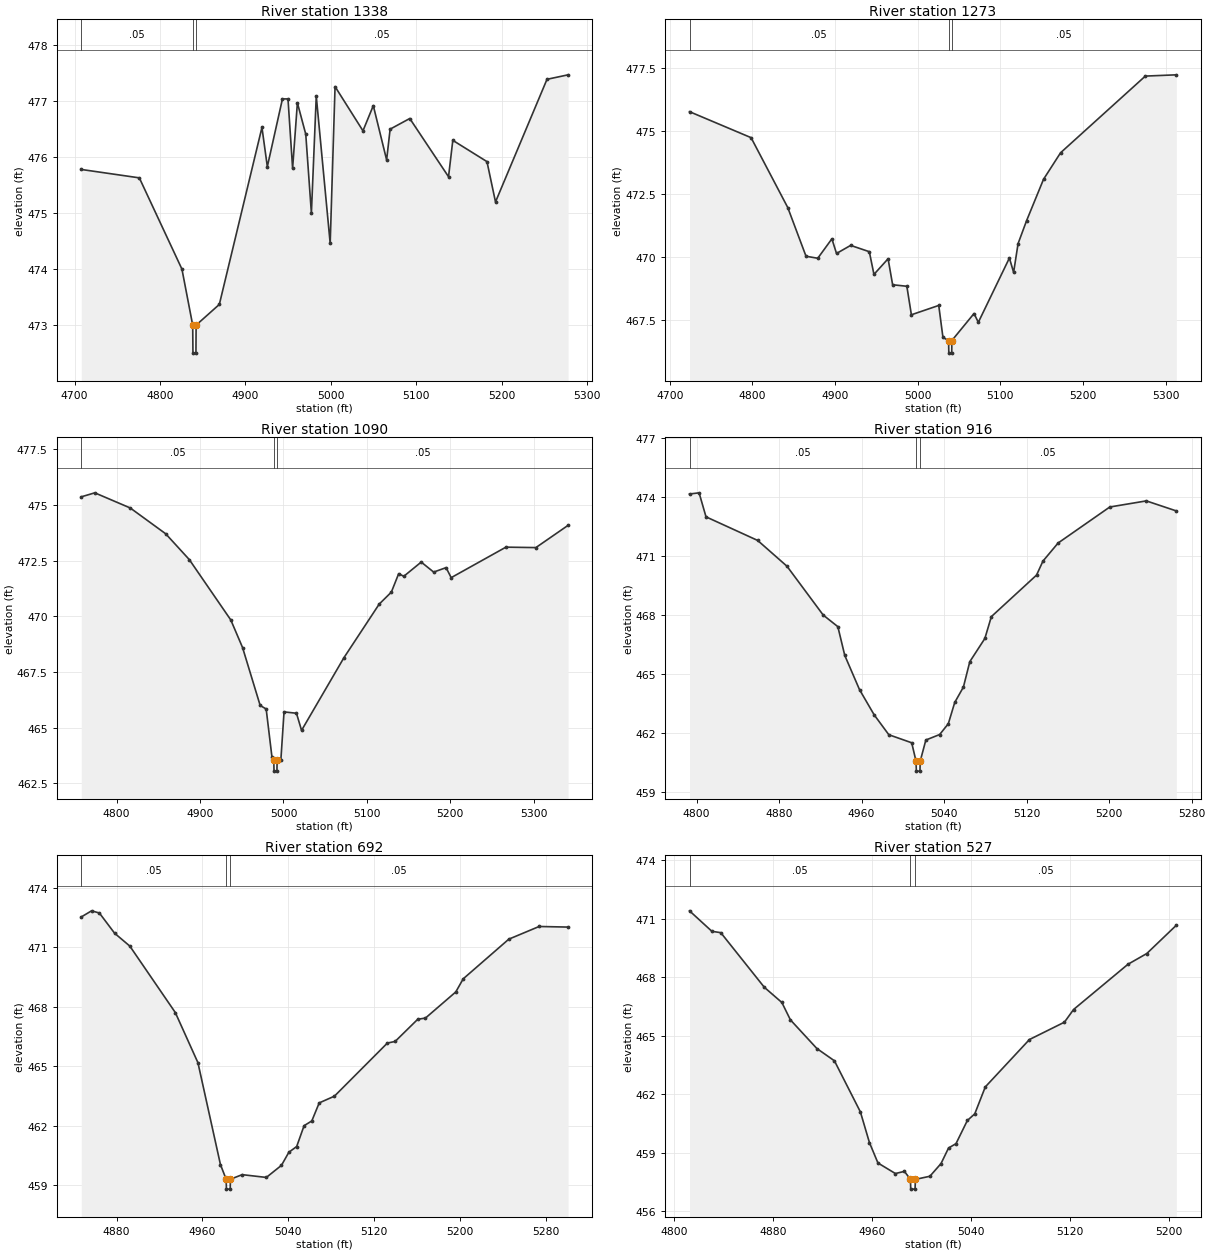
Type RM Length L Ch R = 1,1338,65,65,65
BEGIN DESCRIPTION:
Lacy 024 3169
END DESCRIPTION:
XS GIS Cut Line= 4
      2757676.37      6870255.91      2757486.05      6870399.24
      2757427.19      6870510.81      2757407.89      6870715.61
#Sta/Elev= 30
  4707.8  475.78  4775.8  475.63  4825.7  474.00  4838.3  473.00  4838.6  472.50
  4842.1  472.50  4842.3  473.00  4869.5  473.37  4919.4  476.53  4925.7  475.83
  4943.4  477.04  4949.9  477.04  4955.3  475.80  4960.9  476.97  4970.7  476.41
  4977.3  475.00  4983.0  477.09  4999.3  474.46  5005.0  477.26  5037.7  476.47
  5049.8  476.92  5065.4  475.95  5069.5  476.50  5092.5  476.69  5137.9  475.65
  5142.9  476.30  5182.9  475.92  5192.9  475.20  5253.2  477.39  5277.9  477.47
#Mann=3,-1,0
  4707.8    0.05       0  4838.3    0.04       0  4842.3    0.05       0
Bank Sta=4838.3,4842.3
Exp/Cntr=0.3,0.1

Type RM Length L Ch R = 1,1273,183,183,183
BEGIN DESCRIPTION:
Lacy 024 3170
END DESCRIPTION:
XS GIS Cut Line= 3
      2757527.03      6870163.82      2757406.39      6870415.49
      2757336.59      6870717.54
#Sta/Elev= 30
  4723.8  475.76  4798.3  474.73  4842.7  471.96  4864.8  470.03  4879.0  469.95
  4896.1  470.72  4901.7  470.14  4918.8  470.46  4941.4  470.21  4947.0  469.31
  4964.1  469.93  4969.6  468.90  4986.8  468.84  4992.3  467.71  5025.4  468.08
  5030.5  466.81  5037.3  466.69  5037.6  466.19  5041.1  466.19  5041.3  466.69
  5068.1  467.76  5073.3  467.41  5110.9  469.96  5116.0  469.39  5121.4  470.53
  5131.7  471.44  5152.2  473.08  5172.8  474.13  5275.4  477.17  5312.9  477.22
#Mann=3,-1,0
  4723.8    0.05       0  5037.3    0.04       0  5041.3    0.05       0
Bank Sta=5037.3,5041.3
Exp/Cntr=0.3,0.1

Type RM Length L Ch R = 1,1090,174,174,174
BEGIN DESCRIPTION:
Lacy 024 3171
END DESCRIPTION:
XS GIS Cut Line= 3
      2757506.56      6870098.44      2757335.28      6870261.79
      2757138.97      6870547.57
#Sta/Elev= 30
  4757.7  475.37  4773.9  475.55  4816.4  474.87  4858.9  473.71  4887.2  472.55
  4936.9  469.84  4951.0  468.60  4972.1  466.00  4979.3  465.84  4986.2  463.69
  4988.4  463.55  4988.7  463.05  4992.2  463.05  4992.4  463.55  4996.9  463.55
  5000.7  465.71  5015.6  465.65  5021.7  464.88  5072.4  468.14  5114.7  470.55
  5129.3  471.09  5138.1  471.92  5144.2  471.80  5165.1  472.44  5180.0  471.99
  5194.9  472.19  5201.0  471.74  5266.6  473.11  5302.5  473.09  5341.1  474.09
#Mann=3,-1,0
  4757.7    0.05       0  4988.4    0.04       0  4992.4    0.05       0
Bank Sta=4988.4,4992.4
Exp/Cntr=0.3,0.1

Type RM Length L Ch R = 1,916,224,224,224
BEGIN DESCRIPTION:
Lacy 024 3172
END DESCRIPTION:
XS GIS Cut Line= 3
      2757347.41      6869989.34      2757207.11      6870145.67
      2757051.25      6870356.07
#Sta/Elev= 30
  4793.2  474.16  4802.5  474.22  4809.2  473.00  4859.3  471.80  4887.7  470.49
  4922.8  468.01  4937.0  467.42  4943.7  465.96  4958.0  464.22  4972.2  462.94
  4986.4  461.93  5008.6  461.52  5012.8  460.58  5013.1  460.08  5016.6  460.08
  5016.8  460.58  5022.3  461.66  5035.7  461.94  5044.1  462.49  5050.3  463.57
  5058.7  464.35  5064.9  465.64  5079.5  466.82  5085.8  467.93  5129.6  470.04
  5135.8  470.75  5150.5  471.67  5200.6  473.50  5236.0  473.81  5265.1  473.30
#Mann=3,-1,0
  4793.2    0.05       0  5012.8    0.04       0  5016.8    0.05       0
Bank Sta=5012.8,5016.8
Exp/Cntr=0.3,0.1

Type RM Length L Ch R = 1,692,165,165,165
BEGIN DESCRIPTION:
Lacy 024 3168
END DESCRIPTION:
XS GIS Cut Line= 3
      2757185.52      6869856.80      2757082.66      6869967.29
      2756863.05      6870176.11
#Sta/Elev= 30
  4847.0  472.53  4856.6  472.84  4863.9  472.73  4878.1  471.71  4892.3  471.06
  4934.7  467.71  4955.8  465.18  4976.8  460.04  4982.1  459.30  4982.4  458.80
  4985.9  458.80  4986.1  459.30  4997.1  459.53  5019.6  459.39  5033.7  460.00
  5040.6  460.66  5047.9  460.95  5054.8  462.00  5062.0  462.24  5068.9  463.15
  5083.1  463.49  5132.5  466.17  5139.7  466.25  5160.8  467.37  5168.0  467.43
  5196.3  468.75  5203.2  469.41  5245.7  471.41  5274.0  472.05  5301.0  472.02
#Mann=3,-1,0
  4847.0    0.05       0  4982.1    0.04       0  4986.1    0.05       0
Bank Sta=4982.1,4986.1
Exp/Cntr=0.3,0.1

Type RM Length L Ch R = 1,527,76,76,76
BEGIN DESCRIPTION:
Lacy 024 3167
END DESCRIPTION:
XS GIS Cut Line= 3
      2757062.95      6869782.36      2756931.90      6869919.46
      2756821.00      6870090.73
#Sta/Elev= 30
  4812.3  471.41  4830.4  470.36  4837.6  470.29  4872.8  467.49  4887.0  466.71
  4893.9  465.82  4915.3  464.35  4929.5  463.72  4950.5  461.10  4957.8  459.53
  4964.7  458.48  4978.8  457.94  4986.1  458.05  4991.0  457.64  4991.2  457.14
  4994.7  457.14  4995.0  457.64  5006.7  457.80  5015.7  458.45  5021.8  459.25
  5027.8  459.47  5037.0  460.66  5043.0  461.00  5051.5  462.38  5087.2  464.81
  5115.5  465.70  5122.9  466.35  5166.9  468.67  5182.1  469.22  5206.0  470.67
#Mann=3,-1,0
  4812.3    0.05       0  4991.0    0.04       0  4995.0    0.05       0
Bank Sta=4991,4995
Exp/Cntr=0.3,0.1

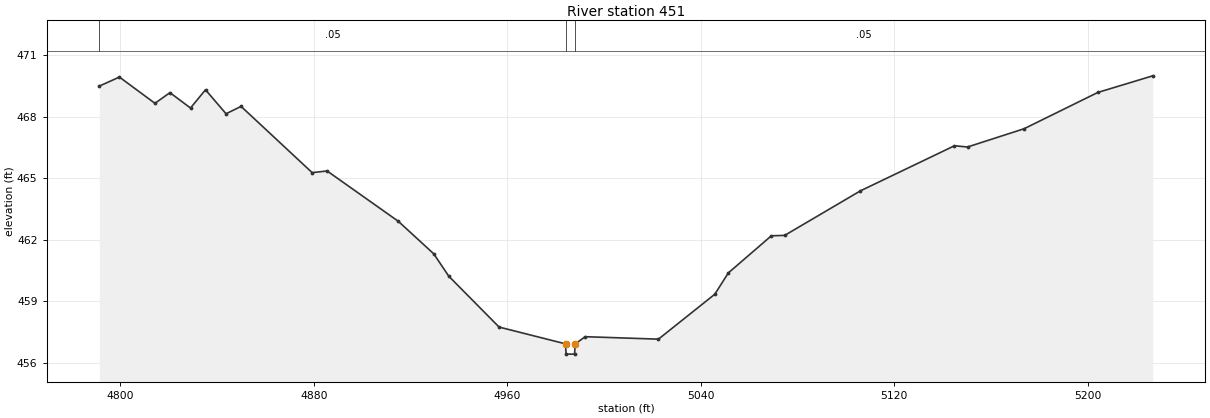
Type RM Length L Ch R = 1,451,0,0,0
BEGIN DESCRIPTION:
Lacy 024 3166
END DESCRIPTION:
XS GIS Cut Line= 3
      2757048.54      6869741.74      2756879.33      6869863.90
      2756788.40      6870071.79
#Sta/Elev= 30
  4791.3  469.50  4799.6  469.94  4814.3  468.66  4820.5  469.18  4829.0  468.43
  4835.2  469.32  4843.7  468.15  4849.9  468.51  4879.3  465.28  4885.5  465.36
  4914.9  462.91  4929.6  461.32  4935.8  460.23  4956.6  457.75  4984.1  456.93
  4984.3  456.43  4987.8  456.43  4988.1  456.93  4992.2  457.28  5022.5  457.16
  5045.8  459.35  5051.4  460.39  5069.2  462.20  5074.7  462.22  5106.0  464.39
  5144.9  466.59  5150.3  466.53  5173.7  467.42  5204.2  469.19  5226.9  470.00
#Mann=3,-1,0
  4791.3    0.05       0  4984.1    0.04       0  4988.1    0.05       0
Bank Sta=4984.1,4988.1
Exp/Cntr=0.3,0.1

Chan Stop Cuts=-1