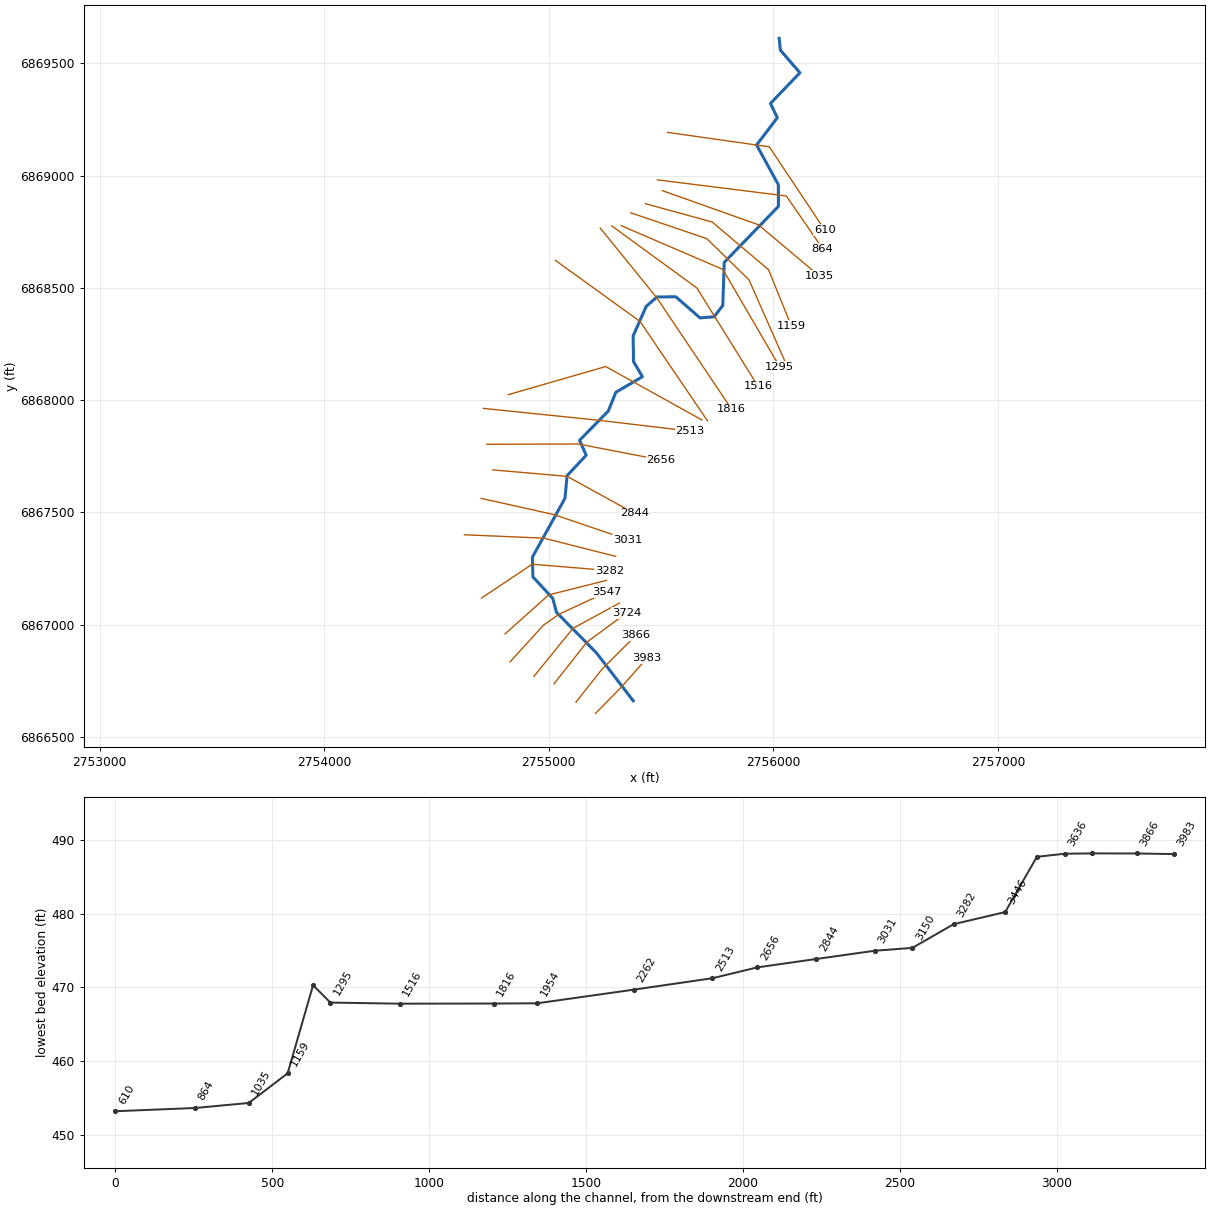
--- Lacy 025.prj (project) ---

Proj Title=Lacy 025 Base Level Engineering
Current Plan=p01
Default Exp/Contr=0.3,0.1
English Units
Geom File=g01
Flow File=f01
Plan File=p01
BEGIN DESCRIPTION:
Lacy 025
END DESCRIPTION:

--- Lacy 025.p01 (plan) ---

Plan Title=Multiple Run
Short Identifier=Multiple
Geom File=g01
Flow File=f01
Subcritical Flow
K Sum by GR= 0
Std Step Tol= 0.01
Critical Tol= 0.01
Num of Std Step Trials= 20
Max Error Tol= 0.3
Flow Tol Ratio= 0.001
Split Flow NTrial= 30
Split Flow Tol= 0.02
Split Flow Ratio= 0.02
Log Output Level= 0
Friction Slope Method= 1
Unsteady Friction Slope Method= 2
Unsteady Bridges Friction Slope Method= 1
Parabolic Critical Depth
Global Vel Dist=  1 , 1 , 1
Global Log Level= 0
CheckData=True
Encroach Param= -1, 0, 0, 0
BEGIN DESCRIPTION:
Multiple Run
END DESCRIPTION:

--- Lacy 025.f01 (steady flow) ---

Flow Title=Multiple
Number of Profiles=7
Profile Names=10-year,25-year,50-year,1pct_min,100-year,1pct_plu,500-year
River Rch & RM= Lacy 025,Reach-1,3983
     243     310     362     211     421     841     570
Boundary for River Rch & Prof#=Lacy 025,Reach-1,1
Up Type=0
Dn Type=3
Dn Slope=0.005
Boundary for River Rch & Prof#=Lacy 025,Reach-1,2
Up Type=0
Dn Type=3
Dn Slope=0.005
Boundary for River Rch & Prof#=Lacy 025,Reach-1,3
Up Type=0
Dn Type=3
Dn Slope=0.005
Boundary for River Rch & Prof#=Lacy 025,Reach-1,4
Up Type=0
Dn Type=3
Dn Slope=0.005
Boundary for River Rch & Prof#=Lacy 025,Reach-1,5
Up Type=0
Dn Type=3
Dn Slope=0.005
Boundary for River Rch & Prof#=Lacy 025,Reach-1,6
Up Type=0
Dn Type=3
Dn Slope=0.005
Boundary for River Rch & Prof#=Lacy 025,Reach-1,7
Up Type=0
Dn Type=3
Dn Slope=0.005

--- Lacy 025.g01 (geometry) ---

Geom Title=Existing Conditions

River Reach=Lacy 025,Reach-1
Reach XY= 30
      2755376.00      6866661.00      2755212.37      6866874.21
      2755034.16      6867054.95      2755017.82      6867117.04
      2754929.47      6867212.50      2754927.08      6867300.45
      2755072.17      6867562.59      2755081.55      6867663.43
      2755166.68      6867754.34      2755137.24      6867821.00
      2755265.21      6867951.34      2755298.87      6868034.84
      2755416.99      6868103.98      2755377.38      6868171.43
      2755375.76      6868286.08      2755434.00      6868417.39
      2755481.71      6868459.12      2755565.51      6868460.07
      2755673.74      6868366.07      2755736.05      6868371.02
      2755775.01      6868421.24      2755781.46      6868613.45
      2756022.54      6868862.50      2756022.33      6868959.41
      2755925.50      6869136.04      2756017.98      6869257.67
      2755987.24      6869321.00      2756118.42      6869457.66
      2756031.35      6869558.48      2756026.00      6869611.00

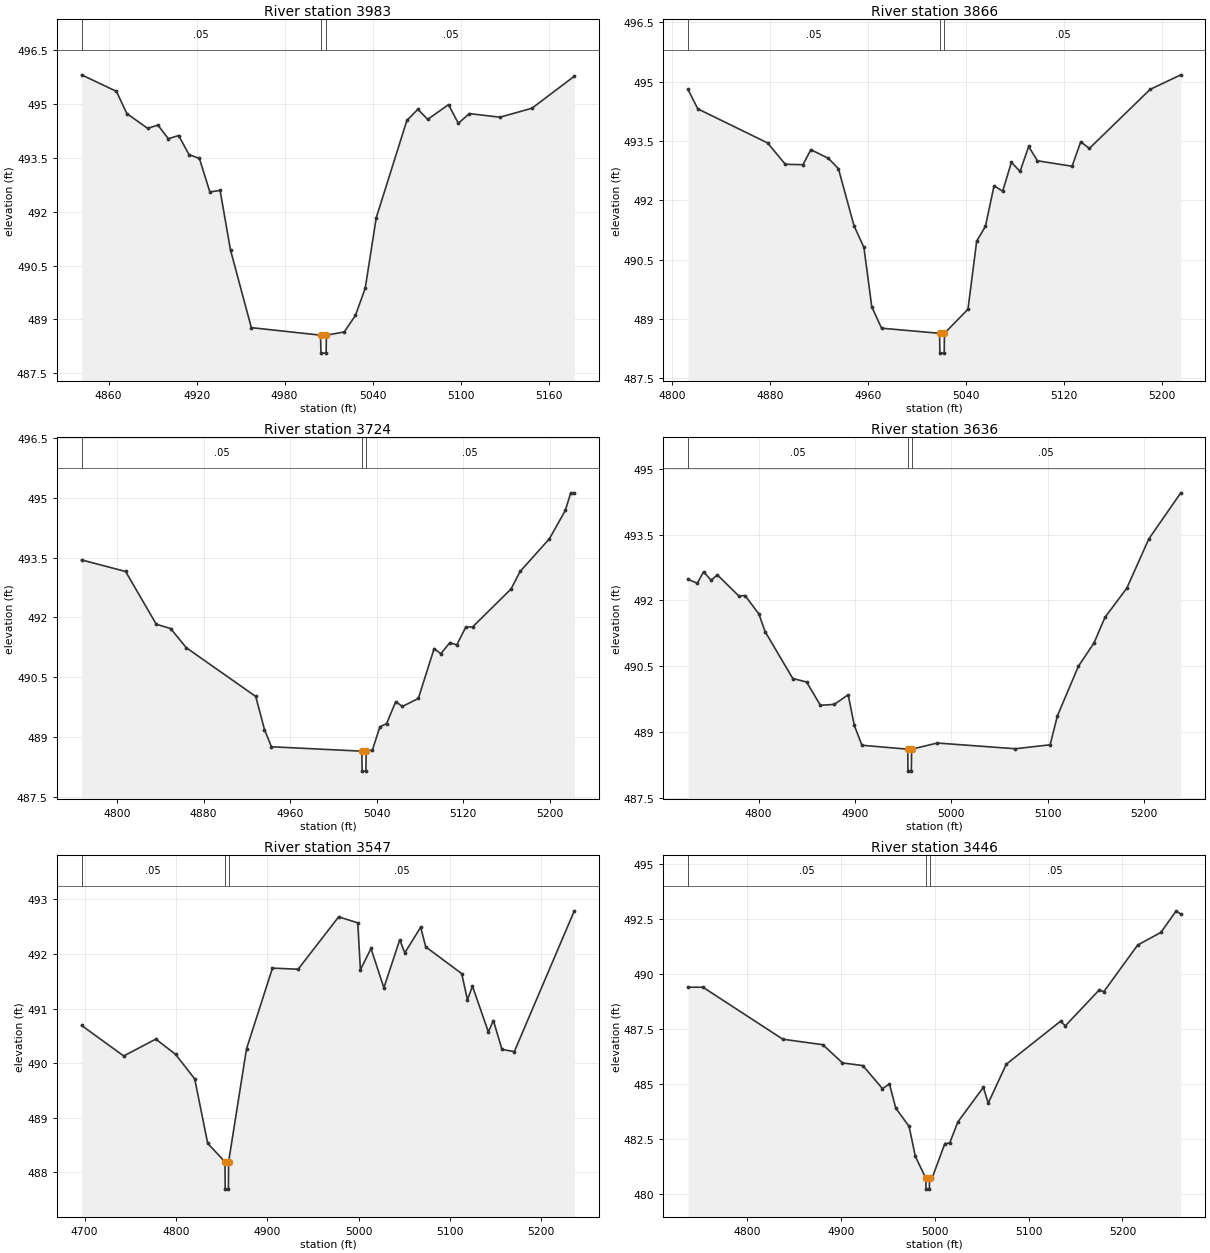
Type RM Length L Ch R = 1,3983,117,117,117
BEGIN DESCRIPTION:
Lacy 025 3163
END DESCRIPTION:
XS GIS Cut Line= 3
      2755208.47      6866604.83      2755319.50      6866717.94
      2755437.42      6866850.74
#Sta/Elev= 30
  4841.5  495.81  4865.3  495.35  4872.4  494.73  4886.6  494.32  4893.6  494.41
  4900.7  494.03  4907.7  494.12  4914.8  493.59  4921.9  493.48  4929.0  492.55
  4936.0  492.59  4943.1  490.93  4957.3  488.77  5004.5  488.56  5004.8  488.06
  5008.3  488.06  5008.5  488.56  5020.7  488.65  5028.3  489.11  5035.0  489.87
  5042.5  491.83  5063.4  494.54  5070.9  494.85  5077.6  494.57  5091.8  494.98
  5098.5  494.46  5106.0  494.73  5126.9  494.63  5148.7  494.88  5177.6  495.77
#Mann=3,-1,0
  4841.5    0.05       0  5004.5    0.04       0  5008.5    0.05       0
Bank Sta=5004.5,5008.5
Exp/Cntr=0.3,0.1

Type RM Length L Ch R = 1,3866,142,142,142
BEGIN DESCRIPTION:
Lacy 025 3162
END DESCRIPTION:
XS GIS Cut Line= 3
      2755121.04      6866654.69      2755236.77      6866801.32
      2755389.01      6866953.43
#Sta/Elev= 30
  4813.2  494.80  4821.2  494.31  4878.1  493.45  4892.6  492.91  4907.0  492.90
  4913.4  493.28  4927.8  493.06  4935.9  492.80  4948.6  491.36  4956.7  490.81
  4963.1  489.31  4971.1  488.77  5018.4  488.64  5018.7  488.14  5022.2  488.14
  5022.4  488.64  5041.6  489.25  5048.7  490.97  5055.8  491.34  5062.9  492.37
  5069.9  492.23  5077.0  492.96  5084.1  492.73  5091.1  493.36  5098.2  493.00
  5126.5  492.86  5133.6  493.48  5140.6  493.31  5190.1  494.80  5215.2  495.17
#Mann=3,-1,0
  4813.2    0.05       0  5018.4    0.04       0  5022.4    0.05       0
Bank Sta=5018.4,5022.4
Exp/Cntr=0.3,0.1

Type RM Length L Ch R = 1,3724,88,88,88
BEGIN DESCRIPTION:
Lacy 025 3158
END DESCRIPTION:
XS GIS Cut Line= 3
      2755023.66      6866736.78      2755169.59      6866922.13
      2755346.29      6867052.00
#Sta/Elev= 30
  4767.3  493.44  4808.0  493.15  4836.3  491.83  4849.6  491.72  4864.1  491.24
  4928.2  490.02  4936.3  489.19  4942.7  488.76  5026.2  488.65  5026.5  488.15
  5030.0  488.15  5030.2  488.65  5036.0  488.68  5042.9  489.26  5049.1  489.34
  5057.5  489.89  5063.7  489.77  5078.4  489.97  5093.0  491.22  5099.2  491.09
  5107.6  491.37  5113.9  491.31  5122.3  491.76  5128.5  491.76  5164.0  492.71
  5172.4  493.15  5199.5  493.97  5214.2  494.68  5219.2  495.12  5222.5  495.12
#Mann=3,-1,0
  4767.3    0.05       0  5026.2    0.04       0  5030.2    0.05       0
Bank Sta=5026.2,5030.2
Exp/Cntr=0.3,0.1

Type RM Length L Ch R = 1,3636,89,89,89
BEGIN DESCRIPTION:
Lacy 025 3157
END DESCRIPTION:
XS GIS Cut Line= 3
      2754934.02      6866769.63      2755107.55      6866983.40
      2755315.18      6867096.35
#Sta/Elev= 30
  4726.7  492.48  4736.3  492.39  4742.8  492.65  4750.7  492.46  4757.2  492.58
  4779.5  492.10  4785.9  492.11  4800.3  491.69  4806.7  491.29  4835.5  490.22
  4849.8  490.14  4864.2  489.61  4878.6  489.63  4893.0  489.85  4899.4  489.15
  4907.3  488.70  4954.9  488.61  4955.1  488.11  4958.6  488.11  4958.9  488.61
  4985.6  488.75  5066.6  488.62  5102.7  488.71  5110.3  489.37  5132.1  490.50
  5148.3  491.03  5159.6  491.61  5182.4  492.28  5205.2  493.40  5238.4  494.45
#Mann=3,-1,0
  4726.7    0.05       0  4954.9    0.04       0  4958.9    0.05       0
Bank Sta=4954.9,4958.9
Exp/Cntr=0.3,0.1

Type RM Length L Ch R = 1,3547,101,101,101
BEGIN DESCRIPTION:
Lacy 025 3156
END DESCRIPTION:
XS GIS Cut Line= 4
      2754827.78      6866834.23      2754976.30      6866997.59
      2755045.68      6867046.27      2755257.75      6867145.08
#Sta/Elev= 30
  4696.6  490.69  4742.8  490.13  4777.9  490.44  4799.5  490.16  4820.5  489.71
  4834.7  488.53  4853.6  488.19  4853.9  487.69  4857.4  487.69  4857.6  488.19
  4877.2  490.26  4905.6  491.74  4933.7  491.72  4978.1  492.68  4999.0  492.57
  5001.9  491.71  5013.5  492.10  5027.6  491.38  5045.0  492.26  5050.5  492.02
  5067.9  492.49  5073.4  492.13  5112.8  491.64  5119.1  491.16  5124.6  491.41
  5142.0  490.57  5147.5  490.78  5156.9  490.25  5170.4  490.21  5236.1  492.79
#Mann=3,-1,0
  4696.6    0.05       0  4853.6    0.04       0  4857.6    0.05       0
Bank Sta=4853.6,4857.6
Exp/Cntr=0.3,0.1

Type RM Length L Ch R = 1,3446,164,164,164
BEGIN DESCRIPTION:
Lacy 025 3155
END DESCRIPTION:
XS GIS Cut Line= 3
      2754805.41      6866958.77      2754999.35      6867132.31
      2755256.49      6867197.00
#Sta/Elev= 30
  4736.8  489.40  4752.7  489.40  4837.9  487.03  4880.6  486.78  4901.5  485.95
  4923.2  485.83  4944.1  484.78  4951.6  484.99  4958.3  483.89  4972.5  483.06
  4979.2  481.69  4990.3  480.70  4990.6  480.20  4994.1  480.20  4994.3  480.70
  4997.0  480.70  5010.6  482.27  5015.8  482.30  5024.5  483.26  5051.7  484.84
  5056.9  484.12  5076.1  485.89  5134.0  487.85  5139.1  487.64  5175.1  489.27
  5180.2  489.20  5216.2  491.32  5241.1  491.90  5257.3  492.88  5262.2  492.73
#Mann=3,-1,0
  4736.8    0.05       0  4990.3   0.035       0  4994.3    0.05       0
Bank Sta=4990.3,4994.3
Exp/Cntr=0.3,0.1

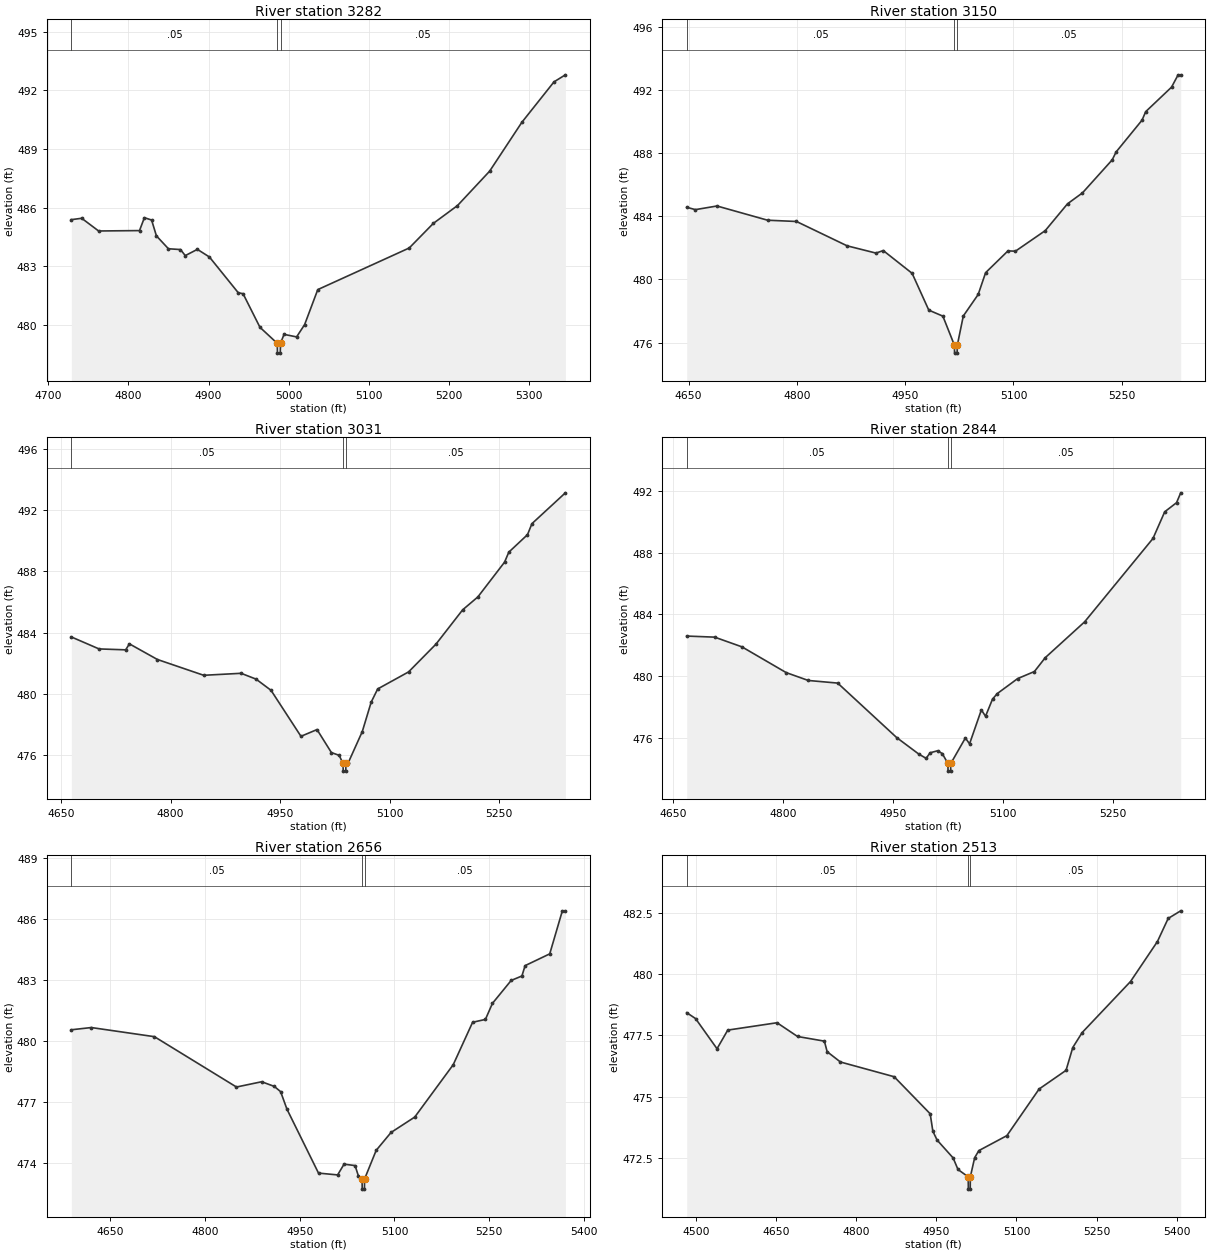
Type RM Length L Ch R = 1,3282,132,132,132
BEGIN DESCRIPTION:
Lacy 025 3154
END DESCRIPTION:
XS GIS Cut Line= 3
      2754700.61      6867118.57      2754926.30      6867269.08
      2755270.15      6867240.63
#Sta/Elev= 30
  4728.9  485.39  4741.8  485.46  4762.9  484.81  4813.9  484.83  4820.0  485.49
  4829.0  485.37  4835.0  484.56  4850.0  483.90  4865.0  483.86  4871.0  483.55
  4886.1  483.87  4901.1  483.48  4937.1  481.65  4943.1  481.60  4964.2  479.88
  4985.8  479.06  4986.0  478.56  4989.5  478.56  4989.8  479.06  4994.2  479.52
  5009.9  479.39  5019.9  480.02  5036.3  481.81  5150.4  483.94  5180.5  485.20
  5210.6  486.11  5250.7  487.87  5290.9  490.37  5331.0  492.44  5345.2  492.80
#Mann=3,-1,0
  4728.9    0.05       0  4985.8   0.035       0  4989.8    0.05       0
Bank Sta=4985.8,4989.8
Exp/Cntr=0.3,0.1

Type RM Length L Ch R = 1,3150,119,119,119
BEGIN DESCRIPTION:
Lacy 025 3153
END DESCRIPTION:
XS GIS Cut Line= 3
      2754624.00      6867400.29      2754978.53      6867385.08
      2755297.96      6867304.08
#Sta/Elev= 30
  4647.3  484.57  4659.3  484.42  4689.3  484.65  4759.4  483.75  4799.4  483.67
  4869.5  482.13  4909.5  481.67  4919.6  481.83  4959.6  480.39  4982.7  478.06
  5002.2  477.68  5018.2  475.84  5018.4  475.34  5021.9  475.34  5022.2  475.84
  5030.5  477.69  5051.1  479.05  5061.4  480.43  5092.4  481.81  5102.7  481.79
  5144.0  483.09  5174.9  484.79  5195.6  485.48  5236.8  487.57  5242.2  488.07
  5278.1  490.08  5283.2  490.62  5319.0  492.17  5328.1  492.95  5331.7  492.95
#Mann=3,-1,0
  4647.3    0.05       0  5018.2   0.035       0  5022.2    0.05       0
Bank Sta=5018.2,5022.2
Exp/Cntr=0.3,0.1

Type RM Length L Ch R = 1,3031,187,187,187
BEGIN DESCRIPTION:
Lacy 025 3152
END DESCRIPTION:
XS GIS Cut Line= 3
      2754699.01      6867562.29      2755023.69      6867490.09
      2755349.33      6867378.93
#Sta/Elev= 30
  4664.2  483.71  4702.1  482.93  4738.6  482.87  4743.7  483.26  4782.1  482.24
  4845.5  481.21  4896.7  481.34  4917.2  480.96  4937.7  480.23  4978.7  477.23
  5000.7  477.67  5020.4  476.17  5031.0  475.99  5036.3  475.46  5036.6  474.96
  5040.1  474.96  5040.3  475.46  5043.6  475.52  5062.7  477.54  5074.9  479.46
  5083.8  480.32  5126.1  481.43  5163.6  483.24  5200.2  485.48  5221.0  486.32
  5257.6  488.59  5263.4  489.24  5289.0  490.38  5295.1  491.10  5340.9  493.11
#Mann=3,-1,0
  4664.2    0.05       0  5036.3    0.04       0  5040.3    0.05       0
Bank Sta=5036.3,5040.3
Exp/Cntr=0.3,0.1

Type RM Length L Ch R = 1,2844,188,188,188
BEGIN DESCRIPTION:
Lacy 025 3151
END DESCRIPTION:
XS GIS Cut Line= 3
      2754750.95      6867689.12      2755081.94      6867660.35
      2755380.72      6867495.87
#Sta/Elev= 30
  4669.0  482.60  4707.1  482.53  4744.3  481.90  4804.6  480.23  4834.7  479.72
  4874.8  479.55  4955.1  476.02  4985.2  474.95  4995.3  474.67  5000.8  475.03
  5010.9  475.16  5017.3  474.98  5025.0  474.34  5025.2  473.84  5028.7  473.84
  5029.0  474.34  5048.8  475.99  5054.5  475.61  5070.6  477.81  5076.3  477.40
  5085.8  478.51  5092.3  478.87  5120.0  479.84  5142.9  480.30  5157.7  481.20
  5211.3  483.52  5304.5  488.93  5320.5  490.66  5336.6  491.25  5342.3  491.89
#Mann=3,-1,0
  4669.0    0.05       0  5025.0    0.04       0  5029.0    0.05       0
Bank Sta=5025,5029
Exp/Cntr=0.3,0.1

Type RM Length L Ch R = 1,2656,143,143,143
BEGIN DESCRIPTION:
Lacy 025 3148
END DESCRIPTION:
XS GIS Cut Line= 3
      2754724.37      6867803.20      2755131.65      6867804.43
      2755500.37      6867733.29
#Sta/Elev= 30
  4588.0  480.55  4619.6  480.66  4719.6  480.21  4849.6  477.73  4889.6  477.99
  4909.6  477.76  4919.6  477.50  4929.6  476.64  4979.6  473.49  5009.9  473.40
  5020.1  473.93  5037.6  473.86  5042.7  473.36  5048.6  473.20  5048.9  472.70
  5052.4  472.70  5052.6  473.20  5071.0  474.61  5094.5  475.49  5132.1  476.25
  5193.1  478.83  5223.8  480.92  5244.1  481.06  5255.2  481.85  5284.9  482.98
  5301.9  483.20  5307.0  483.71  5346.0  484.29  5366.0  486.41  5370.8  486.41
#Mann=3,-1,0
  4588.0    0.05       0  5048.6    0.04       0  5052.6    0.05       0
Bank Sta=5048.6,5052.6
Exp/Cntr=0.3,0.1

Type RM Length L Ch R = 1,2513,251,251,251
BEGIN DESCRIPTION:
Lacy 025 3149
END DESCRIPTION:
XS GIS Cut Line= 3
      2754709.49      6867963.03      2755218.98      6867910.46
      2755629.33      6867861.99
#Sta/Elev= 30
  4482.3  478.42  4498.9  478.18  4539.1  476.95  4559.2  477.71  4651.5  478.01
  4689.9  477.45  4740.2  477.26  4745.4  476.83  4770.3  476.41  4870.9  475.81
  4938.4  474.30  4943.4  473.59  4951.3  473.23  4981.4  472.50  4990.5  472.03
  5009.6  471.73  5009.9  471.23  5013.4  471.23  5013.6  471.73  5021.7  472.51
  5029.6  472.80  5082.1  473.41  5142.5  475.31  5192.9  476.07  5205.5  477.00
  5223.1  477.61  5313.7  479.69  5364.1  481.32  5384.2  482.26  5407.7  482.57
#Mann=3,-1,0
  4482.3    0.05       0  5009.6    0.04       0  5013.6    0.05       0
Bank Sta=5009.6,5013.6
Exp/Cntr=0.3,0.1

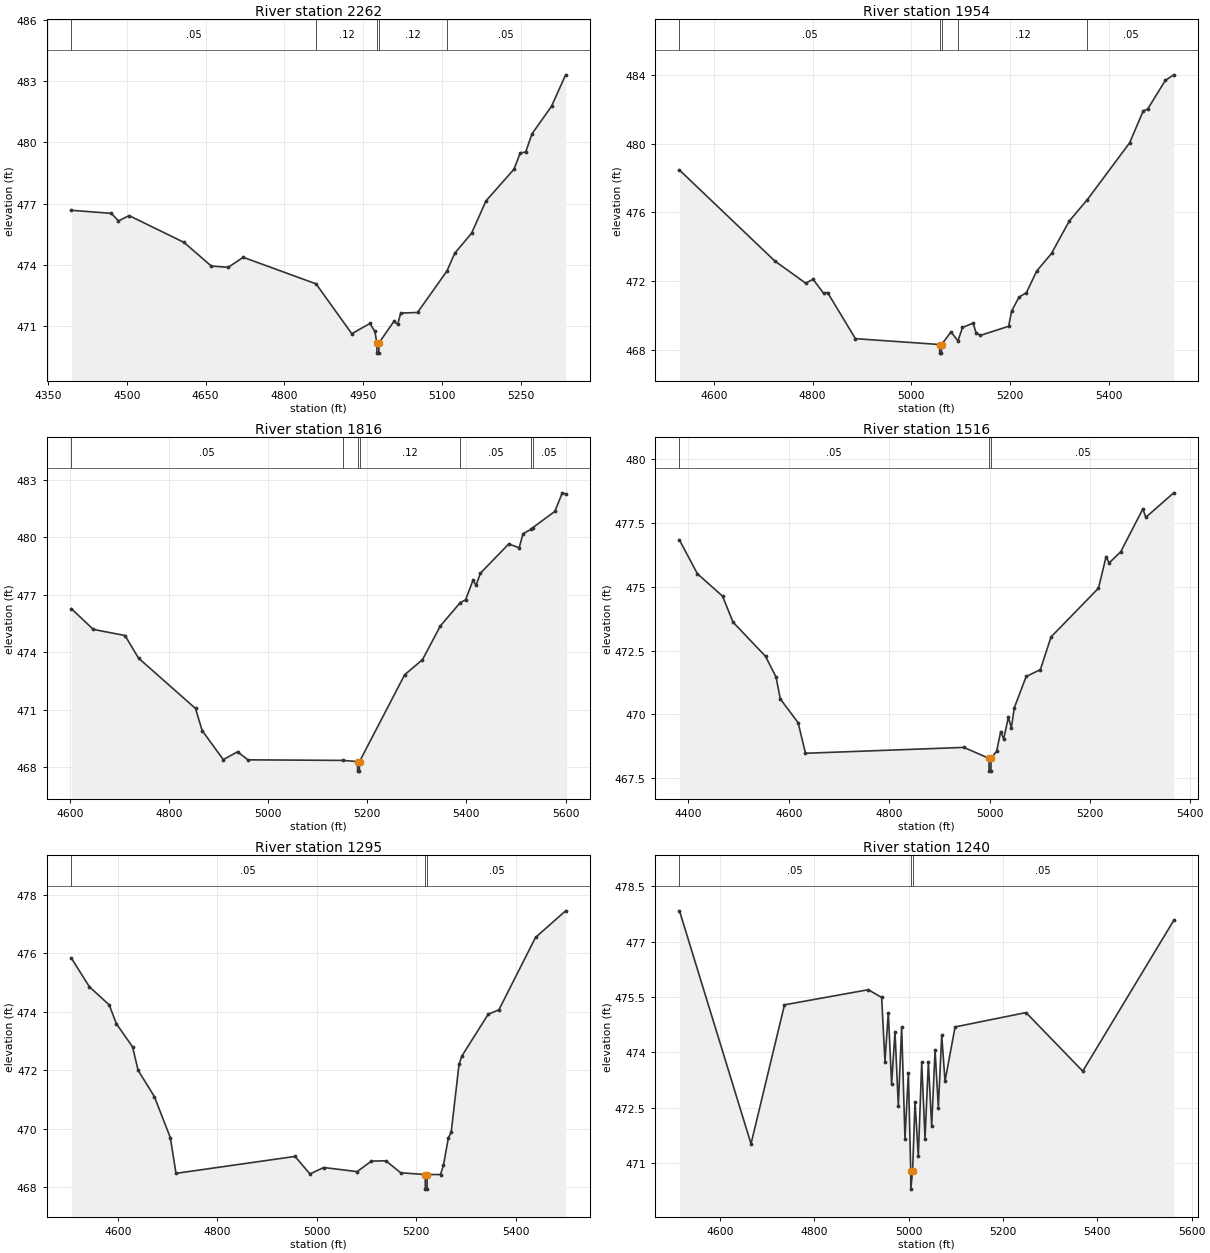
Type RM Length L Ch R = 1,2262,308,308,308
BEGIN DESCRIPTION:
Lacy 025 3150
END DESCRIPTION:
XS GIS Cut Line= 3
      2754819.90      6868024.17      2755253.54      6868149.43
      2755682.07      6867911.54
#Sta/Elev= 30
  4394.3  476.67  4470.6  476.52  4483.9  476.15  4504.3  476.41  4608.8  475.10
  4660.9  473.94  4693.2  473.88  4721.7  474.37  4860.4  473.07  4928.5  470.63
  4962.9  471.13  4972.5  470.74  4976.2  470.18  4976.4  469.68  4979.9  469.68
  4980.2  470.18  5008.6  471.23  5015.9  471.09  5021.7  471.64  5053.7  471.67
  5109.5  473.69  5124.6  474.57  5156.7  475.55  5184.1  477.13  5237.4  478.68
  5249.4  479.48  5259.7  479.52  5271.7  480.41  5308.9  481.76  5335.8  483.30
#Mann=5,-1,0
  4394.3    0.05       0  4860.4    0.12       0  4976.2    0.07       0
  4980.2    0.12       0  5109.5    0.05       0
Bank Sta=4976.2,4980.2
Exp/Cntr=0.3,0.1

Type RM Length L Ch R = 1,1954,138,138,138
BEGIN DESCRIPTION:
Lacy 025 3147
END DESCRIPTION:
XS GIS Cut Line= 3
      2755029.24      6868622.37      2755406.46      6868350.14
      2755707.15      6867907.15
#Sta/Elev= 30
  4530.7  478.46  4723.7  473.18  4786.3  471.89  4801.0  472.12  4822.7  471.30
  4830.5  471.35  4886.9  468.67  5057.4  468.33  5057.6  467.83  5061.1  467.83
  5061.4  468.33  5080.3  469.06  5094.5  468.54  5103.6  469.32  5125.2  469.57
  5131.2  469.01  5139.9  468.86  5197.1  469.39  5203.1  470.27  5218.0  471.08
  5233.0  471.34  5254.0  472.60  5283.9  473.62  5319.8  475.50  5356.1  476.73
  5442.0  480.04  5469.6  481.90  5478.3  481.99  5514.4  483.67  5531.3  483.99
#Mann=5,-1,0
  4530.7    0.05       0  5057.4    0.04       0  5061.4    0.05       0
  5094.5    0.12       0  5356.1    0.05       0
Bank Sta=5057.4,5061.4
Exp/Cntr=0.3,0.1

Type RM Length L Ch R = 1,1816,300,300,300
BEGIN DESCRIPTION:
Lacy 025 3146
END DESCRIPTION:
XS GIS Cut Line= 3
      2755229.41      6868765.78      2755480.96      6868455.85
      2755814.11      6867959.57
#Sta/Elev= 30
  4603.3  476.28  4647.5  475.20  4711.5  474.88  4738.7  473.70  4853.7  471.07
  4867.0  469.92  4909.7  468.40  4938.5  468.81  4959.3  468.39  5150.7  468.36
  5180.5  468.30  5180.7  467.80  5184.2  467.80  5184.5  468.30  5275.5  472.83
  5311.5  473.62  5347.5  475.38  5387.4  476.59  5398.5  476.75  5413.5  477.77
  5419.5  477.50  5428.5  478.14  5485.5  479.66  5506.5  479.46  5514.2  480.19
  5529.9  480.42  5533.8  480.51  5578.5  481.36  5593.5  482.33  5600.2  482.27
#Mann=7,-1,0
  4603.3    0.05       0  5150.7    0.12       0  5180.5    0.03       0
  5184.5    0.12       0  5387.4    0.05       0  5529.9    0.12       0
  5533.8    0.05       0
Bank Sta=5180.5,5184.5
Exp/Cntr=0.3,0.1

Type RM Length L Ch R = 1,1516,221,221,221
BEGIN DESCRIPTION:
Lacy 025 3145
END DESCRIPTION:
XS GIS Cut Line= 3
      2755280.52      6868775.71      2755659.72      6868499.16
      2755931.89      6868061.29
#Sta/Elev= 30
  4382.2  476.84  4417.8  475.52  4468.0  474.64  4488.9  473.62  4553.7  472.28
  4574.6  471.47  4583.1  470.61  4618.6  469.68  4633.3  468.48  4949.1  468.71
  4999.0  468.28  4999.3  467.78  5002.8  467.78  5003.0  468.28  5014.2  468.56
  5022.3  469.33  5028.2  469.04  5037.6  469.89  5043.5  469.48  5049.5  470.27
  5073.1  471.49  5101.4  471.76  5122.6  473.04  5217.1  474.95  5232.4  476.19
  5238.3  475.94  5261.5  476.38  5305.6  478.06  5311.5  477.73  5367.1  478.69
#Mann=3,-1,0
  4382.2    0.05       0  4999.0    0.03       0  5003.0    0.05       0
Bank Sta=4999,5003
Exp/Cntr=0.3,0.1

Type RM Length L Ch R = 1,1295,55,55,55
BEGIN DESCRIPTION:
Lacy 025 3144
END DESCRIPTION:
XS GIS Cut Line= 3
      2755322.73      6868776.71      2755775.13      6868582.07
      2756027.85      6868148.78
#Sta/Elev= 30
  4506.4  475.84  4542.6  474.86  4582.4  474.24  4597.1  473.59  4629.5  472.80
  4640.6  472.00  4673.3  471.10  4705.5  469.69  4716.8  468.47  4956.3  469.05
  4986.2  468.45  5014.0  468.67  5081.2  468.53  5109.9  468.89  5139.1  468.90
  5168.7  468.49  5218.1  468.43  5218.3  467.93  5221.8  467.93  5222.1  468.43
  5248.9  468.43  5254.8  468.75  5264.6  469.68  5270.4  469.89  5286.1  472.20
  5291.9  472.49  5344.8  473.92  5366.3  474.07  5440.0  476.55  5500.5  477.46
#Mann=3,-1,0
  4506.4    0.05       0  5218.1    0.03       0  5222.1    0.05       0
Bank Sta=5218.1,5222.1
Exp/Cntr=0.3,0.1

Type RM Length L Ch R = 1,1240,81,81,81
BEGIN DESCRIPTION:
Lacy 025 3142
END DESCRIPTION:
XS GIS Cut Line= 4
      2755365.31      6868834.05      2755703.92      6868718.88
      2755891.87      6868535.12      2756064.06      6868144.61
#Sta/Elev= 30
  4514.7  477.84  4666.3  471.52  4737.2  475.29  4914.8  475.70  4943.1  475.49
  4950.1  473.75  4957.2  475.08  4964.2  473.14  4971.4  474.56  4978.4  472.55
  4985.5  474.69  4992.5  471.66  4999.7  473.43  5004.7  470.79  5004.9  470.29
  5008.7  470.79  5013.8  472.66  5020.8  471.18  5028.0  473.73  5035.0  471.66
  5042.1  473.74  5049.1  472.00  5056.3  474.06  5063.2  472.50  5070.4  474.46
  5077.4  473.22  5098.7  474.69  5249.0  475.08  5369.2  473.49  5562.0  477.58
#Mann=3,-1,0
  4514.7    0.05       0  5004.7    0.04       0  5008.7    0.05       0
Bank Sta=5004.7,5008.7
Exp/Cntr=0.3,0.1

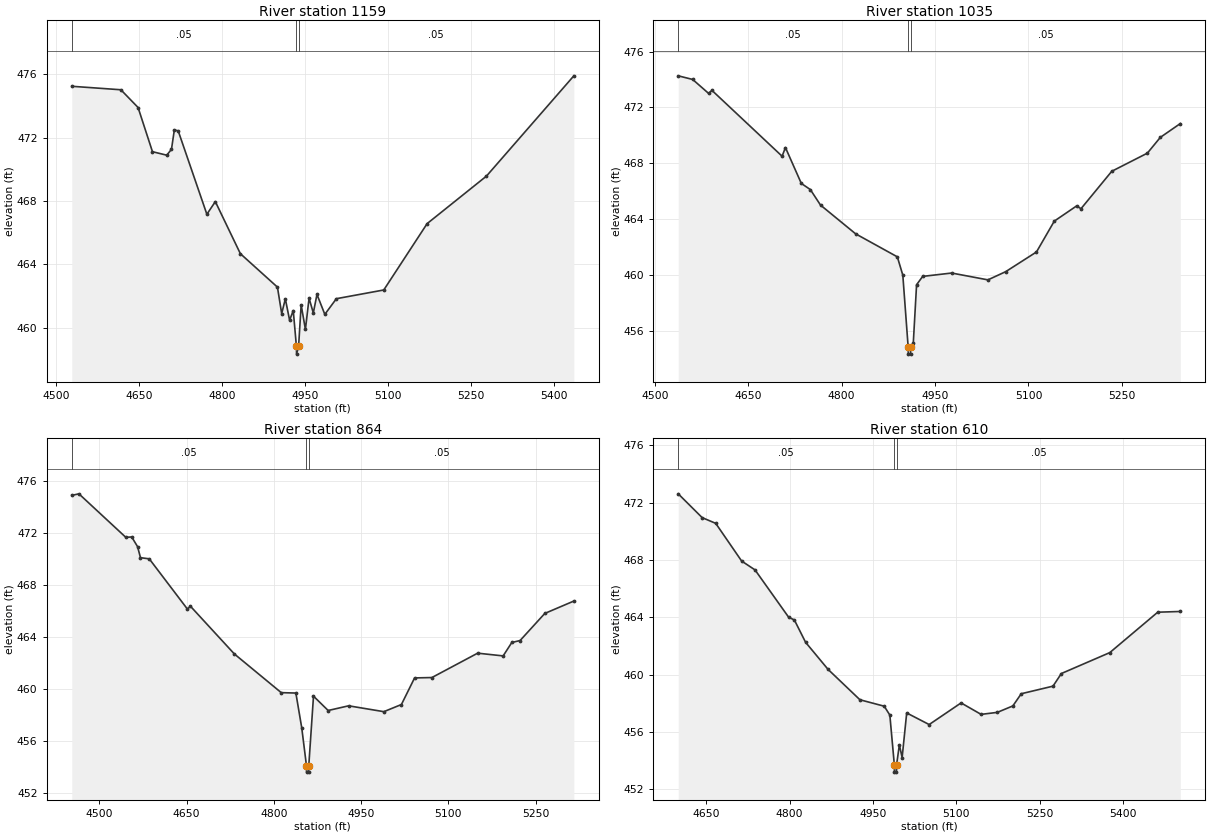
Type RM Length L Ch R = 1,1159,124,124,124
BEGIN DESCRIPTION:
Lacy 025 3143
END DESCRIPTION:
XS GIS Cut Line= 4
      2755430.40      6868874.59      2755727.80      6868793.06
      2755978.83      6868580.52      2756080.36      6868329.69
#Sta/Elev= 30
  4528.5  475.25  4617.3  475.03  4648.4  473.91  4674.4  471.12  4700.2  470.90
  4708.8  471.27  4714.0  472.50  4721.0  472.43  4772.8  467.17  4788.1  467.97
  4833.4  464.68  4900.4  462.57  4908.1  460.90  4914.7  461.83  4922.4  460.48
  4929.0  461.09  4934.7  458.84  4935.0  458.34  4938.7  458.84  4943.3  461.45
  4951.0  459.90  4957.6  461.87  4965.3  460.94  4971.9  462.11  4986.1  460.85
  5007.0  461.84  5092.7  462.39  5171.1  466.58  5278.4  469.58  5436.4  475.91
#Mann=3,-1,0
  4528.5    0.05       0  4934.7    0.05       0  4938.7    0.05       0
Bank Sta=4934.7,4938.7
Exp/Cntr=0.3,0.1

Type RM Length L Ch R = 1,1035,171,171,171
BEGIN DESCRIPTION:
Lacy 025 3141
END DESCRIPTION:
XS GIS Cut Line= 3
      2755506.10      6868932.70      2755933.60      6868780.75
      2756203.34      6868553.51
#Sta/Elev= 30
  4537.5  474.26  4560.7  474.00  4586.3  473.00  4591.6  473.22  4704.3  468.50
  4709.7  469.12  4735.2  466.55  4749.7  466.11  4766.0  465.00  4822.4  462.94
  4889.4  461.29  4898.2  459.98  4906.8  454.82  4907.1  454.32  4910.6  454.32
  4910.8  454.82  4915.0  455.09  4920.3  459.29  4930.1  459.89  4976.7  460.13
  5034.9  459.64  5063.5  460.23  5112.9  461.64  5141.5  463.85  5177.4  464.94
  5184.4  464.74  5233.8  467.42  5291.0  468.72  5311.8  469.85  5343.9  470.84
#Mann=3,-1,0
  4537.5    0.05       0  4906.8    0.04       0  4910.8    0.05       0
Bank Sta=4906.8,4910.8
Exp/Cntr=0.3,0.1

Type RM Length L Ch R = 1,864,254,254,254
BEGIN DESCRIPTION:
Lacy 025 3161
END DESCRIPTION:
XS GIS Cut Line= 3
      2755483.83      6868980.66      2756058.00      6868908.90
      2756219.29      6868674.94
#Sta/Elev= 30
  4452.8  474.88  4465.1  475.00  4545.7  471.66  4555.8  471.69  4565.8  470.95
  4570.9  470.10  4586.0  470.01  4651.6  466.15  4656.6  466.38  4732.2  462.71
  4812.8  459.74  4837.9  459.71  4848.0  457.04  4856.1  454.14  4856.3  453.64
  4859.8  453.64  4860.1  454.14  4868.2  459.47  4893.4  458.37  4928.6  458.73
  4989.1  458.28  5019.3  458.83  5041.9  460.87  5071.7  460.90  5150.3  462.77
  5194.1  462.56  5209.0  463.59  5223.2  463.74  5265.7  465.82  5315.6  466.77
#Mann=3,-1,0
  4452.8    0.05       0  4856.1    0.04       0  4860.1    0.05       0
Bank Sta=4856.1,4860.1
Exp/Cntr=0.3,0.1

Type RM Length L Ch R = 1,610,0,0,0
BEGIN DESCRIPTION:
Lacy 025 3160
END DESCRIPTION:
XS GIS Cut Line= 3
      2755529.30      6869192.18      2755982.22      6869127.86
      2756229.04      6868757.18
#Sta/Elev= 30
  4599.8  472.62  4642.8  470.96  4667.2  470.56  4713.8  467.93  4737.9  467.31
  4798.5  464.00  4808.6  463.82  4828.8  462.26  4869.2  460.37  4926.5  458.25
  4970.2  457.80  4980.3  457.18  4988.4  453.70  4988.6  453.20  4992.1  453.20
  4992.4  453.70  4997.4  455.10  5002.4  454.22  5010.6  457.33  5051.0  456.52
  5108.4  458.03  5144.4  457.23  5173.6  457.37  5201.5  457.82  5216.6  458.67
  5273.7  459.20  5288.7  460.08  5375.8  461.54  5462.0  464.36  5502.6  464.41
#Mann=3,-1,0
  4599.8    0.05       0  4988.4    0.04       0  4992.4    0.05       0
Bank Sta=4988.4,4992.4
Exp/Cntr=0.3,0.1

Chan Stop Cuts=-1