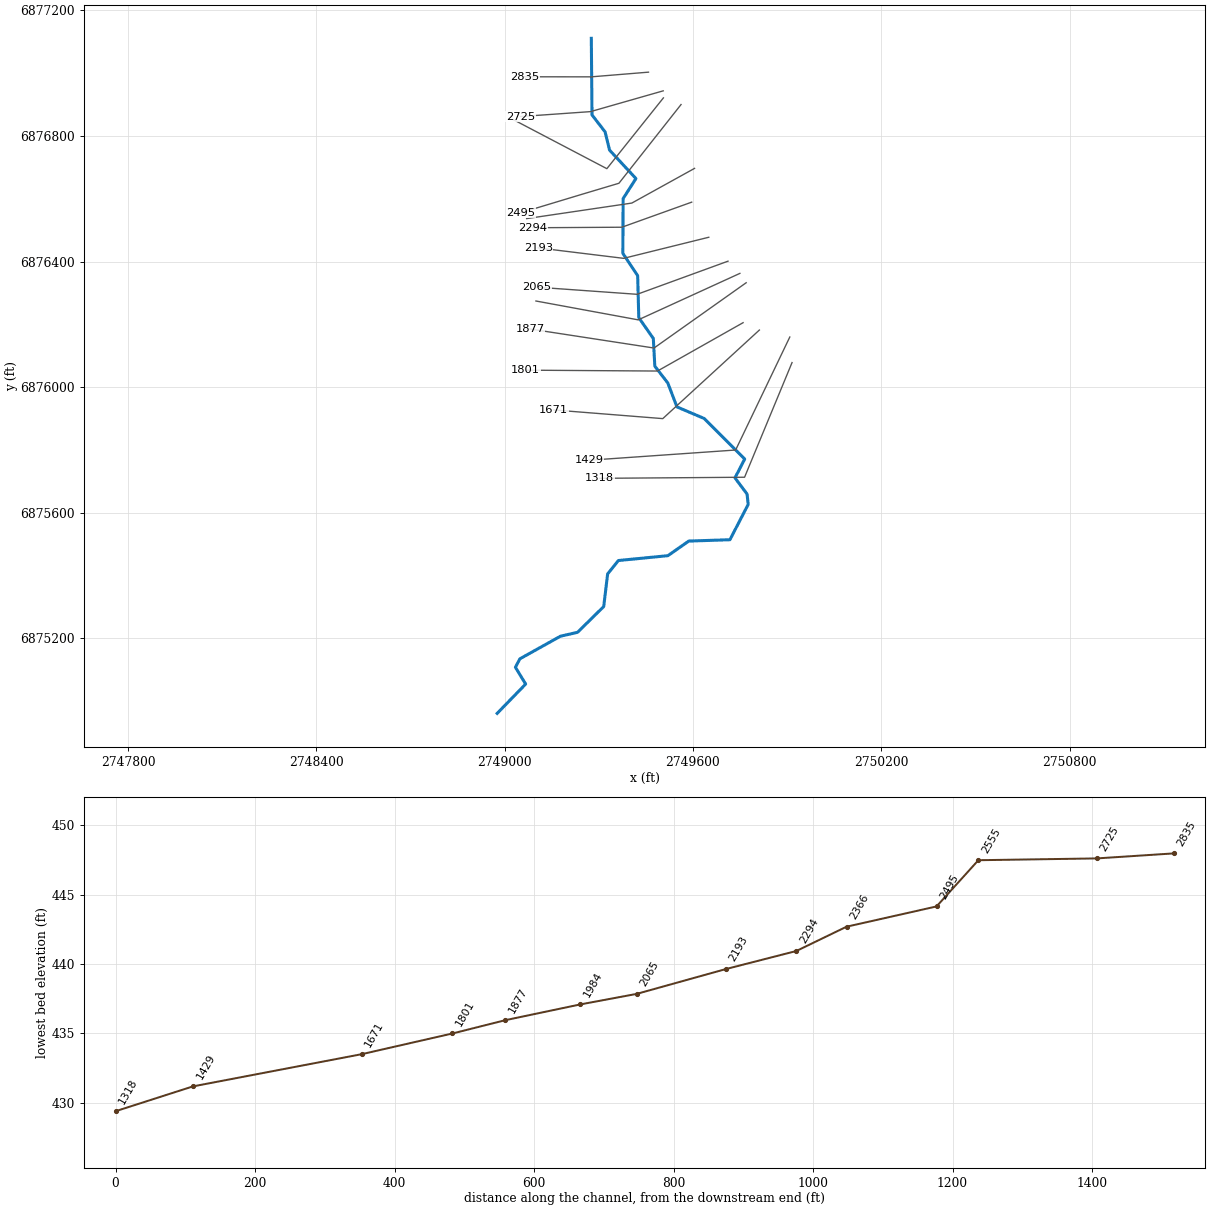
--- Lacy 026.prj (project) ---

Proj Title=Lacy 026 Base Level Engineering
Current Plan=p01
Default Exp/Contr=0.3,0.1
English Units
Geom File=g01
Flow File=f01
Plan File=p01
BEGIN DESCRIPTION:
Lacy 026
END DESCRIPTION:

--- Lacy 026.p01 (plan) ---

Plan Title=Multiple Run
Short Identifier=Multiple
Geom File=g01
Flow File=f01
Subcritical Flow
K Sum by GR= 0
Std Step Tol= 0.01
Critical Tol= 0.01
Num of Std Step Trials= 20
Max Error Tol= 0.3
Flow Tol Ratio= 0.001
Split Flow NTrial= 30
Split Flow Tol= 0.02
Split Flow Ratio= 0.02
Log Output Level= 0
Friction Slope Method= 1
Unsteady Friction Slope Method= 2
Unsteady Bridges Friction Slope Method= 1
Parabolic Critical Depth
Global Vel Dist=  1 , 1 , 1
Global Log Level= 0
CheckData=True
Encroach Param= -1, 0, 0, 0
BEGIN DESCRIPTION:
Multiple Run
END DESCRIPTION:

--- Lacy 026.f01 (steady flow) ---

Flow Title=Multiple
Number of Profiles=7
Profile Names=10-year,25-year,50-year,1pct_min,100-year,1pct_plu,500-year
River Rch & RM= Lacy 026,Reach-1,2835
     136     165     187     106     212     423     270
Boundary for River Rch & Prof#=Lacy 026,Reach-1,1
Up Type=0
Dn Type=3
Dn Slope=0.005
Boundary for River Rch & Prof#=Lacy 026,Reach-1,2
Up Type=0
Dn Type=3
Dn Slope=0.005
Boundary for River Rch & Prof#=Lacy 026,Reach-1,3
Up Type=0
Dn Type=3
Dn Slope=0.005
Boundary for River Rch & Prof#=Lacy 026,Reach-1,4
Up Type=0
Dn Type=3
Dn Slope=0.005
Boundary for River Rch & Prof#=Lacy 026,Reach-1,5
Up Type=0
Dn Type=3
Dn Slope=0.005
Boundary for River Rch & Prof#=Lacy 026,Reach-1,6
Up Type=0
Dn Type=3
Dn Slope=0.005
Boundary for River Rch & Prof#=Lacy 026,Reach-1,7
Up Type=0
Dn Type=3
Dn Slope=0.005

--- Lacy 026.g01 (geometry) ---

Geom Title=Existing Conditions

River Reach=Lacy 026,Reach-1
Reach XY= 30
      2749276.00      6877111.00      2749278.24      6876866.93
      2749319.86      6876813.17      2749334.18      6876754.94
      2749418.19      6876664.41      2749377.39      6876600.57
      2749376.52      6876426.22      2749423.73      6876355.06
      2749427.23      6876221.51      2749473.64      6876155.02
      2749478.33      6876066.96      2749519.85      6876013.15
      2749548.85      6875937.16      2749635.66      6875900.21
      2749764.76      6875771.00      2749733.84      6875711.09
      2749772.41      6875659.36      2749775.87      6875626.40
      2749717.72      6875514.07      2749586.52      6875509.76
      2749520.06      6875463.27      2749362.27      6875447.80
      2749328.07      6875405.31      2749315.49      6875301.19
      2749232.07      6875219.13      2749177.73      6875206.81
      2749048.36      6875134.71      2749034.07      6875107.85
      2749066.82      6875054.34      2748976.00      6874961.00

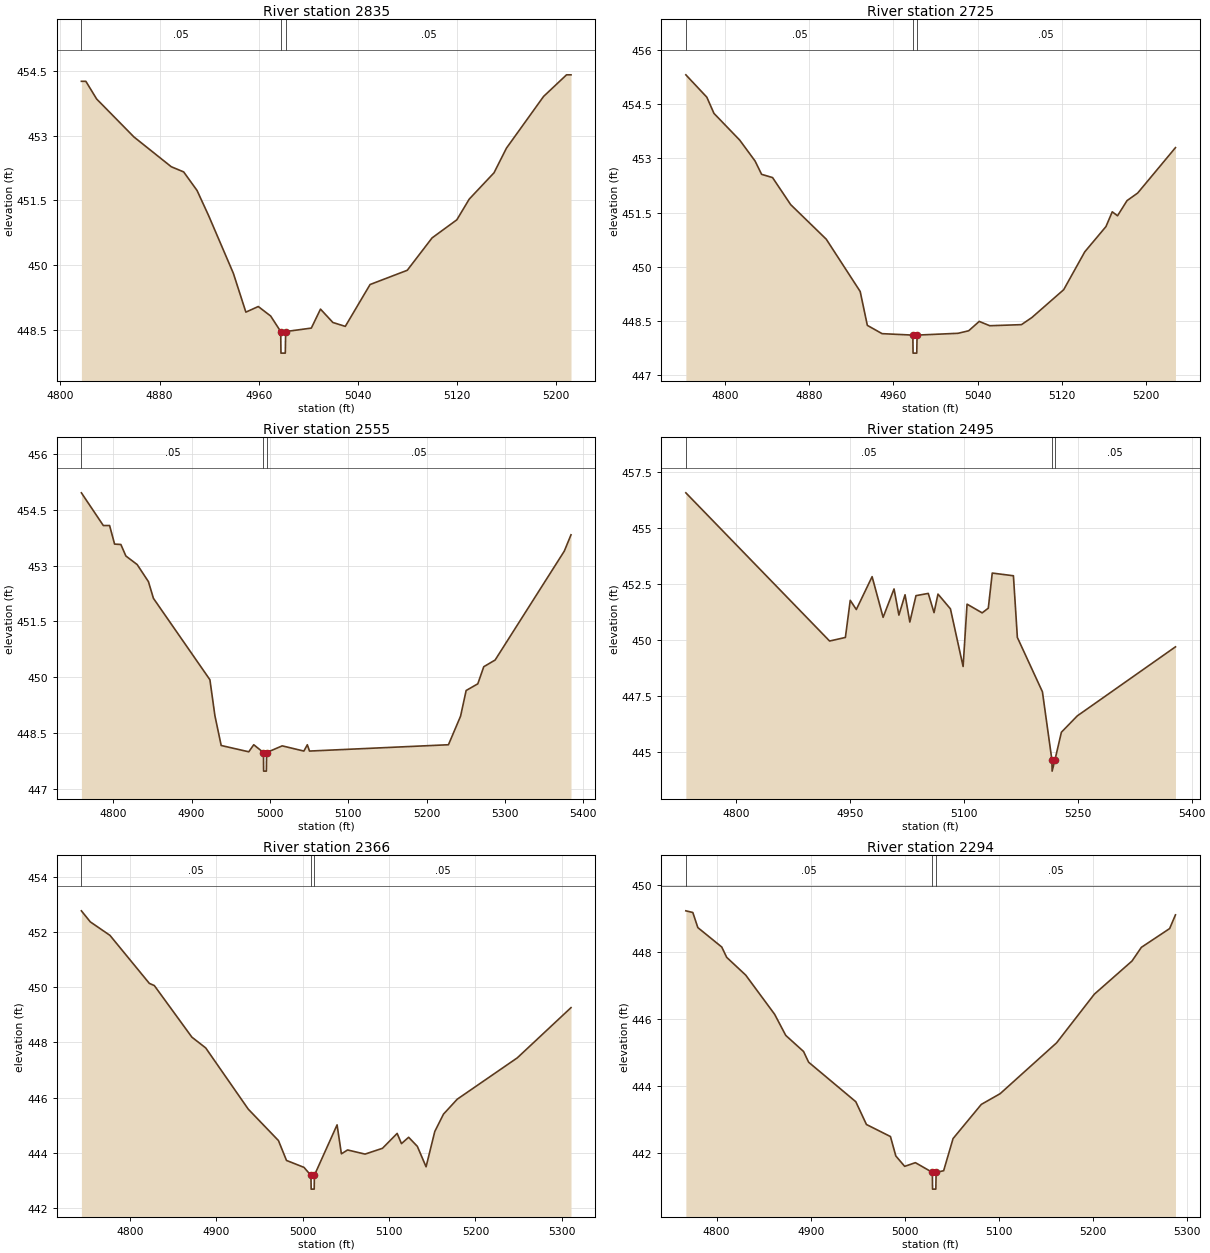
Type RM Length L Ch R = 1,2835,110,110,110
BEGIN DESCRIPTION:
Lacy 026 3082
END DESCRIPTION:
XS GIS Cut Line= 3
      2749458.24      6877003.27      2749275.75      6876988.34
      2749063.85      6876988.56
#Sta/Elev= 30
  4816.9  454.26  4820.5  454.26  4829.2  453.85  4859.3  452.97  4889.4  452.28
  4899.4  452.16  4910.2  451.73  4919.5  451.15  4939.5  449.81  4949.6  448.91
  4959.6  449.04  4969.6  448.82  4977.7  448.46  4977.9  447.96  4981.4  447.96
  4981.7  448.46  5002.4  448.54  5009.8  448.98  5019.8  448.67  5029.8  448.58
  5049.8  449.55  5079.8  449.88  5099.8  450.63  5119.8  451.05  5129.8  451.53
  5149.8  452.14  5159.8  452.71  5189.8  453.91  5208.3  454.41  5211.9  454.41
#Mann=3,-1,0
  4816.9    0.05       0  4977.7    0.04       0  4981.7    0.05       0
Bank Sta=4977.7,4981.7
Exp/Cntr=0.3,0.1

Type RM Length L Ch R = 1,2725,170,170,170
BEGIN DESCRIPTION:
Lacy 026 3076
END DESCRIPTION:
XS GIS Cut Line= 3
      2749505.13      6876943.78      2749273.40      6876877.58
      2749050.15      6876861.85
#Sta/Elev= 30
  4762.9  455.32  4782.8  454.70  4789.6  454.25  4814.0  453.51  4828.6  452.93
  4834.8  452.56  4845.2  452.47  4862.4  451.72  4896.2  450.76  4928.4  449.31
  4935.2  448.37  4949.2  448.14  4978.4  448.10  4978.6  447.60  4982.1  447.60
  4982.4  448.10  5021.3  448.15  5031.4  448.22  5041.4  448.48  5051.4  448.36
  5081.5  448.39  5091.5  448.59  5121.6  449.36  5141.6  450.41  5161.7  451.11
  5167.7  451.52  5172.7  451.41  5181.7  451.83  5191.8  452.04  5227.7  453.30
#Mann=3,-1,0
  4762.9    0.05       0  4978.4    0.04       0  4982.4    0.05       0
Bank Sta=4978.4,4982.4
Exp/Cntr=0.3,0.1

Type RM Length L Ch R = 1,2555,60,60,60
BEGIN DESCRIPTION:
Lacy 026 3075
END DESCRIPTION:
XS GIS Cut Line= 3
      2749505.70      6876921.30      2749325.54      6876695.88
      2749027.37      6876852.12
#Sta/Elev= 30
  4759.3  454.96  4787.3  454.08  4795.3  454.08  4801.7  453.58  4809.7  453.57
  4816.1  453.26  4830.5  453.03  4844.9  452.57  4851.3  452.12  4923.4  449.93
  4929.8  448.96  4937.8  448.16  4973.0  447.99  4979.4  448.18  4991.8  447.97
  4992.0  447.47  4995.5  447.47  4995.8  447.97  5015.7  448.15  5043.4  448.01
  5047.8  448.18  5050.6  448.01  5228.0  448.18  5243.5  448.95  5250.6  449.64
  5265.5  449.82  5273.1  450.28  5287.6  450.46  5375.9  453.39  5384.5  453.83
#Mann=3,-1,0
  4759.3    0.05       0  4991.8    0.04       0  4995.8    0.05       0
Bank Sta=4991.8,4995.8
Exp/Cntr=0.3,0.1

Type RM Length L Ch R = 1,2495,129,129,129
BEGIN DESCRIPTION:
Lacy 026 3072
END DESCRIPTION:
XS GIS Cut Line= 4
      2749561.94      6876900.11      2749364.02      6876649.43
      2749250.37      6876615.52      2749052.09      6876555.69
#Sta/Elev= 30
  4733.6  456.59  4923.0  449.96  4943.8  450.12  4950.2  451.78  4958.2  451.37
  4979.0  452.84  4993.5  451.02  5007.9  452.29  5014.3  451.12  5022.4  452.03
  5028.7  450.81  5036.8  451.99  5053.0  452.09  5060.6  451.23  5065.8  452.06
  5082.2  451.40  5098.9  448.82  5104.1  451.61  5124.0  451.22  5132.1  451.43
  5137.3  453.00  5165.2  452.88  5170.4  450.12  5203.4  447.69  5215.9  444.64
  5216.2  444.14  5219.9  444.64  5228.4  445.88  5249.3  446.61  5378.7  449.70
#Mann=3,-1,0
  4733.6    0.05       0  5215.9    0.04       0  5219.9    0.05       0
Bank Sta=5215.9,5219.9
Exp/Cntr=0.3,0.1

Type RM Length L Ch R = 1,2366,72,72,72
BEGIN DESCRIPTION:
Lacy 026 3074
END DESCRIPTION:
XS GIS Cut Line= 3
      2749605.00      6876696.81      2749405.16      6876586.35
      2749069.93      6876536.84
#Sta/Elev= 30
  4743.5  452.77  4753.8  452.37  4776.6  451.88  4822.2  450.14  4828.0  450.06
  4871.5  448.19  4887.5  447.80  4936.8  445.58  4971.8  444.44  4981.1  443.72
  5001.3  443.47  5009.4  443.18  5009.7  442.68  5013.2  442.68  5013.4  443.18
  5039.7  445.01  5044.7  443.96  5051.9  444.10  5072.1  443.95  5092.3  444.16
  5109.3  444.70  5114.3  444.33  5122.6  444.56  5132.7  444.23  5142.8  443.49
  5152.9  444.77  5163.0  445.40  5178.9  445.94  5248.5  447.44  5310.7  449.26
#Mann=3,-1,0
  4743.5    0.05       0  5009.4    0.04       0  5013.4    0.05       0
Bank Sta=5009.4,5013.4
Exp/Cntr=0.3,0.1

Type RM Length L Ch R = 1,2294,101,101,101
BEGIN DESCRIPTION:
Lacy 026 3073
END DESCRIPTION:
XS GIS Cut Line= 3
      2749595.89      6876589.23      2749373.27      6876509.38
      2749089.78      6876507.72
#Sta/Elev= 30
  4767.4  449.24  4774.8  449.19  4780.1  448.74  4805.5  448.16  4810.8  447.85
  4831.0  447.32  4861.7  446.15  4873.5  445.52  4892.4  445.04  4897.8  444.72
  4947.9  443.54  4959.2  442.86  4984.7  442.50  4990.4  441.92  4999.8  441.61
  5011.2  441.72  5029.2  441.43  5029.4  440.93  5032.9  440.93  5033.2  441.43
  5041.2  441.48  5051.2  442.44  5081.2  443.46  5101.2  443.78  5161.2  445.30
  5201.2  446.75  5241.2  447.74  5251.2  448.15  5281.2  448.71  5287.4  449.12
#Mann=3,-1,0
  4767.4    0.05       0  5029.2    0.04       0  5033.2    0.05       0
Bank Sta=5029.2,5033.2
Exp/Cntr=0.3,0.1

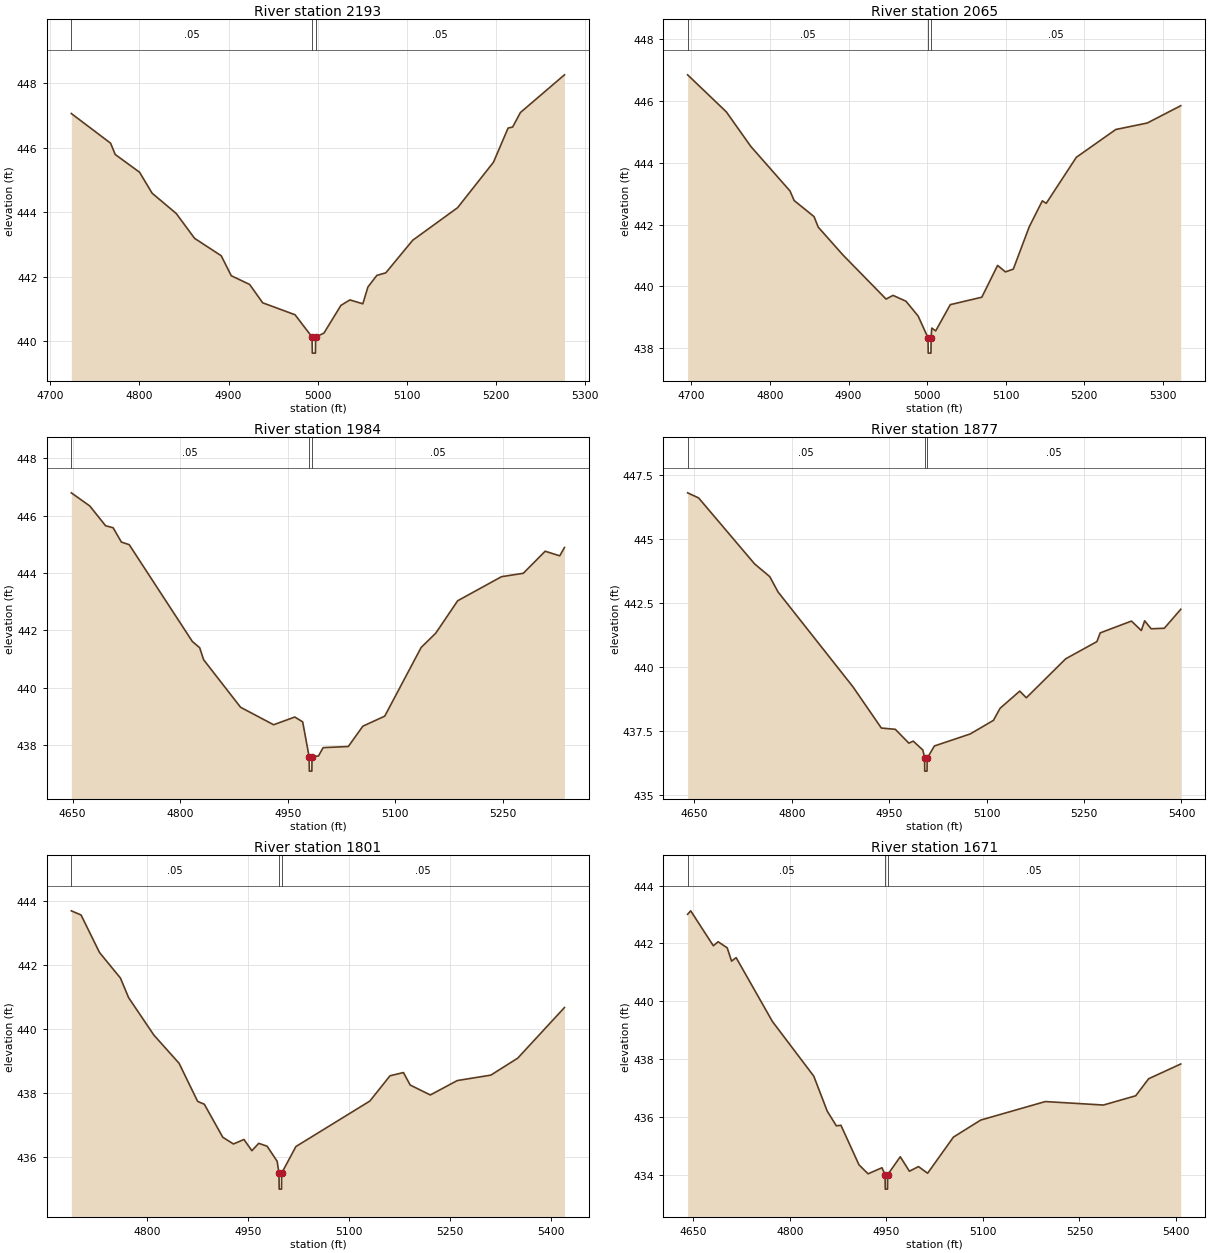
Type RM Length L Ch R = 1,2193,128,128,128
BEGIN DESCRIPTION:
Lacy 026 3071
END DESCRIPTION:
XS GIS Cut Line= 3
      2749650.36      6876477.46      2749379.03      6876410.28
      2749106.88      6876443.51
#Sta/Elev= 30
  4723.5  447.06  4767.6  446.14  4772.8  445.79  4800.1  445.24  4814.2  444.59
  4841.3  443.96  4861.9  443.19  4891.8  442.65  4903.1  442.03  4923.7  441.76
  4938.4  441.19  4974.7  440.82  4993.8  440.13  4994.1  439.63  4997.6  439.63
  4997.8  440.13  5007.1  440.25  5026.2  441.11  5036.3  441.28  5050.8  441.16
  5056.5  441.68  5066.5  442.04  5076.6  442.12  5106.8  443.13  5157.2  444.14
  5197.5  445.55  5213.9  446.61  5219.0  446.64  5227.7  447.09  5277.2  448.26
#Mann=3,-1,0
  4723.5    0.05       0  4993.8    0.04       0  4997.8    0.05       0
Bank Sta=4993.8,4997.8
Exp/Cntr=0.3,0.1

Type RM Length L Ch R = 1,2065,81,81,81
BEGIN DESCRIPTION:
Lacy 026 3069
END DESCRIPTION:
XS GIS Cut Line= 3
      2749711.64      6876401.27      2749421.93      6876295.73
      2749103.47      6876318.37
#Sta/Elev= 30
  4695.2  446.85  4744.5  445.65  4775.7  444.53  4825.5  443.09  4830.8  442.78
  4856.1  442.26  4861.4  441.92  4892.8  441.02  4947.8  439.59  4956.6  439.71
  4973.1  439.52  4988.6  439.04  5001.1  438.34  5001.4  437.84  5004.9  437.84
  5005.1  438.34  5005.9  438.65  5010.9  438.56  5029.5  439.41  5069.6  439.65
  5089.7  440.68  5099.7  440.47  5109.7  440.56  5129.8  441.92  5146.6  442.77
  5151.6  442.69  5189.9  444.18  5240.1  445.08  5280.2  445.29  5322.8  445.85
#Mann=3,-1,0
  4695.2    0.05       0  5001.1    0.04       0  5005.1    0.05       0
Bank Sta=5001.1,5005.1
Exp/Cntr=0.3,0.1

Type RM Length L Ch R = 1,1984,107,107,107
BEGIN DESCRIPTION:
Lacy 026 3068
END DESCRIPTION:
XS GIS Cut Line= 3
      2749749.44      6876362.36      2749425.50      6876214.34
      2749099.54      6876274.40
#Sta/Elev= 30
  4648.2  446.80  4674.0  446.34  4696.0  445.65  4706.5  445.58  4718.0  445.08
  4728.9  444.99  4816.9  441.61  4827.2  441.39  4832.7  440.97  4884.2  439.31
  4930.3  438.70  4959.8  438.97  4970.8  438.80  4979.8  437.58  4980.1  437.08
  4983.6  437.08  4983.8  437.58  4992.8  437.61  4999.3  437.90  5034.4  437.94
  5054.7  438.65  5085.2  439.00  5136.0  441.40  5156.4  441.90  5186.9  443.03
  5247.9  443.87  5278.4  443.99  5308.9  444.76  5329.2  444.60  5335.8  444.89
#Mann=3,-1,0
  4648.2    0.05       0  4979.8    0.04       0  4983.8    0.05       0
Bank Sta=4979.8,4983.8
Exp/Cntr=0.3,0.1

Type RM Length L Ch R = 1,1877,76,76,76
BEGIN DESCRIPTION:
Lacy 026 3067
END DESCRIPTION:
XS GIS Cut Line= 3
      2749769.48      6876332.56      2749475.83      6876124.61
      2749080.97      6876185.20
#Sta/Elev= 30
  4639.6  446.80  4656.6  446.60  4742.7  444.03  4766.2  443.53  4778.7  442.94
  4894.1  439.24  4937.9  437.63  4959.4  437.58  4980.3  437.04  4987.0  437.12
  5001.9  436.77  5004.5  436.45  5004.7  435.95  5008.2  435.95  5008.5  436.45
  5019.5  436.93  5074.8  437.40  5110.5  437.93  5120.7  438.40  5151.0  439.07
  5161.1  438.81  5221.8  440.33  5269.8  441.00  5274.9  441.34  5323.0  441.80
  5338.2  441.43  5343.3  441.81  5353.3  441.50  5373.6  441.52  5398.9  442.26
#Mann=3,-1,0
  4639.6    0.05       0  5004.5    0.04       0  5008.5    0.05       0
Bank Sta=5004.5,5008.5
Exp/Cntr=0.3,0.1

Type RM Length L Ch R = 1,1801,130,130,130
BEGIN DESCRIPTION:
Lacy 026 3081
END DESCRIPTION:
XS GIS Cut Line= 3
      2749759.67      6876205.35      2749486.83      6876051.34
      2749066.54      6876054.10
#Sta/Elev= 30
  4686.7  443.68  4701.2  443.55  4728.6  442.38  4759.8  441.58  4771.9  440.97
  4809.5  439.80  4847.0  438.92  4874.6  437.73  4884.6  437.64  4912.0  436.61
  4927.9  436.40  4943.5  436.54  4955.3  436.19  4965.5  436.42  4978.0  436.33
  4992.9  435.86  4995.6  435.49  4995.9  434.99  4999.4  434.99  4999.6  435.49
  5020.8  436.32  5130.8  437.74  5160.8  438.53  5180.8  438.63  5190.8  438.24
  5220.8  437.93  5260.8  438.38  5310.8  438.55  5350.8  439.08  5420.3  440.66
#Mann=3,-1,0
  4686.7    0.05       0  4995.6    0.04       0  4999.6    0.05       0
Bank Sta=4995.6,4999.6
Exp/Cntr=0.3,0.1

Type RM Length L Ch R = 1,1671,242,242,242
BEGIN DESCRIPTION:
Lacy 026 3080
END DESCRIPTION:
XS GIS Cut Line= 3
      2749811.59      6876181.95      2749503.73      6875899.80
      2749156.22      6875927.43
#Sta/Elev= 30
  4641.2  443.01  4646.0  443.13  4681.2  441.92  4688.6  442.06  4702.7  441.85
  4709.5  441.39  4716.6  441.51  4773.0  439.30  4837.2  437.41  4858.1  436.20
  4872.3  435.69  4879.4  435.71  4907.5  434.34  4921.6  434.03  4943.2  434.24
  4948.0  434.00  4948.3  433.50  4951.8  433.50  4952.0  434.00  4971.6  434.62
  4985.8  434.12  4999.9  434.28  5014.1  434.05  5054.2  435.30  5096.6  435.89
  5197.0  436.53  5287.2  436.41  5337.4  436.73  5357.5  437.32  5407.4  437.83
#Mann=3,-1,0
  4641.2    0.05       0  4948.0    0.04       0  4952.0    0.05       0
Bank Sta=4948,4952
Exp/Cntr=0.3,0.1

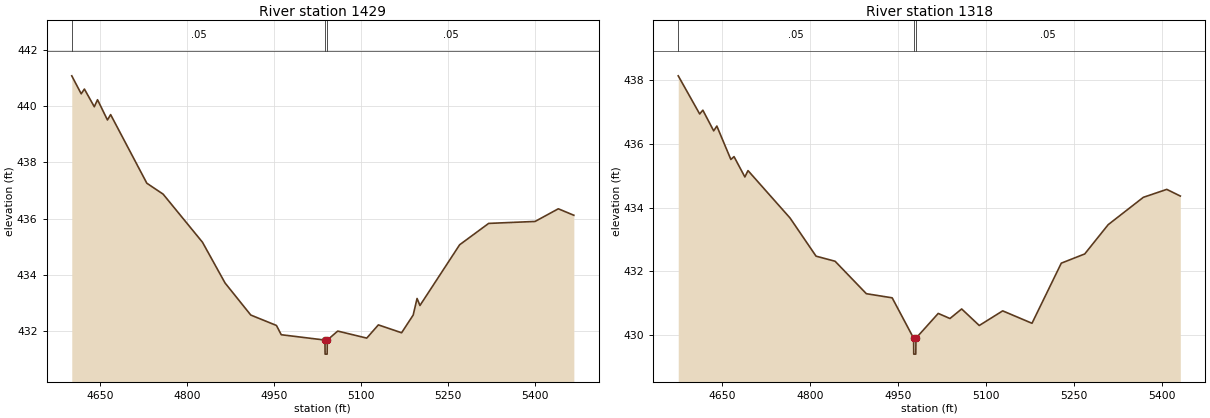
Type RM Length L Ch R = 1,1429,111,111,111
BEGIN DESCRIPTION:
Lacy 026 3079
END DESCRIPTION:
XS GIS Cut Line= 3
      2749908.51      6876159.70      2749735.97      6875799.82
      2749269.30      6875767.27
#Sta/Elev= 30
  4600.9  441.08  4617.2  440.44  4622.7  440.61  4639.8  439.98  4645.4  440.23
  4662.5  439.51  4668.0  439.70  4730.5  437.26  4758.7  436.87  4826.6  435.16
  4865.6  433.71  4910.0  432.57  4954.3  432.20  4962.6  431.87  5038.1  431.68
  5038.3  431.18  5041.8  431.18  5042.1  431.68  5060.1  432.00  5110.2  431.75
  5130.3  432.22  5170.4  431.94  5190.4  432.57  5197.1  433.16  5202.1  432.91
  5270.6  435.07  5320.7  435.83  5400.9  435.90  5441.0  436.35  5467.8  436.12
#Mann=3,-1,0
  4600.9    0.05       0  5038.1    0.04       0  5042.1    0.05       0
Bank Sta=5038.1,5042.1
Exp/Cntr=0.3,0.1

Type RM Length L Ch R = 1,1318,0,0,0
BEGIN DESCRIPTION:
Lacy 026 3078
END DESCRIPTION:
XS GIS Cut Line= 3
      2749915.65      6876078.29      2749764.38      6875713.10
      2749302.87      6875709.64
#Sta/Elev= 30
  4574.9  438.14  4611.5  436.94  4616.9  437.06  4635.4  436.41  4640.8  436.56
  4664.7  435.51  4670.1  435.60  4688.6  434.96  4694.0  435.16  4765.7  433.67
  4810.1  432.47  4842.6  432.31  4895.9  431.29  4940.0  431.16  4976.6  429.89
  4976.8  429.39  4980.3  429.39  4980.6  429.89  5018.6  430.67  5038.6  430.51
  5058.6  430.81  5088.6  430.29  5128.6  430.75  5178.6  430.36  5228.6  432.25
  5268.6  432.54  5308.6  433.46  5368.6  434.32  5408.6  434.57  5431.7  434.36
#Mann=3,-1,0
  4574.9    0.05       0  4976.6    0.05       0  4980.6    0.05       0
Bank Sta=4976.6,4980.6
Exp/Cntr=0.3,0.1

Chan Stop Cuts=-1