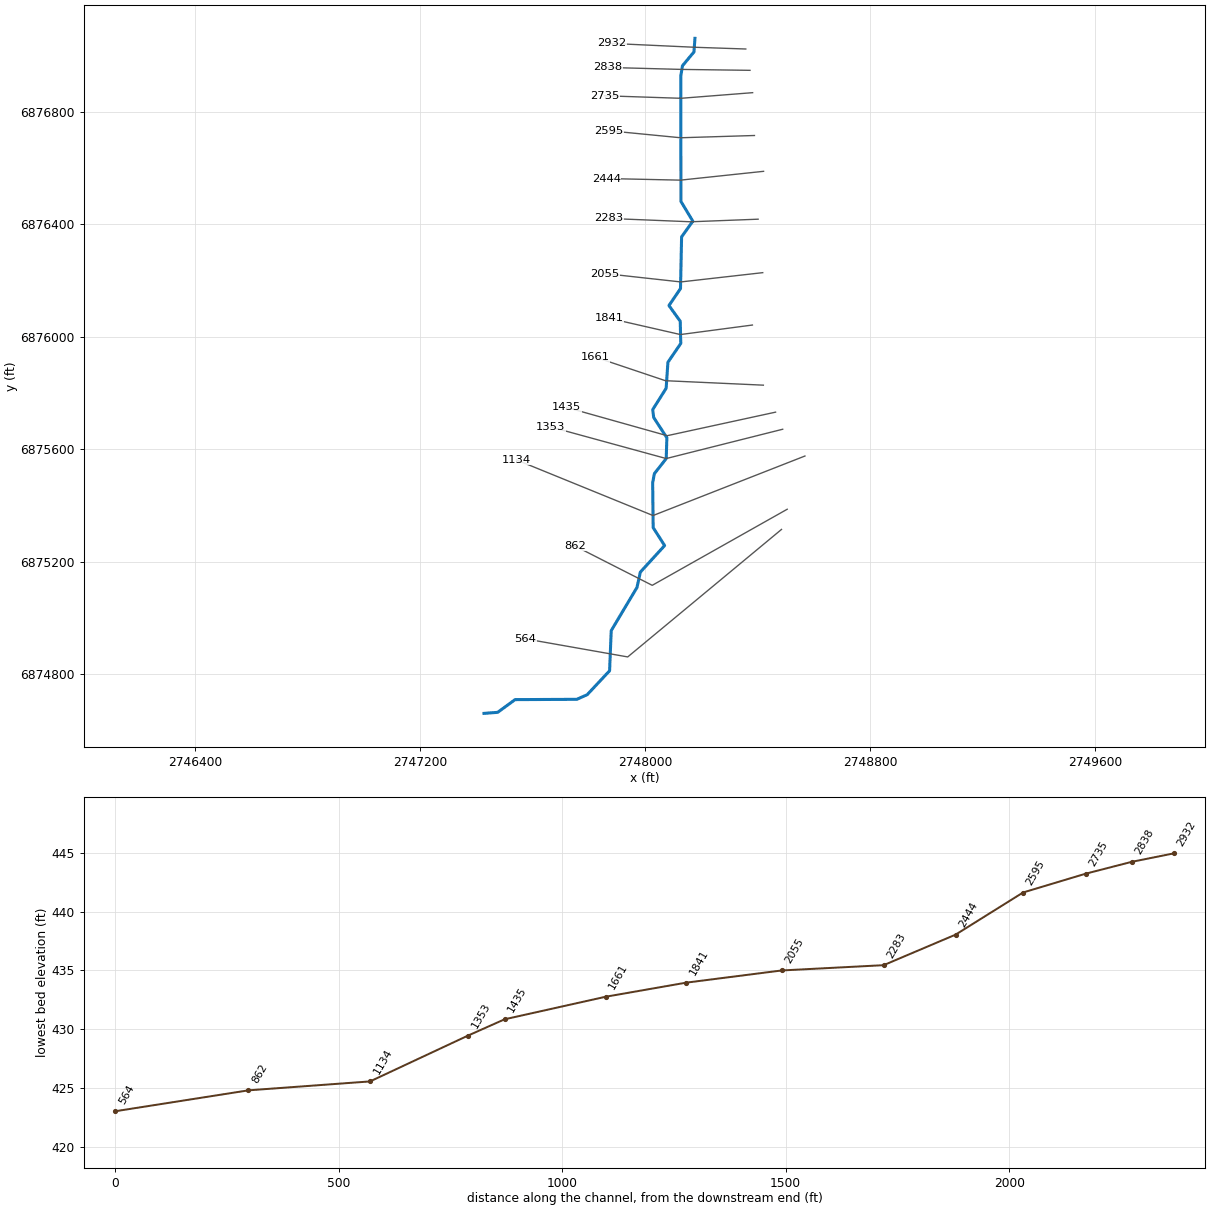
--- Lacy 027.prj (project) ---

Proj Title=Lacy 027 Base Level Engineering
Current Plan=p01
Default Exp/Contr=0.3,0.1
English Units
Geom File=g01
Flow File=f01
Plan File=p01
BEGIN DESCRIPTION:
Lacy 027
END DESCRIPTION:

--- Lacy 027.p01 (plan) ---

Plan Title=Multiple Run
Short Identifier=Multiple
Geom File=g01
Flow File=f01
Subcritical Flow
K Sum by GR= 0
Std Step Tol= 0.01
Critical Tol= 0.01
Num of Std Step Trials= 20
Max Error Tol= 0.3
Flow Tol Ratio= 0.001
Split Flow NTrial= 30
Split Flow Tol= 0.02
Split Flow Ratio= 0.02
Log Output Level= 0
Friction Slope Method= 1
Unsteady Friction Slope Method= 2
Unsteady Bridges Friction Slope Method= 1
Parabolic Critical Depth
Global Vel Dist=  1 , 1 , 1
Global Log Level= 0
CheckData=True
Encroach Param= -1, 0, 0, 0
BEGIN DESCRIPTION:
Multiple Run
END DESCRIPTION:

--- Lacy 027.f01 (steady flow) ---

Flow Title=Multiple
Number of Profiles=7
Profile Names=10-year,25-year,50-year,1pct_min,100-year,1pct_plu,500-year
River Rch & RM= Lacy 027,Reach-1,2932
     150     185     210     120     238     476     307
Boundary for River Rch & Prof#=Lacy 027,Reach-1,1
Up Type=0
Dn Type=3
Dn Slope=0.005
Boundary for River Rch & Prof#=Lacy 027,Reach-1,2
Up Type=0
Dn Type=3
Dn Slope=0.005
Boundary for River Rch & Prof#=Lacy 027,Reach-1,3
Up Type=0
Dn Type=3
Dn Slope=0.005
Boundary for River Rch & Prof#=Lacy 027,Reach-1,4
Up Type=0
Dn Type=3
Dn Slope=0.005
Boundary for River Rch & Prof#=Lacy 027,Reach-1,5
Up Type=0
Dn Type=3
Dn Slope=0.005
Boundary for River Rch & Prof#=Lacy 027,Reach-1,6
Up Type=0
Dn Type=3
Dn Slope=0.005
Boundary for River Rch & Prof#=Lacy 027,Reach-1,7
Up Type=0
Dn Type=3
Dn Slope=0.005

--- Lacy 027.g01 (geometry) ---

Geom Title=Existing Conditions

River Reach=Lacy 027,Reach-1
Reach XY= 30
      2748176.00      6877061.00      2748172.35      6877012.51
      2748131.53      6876963.42      2748125.56      6876926.18
      2748126.18      6876480.98      2748168.44      6876411.00
      2748128.46      6876355.14      2748124.62      6876171.44
      2748083.56      6876111.00      2748123.64      6876055.11
      2748125.61      6875976.28      2748079.86      6875909.40
      2748073.62      6875816.97      2748025.72      6875740.82
      2748029.38      6875712.73      2748076.08      6875640.91
      2748073.83      6875566.98      2748031.75      6875513.33
      2748025.64      6875481.15      2748027.39      6875321.43
      2748068.19      6875257.59      2747981.86      6875163.30
      2747969.90      6875108.81      2747878.25      6874955.07
      2747872.46      6874812.46      2747792.80      6874727.41
      2747756.02      6874710.96      2747536.46      6874709.88
      2747474.49      6874664.65      2747426.00      6874661.00

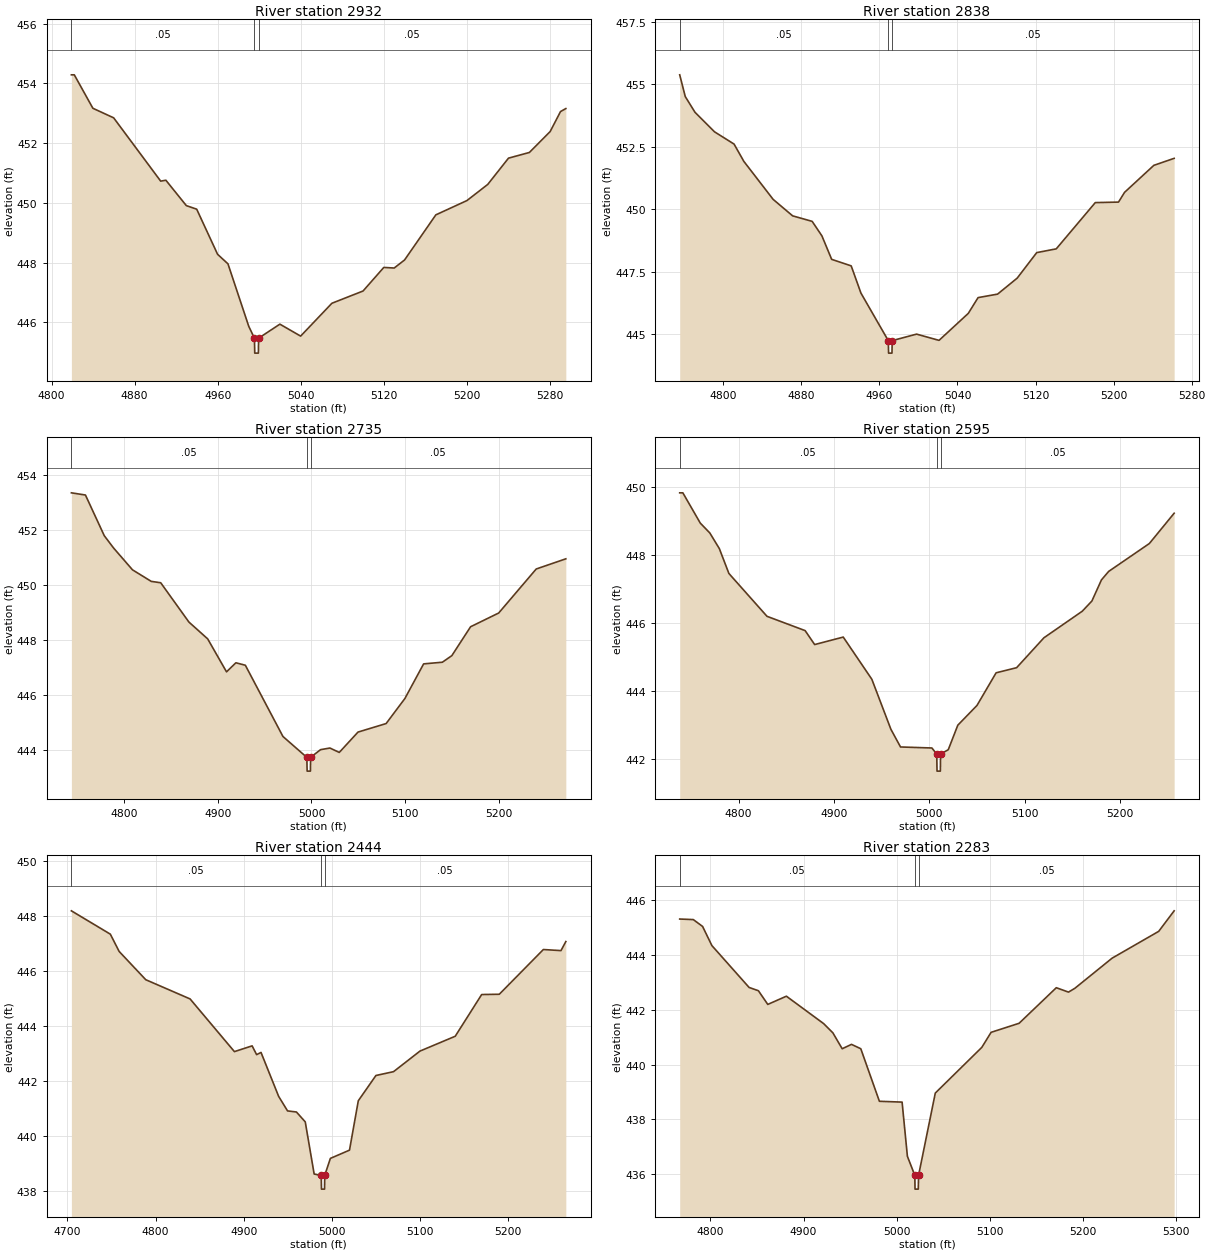
Type RM Length L Ch R = 1,2932,94,94,94
BEGIN DESCRIPTION:
Lacy 027 3061
END DESCRIPTION:
XS GIS Cut Line= 3
      2748356.68      6877023.08      2748175.88      6877029.20
      2747880.89      6877042.78
#Sta/Elev= 30
  4819.1  454.29  4821.9  454.29  4839.8  453.17  4859.8  452.85  4905.1  450.73
  4910.1  450.76  4929.8  449.91  4939.8  449.79  4959.9  448.28  4969.9  447.96
  4989.9  445.87  4995.4  445.47  4995.7  444.97  4999.2  444.97  4999.4  445.47
  5019.9  445.94  5039.9  445.54  5070.0  446.64  5100.0  447.05  5120.0  447.84
  5130.0  447.82  5140.0  448.09  5170.1  449.60  5200.1  450.08  5220.1  450.62
  5240.1  451.50  5260.2  451.69  5280.2  452.39  5290.2  453.06  5295.3  453.16
#Mann=3,-1,0
  4819.1    0.05       0  4995.4    0.04       0  4999.4    0.05       0
Bank Sta=4995.4,4999.4
Exp/Cntr=0.3,0.1

Type RM Length L Ch R = 1,2838,103,103,103
BEGIN DESCRIPTION:
Lacy 027 3060
END DESCRIPTION:
XS GIS Cut Line= 3
      2748371.69      6876947.24      2748127.12      6876950.54
      2747865.21      6876957.56
#Sta/Elev= 30
  4755.4  455.38  4761.1  454.51  4771.1  453.88  4791.1  453.10  4811.1  452.61
  4821.1  451.92  4851.1  450.40  4871.1  449.74  4891.1  449.52  4901.1  448.94
  4911.1  448.00  4931.1  447.74  4941.1  446.65  4969.1  444.75  4969.4  444.25
  4972.9  444.25  4973.1  444.75  4998.1  445.01  5021.1  444.76  5051.1  445.84
  5061.1  446.47  5081.1  446.61  5101.2  447.25  5121.2  448.27  5141.2  448.42
  5181.2  450.27  5205.0  450.29  5211.2  450.68  5241.2  451.76  5262.0  452.04
#Mann=3,-1,0
  4755.4    0.05       0  4969.1    0.04       0  4973.1    0.05       0
Bank Sta=4969.1,4973.1
Exp/Cntr=0.3,0.1

Type RM Length L Ch R = 1,2735,140,140,140
BEGIN DESCRIPTION:
Lacy 027 3053
END DESCRIPTION:
XS GIS Cut Line= 3
      2748380.98      6876867.81      2748126.10      6876847.81
      2747854.42      6876856.85
#Sta/Elev= 30
  4743.9  453.36  4758.9  453.28  4779.0  451.80  4789.0  451.35  4809.1  450.56
  4829.1  450.14  4839.2  450.09  4869.3  448.66  4889.3  448.05  4909.4  446.85
  4919.4  447.18  4929.5  447.09  4969.6  444.50  4995.1  443.74  4995.4  443.24
  4998.9  443.24  4999.1  443.74  5009.7  444.02  5019.7  444.08  5029.7  443.92
  5049.7  444.66  5079.7  444.97  5099.7  445.88  5119.7  447.14  5139.7  447.20
  5149.8  447.44  5169.8  448.49  5199.8  448.99  5239.8  450.59  5271.4  450.96
#Mann=3,-1,0
  4743.9    0.05       0  4995.1    0.04       0  4999.1    0.05       0
Bank Sta=4995.1,4999.1
Exp/Cntr=0.3,0.1

Type RM Length L Ch R = 1,2595,151,151,151
BEGIN DESCRIPTION:
Lacy 027 3055
END DESCRIPTION:
XS GIS Cut Line= 3
      2748387.54      6876715.56      2748125.07      6876707.51
      2747870.08      6876732.43
#Sta/Elev= 30
  4738.2  449.82  4741.5  449.82  4759.8  448.93  4769.8  448.64  4779.8  448.18
  4789.8  447.45  4829.8  446.19  4869.8  445.77  4879.8  445.36  4909.8  445.58
  4939.8  444.34  4959.8  442.87  4969.9  442.35  5002.8  442.32  5007.9  442.14
  5008.2  441.64  5011.7  441.64  5011.9  442.14  5020.0  442.27  5030.0  442.99
  5050.1  443.57  5070.2  444.53  5091.7  444.68  5120.4  445.56  5160.6  446.34
  5170.7  446.64  5180.7  447.26  5188.3  447.51  5231.0  448.33  5257.0  449.22
#Mann=3,-1,0
  4738.2    0.05       0  5007.9    0.04       0  5011.9    0.05       0
Bank Sta=5007.9,5011.9
Exp/Cntr=0.3,0.1

Type RM Length L Ch R = 1,2444,161,161,161
BEGIN DESCRIPTION:
Lacy 027 3054
END DESCRIPTION:
XS GIS Cut Line= 3
      2748419.93      6876588.19      2748124.30      6876556.83
      2747860.55      6876562.57
#Sta/Elev= 30
  4704.5  448.19  4748.7  447.34  4758.7  446.71  4788.9  445.68  4839.2  444.98
  4889.5  443.06  4909.6  443.27  4914.7  442.95  4919.7  443.03  4939.7  441.43
  4949.8  440.90  4959.9  440.86  4969.9  440.50  4980.0  438.60  4988.0  438.55
  4988.3  438.05  4991.8  438.05  4992.0  438.55  4998.4  439.17  5020.1  439.47
  5030.1  441.27  5050.1  442.19  5070.1  442.33  5100.1  443.08  5140.1  443.62
  5170.1  445.14  5190.1  445.15  5240.1  446.78  5260.1  446.74  5265.6  447.07
#Mann=3,-1,0
  4704.5    0.05       0  4988.0    0.04       0  4992.0    0.05       0
Bank Sta=4988,4992
Exp/Cntr=0.3,0.1

Type RM Length L Ch R = 1,2283,228,228,228
BEGIN DESCRIPTION:
Lacy 027 3052
END DESCRIPTION:
XS GIS Cut Line= 3
      2748400.58      6876418.01      2748161.62      6876408.79
      2747869.40      6876420.70
#Sta/Elev= 30
  4766.9  445.32  4781.5  445.30  4791.5  445.05  4801.5  444.35  4841.5  442.82
  4851.5  442.70  4861.6  442.20  4881.6  442.50  4921.6  441.50  4931.6  441.16
  4941.6  440.58  4951.6  440.74  4961.6  440.58  4981.6  438.66  5006.0  438.63
  5011.7  436.65  5019.7  435.95  5019.9  435.45  5023.4  435.45  5023.7  435.95
  5041.7  438.96  5091.7  440.63  5101.7  441.18  5131.8  441.51  5171.8  442.81
  5184.9  442.65  5191.8  442.79  5231.8  443.89  5281.9  444.87  5298.5  445.62
#Mann=3,-1,0
  4766.9    0.05       0  5019.7    0.04       0  5023.7    0.05       0
Bank Sta=5019.7,5023.7
Exp/Cntr=0.3,0.1

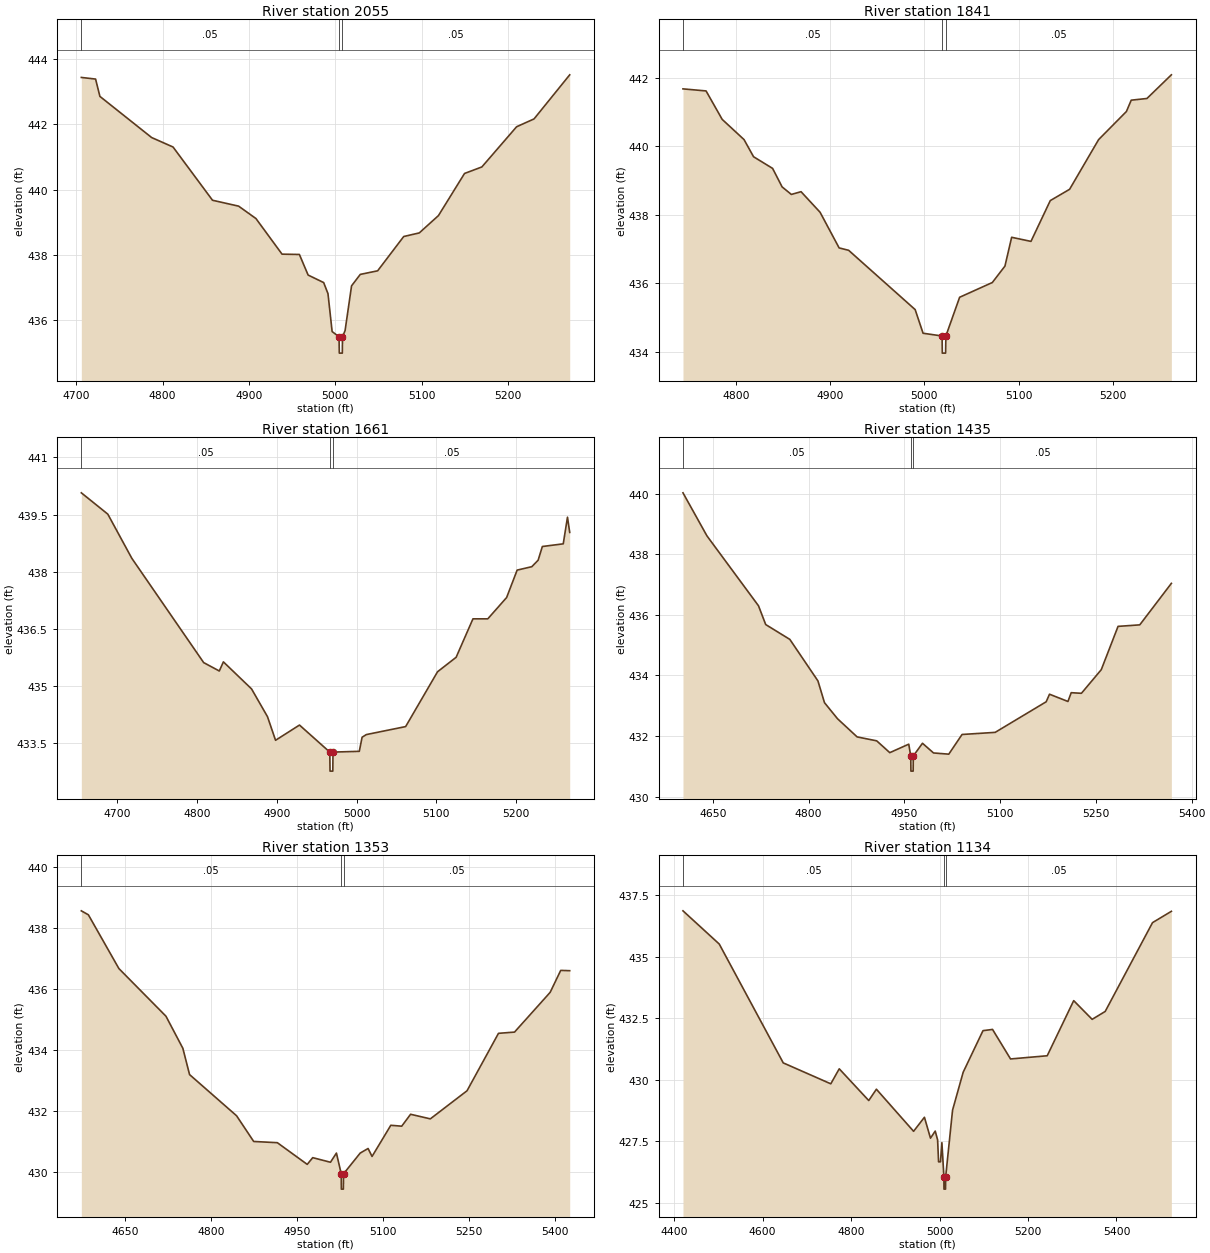
Type RM Length L Ch R = 1,2055,214,214,214
BEGIN DESCRIPTION:
Lacy 027 3051
END DESCRIPTION:
XS GIS Cut Line= 3
      2748416.91      6876227.90      2748125.68      6876194.91
      2747854.91      6876224.76
#Sta/Elev= 30
  4706.0  443.44  4722.5  443.39  4727.5  442.86  4787.4  441.60  4812.2  441.31
  4857.9  439.68  4888.1  439.50  4908.2  439.12  4938.4  438.03  4958.5  438.02
  4968.6  437.39  4986.6  437.16  4991.6  436.82  4996.4  435.66  5004.4  435.50
  5004.7  435.00  5008.2  435.00  5008.4  435.50  5011.4  435.69  5018.9  437.06
  5029.0  437.41  5049.1  437.52  5079.3  438.57  5097.3  438.68  5119.5  439.21
  5149.7  440.50  5169.8  440.70  5210.0  441.93  5230.2  442.17  5271.5  443.52
#Mann=3,-1,0
  4706.0    0.05       0  5004.4    0.04       0  5008.4    0.05       0
Bank Sta=5004.4,5008.4
Exp/Cntr=0.3,0.1

Type RM Length L Ch R = 1,1841,180,180,180
BEGIN DESCRIPTION:
Lacy 027 3050
END DESCRIPTION:
XS GIS Cut Line= 3
      2748380.26      6876041.71      2748124.31      6876007.84
      2747870.72      6876065.76
#Sta/Elev= 30
  4743.8  441.67  4768.3  441.61  4785.4  440.78  4808.6  440.19  4818.7  439.69
  4838.9  439.35  4849.0  438.81  4858.8  438.59  4869.1  438.67  4889.3  438.07
  4909.5  437.03  4919.6  436.96  4990.2  435.23  4998.6  434.54  5018.8  434.46
  5019.0  433.96  5022.5  433.96  5022.8  434.46  5037.4  435.59  5072.1  436.02
  5085.5  436.50  5092.6  437.34  5113.1  437.22  5133.6  438.41  5154.1  438.74
  5184.9  440.19  5214.4  441.01  5219.5  441.34  5236.2  441.39  5262.1  442.08
#Mann=3,-1,0
  4743.8    0.05       0  5018.8    0.04       0  5022.8    0.05       0
Bank Sta=5018.8,5022.8
Exp/Cntr=0.3,0.1

Type RM Length L Ch R = 1,1661,226,226,226
BEGIN DESCRIPTION:
Lacy 027 3049
END DESCRIPTION:
XS GIS Cut Line= 3
      2748419.21      6875827.91      2748071.03      6875843.77
      2747821.01      6875927.80
#Sta/Elev= 30
  4655.0  440.07  4688.2  439.51  4718.3  438.35  4808.4  435.61  4828.0  435.39
  4833.1  435.63  4868.4  434.92  4888.4  434.19  4898.5  433.57  4928.5  433.97
  4966.5  433.26  4966.8  432.76  4970.3  432.76  4970.5  433.26  5003.5  433.28
  5007.0  433.65  5012.3  433.72  5061.6  433.93  5101.6  435.37  5124.9  435.75
  5146.0  436.76  5164.6  436.76  5188.2  437.32  5201.4  438.04  5219.8  438.13
  5227.7  438.30  5233.0  438.66  5259.2  438.73  5264.5  439.43  5267.3  439.03
#Mann=3,-1,0
  4655.0    0.05       0  4966.5    0.04       0  4970.5    0.05       0
Bank Sta=4966.5,4970.5
Exp/Cntr=0.3,0.1

Type RM Length L Ch R = 1,1435,82,82,82
BEGIN DESCRIPTION:
Lacy 027 3048
END DESCRIPTION:
XS GIS Cut Line= 3
      2748462.61      6875731.98      2748077.21      6875648.23
      2747720.33      6875748.53
#Sta/Elev= 30
  4603.1  440.03  4640.6  438.61  4721.4  436.30  4732.7  435.68  4770.5  435.19
  4814.5  433.82  4824.8  433.10  4845.2  432.57  4875.9  431.97  4906.6  431.84
  4927.1  431.45  4956.8  431.73  4959.9  431.34  4960.2  430.84  4963.7  430.84
  4963.9  431.34  4978.3  431.76  4995.6  431.44  5019.5  431.40  5040.3  432.05
  5092.2  432.12  5172.1  433.13  5177.3  433.38  5206.2  433.14  5211.3  433.43
  5227.3  433.41  5258.4  434.19  5284.7  435.62  5318.7  435.67  5368.2  437.04
#Mann=3,-1,0
  4603.1    0.05       0  4959.9    0.04       0  4963.9    0.05       0
Bank Sta=4959.9,4963.9
Exp/Cntr=0.3,0.1

Type RM Length L Ch R = 1,1353,219,219,219
BEGIN DESCRIPTION:
Lacy 027 3059
END DESCRIPTION:
XS GIS Cut Line= 3
      2748487.92      6875671.19      2748073.83      6875566.98
      2747663.04      6875679.40
#Sta/Elev= 30
  4573.0  438.56  4585.3  438.43  4638.6  436.67  4720.8  435.11  4750.3  434.06
  4762.0  433.20  4844.2  431.85  4874.0  431.01  4915.3  430.97  4967.5  430.26
  4977.1  430.48  5008.1  430.33  5018.5  430.63  5026.9  429.95  5027.1  429.45
  5030.6  429.45  5030.9  429.95  5060.0  430.63  5073.8  430.78  5080.7  430.52
  5113.5  431.54  5132.5  431.51  5148.0  431.90  5182.5  431.75  5246.6  432.67
  5301.5  434.55  5329.5  434.59  5391.7  435.89  5410.2  436.61  5425.9  436.60
#Mann=3,-1,0
  4573.0    0.05       0  5026.9    0.04       0  5030.9    0.05       0
Bank Sta=5026.9,5030.9
Exp/Cntr=0.3,0.1

Type RM Length L Ch R = 1,1134,272,272,272
BEGIN DESCRIPTION:
Lacy 027 3057
END DESCRIPTION:
XS GIS Cut Line= 3
      2748567.04      6875576.00      2748026.92      6875364.38
      2747541.55      6875562.10
#Sta/Elev= 30
  4419.9  436.86  4501.9  435.51  4646.6  430.68  4754.1  429.83  4773.2  430.44
  4839.9  429.15  4857.2  429.61  4941.3  427.90  4965.8  428.47  4979.5  427.62
  4990.2  427.91  4995.6  427.55  4997.8  426.66  5002.1  426.66  5005.3  427.44
  5009.8  426.05  5010.0  425.55  5013.5  425.55  5013.8  426.05  5029.4  428.76
  5053.4  430.30  5098.2  431.99  5119.8  432.04  5160.5  430.84  5243.4  430.97
  5303.3  433.21  5345.0  432.45  5374.5  432.77  5481.5  436.38  5524.1  436.84
#Mann=3,-1,0
  4419.9    0.05       0  5009.8    0.04       0  5013.8    0.05       0
Bank Sta=5009.8,5013.8
Exp/Cntr=0.3,0.1

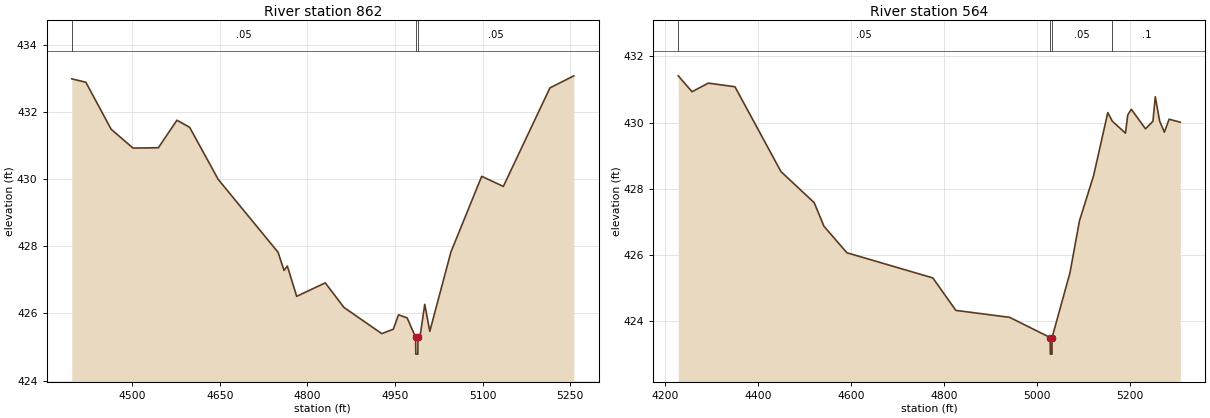
Type RM Length L Ch R = 1,862,298,298,298
BEGIN DESCRIPTION:
Lacy 027 3058
END DESCRIPTION:
XS GIS Cut Line= 3
      2748503.96      6875386.76      2748024.05      6875116.26
      2747748.29      6875256.57
#Sta/Elev= 30
  4396.1  432.98  4420.2  432.88  4463.6  431.48  4501.1  430.92  4544.5  430.93
  4576.3  431.75  4598.0  431.54  4647.0  429.99  4749.6  427.82  4759.8  427.28
  4765.5  427.41  4781.5  426.51  4830.5  426.91  4862.4  426.18  4927.3  425.40
  4947.0  425.53  4956.0  425.96  4970.7  425.87  4985.3  425.29  4985.6  424.79
  4989.1  424.79  4989.3  425.29  4992.9  425.32  5000.9  426.27  5009.6  425.47
  5045.8  427.83  5098.5  430.08  5135.6  429.78  5215.4  432.71  5256.4  433.07
#Mann=3,-1,0
  4396.1    0.05       0  4985.3    0.04       0  4989.3    0.05       0
Bank Sta=4985.3,4989.3
Exp/Cntr=0.3,0.1

Type RM Length L Ch R = 1,564,0,0,0
BEGIN DESCRIPTION:
Lacy 027 3056
END DESCRIPTION:
XS GIS Cut Line= 3
      2748483.70      6875315.04      2747936.92      6874861.69
      2747572.25      6874926.13
#Sta/Elev= 30
  4227.9  431.41  4257.6  430.93  4292.7  431.19  4350.0  431.08  4449.0  428.52
  4520.6  427.58  4541.5  426.87  4590.9  426.07  4775.9  425.31  4825.4  424.33
  4941.2  424.12  5028.5  423.51  5028.8  423.01  5032.3  423.01  5032.5  423.51
  5071.1  425.47  5091.4  427.03  5121.9  428.40  5152.4  430.30  5162.2  430.04
  5190.4  429.68  5195.4  430.23  5203.1  430.40  5233.6  429.81  5249.6  430.04
  5254.6  430.78  5264.1  430.04  5274.2  429.71  5284.4  430.10  5308.5  430.01
#Mann=4,-1,0
  4227.9    0.05       0  5028.5    0.04       0  5032.5    0.05       0
  5162.2     0.1       0
Bank Sta=5028.5,5032.5
Exp/Cntr=0.3,0.1

Chan Stop Cuts=-1