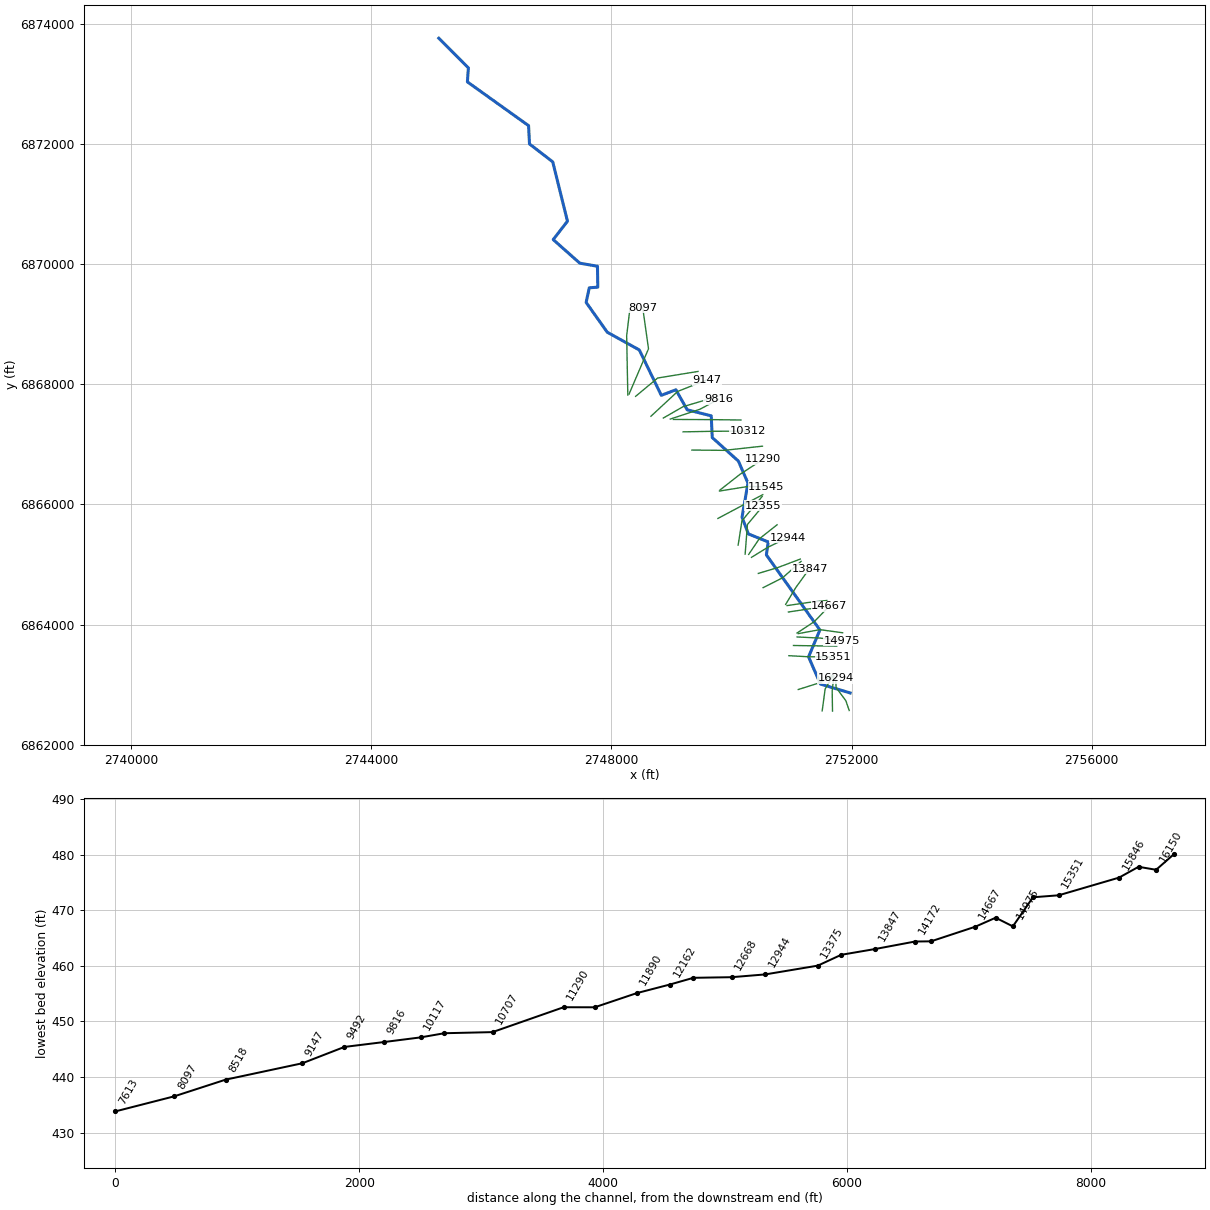
--- Lacy 028.prj (project) ---

Proj Title=Lacy 028 Base Level Engineering
Current Plan=p01
Default Exp/Contr=0.3,0.1
English Units
Geom File=g01
Flow File=f01
Plan File=p01
BEGIN DESCRIPTION:
Lacy 028
END DESCRIPTION:

--- Lacy 028.p01 (plan) ---

Plan Title=Multiple Run
Short Identifier=Multiple
Geom File=g01
Flow File=f01
Subcritical Flow
K Sum by GR= 0
Std Step Tol= 0.01
Critical Tol= 0.01
Num of Std Step Trials= 20
Max Error Tol= 0.3
Flow Tol Ratio= 0.001
Split Flow NTrial= 30
Split Flow Tol= 0.02
Split Flow Ratio= 0.02
Log Output Level= 0
Friction Slope Method= 1
Unsteady Friction Slope Method= 2
Unsteady Bridges Friction Slope Method= 1
Parabolic Critical Depth
Global Vel Dist=  1 , 1 , 1
Global Log Level= 0
CheckData=True
Encroach Param= -1, 0, 0, 0
BEGIN DESCRIPTION:
Multiple Run
END DESCRIPTION:

--- Lacy 028.f01 (steady flow) ---

Flow Title=Multiple
Number of Profiles=7
Profile Names=10-year,25-year,50-year,1pct_min,100-year,1pct_plu,500-year
River Rch & RM= Lacy 028,Reach-1,16294
     387     506     600     354     707    1410     982
River Rch & RM= Lacy 028,Reach-1,10707
     553     736     885     528    1054    2103    1499
River Rch & RM= Lacy 028,Reach-1,7613
    1015    1396    1712    1041    2078    4146    3069
River Rch & RM= Lacy 028,Reach-1,2704
    1076    1480    1816    1105    2204    4398    3255
Boundary for River Rch & Prof#=Lacy 028,Reach-1,1
Up Type=0
Dn Type=3
Dn Slope=0.005
Boundary for River Rch & Prof#=Lacy 028,Reach-1,2
Up Type=0
Dn Type=3
Dn Slope=0.005
Boundary for River Rch & Prof#=Lacy 028,Reach-1,3
Up Type=0
Dn Type=3
Dn Slope=0.005
Boundary for River Rch & Prof#=Lacy 028,Reach-1,4
Up Type=0
Dn Type=3
Dn Slope=0.005
Boundary for River Rch & Prof#=Lacy 028,Reach-1,5
Up Type=0
Dn Type=3
Dn Slope=0.005
Boundary for River Rch & Prof#=Lacy 028,Reach-1,6
Up Type=0
Dn Type=3
Dn Slope=0.005
Boundary for River Rch & Prof#=Lacy 028,Reach-1,7
Up Type=0
Dn Type=3
Dn Slope=0.005

--- Lacy 028.g01 (geometry) ---

Geom Title=Existing Conditions

River Reach=Lacy 028,Reach-1
Reach XY= 30
      2751976.00      6862861.00      2751481.76      6863008.64
      2751283.53      6863461.01      2751472.26      6863909.44
      2750581.11      6865158.71      2750612.53      6865374.75
      2750281.83      6865508.16      2750175.60      6865786.00
      2750274.04      6866355.11      2750115.26      6866720.70
      2749679.54      6867112.46      2749662.64      6867474.35
      2749262.58      6867574.52      2749074.35      6867907.89
      2748831.03      6867815.92      2748465.35      6868570.99
      2747931.44      6868866.19      2747579.47      6869362.27
      2747631.59      6869606.21      2747773.95      6869616.45
      2747768.01      6869964.37      2747473.27      6870016.34
      2747030.96      6870408.46      2747268.40      6870714.33
      2747023.34      6871702.52      2746635.99      6872001.05
      2746620.74      6872305.53      2745601.91      6873033.86
      2745618.31      6873267.44      2745126.00      6873761.00

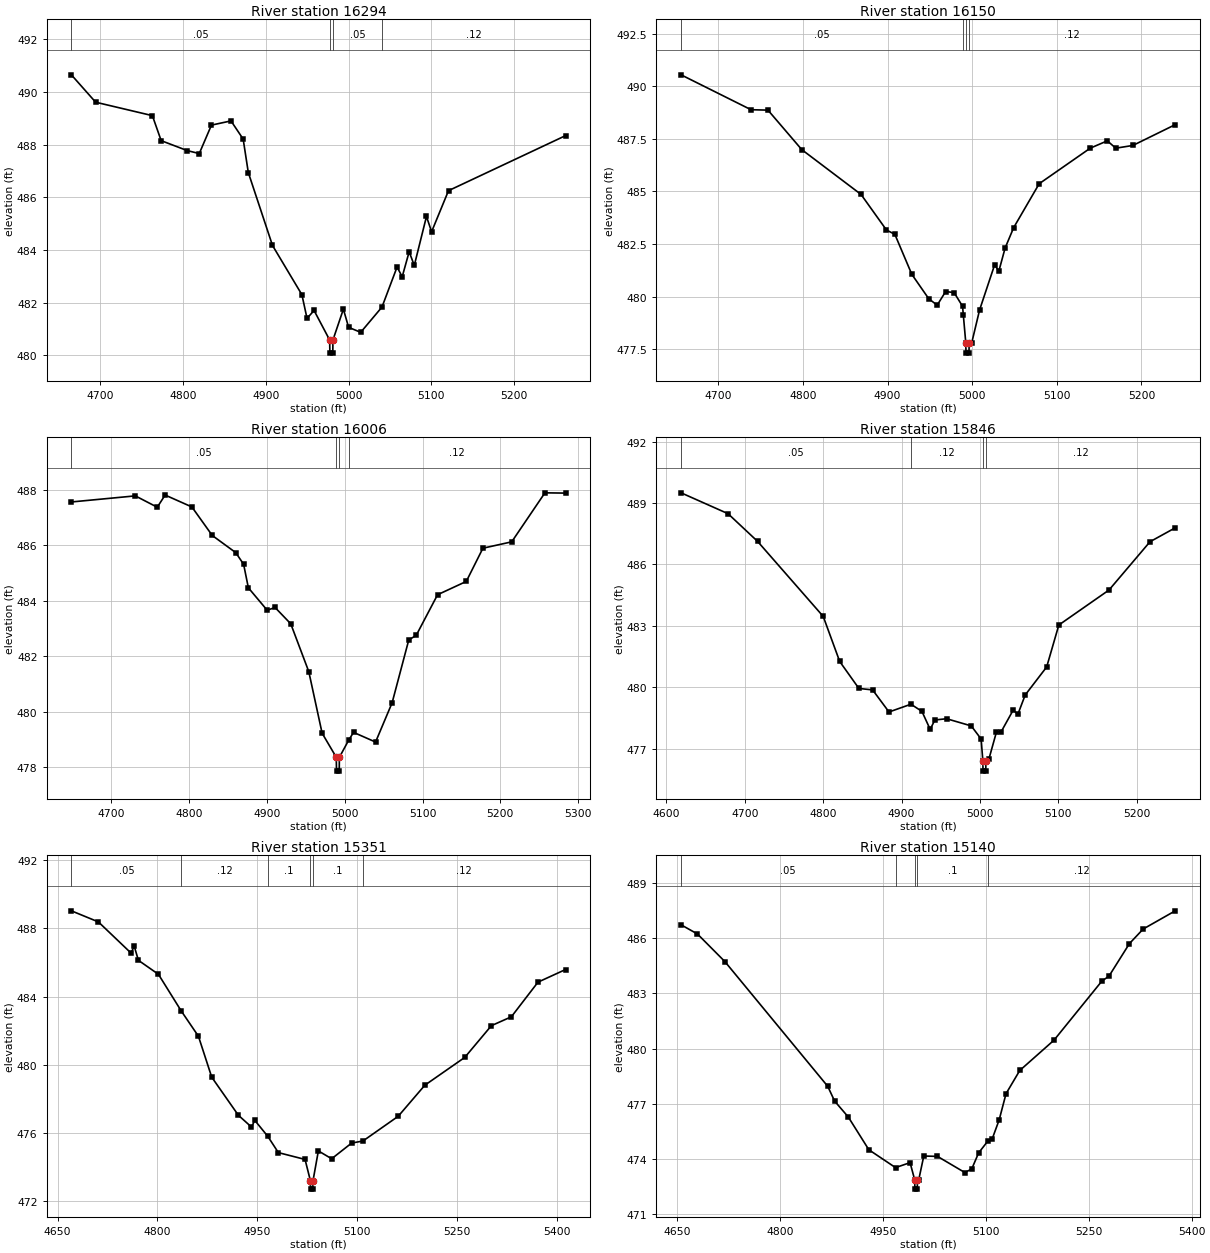
Type RM Length L Ch R = 1,16294,144,144,144
BEGIN DESCRIPTION:
Lacy 028 3033
END DESCRIPTION:
XS GIS Cut Line= 5
      2751960.56      6862568.49      2751904.87      6862730.84
      2751756.89      6862931.18      2751742.08      6862951.60
      2751735.13      6863102.11
#Sta/Elev= 30
  4665.4  490.65  4694.7  489.61  4763.2  489.10  4773.8  488.15  4805.5  487.77
  4819.8  487.66  4834.5  488.74  4858.1  488.90  4872.8  488.21  4879.0  486.94
  4908.2  484.17  4943.7  482.30  4949.9  481.40  4958.4  481.70  4977.2  480.58
  4977.5  480.08  4981.0  480.08  4981.2  480.58  4993.8  481.75  5000.1  481.06
  5014.7  480.87  5040.4  481.83  5058.6  483.35  5064.8  482.98  5073.2  483.93
  5079.4  483.41  5094.1  485.27  5100.3  484.69  5120.7  486.25  5262.0  488.34
#Mann=4,-1,0
  4665.4    0.05       0  4977.2    0.04       0  4981.2    0.05       0
  5040.4    0.12       0
Bank Sta=4977.2,4981.2
Exp/Cntr=0.3,0.1

Type RM Length L Ch R = 1,16150,144,144,144
BEGIN DESCRIPTION:
Lacy 028 3030
END DESCRIPTION:
XS GIS Cut Line= 3
      2751682.40      6862558.34      2751677.13      6862897.64
      2751705.03      6863140.80
#Sta/Elev= 30
  4655.9  490.55  4738.6  488.89  4758.6  488.87  4798.6  486.99  4868.6  484.86
  4898.6  483.17  4908.6  482.96  4928.6  481.06  4948.6  479.90  4958.6  479.59
  4968.6  480.24  4978.6  480.19  4988.6  479.54  4989.5  479.13  4992.4  477.81
  4992.7  477.31  4996.2  477.31  4996.4  477.81  4999.5  477.81  5008.7  479.36
  5026.5  481.51  5031.5  481.21  5038.9  482.31  5049.0  483.28  5079.2  485.37
  5139.5  487.06  5159.7  487.41  5169.7  487.06  5189.9  487.19  5240.0  488.18
#Mann=4,-1,0
  4655.9    0.05       0  4989.5    0.12       0  4992.4    0.07       0
  4996.4    0.12       0
Bank Sta=4992.4,4996.4
Exp/Cntr=0.3,0.1

Type RM Length L Ch R = 1,16006,160,160,160
BEGIN DESCRIPTION:
Lacy 028 3036
END DESCRIPTION:
XS GIS Cut Line= 3
      2751510.38      6862561.57      2751559.88      6862927.71
      2751696.39      6863155.70
#Sta/Elev= 30
  4648.6  487.57  4730.8  487.79  4759.0  487.38  4769.1  487.82  4803.5  487.39
  4829.7  486.36  4859.9  485.74  4870.0  485.32  4876.1  484.47  4900.3  483.66
  4910.4  483.76  4930.6  483.17  4953.8  481.44  4970.9  479.22  4989.1  478.35
  4989.4  477.85  4992.9  477.85  4993.1  478.35  5004.9  478.96  5011.3  479.25
  5039.6  478.90  5060.9  480.32  5082.3  482.59  5091.8  482.75  5119.3  484.22
  5156.2  484.70  5177.6  485.90  5214.6  486.13  5257.3  487.90  5283.8  487.89
#Mann=4,-1,0
  4648.6    0.05       0  4989.1    0.04       0  4993.1    0.05       0
  5004.9    0.12       0
Bank Sta=4989.1,4993.1
Exp/Cntr=0.3,0.1

Type RM Length L Ch R = 1,15846,495,495,495
BEGIN DESCRIPTION:
Lacy 028 3035
END DESCRIPTION:
XS GIS Cut Line= 3
      2751113.08      6862918.21      2751478.04      6863033.54
      2751689.63      6863162.04
#Sta/Elev= 30
  4618.8  489.50  4678.7  488.48  4716.3  487.13  4800.1  483.46  4821.1  481.26
  4845.6  479.94  4863.1  479.87  4884.0  478.79  4912.0  479.17  4926.0  478.82
  4936.5  477.94  4942.5  478.40  4957.5  478.46  4988.9  478.11  5001.5  477.47
  5003.7  476.40  5003.9  475.90  5007.4  475.90  5007.7  476.40  5011.5  476.50
  5021.1  477.82  5027.0  477.82  5042.5  478.89  5048.3  478.67  5057.7  479.62
  5085.1  480.99  5100.6  483.04  5164.6  484.75  5216.9  487.11  5249.1  487.79
#Mann=4,-1,0
  4618.8    0.05       0  4912.0    0.12       0  5003.7    0.07       0
  5007.7    0.12       0
Bank Sta=5003.7,5007.7
Exp/Cntr=0.3,0.1

Type RM Length L Ch R = 1,15351,211,211,211
BEGIN DESCRIPTION:
Lacy 028 3028
END DESCRIPTION:
XS GIS Cut Line= 3
      2750955.43      6863481.13      2751283.23      6863463.08
      2751697.40      6863457.50
#Sta/Elev= 30
  4670.6  489.03  4711.2  488.38  4760.1  486.56  4765.1  486.95  4771.3  486.13
  4801.4  485.31  4835.7  483.16  4861.5  481.68  4881.5  479.28  4921.5  477.05
  4941.2  476.36  4946.2  476.75  4965.8  475.81  4981.6  474.86  5021.7  474.46
  5029.7  473.22  5029.9  472.72  5033.4  472.72  5033.7  473.22  5041.7  474.96
  5061.7  474.50  5091.7  475.42  5108.7  475.54  5161.7  476.99  5201.7  478.81
  5261.7  480.44  5301.7  482.30  5331.7  482.82  5371.7  484.85  5413.1  485.59
#Mann=6,-1,0
  4670.6    0.05       0  4835.7    0.12       0  4965.8     0.1       0
  5029.7    0.07       0  5033.7     0.1       0  5108.7    0.12       0
Bank Sta=5029.7,5033.7
Exp/Cntr=0.3,0.1

Type RM Length L Ch R = 1,15140,165,165,165
BEGIN DESCRIPTION:
Lacy 028 3027
END DESCRIPTION:
XS GIS Cut Line= 3
      2751032.09      6863650.97      2751378.65      6863645.49
      2751752.82      6863640.75
#Sta/Elev= 30
  4655.3  486.73  4679.2  486.23  4719.2  484.73  4869.2  477.95  4879.2  477.15
  4899.2  476.28  4929.2  474.50  4968.1  473.53  4989.3  473.80  4996.1  472.86
  4996.3  472.36  4999.8  472.36  5000.1  472.86  5001.9  472.86  5009.3  474.16
  5029.3  474.14  5069.3  473.26  5079.3  473.46  5089.3  474.33  5103.1  474.99
  5109.3  475.11  5119.3  476.13  5129.3  477.55  5149.3  478.81  5199.3  480.46
  5269.3  483.68  5279.3  483.93  5309.3  485.71  5329.3  486.50  5376.1  487.49
#Mann=5,-1,0
  4655.3    0.05       0  4968.1     0.1       0  4996.1    0.07       0
  5000.1     0.1       0  5103.1    0.12       0
Bank Sta=4996.1,5000.1
Exp/Cntr=0.3,0.1

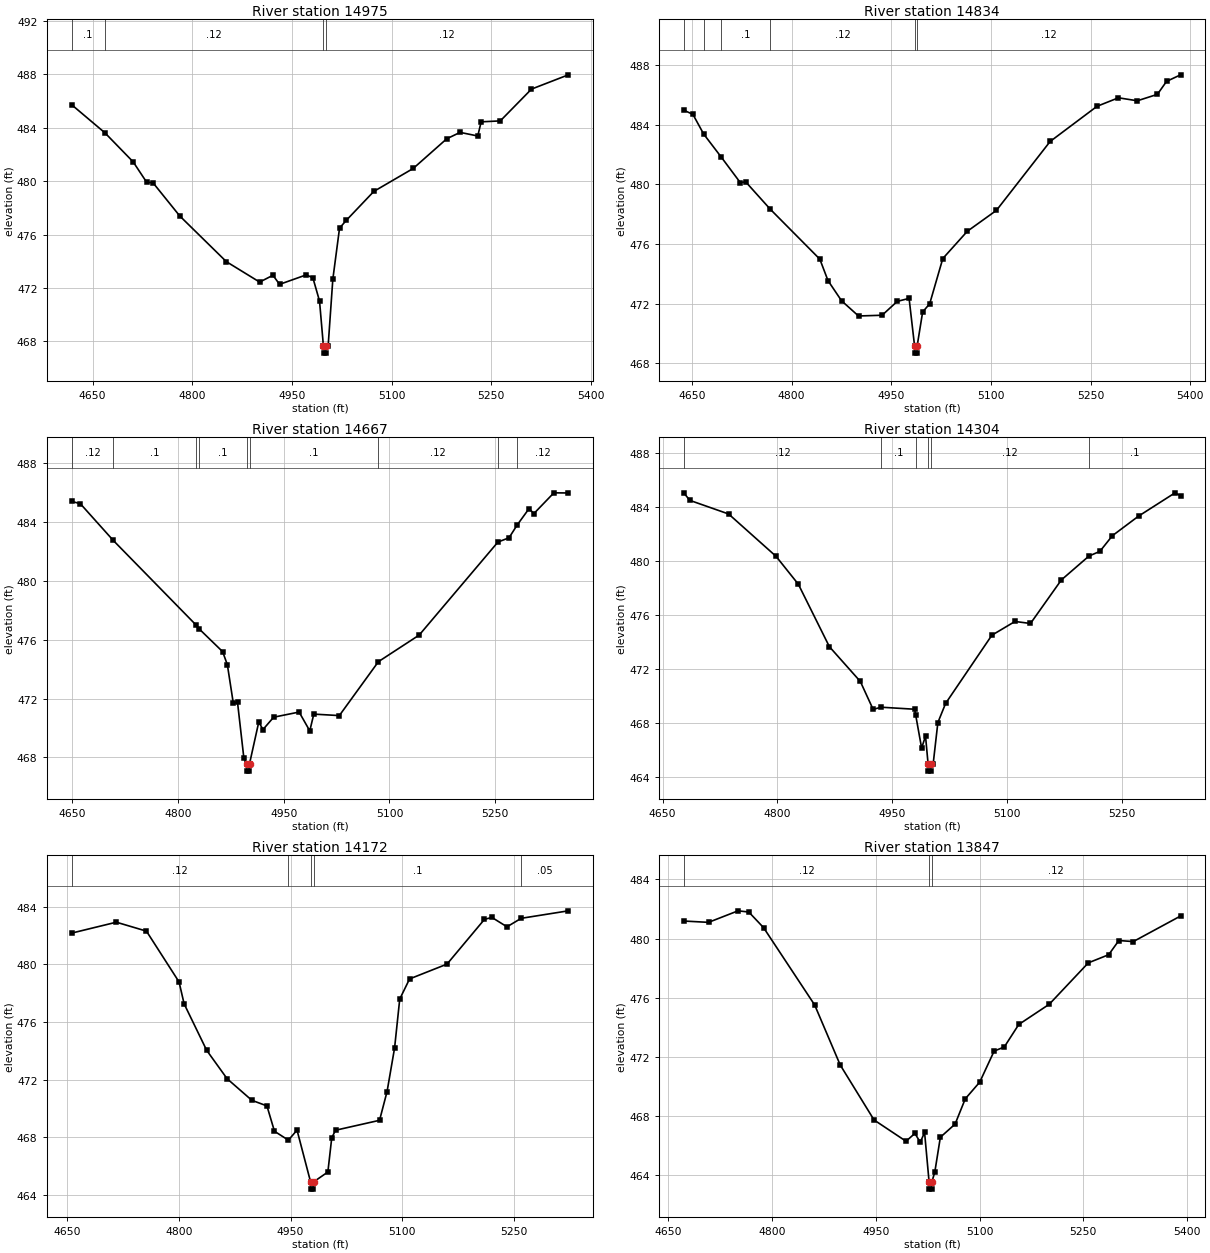
Type RM Length L Ch R = 1,14975,141,141,141
BEGIN DESCRIPTION:
Lacy 028 3026
END DESCRIPTION:
XS GIS Cut Line= 3
      2751093.27      6863792.72      2751476.83      6863774.29
      2751837.63      6863729.32
#Sta/Elev= 30
  4618.4  485.73  4668.6  483.62  4711.2  481.44  4731.3  479.93  4741.3  479.86
  4781.3  477.39  4851.4  473.97  4901.5  472.44  4921.5  472.95  4931.5  472.27
  4971.6  472.98  4981.6  472.76  4991.6  471.02  4997.5  467.62  4997.7  467.12
  5001.2  467.12  5001.5  467.62  5004.5  467.62  5011.6  472.65  5021.7  476.48
  5031.8  477.06  5073.3  479.23  5132.6  480.95  5183.0  483.17  5203.1  483.65
  5229.7  483.38  5234.8  484.44  5263.6  484.51  5310.5  486.89  5366.0  487.96
#Mann=4,-1,0
  4618.4     0.1       0  4668.6    0.12       0  4997.5    0.07       0
  5001.5    0.12       0
Bank Sta=4997.5,5001.5
Exp/Cntr=0.3,0.1

Type RM Length L Ch R = 1,14834,167,167,167
BEGIN DESCRIPTION:
Lacy 028 3025
END DESCRIPTION:
XS GIS Cut Line= 3
      2751112.41      6863848.60      2751471.98      6863914.45
      2751850.55      6863862.98
#Sta/Elev= 30
  4637.8  484.97  4651.6  484.69  4667.8  483.37  4694.5  481.81  4722.8  480.12
  4731.1  480.16  4768.0  478.33  4842.6  474.98  4854.9  473.54  4875.3  472.19
  4900.8  471.17  4936.3  471.22  4959.1  472.15  4976.9  472.35  4985.1  469.18
  4985.4  468.68  4988.9  468.68  4989.1  469.18  4997.3  471.44  5007.9  471.99
  5027.6  475.02  5064.5  476.85  5108.3  478.25  5189.1  482.87  5259.7  485.23
  5291.9  485.80  5320.3  485.60  5350.5  486.03  5364.3  486.90  5385.4  487.34
#Mann=6,-1,0
  4637.8     0.1       0  4667.8    0.12       0  4694.5     0.1       0
  4768.0    0.12       0  4985.1    0.07       0  4989.1    0.12       0
Bank Sta=4985.1,4989.1
Exp/Cntr=0.3,0.1

Type RM Length L Ch R = 1,14667,363,363,363
BEGIN DESCRIPTION:
Lacy 028 3024
END DESCRIPTION:
XS GIS Cut Line= 3
      2751091.59      6863858.47      2751380.64      6864049.05
      2751628.90      6864306.96
#Sta/Elev= 30
  4649.3  485.42  4661.8  485.26  4708.5  482.76  4825.3  477.03  4829.8  476.76
  4863.5  475.19  4870.2  474.30  4878.6  471.69  4884.6  471.74  4893.6  467.94
  4897.6  467.56  4897.9  467.06  4901.4  467.06  4901.6  467.56  4914.7  470.40
  4920.7  469.89  4935.8  470.73  4971.9  471.08  4987.0  469.80  4992.7  470.94
  5028.9  470.84  5084.3  474.51  5142.1  476.32  5253.7  482.65  5269.4  482.94
  5281.1  483.82  5297.7  484.92  5304.7  484.59  5333.0  486.00  5353.5  485.99
#Mann=9,-1,0
  4649.3    0.12       0  4708.5     0.1       0  4825.3    0.12       0
  4829.8     0.1       0  4897.6    0.07       0  4901.6     0.1       0
  5084.3    0.12       0  5253.7     0.1       0  5281.1    0.12       0
Bank Sta=4897.6,4901.6
Exp/Cntr=0.3,0.1

Type RM Length L Ch R = 1,14304,132,132,132
BEGIN DESCRIPTION:
Lacy 028 3023
END DESCRIPTION:
XS GIS Cut Line= 3
      2750948.12      6864208.32      2751269.90      6864257.66
      2751590.51      6864296.58
#Sta/Elev= 30
  4677.7  485.07  4685.7  484.51  4736.3  483.50  4798.2  480.36  4827.3  478.29
  4867.8  473.66  4908.2  471.08  4924.9  469.01  4935.4  469.17  4979.1  469.02
  4980.4  468.61  4988.2  466.14  4993.3  467.03  4996.7  464.93  4997.0  464.43
  5000.5  464.43  5000.7  464.93  5003.2  464.93  5009.4  468.03  5019.5  469.45
  5079.9  474.51  5110.1  475.53  5130.3  475.38  5170.6  478.61  5206.6  480.38
  5220.9  480.73  5237.2  481.89  5271.3  483.34  5319.0  485.07  5326.2  484.85
#Mann=6,-1,0
  4677.7    0.12       0  4935.4     0.1       0  4980.4    0.12       0
  4996.7    0.07       0  5000.7    0.12       0  5206.6     0.1       0
Bank Sta=4996.7,5000.7
Exp/Cntr=0.3,0.1

Type RM Length L Ch R = 1,14172,325,325,325
BEGIN DESCRIPTION:
Lacy 028 3022
END DESCRIPTION:
XS GIS Cut Line= 3
      2750926.45      6864315.16      2751262.90      6864364.86
      2751587.96      6864400.43
#Sta/Elev= 30
  4655.9  482.17  4716.1  482.93  4756.5  482.31  4800.3  478.78  4807.1  477.26
  4837.4  474.03  4864.8  472.06  4898.0  470.56  4918.3  470.17  4928.4  468.41
  4947.1  467.79  4958.7  468.49  4976.9  464.89  4977.2  464.39  4980.7  464.39
  4980.9  464.89  5000.1  465.58  5005.3  467.95  5010.4  468.48  5069.5  469.17
  5079.6  471.17  5089.7  474.20  5096.6  477.59  5109.8  478.99  5160.1  480.02
  5210.4  483.13  5220.4  483.26  5240.6  482.61  5259.7  483.20  5323.0  483.72
#Mann=5,-1,0
  4655.9    0.12       0  4947.1     0.1       0  4976.9    0.07       0
  4980.9     0.1       0  5259.7    0.05       0
Bank Sta=4976.9,4980.9
Exp/Cntr=0.3,0.1

Type RM Length L Ch R = 1,13847,280,280,280
BEGIN DESCRIPTION:
Lacy 028 3021
END DESCRIPTION:
XS GIS Cut Line= 3
      2750902.50      6864335.40      2751071.85      6864616.55
      2751300.57      6864932.06
#Sta/Elev= 30
  4672.6  481.19  4708.4  481.10  4751.1  481.88  4766.6  481.80  4788.0  480.74
  4861.8  475.51  4898.7  471.45  4947.6  467.73  4993.8  466.29  5006.6  466.82
  5014.4  466.22  5020.6  466.89  5027.1  463.55  5027.4  463.05  5030.9  463.05
  5031.1  463.55  5035.3  464.18  5043.4  466.56  5064.7  467.45  5079.4  469.16
  5100.3  470.29  5121.1  472.39  5135.8  472.67  5156.7  474.19  5200.8  475.56
  5257.2  478.36  5286.6  478.91  5301.3  479.87  5322.2  479.80  5390.5  481.53
#Mann=3,-1,0
  4672.6    0.12       0  5027.1    0.07       0  5031.1    0.12       0
Bank Sta=5027.1,5031.1
Exp/Cntr=0.3,0.1

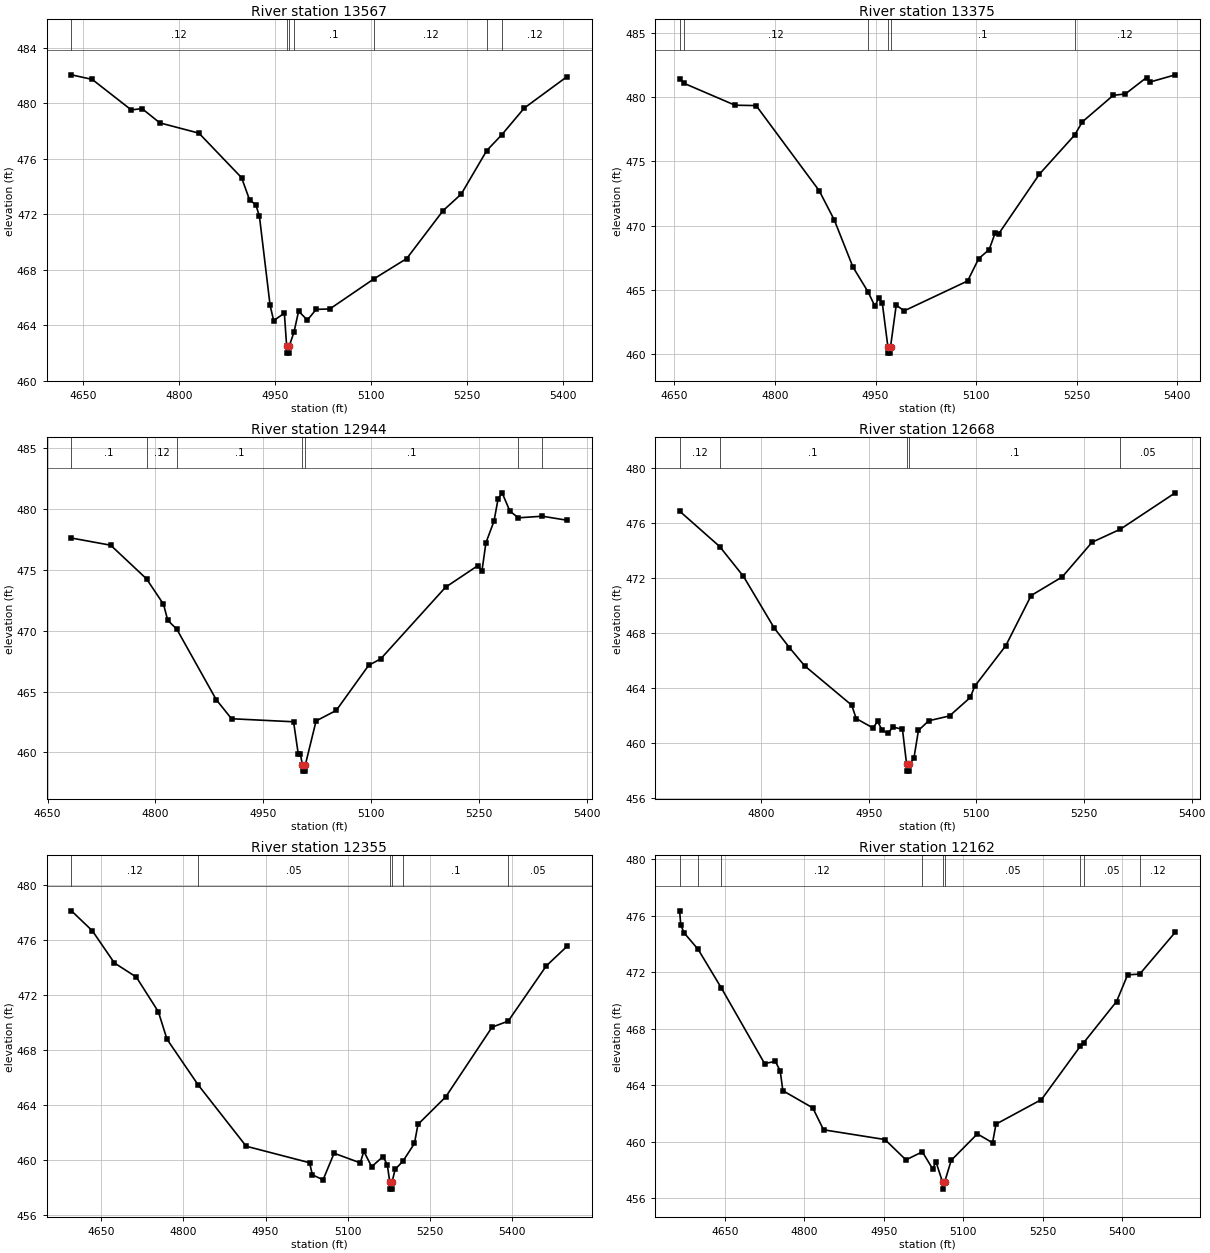
Type RM Length L Ch R = 1,13567,192,192,192
BEGIN DESCRIPTION:
Lacy 028 3020
END DESCRIPTION:
XS GIS Cut Line= 3
      2750527.24      6864613.77      2750850.69      6864777.46
      2751159.69      6865051.62
#Sta/Elev= 30
  4631.4  482.04  4663.9  481.71  4725.1  479.51  4741.8  479.61  4769.7  478.58
  4830.9  477.84  4897.7  474.63  4910.2  473.03  4920.0  472.68  4925.6  471.85
  4942.3  465.43  4947.9  464.34  4964.6  464.88  4968.2  462.50  4968.4  462.00
  4971.9  462.00  4972.2  462.50  4979.6  463.50  4986.9  465.02  5000.6  464.38
  5014.4  465.15  5035.7  465.18  5105.5  467.37  5156.1  468.81  5213.0  472.26
  5241.4  473.45  5281.4  476.59  5305.0  477.73  5340.1  479.65  5407.0  481.91
#Mann=7,-1,0
  4631.4    0.12       0  4968.2    0.07       0  4972.2    0.12       0
  4979.6     0.1       0  5105.5    0.12       0  5281.4     0.1       0
  5305.0    0.12       0
Bank Sta=4968.2,4972.2
Exp/Cntr=0.3,0.1

Type RM Length L Ch R = 1,13375,431,431,431
BEGIN DESCRIPTION:
Lacy 028 3019
END DESCRIPTION:
XS GIS Cut Line= 3
      2750446.67      6864850.82      2750773.15      6864948.77
      2751145.53      6865089.37
#Sta/Elev= 30
  4657.8  481.47  4664.3  481.10  4740.4  479.39  4771.9  479.36  4865.9  472.72
  4888.3  470.45  4916.2  466.77  4938.6  464.84  4949.2  463.69  4954.4  464.37
  4959.9  463.99  4968.3  460.55  4968.6  460.05  4972.1  460.05  4972.3  460.55
  4980.7  463.79  4992.7  463.35  5087.2  465.68  5103.7  467.42  5119.3  468.13
  5128.5  469.46  5133.8  469.38  5194.2  474.01  5246.9  477.07  5258.2  478.09
  5304.3  480.16  5322.4  480.27  5354.0  481.55  5359.3  481.20  5396.7  481.76
#Mann=6,-1,0
  4657.8     0.1       0  4664.3    0.12       0  4938.6     0.1       0
  4968.3    0.07       0  4972.3     0.1       0  5246.9    0.12       0
Bank Sta=4968.3,4972.3
Exp/Cntr=0.3,0.1

Type RM Length L Ch R = 1,12944,276,276,276
BEGIN DESCRIPTION:
Lacy 028 3018
END DESCRIPTION:
XS GIS Cut Line= 3
      2750333.04      6865118.23      2750602.11      6865284.07
      2750937.28      6865448.04
#Sta/Elev= 30
  4683.2  477.60  4737.8  477.01  4787.6  474.25  4811.2  472.17  4817.1  470.85
  4829.8  470.11  4884.5  464.34  4905.8  462.77  4992.1  462.52  4998.6  459.88
  5001.5  459.88  5004.4  458.97  5004.7  458.47  5008.2  458.47  5008.4  458.97
  5023.4  462.59  5051.4  463.45  5096.5  467.15  5113.4  467.69  5203.4  473.56
  5248.5  475.34  5254.0  474.86  5259.6  477.21  5270.8  478.98  5276.5  480.81
  5282.1  481.31  5293.0  479.80  5304.8  479.26  5338.0  479.39  5372.4  479.06
#Mann=7,-1,0
  4683.2     0.1       0  4787.6    0.12       0  4829.8     0.1       0
  5004.4    0.07       0  5008.4     0.1       0  5304.8    0.12       0
  5338.0     0.1       0
Bank Sta=5004.4,5008.4
Exp/Cntr=0.3,0.1

Type RM Length L Ch R = 1,12668,313,313,313
BEGIN DESCRIPTION:
Lacy 028 3017
END DESCRIPTION:
XS GIS Cut Line= 3
      2750286.37      6865167.34      2750460.73      6865424.39
      2750758.94      6865660.22
#Sta/Elev= 30
  4686.3  476.86  4742.1  474.29  4775.3  472.12  4818.4  468.35  4839.4  466.94
  4860.4  465.63  4926.2  462.76  4932.4  461.79  4956.1  461.10  4962.2  461.60
  4968.6  460.93  4977.1  460.71  4983.2  461.18  4996.9  461.01  5002.7  458.47
  5003.0  457.97  5006.5  457.97  5006.7  458.47  5012.8  458.89  5019.2  460.93
  5033.6  461.63  5062.5  461.98  5091.4  463.32  5097.7  464.14  5141.0  467.09
  5176.3  470.73  5219.6  472.08  5261.2  474.60  5300.4  475.54  5377.1  478.19
#Mann=5,-1,0
  4686.3    0.12       0  4742.1     0.1       0  5002.7    0.07       0
  5006.7     0.1       0  5300.4    0.05       0
Bank Sta=5002.7,5006.7
Exp/Cntr=0.3,0.1

Type RM Length L Ch R = 1,12355,193,193,193
BEGIN DESCRIPTION:
Lacy 028 3016
END DESCRIPTION:
XS GIS Cut Line= 3
      2750227.52      6865172.82      2750265.54      6865665.60
      2750529.54      6865980.27
#Sta/Elev= 30
  4595.5  478.10  4633.8  476.64  4673.9  474.31  4714.0  473.28  4754.2  470.76
  4770.0  468.76  4826.7  465.45  4914.6  460.98  5030.4  459.78  5035.4  458.90
  5055.0  458.54  5075.1  460.47  5122.9  459.77  5129.4  460.61  5143.7  459.49
  5164.5  460.23  5172.3  459.63  5176.8  458.36  5177.1  457.86  5180.6  457.86
  5180.8  458.36  5186.6  459.30  5200.8  459.89  5221.8  461.18  5228.3  462.57
  5279.0  464.57  5363.6  469.64  5393.1  470.08  5462.5  474.09  5500.5  475.52
#Mann=6,-1,0
  4595.5    0.12       0  4826.7    0.05       0  5176.8    0.03       0
  5180.8    0.05       0  5200.8     0.1       0  5393.1    0.05       0
Bank Sta=5176.8,5180.8
Exp/Cntr=0.3,0.1

Type RM Length L Ch R = 1,12162,272,272,272
BEGIN DESCRIPTION:
Lacy 028 3014
END DESCRIPTION:
XS GIS Cut Line= 3
      2750110.87      6865322.44      2750174.50      6865727.48
      2750511.07      6866132.08
#Sta/Elev= 30
  4564.3  476.35  4566.5  475.33  4573.0  474.78  4599.3  473.62  4643.3  470.88
  4724.8  465.54  4745.1  465.69  4754.3  465.03  4759.3  463.62  4815.9  462.40
  4836.2  460.85  4952.2  460.16  4991.9  458.72  5022.9  459.29  5042.2  458.09
  5048.7  458.57  5061.0  457.15  5061.3  456.65  5065.0  457.15  5077.4  458.69
  5126.8  460.56  5155.5  459.93  5162.0  461.25  5247.9  462.99  5321.4  466.77
  5327.4  467.00  5389.8  469.93  5410.7  471.82  5433.5  471.87  5500.6  474.83
#Mann=9,-1,0
  4564.3     0.1       0  4599.3    0.05       0  4643.3    0.12       0
  5022.9    0.05       0  5061.0    0.07       0  5065.0    0.05       0
  5321.4    0.12       0  5327.4    0.05       0  5433.5    0.12       0
Bank Sta=5061,5065
Exp/Cntr=0.3,0.1

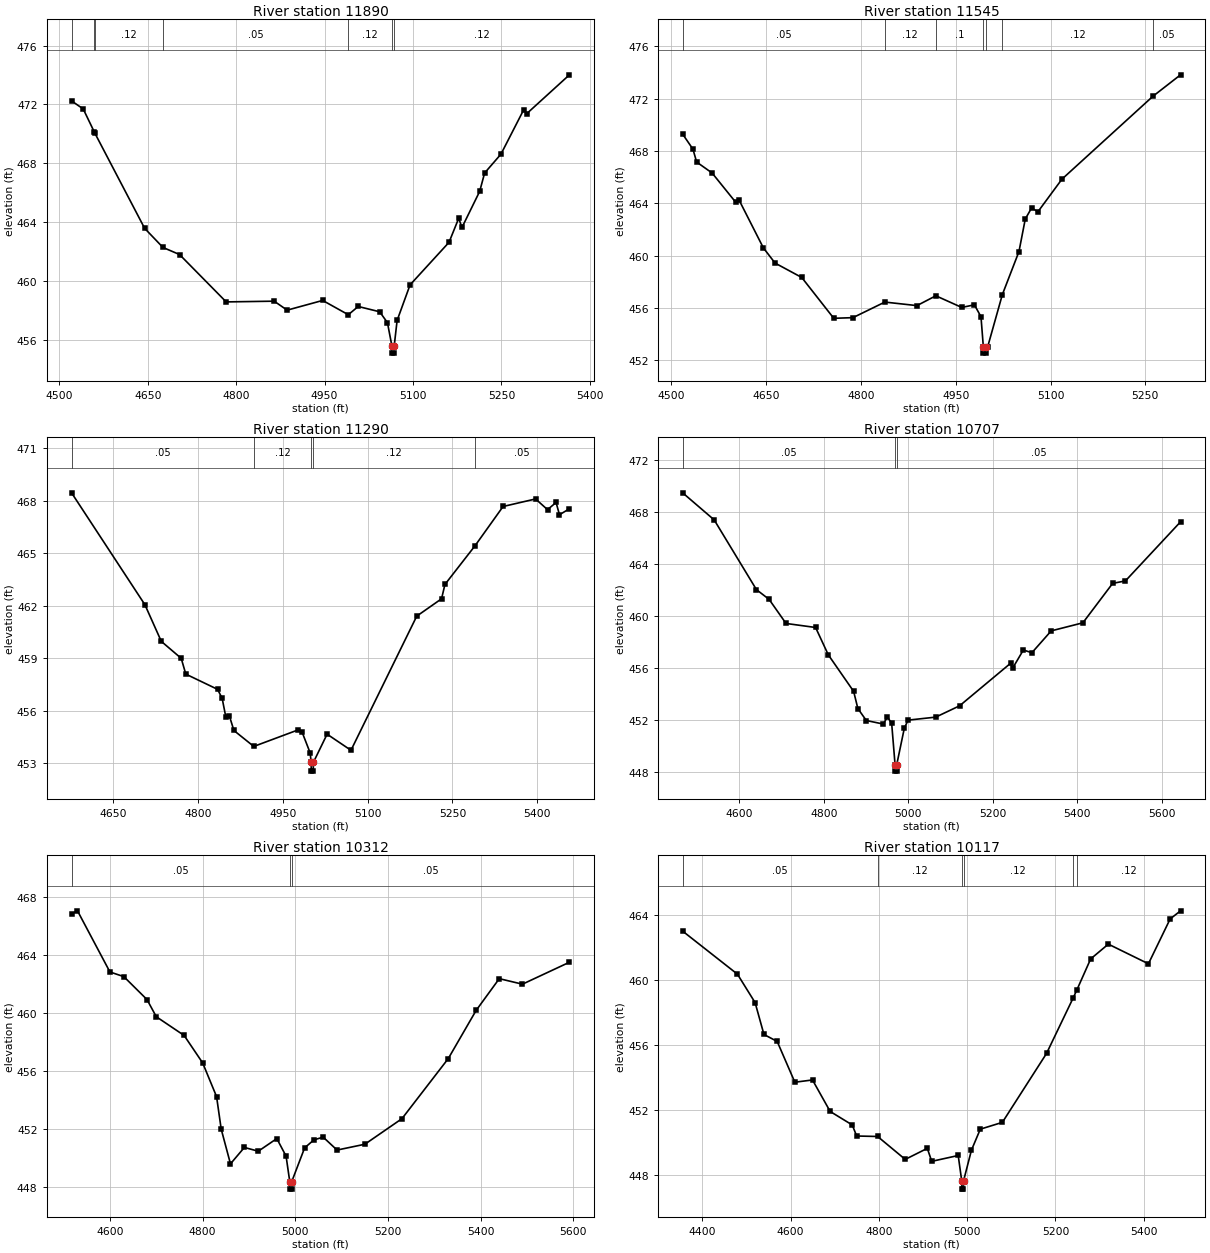
Type RM Length L Ch R = 1,11890,345,345,345
BEGIN DESCRIPTION:
Lacy 028 3015
END DESCRIPTION:
XS GIS Cut Line= 3
      2749774.26      6865766.31      2750197.49      6865991.27
      2750520.73      6866161.86
#Sta/Elev= 30
  4520.6  472.24  4540.4  471.69  4559.5  470.10  4560.1  470.05  4644.6  463.58
  4675.7  462.28  4703.8  461.80  4783.0  458.58  4864.4  458.63  4886.4  458.02
  4946.7  458.68  4990.2  457.71  5007.0  458.27  5043.4  457.91  5056.6  457.17
  5064.1  455.60  5064.3  455.10  5067.8  455.10  5068.1  455.60  5073.0  457.32
  5095.0  459.74  5161.1  462.63  5177.5  464.26  5183.1  463.64  5213.1  466.09
  5221.5  467.34  5249.2  468.62  5287.6  471.62  5293.2  471.38  5365.4  474.01
#Mann=7,-1,0
  4520.6    0.12       0  4559.5     0.1       0  4560.1    0.12       0
  4675.7    0.05       0  4990.2    0.12       0  5064.1    0.07       0
  5068.1    0.12       0
Bank Sta=5064.1,5068.1
Exp/Cntr=0.3,0.1

Type RM Length L Ch R = 1,11545,255,255,255
BEGIN DESCRIPTION:
Lacy 028 3013
END DESCRIPTION:
XS GIS Cut Line= 3
      2749799.94      6866222.39      2750272.29      6866297.87
      2750581.61      6866293.23
#Sta/Elev= 30
  4518.0  469.28  4534.3  468.13  4540.1  467.15  4564.6  466.31  4602.2  464.06
  4607.2  464.25  4645.7  460.59  4664.2  459.43  4706.4  458.33  4757.1  455.21
  4787.4  455.26  4837.9  456.45  4888.7  456.18  4918.6  456.93  4959.6  456.04
  4979.6  456.24  4990.0  455.33  4993.7  453.05  4993.9  452.55  4997.4  452.55
  4997.7  453.05  5000.7  453.05  5023.8  457.02  5050.1  460.31  5060.1  462.80
  5070.1  463.64  5080.1  463.35  5118.1  465.84  5262.0  472.17  5305.7  473.81
#Mann=7,-1,0
  4518.0    0.05       0  4837.9    0.12       0  4918.6     0.1       0
  4993.7    0.07       0  4997.7     0.1       0  5023.8    0.12       0
  5262.0    0.05       0
Bank Sta=4993.7,4997.7
Exp/Cntr=0.3,0.1

Type RM Length L Ch R = 1,11290,583,583,583
BEGIN DESCRIPTION:
Lacy 028 3001
END DESCRIPTION:
XS GIS Cut Line= 3
      2749806.72      6866237.88      2750141.66      6866500.53
      2750522.11      6866748.01
#Sta/Elev= 30
  4577.1  468.45  4706.7  462.06  4735.6  459.97  4770.8  459.00  4778.9  458.10
  4835.0  457.23  4843.1  456.72  4849.5  455.67  4855.8  455.72  4863.9  454.88
  4899.0  453.97  4977.8  454.92  4984.2  454.80  4998.7  453.59  5000.3  453.06
  5000.6  452.56  5004.1  452.56  5004.3  453.06  5028.5  454.67  5070.7  453.75
  5186.9  461.41  5230.7  462.40  5236.7  463.22  5289.9  465.43  5339.4  467.67
  5396.8  468.10  5417.9  467.49  5433.0  467.90  5439.0  467.20  5456.6  467.54
#Mann=5,-1,0
  4577.1    0.05       0  4899.0    0.12       0  5000.3    0.07       0
  5004.3    0.12       0  5289.9    0.05       0
Bank Sta=5000.3,5004.3
Exp/Cntr=0.3,0.1

Type RM Length L Ch R = 1,10707,395,395,395
BEGIN DESCRIPTION:
Lacy 028 2979
END DESCRIPTION:
XS GIS Cut Line= 3
      2749341.40      6866904.65      2749878.82      6866899.43
      2750515.64      6866969.35
#Sta/Elev= 30
  4466.1  469.47  4540.7  467.39  4640.7  462.03  4670.7  461.28  4710.7  459.43
  4780.7  459.12  4810.7  457.02  4870.7  454.21  4880.7  452.89  4900.7  451.97
  4940.7  451.70  4950.7  452.24  4960.7  451.75  4968.7  448.58  4969.0  448.08
  4972.5  448.08  4972.7  448.58  4990.7  451.39  4999.6  452.00  5064.9  452.23
  5121.4  453.10  5242.1  456.37  5247.1  456.00  5272.3  457.39  5292.5  457.18
  5338.2  458.86  5413.2  459.48  5483.6  462.51  5513.8  462.70  5644.2  467.24
#Mann=3,-1,0
  4466.1    0.05       0  4968.7    0.04       0  4972.7    0.05       0
Bank Sta=4968.7,4972.7
Exp/Cntr=0.3,0.1

Type RM Length L Ch R = 1,10312,195,195,195
BEGIN DESCRIPTION:
Lacy 028 2978
END DESCRIPTION:
XS GIS Cut Line= 3
      2749193.19      6867207.60      2749677.40      6867216.68
      2750267.39      6867220.53
#Sta/Elev= 30
  4517.4  466.83  4530.2  467.04  4600.2  462.83  4630.2  462.51  4680.2  460.93
  4700.2  459.75  4760.3  458.46  4800.3  456.57  4830.3  454.25  4840.3  452.01
  4860.3  449.62  4890.3  450.75  4920.3  450.49  4960.3  451.36  4980.3  450.15
  4988.3  448.38  4988.5  447.88  4992.0  447.88  4992.3  448.38  5020.3  450.72
  5040.3  451.27  5060.3  451.46  5090.3  450.57  5150.3  450.97  5230.3  452.73
  5330.3  456.87  5390.3  460.18  5440.3  462.37  5490.3  461.99  5591.7  463.50
#Mann=3,-1,0
  4517.4    0.05       0  4988.3    0.04       0  4992.3    0.05       0
Bank Sta=4988.3,4992.3
Exp/Cntr=0.3,0.1

Type RM Length L Ch R = 1,10117,301,301,301
BEGIN DESCRIPTION:
Lacy 028 2977
END DESCRIPTION:
XS GIS Cut Line= 3
      2749031.94      6867414.13      2749677.10      6867411.50
      2750159.49      6867404.96
#Sta/Elev= 30
  4355.7  463.01  4479.8  460.36  4519.8  458.61  4539.8  456.65  4569.8  456.22
  4609.8  453.71  4649.8  453.85  4689.8  451.91  4739.8  451.08  4749.8  450.40
  4797.3  450.37  4859.8  448.96  4909.8  449.64  4919.8  448.84  4979.8  449.20
  4987.8  447.63  4988.0  447.13  4991.5  447.13  4991.8  447.63  5009.8  449.53
  5029.8  450.82  5079.8  451.24  5179.8  455.48  5240.0  458.89  5248.2  459.37
  5279.8  461.30  5319.8  462.21  5410.6  461.00  5459.8  463.76  5483.3  464.26
#Mann=6,-1,0
  4355.7    0.05       0  4797.3    0.12       0  4987.8    0.07       0
  4991.8    0.12       0  5240.0    0.05       0  5248.2    0.12       0
Bank Sta=4987.8,4991.8
Exp/Cntr=0.3,0.1

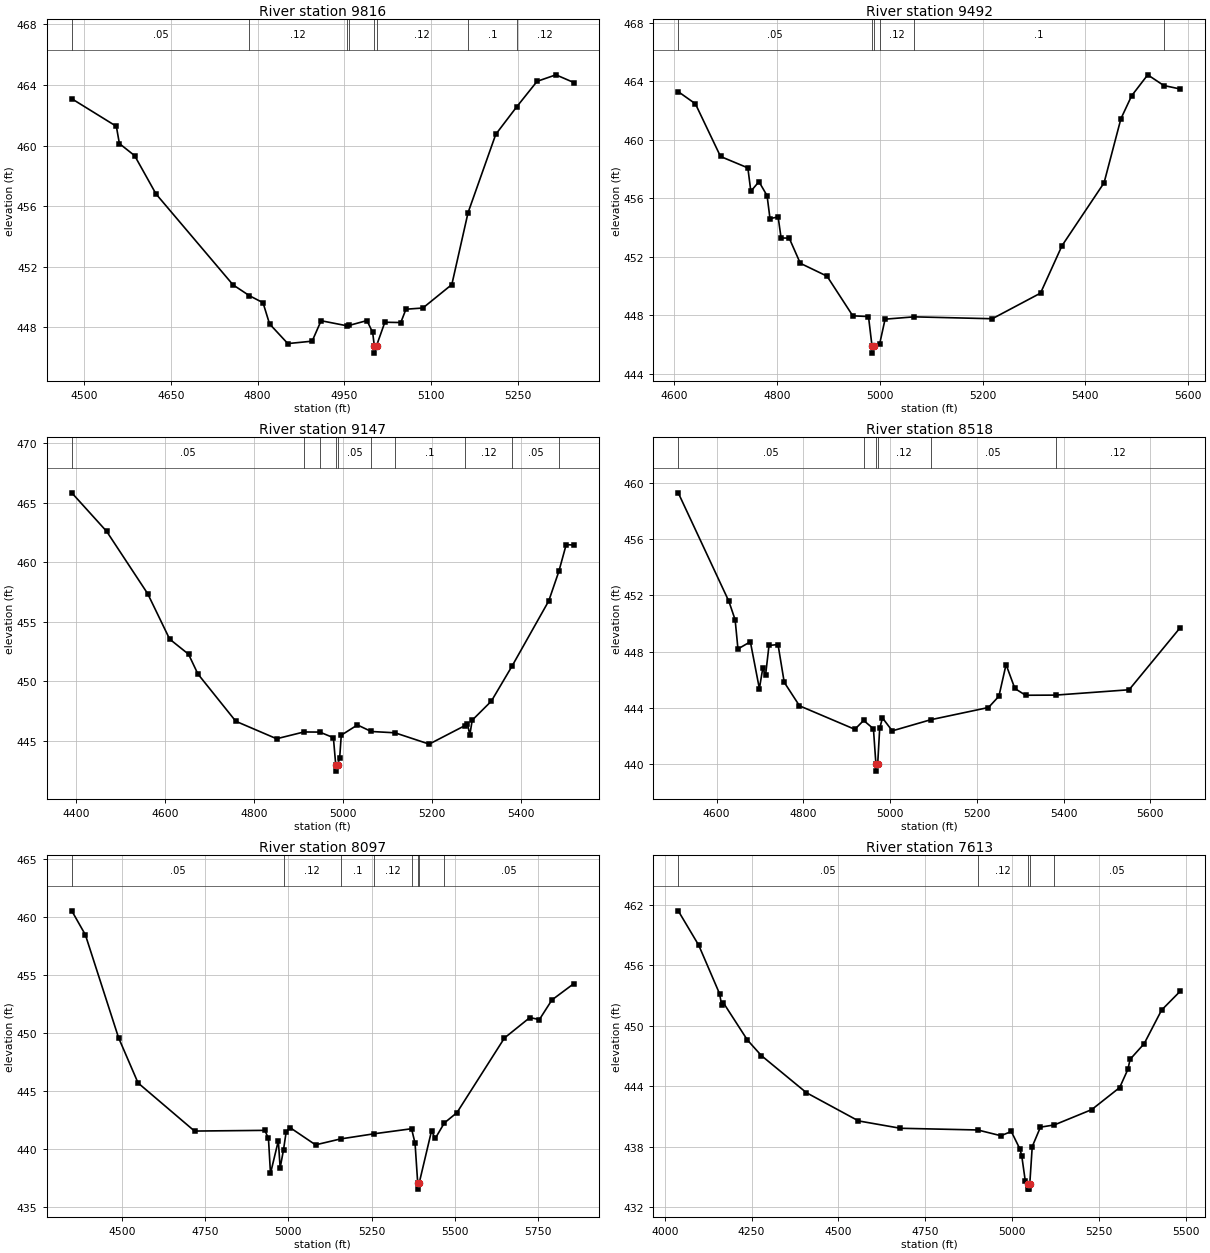
Type RM Length L Ch R = 1,9816,324,324,324
BEGIN DESCRIPTION:
Lacy 028 2980
END DESCRIPTION:
XS GIS Cut Line= 3
      2748981.09      6867420.70      2749472.59      6867583.21
      2749782.26      6867748.53
#Sta/Elev= 30
  4478.6  463.09  4555.7  461.27  4561.0  460.13  4587.4  459.33  4624.4  456.80
  4757.6  450.80  4786.1  450.08  4809.5  449.62  4820.8  448.22  4852.4  446.92
  4894.5  447.08  4910.0  448.43  4954.1  448.10  4958.5  448.12  4989.3  448.44
  4999.2  447.66  5002.0  446.79  5002.2  446.29  5006.0  446.79  5020.3  448.33
  5047.9  448.31  5056.8  449.19  5086.1  449.27  5136.2  450.82  5164.2  455.56
  5212.2  460.74  5248.3  462.55  5283.7  464.24  5316.3  464.67  5347.3  464.16
#Mann=8,-1,0
  4478.6    0.05       0  4786.1    0.12       0  4954.1     0.1       0
  4958.5    0.12       0  5002.0    0.07       0  5006.0    0.12       0
  5164.2     0.1       0  5248.3    0.12       0
Bank Sta=5002,5006
Exp/Cntr=0.3,0.1

Type RM Length L Ch R = 1,9492,345,345,345
BEGIN DESCRIPTION:
Lacy 028 3504
END DESCRIPTION:
XS GIS Cut Line= 3
      2748864.82      6867437.78      2749194.53      6867627.05
      2749766.79      6867797.25
#Sta/Elev= 30
  4607.5  463.28  4640.9  462.45  4689.8  458.85  4743.0  458.07  4748.8  456.47
  4764.6  457.13  4780.4  456.17  4786.1  454.60  4801.9  454.72  4807.7  453.28
  4823.5  453.27  4845.1  451.55  4897.1  450.67  4947.2  447.96  4977.8  447.91
  4984.6  445.91  4984.9  445.41  4988.6  445.91  4999.4  446.02  5010.1  447.73
  5066.3  447.89  5218.7  447.76  5312.6  449.51  5354.4  452.75  5436.3  457.05
  5469.1  461.43  5490.0  463.00  5521.3  464.43  5552.5  463.70  5584.7  463.46
#Mann=6,-1,0
  4607.5    0.05       0  4984.6    0.07       0  4988.6    0.05       0
  4999.4    0.12       0  5066.3     0.1       0  5552.5    0.12       0
Bank Sta=4984.6,4988.6
Exp/Cntr=0.3,0.1

Type RM Length L Ch R = 1,9147,629,629,629
BEGIN DESCRIPTION:
Lacy 028 2983
END DESCRIPTION:
XS GIS Cut Line= 3
      2748658.51      6867467.48      2749104.32      6867880.86
      2749588.47      6868071.76
#Sta/Elev= 30
  4390.0  465.85  4468.4  462.61  4560.7  457.37  4610.0  453.56  4652.5  452.29
  4673.5  450.63  4758.6  446.66  4850.4  445.19  4911.8  445.76  4947.4  445.75
  4978.0  445.28  4983.3  442.97  4983.6  442.47  4987.3  442.97  4992.1  443.59
  4995.7  445.49  5032.0  446.35  5063.0  445.80  5116.4  445.69  5193.3  444.74
  5273.9  446.30  5279.2  446.46  5284.6  445.51  5290.0  446.75  5333.0  448.35
  5379.3  451.28  5462.0  456.77  5484.7  459.25  5501.2  461.50  5518.4  461.46
#Mann=10,-1,0
  4390.0    0.05       0  4911.8    0.12       0  4947.4    0.05       0
  4983.3    0.05       0  4987.3    0.05       0  5063.0    0.12       0
  5116.4     0.1       0  5273.9    0.12       0  5379.3    0.05       0
  5484.7    0.12       0
Bank Sta=4983.3,4987.3
Exp/Cntr=0.3,0.1

Type RM Length L Ch R = 1,8518,421,421,421
BEGIN DESCRIPTION:
Lacy 028 2982
END DESCRIPTION:
XS GIS Cut Line= 3
      2748403.90      6867799.04      2748770.87      6868104.02
      2749442.55      6868213.50
#Sta/Elev= 30
  4511.6  459.29  4628.4  451.58  4642.8  450.27  4649.3  448.20  4677.9  448.71
  4698.7  445.38  4706.5  446.82  4713.0  446.34  4720.9  448.45  4741.7  448.51
  4756.0  445.83  4791.2  444.16  4918.8  442.49  4939.1  443.12  4961.7  442.53
  4967.4  440.02  4967.7  439.52  4971.5  440.02  4976.1  442.55  4982.5  443.30
  5005.1  442.38  5093.7  443.17  5227.0  444.04  5251.0  444.84  5267.5  447.09
  5287.8  445.39  5312.5  444.91  5381.6  444.92  5551.2  445.30  5669.3  449.72
#Mann=6,-1,0
  4511.6    0.05       0  4939.1    0.12       0  4967.4    0.07       0
  4971.5    0.12       0  5093.7    0.05       0  5381.6    0.12       0
Bank Sta=4967.4,4971.5
Exp/Cntr=0.3,0.1

Type RM Length L Ch R = 1,8097,484,484,484
BEGIN DESCRIPTION:
Lacy 028 2975
END DESCRIPTION:
XS GIS Cut Line= 3
      2748295.08      6867837.97      2748618.06      6868590.00
      2748522.15      6869273.45
#Sta/Elev= 30
  4349.2  460.53  4390.1  458.46  4489.7  449.59  4548.4  445.68  4718.0  441.53
  4929.3  441.59  4940.2  440.89  4946.3  437.87  4969.9  440.70  4975.3  438.35
  4985.4  439.91  4993.4  441.46  5005.5  441.82  5081.7  440.34  5156.8  440.85
  5258.8  441.30  5370.2  441.73  5380.7  440.47  5388.7  437.02  5389.1  436.52
  5392.9  437.02  5430.2  441.55  5441.3  440.89  5468.7  442.23  5506.6  443.12
  5649.3  449.56  5725.6  451.32  5754.3  451.15  5791.9  452.84  5857.8  454.25
#Mann=8,-1,0
  4349.2    0.05       0  4985.4    0.12       0  5156.8     0.1       0
  5258.8    0.12       0  5370.2     0.1       0  5388.7    0.07       0
  5392.9     0.1       0  5468.7    0.05       0
Bank Sta=5388.7,5392.9
Exp/Cntr=0.3,0.1

Type RM Length L Ch R = 1,7613,93,93,93
BEGIN DESCRIPTION:
Lacy 028 2971
END DESCRIPTION:
XS GIS Cut Line= 3
      2748273.45      6867821.87      2748254.16      6868805.95
      2748309.18      6869264.49
#Sta/Elev= 30
  4038.7  461.42  4097.8  458.00  4157.9  453.18  4163.4  452.12  4168.4  452.31
  4237.9  448.60  4277.9  447.06  4407.9  443.37  4557.9  440.57  4678.5  439.84
  4901.5  439.67  4968.0  439.10  4998.0  439.52  5023.0  437.77  5028.1  437.10
  5038.1  434.65  5045.1  434.30  5046.1  433.80  5050.2  433.80  5051.2  434.30
  5058.3  438.02  5081.9  439.95  5121.8  440.17  5229.5  441.69  5310.1  443.88
  5333.7  445.68  5340.3  446.69  5380.6  448.23  5430.9  451.57  5484.8  453.45
#Mann=5,-1,0
  4038.7    0.05       0  4901.5    0.12       0  5045.1    0.07       0
  5051.2    0.12       0  5121.8    0.05       0
Bank Sta=5045.1,5051.2
Exp/Cntr=0.3,0.1