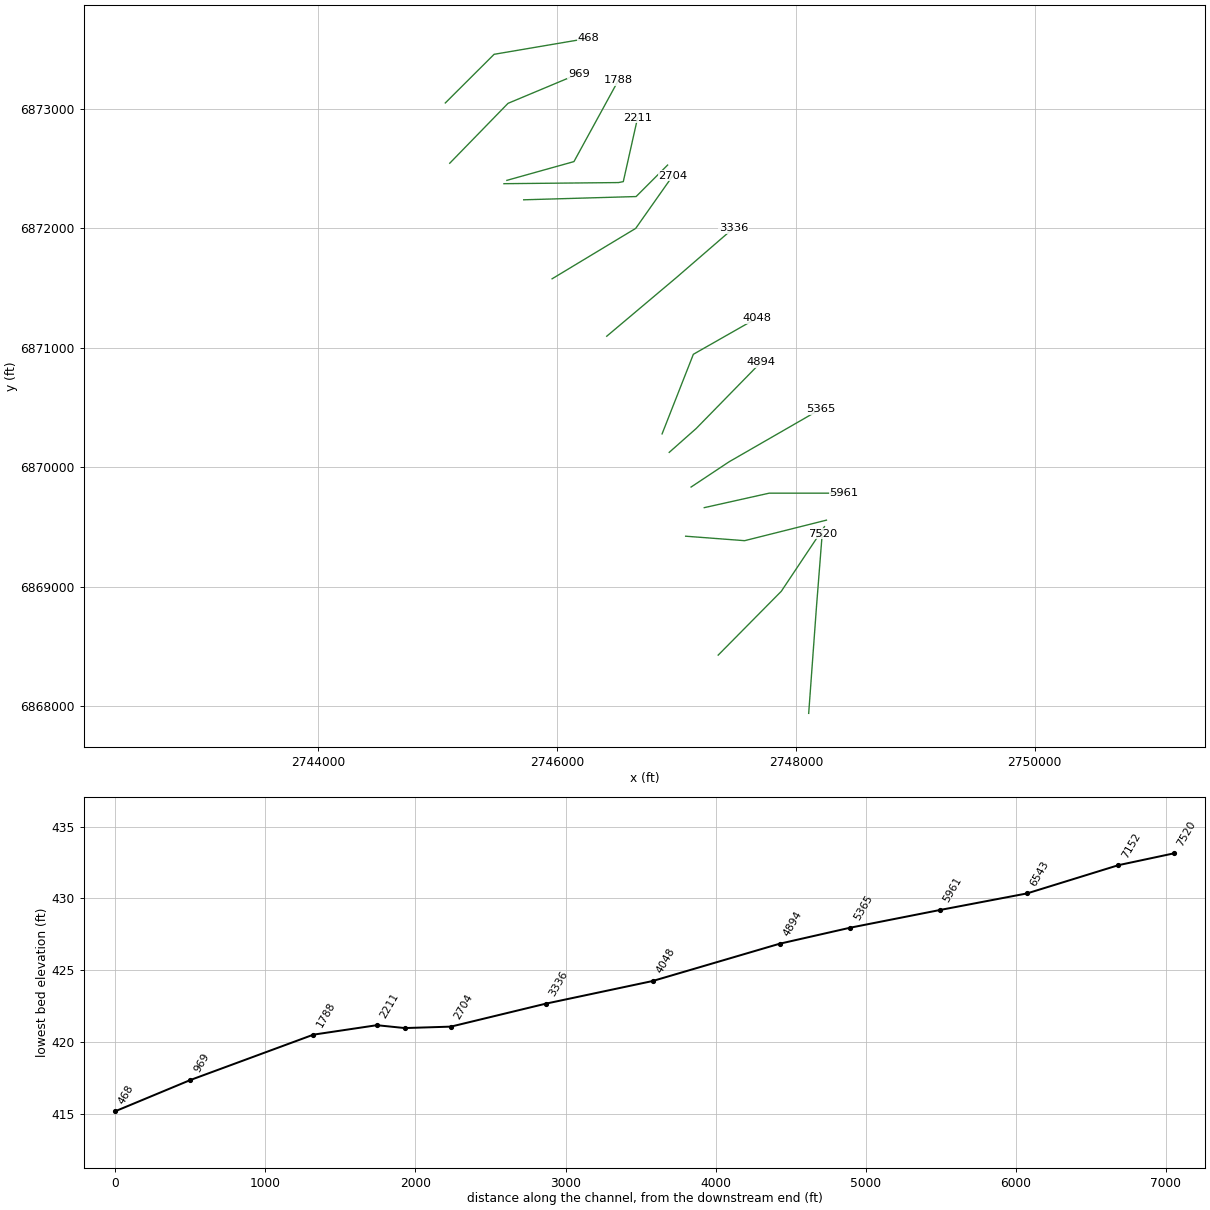
HEC-RAS study Lacy 028.prj: Lacy 028 Base Level Engineering

--- Lacy 028.g01 (geometry) --- (continued)

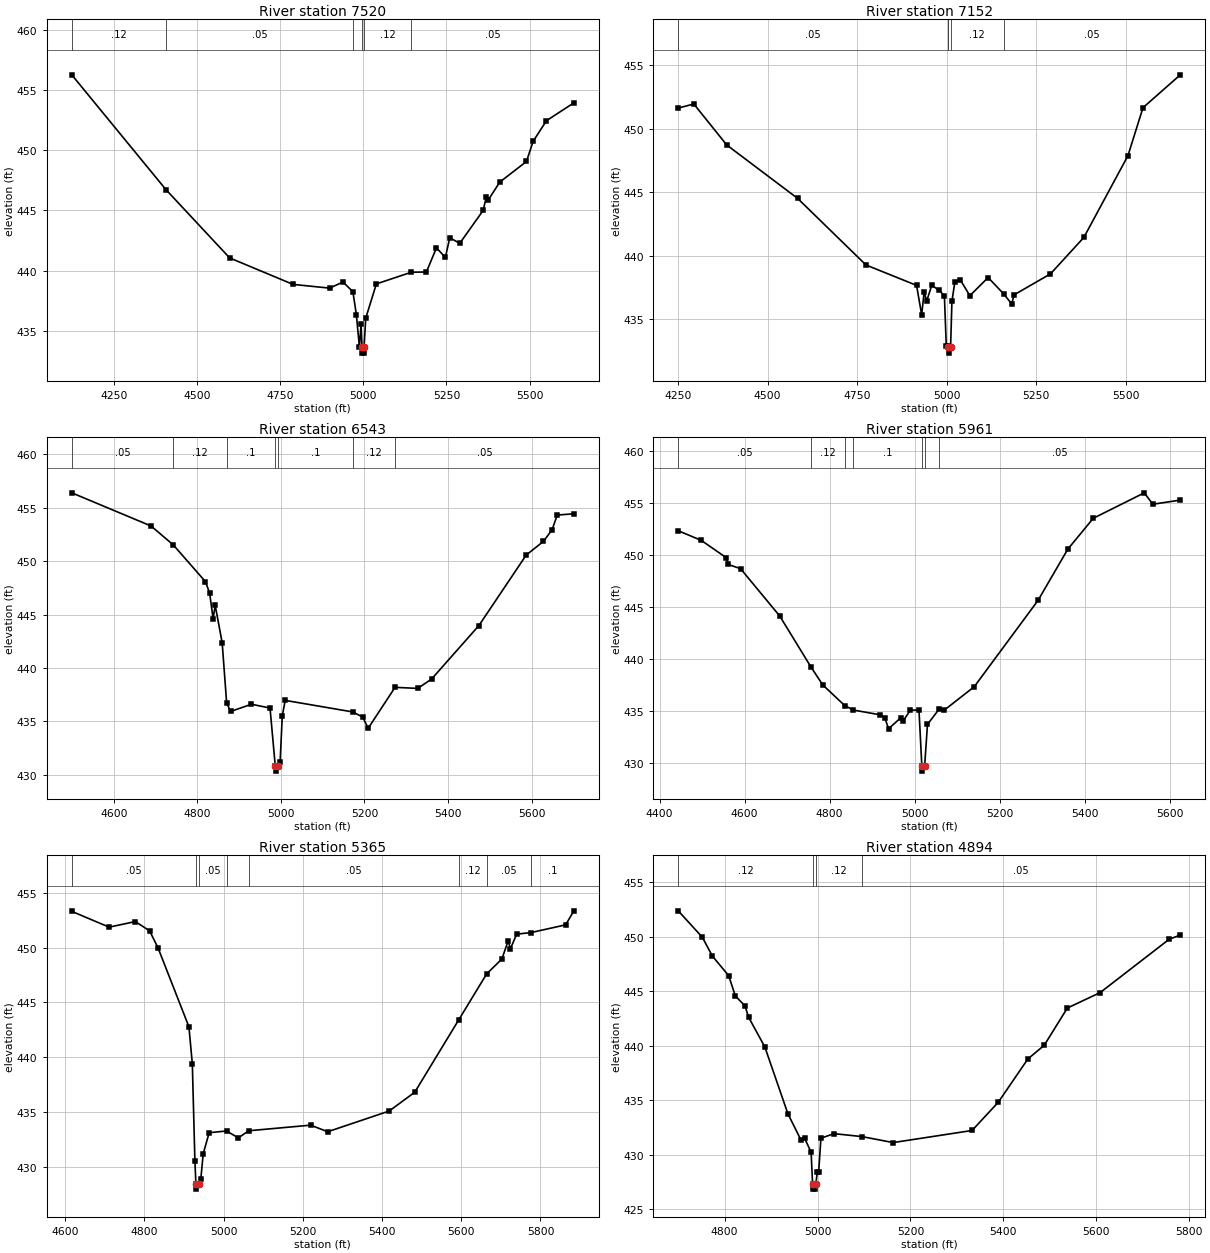
Type RM Length L Ch R = 1,7520,368,368,368
BEGIN DESCRIPTION:
Lacy 028 2972
END DESCRIPTION:
XS GIS Cut Line= 3
      2748107.74      6867937.41      2748172.31      6868822.16
      2748221.09      6869443.05
#Sta/Elev= 30
  4123.2  456.26  4406.5  446.72  4598.0  441.05  4788.6  438.85  4898.8  438.54
  4938.9  439.05  4968.6  438.24  4979.1  436.34  4988.2  433.64  4993.2  435.55
  4996.1  433.64  4997.1  433.14  5001.2  433.14  5002.2  433.64  5007.2  436.04
  5039.2  438.89  5144.4  439.86  5189.7  439.88  5219.8  441.88  5246.9  441.10
  5259.9  442.73  5290.0  442.26  5360.2  444.99  5370.2  446.15  5375.9  445.87
  5410.4  447.35  5490.6  449.06  5510.7  450.74  5550.8  452.45  5633.1  453.93
#Mann=6,-1,0
  4123.2    0.12       0  4406.5    0.05       0  4968.6    0.12       0
  4996.1    0.07       0  5002.2    0.12       0  5144.4    0.05       0
Bank Sta=4996.1,5002.2
Exp/Cntr=0.3,0.1

Type RM Length L Ch R = 1,7152,609,609,609
BEGIN DESCRIPTION:
Lacy 028 2973
END DESCRIPTION:
XS GIS Cut Line= 3
      2747349.58      6868425.70      2747878.35      6868960.55
      2748239.60      6869501.76
#Sta/Elev= 30
  4250.2  451.64  4293.8  451.96  4385.7  448.73  4583.7  444.52  4774.7  439.27
  4916.1  437.66  4930.3  435.35  4937.3  437.11  4944.4  436.44  4958.6  437.66
  4979.7  437.27  4993.9  436.82  4999.1  432.92  5003.2  432.88  5004.7  432.82
  5005.8  432.32  5011.2  432.82  5014.9  436.40  5023.0  437.92  5038.0  438.11
  5065.0  436.85  5116.1  438.28  5159.4  436.99  5182.2  436.19  5188.2  436.91
  5290.3  438.57  5383.5  441.44  5506.6  447.88  5548.7  451.67  5653.0  454.26
#Mann=5,-1,0
  4250.2    0.05       0  5003.2    0.12       0  5004.7    0.05       0
  5011.2    0.12       0  5159.4    0.05       0
Bank Sta=5004.7,5011.2
Exp/Cntr=0.3,0.1

Type RM Length L Ch R = 1,6543,582,582,582
BEGIN DESCRIPTION:
Lacy 028 2974
END DESCRIPTION:
XS GIS Cut Line= 3
      2747076.80      6869421.85      2747570.91      6869384.37
      2748256.53      6869556.38
#Sta/Elev= 30
  4499.0  456.39  4688.7  453.29  4742.1  451.52  4819.1  448.08  4829.1  447.02
  4837.5  444.62  4842.5  445.86  4859.2  442.36  4869.9  436.74  4879.3  435.93
  4929.4  436.61  4973.8  436.25  4986.3  430.85  4987.3  430.35  4992.9  430.85
  4997.9  431.16  5003.1  435.50  5010.1  436.97  5171.7  435.89  5195.7  435.41
  5208.9  434.36  5273.2  438.19  5327.3  438.09  5360.6  438.96  5474.0  443.97
  5587.4  450.57  5628.7  451.85  5649.3  452.94  5661.7  454.31  5701.4  454.43
#Mann=7,-1,0
  4499.0    0.05       0  4742.1    0.12       0  4869.9     0.1       0
  4986.3    0.07       0  4992.9     0.1       0  5171.7    0.12       0
  5273.2    0.05       0
Bank Sta=4986.3,4992.9
Exp/Cntr=0.3,0.1

Type RM Length L Ch R = 1,5961,596,596,596
BEGIN DESCRIPTION:
Lacy 028 2970
END DESCRIPTION:
XS GIS Cut Line= 3
      2747233.05      6869661.12      2747776.92      6869782.45
      2748400.68      6869782.31
#Sta/Elev= 30
  4444.0  452.34  4498.2  451.41  4556.4  449.76  4561.6  449.09  4590.5  448.69
  4682.7  444.13  4756.0  439.23  4784.0  437.49  4835.7  435.50  4856.1  435.07
  4918.3  434.62  4929.7  434.35  4938.8  433.27  4968.0  434.35  4973.1  434.02
  4990.0  435.07  5010.3  435.07  5017.0  429.69  5018.1  429.19  5023.6  429.69
  5030.3  433.69  5057.6  435.16  5070.3  435.08  5140.3  437.32  5290.3  445.63
  5360.3  450.56  5420.3  453.54  5540.3  455.99  5560.3  454.89  5625.0  455.29
#Mann=7,-1,0
  4444.0    0.05       0  4756.0    0.12       0  4835.7    0.05       0
  4856.1     0.1       0  5017.0    0.07       0  5023.6     0.1       0
  5057.6    0.05       0
Bank Sta=5017,5023.6
Exp/Cntr=0.3,0.1

Type RM Length L Ch R = 1,5365,471,471,471
BEGIN DESCRIPTION:
Lacy 028 2969
END DESCRIPTION:
XS GIS Cut Line= 3
      2747122.50      6869833.80      2747440.35      6870044.94
      2748207.94      6870486.87
#Sta/Elev= 30
  4617.0  453.32  4711.3  451.88  4777.3  452.39  4813.3  451.55  4834.6  450.00
  4912.7  442.78  4921.3  439.40  4927.8  430.54  4930.3  428.46  4931.4  427.96
  4937.2  428.46  4942.8  428.91  4948.8  431.20  4963.8  433.11  5007.6  433.27
  5037.4  432.64  5063.8  433.29  5219.9  433.80  5263.0  433.20  5418.2  435.09
  5482.8  436.81  5593.8  443.42  5664.2  447.61  5702.7  448.97  5718.5  450.63
  5724.3  449.91  5740.0  451.24  5776.9  451.39  5863.6  452.09  5884.3  453.37
#Mann=8,-1,0
  4617.0    0.05       0  4930.3    0.04       0  4937.2    0.05       0
  5007.6    0.12       0  5063.8    0.05       0  5593.8    0.12       0
  5664.2    0.05       0  5776.9     0.1       0
Bank Sta=4930.3,4937.2
Exp/Cntr=0.3,0.1

Type RM Length L Ch R = 1,4894,846,846,846
BEGIN DESCRIPTION:
Lacy 028 2954
END DESCRIPTION:
XS GIS Cut Line= 3
      2746939.23      6870124.37      2747165.58      6870324.62
      2747709.90      6870881.04
#Sta/Elev= 30
  4700.2  452.37  4752.0  449.95  4773.7  448.22  4808.8  446.42  4823.1  444.56
  4844.0  443.64  4851.5  442.62  4886.6  439.88  4936.2  433.76  4964.4  431.34
  4972.0  431.52  4986.2  430.23  4989.3  427.34  4990.4  426.84  4995.4  426.84
  4996.5  427.34  4999.4  428.39  5002.4  428.39  5007.3  431.51  5035.5  431.93
  5095.4  431.66  5162.8  431.11  5332.6  432.22  5389.0  434.81  5452.7  438.78
  5488.0  440.04  5537.6  443.45  5608.3  444.87  5756.8  449.76  5780.8  450.15
#Mann=4,-1,0
  4700.2    0.12       0  4989.3    0.07       0  4996.5    0.12       0
  5095.4    0.05       0
Bank Sta=4989.3,4996.5
Exp/Cntr=0.3,0.1

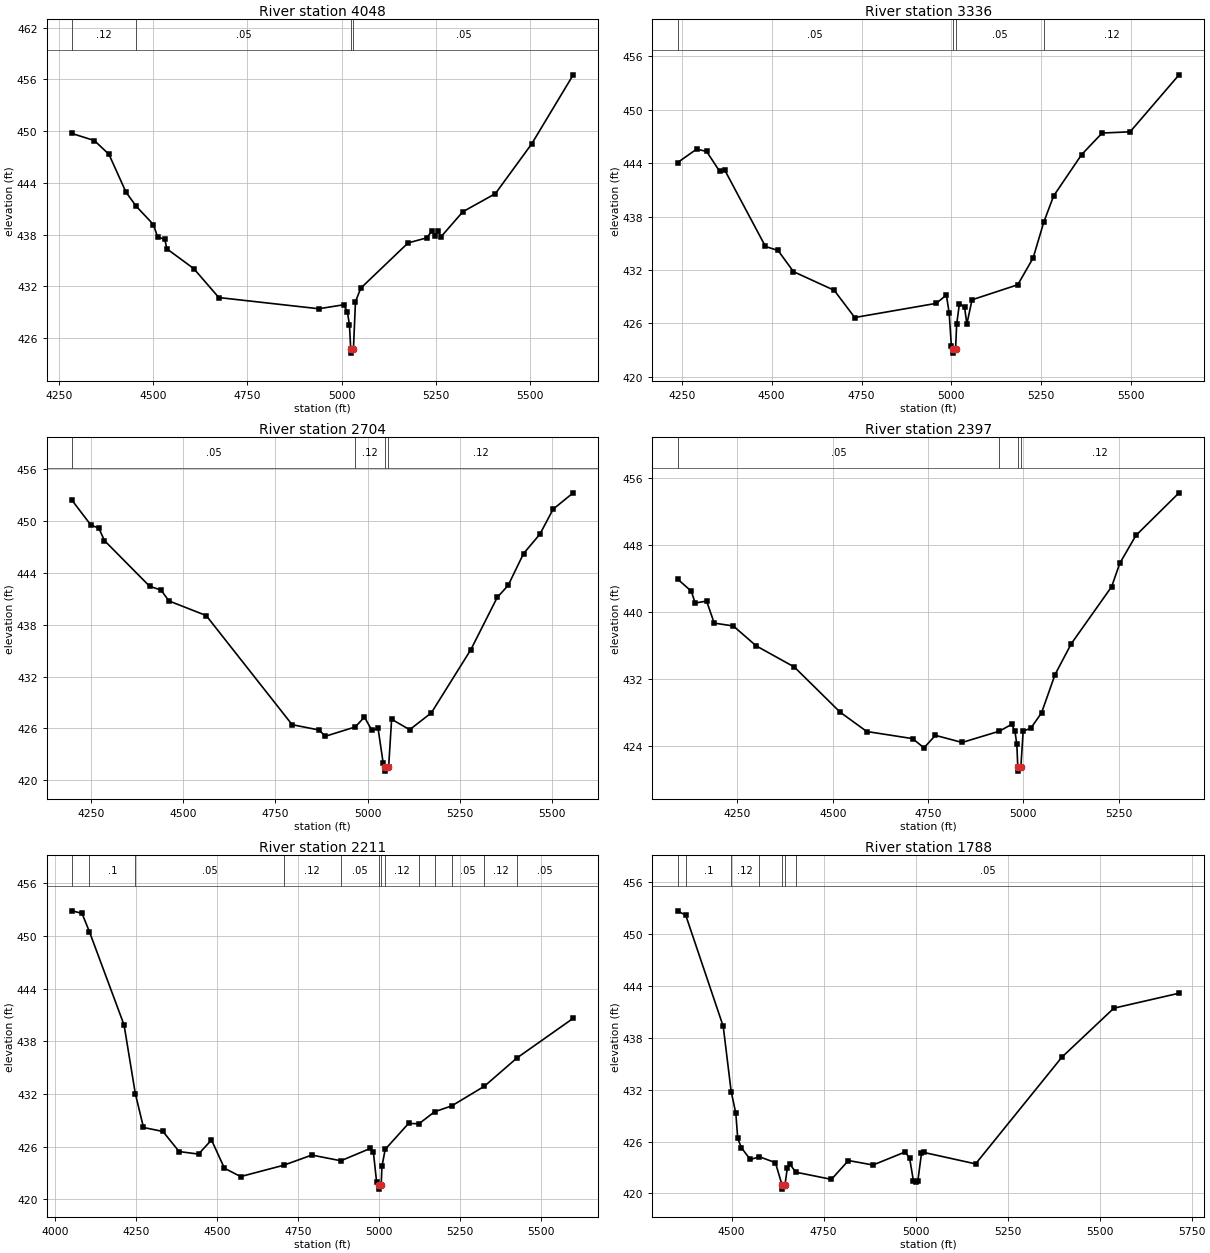
Type RM Length L Ch R = 1,4048,712,712,712
BEGIN DESCRIPTION:
Lacy 028 2953
END DESCRIPTION:
XS GIS Cut Line= 3
      2746879.37      6870278.97      2747141.42      6870946.06
      2747676.75      6871250.59
#Sta/Elev= 30
  4283.1  449.74  4343.3  448.91  4382.0  447.31  4427.3  442.92  4454.5  441.28
  4500.2  439.16  4511.3  437.71  4530.4  437.46  4535.7  436.35  4607.6  434.04
  4673.9  430.69  4939.6  429.39  5005.3  429.85  5015.4  429.06  5021.1  427.49
  5024.4  424.74  5025.6  424.24  5031.7  424.74  5037.0  430.19  5051.1  431.78
  5176.8  437.03  5225.8  437.61  5241.7  438.47  5247.4  437.78  5257.5  438.46
  5263.3  437.69  5322.4  440.65  5408.8  442.75  5505.4  448.53  5615.7  456.54
#Mann=4,-1,0
  4283.1    0.12       0  4454.5    0.05       0  5024.4    0.04       0
  5031.7    0.05       0
Bank Sta=5024.4,5031.7
Exp/Cntr=0.3,0.1

Type RM Length L Ch R = 1,3336,632,632,632
BEGIN DESCRIPTION:
Lacy 028 2952
END DESCRIPTION:
XS GIS Cut Line= 3
      2746415.51      6871097.23      2747000.41      6871589.81
      2747477.13      6872002.31
#Sta/Elev= 30
  4238.2  444.06  4291.1  445.57  4318.9  445.32  4355.2  443.09  4369.5  443.22
  4482.7  434.64  4517.8  434.19  4560.7  431.81  4673.9  429.72  4731.1  426.66
  4957.9  428.25  4986.0  429.19  4993.8  427.17  4999.9  423.47  5004.4  423.16
  5005.5  422.66  5011.7  423.16  5014.6  425.88  5022.3  428.21  5036.5  427.83
  5043.1  425.94  5057.4  428.65  5184.6  430.34  5227.4  433.35  5256.8  437.35
  5284.4  440.32  5362.3  444.96  5419.3  447.38  5497.2  447.52  5633.3  453.92
#Mann=4,-1,0
  4238.2    0.05       0  5004.4    0.04       0  5011.7    0.05       0
  5256.8    0.12       0
Bank Sta=5004.4,5011.7
Exp/Cntr=0.3,0.1

Type RM Length L Ch R = 1,2704,307,307,307
BEGIN DESCRIPTION:
Lacy 028 2951
END DESCRIPTION:
XS GIS Cut Line= 3
      2745957.81      6871578.41      2746658.37      6872000.87
      2746970.22      6872443.58
#Sta/Elev= 30
  4198.1  452.42  4250.0  449.51  4271.4  449.16  4286.9  447.71  4409.2  442.44
  4440.3  441.99  4461.6  440.74  4562.6  439.05  4795.6  426.43  4869.3  425.81
  4884.8  425.08  4966.9  426.17  4991.6  427.31  5011.9  425.77  5028.6  426.01
  5042.5  421.97  5047.1  421.56  5048.3  421.06  5055.2  421.56  5057.3  421.58
  5065.3  427.06  5114.2  425.85  5173.1  427.80  5280.3  435.12  5351.7  441.15
  5381.3  442.54  5423.1  446.22  5467.5  448.47  5503.2  451.35  5557.7  453.24
#Mann=4,-1,0
  4198.1    0.05       0  4966.9    0.12       0  5047.1    0.07       0
  5055.2    0.12       0
Bank Sta=5047.1,5055.2
Exp/Cntr=0.3,0.1

Type RM Length L Ch R = 1,2397,186,186,186
BEGIN DESCRIPTION:
Lacy 028 2948
END DESCRIPTION:
XS GIS Cut Line= 3
      2745719.89      6872240.37      2746661.62      6872267.55
      2746925.66      6872531.41
#Sta/Elev= 30
  4092.8  443.94  4128.9  442.49  4138.9  441.07  4168.9  441.31  4189.0  438.67
  4239.0  438.33  4299.0  435.95  4399.0  433.42  4519.1  428.02  4589.1  425.70
  4709.2  424.85  4739.2  423.75  4769.2  425.24  4839.2  424.39  4936.9  425.74
  4969.3  426.56  4977.7  425.73  4982.7  424.19  4985.2  421.46  4986.4  420.96
  4993.3  421.46  4999.3  425.75  5019.3  426.09  5047.5  427.93  5082.9  432.51
  5125.3  436.19  5231.4  443.03  5252.6  445.81  5295.0  449.16  5408.2  454.26
#Mann=4,-1,0
  4092.8    0.05       0  4936.9    0.12       0  4985.2    0.07       0
  4993.3    0.12       0
Bank Sta=4985.2,4993.3
Exp/Cntr=0.3,0.1

Type RM Length L Ch R = 1,2211,423,423,423
BEGIN DESCRIPTION:
Lacy 028 2947
END DESCRIPTION:
XS GIS Cut Line= 4
      2745554.43      6872375.40      2746513.96      6872384.77
      2746554.33      6872392.58      2746674.40      6872927.37
#Sta/Elev= 30
  4051.0  452.86  4082.6  452.58  4105.6  450.48  4212.6  439.86  4247.3  432.05
  4272.6  428.18  4332.6  427.73  4382.6  425.44  4442.6  425.15  4482.6  426.76
  4522.6  423.54  4572.6  422.59  4705.4  423.88  4792.6  425.04  4882.2  424.39
  4972.6  425.79  4982.6  425.37  4992.6  421.96  4998.6  421.66  4999.8  421.16
  5006.7  421.66  5009.1  423.76  5019.1  425.69  5091.1  428.64  5123.6  428.61
  5171.5  429.97  5224.5  430.64  5325.4  432.88  5426.3  436.11  5599.8  440.62
#Mann=13,-1,0
  4051.0    0.05       0  4105.6     0.1       0  4247.3    0.05       0
  4705.4    0.12       0  4882.2    0.05       0  4998.6    0.05       0
  5006.7    0.05       0  5019.1    0.12       0  5123.6    0.05       0
  5171.5    0.12       0  5224.5    0.05       0  5325.4    0.12       0
  5426.3    0.05       0
Bank Sta=4998.6,5006.7
Exp/Cntr=0.3,0.1

Type RM Length L Ch R = 1,1788,819,819,819
BEGIN DESCRIPTION:
Lacy 028 2950
END DESCRIPTION:
XS GIS Cut Line= 3
      2745578.82      6872403.32      2746140.90      6872560.38
      2746514.59      6873243.89
#Sta/Elev= 30
  4353.2  452.69  4375.5  452.17  4477.3  439.32  4498.9  431.78  4511.5  429.27
  4516.7  426.36  4526.8  425.28  4550.8  423.93  4575.8  424.24  4619.1  423.56
  4636.9  421.00  4638.1  420.50  4645.0  421.00  4651.4  422.92  4658.5  423.39
  4674.3  422.46  4771.3  421.63  4817.5  423.81  4884.2  423.29  4971.7  424.80
  4983.8  424.06  4994.2  421.42  4999.9  421.36  5005.9  421.40  5016.0  424.64
  5021.7  424.75  5163.0  423.42  5397.4  435.76  5538.7  441.43  5715.8  443.16
#Mann=7,-1,0
  4353.2    0.05       0  4375.5     0.1       0  4498.9    0.12       0
  4575.8     0.1       0  4636.9    0.04       0  4645.0     0.1       0
  4674.3    0.05       0
Bank Sta=4636.9,4645
Exp/Cntr=0.3,0.1

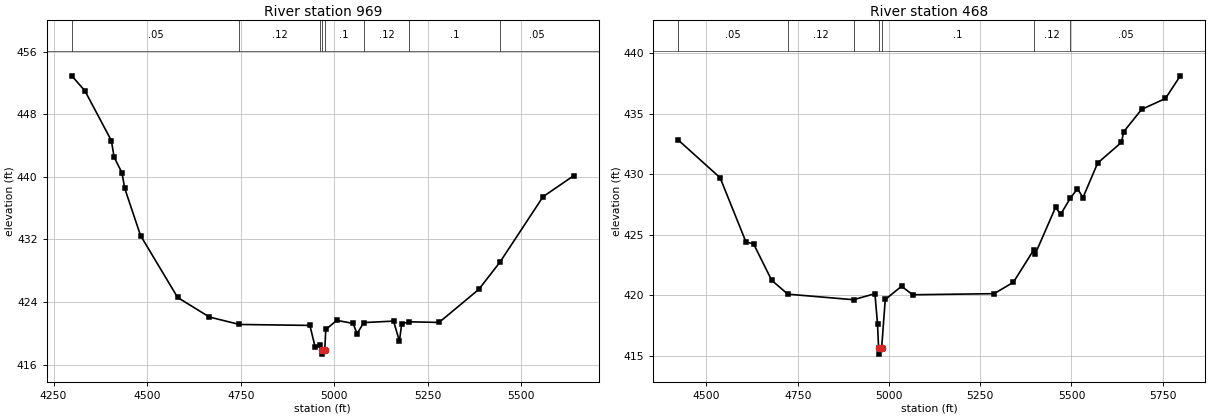
Type RM Length L Ch R = 1,969,501,501,501
BEGIN DESCRIPTION:
Lacy 028 2946
END DESCRIPTION:
XS GIS Cut Line= 3
      2745100.32      6872546.78      2745588.47      6873048.43
      2746180.32      6873296.26
#Sta/Elev= 30
  4298.6  452.90  4333.8  450.98  4404.5  444.61  4411.7  442.51  4432.8  440.50
  4440.0  438.54  4482.4  432.49  4581.5  424.58  4666.3  422.08  4746.7  421.13
  4934.9  421.01  4949.1  418.20  4960.8  418.54  4966.2  417.84  4967.4  417.34
  4974.5  417.84  4977.4  420.49  5006.7  421.65  5050.1  421.27  5060.9  419.95
  5078.8  421.37  5158.5  421.56  5174.1  418.99  5180.2  421.22  5200.5  421.47
  5280.1  421.39  5386.2  425.61  5442.7  429.09  5558.0  437.46  5640.2  440.15
#Mann=8,-1,0
  4298.6    0.05       0  4746.7    0.12       0  4960.8     0.1       0
  4966.2    0.07       0  4974.5     0.1       0  5078.8    0.12       0
  5200.5     0.1       0  5442.7    0.05       0
Bank Sta=4966.2,4974.5
Exp/Cntr=0.3,0.1

Type RM Length L Ch R = 1,468,0,0,0
BEGIN DESCRIPTION:
Lacy 028 2944
END DESCRIPTION:
XS GIS Cut Line= 3
      2745063.10      6873051.75      2745472.05      6873459.36
      2746258.96      6873593.18
#Sta/Elev= 30
  4422.6  432.83  4537.3  429.72  4608.0  424.43  4629.2  424.25  4678.7  421.25
  4722.8  420.11  4902.8  419.65  4961.5  420.15  4968.6  417.65  4971.5  415.66
  4972.7  415.16  4979.9  415.66  4989.8  419.67  5034.4  420.76  5064.9  420.06
  5288.0  420.15  5340.8  421.09  5397.0  423.78  5401.1  423.45  5456.3  427.27
  5470.6  426.71  5497.0  428.04  5516.5  428.81  5531.5  428.08  5571.7  430.93
  5637.0  432.64  5643.0  433.51  5692.2  435.36  5757.5  436.26  5798.2  438.13
#Mann=7,-1,0
  4422.6    0.05       0  4722.8    0.12       0  4902.8     0.1       0
  4971.5    0.07       0  4979.9     0.1       0  5397.0    0.12       0
  5497.0    0.05       0
Bank Sta=4971.5,4979.9
Exp/Cntr=0.3,0.1

Chan Stop Cuts=-1