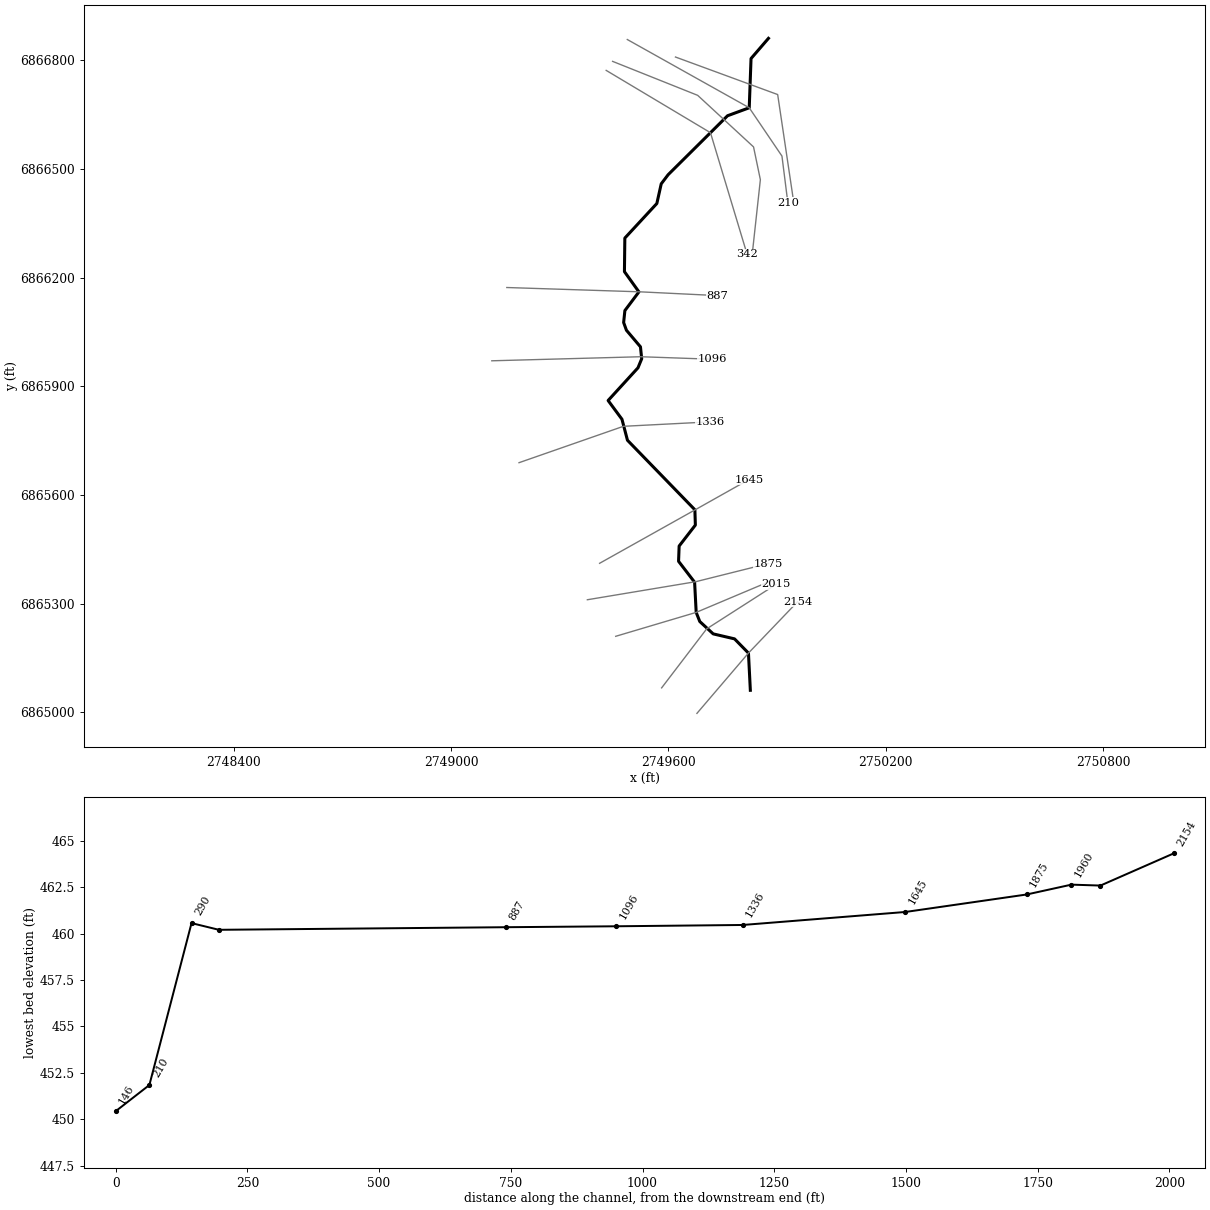
--- Lacy 029.prj (project) ---

Proj Title=Lacy 029 Base Level Engineering
Current Plan=p01
Default Exp/Contr=0.3,0.1
English Units
Geom File=g01
Flow File=f01
Plan File=p01
BEGIN DESCRIPTION:
Lacy 029
END DESCRIPTION:

--- Lacy 029.p01 (plan) ---

Plan Title=Multiple Run
Short Identifier=Multiple
Geom File=g01
Flow File=f01
Subcritical Flow
K Sum by GR= 0
Std Step Tol= 0.01
Critical Tol= 0.01
Num of Std Step Trials= 20
Max Error Tol= 0.3
Flow Tol Ratio= 0.001
Split Flow NTrial= 30
Split Flow Tol= 0.02
Split Flow Ratio= 0.02
Log Output Level= 0
Friction Slope Method= 1
Unsteady Friction Slope Method= 2
Unsteady Bridges Friction Slope Method= 1
Parabolic Critical Depth
Global Vel Dist=  1 , 1 , 1
Global Log Level= 0
CheckData=True
Encroach Param= -1, 0, 0, 0
BEGIN DESCRIPTION:
Multiple Run
END DESCRIPTION:

--- Lacy 029.f01 (steady flow) ---

Flow Title=Multiple
Number of Profiles=7
Profile Names=10-year,25-year,50-year,1pct_min,100-year,1pct_plu,500-year
River Rch & RM= Lacy 029,Reach-1,2154
     146     178     202     114     228     454     290
Boundary for River Rch & Prof#=Lacy 029,Reach-1,1
Up Type=0
Dn Type=3
Dn Slope=0.005
Boundary for River Rch & Prof#=Lacy 029,Reach-1,2
Up Type=0
Dn Type=3
Dn Slope=0.005
Boundary for River Rch & Prof#=Lacy 029,Reach-1,3
Up Type=0
Dn Type=3
Dn Slope=0.005
Boundary for River Rch & Prof#=Lacy 029,Reach-1,4
Up Type=0
Dn Type=3
Dn Slope=0.005
Boundary for River Rch & Prof#=Lacy 029,Reach-1,5
Up Type=0
Dn Type=3
Dn Slope=0.005
Boundary for River Rch & Prof#=Lacy 029,Reach-1,6
Up Type=0
Dn Type=3
Dn Slope=0.005
Boundary for River Rch & Prof#=Lacy 029,Reach-1,7
Up Type=0
Dn Type=3
Dn Slope=0.005

--- Lacy 029.g01 (geometry) ---

Geom Title=Existing Conditions

River Reach=Lacy 029,Reach-1
Reach XY= 30
      2749826.00      6865061.00      2749820.77      6865163.78
      2749782.35      6865202.98      2749723.45      6865216.75
      2749686.39      6865250.90      2749676.47      6865276.09
      2749672.11      6865359.41      2749627.82      6865417.12
      2749629.40      6865459.28      2749674.19      6865517.13
      2749672.87      6865559.37      2749486.75      6865751.32
      2749471.53      6865809.35      2749433.30      6865861.08
      2749515.76      6865951.32      2749526.03      6865976.34
      2749522.63      6866009.26      2749483.88      6866055.07
      2749476.17      6866076.41      2749479.61      6866109.36
      2749518.40      6866160.99      2749478.36      6866216.90
      2749479.47      6866309.50      2749567.82      6866404.96
      2749579.97      6866459.35      2749599.01      6866484.47
      2749763.05      6866647.26      2749822.93      6866669.30
      2749827.91      6866805.20      2749876.00      6866861.00

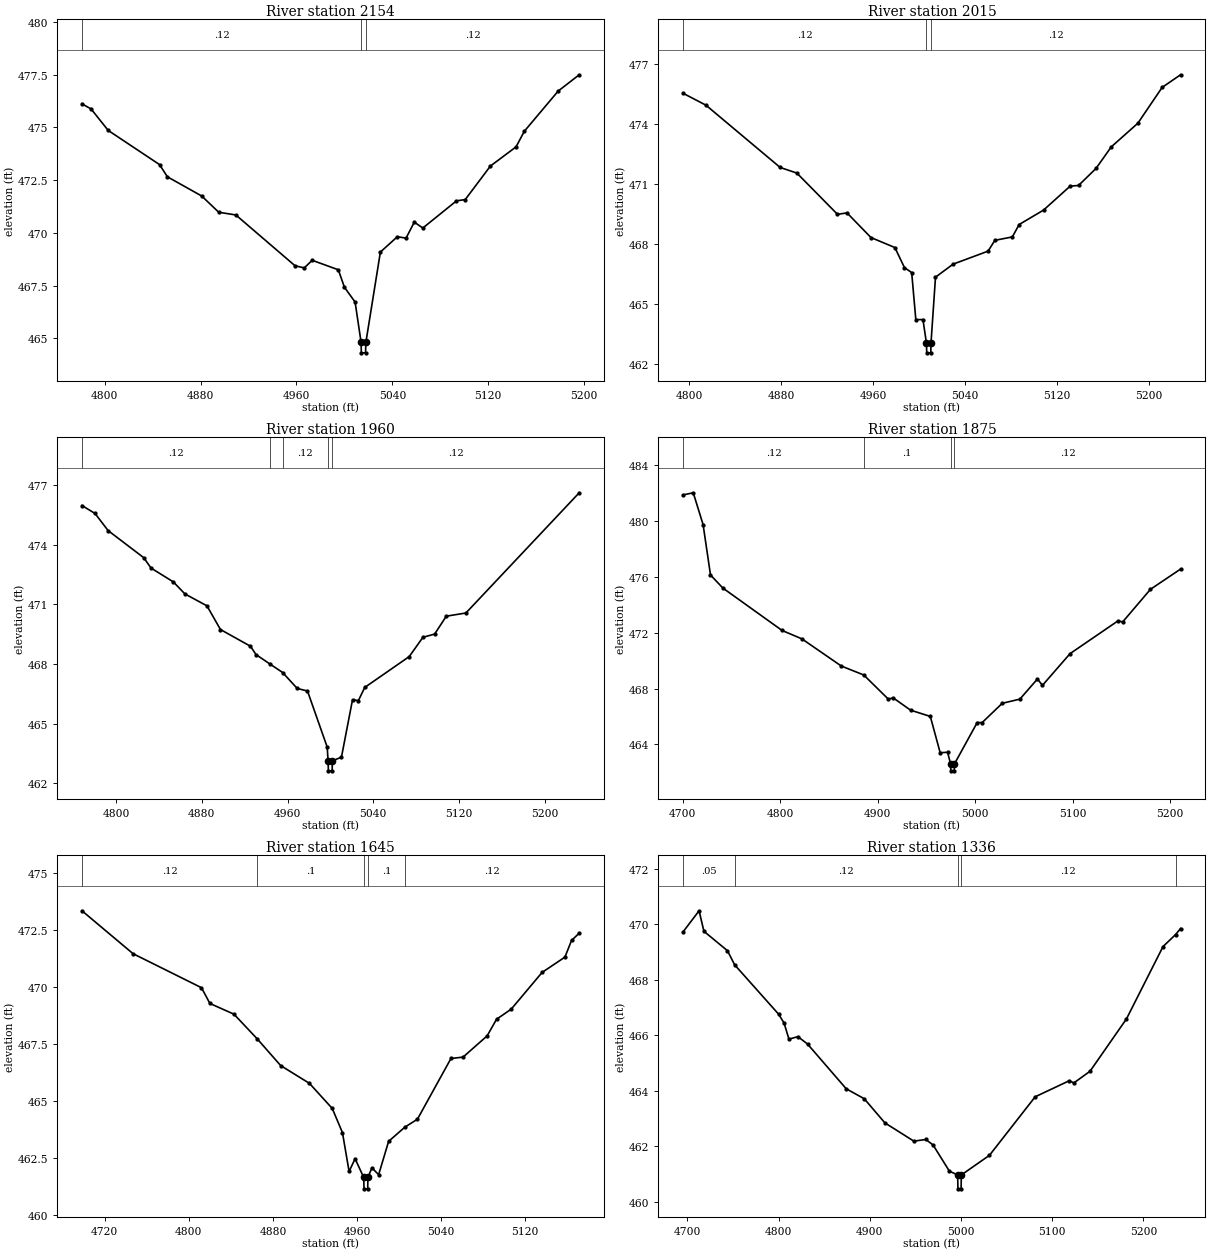
Type RM Length L Ch R = 1,2154,139,139,139
BEGIN DESCRIPTION:
Lacy 029 3010
END DESCRIPTION:
XS GIS Cut Line= 3
      2749678.52      6864997.27      2749820.77      6865163.78
      2749956.24      6865305.29
#Sta/Elev= 30
  4781.0  476.12  4788.6  475.88  4802.9  474.86  4845.7  473.24  4852.3  472.66
  4880.9  471.75  4895.1  470.98  4909.4  470.85  4958.8  468.44  4966.5  468.34
  4973.1  468.70  4994.9  468.25  5000.0  467.42  5008.9  466.72  5013.9  464.81
  5014.1  464.31  5017.6  464.31  5017.9  464.81  5030.0  469.09  5044.2  469.82
  5051.4  469.75  5058.3  470.51  5065.4  470.23  5093.5  471.52  5100.8  471.58
  5121.8  473.17  5143.2  474.08  5150.1  474.82  5178.4  476.73  5195.9  477.50
#Mann=3,-1,0
  4781.0    0.12       0  5013.9    0.07       0  5017.9    0.12       0
Bank Sta=5013.9,5017.9
Exp/Cntr=0.3,0.1

Type RM Length L Ch R = 1,2015,55,55,55
BEGIN DESCRIPTION:
Lacy 029 3012
END DESCRIPTION:
XS GIS Cut Line= 3
      2749581.04      6865067.66      2749705.44      6865230.59
      2749896.72      6865353.20
#Sta/Elev= 30
  4795.0  475.54  4814.7  474.95  4879.2  471.84  4893.7  471.56  4929.0  469.50
  4937.3  469.57  4958.1  468.34  4978.9  467.84  4987.2  466.84  4993.5  466.59
  4997.1  464.24  5003.3  464.24  5006.3  463.08  5006.6  462.58  5010.1  462.58
  5010.3  463.08  5014.2  466.36  5029.5  467.01  5059.9  467.66  5065.8  468.20
  5081.0  468.37  5086.9  468.99  5108.1  469.71  5131.3  470.91  5138.5  470.94
  5153.7  471.79  5167.0  472.87  5190.1  474.05  5211.2  475.84  5227.2  476.47
#Mann=3,-1,0
  4795.0    0.12       0  5006.3    0.07       0  5010.3    0.12       0
Bank Sta=5006.3,5010.3
Exp/Cntr=0.3,0.1

Type RM Length L Ch R = 1,1960,85,85,85
BEGIN DESCRIPTION:
Lacy 029 3011
END DESCRIPTION:
XS GIS Cut Line= 3
      2749454.28      6865210.05      2749676.47      6865276.09
      2749890.34      6865366.25
#Sta/Elev= 30
  4768.2  475.96  4780.4  475.56  4792.6  474.70  4825.8  473.34  4832.6  472.82
  4853.5  472.12  4864.2  471.52  4884.8  470.92  4897.4  469.73  4925.4  468.89
  4930.6  468.47  4943.5  468.00  4955.4  467.57  4969.0  466.77  4978.6  466.64
  4997.0  463.82  4997.8  463.13  4998.1  462.63  5001.6  462.63  5001.8  463.13
  5010.3  463.32  5020.6  466.20  5026.1  466.16  5032.0  466.82  5073.5  468.37
  5086.3  469.34  5097.2  469.50  5108.1  470.40  5126.4  470.56  5232.1  476.60
#Mann=5,-1,0
  4768.2    0.12       0  4943.5     0.1       0  4955.4    0.12       0
  4997.8    0.07       0  5001.8    0.12       0
Bank Sta=4997.8,5001.8
Exp/Cntr=0.3,0.1

Type RM Length L Ch R = 1,1875,230,230,230
BEGIN DESCRIPTION:
Lacy 029 79
END DESCRIPTION:
XS GIS Cut Line= 3
      2749375.99      6865311.00      2749676.00      6865361.00
      2749875.99      6865411.00
#Sta/Elev= 30
  4700.5  481.88  4710.7  482.03  4720.8  479.75  4728.4  476.14  4741.1  475.20
  4801.9  472.16  4822.2  471.56  4862.7  469.61  4885.7  468.97  4910.9  467.24
  4915.9  467.33  4933.7  466.45  4954.0  466.00  4964.1  463.40  4971.7  463.43
  4974.8  462.60  4975.0  462.10  4978.5  462.10  4978.8  462.60  5002.1  465.56
  5007.2  465.56  5027.8  466.94  5045.9  467.24  5063.9  468.68  5069.1  468.23
  5097.4  470.50  5146.4  472.84  5151.5  472.78  5179.9  475.11  5210.8  476.56
#Mann=4,-1,0
  4700.5    0.12       0  4885.7     0.1       0  4974.8    0.07       0
  4978.8    0.12       0
Bank Sta=4974.8,4978.8
Exp/Cntr=0.3,0.1

Type RM Length L Ch R = 1,1645,309,309,309
BEGIN DESCRIPTION:
Lacy 029 3006
END DESCRIPTION:
XS GIS Cut Line= 3
      2749409.79      6865411.60      2749671.58      6865558.18
      2749822.36      6865642.95
#Sta/Elev= 30
  4698.4  473.34  4747.0  471.46  4812.1  469.97  4820.1  469.28  4843.0  468.81
  4865.1  467.73  4887.4  466.56  4914.8  465.78  4936.5  464.68  4946.2  463.62
  4952.5  461.92  4958.2  462.48  4966.4  461.66  4966.7  461.16  4970.2  461.16
  4970.4  461.66  4974.2  462.08  4980.6  461.78  4990.1  463.24  5005.5  463.86
  5017.5  464.21  5049.4  466.87  5060.9  466.93  5083.8  467.86  5092.8  468.59
  5106.7  469.03  5136.1  470.64  5157.8  471.31  5164.1  472.04  5171.4  472.36
#Mann=5,-1,0
  4698.4    0.12       0  4865.1     0.1       0  4966.4    0.07       0
  4970.4     0.1       0  5005.5    0.12       0
Bank Sta=4966.4,4970.4
Exp/Cntr=0.3,0.1

Type RM Length L Ch R = 1,1336,240,240,240
BEGIN DESCRIPTION:
Lacy 029 3005
END DESCRIPTION:
XS GIS Cut Line= 3
      2749187.33      6865689.39      2749475.52      6865789.84
      2749715.21      6865802.12
#Sta/Elev= 30
  4695.6  469.74  4712.9  470.49  4718.2  469.75  4744.0  469.05  4751.9  468.54
  4800.1  466.76  4806.1  466.44  4811.4  465.86  4821.3  465.95  4831.9  465.68
  4874.2  464.07  4894.0  463.71  4916.6  462.84  4948.4  462.18  4961.5  462.24
  4969.5  462.04  4987.3  461.10  4996.4  460.96  4996.7  460.46  5000.2  460.46
  5000.4  460.96  5031.3  461.67  5081.4  463.78  5118.8  464.36  5123.8  464.28
  5141.5  464.70  5181.5  466.59  5221.6  469.20  5235.3  469.63  5240.8  469.85
#Mann=5,-1,0
  4695.6    0.05       0  4751.9    0.12       0  4996.4    0.07       0
  5000.4    0.12       0  5235.3     0.1       0
Bank Sta=4996.4,5000.4
Exp/Cntr=0.3,0.1

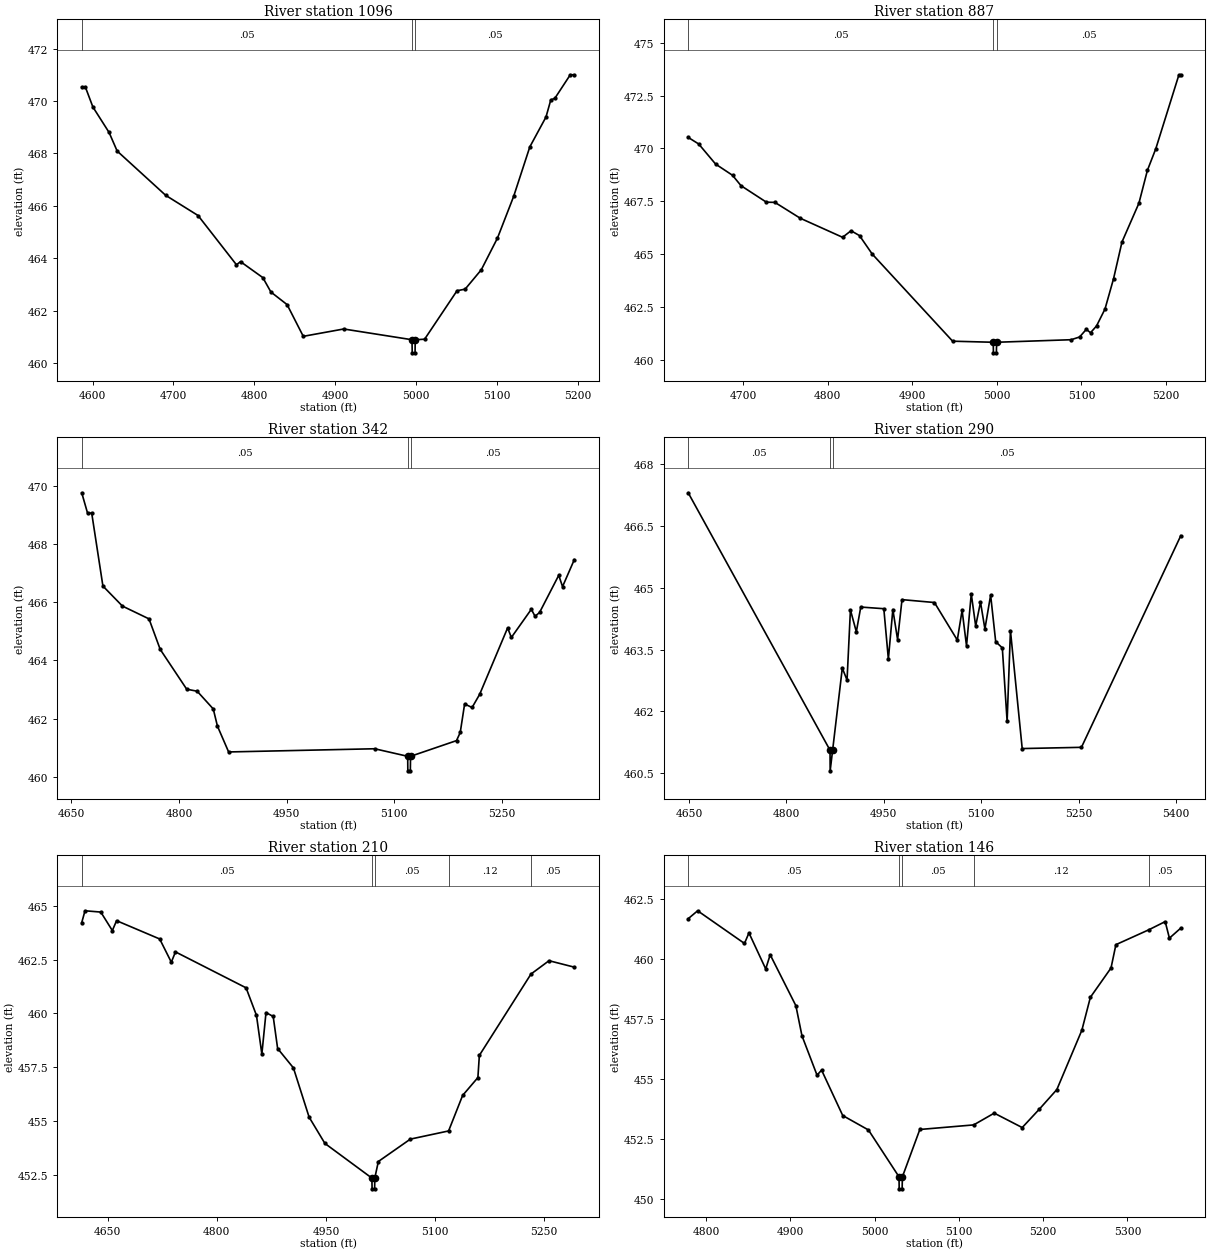
Type RM Length L Ch R = 1,1096,209,209,209
BEGIN DESCRIPTION:
Lacy 029 3004
END DESCRIPTION:
XS GIS Cut Line= 3
      2749112.21      6865970.72      2749523.73      6865981.94
      2749720.94      6865975.01
#Sta/Elev= 30
  4586.6  470.54  4591.0  470.54  4600.4  469.77  4620.4  468.80  4630.4  468.09
  4690.4  466.40  4730.4  465.63  4777.9  463.75  4782.9  463.87  4810.5  463.26
  4820.5  462.71  4840.5  462.23  4860.5  461.02  4910.5  461.30  4994.9  460.89
  4995.2  460.39  4998.7  460.39  4998.9  460.89  5010.5  460.91  5050.6  462.76
  5060.6  462.82  5080.6  463.56  5100.6  464.77  5120.6  466.36  5140.6  468.25
  5160.6  469.39  5166.5  470.04  5171.5  470.10  5190.6  471.00  5195.6  471.00
#Mann=3,-1,0
  4586.6    0.05       0  4994.9    0.03       0  4998.9    0.05       0
Bank Sta=4994.9,4998.9
Exp/Cntr=0.3,0.1

Type RM Length L Ch R = 1,887,545,545,545
BEGIN DESCRIPTION:
Lacy 029 3003
END DESCRIPTION:
XS GIS Cut Line= 3
      2749153.60      6866173.04      2749521.61      6866161.13
      2749735.45      6866150.70
#Sta/Elev= 30
  4635.1  470.52  4647.5  470.21  4667.5  469.26  4687.5  468.73  4697.5  468.24
  4727.5  467.46  4737.6  467.45  4767.6  466.70  4817.6  465.80  4827.6  466.11
  4837.6  465.88  4852.6  465.01  4947.7  460.89  4995.7  460.84  4995.9  460.34
  4999.4  460.34  4999.7  460.84  5087.8  460.96  5097.8  461.09  5105.7  461.45
  5110.7  461.29  5117.8  461.61  5127.8  462.41  5137.9  463.84  5147.9  465.58
  5167.9  467.41  5177.9  468.96  5187.9  469.99  5215.2  473.48  5217.4  473.48
#Mann=3,-1,0
  4635.1    0.05       0  4995.7    0.03       0  4999.7    0.05       0
Bank Sta=4995.7,4999.7
Exp/Cntr=0.3,0.1

Type RM Length L Ch R = 1,342,52,52,52
BEGIN DESCRIPTION:
Lacy 029 3009
END DESCRIPTION:
XS GIS Cut Line= 3
      2749427.98      6866772.49      2749715.91      6866600.48
      2749817.08      6866264.69
#Sta/Elev= 30
  4664.6  469.77  4672.7  469.07  4678.5  469.07  4694.1  466.56  4721.3  465.87
  4758.3  465.43  4773.9  464.38  4810.8  463.01  4825.4  462.94  4847.8  462.33
  4853.6  461.74  4869.2  460.85  5072.6  460.96  5118.6  460.70  5118.8  460.20
  5122.3  460.20  5122.6  460.70  5186.6  461.24  5191.8  461.52  5197.9  462.50
  5208.3  462.38  5218.8  462.83  5257.8  465.12  5263.0  464.79  5290.8  465.76
  5296.0  465.52  5302.3  465.65  5329.0  466.93  5334.3  466.54  5350.7  467.47
#Mann=3,-1,0
  4664.6    0.05       0  5118.6    0.03       0  5122.6    0.05       0
Bank Sta=5118.6,5122.6
Exp/Cntr=0.3,0.1

Type RM Length L Ch R = 1,290,80,80,80
BEGIN DESCRIPTION:
Lacy 029 3008
END DESCRIPTION:
XS GIS Cut Line= 5
      2749445.70      6866797.40      2749680.63      6866703.59
      2749834.85      6866561.19      2749853.66      6866470.69
      2749831.63      6866269.00
#Sta/Elev= 30
  4648.9  467.30  4867.2  461.06  4867.4  460.56  4871.2  461.06  4886.1  463.05
  4893.4  462.76  4898.6  464.46  4907.7  463.93  4914.5  464.53  4950.0  464.49
  4957.0  463.27  4963.9  464.47  4971.2  463.74  4978.0  464.71  5027.9  464.64
  5063.1  463.73  5070.5  464.45  5077.3  463.59  5084.6  464.85  5091.4  464.07
  5098.8  464.65  5105.6  464.00  5114.4  464.82  5122.2  463.69  5132.4  463.54
  5139.8  461.76  5144.9  463.96  5163.0  461.10  5254.2  461.13  5407.1  466.26
#Mann=3,-1,0
  4648.9    0.05       0  4867.2    0.03       0  4871.2    0.05       0
Bank Sta=4867.2,4871.2
Exp/Cntr=0.3,0.1

Type RM Length L Ch R = 1,210,64,64,64
BEGIN DESCRIPTION:
Lacy 029 3007
END DESCRIPTION:
XS GIS Cut Line= 4
      2749486.27      6866857.73      2749822.93      6866669.30
      2749913.26      6866535.93      2749929.60      6866406.44
#Sta/Elev= 30
  4614.2  464.22  4618.7  464.77  4640.4  464.71  4656.3  463.85  4662.1  464.31
  4721.4  463.46  4737.4  462.38  4743.1  462.86  4840.2  461.19  4854.5  459.91
  4861.9  458.11  4867.6  460.04  4877.5  459.86  4883.6  458.37  4905.3  457.47
  4926.9  455.18  4948.6  453.96  5013.2  452.35  5013.5  451.85  5017.0  451.85
  5017.2  452.35  5022.1  453.12  5066.1  454.16  5118.7  454.54  5138.0  456.19
  5159.0  457.02  5161.0  458.05  5232.0  461.83  5256.8  462.45  5291.6  462.15
#Mann=5,-1,0
  4614.2    0.05       0  5013.2    0.04       0  5017.2    0.05       0
  5118.7    0.12       0  5232.0    0.05       0
Bank Sta=5013.2,5017.2
Exp/Cntr=0.3,0.1

Type RM Length L Ch R = 1,146,0,0,0
BEGIN DESCRIPTION:
Lacy 029 3510
END DESCRIPTION:
XS GIS Cut Line= 3
      2749619.30      6866809.40      2749901.46      6866705.80
      2749943.32      6866424.88
#Sta/Elev= 30
  4778.7  461.68  4789.9  462.01  4845.5  460.65  4850.8  461.09  4870.7  459.59
  4876.0  460.18  4906.5  458.06  4913.7  456.81  4931.6  455.17  4937.0  455.38
  4962.1  453.49  4992.6  452.89  5028.9  450.94  5029.1  450.44  5032.6  450.44
  5032.9  450.94  5053.6  452.91  5117.5  453.10  5141.9  453.59  5175.1  452.99
  5195.3  453.75  5216.2  454.57  5245.9  457.04  5256.0  458.41  5280.5  459.63
  5286.3  460.60  5325.4  461.22  5344.8  461.56  5349.8  460.87  5363.3  461.29
#Mann=5,-1,0
  4778.7    0.05       0  5028.9    0.04       0  5032.9    0.05       0
  5117.5    0.12       0  5325.4    0.05       0
Bank Sta=5028.9,5032.9
Exp/Cntr=0.3,0.1

Chan Stop Cuts=-1