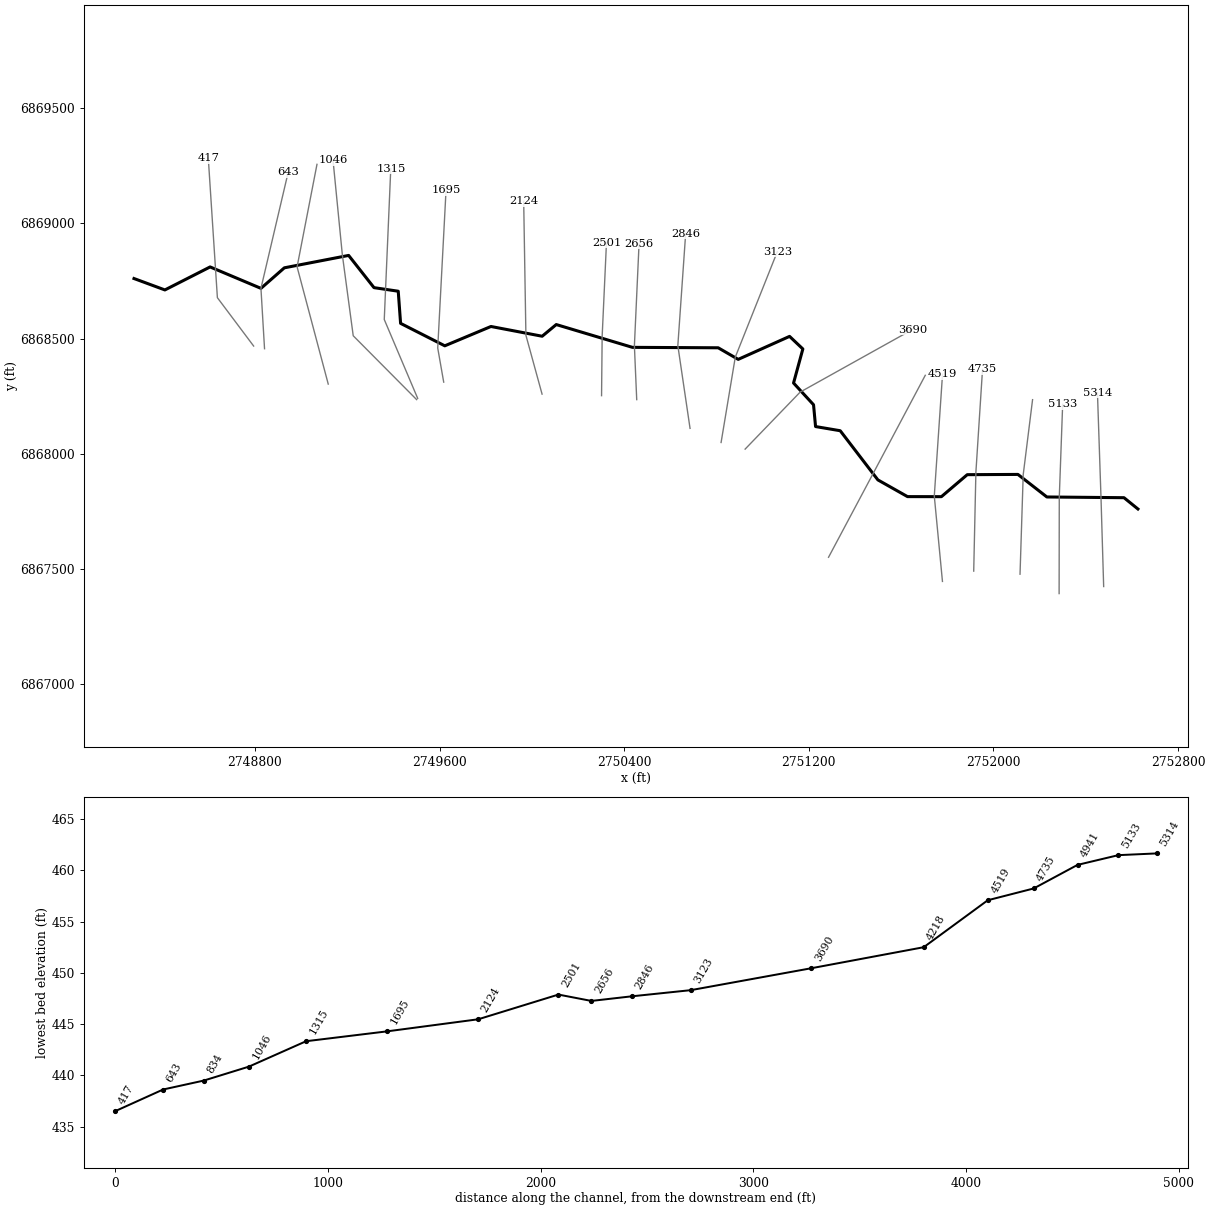
--- Lacy 030.prj (project) ---

Proj Title=Lacy 030 Base Level Engineering
Current Plan=p01
Default Exp/Contr=0.3,0.1
English Units
Geom File=g01
Flow File=f01
Plan File=p01
BEGIN DESCRIPTION:
Lacy 030
END DESCRIPTION:

--- Lacy 030.p01 (plan) ---

Plan Title=Multiple Run
Short Identifier=Multiple
Geom File=g01
Flow File=f01
Subcritical Flow
K Sum by GR= 0
Std Step Tol= 0.01
Critical Tol= 0.01
Num of Std Step Trials= 20
Max Error Tol= 0.3
Flow Tol Ratio= 0.001
Split Flow NTrial= 30
Split Flow Tol= 0.02
Split Flow Ratio= 0.02
Log Output Level= 0
Friction Slope Method= 1
Unsteady Friction Slope Method= 2
Unsteady Bridges Friction Slope Method= 1
Parabolic Critical Depth
Global Vel Dist=  1 , 1 , 1
Global Log Level= 0
CheckData=True
Encroach Param= -1, 0, 0, 0
BEGIN DESCRIPTION:
Multiple Run
END DESCRIPTION:

--- Lacy 030.f01 (steady flow) ---

Flow Title=Multiple
Number of Profiles=7
Profile Names=10-year,25-year,50-year,1pct_min,100-year,1pct_plu,500-year
River Rch & RM= Lacy 030,Reach-1,5314
     488     645     770     457     913    1821    1284
Boundary for River Rch & Prof#=Lacy 030,Reach-1,1
Up Type=0
Dn Type=3
Dn Slope=0.005
Boundary for River Rch & Prof#=Lacy 030,Reach-1,2
Up Type=0
Dn Type=3
Dn Slope=0.005
Boundary for River Rch & Prof#=Lacy 030,Reach-1,3
Up Type=0
Dn Type=3
Dn Slope=0.005
Boundary for River Rch & Prof#=Lacy 030,Reach-1,4
Up Type=0
Dn Type=3
Dn Slope=0.005
Boundary for River Rch & Prof#=Lacy 030,Reach-1,5
Up Type=0
Dn Type=3
Dn Slope=0.005
Boundary for River Rch & Prof#=Lacy 030,Reach-1,6
Up Type=0
Dn Type=3
Dn Slope=0.005
Boundary for River Rch & Prof#=Lacy 030,Reach-1,7
Up Type=0
Dn Type=3
Dn Slope=0.005

--- Lacy 030.g01 (geometry) ---

Geom Title=Existing Conditions

River Reach=Lacy 030,Reach-1
Reach XY= 30
      2752626.00      6867761.00      2752565.60      6867810.04
      2752231.45      6867813.18      2752106.02      6867911.04
      2751886.44      6867909.94      2751774.53      6867814.54
      2751627.56      6867814.74      2751499.18      6867887.29
      2751336.06      6868100.60      2751229.19      6868118.72
      2751220.42      6868213.36      2751133.81      6868307.59
      2751174.12      6868455.32      2751116.54      6868509.98
      2750894.04      6868410.21      2750807.32      6868460.49
      2750435.66      6868462.38      2750105.61      6868561.29
      2750044.61      6868510.60      2749822.70      6868552.92
      2749622.68      6868469.04      2749431.18      6868566.42
      2749420.95      6868705.91      2749315.94      6868721.41
      2749206.05      6868861.25      2748927.47      6868807.43
      2748826.10      6868718.33      2748605.82      6868811.28
      2748409.90      6868711.48      2748276.00      6868761.00

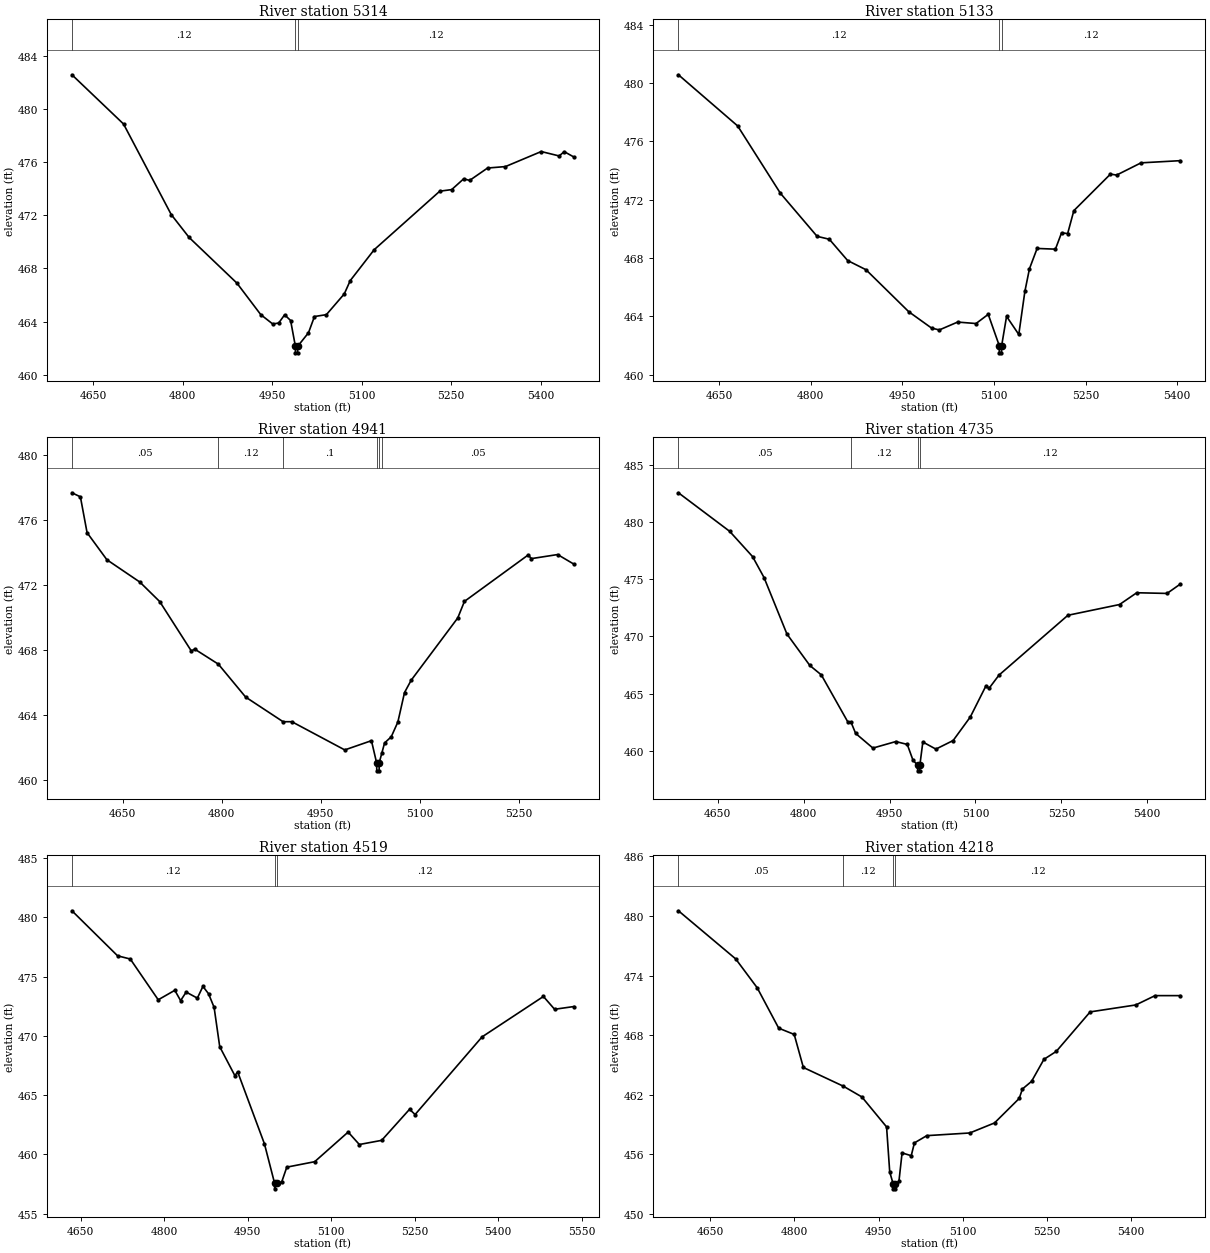
Type RM Length L Ch R = 1,5314,181,181,181
BEGIN DESCRIPTION:
Lacy 030 2999
END DESCRIPTION:
XS GIS Cut Line= 3
      2752477.54      6867424.57      2752465.98      6867810.20
      2752450.58      6868265.64
#Sta/Elev= 30
  4614.2  482.56  4700.7  478.86  4780.7  472.05  4810.7  470.33  4890.8  466.90
  4930.8  464.53  4950.8  463.83  4960.8  463.90  4970.8  464.52  4980.8  464.09
  4988.8  462.16  4989.0  461.66  4992.5  461.66  4992.8  462.16  5010.8  463.17
  5020.8  464.39  5040.8  464.53  5070.8  466.09  5080.8  467.09  5120.9  469.41
  5230.9  473.81  5250.9  473.93  5271.0  474.74  5281.0  474.62  5311.0  475.55
  5341.0  475.66  5401.0  476.79  5431.0  476.46  5439.6  476.78  5455.7  476.38
#Mann=3,-1,0
  4614.2    0.12       0  4988.8    0.07       0  4992.8    0.12       0
Bank Sta=4988.8,4992.8
Exp/Cntr=0.3,0.1

Type RM Length L Ch R = 1,5133,192,192,192
BEGIN DESCRIPTION:
Lacy 030 2998
END DESCRIPTION:
XS GIS Cut Line= 3
      2752284.52      6867394.00      2752285.18      6867810.50
      2752299.87      6868215.23
#Sta/Elev= 30
  4583.5  480.56  4680.5  477.05  4750.5  472.43  4810.5  469.48  4830.5  469.28
  4860.5  467.82  4890.5  467.19  4960.5  464.31  4997.8  463.19  5010.5  463.06
  5040.5  463.60  5070.6  463.50  5090.6  464.13  5108.6  461.99  5108.8  461.49
  5112.3  461.49  5112.6  461.99  5120.6  463.99  5140.6  462.75  5150.6  465.71
  5158.1  467.26  5170.6  468.65  5200.6  468.60  5210.6  469.72  5220.6  469.67
  5230.7  471.24  5290.7  473.75  5300.7  473.68  5340.7  474.52  5405.0  474.67
#Mann=3,-1,0
  4583.5    0.12       0  5108.6    0.07       0  5112.6    0.12       0
Bank Sta=5108.6,5112.6
Exp/Cntr=0.3,0.1

Type RM Length L Ch R = 1,4941,206,206,206
BEGIN DESCRIPTION:
Lacy 030 2994
END DESCRIPTION:
XS GIS Cut Line= 3
      2752115.14      6867478.16      2752128.92      6867909.75
      2752169.47      6868235.42
#Sta/Elev= 30
  4573.1  477.69  4585.9  477.44  4596.0  475.23  4626.0  473.56  4676.0  472.18
  4706.0  470.98  4753.9  467.93  4758.9  468.05  4794.8  467.12  4836.1  465.09
  4892.8  463.57  4906.1  463.57  4986.2  461.83  5026.6  462.40  5034.4  461.04
  5034.7  460.54  5038.2  460.54  5038.4  461.04  5042.5  461.66  5046.5  462.26
  5056.6  462.64  5066.6  463.55  5076.7  465.37  5086.8  466.13  5157.3  469.97
  5167.4  470.99  5263.8  473.85  5268.9  473.63  5308.5  473.88  5333.1  473.29
#Mann=6,-1,0
  4573.1    0.05       0  4794.8    0.12       0  4892.8     0.1       0
  5034.4    0.07       0  5038.4     0.1       0  5042.5    0.05       0
Bank Sta=5034.4,5038.4
Exp/Cntr=0.3,0.1

Type RM Length L Ch R = 1,4735,216,216,216
BEGIN DESCRIPTION:
Lacy 030 2995
END DESCRIPTION:
XS GIS Cut Line= 3
      2751914.45      6867491.53      2751923.89      6867920.37
      2751952.64      6868366.90
#Sta/Elev= 30
  4581.3  482.55  4670.8  479.18  4710.8  476.97  4730.8  475.14  4770.8  470.20
  4810.8  467.45  4830.8  466.63  4877.4  462.49  4882.7  462.49  4890.8  461.51
  4920.9  460.23  4960.9  460.80  4980.9  460.55  4990.9  459.17  4998.9  458.74
  4999.1  458.24  5002.6  458.24  5002.9  458.74  5008.1  460.76  5030.9  460.14
  5061.0  460.89  5091.0  462.95  5118.5  465.69  5123.5  465.44  5141.1  466.61
  5261.4  471.84  5351.6  472.78  5381.6  473.81  5434.5  473.75  5457.7  474.57
#Mann=4,-1,0
  4581.3    0.05       0  4882.7    0.12       0  4998.9    0.07       0
  5002.9    0.12       0
Bank Sta=4998.9,5002.9
Exp/Cntr=0.3,0.1

Type RM Length L Ch R = 1,4519,301,301,301
BEGIN DESCRIPTION:
Lacy 030 2996
END DESCRIPTION:
XS GIS Cut Line= 3
      2751779.02      6867446.72      2751743.63      6867817.30
      2751779.30      6868345.53
#Sta/Elev= 30
  4634.4  480.55  4716.4  476.75  4739.2  476.48  4789.4  473.04  4819.2  473.84
  4829.6  472.97  4839.6  473.69  4859.7  473.18  4869.7  474.17  4879.8  473.55
  4889.8  472.40  4899.9  469.08  4927.1  466.64  4932.1  466.96  4980.2  460.89
  4998.3  457.59  4998.6  457.09  5002.3  457.59  5011.0  457.64  5020.4  458.92
  5070.5  459.38  5130.6  461.88  5150.7  460.83  5190.8  461.18  5240.9  463.80
  5250.9  463.36  5371.2  469.91  5481.4  473.32  5501.5  472.24  5536.1  472.47
#Mann=3,-1,0
  4634.4    0.12       0  4998.3    0.07       0  5002.3    0.12       0
Bank Sta=4998.3,5002.3
Exp/Cntr=0.3,0.1

Type RM Length L Ch R = 1,4218,528,528,528
BEGIN DESCRIPTION:
Lacy 030 2993
END DESCRIPTION:
XS GIS Cut Line= 3
      2751285.45      6867551.61      2751477.12      6867912.17
      2751704.53      6868341.07
#Sta/Elev= 30
  4593.5  480.53  4695.5  475.68  4733.8  472.77  4772.1  468.70  4799.7  468.07
  4816.0  464.74  4887.3  462.85  4920.2  461.77  4964.2  458.75  4969.8  454.21
  4975.9  453.01  4976.1  452.51  4979.6  452.51  4979.9  453.01  4986.2  453.26
  4991.8  456.13  5008.1  455.85  5013.8  457.14  5035.8  457.87  5112.4  458.14
  5156.4  459.15  5200.4  461.62  5206.1  462.57  5222.4  463.34  5244.4  465.56
  5266.4  466.36  5326.7  470.34  5408.0  471.04  5442.3  471.98  5487.3  471.98
#Mann=4,-1,0
  4593.5    0.05       0  4887.3    0.12       0  4975.9    0.07       0
  4979.9    0.12       0
Bank Sta=4975.9,4979.9
Exp/Cntr=0.3,0.1

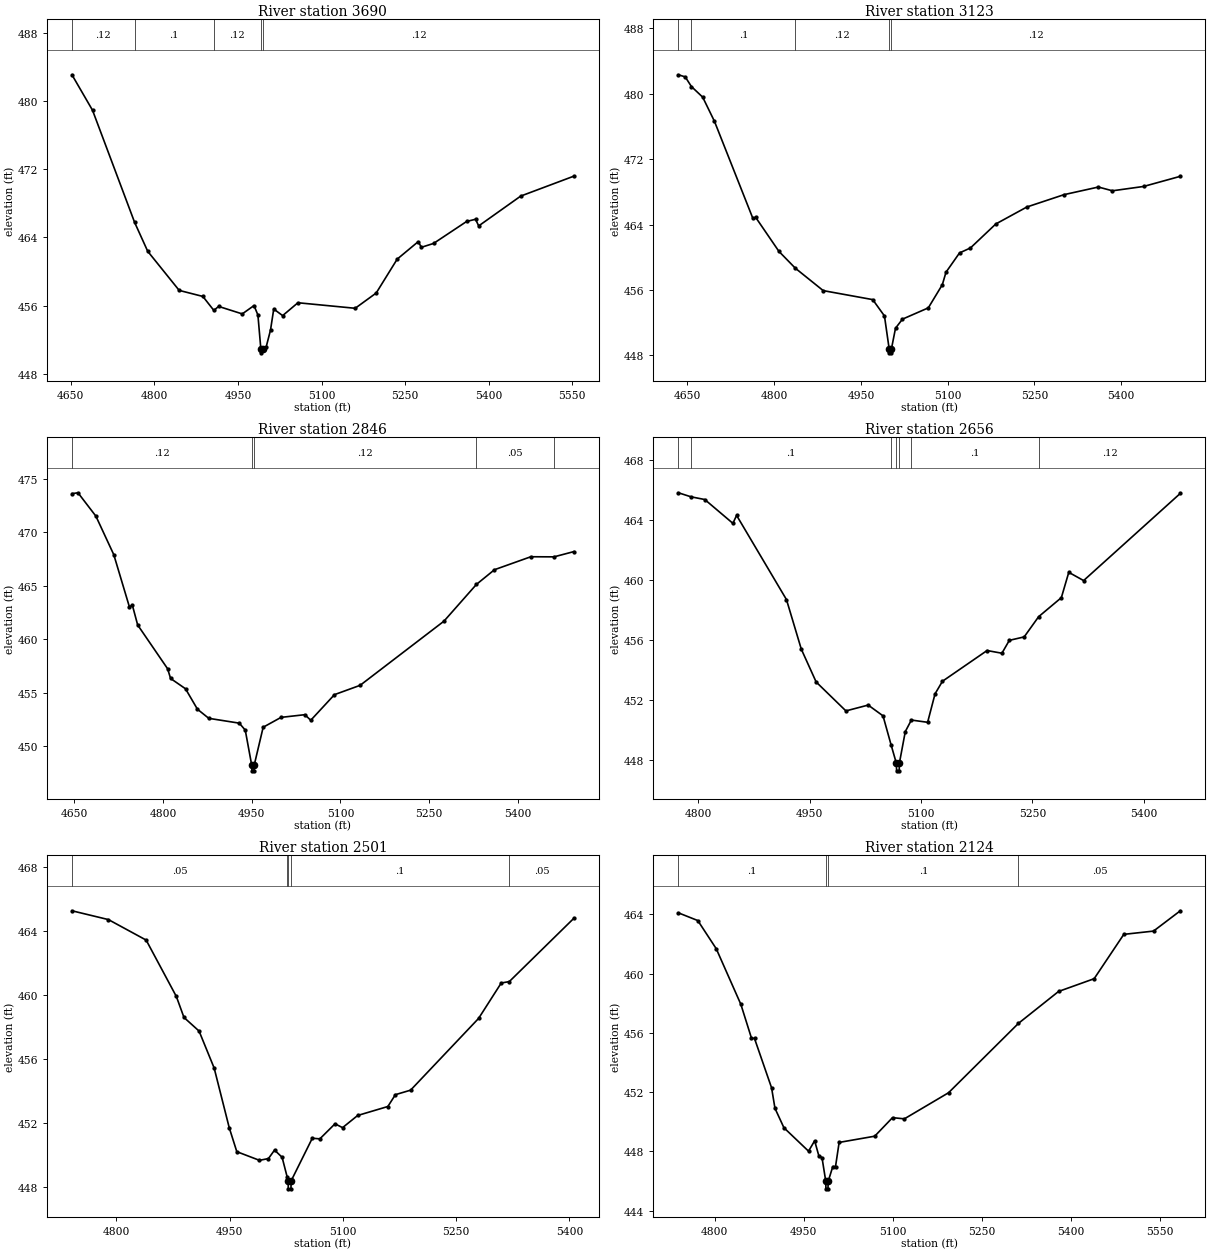
Type RM Length L Ch R = 1,3690,567,567,567
BEGIN DESCRIPTION:
Lacy 030 2992
END DESCRIPTION:
XS GIS Cut Line= 3
      2750924.01      6868020.86      2751162.46      6868268.24
      2751649.13      6868539.79
#Sta/Elev= 30
  4652.0  483.10  4688.9  478.94  4764.5  465.77  4788.0  462.38  4844.5  457.79
  4887.0  457.08  4906.7  455.44  4915.3  455.91  4957.7  455.03  4978.8  456.01
  4985.8  454.90  4991.0  450.96  4991.2  450.46  4995.0  450.96  5000.5  451.12
  5008.4  453.13  5014.2  455.60  5030.2  454.83  5057.6  456.34  5160.4  455.69
  5198.1  457.48  5235.8  461.46  5273.5  463.51  5279.3  462.85  5301.0  463.30
  5360.4  465.88  5376.4  466.14  5382.1  465.36  5457.5  468.86  5552.9  471.20
#Mann=5,-1,0
  4652.0    0.12       0  4764.5     0.1       0  4906.7    0.12       0
  4991.0    0.07       0  4995.0    0.12       0
Bank Sta=4991,4995
Exp/Cntr=0.3,0.1

Type RM Length L Ch R = 1,3123,277,277,277
BEGIN DESCRIPTION:
Lacy 030 2990
END DESCRIPTION:
XS GIS Cut Line= 3
      2750819.86      6868049.56      2750881.37      6868419.91
      2751063.47      6868877.49
#Sta/Elev= 30
  4634.3  482.33  4646.1  482.07  4656.8  480.89  4676.3  479.59  4696.6  476.64
  4762.9  464.79  4768.0  464.88  4808.1  460.73  4836.5  458.67  4884.7  455.93
  4970.3  454.83  4990.6  452.83  4998.7  448.82  4998.9  448.32  5002.4  448.32
  5002.7  448.82  5009.7  451.33  5021.7  452.44  5066.4  453.82  5090.7  456.66
  5097.0  458.18  5120.4  460.54  5139.3  461.15  5183.1  464.08  5236.9  466.16
  5301.2  467.67  5360.5  468.60  5384.8  468.14  5438.7  468.67  5502.2  469.91
#Mann=5,-1,0
  4634.3    0.12       0  4656.8     0.1       0  4836.5    0.12       0
  4998.7    0.07       0  5002.7    0.12       0
Bank Sta=4998.7,5002.7
Exp/Cntr=0.3,0.1

Type RM Length L Ch R = 1,2846,190,190,190
BEGIN DESCRIPTION:
Lacy 030 3504
END DESCRIPTION:
XS GIS Cut Line= 3
      2750685.33      6868110.96      2750632.44      6868469.97
      2750666.32      6868955.00
#Sta/Elev= 30
  4645.8  473.59  4656.0  473.67  4686.3  471.49  4716.6  467.89  4743.0  463.02
  4748.0  463.18  4757.0  461.33  4807.6  457.25  4812.7  456.34  4837.9  455.38
  4858.1  453.47  4877.3  452.62  4928.9  452.17  4939.0  451.52  4950.0  448.22
  4950.3  447.72  4953.8  447.72  4954.0  448.22  4969.3  451.79  4999.6  452.71
  5039.8  452.96  5049.8  452.44  5089.9  454.83  5133.3  455.70  5275.2  461.69
  5330.1  465.12  5360.6  466.49  5422.1  467.70  5461.3  467.69  5494.9  468.18
#Mann=5,-1,0
  4645.8    0.12       0  4950.0    0.07       0  4954.0    0.12       0
  5330.1    0.05       0  5461.3    0.12       0
Bank Sta=4950,4954
Exp/Cntr=0.3,0.1

Type RM Length L Ch R = 1,2656,155,155,155
BEGIN DESCRIPTION:
Lacy 030 2988
END DESCRIPTION:
XS GIS Cut Line= 3
      2750454.27      6868235.54      2750444.23      6868469.10
      2750464.38      6868911.17
#Sta/Elev= 30
  4773.0  465.83  4790.0  465.56  4808.5  465.38  4846.4  463.79  4851.4  464.32
  4918.6  458.70  4938.6  455.39  4958.6  453.20  4998.7  451.27  5028.7  451.66
  5048.7  450.94  5059.7  448.98  5066.7  447.77  5067.0  447.27  5070.5  447.27
  5070.7  447.77  5078.7  449.89  5086.9  450.66  5108.8  450.51  5118.8  452.41
  5128.8  453.25  5188.9  455.30  5208.9  455.12  5218.9  455.98  5238.9  456.21
  5258.4  457.56  5289.0  458.83  5299.0  460.52  5319.0  459.97  5449.3  465.79
#Mann=7,-1,0
  4773.0    0.12       0  4790.0     0.1       0  5059.7    0.12       0
  5066.7    0.07       0  5070.7    0.12       0  5086.9     0.1       0
  5258.4    0.12       0
Bank Sta=5066.7,5070.7
Exp/Cntr=0.3,0.1

Type RM Length L Ch R = 1,2501,377,377,377
BEGIN DESCRIPTION:
Lacy 030 2987
END DESCRIPTION:
XS GIS Cut Line= 3
      2750301.94      6868252.66      2750304.53      6868509.89
      2750323.25      6868917.11
#Sta/Elev= 30
  4741.0  465.25  4789.3  464.70  4839.3  463.42  4879.3  459.90  4889.4  458.59
  4909.4  457.74  4929.4  455.43  4949.4  451.70  4959.4  450.21  4989.4  449.67
  5001.3  449.78  5009.4  450.31  5019.4  449.86  5026.0  448.65  5027.4  448.39
  5027.6  447.89  5031.1  447.89  5031.4  448.39  5059.4  451.05  5069.4  451.01
  5089.5  451.95  5099.5  451.71  5119.5  452.47  5159.5  453.03  5169.5  453.77
  5189.6  454.05  5279.7  458.53  5309.7  460.74  5320.4  460.83  5405.9  464.78
#Mann=5,-1,0
  4741.0    0.05       0  5026.0     0.1       0  5027.4    0.03       0
  5031.4     0.1       0  5320.4    0.05       0
Bank Sta=5027.4,5031.4
Exp/Cntr=0.3,0.1

Type RM Length L Ch R = 1,2124,429,429,429
BEGIN DESCRIPTION:
Lacy 030 2989
END DESCRIPTION:
XS GIS Cut Line= 3
      2750044.16      6868259.44      2749974.15      6868514.90
      2749964.52      6869096.24
#Sta/Elev= 30
  4738.7  464.09  4771.4  463.57  4802.5  461.67  4844.0  457.92  4861.9  455.64
  4867.0  455.62  4895.8  452.29  4901.5  450.91  4916.6  449.60  4958.1  448.02
  4968.4  448.72  4975.6  447.69  4980.8  447.59  4987.2  445.98  4987.4  445.48
  4990.9  445.48  4991.2  445.98  4999.0  446.98  5003.6  446.98  5009.7  448.61
  5069.7  449.03  5099.7  450.28  5119.7  450.20  5194.2  451.96  5312.1  456.64
  5379.7  458.79  5439.7  459.65  5489.7  462.64  5539.8  462.86  5585.0  464.23
#Mann=4,-1,0
  4738.7     0.1       0  4987.2    0.07       0  4991.2     0.1       0
  5312.1    0.05       0
Bank Sta=4987.2,4991.2
Exp/Cntr=0.3,0.1

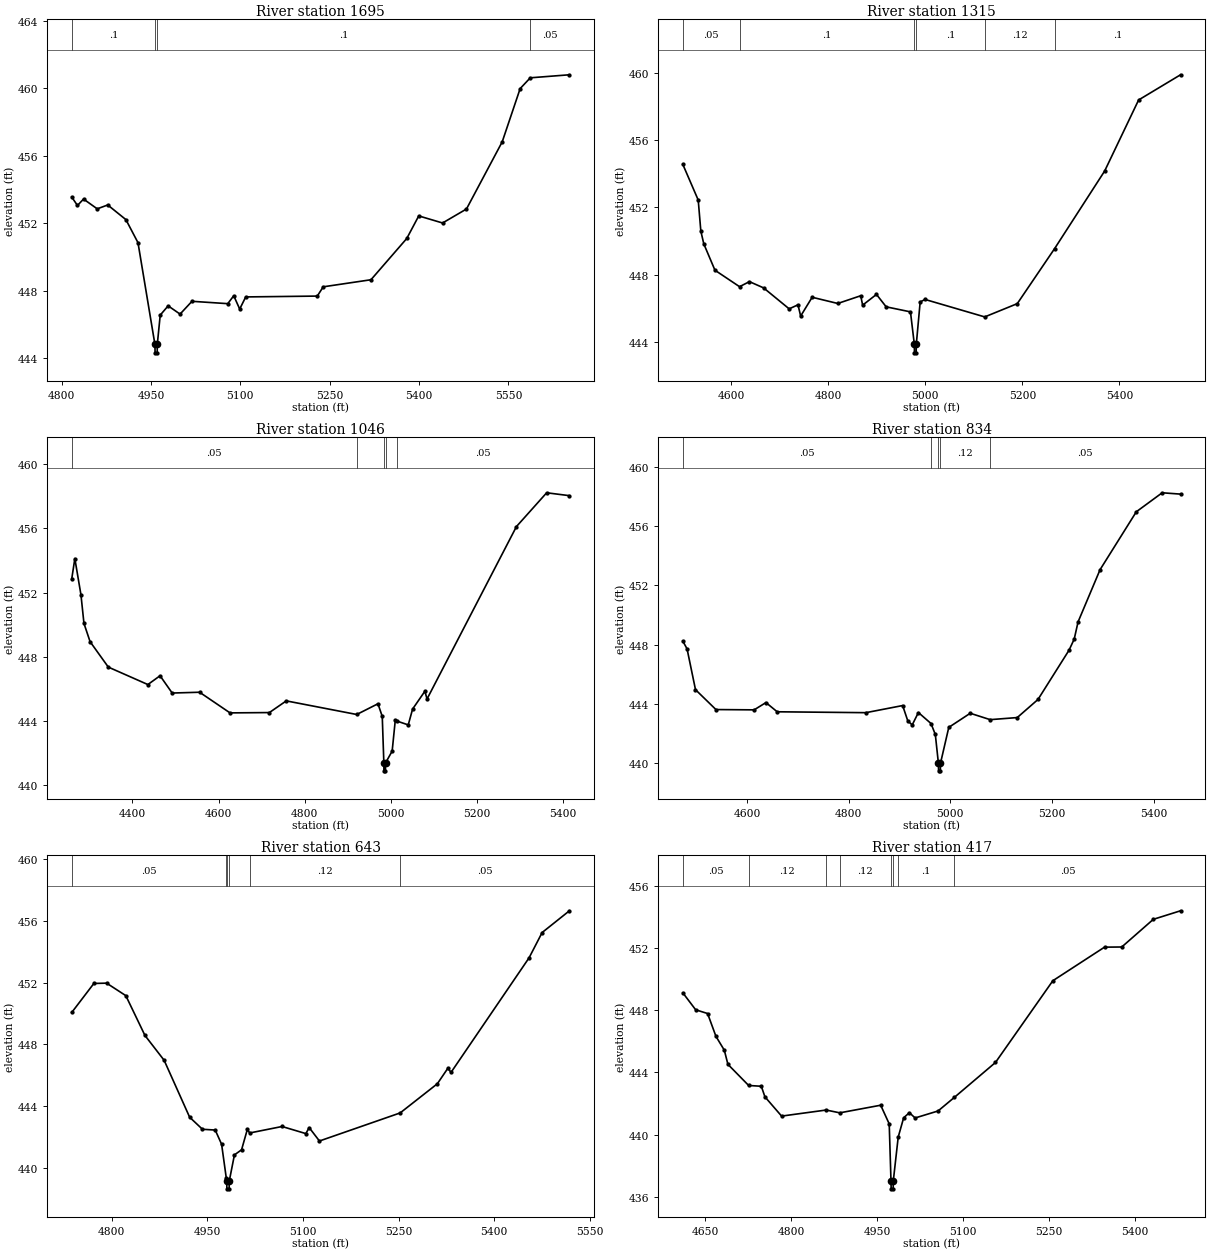
Type RM Length L Ch R = 1,1695,380,380,380
BEGIN DESCRIPTION:
Lacy 030 2986
END DESCRIPTION:
XS GIS Cut Line= 3
      2749617.96      6868311.49      2749592.06      6868459.53
      2749628.07      6869143.60
#Sta/Elev= 30
  4817.0  453.55  4826.6  453.05  4836.8  453.43  4859.8  452.85  4877.4  453.08
  4907.9  452.21  4928.2  450.84  4956.6  444.80  4956.9  444.30  4960.4  444.30
  4960.6  444.80  4965.5  446.54  4978.8  447.09  4998.8  446.60  5018.8  447.36
  5078.9  447.22  5088.9  447.69  5098.9  446.90  5109.0  447.62  5229.1  447.67
  5239.1  448.22  5319.2  448.64  5379.3  451.09  5399.4  452.43  5439.4  452.01
  5479.5  452.84  5539.5  456.83  5569.6  459.99  5586.6  460.63  5652.3  460.81
#Mann=4,-1,0
  4817.0     0.1       0  4956.6    0.07       0  4960.6     0.1       0
  5586.6    0.05       0
Bank Sta=4956.6,4960.6
Exp/Cntr=0.3,0.1

Type RM Length L Ch R = 1,1315,269,269,269
BEGIN DESCRIPTION:
Lacy 030 2985
END DESCRIPTION:
XS GIS Cut Line= 3
      2749505.18      6868241.18      2749360.41      6868583.22
      2749388.59      6869237.30
#Sta/Elev= 30
  4500.0  454.56  4531.7  452.44  4537.1  450.59  4543.2  449.83  4566.2  448.26
  4616.9  447.28  4637.3  447.58  4666.4  447.21  4719.2  445.96  4737.4  446.20
  4742.9  445.53  4766.6  446.65  4819.4  446.28  4866.7  446.74  4870.7  446.18
  4899.2  446.82  4919.2  446.08  4969.3  445.78  4977.3  443.84  4977.5  443.34
  4981.0  443.34  4981.3  443.84  4989.3  446.37  4999.3  446.52  5122.4  445.48
  5189.5  446.27  5266.3  449.54  5369.7  454.17  5439.7  458.40  5526.1  459.90
#Mann=6,-1,0
  4500.0    0.05       0  4616.9     0.1       0  4977.3    0.07       0
  4981.3     0.1       0  5122.4    0.12       0  5266.3     0.1       0
Bank Sta=4977.3,4981.3
Exp/Cntr=0.3,0.1

Type RM Length L Ch R = 1,1046,212,212,212
BEGIN DESCRIPTION:
Lacy 030 3503
END DESCRIPTION:
XS GIS Cut Line= 4
      2749500.74      6868235.56      2749225.93      6868512.66
      2749178.78      6868863.71      2749138.49      6869273.67
#Sta/Elev= 30
  4258.9  452.85  4266.1  454.12  4280.3  451.86  4287.3  450.07  4301.5  448.93
  4343.9  447.34  4435.8  446.25  4464.1  446.80  4492.3  445.72  4556.0  445.77
  4626.7  444.48  4718.1  444.50  4757.4  445.23  4921.1  444.38  4970.4  445.05
  4980.4  444.26  4984.1  441.36  4984.3  440.86  4987.8  440.86  4988.1  441.36
  5003.4  442.09  5010.7  444.03  5014.4  443.97  5040.8  443.73  5050.9  444.72
  5079.4  445.83  5084.5  445.35  5292.2  456.12  5362.4  458.23  5415.3  458.05
#Mann=5,-1,0
  4258.9    0.05       0  4921.1    0.12       0  4984.1    0.07       0
  4988.1    0.12       0  5014.4    0.05       0
Bank Sta=4984.1,4988.1
Exp/Cntr=0.3,0.1

Type RM Length L Ch R = 1,834,191,191,191
BEGIN DESCRIPTION:
Lacy 030 2997
END DESCRIPTION:
XS GIS Cut Line= 3
      2749117.67      6868302.98      2748982.71      6868811.57
      2749068.88      6869256.41
#Sta/Elev= 30
  4473.8  448.24  4482.1  447.72  4498.7  444.97  4538.9  443.63  4614.1  443.61
  4637.3  444.10  4659.5  443.48  4833.9  443.42  4906.3  443.90  4916.6  442.85
  4925.2  442.60  4937.3  443.43  4962.1  442.69  4970.6  441.95  4976.7  440.00
  4977.0  439.50  4980.5  439.50  4980.7  440.00  4997.1  442.43  5039.3  443.38
  5078.5  442.95  5131.8  443.09  5172.6  444.31  5233.7  447.63  5243.9  448.38
  5251.5  449.54  5294.8  453.06  5366.1  456.96  5417.0  458.24  5453.1  458.15
#Mann=5,-1,0
  4473.8    0.05       0  4962.1    0.12       0  4976.7    0.07       0
  4980.7    0.12       0  5078.5    0.05       0
Bank Sta=4976.7,4980.7
Exp/Cntr=0.3,0.1

Type RM Length L Ch R = 1,643,226,226,226
BEGIN DESCRIPTION:
Lacy 030 2976
END DESCRIPTION:
XS GIS Cut Line= 3
      2748841.65      6868456.39      2748826.10      6868718.33
      2748944.29      6869222.66
#Sta/Elev= 30
  4737.6  450.06  4772.3  451.94  4792.3  451.96  4822.4  451.15  4852.4  448.57
  4882.5  446.96  4922.5  443.27  4942.6  442.49  4962.6  442.44  4972.6  441.52
  4980.0  439.31  4980.6  439.13  4980.9  438.63  4984.4  438.63  4984.6  439.13
  4992.7  440.83  5003.9  441.16  5013.0  442.49  5016.6  442.25  5067.4  442.67
  5104.7  442.21  5109.9  442.60  5126.0  441.73  5252.6  443.55  5310.9  445.44
  5327.3  446.44  5332.4  446.18  5454.7  453.60  5475.2  455.24  5518.0  456.65
#Mann=6,-1,0
  4737.6    0.05       0  4980.0     0.1       0  4980.6    0.07       0
  4984.6     0.1       0  5016.6    0.12       0  5252.6    0.05       0
Bank Sta=4980.6,4984.6
Exp/Cntr=0.3,0.1

Type RM Length L Ch R = 1,417,0,0,0
BEGIN DESCRIPTION:
Lacy 030 3505
END DESCRIPTION:
XS GIS Cut Line= 3
      2748794.43      6868468.06      2748637.38      6868677.83
      2748597.92      6869283.40
#Sta/Elev= 30
  4610.7  449.12  4633.1  448.03  4653.9  447.79  4668.5  446.32  4683.1  445.43
  4689.4  444.52  4725.6  443.16  4747.7  443.11  4754.0  442.43  4783.1  441.19
  4860.9  441.58  4884.7  441.40  4956.1  441.89  4971.0  440.69  4974.1  437.01
  4974.4  436.51  4977.9  436.51  4978.1  437.01  4986.7  439.84  4996.2  441.08
  5006.2  441.41  5016.2  441.07  5056.3  441.52  5084.6  442.39  5156.5  444.64
  5256.7  449.90  5346.9  452.06  5377.0  452.07  5432.1  453.85  5479.6  454.40
#Mann=8,-1,0
  4610.7    0.05       0  4725.6    0.12       0  4860.9     0.1       0
  4884.7    0.12       0  4974.1    0.07       0  4978.1    0.12       0
  4986.7     0.1       0  5084.6    0.05       0
Bank Sta=4974.1,4978.1
Exp/Cntr=0.3,0.1

Chan Stop Cuts=-1