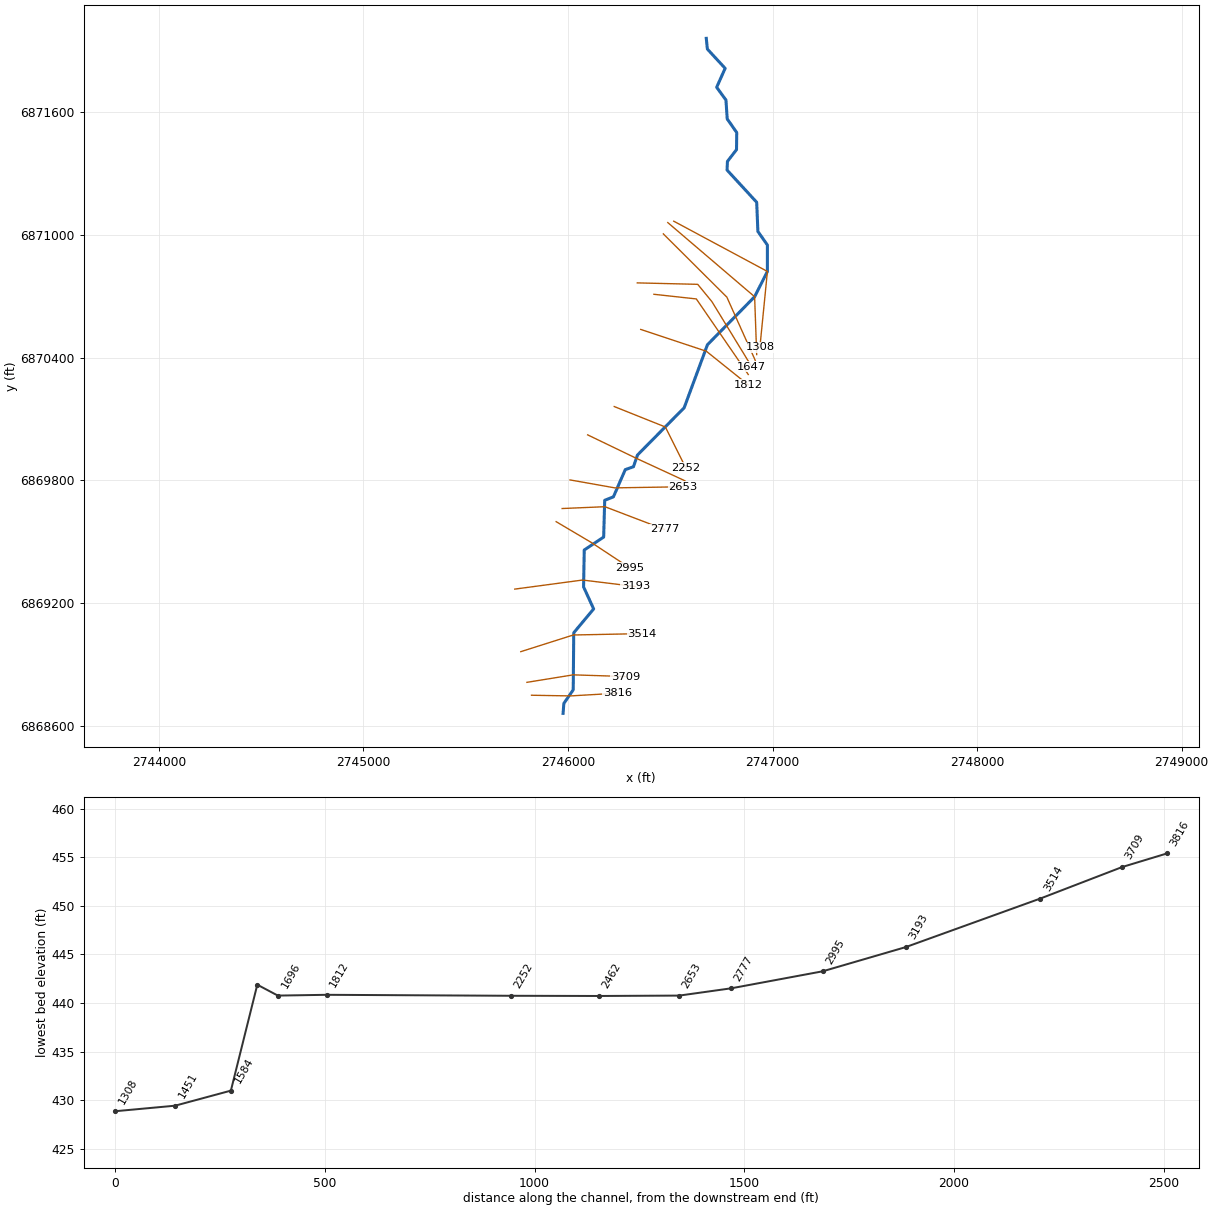
--- Lacy 031.prj (project) ---

Proj Title=Lacy 031 Base Level Engineering
Current Plan=p01
Default Exp/Contr=0.3,0.1
English Units
Geom File=g01
Flow File=f01
Plan File=p01
BEGIN DESCRIPTION:
Lacy 031
END DESCRIPTION:

--- Lacy 031.p01 (plan) ---

Plan Title=Multiple Run
Short Identifier=Multiple
Geom File=g01
Flow File=f01
Subcritical Flow
K Sum by GR= 0
Std Step Tol= 0.01
Critical Tol= 0.01
Num of Std Step Trials= 20
Max Error Tol= 0.3
Flow Tol Ratio= 0.001
Split Flow NTrial= 30
Split Flow Tol= 0.02
Split Flow Ratio= 0.02
Log Output Level= 0
Friction Slope Method= 1
Unsteady Friction Slope Method= 2
Unsteady Bridges Friction Slope Method= 1
Parabolic Critical Depth
Global Vel Dist=  1 , 1 , 1
Global Log Level= 0
CheckData=True
Encroach Param= -1, 0, 0, 0
BEGIN DESCRIPTION:
Multiple Run
END DESCRIPTION:

--- Lacy 031.f01 (steady flow) ---

Flow Title=Multiple
Number of Profiles=7
Profile Names=10-year,25-year,50-year,1pct_min,100-year,1pct_plu,500-year
River Rch & RM= Lacy 031,Reach-1,3816
     192     240     275     158     316     630     413
Boundary for River Rch & Prof#=Lacy 031,Reach-1,1
Up Type=0
Dn Type=3
Dn Slope=0.005
Boundary for River Rch & Prof#=Lacy 031,Reach-1,2
Up Type=0
Dn Type=3
Dn Slope=0.005
Boundary for River Rch & Prof#=Lacy 031,Reach-1,3
Up Type=0
Dn Type=3
Dn Slope=0.005
Boundary for River Rch & Prof#=Lacy 031,Reach-1,4
Up Type=0
Dn Type=3
Dn Slope=0.005
Boundary for River Rch & Prof#=Lacy 031,Reach-1,5
Up Type=0
Dn Type=3
Dn Slope=0.005
Boundary for River Rch & Prof#=Lacy 031,Reach-1,6
Up Type=0
Dn Type=3
Dn Slope=0.005
Boundary for River Rch & Prof#=Lacy 031,Reach-1,7
Up Type=0
Dn Type=3
Dn Slope=0.005

--- Lacy 031.g01 (geometry) ---

Geom Title=Existing Conditions

River Reach=Lacy 031,Reach-1
Reach XY= 30
      2745976.00      6868661.00      2745979.65      6868709.49
      2746025.55      6868776.19      2746028.07      6869055.14
      2746125.43      6869171.61      2746076.14      6869279.19
      2746079.44      6869459.76      2746174.35      6869522.84
      2746179.40      6869702.56      2746222.09      6869719.65
      2746279.84      6869852.38      2746320.01      6869866.77
      2746339.69      6869924.00      2746567.86      6870154.94
      2746681.83      6870463.30      2746912.38      6870697.78
      2746974.81      6870821.50      2746974.79      6870950.49
      2746928.27      6871016.94      2746922.46      6871159.53
      2746777.62      6871317.03      2746779.34      6871359.25
      2746823.81      6871416.97      2746824.90      6871500.45
      2746778.36      6871566.97      2746772.11      6871659.42
      2746726.82      6871721.71      2746768.19      6871814.41
      2746681.35      6871908.48      2746676.00      6871961.00

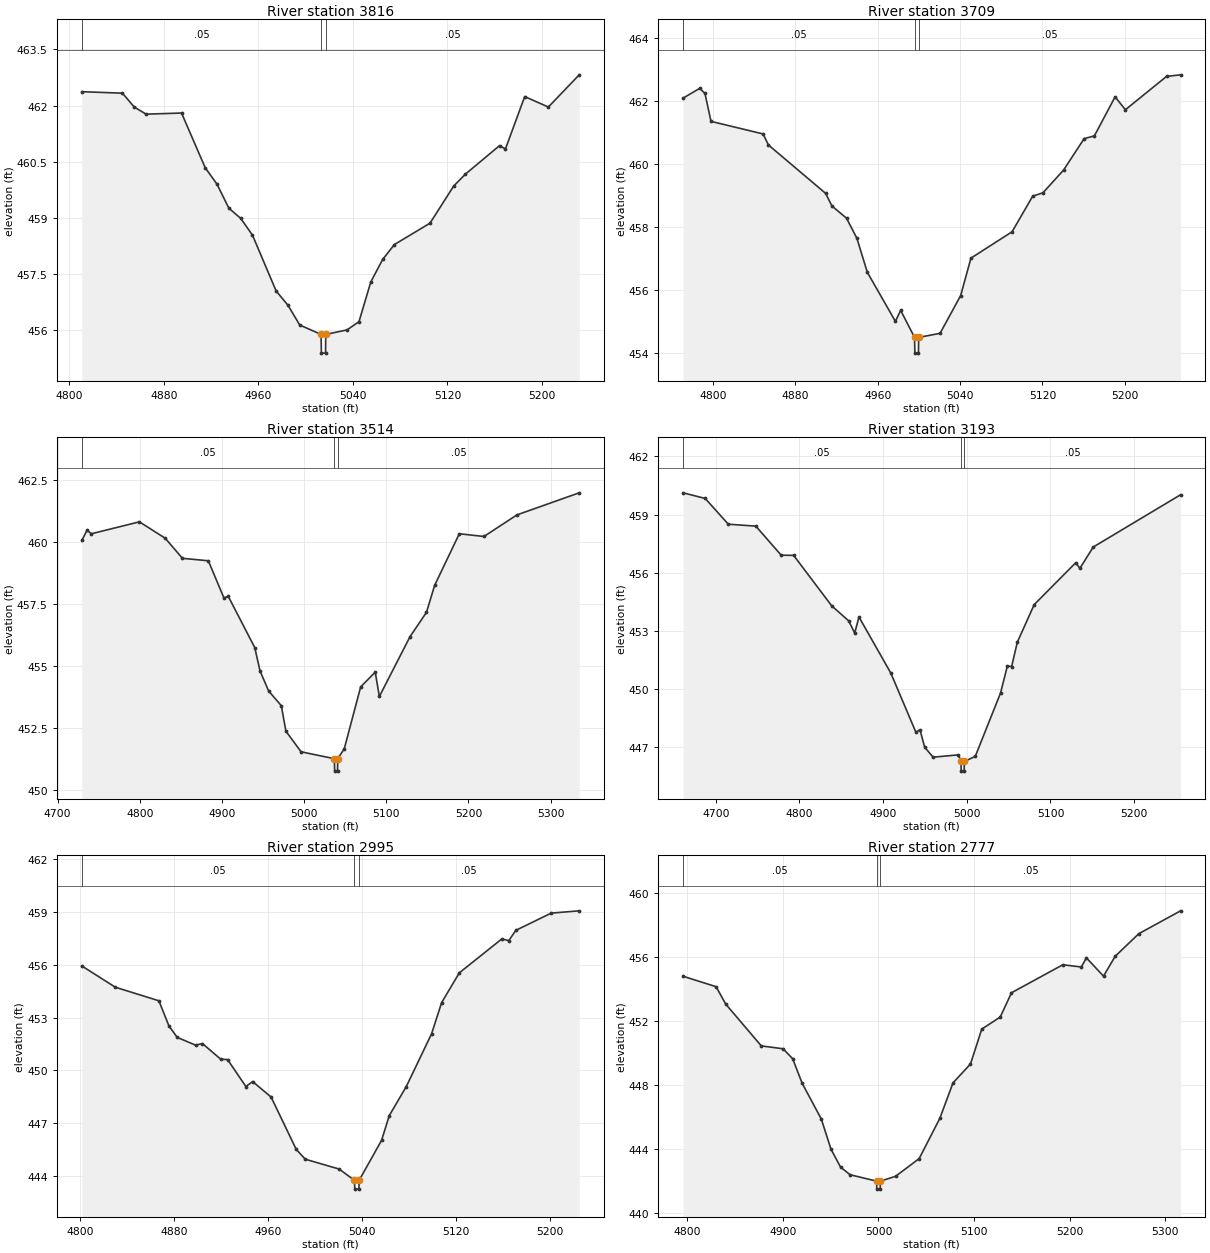
Type RM Length L Ch R = 1,3816,107,107,107
BEGIN DESCRIPTION:
Lacy 031 2967
END DESCRIPTION:
XS GIS Cut Line= 3
      2745821.64      6868749.63      2746012.01      6868746.34
      2746242.03      6868759.69
#Sta/Elev= 30
  4810.7  462.37  4845.1  462.33  4855.1  461.96  4865.1  461.77  4895.1  461.80
  4915.1  460.34  4925.1  459.90  4935.1  459.26  4945.1  458.99  4955.1  458.54
  4975.1  457.05  4985.1  456.67  4995.1  456.14  5013.1  455.89  5013.4  455.39
  5016.9  455.39  5017.1  455.89  5035.1  456.01  5045.2  456.23  5055.2  457.29
  5065.2  457.89  5075.2  458.29  5105.3  458.86  5125.3  459.85  5135.3  460.17
  5164.1  460.93  5169.1  460.84  5185.4  462.24  5205.4  461.96  5231.5  462.82
#Mann=3,-1,0
  4810.7    0.05       0  5013.1    0.04       0  5017.1    0.05       0
Bank Sta=5013.1,5017.1
Exp/Cntr=0.3,0.1

Type RM Length L Ch R = 1,3709,195,195,195
BEGIN DESCRIPTION:
Lacy 031 2966
END DESCRIPTION:
XS GIS Cut Line= 3
      2745799.28      6868812.74      2746025.54      6868849.33
      2746279.61      6868841.16
#Sta/Elev= 30
  4770.8  462.10  4786.9  462.41  4792.0  462.25  4797.9  461.36  4848.5  460.96
  4853.7  460.61  4909.3  459.07  4915.4  458.67  4929.6  458.28  4939.7  457.64
  4949.8  456.56  4977.1  455.00  4982.2  455.35  4995.7  454.49  4996.0  453.99
  4999.5  453.99  4999.7  454.49  5020.5  454.62  5040.5  455.82  5050.5  457.01
  5090.5  457.85  5110.5  458.98  5120.5  459.09  5140.5  459.81  5160.5  460.81
  5170.5  460.90  5190.6  462.14  5200.6  461.73  5240.6  462.79  5254.2  462.84
#Mann=3,-1,0
  4770.8    0.05       0  4995.7    0.04       0  4999.7    0.05       0
Bank Sta=4995.7,4999.7
Exp/Cntr=0.3,0.1

Type RM Length L Ch R = 1,3514,321,321,321
BEGIN DESCRIPTION:
Lacy 031 2961
END DESCRIPTION:
XS GIS Cut Line= 3
      2745769.22      6868962.68      2746025.96      6869044.18
      2746361.83      6869050.95
#Sta/Elev= 30
  4729.5  460.05  4735.9  460.46  4741.2  460.32  4799.6  460.80  4831.0  460.14
  4852.0  459.33  4883.5  459.23  4902.5  457.73  4907.7  457.80  4940.0  455.73
  4946.4  454.79  4956.9  453.98  4972.3  453.39  4977.9  452.36  4996.3  451.53
  5036.9  451.25  5037.2  450.75  5040.7  450.75  5040.9  451.25  5048.9  451.65
  5068.9  454.15  5086.6  454.74  5091.6  453.76  5128.9  456.17  5148.9  457.15
  5158.9  458.24  5188.9  460.32  5218.9  460.21  5259.0  461.08  5334.8  461.97
#Mann=3,-1,0
  4729.5    0.05       0  5036.9    0.04       0  5040.9    0.05       0
Bank Sta=5036.9,5040.9
Exp/Cntr=0.3,0.1

Type RM Length L Ch R = 1,3193,198,198,198
BEGIN DESCRIPTION:
Lacy 031 2960
END DESCRIPTION:
XS GIS Cut Line= 3
      2745739.88      6869268.51      2746071.25      6869312.83
      2746329.62      6869281.36
#Sta/Elev= 30
  4660.9  460.12  4687.3  459.83  4714.9  458.50  4747.8  458.40  4778.1  456.90
  4793.0  456.89  4838.6  454.28  4858.8  453.51  4866.0  452.88  4871.1  453.71
  4909.2  450.81  4939.1  447.76  4944.1  447.88  4949.6  446.99  4959.7  446.47
  4989.9  446.59  4993.1  446.25  4993.3  445.75  4996.8  445.75  4997.1  446.25
  5010.1  446.51  5040.3  449.78  5048.5  451.18  5053.6  451.15  5060.4  452.41
  5080.6  454.35  5130.2  456.51  5135.2  456.22  5151.1  457.32  5255.5  460.02
#Mann=3,-1,0
  4660.9    0.05       0  4993.1    0.04       0  4997.1    0.05       0
Bank Sta=4993.1,4997.1
Exp/Cntr=0.3,0.1

Type RM Length L Ch R = 1,2995,218,218,218
BEGIN DESCRIPTION:
Lacy 031 2959
END DESCRIPTION:
XS GIS Cut Line= 3
      2745942.17      6869598.10      2746113.07      6869496.97
      2746301.02      6869372.87
#Sta/Elev= 30
  4801.3  455.94  4829.9  454.73  4867.0  453.96  4875.5  452.54  4882.6  451.88
  4898.2  451.44  4904.1  451.53  4919.7  450.64  4925.5  450.62  4941.1  449.09
  4946.9  449.37  4962.6  448.49  4984.0  445.52  4991.7  444.96  5020.6  444.40
  5033.6  443.76  5033.9  443.26  5037.4  443.26  5037.6  443.76  5056.7  446.03
  5063.3  447.44  5077.8  449.09  5099.3  452.08  5107.9  453.86  5123.0  455.55
  5159.1  457.47  5165.1  457.38  5171.1  457.96  5201.2  458.94  5225.1  459.07
#Mann=3,-1,0
  4801.3    0.05       0  5033.6    0.04       0  5037.6    0.05       0
Bank Sta=5033.6,5037.6
Exp/Cntr=0.3,0.1

Type RM Length L Ch R = 1,2777,124,124,124
BEGIN DESCRIPTION:
Lacy 031 2958
END DESCRIPTION:
XS GIS Cut Line= 3
      2745971.48      6869662.42      2746180.44      6869671.33
      2746471.29      6869560.22
#Sta/Elev= 30
  4795.6  454.81  4830.1  454.16  4840.2  453.07  4877.4  450.46  4900.2  450.28
  4910.2  449.66  4920.2  448.12  4940.2  445.89  4950.3  444.01  4960.3  442.89
  4970.3  442.41  4998.0  442.01  4998.3  441.51  5001.8  441.51  5002.0  442.01
  5017.9  442.31  5042.6  443.42  5064.2  445.93  5078.0  448.15  5096.3  449.33
  5108.1  451.51  5127.4  452.26  5139.2  453.78  5192.9  455.53  5212.3  455.39
  5217.6  455.96  5235.5  454.82  5247.7  456.06  5272.4  457.47  5316.1  458.90
#Mann=3,-1,0
  4795.6    0.05       0  4998.0    0.04       0  5002.0    0.05       0
Bank Sta=4998,5002
Exp/Cntr=0.3,0.1

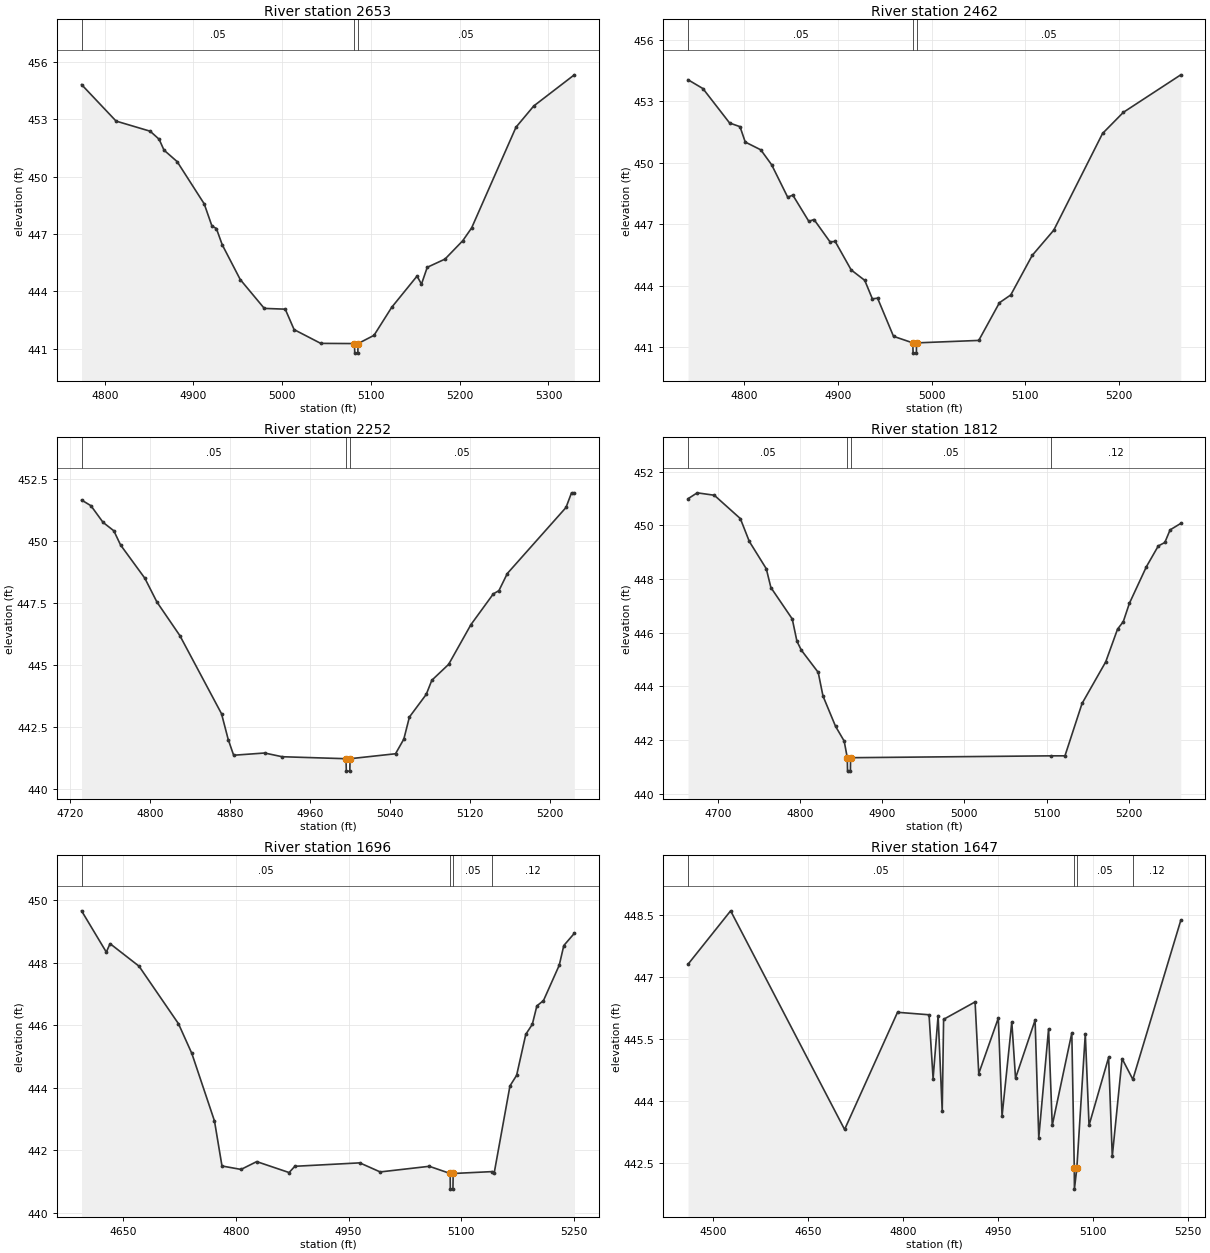
Type RM Length L Ch R = 1,2653,191,191,191
BEGIN DESCRIPTION:
Lacy 031 2956
END DESCRIPTION:
XS GIS Cut Line= 3
      2746009.94      6869802.32      2746228.86      6869763.42
      2746561.66      6869768.82
#Sta/Elev= 30
  4773.9  454.81  4812.8  452.90  4851.2  452.37  4861.3  451.95  4866.8  451.38
  4881.6  450.78  4912.1  448.57  4920.8  447.41  4925.8  447.28  4932.4  446.43
  4952.7  444.61  4979.8  443.10  5003.4  443.06  5013.4  441.99  5043.4  441.27
  5081.4  441.26  5081.7  440.76  5085.2  440.76  5085.4  441.26  5103.4  441.69
  5123.4  443.16  5151.9  444.79  5156.9  444.37  5163.4  445.25  5183.4  445.68
  5203.4  446.64  5213.4  447.31  5263.4  452.58  5283.4  453.69  5329.1  455.32
#Mann=3,-1,0
  4773.9    0.05       0  5081.4    0.04       0  5085.4    0.05       0
Bank Sta=5081.4,5085.4
Exp/Cntr=0.3,0.1

Type RM Length L Ch R = 1,2462,210,210,210
BEGIN DESCRIPTION:
Lacy 031 2957
END DESCRIPTION:
XS GIS Cut Line= 3
      2746096.04      6870022.59      2746332.15      6869908.77
      2746571.79      6869798.03
#Sta/Elev= 30
  4739.8  454.06  4755.7  453.63  4784.2  451.95  4795.3  451.77  4800.9  451.02
  4817.5  450.64  4829.1  449.91  4846.2  448.33  4851.7  448.43  4868.8  447.15
  4874.3  447.24  4891.4  446.15  4896.9  446.17  4914.0  444.78  4928.5  444.27
  4936.6  443.37  4942.2  443.40  4959.2  441.54  4979.8  441.22  4980.1  440.72
  4983.6  440.72  4983.8  441.22  5050.2  441.34  5072.3  443.18  5084.4  443.56
  5107.3  445.49  5130.3  446.72  5182.4  451.44  5204.6  452.47  5265.9  454.30
#Mann=3,-1,0
  4739.8    0.05       0  4979.8    0.04       0  4983.8    0.05       0
Bank Sta=4979.8,4983.8
Exp/Cntr=0.3,0.1

Type RM Length L Ch R = 1,2252,440,440,440
BEGIN DESCRIPTION:
Lacy 031 72
END DESCRIPTION:
XS GIS Cut Line= 3
      2746226.02      6870160.99      2746476.00      6870061.00
      2746575.98      6869861.04
#Sta/Elev= 30
  4731.5  451.66  4740.9  451.43  4753.0  450.76  4763.8  450.42  4770.5  449.85
  4794.8  448.51  4806.9  447.55  4829.8  446.20  4871.5  443.05  4878.2  442.01
  4883.6  441.38  4914.6  441.47  4932.1  441.32  4996.0  441.24  4996.3  440.74
  4999.8  440.74  5000.0  441.24  5045.5  441.44  5053.8  442.03  5059.4  442.92
  5076.2  443.83  5081.8  444.40  5098.6  445.04  5120.9  446.64  5143.3  447.88
  5148.9  448.01  5157.3  448.70  5216.0  451.36  5221.5  451.95  5224.3  451.95
#Mann=3,-1,0
  4731.5    0.05       0  4996.0    0.03       0  5000.0    0.05       0
Bank Sta=4996,5000
Exp/Cntr=0.3,0.1

Type RM Length L Ch R = 1,1812,116,116,116
BEGIN DESCRIPTION:
Lacy 031 2955
END DESCRIPTION:
XS GIS Cut Line= 3
      2746355.59      6870537.97      2746676.26      6870431.38
      2746880.59      6870267.41
#Sta/Elev= 30
  4663.5  450.99  4674.7  451.21  4695.5  451.12  4727.2  450.25  4738.1  449.40
  4758.8  448.38  4764.4  447.68  4790.4  446.51  4796.1  445.68  4801.4  445.35
  4822.0  444.52  4827.8  443.64  4843.1  442.51  4853.6  441.96  4857.4  441.34
  4857.7  440.84  4861.2  440.84  4861.4  441.34  5105.7  441.41  5122.4  441.41
  5143.2  443.36  5172.0  444.91  5186.4  446.13  5193.4  446.41  5200.8  447.09
  5221.6  448.46  5236.0  449.23  5244.0  449.36  5250.4  449.83  5263.4  450.07
#Mann=4,-1,0
  4663.5    0.05       0  4857.4    0.03       0  4861.4    0.05       0
  5105.7    0.12       0
Bank Sta=4857.4,4861.4
Exp/Cntr=0.3,0.1

Type RM Length L Ch R = 1,1696,49,49,49
BEGIN DESCRIPTION:
Lacy 031 2965
END DESCRIPTION:
XS GIS Cut Line= 3
      2746419.89      6870709.78      2746627.37      6870687.05
      2746881.16      6870317.66
#Sta/Elev= 30
  4594.1  449.66  4627.1  448.34  4632.1  448.61  4670.7  447.89  4723.3  446.05
  4741.1  445.10  4771.3  442.94  4781.3  441.50  4806.7  441.39  4827.6  441.64
  4870.8  441.29  4878.4  441.49  4965.0  441.60  4992.2  441.31  5057.7  441.49
  5085.5  441.26  5085.7  440.76  5089.2  440.76  5089.5  441.26  5141.3  441.32
  5144.3  441.29  5165.2  444.06  5174.1  444.40  5186.3  445.71  5195.0  446.03
  5201.1  446.62  5209.9  446.79  5230.9  447.92  5237.0  448.55  5251.0  448.94
#Mann=4,-1,0
  4594.1    0.05       0  5085.5    0.03       0  5089.5    0.05       0
  5141.3    0.12       0
Bank Sta=5085.5,5089.5
Exp/Cntr=0.3,0.1

Type RM Length L Ch R = 1,1647,63,63,63
BEGIN DESCRIPTION:
Lacy 031 2964
END DESCRIPTION:
XS GIS Cut Line= 4
      2746338.74      6870765.51      2746634.15      6870758.40
      2746703.79      6870673.49      2746898.37      6870355.28
#Sta/Elev= 30
  4460.7  447.31  4528.0  448.60  4708.0  443.32  4791.6  446.15  4841.4  446.09
  4847.8  444.55  4855.7  446.07  4862.2  443.76  4864.4  445.98  4914.1  446.40
  4919.9  444.67  4950.8  446.01  4956.7  443.64  4972.1  445.92  4978.0  444.56
  5008.9  445.96  5014.7  443.12  5030.2  445.75  5036.0  443.42  5066.9  445.65
  5070.8  442.38  5071.0  441.88  5074.8  442.38  5088.2  445.63  5094.1  443.42
  5125.0  445.06  5130.8  442.67  5146.3  445.03  5163.3  444.53  5239.0  448.37
#Mann=4,-1,0
  4460.7    0.05       0  5070.8    0.03       0  5074.8    0.05       0
  5163.3    0.12       0
Bank Sta=5070.8,5074.8
Exp/Cntr=0.3,0.1

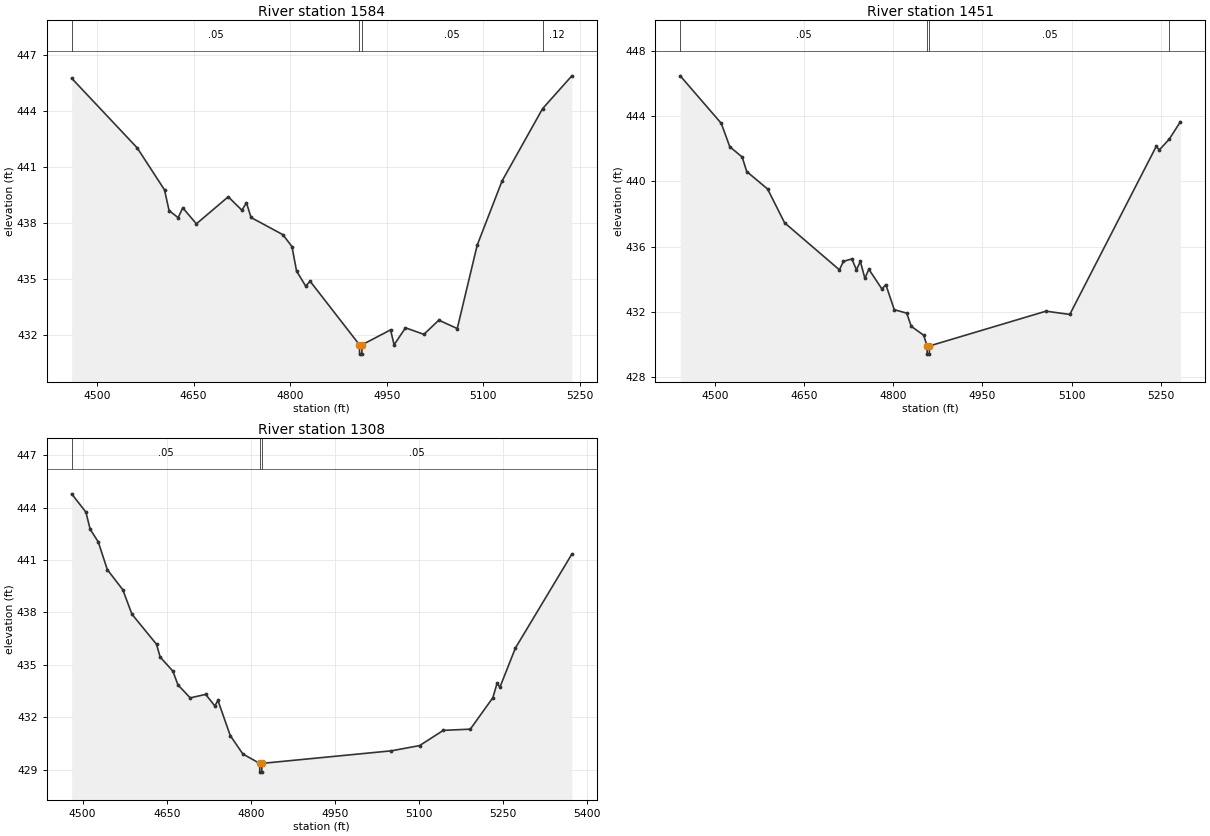
Type RM Length L Ch R = 1,1584,133,133,133
BEGIN DESCRIPTION:
Lacy 031 2963
END DESCRIPTION:
XS GIS Cut Line= 3
      2746466.03      6871004.99      2746776.64      6870695.75
      2746915.40      6870386.89
#Sta/Elev= 30
  4460.6  445.76  4562.4  442.03  4604.8  439.78  4611.9  438.67  4626.0  438.29
  4633.1  438.82  4654.3  437.96  4703.8  439.41  4725.0  438.69  4732.1  439.09
  4739.2  438.30  4788.7  437.38  4802.8  436.74  4809.9  435.43  4824.0  434.63
  4831.1  434.88  4907.6  431.48  4907.8  430.98  4911.3  430.98  4911.6  431.48
  4955.9  432.28  4961.4  431.48  4979.1  432.39  5007.7  432.04  5030.9  432.80
  5059.5  432.35  5090.5  436.82  5129.0  440.25  5192.0  444.13  5237.5  445.89
#Mann=4,-1,0
  4460.6    0.05       0  4907.6    0.04       0  4911.6    0.05       0
  5192.0    0.12       0
Bank Sta=4907.6,4911.6
Exp/Cntr=0.3,0.1

Type RM Length L Ch R = 1,1451,143,143,143
BEGIN DESCRIPTION:
Lacy 031 2962
END DESCRIPTION:
XS GIS Cut Line= 3
      2746487.86      6871060.23      2746912.38      6870697.78
      2746922.43      6870415.16
#Sta/Elev= 30
  4441.8  446.47  4510.8  443.56  4525.1  442.13  4545.9  441.50  4553.6  440.61
  4588.7  439.54  4617.3  437.47  4709.5  434.59  4716.1  435.11  4730.4  435.26
  4738.1  434.59  4744.6  435.11  4752.3  434.07  4758.9  434.63  4780.9  433.42
  4787.5  433.69  4801.7  432.15  4822.6  431.94  4830.3  431.13  4851.1  430.59
  4856.8  429.93  4857.1  429.43  4860.6  429.43  4860.8  429.93  5056.8  432.06
  5096.8  431.86  5242.3  442.16  5247.3  441.93  5264.0  442.59  5282.8  443.66
#Mann=4,-1,0
  4441.8    0.05       0  4856.8    0.04       0  4860.8    0.05       0
  5264.0    0.12       0
Bank Sta=4856.8,4860.8
Exp/Cntr=0.3,0.1

Type RM Length L Ch R = 1,1308,0,0,0
BEGIN DESCRIPTION:
Lacy 031
END DESCRIPTION:
XS GIS Cut Line= 3
      2746516.95      6871067.15      2746974.81      6870821.50
      2746938.10      6870450.82
#Sta/Elev= 30
  4480.4  444.79  4505.8  443.74  4513.4  442.76  4527.8  442.04  4544.0  440.45
  4571.6  439.30  4587.9  437.90  4631.7  436.18  4638.2  435.45  4660.9  434.64
  4669.9  433.86  4691.8  433.11  4719.4  433.31  4735.7  432.65  4741.3  432.96
  4763.3  430.95  4785.7  429.90  4815.7  429.36  4815.9  428.86  4819.4  428.86
  4819.7  429.36  5050.7  430.08  5101.0  430.38  5143.2  431.25  5191.4  431.32
  5231.6  433.12  5239.1  433.94  5244.2  433.72  5271.8  435.96  5372.5  441.34
#Mann=3,-1,0
  4480.4    0.05       0  4815.7    0.04       0  4819.7    0.05       0
Bank Sta=4815.7,4819.7
Exp/Cntr=0.3,0.1

Chan Stop Cuts=-1