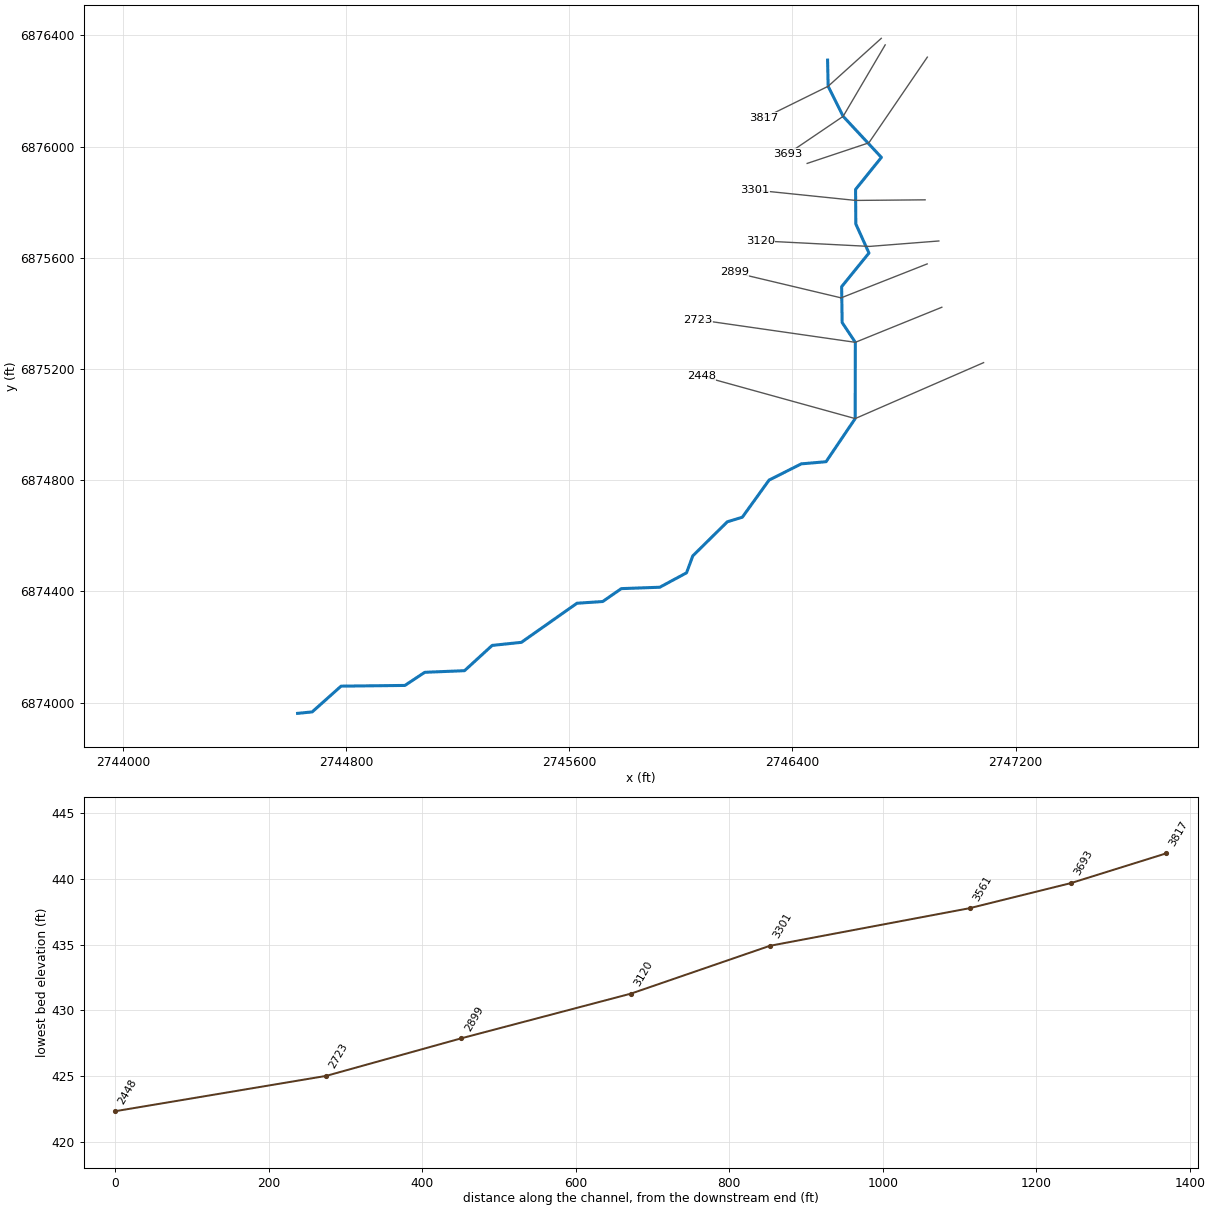
--- Lacy 033.prj (project) ---

Proj Title=Lacy 033 Base Level Engineering
Current Plan=p01
Default Exp/Contr=0.3,0.1
English Units
Geom File=g01
Flow File=f01
Plan File=p01
BEGIN DESCRIPTION:
Lacy 033
END DESCRIPTION:

--- Lacy 033.p01 (plan) ---

Plan Title=Multiple Run
Short Identifier=Multiple
Geom File=g01
Flow File=f01
Subcritical Flow
K Sum by GR= 0
Std Step Tol= 0.01
Critical Tol= 0.01
Num of Std Step Trials= 20
Max Error Tol= 0.3
Flow Tol Ratio= 0.001
Split Flow NTrial= 30
Split Flow Tol= 0.02
Split Flow Ratio= 0.02
Log Output Level= 0
Friction Slope Method= 1
Unsteady Friction Slope Method= 2
Unsteady Bridges Friction Slope Method= 1
Parabolic Critical Depth
Global Vel Dist=  1 , 1 , 1
Global Log Level= 0
CheckData=True
Encroach Param= -1, 0, 0, 0
BEGIN DESCRIPTION:
Multiple Run
END DESCRIPTION:

--- Lacy 033.f01 (steady flow) ---

Flow Title=Multiple
Number of Profiles=7
Profile Names=10-year,25-year,50-year,1pct_min,100-year,1pct_plu,500-year
River Rch & RM= Lacy 033,Reach-1,3817
     122     147     165      93     185     370     233
Boundary for River Rch & Prof#=Lacy 033,Reach-1,1
Up Type=0
Dn Type=3
Dn Slope=0.005
Boundary for River Rch & Prof#=Lacy 033,Reach-1,2
Up Type=0
Dn Type=3
Dn Slope=0.005
Boundary for River Rch & Prof#=Lacy 033,Reach-1,3
Up Type=0
Dn Type=3
Dn Slope=0.005
Boundary for River Rch & Prof#=Lacy 033,Reach-1,4
Up Type=0
Dn Type=3
Dn Slope=0.005
Boundary for River Rch & Prof#=Lacy 033,Reach-1,5
Up Type=0
Dn Type=3
Dn Slope=0.005
Boundary for River Rch & Prof#=Lacy 033,Reach-1,6
Up Type=0
Dn Type=3
Dn Slope=0.005
Boundary for River Rch & Prof#=Lacy 033,Reach-1,7
Up Type=0
Dn Type=3
Dn Slope=0.005

--- Lacy 033.g01 (geometry) ---

Geom Title=Existing Conditions

River Reach=Lacy 033,Reach-1
Reach XY= 30
      2746526.00      6876311.00      2746528.07      6876216.86
      2746581.83      6876108.70      2746718.92      6875961.00
      2746626.38      6875845.84      2746627.23      6875721.50
      2746674.37      6875617.04      2746576.37      6875495.83
      2746578.25      6875366.94      2746625.48      6875295.78
      2746624.95      6875021.44      2746520.53      6874866.26
      2746432.05      6874858.63      2746316.30      6874800.24
      2746220.38      6874666.62      2746166.58      6874650.11
      2746042.73      6874527.48      2746020.39      6874466.59
      2745924.47      6874414.74      2745786.51      6874409.77
      2745720.02      6874363.36      2745627.58      6874357.17
      2745428.42      6874216.54      2745323.58      6874205.46
      2745224.53      6874114.56      2745081.94      6874108.73
      2745010.78      6874061.52      2744781.85      6874058.94
      2744678.51      6873966.33      2744626.00      6873961.00

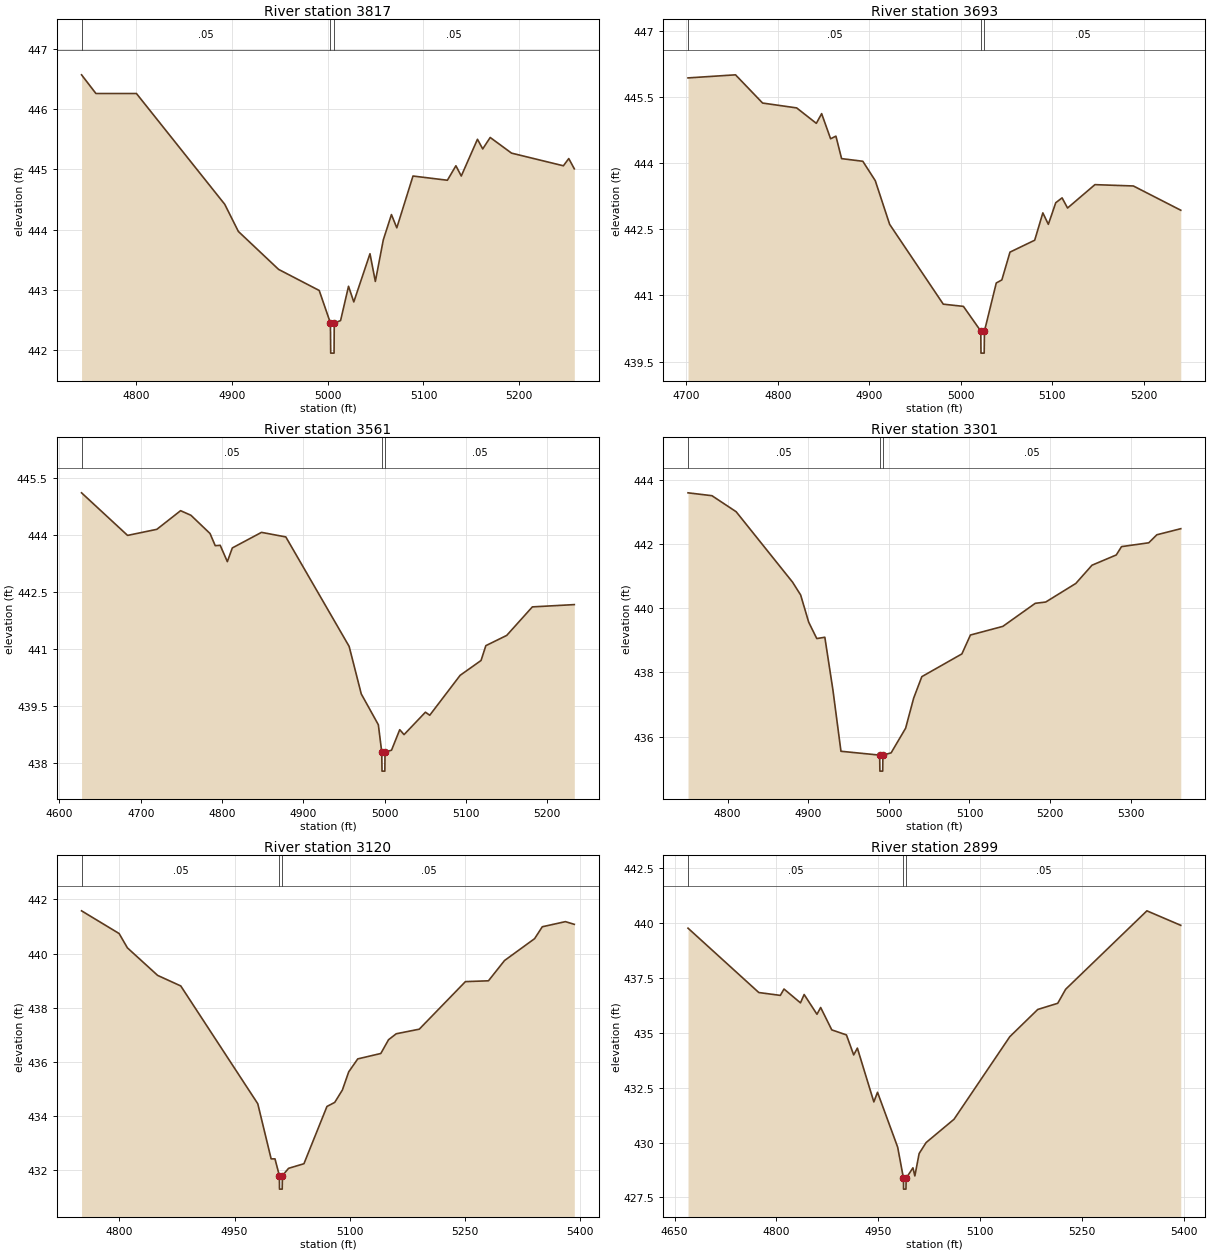
Type RM Length L Ch R = 1,3817,124,124,124
BEGIN DESCRIPTION:
Lacy 033 3044
END DESCRIPTION:
XS GIS Cut Line= 3
      2746718.51      6876389.29      2746528.07      6876216.86
      2746297.27      6876102.68
#Sta/Elev= 30
  4743.1  446.57  4758.1  446.26  4800.4  446.26  4892.6  444.42  4906.8  443.97
  4948.8  443.34  4991.2  442.99  5002.9  442.45  5003.2  441.95  5006.7  441.95
  5006.9  442.45  5013.5  442.49  5021.8  443.06  5027.3  442.80  5044.2  443.60
  5049.8  443.14  5058.1  443.83  5066.6  444.25  5072.2  444.03  5089.1  444.89
  5125.0  444.82  5133.9  445.06  5139.5  444.89  5156.4  445.50  5161.9  445.34
  5169.7  445.53  5192.0  445.27  5246.1  445.06  5251.7  445.18  5257.5  445.01
#Mann=3,-1,0
  4743.1    0.05       0  5002.9    0.04       0  5006.9    0.05       0
Bank Sta=5002.9,5006.9
Exp/Cntr=0.3,0.1

Type RM Length L Ch R = 1,3693,132,132,132
BEGIN DESCRIPTION:
Lacy 033 3043
END DESCRIPTION:
XS GIS Cut Line= 3
      2746732.56      6876365.77      2746581.83      6876108.70
      2746383.04      6875973.52
#Sta/Elev= 30
  4702.0  445.93  4753.9  446.00  4783.5  445.36  4820.7  445.25  4842.2  444.90
  4848.0  445.12  4857.8  444.55  4863.6  444.61  4869.8  444.10  4893.0  444.04
  4906.6  443.60  4922.3  442.61  4980.9  440.80  5002.9  440.75  5021.9  440.19
  5022.1  439.69  5025.6  439.69  5025.9  440.19  5038.8  441.28  5044.9  441.35
  5053.8  441.98  5080.8  442.25  5089.7  442.87  5095.7  442.61  5103.8  443.10
  5110.7  443.21  5116.7  442.98  5146.6  443.51  5188.6  443.48  5240.4  442.93
#Mann=3,-1,0
  4702.0    0.05       0  5021.9    0.04       0  5025.9    0.05       0
Bank Sta=5021.9,5025.9
Exp/Cntr=0.3,0.1

Type RM Length L Ch R = 1,3561,260,260,260
BEGIN DESCRIPTION:
Lacy 033 3045
END DESCRIPTION:
XS GIS Cut Line= 3
      2746883.63      6876321.68      2746674.01      6876013.40
      2746452.87      6875939.36
#Sta/Elev= 30
  4627.2  445.10  4683.8  443.98  4719.8  444.14  4749.0  444.63  4761.7  444.51
  4785.2  444.03  4791.6  443.71  4797.7  443.72  4806.5  443.29  4812.6  443.65
  4848.5  444.06  4878.4  443.94  4956.3  441.06  4971.2  439.81  4992.2  439.00
  4996.4  438.28  4996.7  437.78  5000.2  437.78  5000.4  438.28  5008.4  438.33
  5018.5  438.87  5023.8  438.74  5050.1  439.33  5055.4  439.25  5092.8  440.30
  5118.5  440.69  5124.4  441.08  5150.1  441.35  5181.6  442.10  5233.2  442.16
#Mann=3,-1,0
  4627.2    0.05       0  4996.4    0.04       0  5000.4    0.05       0
Bank Sta=4996.4,5000.4
Exp/Cntr=0.3,0.1

Type RM Length L Ch R = 1,3301,181,181,181
BEGIN DESCRIPTION:
Lacy 033 3042
END DESCRIPTION:
XS GIS Cut Line= 3
      2746875.74      6875808.33      2746626.65      6875806.23
      2746266.46      6875843.41
#Sta/Elev= 30
  4750.9  443.61  4780.6  443.52  4810.6  443.02  4880.6  440.82  4890.6  440.42
  4900.6  439.57  4910.6  439.06  4920.6  439.10  4930.6  437.46  4940.6  435.54
  4988.6  435.42  4988.9  434.92  4992.4  434.92  4992.6  435.42  5002.8  435.49
  5020.8  436.26  5030.8  437.20  5040.9  437.87  5090.6  438.58  5101.2  439.17
  5141.4  439.44  5181.6  440.16  5194.6  440.20  5231.9  440.78  5252.0  441.35
  5282.1  441.67  5288.6  441.93  5322.4  442.05  5332.4  442.30  5362.1  442.49
#Mann=3,-1,0
  4750.9    0.05       0  4988.6    0.04       0  4992.6    0.05       0
Bank Sta=4988.6,4992.6
Exp/Cntr=0.3,0.1

Type RM Length L Ch R = 1,3120,221,221,221
BEGIN DESCRIPTION:
Lacy 033 3040
END DESCRIPTION:
XS GIS Cut Line= 3
      2746924.79      6875660.34      2746676.36      6875640.79
      2746284.37      6875660.86
#Sta/Elev= 30
  4750.8  441.58  4799.7  440.74  4810.5  440.21  4849.9  439.19  4880.0  438.80
  4980.3  434.44  4997.7  432.40  5002.7  432.40  5008.4  431.78  5008.6  431.28
  5012.1  431.28  5012.4  431.78  5020.4  432.05  5040.4  432.22  5070.4  434.34
  5080.5  434.49  5090.5  434.95  5098.7  435.62  5110.5  436.10  5140.5  436.30
  5150.6  436.81  5160.6  437.03  5190.6  437.20  5250.7  438.96  5280.7  438.99
  5301.6  439.74  5340.8  440.55  5350.8  440.99  5380.9  441.18  5392.5  441.08
#Mann=3,-1,0
  4750.8    0.05       0  5008.4    0.04       0  5012.4    0.05       0
Bank Sta=5008.4,5012.4
Exp/Cntr=0.3,0.1

Type RM Length L Ch R = 1,2899,176,176,176
BEGIN DESCRIPTION:
Lacy 033 3041
END DESCRIPTION:
XS GIS Cut Line= 3
      2746882.98      6875577.80      2746574.50      6875455.72
      2746191.02      6875547.23
#Sta/Elev= 30
  4669.9  439.76  4774.2  436.83  4805.9  436.70  4811.3  436.99  4835.6  436.36
  4841.0  436.74  4859.9  435.84  4865.3  436.15  4881.7  435.13  4903.3  434.90
  4914.0  433.99  4919.4  434.30  4943.7  431.85  4949.1  432.29  4978.8  429.79
  4987.3  428.38  4987.5  427.88  4991.0  427.88  4991.3  428.38  5001.3  428.85
  5004.1  428.48  5010.4  429.50  5020.7  430.00  5061.8  431.06  5144.0  434.82
  5185.2  436.06  5214.6  436.34  5226.3  436.98  5346.0  440.55  5395.9  439.89
#Mann=3,-1,0
  4669.9    0.05       0  4987.3    0.04       0  4991.3    0.05       0
Bank Sta=4987.3,4991.3
Exp/Cntr=0.3,0.1

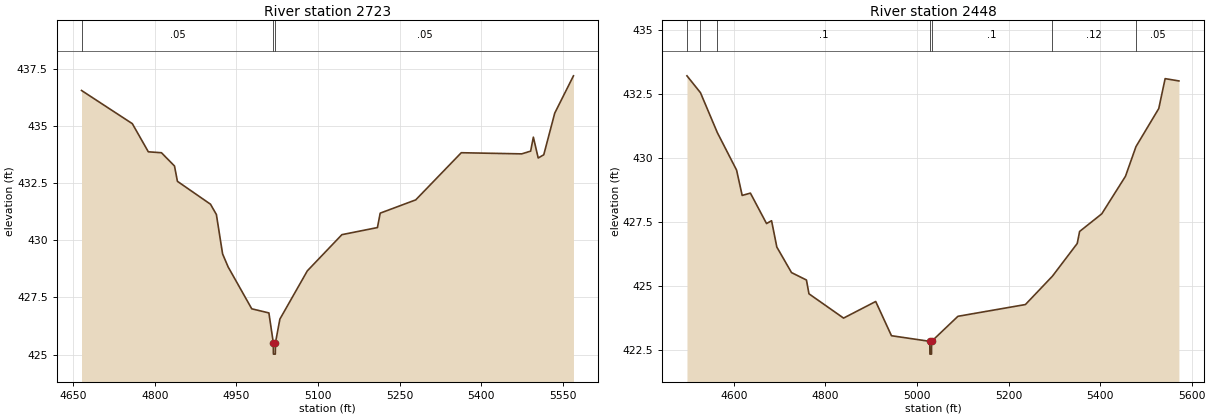
Type RM Length L Ch R = 1,2723,275,275,275
BEGIN DESCRIPTION:
Lacy 033 3039
END DESCRIPTION:
XS GIS Cut Line= 3
      2746935.60      6875421.94      2746625.48      6875295.78
      2746061.91      6875377.08
#Sta/Elev= 30
  4665.2  436.54  4758.6  435.09  4788.0  433.86  4812.1  433.82  4836.1  433.24
  4841.5  432.57  4902.3  431.57  4913.1  431.12  4924.5  429.40  4934.7  428.83
  4978.1  427.00  5009.6  426.82  5017.7  425.52  5017.9  425.02  5021.4  425.02
  5021.7  425.52  5029.8  426.55  5080.3  428.66  5143.8  430.24  5209.1  430.55
  5214.2  431.18  5279.5  431.76  5363.2  433.82  5474.3  433.77  5490.7  433.89
  5495.7  434.50  5504.6  433.59  5514.8  433.73  5535.0  435.55  5569.4  437.18
#Mann=3,-1,0
  4665.2    0.05       0  5017.7    0.04       0  5021.7    0.05       0
Bank Sta=5017.7,5021.7
Exp/Cntr=0.3,0.1

Type RM Length L Ch R = 1,2448,0,0,0
BEGIN DESCRIPTION:
Lacy 033 3038
END DESCRIPTION:
XS GIS Cut Line= 3
      2747085.29      6875222.66      2746624.95      6875021.44
      2746073.59      6875174.47
#Sta/Elev= 30
  4497.6  433.22  4527.1  432.56  4563.9  431.00  4606.0  429.53  4618.2  428.54
  4636.2  428.63  4671.4  427.44  4682.4  427.55  4693.9  426.52  4726.0  425.52
  4758.6  425.23  4764.1  424.69  4839.7  423.74  4909.9  424.39  4944.3  423.05
  5028.0  422.83  5028.3  422.33  5031.8  422.33  5032.0  422.83  5089.5  423.81
  5236.9  424.27  5295.9  425.38  5350.1  426.66  5355.3  427.13  5403.7  427.82
  5455.5  429.29  5478.4  430.45  5528.2  431.94  5542.1  433.11  5572.2  433.02
#Mann=7,-1,0
  4497.6    0.05       0  4527.1    0.12       0  4563.9     0.1       0
  5028.0    0.07       0  5032.0     0.1       0  5295.9    0.12       0
  5478.4    0.05       0
Bank Sta=5028,5032
Exp/Cntr=0.3,0.1

Chan Stop Cuts=-1