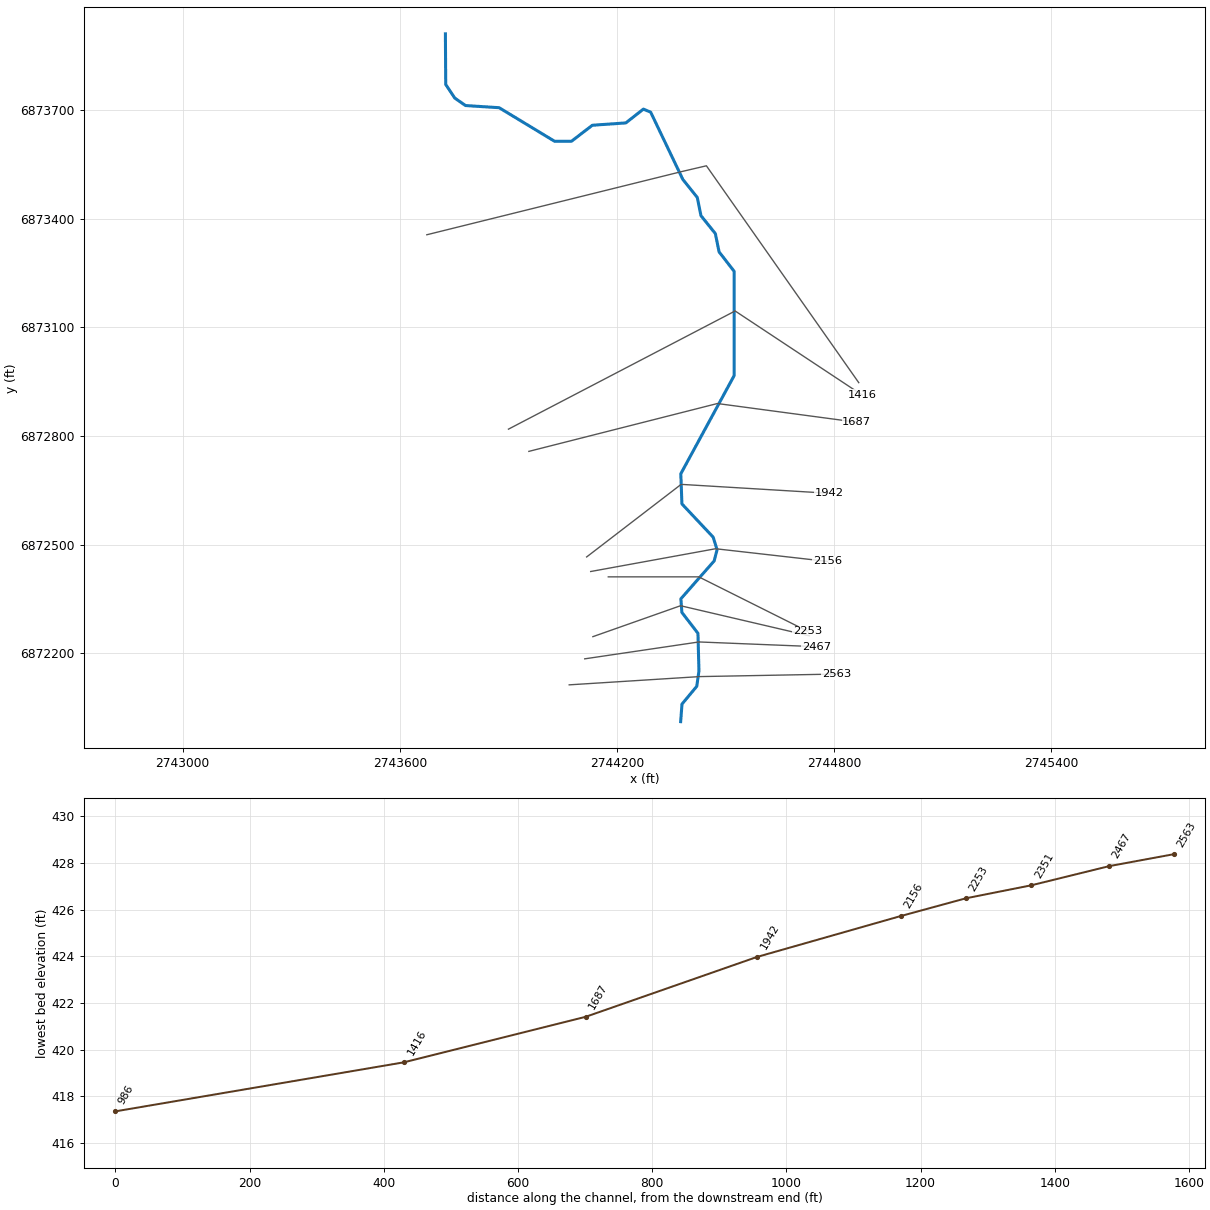
--- Lacy 034.prj (project) ---

Proj Title=Lacy 034 Base Level Engineering
Current Plan=p01
Default Exp/Contr=0.3,0.1
English Units
Geom File=g01
Flow File=f01
Plan File=p01
BEGIN DESCRIPTION:
Lacy 034
END DESCRIPTION:

--- Lacy 034.p01 (plan) ---

Plan Title=Multiple Run
Short Identifier=Multiple
Geom File=g01
Flow File=f01
Subcritical Flow
K Sum by GR= 0
Std Step Tol= 0.01
Critical Tol= 0.01
Num of Std Step Trials= 20
Max Error Tol= 0.3
Flow Tol Ratio= 0.001
Split Flow NTrial= 30
Split Flow Tol= 0.02
Split Flow Ratio= 0.02
Log Output Level= 0
Friction Slope Method= 1
Unsteady Friction Slope Method= 2
Unsteady Bridges Friction Slope Method= 1
Parabolic Critical Depth
Global Vel Dist=  1 , 1 , 1
Global Log Level= 0
CheckData=True
Encroach Param= -1, 0, 0, 0
BEGIN DESCRIPTION:
Multiple Run
END DESCRIPTION:

--- Lacy 034.f01 (steady flow) ---

Flow Title=Multiple
Number of Profiles=7
Profile Names=10-year,25-year,50-year,1pct_min,100-year,1pct_plu,500-year
River Rch & RM= Lacy 034,Reach-1,2563
     321     416     490     288     574    1146     789
Boundary for River Rch & Prof#=Lacy 034,Reach-1,1
Up Type=0
Dn Type=3
Dn Slope=0.005
Boundary for River Rch & Prof#=Lacy 034,Reach-1,2
Up Type=0
Dn Type=3
Dn Slope=0.005
Boundary for River Rch & Prof#=Lacy 034,Reach-1,3
Up Type=0
Dn Type=3
Dn Slope=0.005
Boundary for River Rch & Prof#=Lacy 034,Reach-1,4
Up Type=0
Dn Type=3
Dn Slope=0.005
Boundary for River Rch & Prof#=Lacy 034,Reach-1,5
Up Type=0
Dn Type=3
Dn Slope=0.005
Boundary for River Rch & Prof#=Lacy 034,Reach-1,6
Up Type=0
Dn Type=3
Dn Slope=0.005
Boundary for River Rch & Prof#=Lacy 034,Reach-1,7
Up Type=0
Dn Type=3
Dn Slope=0.005

--- Lacy 034.g01 (geometry) ---

Geom Title=Existing Conditions

River Reach=Lacy 034,Reach-1
Reach XY= 30
      2744376.00      6872011.00      2744379.65      6872059.49
      2744420.47      6872108.58      2744426.51      6872150.83
      2744423.72      6872255.07      2744379.34      6872312.75
      2744376.61      6872350.38      2744468.52      6872454.96
      2744476.58      6872486.00      2744465.80      6872520.67
      2744379.47      6872612.50      2744376.36      6872695.73
      2744523.76      6872966.93      2744523.76      6873255.07
      2744482.12      6873308.82      2744471.84      6873359.28
      2744432.08      6873408.80      2744421.84      6873459.28
      2744382.08      6873508.80      2744293.09      6873694.87
      2744272.97      6873703.21      2744224.52      6873665.11
      2744131.97      6873658.62      2744074.26      6873614.37
      2744027.72      6873614.34      2743874.41      6873707.17
      2743781.69      6873713.06      2743751.97      6873733.66
      2743726.92      6873771.23      2743726.00      6873911.00

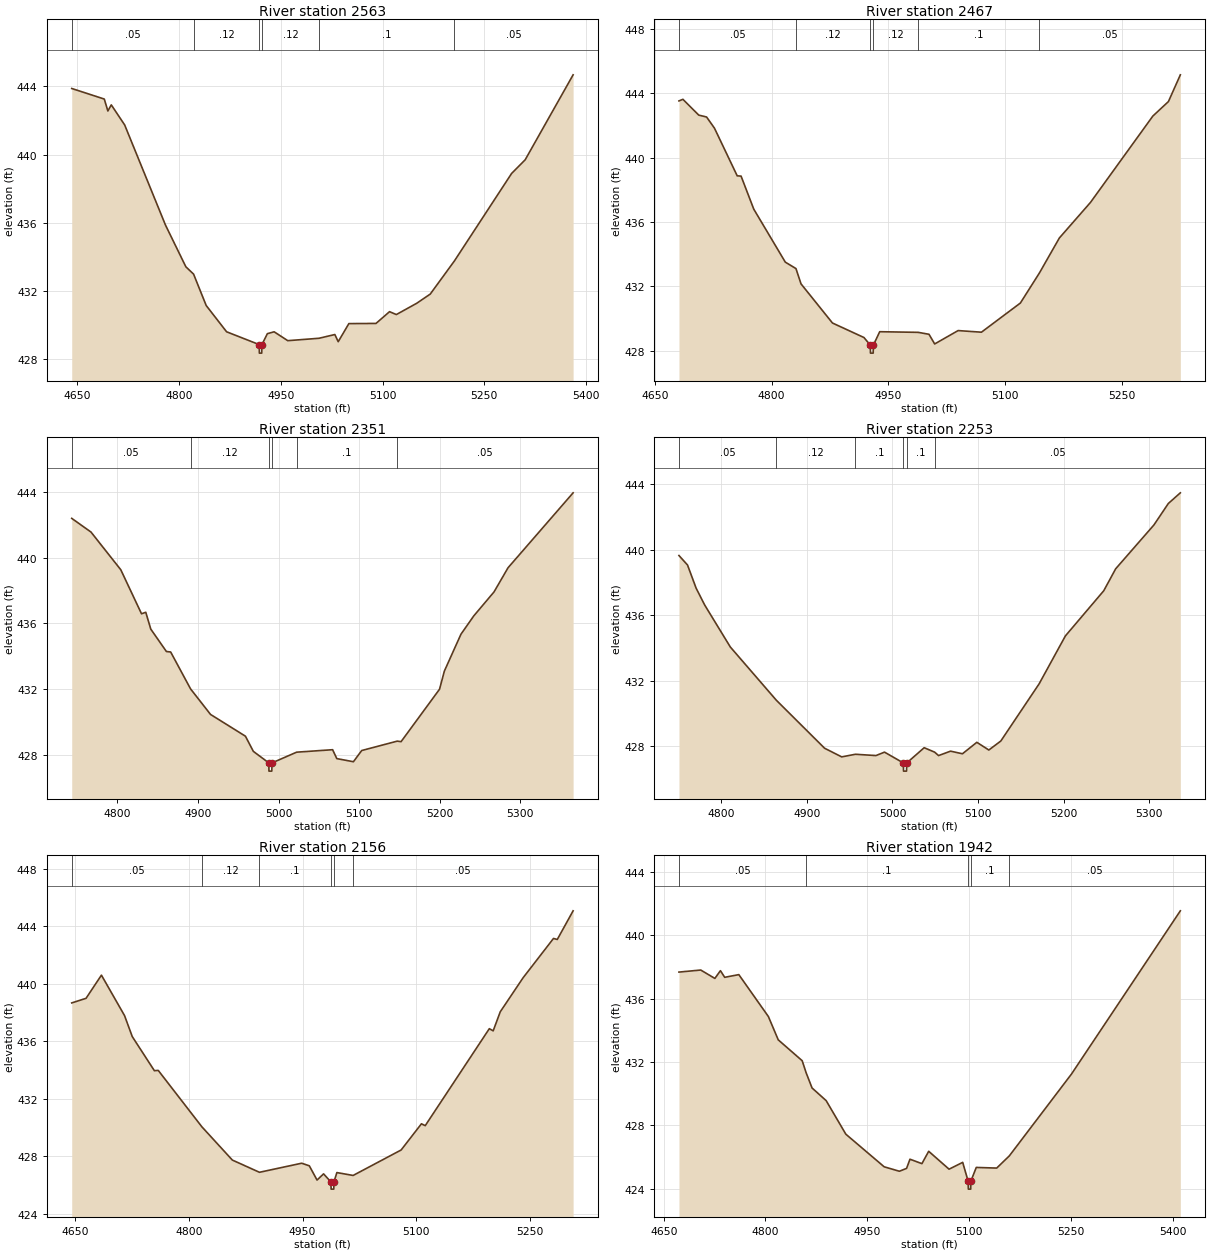
Type RM Length L Ch R = 1,2563,96,96,96
BEGIN DESCRIPTION:
Lacy 034 2912
END DESCRIPTION:
XS GIS Cut Line= 3
      2744068.07      6872112.62      2744427.75      6872135.40
      2744806.68      6872142.46
#Sta/Elev= 30
  4641.7  443.88  4689.7  443.26  4695.0  442.56  4700.0  442.92  4719.8  441.74
  4779.9  435.88  4810.0  433.43  4821.4  433.00  4840.0  431.16  4870.1  429.62
  4918.2  428.87  4918.4  428.37  4921.9  428.37  4922.2  428.87  4930.2  429.51
  4940.2  429.62  4960.3  429.10  5006.3  429.24  5029.7  429.46  5034.7  429.04
  5050.4  430.10  5090.4  430.11  5110.4  430.80  5120.4  430.63  5150.4  431.29
  5170.4  431.83  5206.0  433.77  5290.4  438.90  5310.4  439.70  5381.1  444.68
#Mann=6,-1,0
  4641.7    0.05       0  4821.4    0.12       0  4918.2    0.07       0
  4922.2    0.12       0  5006.3     0.1       0  5206.0    0.05       0
Bank Sta=4918.2,4922.2
Exp/Cntr=0.3,0.1

Type RM Length L Ch R = 1,2467,116,116,116
BEGIN DESCRIPTION:
Lacy 034 2911
END DESCRIPTION:
XS GIS Cut Line= 3
      2744110.91      6872184.48      2744426.38      6872231.14
      2744751.32      6872218.07
#Sta/Elev= 30
  4681.1  443.52  4686.2  443.62  4706.5  442.64  4716.6  442.52  4726.7  441.83
  4755.9  438.87  4760.9  438.85  4777.2  436.80  4817.7  433.51  4831.4  433.11
  4837.9  432.16  4878.3  429.73  4918.7  428.83  4926.9  428.36  4927.1  427.86
  4930.6  427.86  4930.9  428.36  4939.0  429.19  4988.4  429.15  5002.3  429.03
  5009.6  428.43  5039.7  429.26  5069.7  429.16  5119.7  430.97  5144.2  432.84
  5169.8  435.01  5209.8  437.22  5289.9  442.58  5309.9  443.48  5325.2  445.14
#Mann=6,-1,0
  4681.1    0.05       0  4831.4    0.12       0  4926.9    0.07       0
  4930.9    0.12       0  4988.4     0.1       0  5144.2    0.05       0
Bank Sta=4926.9,4930.9
Exp/Cntr=0.3,0.1

Type RM Length L Ch R = 1,2351,98,98,98
BEGIN DESCRIPTION:
Lacy 034 2910
END DESCRIPTION:
XS GIS Cut Line= 3
      2744133.48      6872245.75      2744375.64      6872331.21
      2744731.56      6872248.08
#Sta/Elev= 30
  4743.2  442.38  4767.1  441.55  4804.1  439.26  4829.8  436.59  4835.1  436.68
  4841.3  435.66  4860.7  434.30  4866.0  434.27  4890.7  432.03  4915.5  430.48
  4958.8  429.16  4968.6  428.24  4987.8  427.54  4988.0  427.04  4991.5  427.04
  4991.8  427.54  5022.3  428.19  5067.0  428.34  5072.2  427.80  5092.8  427.61
  5103.1  428.29  5147.2  428.86  5152.0  428.83  5199.7  432.01  5205.7  433.11
  5226.3  435.35  5242.2  436.46  5267.4  437.92  5284.7  439.38  5365.5  443.93
#Mann=6,-1,0
  4743.2    0.05       0  4890.7    0.12       0  4987.8    0.07       0
  4991.8    0.12       0  5022.3     0.1       0  5147.2    0.05       0
Bank Sta=4987.8,4991.8
Exp/Cntr=0.3,0.1

Type RM Length L Ch R = 1,2253,97,97,97
BEGIN DESCRIPTION:
Lacy 034 64
END DESCRIPTION:
XS GIS Cut Line= 3
      2744176.02      6872411.00      2744426.00      6872411.00
      2744726.01      6872261.00
#Sta/Elev= 30
  4750.7  439.65  4760.7  439.07  4770.7  437.66  4780.7  436.63  4810.7  434.06
  4864.4  430.81  4920.7  427.88  4940.7  427.35  4956.7  427.51  4980.7  427.43
  4990.7  427.64  5012.7  426.98  5012.9  426.48  5016.4  426.48  5016.7  426.98
  5037.0  427.91  5049.2  427.64  5053.8  427.43  5067.8  427.70  5081.7  427.54
  5098.5  428.24  5112.5  427.77  5126.5  428.32  5171.2  431.81  5201.9  434.74
  5246.7  437.50  5260.6  438.84  5305.3  441.52  5322.1  442.83  5336.1  443.48
#Mann=6,-1,0
  4750.7    0.05       0  4864.4    0.12       0  4956.7     0.1       0
  5012.7    0.07       0  5016.7     0.1       0  5049.2    0.05       0
Bank Sta=5012.7,5016.7
Exp/Cntr=0.3,0.1

Type RM Length L Ch R = 1,2156,214,214,214
BEGIN DESCRIPTION:
Lacy 034 2906
END DESCRIPTION:
XS GIS Cut Line= 3
      2744127.44      6872425.74      2744472.46      6872488.66
      2744781.58      6872453.63
#Sta/Elev= 30
  4645.4  438.66  4664.3  438.98  4684.6  440.59  4715.1  437.78  4725.3  436.32
  4754.5  433.95  4759.6  433.97  4817.2  430.05  4857.4  427.74  4893.2  426.89
  4948.9  427.52  4959.0  427.34  4969.2  426.35  4977.8  426.78  4987.5  426.22
  4987.8  425.72  4991.3  425.72  4991.5  426.22  4995.4  426.87  5016.8  426.67
  5080.2  428.44  5107.0  430.26  5112.0  430.13  5196.6  436.87  5201.7  436.72
  5211.0  438.04  5241.2  440.41  5281.3  443.14  5286.3  443.07  5307.2  445.06
#Mann=6,-1,0
  4645.4    0.05       0  4817.2    0.12       0  4893.2     0.1       0
  4987.5    0.07       0  4991.5     0.1       0  5016.8    0.05       0
Bank Sta=4987.5,4991.5
Exp/Cntr=0.3,0.1

Type RM Length L Ch R = 1,1942,255,255,255
BEGIN DESCRIPTION:
Lacy 034 2905
END DESCRIPTION:
XS GIS Cut Line= 3
      2744116.22      6872465.97      2744377.28      6872666.52
      2744786.14      6872641.91
#Sta/Elev= 30
  4672.5  437.68  4704.6  437.81  4725.4  437.28  4733.6  437.77  4739.9  437.35
  4760.7  437.52  4804.3  434.87  4818.8  433.40  4854.1  432.08  4859.8  431.33
  4868.6  430.36  4889.4  429.56  4918.4  427.44  4974.9  425.38  4997.3  425.10
  5007.9  425.28  5012.9  425.86  5030.5  425.58  5040.5  426.36  5070.5  425.23
  5090.6  425.66  5098.6  424.47  5098.9  423.97  5102.4  423.97  5102.6  424.47
  5110.6  425.34  5140.7  425.30  5159.3  426.07  5250.9  431.24  5411.3  441.55
#Mann=5,-1,0
  4672.5    0.05       0  4859.8     0.1       0  5098.6    0.07       0
  5102.6     0.1       0  5159.3    0.05       0
Bank Sta=5098.6,5102.6
Exp/Cntr=0.3,0.1

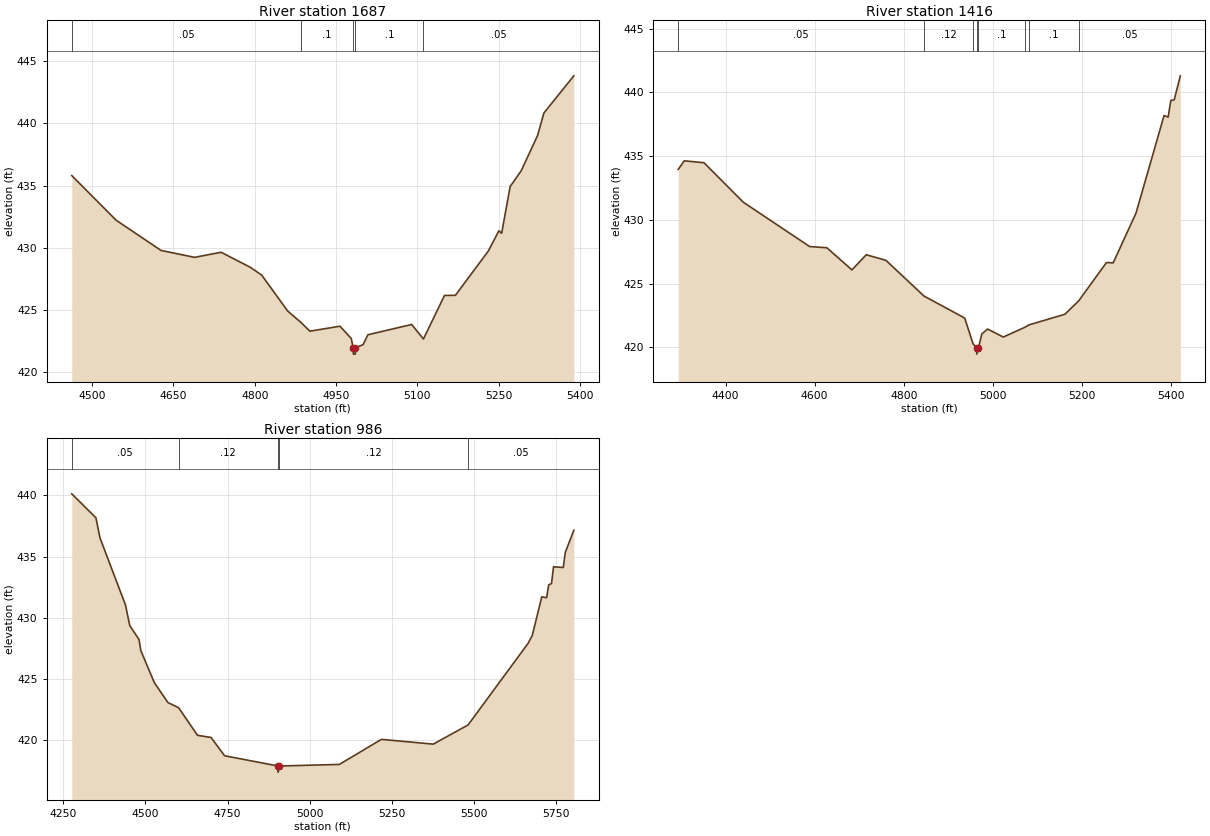
Type RM Length L Ch R = 1,1687,271,271,271
BEGIN DESCRIPTION:
Lacy 034 2909
END DESCRIPTION:
XS GIS Cut Line= 3
      2743956.58      6872757.65      2744477.36      6872889.84
      2744862.43      6872838.26
#Sta/Elev= 30
  4462.7  435.80  4544.6  432.20  4627.2  429.77  4689.1  429.21  4738.0  429.62
  4792.3  428.40  4812.9  427.78  4860.9  424.88  4885.7  423.95  4901.8  423.26
  4957.3  423.66  4978.0  422.67  4981.8  421.91  4982.0  421.41  4985.5  421.41
  4985.8  421.91  5000.0  422.18  5008.7  422.97  5089.4  423.80  5111.2  422.63
  5150.0  426.14  5170.1  426.15  5230.7  429.71  5250.3  431.35  5255.4  431.15
  5271.0  434.91  5291.2  436.17  5321.5  439.02  5333.4  440.85  5388.5  443.84
#Mann=5,-1,0
  4462.7    0.05       0  4885.7     0.1       0  4981.8    0.07       0
  4985.8     0.1       0  5111.2    0.05       0
Bank Sta=4981.8,4985.8
Exp/Cntr=0.3,0.1

Type RM Length L Ch R = 1,1416,430,430,430
BEGIN DESCRIPTION:
Lacy 034 2908
END DESCRIPTION:
XS GIS Cut Line= 3
      2743900.24      6872819.07      2744526.44      6873145.54
      2744877.36      6872913.32
#Sta/Elev= 30
  4293.8  433.96  4307.4  434.63  4351.6  434.48  4439.9  431.38  4588.9  427.90
  4627.3  427.81  4683.7  426.07  4715.9  427.26  4760.0  426.82  4845.4  424.02
  4936.8  422.29  4955.6  420.27  4963.7  419.96  4963.9  419.46  4967.7  419.96
  4975.3  421.04  4988.2  421.43  5023.5  420.80  5072.1  421.57  5080.6  421.75
  5161.8  422.59  5192.7  423.64  5255.1  426.65  5270.1  426.62  5321.3  430.52
  5384.4  438.19  5393.5  438.06  5399.5  439.36  5407.2  439.42  5420.8  441.30
#Mann=8,-1,0
  4293.8    0.05       0  4845.4    0.12       0  4955.6     0.1       0
  4963.7    0.07       0  4967.7     0.1       0  5072.1    0.05       0
  5080.6     0.1       0  5192.7    0.05       0
Bank Sta=4963.7,4967.7
Exp/Cntr=0.3,0.1

Type RM Length L Ch R = 1,986,0,0,0
BEGIN DESCRIPTION:
Lacy 034 2907
END DESCRIPTION:
XS GIS Cut Line= 4
      2743674.68      6873356.10      2744377.70      6873530.41
      2744447.10      6873546.64      2744868.00      6872947.48
#Sta/Elev= 30
  4275.7  440.13  4349.2  438.17  4361.5  436.53  4439.1  431.04  4452.2  429.35
  4480.5  428.20  4485.7  427.31  4527.0  424.68  4568.4  423.05  4600.9  422.63
  4658.3  420.37  4699.5  420.20  4740.7  418.70  4903.5  417.86  4903.8  417.36
  4907.5  417.86  5089.9  417.99  5218.0  420.04  5375.7  419.65  5481.7  421.22
  5664.1  427.89  5677.0  428.54  5705.9  431.70  5720.7  431.63  5726.9  432.68
  5735.6  432.79  5741.7  434.16  5771.3  434.10  5777.4  435.33  5803.5  437.15
#Mann=5,-1,0
  4275.7    0.05       0  4600.9    0.12       0  4903.5    0.07       0
  4907.5    0.12       0  5481.7    0.05       0
Bank Sta=4903.5,4907.5
Exp/Cntr=0.3,0.1

Chan Stop Cuts=-1