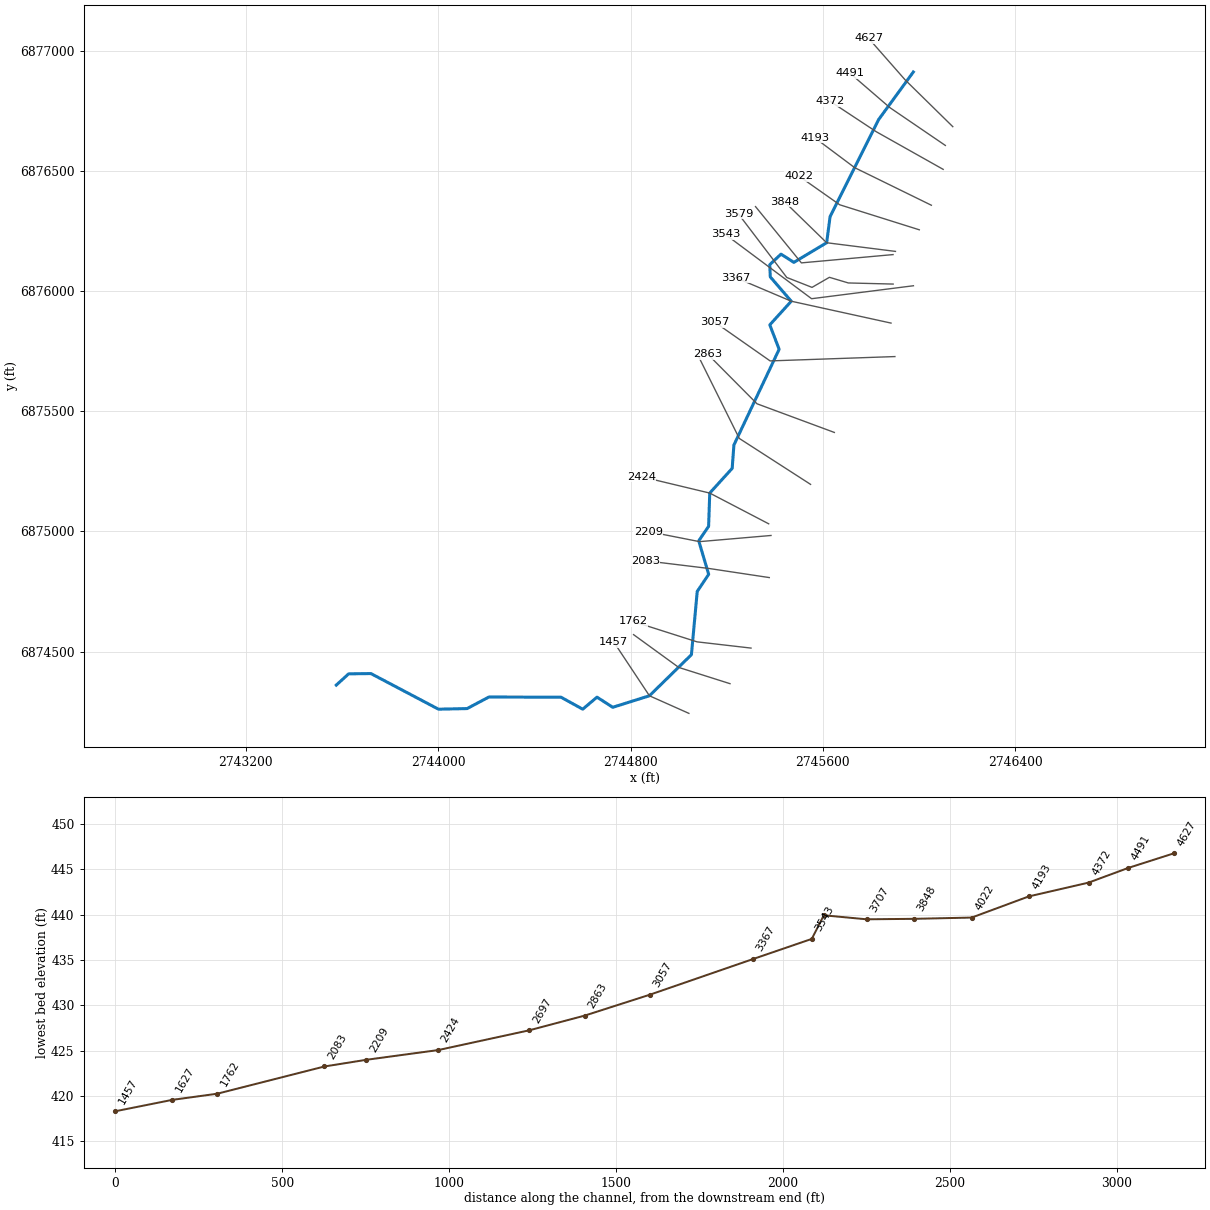
--- Lacy 035.prj (project) ---

Proj Title=Lacy 035 Base Level Engineering
Current Plan=p01
Default Exp/Contr=0.3,0.1
English Units
Geom File=g01
Flow File=f01
Plan File=p01
BEGIN DESCRIPTION:
Lacy 035
END DESCRIPTION:

--- Lacy 035.p01 (plan) ---

Plan Title=Multiple Run
Short Identifier=Multiple
Geom File=g01
Flow File=f01
Subcritical Flow
K Sum by GR= 0
Std Step Tol= 0.01
Critical Tol= 0.01
Num of Std Step Trials= 20
Max Error Tol= 0.3
Flow Tol Ratio= 0.001
Split Flow NTrial= 30
Split Flow Tol= 0.02
Split Flow Ratio= 0.02
Log Output Level= 0
Friction Slope Method= 1
Unsteady Friction Slope Method= 2
Unsteady Bridges Friction Slope Method= 1
Parabolic Critical Depth
Global Vel Dist=  1 , 1 , 1
Global Log Level= 0
CheckData=True
Encroach Param= -1, 0, 0, 0
BEGIN DESCRIPTION:
Multiple Run
END DESCRIPTION:

--- Lacy 035.f01 (steady flow) ---

Flow Title=Multiple
Number of Profiles=7
Profile Names=10-year,25-year,50-year,1pct_min,100-year,1pct_plu,500-year
River Rch & RM= Lacy 035,Reach-1,4627
      99     117     131      73     145     290     178
River Rch & RM= Lacy 035,Reach-1,2424
     169     209     238     136     272     542     351
Boundary for River Rch & Prof#=Lacy 035,Reach-1,1
Up Type=0
Dn Type=3
Dn Slope=0.005
Boundary for River Rch & Prof#=Lacy 035,Reach-1,2
Up Type=0
Dn Type=3
Dn Slope=0.005
Boundary for River Rch & Prof#=Lacy 035,Reach-1,3
Up Type=0
Dn Type=3
Dn Slope=0.005
Boundary for River Rch & Prof#=Lacy 035,Reach-1,4
Up Type=0
Dn Type=3
Dn Slope=0.005
Boundary for River Rch & Prof#=Lacy 035,Reach-1,5
Up Type=0
Dn Type=3
Dn Slope=0.005
Boundary for River Rch & Prof#=Lacy 035,Reach-1,6
Up Type=0
Dn Type=3
Dn Slope=0.005
Boundary for River Rch & Prof#=Lacy 035,Reach-1,7
Up Type=0
Dn Type=3
Dn Slope=0.005

--- Lacy 035.g01 (geometry) ---

Geom Title=Existing Conditions

River Reach=Lacy 035,Reach-1
Reach XY= 30
      2745976.00      6876911.00      2745831.85      6876713.29
      2745629.83      6876309.41      2745615.61      6876200.89
      2745479.22      6876119.25      2745425.72      6876153.54
      2745379.10      6876109.82      2745381.09      6876058.76
      2745468.39      6875957.67      2745379.18      6875859.35
      2745417.93      6875757.69      2745229.80      6875359.43
      2745222.61      6875262.40      2745129.30      6875159.63
      2745124.61      6875021.44      2745083.56      6874961.00
      2745124.89      6874821.55      2745077.22      6874750.50
      2745053.14      6874487.47      2744878.43      6874316.52
      2744725.96      6874268.60      2744660.34      6874310.82
      2744601.05      6874260.70      2744510.80      6874310.46
      2744210.82      6874311.43      2744120.06      6874263.25
      2744000.92      6874260.76      2743720.05      6874408.87
      2743627.40      6874407.81      2743576.00      6874361.00

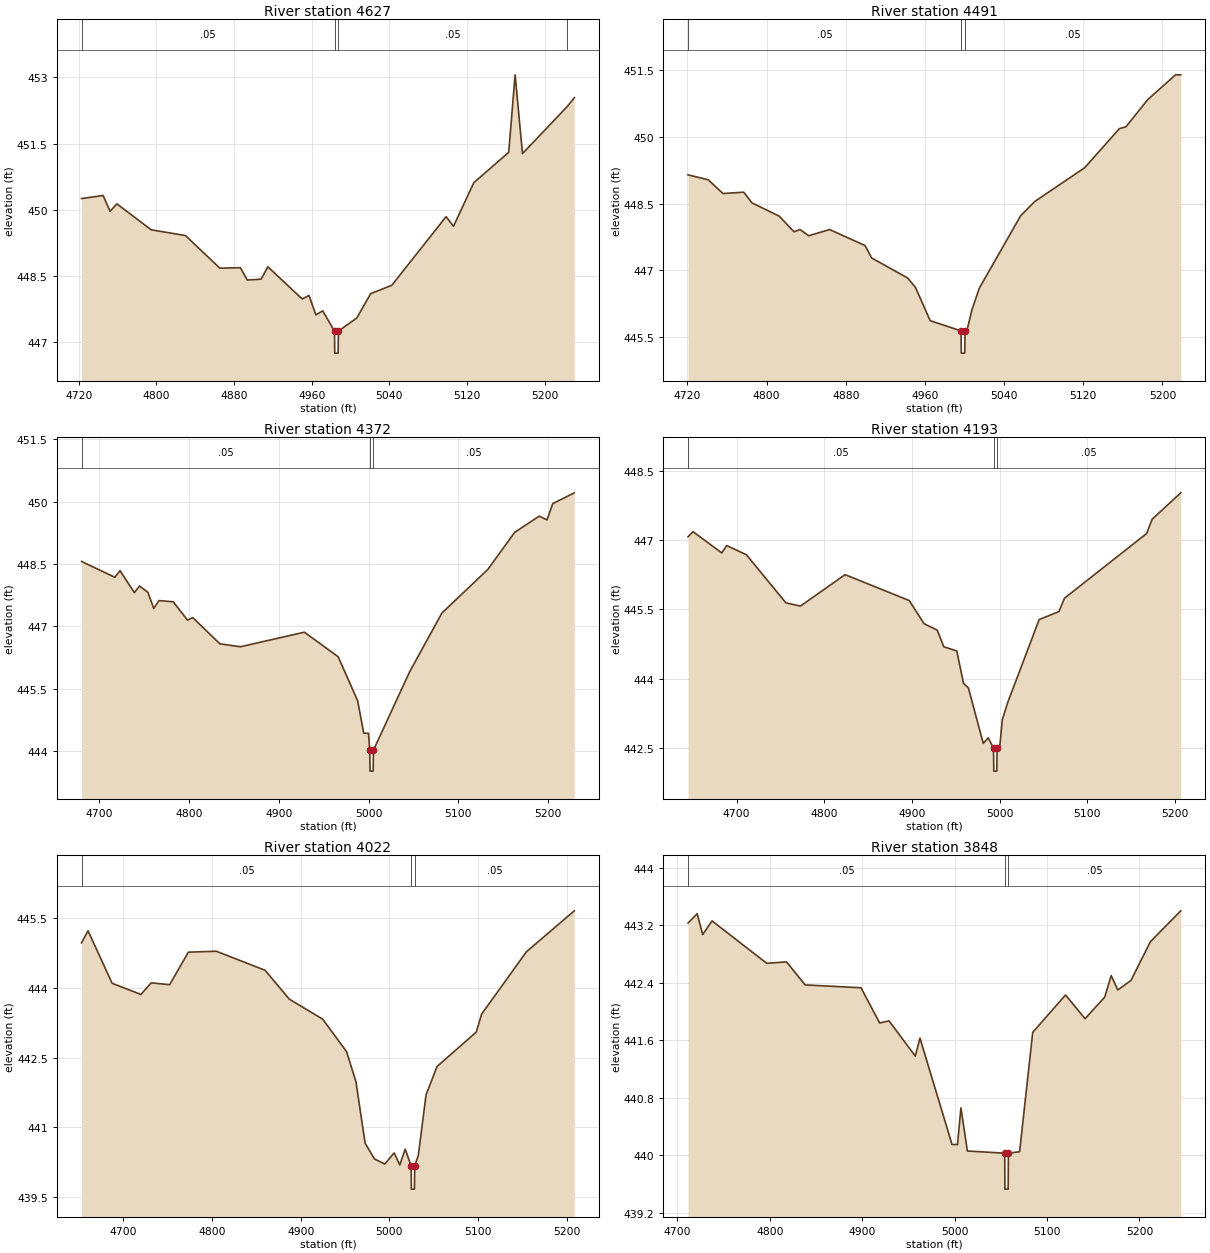
Type RM Length L Ch R = 1,4627,136,136,136
BEGIN DESCRIPTION:
Lacy 035 2931
END DESCRIPTION:
XS GIS Cut Line= 3
      2746140.22      6876683.71      2745942.42      6876877.92
      2745790.15      6877051.09
#Sta/Elev= 30
  4722.8  450.25  4745.0  450.32  4752.2  449.96  4759.2  450.13  4794.6  449.54
  4829.9  449.41  4865.3  448.67  4886.5  448.68  4893.6  448.40  4907.8  448.42
  4914.8  448.70  4950.2  447.97  4957.2  448.05  4964.3  447.61  4971.3  447.70
  4983.5  447.24  4983.7  446.74  4987.2  446.74  4987.5  447.24  5006.5  447.54
  5020.7  448.09  5042.5  448.28  5098.5  449.84  5106.1  449.62  5127.0  450.61
  5163.0  451.30  5169.6  453.06  5177.2  451.27  5223.3  452.34  5230.6  452.54
#Mann=4,-1,0
  4722.8    0.05       0  4983.5    0.04       0  4987.5    0.05       0
  5223.3     0.1       0
Bank Sta=4983.5,4987.5
Exp/Cntr=0.3,0.1

Type RM Length L Ch R = 1,4491,119,119,119
BEGIN DESCRIPTION:
Lacy 035 2930
END DESCRIPTION:
XS GIS Cut Line= 3
      2746109.34      6876605.55      2745878.47      6876762.92
      2745712.97      6876905.58
#Sta/Elev= 30
  4720.6  449.15  4741.0  449.04  4755.9  448.73  4776.9  448.76  4785.2  448.52
  4812.8  448.22  4827.7  447.87  4833.8  447.92  4842.6  447.78  4863.6  447.92
  4899.5  447.56  4906.2  447.28  4942.5  446.83  4950.4  446.62  4965.3  445.87
  4996.5  445.64  4996.7  445.14  5000.2  445.14  5000.5  445.64  5002.4  445.64
  5007.3  446.10  5014.9  446.60  5056.7  448.23  5070.9  448.55  5121.4  449.31
  5156.5  450.19  5163.1  450.23  5185.0  450.84  5213.2  451.40  5218.5  451.40
#Mann=3,-1,0
  4720.6    0.05       0  4996.5    0.04       0  5000.5    0.05       0
Bank Sta=4996.5,5000.5
Exp/Cntr=0.3,0.1

Type RM Length L Ch R = 1,4372,179,179,179
BEGIN DESCRIPTION:
Lacy 035 2929
END DESCRIPTION:
XS GIS Cut Line= 3
      2746100.29      6876506.11      2745821.81      6876662.74
      2745630.61      6876788.95
#Sta/Elev= 30
  4680.5  448.56  4717.6  448.18  4723.3  448.34  4739.3  447.81  4745.0  447.97
  4754.3  447.82  4760.9  447.43  4766.7  447.62  4782.6  447.59  4798.5  447.15
  4804.3  447.21  4834.6  446.58  4857.5  446.51  4928.6  446.86  4966.2  446.27
  4987.9  445.21  4994.7  444.43  5000.0  444.43  5001.4  444.02  5001.7  443.52
  5005.2  443.52  5005.4  444.02  5045.6  445.90  5081.7  447.32  5132.9  448.37
  5162.7  449.26  5190.1  449.65  5198.7  449.56  5205.1  449.95  5229.1  450.21
#Mann=3,-1,0
  4680.5    0.05       0  5001.4    0.04       0  5005.4    0.05       0
Bank Sta=5001.4,5005.4
Exp/Cntr=0.3,0.1

Type RM Length L Ch R = 1,4193,171,171,171
BEGIN DESCRIPTION:
Lacy 035 2928
END DESCRIPTION:
XS GIS Cut Line= 3
      2746051.15      6876356.88      2745732.08      6876513.20
      2745566.76      6876636.93
#Sta/Elev= 30
  4644.7  447.07  4650.4  447.18  4683.2  446.72  4688.8  446.88  4711.3  446.68
  4756.3  445.64  4772.9  445.57  4823.8  446.25  4896.9  445.69  4913.8  445.19
  4928.8  445.05  4936.3  444.69  4951.1  444.60  4958.8  443.90  4964.4  443.80
  4981.3  442.60  4986.9  442.72  4993.0  442.50  4993.3  442.00  4996.8  442.00
  4997.0  442.50  5000.0  442.50  5003.0  443.11  5009.3  443.49  5045.1  445.28
  5067.6  445.45  5073.9  445.74  5167.6  447.14  5173.9  447.45  5206.5  448.02
#Mann=3,-1,0
  4644.7    0.05       0  4993.0    0.04       0  4997.0    0.05       0
Bank Sta=4993,4997
Exp/Cntr=0.3,0.1

Type RM Length L Ch R = 1,4022,174,174,174
BEGIN DESCRIPTION:
Lacy 035 2927
END DESCRIPTION:
XS GIS Cut Line= 3
      2746000.90      6876254.72      2745669.88      6876358.82
      2745499.48      6876478.78
#Sta/Elev= 30
  4653.0  444.97  4660.3  445.23  4687.5  444.10  4719.9  443.86  4731.5  444.11
  4752.3  444.07  4773.4  444.77  4804.9  444.79  4859.9  444.38  4887.1  443.76
  4924.7  443.33  4951.7  442.63  4962.3  441.98  4972.6  440.66  4983.1  440.32
  4994.7  440.21  5005.4  440.45  5011.7  440.19  5017.8  440.53  5024.5  440.17
  5024.7  439.67  5028.2  439.67  5028.5  440.17  5032.6  440.40  5041.3  441.70
  5053.7  442.31  5097.9  443.05  5104.0  443.44  5154.5  444.78  5208.4  445.66
#Mann=3,-1,0
  4653.0    0.05       0  5024.5    0.04       0  5028.5    0.05       0
Bank Sta=5024.5,5028.5
Exp/Cntr=0.3,0.1

Type RM Length L Ch R = 1,3848,141,141,141
BEGIN DESCRIPTION:
Lacy 035 2926
END DESCRIPTION:
XS GIS Cut Line= 3
      2745901.76      6876164.88      2745615.61      6876200.89
      2745440.14      6876371.58
#Sta/Elev= 30
  4711.6  443.23  4721.5  443.36  4727.5  443.07  4737.6  443.26  4796.8  442.67
  4818.2  442.69  4838.3  442.37  4898.8  442.33  4919.0  441.84  4929.1  441.87
  4957.5  441.38  4962.6  441.63  4997.3  440.15  5003.2  440.15  5006.9  440.66
  5013.9  440.06  5054.3  440.03  5054.5  439.53  5058.0  439.53  5058.3  440.03
  5070.4  440.05  5084.6  441.71  5120.1  442.23  5141.2  441.90  5162.5  442.20
  5169.5  442.50  5176.6  442.30  5190.8  442.43  5211.9  442.97  5244.8  443.40
#Mann=3,-1,0
  4711.6    0.05       0  5054.3    0.04       0  5058.3    0.05       0
Bank Sta=5054.3,5058.3
Exp/Cntr=0.3,0.1

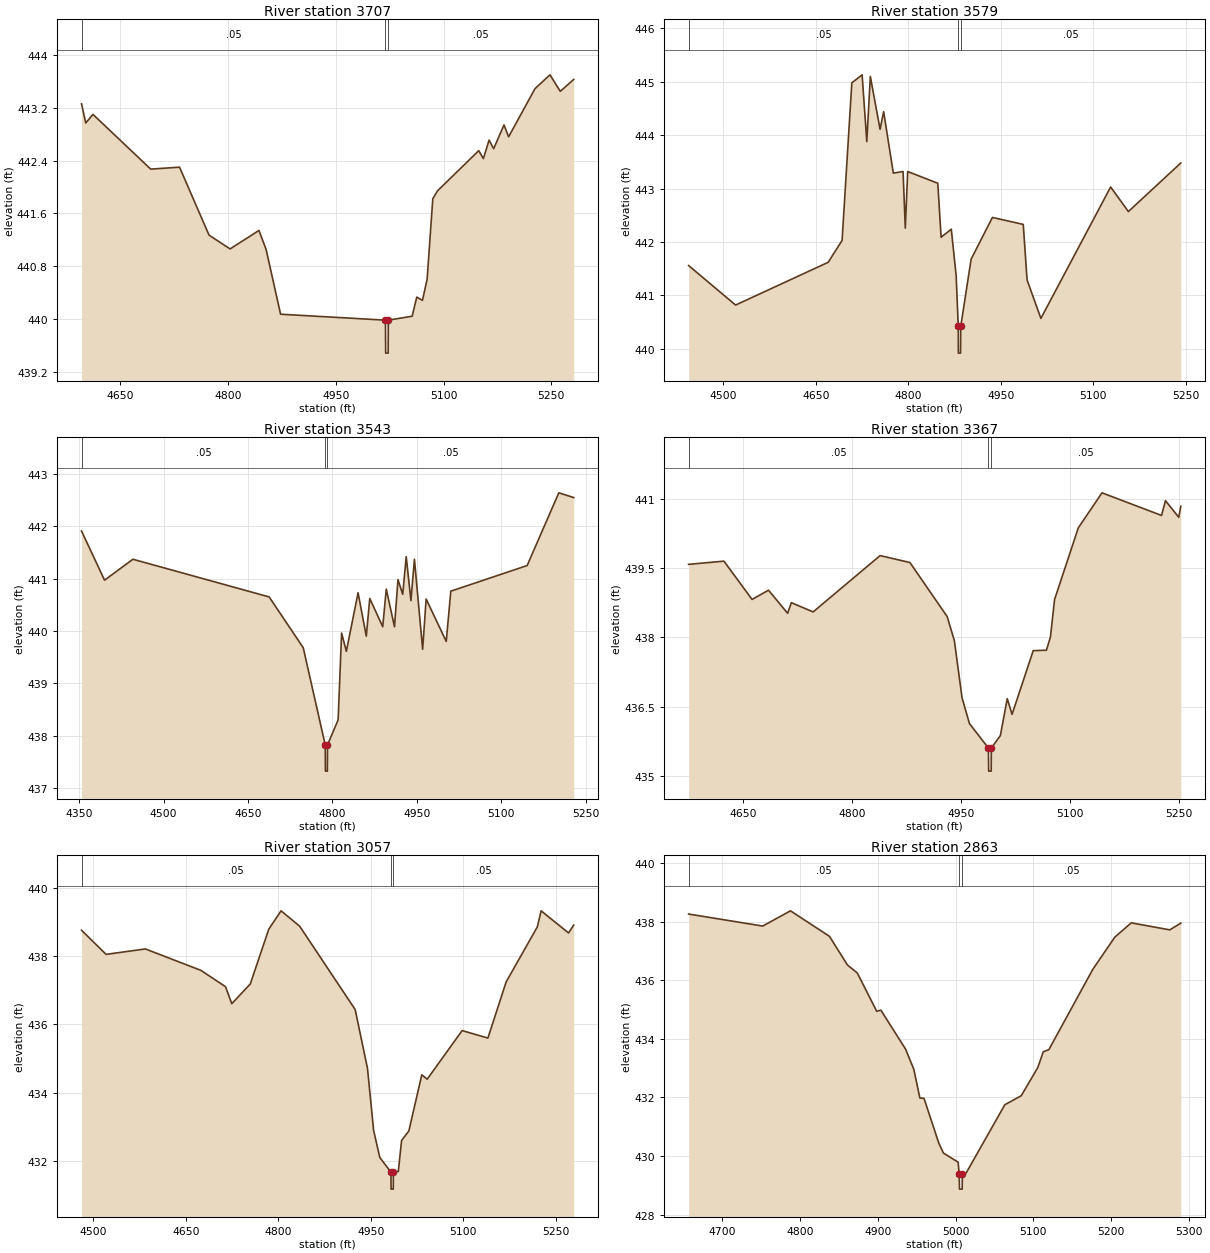
Type RM Length L Ch R = 1,3707,128,128,128
BEGIN DESCRIPTION:
Lacy 035 2925
END DESCRIPTION:
XS GIS Cut Line= 3
      2745891.87      6876151.61      2745510.51      6876117.11
      2745319.72      6876351.20
#Sta/Elev= 30
  4596.3  443.26  4602.2  442.97  4612.2  443.10  4692.6  442.27  4732.7  442.30
  4773.7  441.27  4803.0  441.06  4843.2  441.34  4853.2  441.05  4873.3  440.07
  5019.2  439.98  5019.5  439.48  5023.0  439.48  5023.2  439.98  5056.4  440.04
  5062.8  440.33  5070.7  440.28  5077.2  440.60  5085.1  441.82  5091.6  441.94
  5149.0  442.55  5155.5  442.43  5163.4  442.71  5169.8  442.58  5184.2  442.94
  5190.6  442.76  5227.3  443.49  5248.1  443.70  5262.5  443.45  5281.2  443.63
#Mann=3,-1,0
  4596.3    0.05       0  5019.2    0.04       0  5023.2    0.05       0
Bank Sta=5019.2,5023.2
Exp/Cntr=0.3,0.1

Type RM Length L Ch R = 1,3579,36,36,36
BEGIN DESCRIPTION:
Lacy 035 2923
END DESCRIPTION:
XS GIS Cut Line= 6
      2745892.22      6876028.98      2745705.75      6876033.62
      2745627.04      6876057.07      2745554.72      6876015.23
      2745449.67      6876056.45      2745247.97      6876321.60
#Sta/Elev= 30
  4443.7  441.56  4519.9  440.82  4670.0  441.62  4692.6  442.03  4708.4  444.98
  4725.1  445.13  4732.7  443.88  4738.4  445.10  4754.2  444.11  4760.0  444.44
  4775.7  443.29  4791.5  443.32  4795.1  442.26  4799.0  443.32  4847.8  443.10
  4853.2  442.09  4869.7  442.24  4877.6  441.37  4881.0  440.42  4881.2  439.92
  4884.7  439.92  4885.0  440.42  4901.9  441.68  4936.4  442.46  4986.4  442.33
  4992.6  441.29  5015.0  440.57  5128.1  443.03  5156.9  442.57  5241.9  443.48
#Mann=3,-1,0
  4443.7    0.05       0  4881.0    0.04       0  4885.0    0.05       0
Bank Sta=4881,4885
Exp/Cntr=0.3,0.1

Type RM Length L Ch R = 1,3543,176,176,176
BEGIN DESCRIPTION:
Lacy 035 2924
END DESCRIPTION:
XS GIS Cut Line= 3
      2745976.55      6876022.00      2745553.00      6875968.09
      2745194.52      6876235.35
#Sta/Elev= 30
  4354.4  441.91  4395.3  440.97  4445.7  441.37  4687.6  440.65  4748.1  439.68
  4787.2  437.82  4787.5  437.32  4791.0  437.32  4791.2  437.82  4810.1  438.30
  4816.3  439.96  4824.7  439.61  4845.5  440.73  4860.1  439.90  4866.3  440.62
  4889.3  440.08  4895.6  440.80  4910.2  440.08  4916.4  440.98  4924.8  440.70
  4931.0  441.42  4939.4  440.58  4945.6  441.37  4960.2  439.65  4966.4  440.61
  5002.1  439.80  5010.2  440.76  5145.8  441.25  5202.0  442.64  5228.5  442.55
#Mann=3,-1,0
  4354.4    0.05       0  4787.2   0.035       0  4791.2    0.05       0
Bank Sta=4787.2,4791.2
Exp/Cntr=0.3,0.1

Type RM Length L Ch R = 1,3367,310,310,310
BEGIN DESCRIPTION:
Lacy 035 2922
END DESCRIPTION:
XS GIS Cut Line= 3
      2745883.32      6875866.67      2745468.39      6875957.67
      2745236.23      6876056.20
#Sta/Elev= 30
  4575.2  439.58  4623.8  439.65  4662.5  438.82  4685.1  439.02  4711.4  438.52
  4716.5  438.75  4746.5  438.55  4838.6  439.77  4879.6  439.62  4930.8  438.45
  4940.7  437.93  4951.3  436.69  4961.5  436.13  4987.6  435.60  4987.9  435.10
  4991.4  435.10  4991.6  435.60  5004.0  435.87  5013.5  436.67  5020.1  436.33
  5049.2  437.71  5067.4  437.72  5072.9  438.01  5078.6  438.82  5111.2  440.37
  5143.8  441.13  5225.7  440.64  5231.1  440.96  5249.4  440.60  5252.2  440.84
#Mann=3,-1,0
  4575.2    0.05       0  4987.6   0.035       0  4991.6    0.05       0
Bank Sta=4987.6,4991.6
Exp/Cntr=0.3,0.1

Type RM Length L Ch R = 1,3057,194,194,194
BEGIN DESCRIPTION:
Lacy 035 2921
END DESCRIPTION:
XS GIS Cut Line= 3
      2745899.51      6875727.43      2745380.42      6875709.36
      2745151.94      6875869.31
#Sta/Elev= 30
  4480.6  438.77  4520.4  438.06  4584.2  438.22  4674.2  437.59  4714.2  437.11
  4724.3  436.61  4754.3  437.19  4784.3  438.80  4804.2  439.34  4834.3  438.89
  4924.4  436.44  4944.4  434.71  4954.4  432.88  4964.4  432.09  4982.4  431.66
  4982.7  431.16  4986.2  431.16  4986.4  431.66  4994.4  431.68  4999.7  432.59
  5011.5  432.87  5032.5  434.52  5041.2  434.39  5097.9  435.82  5139.7  435.60
  5169.3  437.25  5219.9  438.87  5226.0  439.34  5270.5  438.69  5278.9  438.92
#Mann=3,-1,0
  4480.6    0.05       0  4982.4   0.035       0  4986.4    0.05       0
Bank Sta=4982.4,4986.4
Exp/Cntr=0.3,0.1

Type RM Length L Ch R = 1,2863,166,166,166
BEGIN DESCRIPTION:
Lacy 035 2920
END DESCRIPTION:
XS GIS Cut Line= 3
      2745647.59      6875411.85      2745325.77      6875531.10
      2745121.61      6875736.63
#Sta/Elev= 30
  4656.8  438.26  4752.1  437.85  4787.8  438.37  4837.9  437.50  4861.1  436.52
  4873.7  436.25  4898.7  434.94  4904.0  434.98  4935.8  433.65  4946.4  432.96
  4954.2  431.98  4959.5  431.97  4978.4  430.45  4984.5  430.10  5003.4  429.79
  5004.8  429.37  5005.1  428.87  5008.6  428.87  5008.8  429.37  5013.9  429.43
  5063.4  431.75  5084.6  432.06  5105.8  433.02  5112.9  433.56  5120.0  433.63
  5176.5  436.37  5204.8  437.47  5226.0  437.96  5275.5  437.72  5289.7  437.95
#Mann=3,-1,0
  4656.8    0.05       0  5004.8   0.035       0  5008.8    0.05       0
Bank Sta=5004.8,5008.8
Exp/Cntr=0.3,0.1

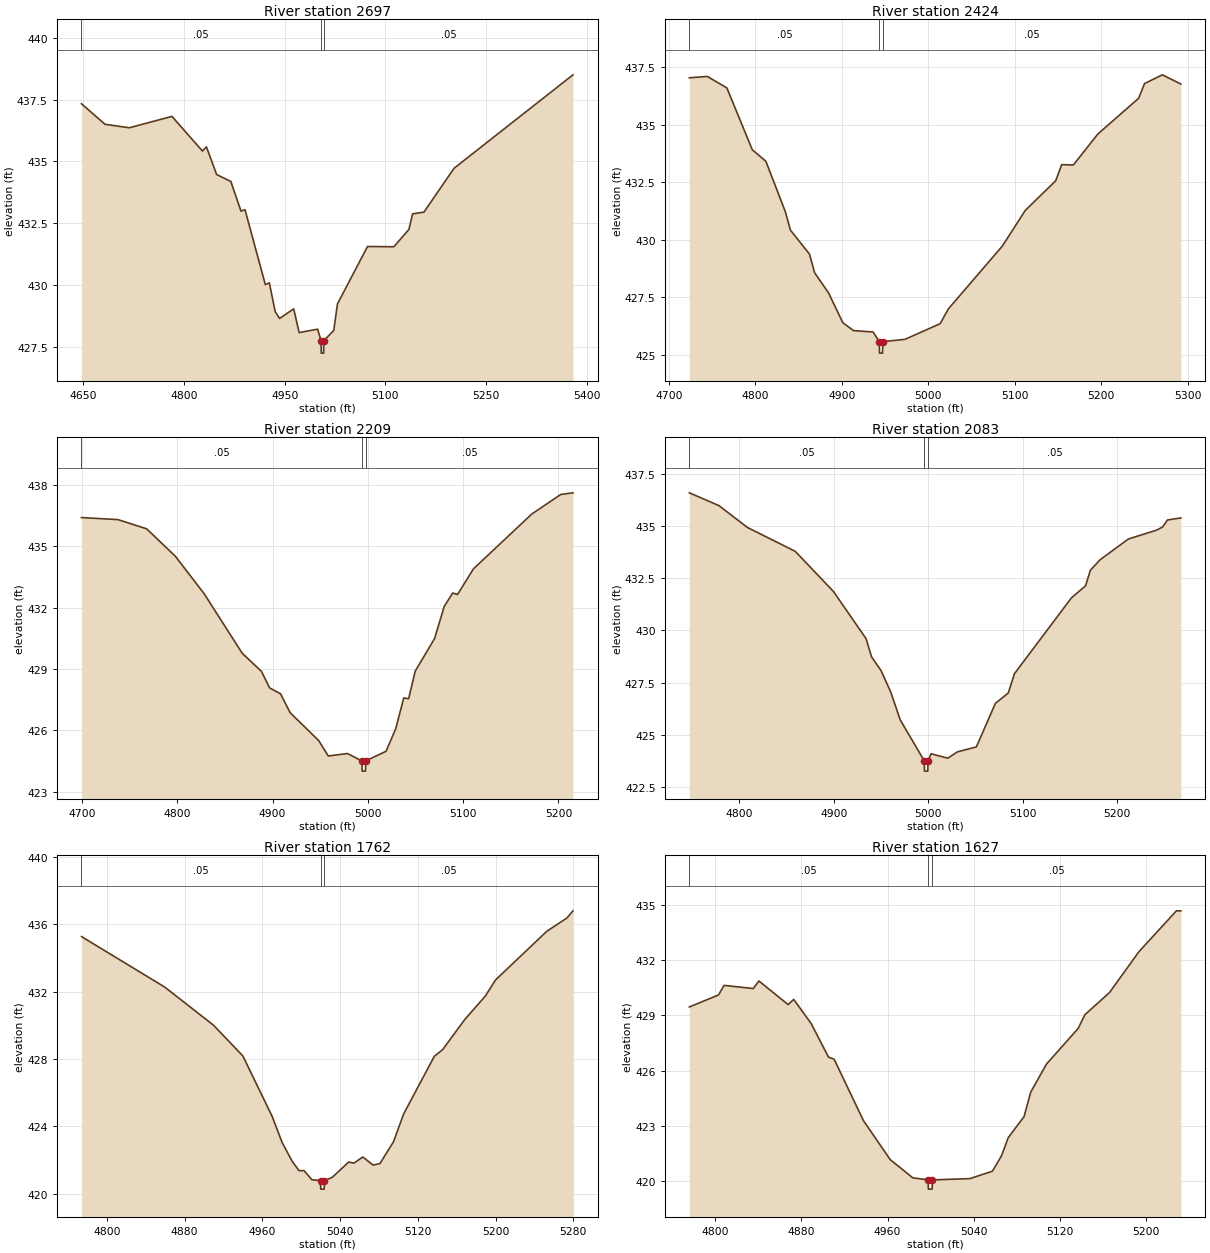
Type RM Length L Ch R = 1,2697,273,273,273
BEGIN DESCRIPTION:
Lacy 035 2919
END DESCRIPTION:
XS GIS Cut Line= 3
      2745548.70      6875195.85      2745252.15      6875386.97
      2745083.15      6875726.98
#Sta/Elev= 30
  4647.2  437.33  4682.3  436.50  4718.6  436.36  4782.0  436.82  4827.5  435.42
  4833.4  435.59  4848.6  434.47  4869.8  434.19  4884.9  432.99  4890.9  433.05
  4921.2  430.02  4927.2  430.09  4935.9  428.93  4942.4  428.65  4963.5  429.04
  4971.6  428.08  4999.1  428.22  5004.3  427.75  5004.6  427.25  5008.1  427.25
  5008.3  427.75  5023.2  428.17  5028.7  429.24  5073.5  431.56  5112.8  431.55
  5135.2  432.25  5140.7  432.88  5157.6  432.95  5202.4  434.72  5379.7  438.50
#Mann=3,-1,0
  4647.2    0.05       0  5004.3   0.035       0  5008.3    0.05       0
Bank Sta=5004.3,5008.3
Exp/Cntr=0.3,0.1

Type RM Length L Ch R = 1,2424,215,215,215
BEGIN DESCRIPTION:
Lacy 035 2918
END DESCRIPTION:
XS GIS Cut Line= 3
      2745374.48      6875031.82      2745129.30      6875159.63
      2744845.15      6875227.74
#Sta/Elev= 30
  4723.5  437.05  4744.3  437.11  4766.9  436.61  4796.3  433.92  4812.0  433.42
  4834.6  431.22  4840.5  430.42  4862.5  429.38  4868.4  428.57  4884.6  427.69
  4901.1  426.39  4913.5  426.05  4936.1  425.99  4943.3  425.57  4943.5  425.07
  4947.0  425.07  4947.3  425.57  4973.0  425.67  5013.7  426.35  5023.1  426.99
  5085.7  429.73  5112.2  431.28  5147.4  432.57  5154.3  433.27  5167.9  433.26
  5196.3  434.61  5243.4  436.16  5250.2  436.80  5270.8  437.18  5292.2  436.78
#Mann=3,-1,0
  4723.5    0.05       0  4943.3    0.04       0  4947.3    0.05       0
Bank Sta=4943.3,4947.3
Exp/Cntr=0.3,0.1

Type RM Length L Ch R = 1,2209,126,126,126
BEGIN DESCRIPTION:
Lacy 035 2917
END DESCRIPTION:
XS GIS Cut Line= 3
      2745384.18      6874983.28      2745086.86      6874957.64
      2744873.47      6874999.62
#Sta/Elev= 30
  4699.4  436.40  4737.7  436.30  4767.8  435.85  4797.9  434.51  4828.1  432.68
  4868.2  429.76  4888.3  428.88  4896.9  428.07  4908.4  427.78  4918.4  426.86
  4948.5  425.49  4958.5  424.74  4978.6  424.86  4993.7  424.50  4994.0  424.00
  4997.5  424.00  4997.7  424.50  5019.1  424.97  5029.3  426.08  5037.7  427.58
  5042.8  427.54  5049.7  428.89  5070.0  430.48  5080.2  432.06  5089.1  432.71
  5094.2  432.64  5110.8  433.89  5172.0  436.57  5202.5  437.53  5215.3  437.61
#Mann=3,-1,0
  4699.4    0.05       0  4993.7   0.035       0  4997.7    0.05       0
Bank Sta=4993.7,4997.7
Exp/Cntr=0.3,0.1

Type RM Length L Ch R = 1,2083,321,321,321
BEGIN DESCRIPTION:
Lacy 035 2916
END DESCRIPTION:
XS GIS Cut Line= 3
      2745376.96      6874808.16      2745126.69      6874845.94
      2744860.84      6874878.18
#Sta/Elev= 30
  4746.9  436.58  4778.2  435.97  4808.5  434.92  4859.1  433.78  4899.6  431.86
  4934.2  429.60  4940.0  428.73  4950.1  428.07  4960.2  427.06  4970.4  425.71
  4995.8  423.76  4996.1  423.26  4999.6  423.26  4999.8  423.76  5003.1  424.09
  5020.8  423.88  5030.9  424.18  5051.1  424.42  5071.2  426.50  5084.9  427.00
  5091.4  427.92  5151.8  431.55  5166.8  432.13  5171.9  432.87  5182.0  433.37
  5212.2  434.37  5242.5  434.80  5248.6  434.95  5253.6  435.28  5267.8  435.38
#Mann=3,-1,0
  4746.9    0.05       0  4995.8    0.04       0  4999.8    0.05       0
Bank Sta=4995.8,4999.8
Exp/Cntr=0.3,0.1

Type RM Length L Ch R = 1,1762,135,135,135
BEGIN DESCRIPTION:
Lacy 035 2915
END DESCRIPTION:
XS GIS Cut Line= 3
      2745301.04      6874514.88      2745076.43      6874540.82
      2744810.03      6874625.72
#Sta/Elev= 30
  4773.9  435.27  4859.5  432.27  4909.8  430.00  4940.0  428.17  4970.2  424.57
  4980.3  423.04  4990.4  421.94  4997.7  421.36  5002.9  421.36  5010.9  420.82
  5019.9  420.76  5020.1  420.26  5023.6  420.26  5023.9  420.76  5031.9  420.96
  5048.8  421.87  5054.1  421.80  5063.4  422.17  5073.9  421.69  5081.0  421.78
  5094.9  423.07  5105.4  424.73  5136.9  428.15  5145.5  428.55  5168.4  430.35
  5189.4  431.73  5199.9  432.69  5252.6  435.58  5273.3  436.37  5279.6  436.80
#Mann=3,-1,0
  4773.9    0.05       0  5019.9    0.04       0  5023.9    0.05       0
Bank Sta=5019.9,5023.9
Exp/Cntr=0.3,0.1

Type RM Length L Ch R = 1,1627,170,170,170
BEGIN DESCRIPTION:
Lacy 035 2914
END DESCRIPTION:
XS GIS Cut Line= 3
      2745213.61      6874366.86      2745000.18      6874434.52
      2744812.47      6874570.85
#Sta/Elev= 30
  4776.1  429.45  4803.1  430.10  4808.3  430.62  4835.4  430.45  4840.6  430.86
  4867.7  429.58  4872.9  429.86  4889.0  428.56  4905.2  426.73  4910.4  426.62
  4937.5  423.30  4962.4  421.18  4983.4  420.19  4997.6  420.08  4997.8  419.58
  5001.3  419.58  5001.6  420.08  5036.3  420.15  5057.2  420.55  5065.7  421.39
  5071.9  422.37  5086.6  423.51  5092.7  424.83  5107.4  426.36  5136.8  428.29
  5143.0  429.03  5165.8  430.23  5193.2  432.45  5227.9  434.66  5232.0  434.66
#Mann=3,-1,0
  4776.1    0.05       0  4997.6    0.04       0  5001.6    0.05       0
Bank Sta=4997.6,5001.6
Exp/Cntr=0.3,0.1

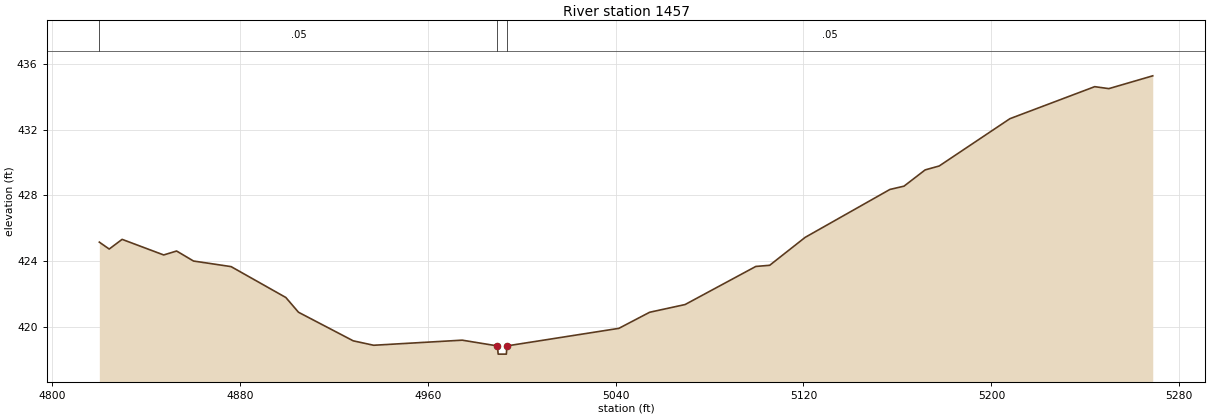
Type RM Length L Ch R = 1,1457,0,0,0
BEGIN DESCRIPTION:
Lacy 035 2913
END DESCRIPTION:
XS GIS Cut Line= 3
      2745042.65      6874243.32      2744878.43      6874316.52
      2744729.99      6874540.50
#Sta/Elev= 30
  4820.2  425.15  4824.4  424.73  4829.9  425.32  4847.6  424.37  4853.1  424.61
  4860.3  424.00  4876.3  423.66  4899.6  421.78  4905.0  420.88  4928.3  419.14
  4937.0  418.87  4974.7  419.18  4989.7  418.83  4990.0  418.33  4993.5  418.33
  4993.7  418.83  5041.4  419.90  5054.5  420.88  5069.6  421.35  5099.7  423.67
  5105.6  423.74  5120.7  425.44  5156.8  428.36  5162.8  428.56  5171.8  429.55
  5177.8  429.79  5207.9  432.67  5244.0  434.62  5250.0  434.50  5268.7  435.28
#Mann=3,-1,0
  4820.2    0.05       0  4989.7    0.04       0  4993.7    0.05       0
Bank Sta=4989.7,4993.7
Exp/Cntr=0.3,0.1

Chan Stop Cuts=-1