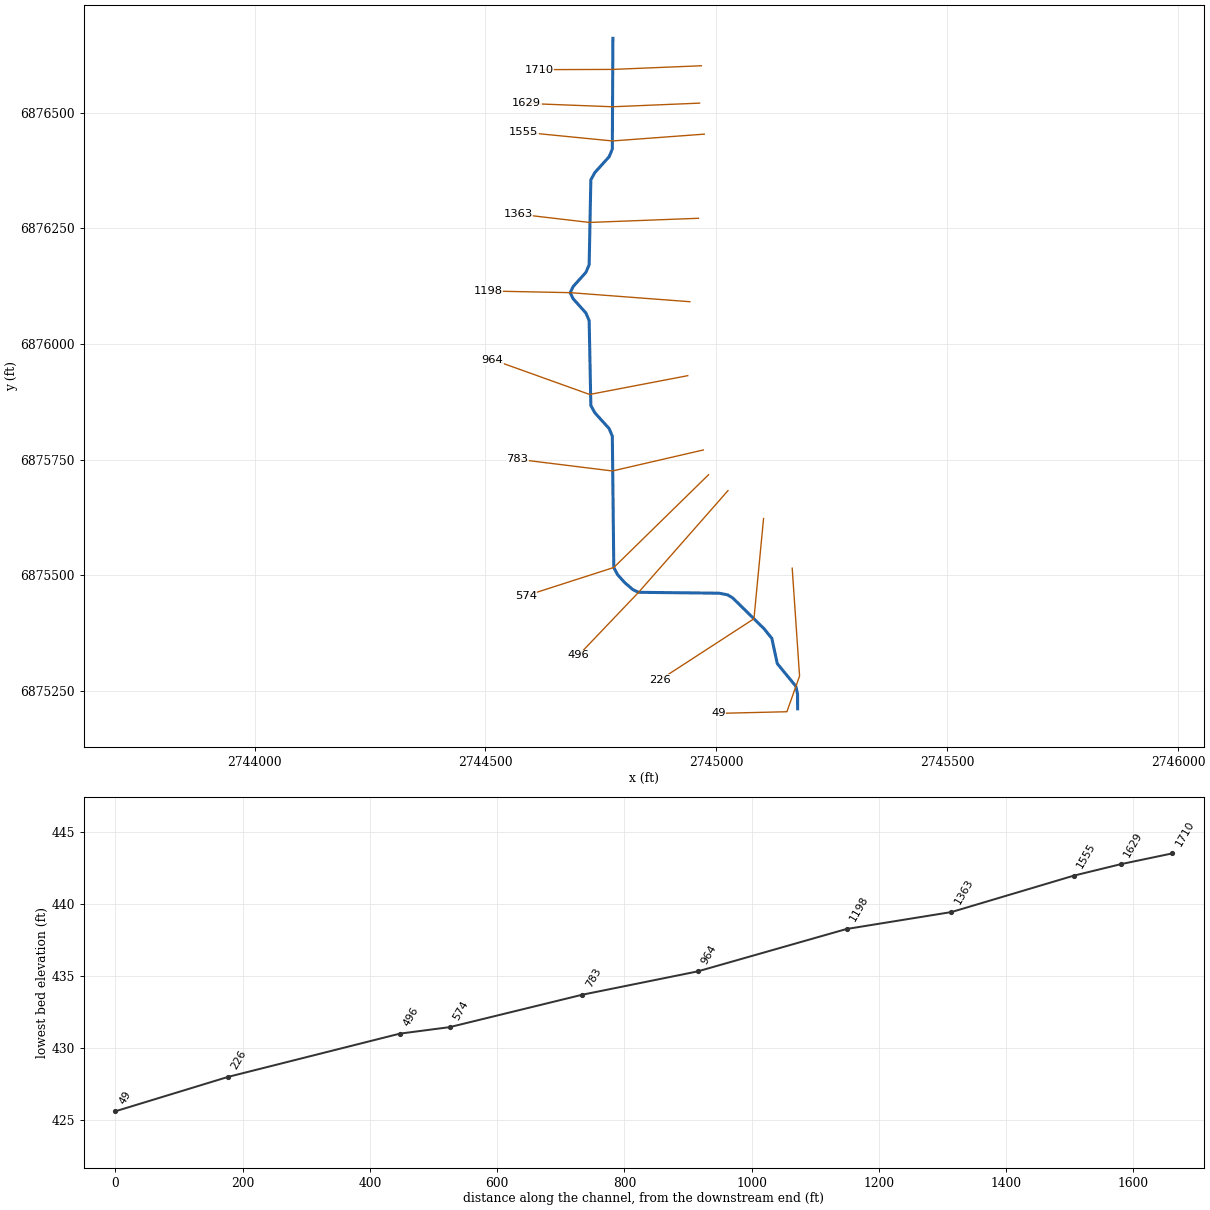
--- Lacy 036.prj (project) ---

Proj Title=Lacy 036 Base Level Engineering
Current Plan=p01
Default Exp/Contr=0.3,0.1
English Units
Geom File=g01
Flow File=f01
Plan File=p01
BEGIN DESCRIPTION:
Lacy 036
END DESCRIPTION:

--- Lacy 036.p01 (plan) ---

Plan Title=Multiple Run
Short Identifier=Multiple
Geom File=g01
Flow File=f01
Subcritical Flow
K Sum by GR= 0
Std Step Tol= 0.01
Critical Tol= 0.01
Num of Std Step Trials= 20
Max Error Tol= 0.3
Flow Tol Ratio= 0.001
Split Flow NTrial= 30
Split Flow Tol= 0.02
Split Flow Ratio= 0.02
Log Output Level= 0
Friction Slope Method= 1
Unsteady Friction Slope Method= 2
Unsteady Bridges Friction Slope Method= 1
Parabolic Critical Depth
Global Vel Dist=  1 , 1 , 1
Global Log Level= 0
CheckData=True
Encroach Param= -1, 0, 0, 0
BEGIN DESCRIPTION:
Multiple Run
END DESCRIPTION:

--- Lacy 036.f01 (steady flow) ---

Flow Title=Multiple
Number of Profiles=7
Profile Names=10-year,25-year,50-year,1pct_min,100-year,1pct_plu,500-year
River Rch & RM= Lacy 036,Reach-1,1710
      68      78      85      46      92     184     109
Boundary for River Rch & Prof#=Lacy 036,Reach-1,1
Up Type=0
Dn Type=3
Dn Slope=0.005
Boundary for River Rch & Prof#=Lacy 036,Reach-1,2
Up Type=0
Dn Type=3
Dn Slope=0.005
Boundary for River Rch & Prof#=Lacy 036,Reach-1,3
Up Type=0
Dn Type=3
Dn Slope=0.005
Boundary for River Rch & Prof#=Lacy 036,Reach-1,4
Up Type=0
Dn Type=3
Dn Slope=0.005
Boundary for River Rch & Prof#=Lacy 036,Reach-1,5
Up Type=0
Dn Type=3
Dn Slope=0.005
Boundary for River Rch & Prof#=Lacy 036,Reach-1,6
Up Type=0
Dn Type=3
Dn Slope=0.005
Boundary for River Rch & Prof#=Lacy 036,Reach-1,7
Up Type=0
Dn Type=3
Dn Slope=0.005

--- Lacy 036.g01 (geometry) ---

Geom Title=Existing Conditions

River Reach=Lacy 036,Reach-1
Reach XY= 30
      2744776.00      6876661.00      2744774.78      6876421.50
      2744767.86      6876404.94      2744736.85      6876370.65
      2744728.26      6876355.06      2744724.62      6876171.44
      2744717.55      6876154.82      2744689.95      6876124.21
      2744683.56      6876111.00      2744689.95      6876097.79
      2744717.55      6876067.18      2744724.62      6876050.56
      2744728.26      6875866.94      2744736.85      6875851.35
      2744767.86      6875817.06      2744774.78      6875800.50
      2744777.97      6875516.65      2744786.32      6875500.82
      2744801.97      6875483.65      2744819.48      6875468.67
      2744831.65      6875462.97      2745006.02      6875461.04
      2745024.55      6875457.47      2745035.82      6875450.53
      2745103.02      6875384.52      2745120.19      6875363.32
      2745131.98      6875308.76      2745172.40      6875259.51
      2745175.90      6875242.81      2745176.00      6875211.00

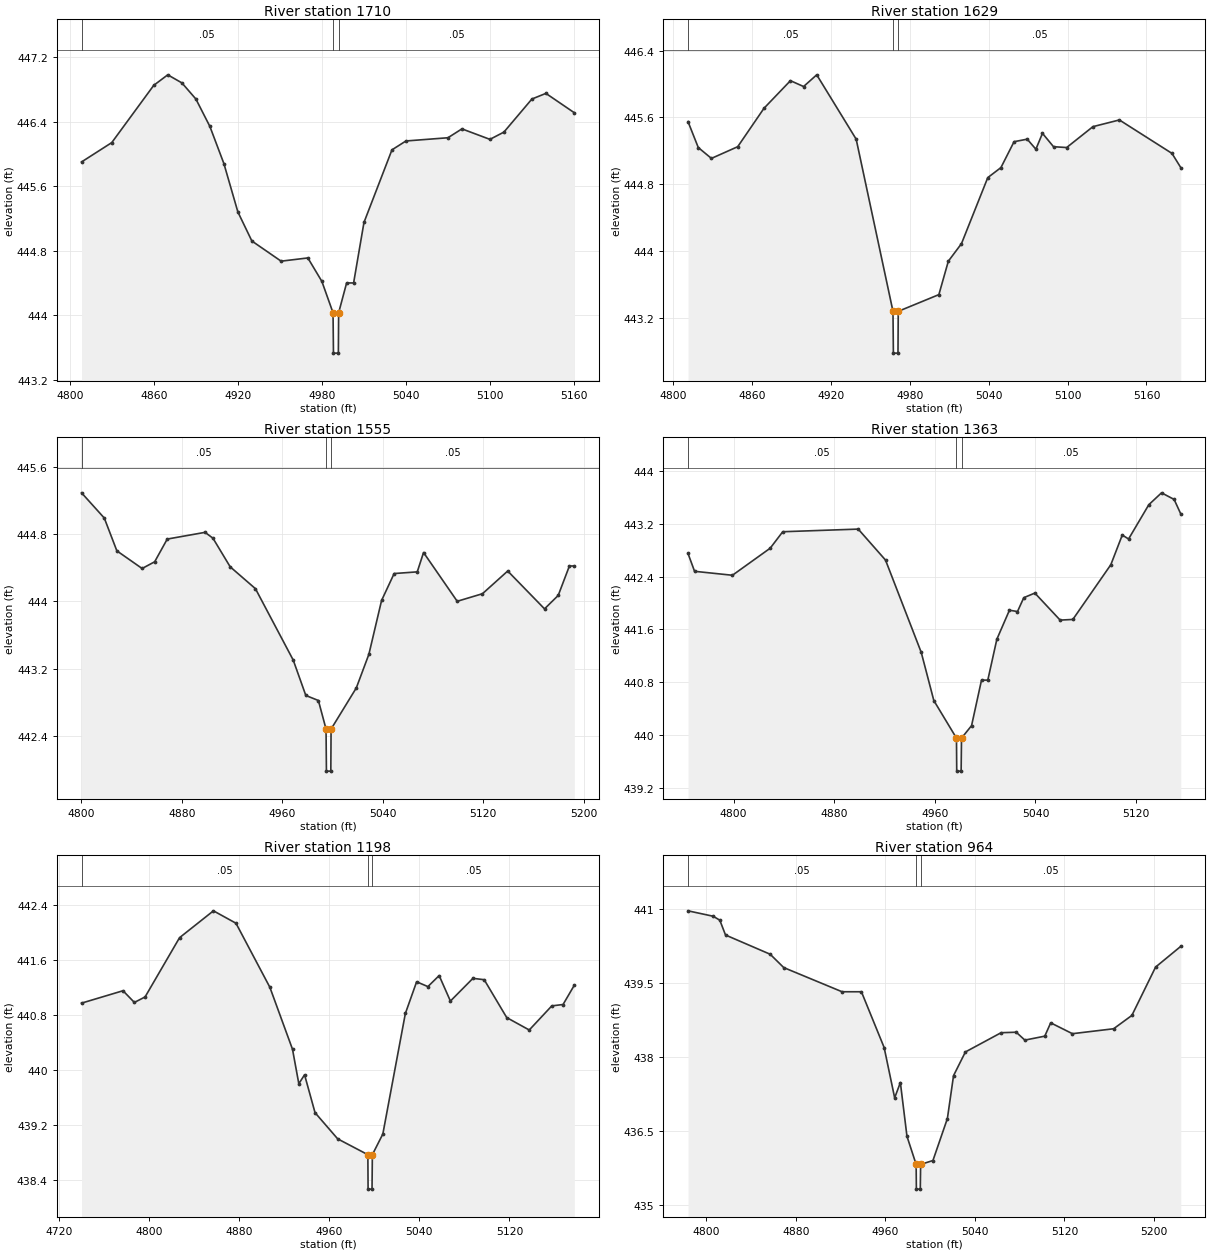
Type RM Length L Ch R = 1,1710,81,81,81
BEGIN DESCRIPTION:
Lacy 036 2942
END DESCRIPTION:
XS GIS Cut Line= 3
      2744967.59      6876601.71      2744775.66      6876593.79
      2744615.66      6876593.28
#Sta/Elev= 29
  4807.9  445.90  4829.5  446.14  4859.5  446.85  4869.5  446.98  4879.6  446.88
  4889.6  446.68  4899.6  446.34  4909.6  445.88  4919.6  445.28  4929.6  444.92
  4950.5  444.67  4969.6  444.71  4979.6  444.42  4987.6  444.03  4987.9  443.53
  4991.4  443.53  4991.6  444.03  4997.3  444.40  5002.3  444.40  5009.7  445.15
  5029.7  446.05  5039.7  446.16  5069.7  446.20  5079.7  446.31  5099.7  446.18
  5109.7  446.27  5129.7  446.68  5139.7  446.75  5160.0  446.51
#Mann=3,-1,0
  4807.9    0.05       0  4987.6    0.04       0  4991.6    0.05       0
Bank Sta=4987.6,4991.6
Exp/Cntr=0.3,0.1

Type RM Length L Ch R = 1,1629,74,74,74
BEGIN DESCRIPTION:
Lacy 036 2941
END DESCRIPTION:
XS GIS Cut Line= 3
      2744963.78      6876520.87      2744775.25      6876513.01
      2744589.29      6876520.19
#Sta/Elev= 28
  4811.3  445.55  4819.1  445.24  4829.1  445.11  4849.1  445.25  4869.1  445.71
  4889.2  446.04  4899.2  445.97  4909.2  446.11  4939.2  445.34  4967.2  443.28
  4967.5  442.78  4971.0  442.78  4971.2  443.28  5002.1  443.48  5009.3  443.88
  5019.3  444.09  5039.3  444.88  5049.3  445.00  5059.3  445.31  5069.3  445.34
  5075.9  445.22  5080.9  445.41  5089.3  445.25  5099.3  445.24  5119.3  445.49
  5139.4  445.57  5179.4  445.17  5186.1  445.00
#Mann=3,-1,0
  4811.3    0.05       0  4967.2    0.04       0  4971.2    0.05       0
Bank Sta=4967.2,4971.2
Exp/Cntr=0.3,0.1

Type RM Length L Ch R = 1,1555,192,192,192
BEGIN DESCRIPTION:
Lacy 036 2940
END DESCRIPTION:
XS GIS Cut Line= 3
      2744974.03      6876453.83      2744774.87      6876439.07
      2744583.30      6876457.92
#Sta/Elev= 30
  4800.3  445.29  4818.4  444.99  4828.4  444.60  4848.5  444.39  4858.5  444.47
  4868.5  444.74  4898.6  444.82  4904.9  444.75  4918.6  444.41  4938.7  444.15
  4968.8  443.30  4978.8  442.88  4988.8  442.82  4994.9  442.48  4995.2  441.98
  4998.7  441.98  4998.9  442.48  5019.0  442.97  5029.0  443.37  5039.1  444.01
  5049.1  444.33  5067.5  444.35  5072.5  444.58  5099.3  444.00  5119.4  444.09
  5139.5  444.36  5168.8  443.91  5179.7  444.07  5188.6  444.42  5192.5  444.42
#Mann=3,-1,0
  4800.3    0.05       0  4994.9   0.035       0  4998.9    0.05       0
Bank Sta=4994.9,4998.9
Exp/Cntr=0.3,0.1

Type RM Length L Ch R = 1,1363,165,165,165
BEGIN DESCRIPTION:
Lacy 036 2939
END DESCRIPTION:
XS GIS Cut Line= 3
      2744961.24      6876271.84      2744725.21      6876262.86
      2744570.76      6876280.94
#Sta/Elev= 30
  4763.8  442.75  4769.0  442.48  4799.1  442.42  4829.1  442.83  4839.1  443.08
  4899.1  443.12  4920.8  442.65  4949.2  441.25  4959.2  440.52  4977.2  439.95
  4977.4  439.45  4980.9  439.45  4981.2  439.95  4989.2  440.14  4997.1  440.83
  5002.1  440.83  5009.3  441.45  5019.3  441.89  5025.7  441.87  5030.7  442.08
  5039.5  442.15  5059.6  441.74  5069.7  441.75  5099.9  442.58  5109.0  443.03
  5114.0  442.97  5130.1  443.49  5140.2  443.67  5150.2  443.57  5155.5  443.35
#Mann=3,-1,0
  4763.8    0.05       0  4977.2   0.035       0  4981.2    0.05       0
Bank Sta=4977.2,4981.2
Exp/Cntr=0.3,0.1

Type RM Length L Ch R = 1,1198,234,234,234
BEGIN DESCRIPTION:
Lacy 036 2938
END DESCRIPTION:
XS GIS Cut Line= 3
      2744942.72      6876091.40      2744683.56      6876111.00
      2744506.00      6876114.57
#Sta/Elev= 30
  4740.1  440.97  4776.9  441.15  4787.0  440.98  4796.5  441.06  4827.1  441.92
  4857.2  442.31  4877.2  442.13  4907.3  441.20  4927.4  440.30  4933.0  439.80
  4938.1  439.93  4947.4  439.38  4967.5  439.00  4994.3  438.77  4994.5  438.27
  4998.0  438.27  4998.3  438.77  5007.6  439.07  5027.6  440.82  5037.6  441.28
  5047.6  441.21  5057.6  441.37  5067.6  441.00  5087.6  441.33  5097.6  441.31
  5117.6  440.76  5137.6  440.58  5157.6  440.93  5167.6  440.95  5177.6  441.23
#Mann=3,-1,0
  4740.1    0.05       0  4994.3    0.04       0  4998.3    0.05       0
Bank Sta=4994.3,4998.3
Exp/Cntr=0.3,0.1

Type RM Length L Ch R = 1,964,181,181,181
BEGIN DESCRIPTION:
Lacy 036 2937
END DESCRIPTION:
XS GIS Cut Line= 3
      2744938.10      6875931.47      2744725.65      6875890.85
      2744514.86      6875966.35
#Sta/Elev= 30
  4783.7  440.96  4806.2  440.85  4812.1  440.77  4817.2  440.47  4857.1  440.08
  4869.2  439.81  4921.3  439.32  4938.6  439.32  4958.9  438.19  4968.3  437.17
  4973.4  437.48  4979.3  436.39  4987.5  435.82  4987.7  435.32  4991.2  435.32
  4991.5  435.82  5002.5  435.90  5015.4  436.75  5020.9  437.62  5031.5  438.10
  5063.4  438.49  5076.9  438.50  5084.6  438.34  5102.4  438.42  5107.7  438.69
  5127.1  438.47  5163.9  438.57  5180.2  438.84  5201.4  439.82  5223.9  440.24
#Mann=3,-1,0
  4783.7    0.05       0  4987.5   0.035       0  4991.5    0.05       0
Bank Sta=4987.5,4991.5
Exp/Cntr=0.3,0.1

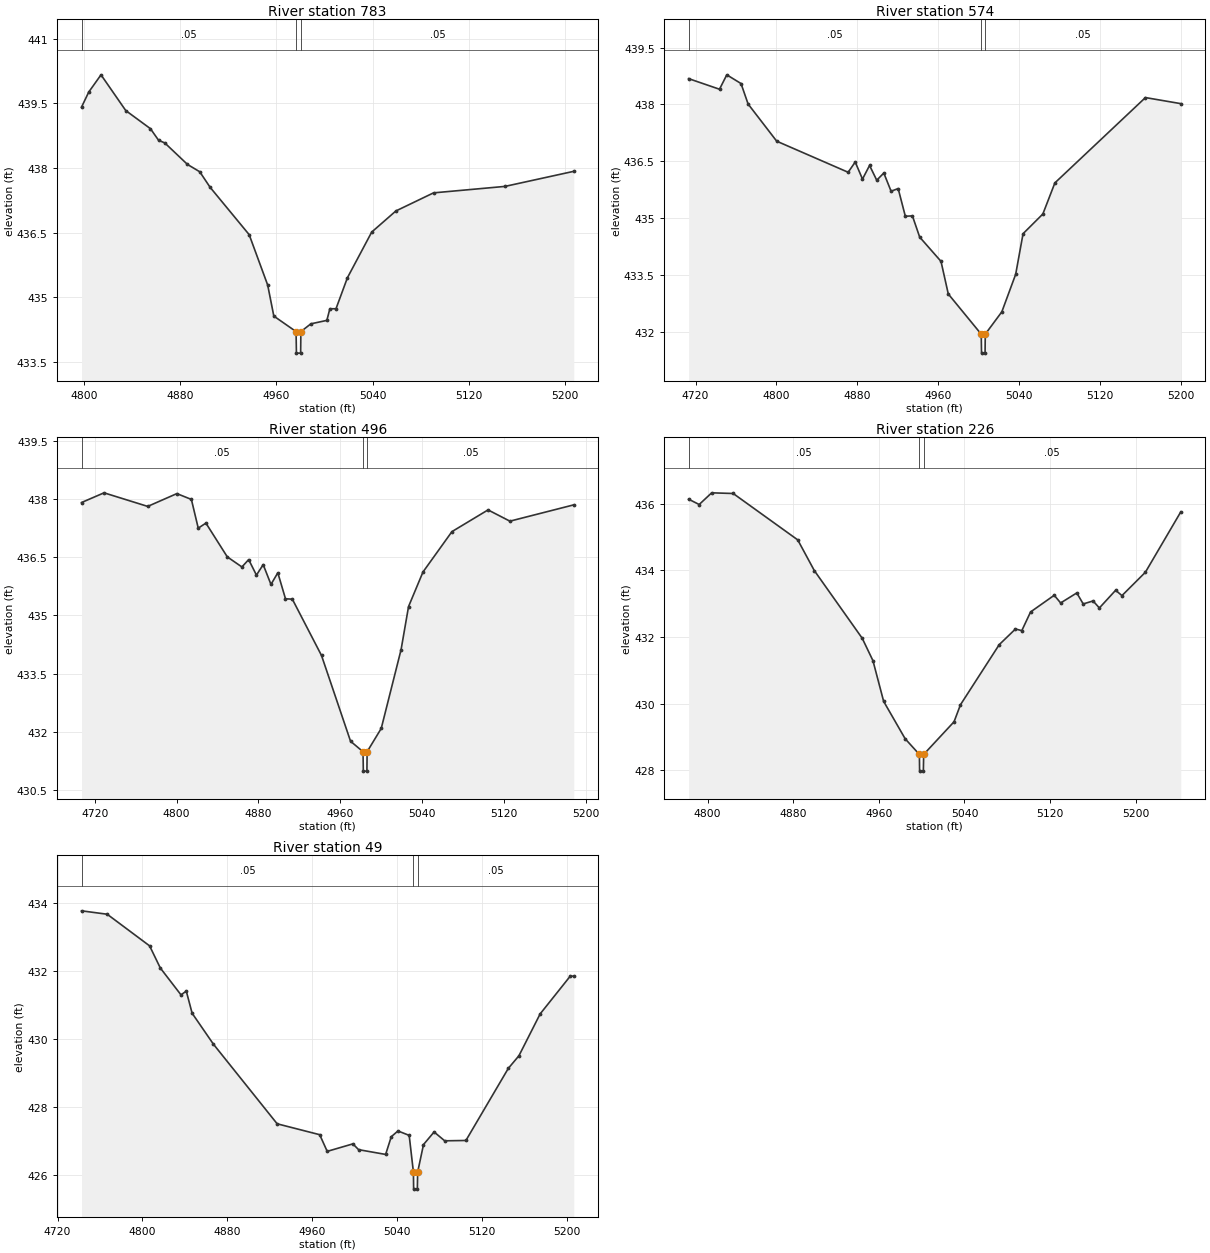
Type RM Length L Ch R = 1,783,209,209,209
BEGIN DESCRIPTION:
Lacy 036 2936
END DESCRIPTION:
XS GIS Cut Line= 3
      2744971.83      6875770.78      2744775.00      6875725.39
      2744569.26      6875750.77
#Sta/Elev= 27
  4798.0  439.41  4804.0  439.76  4814.2  440.16  4834.8  439.33  4855.3  438.91
  4862.1  438.64  4867.2  438.58  4886.1  438.08  4896.3  437.91  4904.9  437.55
  4937.4  436.45  4952.8  435.28  4957.9  434.56  4976.4  434.20  4976.7  433.70
  4980.2  433.70  4980.4  434.20  4988.7  434.38  5002.0  434.46  5004.5  434.73
  5009.6  434.73  5019.1  435.45  5039.3  436.51  5059.4  437.00  5090.7  437.42
  5150.1  437.57  5207.3  437.92
#Mann=3,-1,0
  4798.0    0.05       0  4976.4   0.035       0  4980.4    0.05       0
Bank Sta=4976.4,4980.4
Exp/Cntr=0.3,0.1

Type RM Length L Ch R = 1,574,78,78,78
BEGIN DESCRIPTION:
Lacy 036 2935
END DESCRIPTION:
XS GIS Cut Line= 3
      2744983.11      6875717.22      2744777.97      6875516.65
      2744587.37      6875455.39
#Sta/Elev= 30
  4713.1  438.68  4743.7  438.40  4750.9  438.78  4765.0  438.55  4772.0  438.01
  4800.3  437.03  4871.0  436.21  4878.0  436.48  4885.2  436.03  4892.2  436.39
  4899.3  436.00  4906.3  436.19  4913.5  435.71  4920.5  435.78  4927.6  435.05
  4934.6  435.06  4941.8  434.50  4962.9  433.86  4970.1  433.00  5002.7  431.94
  5003.0  431.44  5006.5  431.44  5006.7  431.94  5023.1  432.53  5036.8  433.52
  5044.1  434.59  5063.7  435.11  5075.6  435.93  5165.2  438.18  5200.2  438.02
#Mann=3,-1,0
  4713.1    0.05       0  5002.7   0.035       0  5006.7    0.05       0
Bank Sta=5002.7,5006.7
Exp/Cntr=0.3,0.1

Type RM Length L Ch R = 1,496,270,270,270
BEGIN DESCRIPTION:
Lacy 036 2934
END DESCRIPTION:
XS GIS Cut Line= 3
      2745025.26      6875682.89      2744831.65      6875462.97
      2744701.64      6875326.90
#Sta/Elev= 30
  4707.0  437.91  4729.0  438.16  4771.7  437.81  4800.2  438.14  4814.4  437.99
  4821.1  437.25  4828.6  437.38  4849.5  436.51  4863.8  436.25  4870.4  436.44
  4878.0  436.04  4884.6  436.31  4892.2  435.80  4898.9  436.10  4906.4  435.43
  4913.1  435.42  4941.6  433.97  4970.0  431.76  4982.2  431.49  4982.5  430.99
  4986.0  430.99  4986.2  431.49  5000.0  432.09  5019.4  434.12  5026.7  435.23
  5040.8  436.12  5069.1  437.16  5104.4  437.72  5125.8  437.43  5188.2  437.85
#Mann=3,-1,0
  4707.0    0.05       0  4982.2   0.035       0  4986.2    0.05       0
Bank Sta=4982.2,4986.2
Exp/Cntr=0.3,0.1

Type RM Length L Ch R = 1,226,177,177,177
BEGIN DESCRIPTION:
Lacy 036 2933
END DESCRIPTION:
XS GIS Cut Line= 3
      2745102.27      6875622.51      2745081.46      6875405.71
      2744878.24      6875273.93
#Sta/Elev= 30
  4782.2  436.13  4792.1  435.97  4803.8  436.32  4823.9  436.30  4884.2  434.91
  4899.7  433.99  4944.5  431.96  4954.5  431.29  4964.5  430.07  4984.6  428.95
  4997.9  428.48  4998.1  427.98  5001.6  427.98  5001.9  428.48  5030.3  429.46
  5036.3  429.97  5072.5  431.77  5087.7  432.24  5093.6  432.19  5101.8  432.75
  5123.9  433.25  5129.9  433.02  5145.0  433.32  5151.0  432.99  5160.2  433.08
  5166.1  432.87  5181.3  433.40  5187.2  433.24  5209.1  433.94  5242.2  435.75
#Mann=3,-1,0
  4782.2    0.05       0  4997.9    0.04       0  5001.9    0.05       0
Bank Sta=4997.9,5001.9
Exp/Cntr=0.3,0.1

Type RM Length L Ch R = 1,49,0,0,0
BEGIN DESCRIPTION:
Lacy 036 2932
END DESCRIPTION:
XS GIS Cut Line= 4
      2745164.31      6875515.10      2745180.23      6875281.87
      2745152.82      6875204.71      2745004.32      6875201.15
#Sta/Elev= 30
  4742.6  433.77  4766.8  433.67  4806.8  432.74  4816.9  432.09  4836.4  431.30
  4841.4  431.41  4846.9  430.76  4867.0  429.85  4927.1  427.51  4967.2  427.19
  4974.3  426.70  4998.5  426.92  5003.9  426.75  5029.4  426.61  5034.7  427.13
  5041.0  427.30  5051.6  427.17  5055.6  426.09  5055.8  425.59  5059.3  425.59
  5059.6  426.09  5065.1  426.90  5075.1  427.27  5085.1  427.01  5105.1  427.02
  5145.1  429.14  5155.1  429.51  5175.1  430.74  5203.5  431.85  5206.8  431.85
#Mann=3,-1,0
  4742.6    0.05       0  5055.6   0.035       0  5059.6    0.05       0
Bank Sta=5055.6,5059.6
Exp/Cntr=0.3,0.1

Chan Stop Cuts=-1