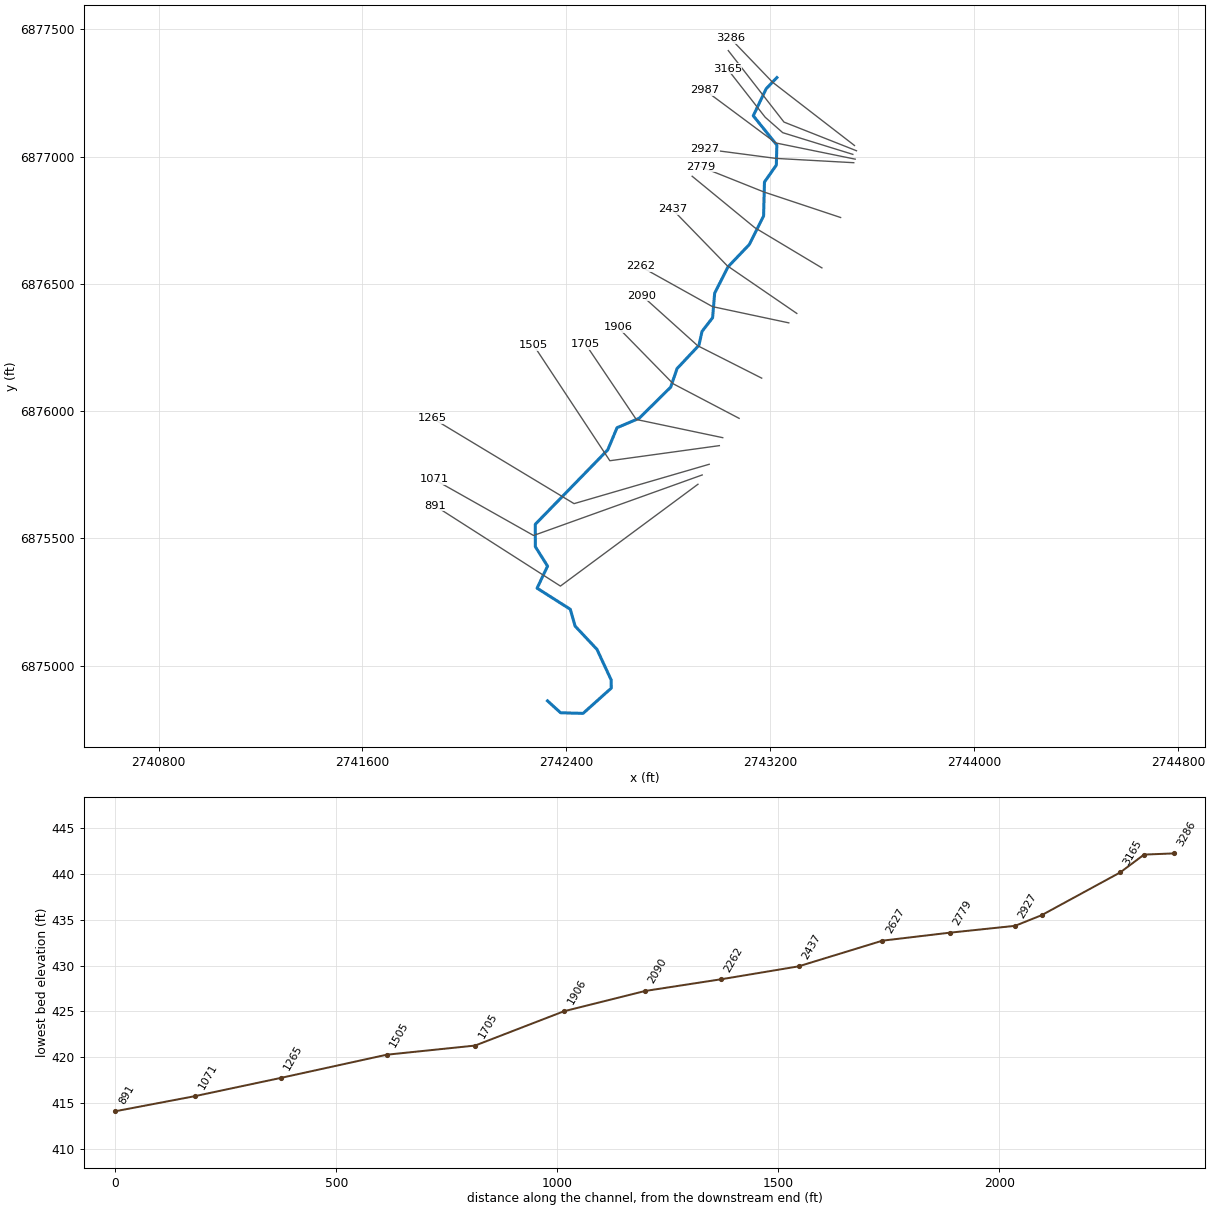
--- Lacy 037.prj (project) ---

Proj Title=Lacy 037 Base Level Engineering
Current Plan=p01
Default Exp/Contr=0.3,0.1
English Units
Geom File=g01
Flow File=f01
Plan File=p01
BEGIN DESCRIPTION:
Lacy 037
END DESCRIPTION:

--- Lacy 037.p01 (plan) ---

Plan Title=Multiple Run
Short Identifier=Multiple
Geom File=g01
Flow File=f01
Subcritical Flow
K Sum by GR= 0
Std Step Tol= 0.01
Critical Tol= 0.01
Num of Std Step Trials= 20
Max Error Tol= 0.3
Flow Tol Ratio= 0.001
Split Flow NTrial= 30
Split Flow Tol= 0.02
Split Flow Ratio= 0.02
Log Output Level= 0
Friction Slope Method= 1
Unsteady Friction Slope Method= 2
Unsteady Bridges Friction Slope Method= 1
Parabolic Critical Depth
Global Vel Dist=  1 , 1 , 1
Global Log Level= 0
CheckData=True
Encroach Param= -1, 0, 0, 0
BEGIN DESCRIPTION:
Multiple Run
END DESCRIPTION:

--- Lacy 037.f01 (steady flow) ---

Flow Title=Multiple
Number of Profiles=7
Profile Names=10-year,25-year,50-year,1pct_min,100-year,1pct_plu,500-year
River Rch & RM= Lacy 037,Reach-1,3286
     156     193     219     125     250     498     322
Boundary for River Rch & Prof#=Lacy 037,Reach-1,1
Up Type=0
Dn Type=3
Dn Slope=0.005
Boundary for River Rch & Prof#=Lacy 037,Reach-1,2
Up Type=0
Dn Type=3
Dn Slope=0.005
Boundary for River Rch & Prof#=Lacy 037,Reach-1,3
Up Type=0
Dn Type=3
Dn Slope=0.005
Boundary for River Rch & Prof#=Lacy 037,Reach-1,4
Up Type=0
Dn Type=3
Dn Slope=0.005
Boundary for River Rch & Prof#=Lacy 037,Reach-1,5
Up Type=0
Dn Type=3
Dn Slope=0.005
Boundary for River Rch & Prof#=Lacy 037,Reach-1,6
Up Type=0
Dn Type=3
Dn Slope=0.005
Boundary for River Rch & Prof#=Lacy 037,Reach-1,7
Up Type=0
Dn Type=3
Dn Slope=0.005

--- Lacy 037.g01 (geometry) ---

Geom Title=Existing Conditions

River Reach=Lacy 037,Reach-1
Reach XY= 30
      2743226.00      6877311.00      2743183.88      6877267.14
      2743133.28      6877160.92      2743225.75      6877045.78
      2743223.84      6876966.98      2743177.23      6876900.49
      2743173.75      6876766.93      2743117.84      6876654.95
      2743034.16      6876567.05      2742981.77      6876463.32
      2742973.67      6876366.97      2742932.14      6876313.17
      2742920.16      6876258.71      2742834.18      6876167.04
      2742809.35      6876094.33      2742685.66      6875971.79
      2742598.86      6875934.84      2742562.36      6875847.80
      2742277.96      6875555.11      2742278.19      6875466.97
      2742326.20      6875390.79      2742285.03      6875303.99
      2742415.35      6875221.00      2742434.18      6875154.98
      2742520.17      6875063.30      2742575.90      6874942.81
      2742576.00      6874911.00      2742465.55      6874811.89
      2742377.40      6874814.18      2742326.00      6874861.00

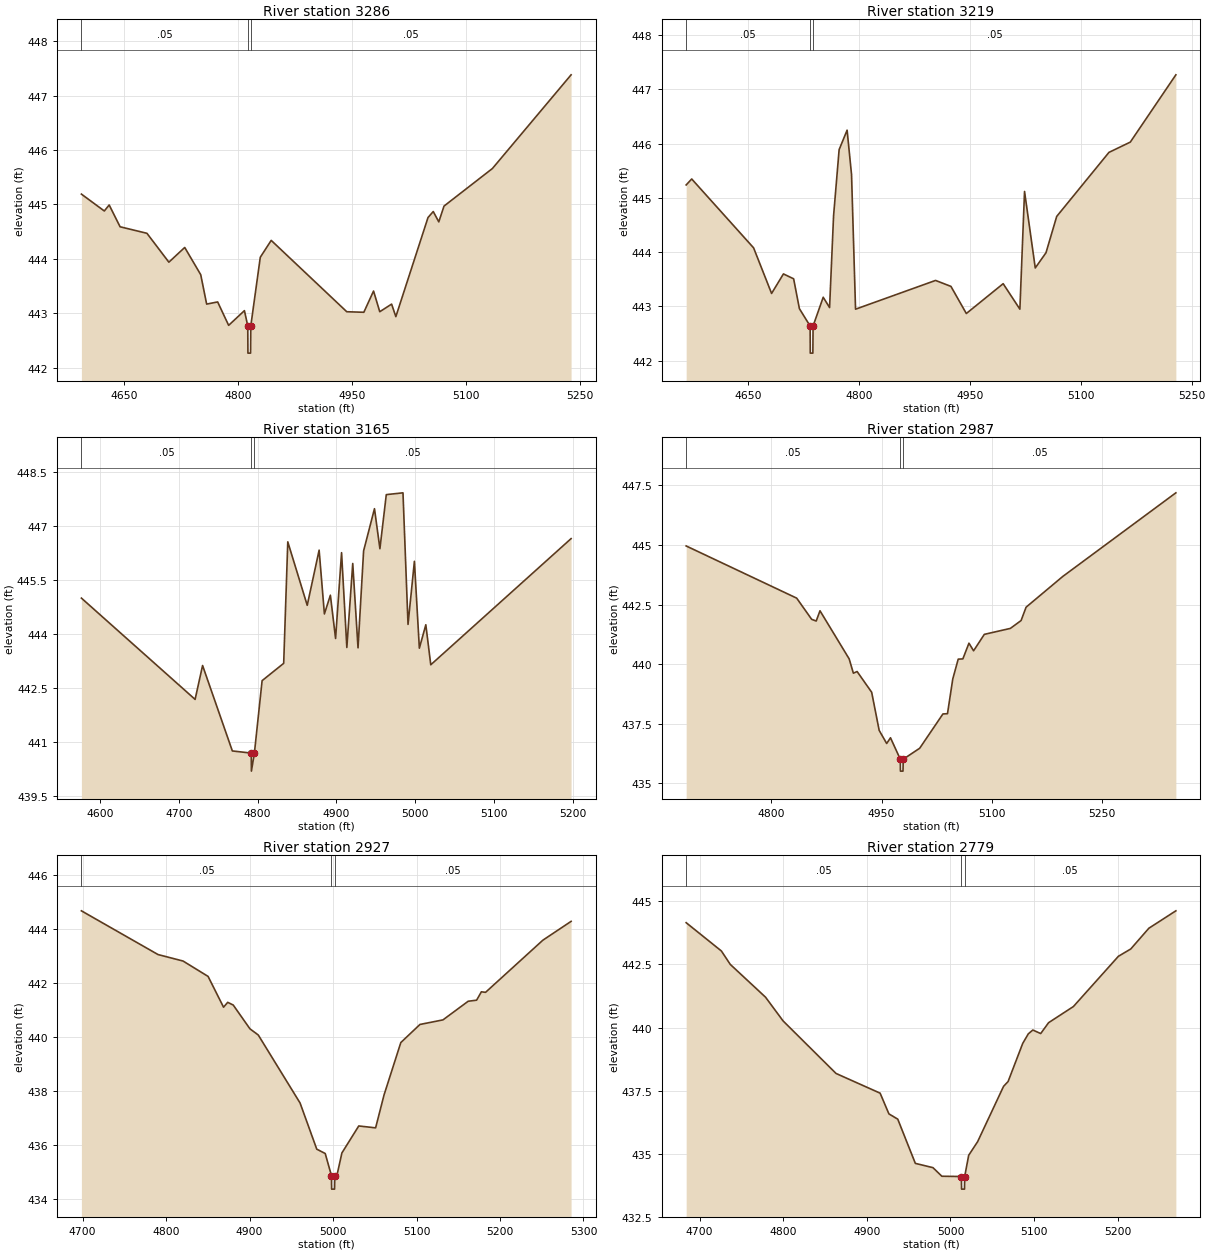
Type RM Length L Ch R = 1,3286,67,67,67
BEGIN DESCRIPTION:
Lacy 037 2885
END DESCRIPTION:
XS GIS Cut Line= 3
      2743530.42      6877044.02      2743208.71      6877292.99
      2743043.47      6877465.26
#Sta/Elev= 30
  4593.2  445.19  4623.4  444.88  4629.8  444.99  4644.2  444.59  4679.6  444.47
  4708.5  443.94  4729.4  444.21  4750.5  443.71  4758.3  443.17  4772.8  443.21
  4787.3  442.78  4808.1  443.05  4812.5  442.77  4812.7  442.27  4816.2  442.27
  4816.5  442.77  4829.0  444.03  4843.4  444.34  4943.0  443.03  4965.5  443.02
  4978.3  443.41  4986.5  443.03  5002.1  443.17  5007.7  442.94  5050.1  444.76
  5057.0  444.87  5064.3  444.68  5071.2  444.97  5135.0  445.66  5238.7  447.38
#Mann=3,-1,0
  4593.2    0.05       0  4812.5   0.035       0  4816.5    0.05       0
Bank Sta=4812.5,4816.5
Exp/Cntr=0.3,0.1

Type RM Length L Ch R = 1,3219,54,54,54
BEGIN DESCRIPTION:
Lacy 037 2883
END DESCRIPTION:
XS GIS Cut Line= 3
      2743538.30      6877023.39      2743253.83      6877136.09
      2743035.18      6877417.18
#Sta/Elev= 30
  4566.5  445.24  4574.0  445.35  4657.7  444.08  4682.0  443.24  4698.0  443.60
  4711.8  443.51  4719.6  442.96  4734.1  442.64  4734.3  442.14  4737.8  442.14
  4738.1  442.64  4751.8  443.17  4760.4  442.98  4765.8  444.67  4773.3  445.89
  4784.1  446.25  4790.1  445.43  4795.5  442.95  4903.7  443.48  4924.5  443.37
  4945.3  442.87  4995.1  443.42  5017.7  442.95  5024.0  445.12  5038.5  443.71
  5053.0  443.99  5067.5  444.66  5138.1  445.84  5167.0  446.03  5228.6  447.27
#Mann=3,-1,0
  4566.5    0.05       0  4734.1   0.035       0  4738.1    0.05       0
Bank Sta=4734.1,4738.1
Exp/Cntr=0.3,0.1

Type RM Length L Ch R = 1,3165,178,178,178
BEGIN DESCRIPTION:
Lacy 037 2881
END DESCRIPTION:
XS GIS Cut Line= 4
      2743523.94      6877009.21      2743248.95      6877094.41
      2743180.00      6877155.10      2743031.05      6877346.03
#Sta/Elev= 30
  4576.2  444.99  4720.6  442.18  4730.1  443.12  4767.9  440.75  4791.9  440.69
  4792.1  440.19  4795.9  440.69  4805.7  442.70  4833.1  443.18  4838.3  446.55
  4863.0  444.79  4878.1  446.32  4884.8  444.55  4892.4  445.07  4899.0  443.87
  4906.6  446.25  4913.3  443.62  4920.8  445.95  4927.5  443.61  4934.6  446.30
  4948.4  447.47  4955.3  446.36  4963.4  447.86  4984.6  447.91  4991.0  444.26
  4999.1  446.01  5005.4  443.60  5013.6  444.25  5019.9  443.14  5198.1  446.64
#Mann=3,-1,0
  4576.2    0.05       0  4791.9   0.035       0  4795.9    0.05       0
Bank Sta=4791.9,4795.9
Exp/Cntr=0.3,0.1

Type RM Length L Ch R = 1,2987,60,60,60
BEGIN DESCRIPTION:
Lacy 037 2882
END DESCRIPTION:
XS GIS Cut Line= 3
      2743533.23      6876990.37      2743222.04      6877053.94
      2742942.62      6877262.01
#Sta/Elev= 30
  4684.3  444.96  4834.6  442.77  4855.0  441.88  4861.2  441.81  4866.3  442.24
  4906.0  440.22  4911.7  439.62  4916.8  439.69  4936.6  438.82  4946.8  437.22
  4957.0  436.67  4962.2  436.91  4975.5  436.01  4975.7  435.51  4979.2  435.51
  4979.5  436.01  5001.9  436.47  5033.5  437.91  5039.7  437.92  5046.9  439.38
  5054.3  440.21  5060.6  440.22  5068.9  440.88  5075.2  440.56  5089.8  441.25
  5125.2  441.50  5139.8  441.83  5146.6  442.39  5196.5  443.68  5350.3  447.19
#Mann=3,-1,0
  4684.3    0.05       0  4975.5    0.04       0  4979.5    0.05       0
Bank Sta=4975.5,4979.5
Exp/Cntr=0.3,0.1

Type RM Length L Ch R = 1,2927,148,148,148
BEGIN DESCRIPTION:
Lacy 037 2880
END DESCRIPTION:
XS GIS Cut Line= 3
      2743527.61      6876976.39      2743222.02      6876993.32
      2742943.78      6877029.96
#Sta/Elev= 30
  4698.5  444.66  4790.3  443.04  4820.3  442.80  4850.3  442.23  4868.8  441.09
  4873.8  441.27  4880.4  441.17  4900.4  440.29  4910.4  440.06  4960.5  437.54
  4980.5  435.83  4990.6  435.67  4998.1  434.85  4998.3  434.35  5001.8  434.35
  5002.1  434.85  5004.6  434.85  5010.6  435.69  5030.8  436.69  5051.0  436.62
  5061.1  437.84  5081.2  439.78  5104.1  440.45  5131.7  440.62  5161.9  441.31
  5172.0  441.35  5177.7  441.66  5182.7  441.64  5251.3  443.57  5285.2  444.27
#Mann=3,-1,0
  4698.5    0.05       0  4998.1    0.04       0  5002.1    0.05       0
Bank Sta=4998.1,5002.1
Exp/Cntr=0.3,0.1

Type RM Length L Ch R = 1,2779,152,152,152
BEGIN DESCRIPTION:
Lacy 037 70
END DESCRIPTION:
XS GIS Cut Line= 3
      2743475.99      6876761.00      2743176.00      6876861.00
      2742925.97      6876961.01
#Sta/Elev= 30
  4684.0  444.15  4726.1  443.03  4736.7  442.50  4778.9  441.20  4799.9  440.26
  4863.2  438.18  4915.9  437.40  4926.4  436.58  4937.0  436.37  4958.0  434.62
  4979.1  434.45  4989.7  434.11  5013.0  434.10  5013.3  433.60  5016.8  433.60
  5017.0  434.10  5021.8  434.94  5032.5  435.48  5063.5  437.67  5068.9  437.86
  5086.4  439.37  5093.1  439.75  5098.5  439.90  5107.9  439.76  5117.3  440.19
  5147.0  440.83  5200.8  442.82  5215.6  443.11  5237.2  443.93  5269.5  444.62
#Mann=3,-1,0
  4684.0    0.05       0  5013.0    0.04       0  5017.0    0.05       0
Bank Sta=5013,5017
Exp/Cntr=0.3,0.1

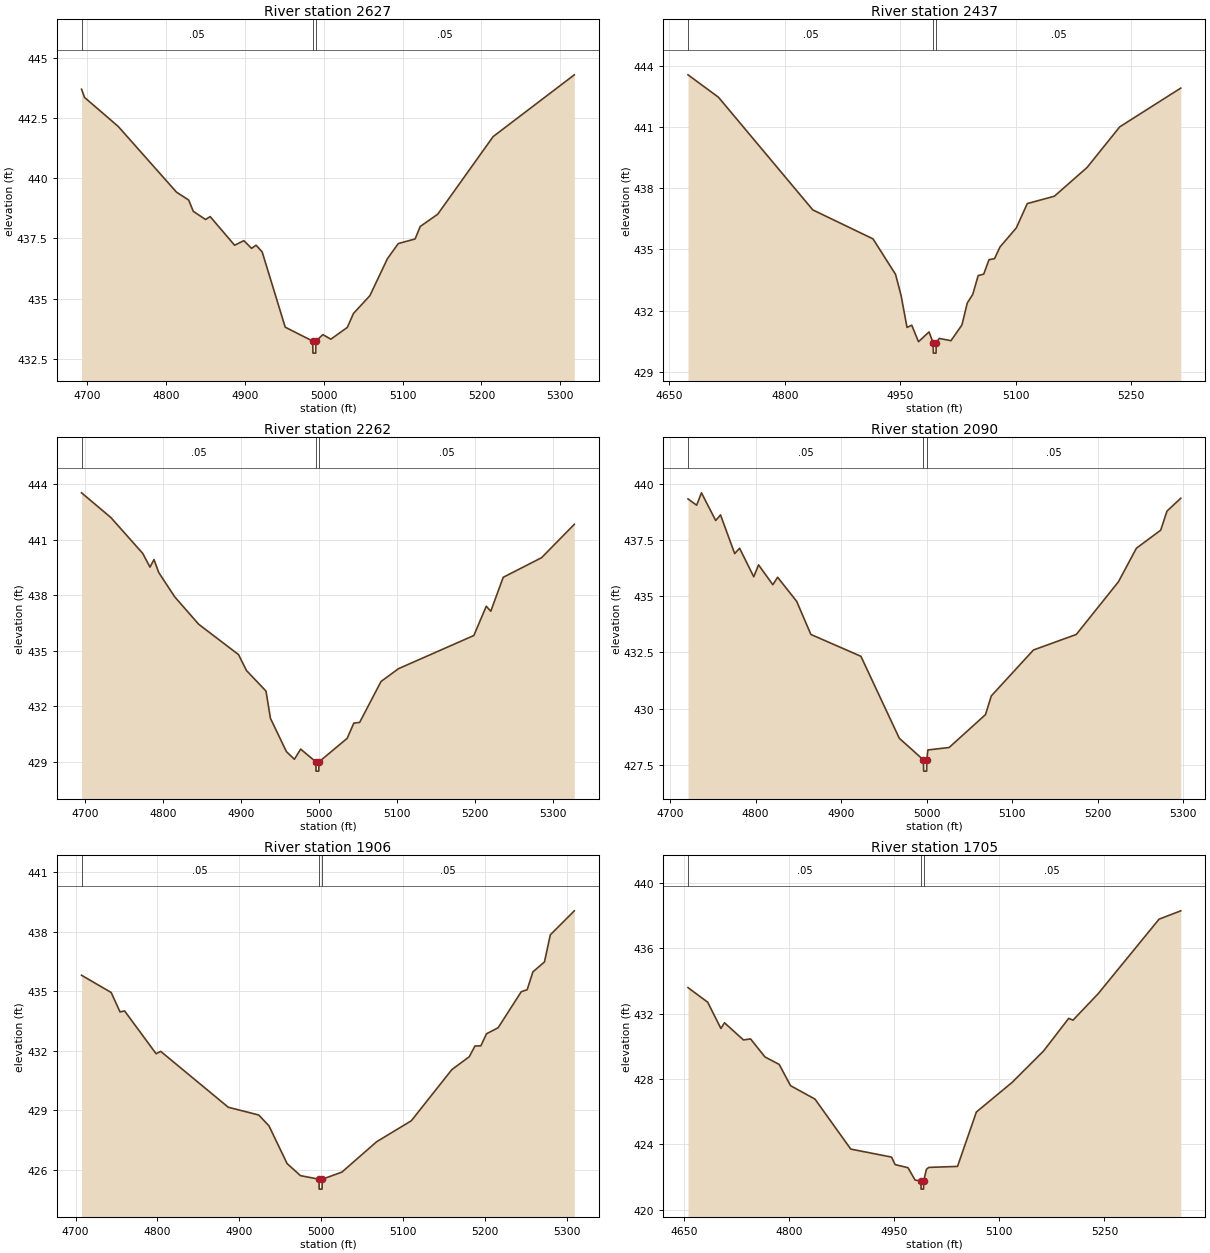
Type RM Length L Ch R = 1,2627,190,190,190
BEGIN DESCRIPTION:
Lacy 037 2879
END DESCRIPTION:
XS GIS Cut Line= 3
      2743402.52      6876562.98      2743139.02      6876721.18
      2742893.55      6876923.10
#Sta/Elev= 30
  4692.7  443.71  4696.5  443.37  4739.3  442.16  4813.1  439.43  4828.6  439.10
  4834.5  438.63  4850.0  438.29  4855.9  438.41  4886.9  437.22  4898.6  437.41
  4908.4  437.09  4914.2  437.22  4921.9  436.94  4951.1  433.81  4986.0  433.23
  4986.3  432.73  4989.8  432.73  4990.0  433.23  4998.9  433.50  5009.0  433.31
  5029.9  433.80  5037.7  434.38  5058.5  435.12  5080.8  436.66  5094.6  437.29
  5115.9  437.48  5122.4  438.00  5144.6  438.51  5214.9  441.74  5317.9  444.31
#Mann=3,-1,0
  4692.7    0.05       0  4986.0    0.04       0  4990.0    0.05       0
Bank Sta=4986,4990
Exp/Cntr=0.3,0.1

Type RM Length L Ch R = 1,2437,175,175,175
BEGIN DESCRIPTION:
Lacy 037 2878
END DESCRIPTION:
XS GIS Cut Line= 3
      2743304.12      6876383.95      2743031.08      6876571.39
      2742815.95      6876793.08
#Sta/Elev= 30
  4674.1  443.56  4713.7  442.46  4836.2  436.94  4914.4  435.52  4943.7  433.78
  4950.8  432.76  4958.6  431.18  4964.7  431.29  4973.5  430.48  4987.2  430.96
  4992.5  430.42  4992.8  429.92  4996.3  429.92  4996.5  430.42  5000.5  430.64
  5015.7  430.53  5029.9  431.30  5036.9  432.38  5044.0  432.80  5051.0  433.72
  5058.2  433.79  5065.1  434.50  5072.3  434.55  5079.3  435.12  5100.6  436.06
  5114.8  437.25  5150.0  437.61  5192.5  439.02  5234.9  441.01  5314.2  442.91
#Mann=3,-1,0
  4674.1    0.05       0  4992.5    0.04       0  4996.5    0.05       0
Bank Sta=4992.5,4996.5
Exp/Cntr=0.3,0.1

Type RM Length L Ch R = 1,2262,172,172,172
BEGIN DESCRIPTION:
Lacy 037 2877
END DESCRIPTION:
XS GIS Cut Line= 3
      2743272.68      6876346.85      2742973.29      6876410.68
      2742689.36      6876569.19
#Sta/Elev= 30
  4695.8  443.53  4733.3  442.20  4774.2  440.26  4783.5  439.52  4788.6  439.93
  4794.7  439.23  4815.1  437.92  4845.8  436.44  4896.9  434.80  4907.1  433.94
  4932.1  432.83  4937.8  431.36  4958.3  429.56  4968.5  429.15  4976.5  429.70
  4996.0  429.01  4996.2  428.51  4999.7  428.51  5000.0  429.01  5036.1  430.28
  5044.6  431.10  5052.1  431.14  5079.5  433.35  5101.9  434.04  5198.4  435.83
  5214.3  437.41  5220.1  437.14  5236.0  438.97  5285.2  440.03  5327.1  441.83
#Mann=3,-1,0
  4695.8    0.05       0  4996.0    0.04       0  5000.0    0.05       0
Bank Sta=4996,5000
Exp/Cntr=0.3,0.1

Type RM Length L Ch R = 1,2090,184,184,184
BEGIN DESCRIPTION:
Lacy 037 2876
END DESCRIPTION:
XS GIS Cut Line= 3
      2743166.36      6876129.57      2742915.33      6876256.90
      2742696.34      6876454.30
#Sta/Elev= 30
  4720.9  439.32  4731.0  439.04  4736.6  439.59  4753.3  438.36  4758.9  438.61
  4775.5  436.89  4781.2  437.13  4797.8  435.86  4803.4  436.39  4820.1  435.51
  4825.7  435.84  4848.0  434.77  4864.6  433.30  4923.1  432.33  4968.0  428.69
  4996.2  427.73  4996.5  427.23  5000.0  427.23  5000.2  427.73  5001.4  428.17
  5026.3  428.28  5068.8  429.74  5075.6  430.57  5124.9  432.61  5175.0  433.30
  5224.3  435.64  5245.3  437.13  5273.7  437.93  5281.1  438.78  5297.2  439.35
#Mann=3,-1,0
  4720.9    0.05       0  4996.2    0.04       0  5000.2    0.05       0
Bank Sta=4996.2,5000.2
Exp/Cntr=0.3,0.1

Type RM Length L Ch R = 1,1906,201,201,201
BEGIN DESCRIPTION:
Lacy 037 2875
END DESCRIPTION:
XS GIS Cut Line= 3
      2743077.71      6875971.57      2742819.12      6876107.40
      2742602.53      6876329.05
#Sta/Elev= 30
  4707.3  435.80  4743.5  434.93  4754.3  433.95  4759.9  434.00  4798.4  431.84
  4804.0  431.96  4886.6  429.14  4923.8  428.75  4936.3  428.20  4958.4  426.30
  4974.8  425.69  4997.4  425.51  4997.6  425.01  5001.1  425.01  5001.4  425.51
  5025.4  425.87  5067.8  427.40  5110.2  428.46  5159.7  431.04  5181.0  431.69
  5187.9  432.23  5195.1  432.24  5202.1  432.85  5216.2  433.15  5244.5  434.97
  5251.7  435.07  5258.7  435.97  5272.8  436.47  5280.0  437.84  5309.3  439.05
#Mann=3,-1,0
  4707.3    0.05       0  4997.4    0.04       0  5001.4    0.05       0
Bank Sta=4997.4,5001.4
Exp/Cntr=0.3,0.1

Type RM Length L Ch R = 1,1705,200,200,200
BEGIN DESCRIPTION:
Lacy 037 2874
END DESCRIPTION:
XS GIS Cut Line= 3
      2743013.50      6875895.57      2742674.26      6875967.12
      2742474.95      6876263.65
#Sta/Elev= 30
  4655.1  433.59  4683.2  432.70  4702.1  431.09  4707.2  431.44  4734.3  430.39
  4744.5  430.45  4765.0  429.35  4785.4  428.89  4801.6  427.59  4836.5  426.77
  4887.6  423.71  4945.9  423.22  4951.0  422.76  4969.4  422.57  4979.6  421.81
  4987.8  421.76  4988.1  421.26  4991.6  421.26  4991.8  421.76  4995.7  422.47
  4999.1  422.59  5040.1  422.65  5067.1  425.98  5118.1  427.79  5163.0  429.71
  5199.0  431.71  5205.1  431.60  5241.1  433.22  5328.1  437.78  5359.1  438.29
#Mann=3,-1,0
  4655.1    0.05       0  4987.8    0.04       0  4991.8    0.05       0
Bank Sta=4987.8,4991.8
Exp/Cntr=0.3,0.1

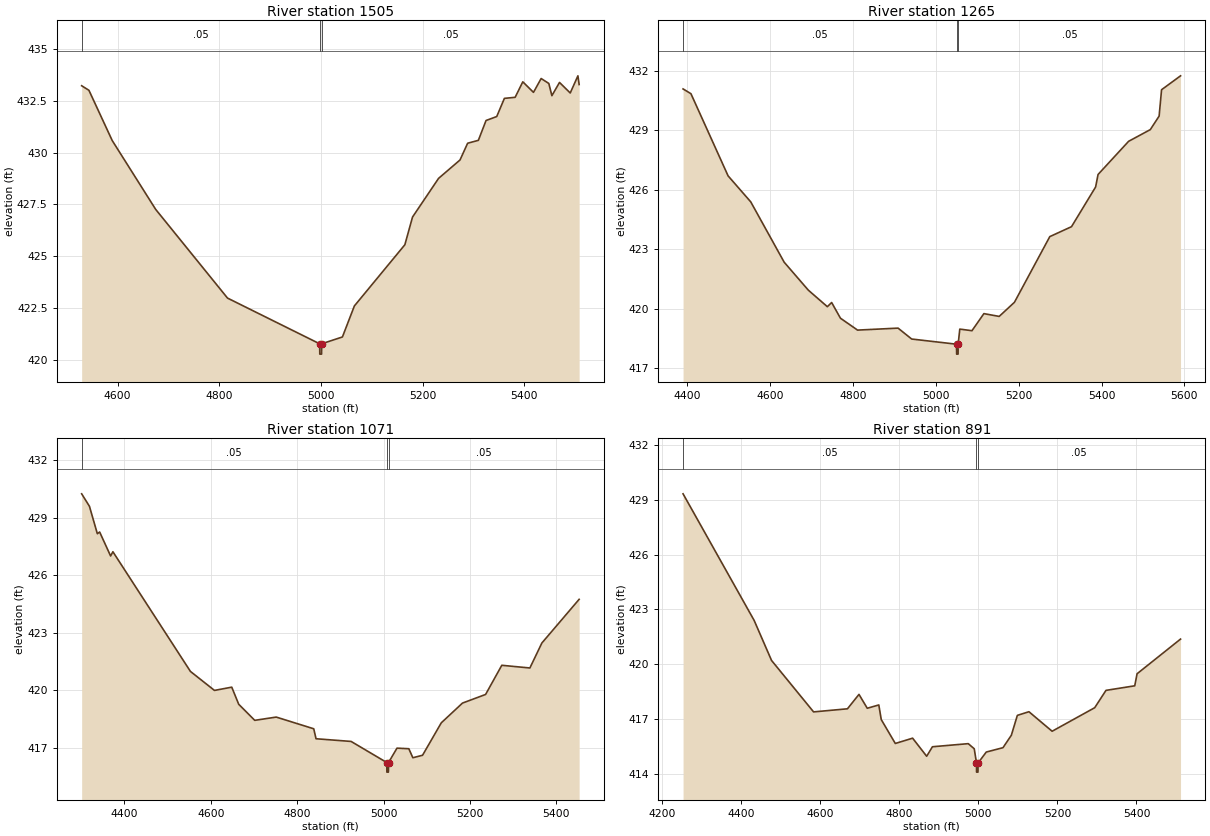
Type RM Length L Ch R = 1,1505,240,240,240
BEGIN DESCRIPTION:
Lacy 037 2873
END DESCRIPTION:
XS GIS Cut Line= 3
      2743000.20      6875864.28      2742570.53      6875804.94
      2742270.89      6876259.88
#Sta/Elev= 30
  4529.4  433.24  4543.7  433.02  4589.5  430.59  4675.0  427.26  4816.3  422.97
  4997.5  420.76  4997.8  420.26  5001.3  420.26  5001.5  420.76  5042.3  421.09
  5065.8  422.59  5165.1  425.55  5180.2  426.89  5231.4  428.76  5273.6  429.65
  5288.6  430.46  5309.7  430.60  5324.8  431.56  5345.8  431.75  5360.9  432.63
  5382.0  432.68  5397.1  433.43  5418.1  432.92  5433.2  433.59  5448.3  433.35
  5454.3  432.76  5469.3  433.40  5490.4  432.89  5505.5  433.72  5507.9  433.30
#Mann=3,-1,0
  4529.4    0.05       0  4997.5    0.04       0  5001.5    0.05       0
Bank Sta=4997.5,5001.5
Exp/Cntr=0.3,0.1

Type RM Length L Ch R = 1,1265,194,194,194
BEGIN DESCRIPTION:
Lacy 037 2872
END DESCRIPTION:
XS GIS Cut Line= 3
      2742960.38      6875791.02      2742430.14      6875636.31
      2741875.03      6875971.68
#Sta/Elev= 30
  4389.8  431.08  4408.8  430.84  4498.5  426.70  4553.2  425.39  4633.9  422.35
  4692.3  420.94  4738.1  420.11  4748.5  420.32  4769.7  419.53  4811.0  418.93
  4908.8  419.03  4941.7  418.48  5049.9  418.22  5050.2  417.72  5053.7  417.72
  5053.9  418.22  5057.8  418.98  5087.2  418.90  5116.0  419.76  5152.9  419.62
  5189.7  420.33  5275.1  423.64  5327.5  424.14  5385.7  426.14  5391.6  426.77
  5465.3  428.44  5517.7  429.03  5539.0  429.71  5544.9  431.04  5590.7  431.74
#Mann=3,-1,0
  4389.8    0.05       0  5049.9    0.04       0  5053.9    0.05       0
Bank Sta=5049.9,5053.9
Exp/Cntr=0.3,0.1

Type RM Length L Ch R = 1,1071,180,180,180
BEGIN DESCRIPTION:
Lacy 037 2871
END DESCRIPTION:
XS GIS Cut Line= 3
      2742932.94      6875749.05      2742271.20      6875511.14
      2741880.87      6875731.60
#Sta/Elev= 30
  4301.1  430.24  4319.1  429.59  4337.4  428.16  4342.7  428.25  4368.1  427.00
  4373.4  427.22  4552.9  420.98  4608.5  419.99  4648.5  420.16  4664.6  419.27
  4701.7  418.43  4751.5  418.60  4838.3  417.99  4843.6  417.47  4924.8  417.33
  5007.4  416.23  5007.6  415.73  5011.1  415.73  5011.4  416.23  5031.0  416.98
  5058.4  416.95  5067.7  416.48  5090.2  416.61  5133.5  418.30  5182.6  419.33
  5236.1  419.78  5273.6  421.30  5338.6  421.16  5366.3  422.46  5452.6  424.74
#Mann=3,-1,0
  4301.1    0.05       0  5007.4    0.04       0  5011.4    0.05       0
Bank Sta=5007.4,5011.4
Exp/Cntr=0.3,0.1

Type RM Length L Ch R = 1,891,0,0,0
BEGIN DESCRIPTION:
Lacy 037 2884
END DESCRIPTION:
XS GIS Cut Line= 3
      2742916.27      6875712.47      2742376.61      6875312.24
      2741883.30      6875628.39
#Sta/Elev= 30
  4253.6  429.33  4433.4  422.39  4477.3  420.20  4583.6  417.38  4669.2  417.55
  4698.4  418.34  4719.3  417.58  4748.5  417.76  4754.7  416.96  4790.2  415.65
  4834.0  415.94  4869.5  414.95  4884.1  415.47  4974.6  415.64  4989.8  415.36
  4995.5  414.58  4995.7  414.08  4999.2  414.08  4999.5  414.58  5020.2  415.18
  5062.5  415.42  5083.6  416.10  5098.8  417.19  5128.1  417.39  5186.7  416.32
  5294.4  417.61  5322.9  418.56  5395.6  418.81  5401.5  419.47  5511.4  421.37
#Mann=3,-1,0
  4253.6    0.05       0  4995.5    0.04       0  4999.5    0.05       0
Bank Sta=4995.5,4999.5
Exp/Cntr=0.3,0.1

Chan Stop Cuts=-1