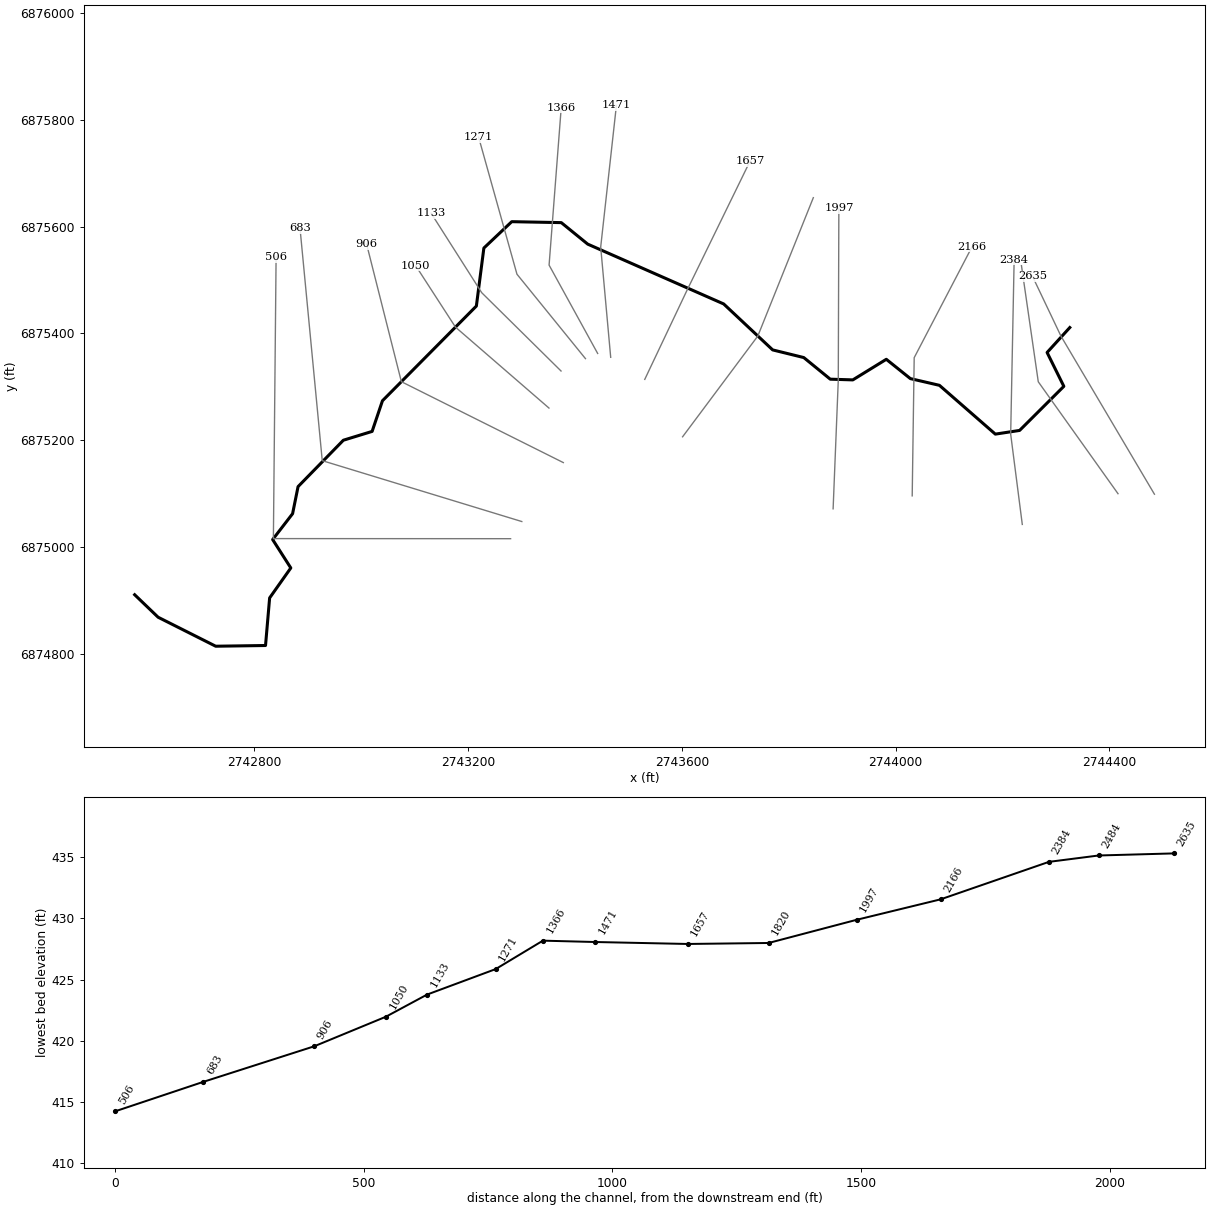
--- Lacy 038.prj (project) ---

Proj Title=Lacy 038 Base Level Engineering
Current Plan=p01
Default Exp/Contr=0.3,0.1
English Units
Geom File=g01
Flow File=f01
Plan File=p01
BEGIN DESCRIPTION:
Lacy 038
END DESCRIPTION:

--- Lacy 038.p01 (plan) ---

Plan Title=Multiple Run
Short Identifier=Multiple
Geom File=g01
Flow File=f01
Subcritical Flow
K Sum by GR= 0
Std Step Tol= 0.01
Critical Tol= 0.01
Num of Std Step Trials= 20
Max Error Tol= 0.3
Flow Tol Ratio= 0.001
Split Flow NTrial= 30
Split Flow Tol= 0.02
Split Flow Ratio= 0.02
Log Output Level= 0
Friction Slope Method= 1
Unsteady Friction Slope Method= 2
Unsteady Bridges Friction Slope Method= 1
Parabolic Critical Depth
Global Vel Dist=  1 , 1 , 1
Global Log Level= 0
CheckData=True
Encroach Param= -1, 0, 0, 0
BEGIN DESCRIPTION:
Multiple Run
END DESCRIPTION:

--- Lacy 038.f01 (steady flow) ---

Flow Title=Multiple
Number of Profiles=7
Profile Names=10-year,25-year,50-year,1pct_min,100-year,1pct_plu,500-year
River Rch & RM= Lacy 038,Reach-1,2635
      77      90      98      54     108     215     128
Boundary for River Rch & Prof#=Lacy 038,Reach-1,1
Up Type=0
Dn Type=3
Dn Slope=0.005
Boundary for River Rch & Prof#=Lacy 038,Reach-1,2
Up Type=0
Dn Type=3
Dn Slope=0.005
Boundary for River Rch & Prof#=Lacy 038,Reach-1,3
Up Type=0
Dn Type=3
Dn Slope=0.005
Boundary for River Rch & Prof#=Lacy 038,Reach-1,4
Up Type=0
Dn Type=3
Dn Slope=0.005
Boundary for River Rch & Prof#=Lacy 038,Reach-1,5
Up Type=0
Dn Type=3
Dn Slope=0.005
Boundary for River Rch & Prof#=Lacy 038,Reach-1,6
Up Type=0
Dn Type=3
Dn Slope=0.005
Boundary for River Rch & Prof#=Lacy 038,Reach-1,7
Up Type=0
Dn Type=3
Dn Slope=0.005

--- Lacy 038.g01 (geometry) ---

Geom Title=Existing Conditions

River Reach=Lacy 038,Reach-1
Reach XY= 30
      2744326.00      6875411.00      2744283.52      6875364.33
      2744314.85      6875300.97      2744232.09      6875218.46
      2744186.65      6875211.55      2744082.04      6875302.86
      2744027.65      6875315.45      2743982.61      6875351.57
      2743919.96      6875313.02      2743877.73      6875314.37
      2743828.19      6875354.82      2743769.95      6875369.15
      2743678.29      6875455.15      2743423.82      6875567.12
      2743374.41      6875607.33      2743281.69      6875609.12
      2743229.51      6875559.75      2743215.48      6875451.22
      2743039.73      6875273.98      2743020.38      6875216.62
      2742966.56      6875200.12      2742881.80      6875113.30
      2742871.56      6875062.65      2742834.24      6875014.23
      2742868.21      6874961.09      2742828.59      6874905.01
      2742820.90      6874815.96      2742727.66      6874814.63
      2742619.85      6874868.91      2742576.00      6874911.00

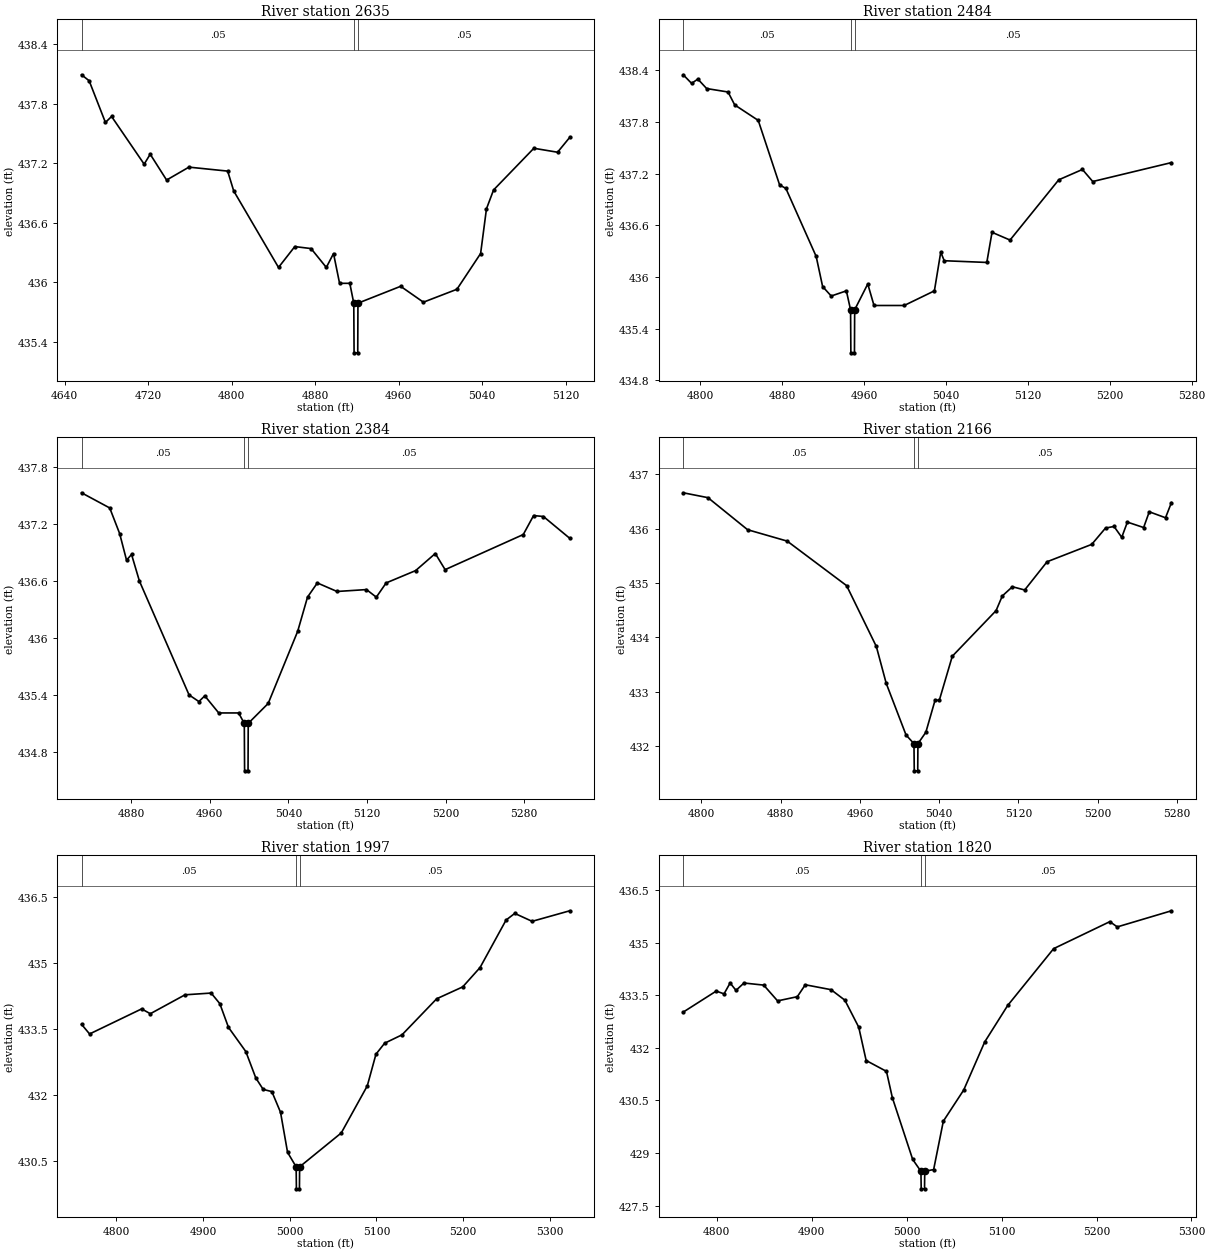
Type RM Length L Ch R = 1,2635,151,151,151
BEGIN DESCRIPTION:
Lacy 038 2898
END DESCRIPTION:
XS GIS Cut Line= 3
      2744484.38      6875099.12      2744309.45      6875394.98
      2744256.15      6875506.93
#Sta/Elev= 30
  4656.3  438.09  4663.6  438.03  4679.2  437.61  4685.1  437.67  4716.3  437.19
  4722.1  437.29  4737.8  437.03  4759.2  437.16  4796.3  437.12  4802.1  436.92
  4845.0  436.15  4860.6  436.36  4876.2  436.34  4890.8  436.15  4897.7  436.29
  4903.5  435.99  4913.3  435.99  4917.1  435.79  4917.4  435.29  4920.9  435.29
  4921.1  435.79  4962.0  435.96  4983.8  435.80  5015.9  435.93  5038.6  436.29
  5044.2  436.74  5051.0  436.93  5089.6  437.35  5112.3  437.31  5124.0  437.46
#Mann=3,-1,0
  4656.3    0.05       0  4917.1    0.04       0  4921.1    0.05       0
Bank Sta=4917.1,4921.1
Exp/Cntr=0.3,0.1

Type RM Length L Ch R = 1,2484,100,100,100
BEGIN DESCRIPTION:
Lacy 038 2901
END DESCRIPTION:
XS GIS Cut Line= 3
      2744416.23      6875100.06      2744267.02      6875309.50
      2744235.53      6875527.08
#Sta/Elev= 30
  4783.2  438.35  4791.4  438.25  4797.5  438.30  4806.1  438.19  4827.0  438.15
  4833.5  438.00  4856.5  437.82  4877.4  437.07  4883.5  437.03  4913.1  436.24
  4919.4  435.89  4927.8  435.78  4942.6  435.84  4946.7  435.62  4947.0  435.12
  4950.5  435.12  4950.7  435.62  4963.5  435.92  4969.6  435.67  4999.1  435.67
  5028.6  435.84  5034.8  436.29  5038.2  436.19  5079.8  436.17  5084.9  436.52
  5102.5  436.43  5150.1  437.13  5173.2  437.25  5183.3  437.11  5260.2  437.33
#Mann=3,-1,0
  4783.2    0.05       0  4946.7    0.04       0  4950.7    0.05       0
Bank Sta=4946.7,4950.7
Exp/Cntr=0.3,0.1

Type RM Length L Ch R = 1,2384,218,218,218
BEGIN DESCRIPTION:
Lacy 038 2899
END DESCRIPTION:
XS GIS Cut Line= 3
      2744237.10      6875042.54      2744215.37      6875211.55
      2744221.85      6875537.78
#Sta/Elev= 30
  4829.6  437.53  4858.3  437.37  4868.4  437.10  4875.4  436.82  4880.5  436.88
  4888.5  436.60  4939.0  435.40  4949.0  435.33  4955.0  435.39  4969.2  435.21
  4989.4  435.21  4995.2  435.10  4995.5  434.60  4999.0  434.60  4999.2  435.10
  5019.5  435.31  5049.5  436.07  5059.5  436.43  5069.5  436.58  5089.5  436.49
  5119.5  436.51  5129.5  436.43  5139.5  436.58  5169.5  436.71  5189.5  436.89
  5199.5  436.72  5279.0  437.09  5289.5  437.29  5299.5  437.28  5326.3  437.05
#Mann=3,-1,0
  4829.6    0.05       0  4995.2    0.04       0  4999.2    0.05       0
Bank Sta=4995.2,4999.2
Exp/Cntr=0.3,0.1

Type RM Length L Ch R = 1,2166,169,169,169
BEGIN DESCRIPTION:
Lacy 038 2897
END DESCRIPTION:
XS GIS Cut Line= 3
      2744031.09      6875096.00      2744034.81      6875354.59
      2744143.20      6875562.40
#Sta/Elev= 30
  4781.6  436.66  4806.6  436.57  4846.6  435.98  4886.6  435.77  4946.6  434.95
  4976.6  433.83  4986.6  433.15  5006.6  432.20  5014.6  432.04  5014.9  431.54
  5018.4  431.54  5018.6  432.04  5026.6  432.25  5035.9  432.84  5040.2  432.84
  5053.3  433.65  5097.5  434.49  5103.8  434.76  5114.0  434.93  5126.4  434.87
  5149.0  435.39  5194.1  435.71  5208.0  436.01  5216.6  436.04  5224.4  435.84
  5230.1  436.12  5246.5  436.02  5252.2  436.31  5268.6  436.20  5274.6  436.48
#Mann=3,-1,0
  4781.6    0.05       0  5014.6    0.04       0  5018.6    0.05       0
Bank Sta=5014.6,5018.6
Exp/Cntr=0.3,0.1

Type RM Length L Ch R = 1,1997,177,177,177
BEGIN DESCRIPTION:
Lacy 038 2896
END DESCRIPTION:
XS GIS Cut Line= 3
      2743883.09      6875071.75      2743892.74      6875312.22
      2743893.83      6875634.36
#Sta/Elev= 30
  4760.1  433.61  4769.4  433.39  4829.4  433.96  4839.4  433.85  4879.4  434.28
  4909.5  434.32  4919.5  434.08  4929.5  433.54  4949.5  432.99  4961.0  432.39
  4969.5  432.13  4979.5  432.08  4989.5  431.61  4997.6  430.70  5007.5  430.37
  5007.8  429.87  5011.3  429.87  5011.5  430.37  5059.5  431.14  5089.5  432.21
  5099.5  432.93  5109.5  433.18  5129.5  433.37  5169.5  434.19  5199.5  434.46
  5219.5  434.90  5249.5  435.98  5259.5  436.13  5279.5  435.95  5322.9  436.19
#Mann=3,-1,0
  4760.1    0.05       0  5007.5    0.04       0  5011.5    0.05       0
Bank Sta=5007.5,5011.5
Exp/Cntr=0.3,0.1

Type RM Length L Ch R = 1,1820,163,163,163
BEGIN DESCRIPTION:
Lacy 038 2895
END DESCRIPTION:
XS GIS Cut Line= 3
      2743601.40      6875206.54      2743742.21      6875395.18
      2743846.05      6875654.03
#Sta/Elev= 30
  4764.6  433.02  4799.4  433.62  4807.6  433.54  4814.0  433.85  4820.2  433.64
  4828.6  433.85  4849.4  433.79  4864.0  433.34  4884.8  433.46  4893.2  433.80
  4920.3  433.66  4934.9  433.36  4949.5  432.59  4957.3  431.64  4978.7  431.33
  4984.9  430.58  5006.3  428.82  5015.0  428.48  5015.3  427.98  5018.8  427.98
  5019.0  428.48  5028.4  428.53  5038.6  429.91  5060.1  430.80  5082.2  432.17
  5106.4  433.21  5154.8  434.83  5214.0  435.60  5221.8  435.45  5278.9  435.91
#Mann=3,-1,0
  4764.6    0.05       0  5015.0    0.04       0  5019.0    0.05       0
Bank Sta=5015,5019
Exp/Cntr=0.3,0.1

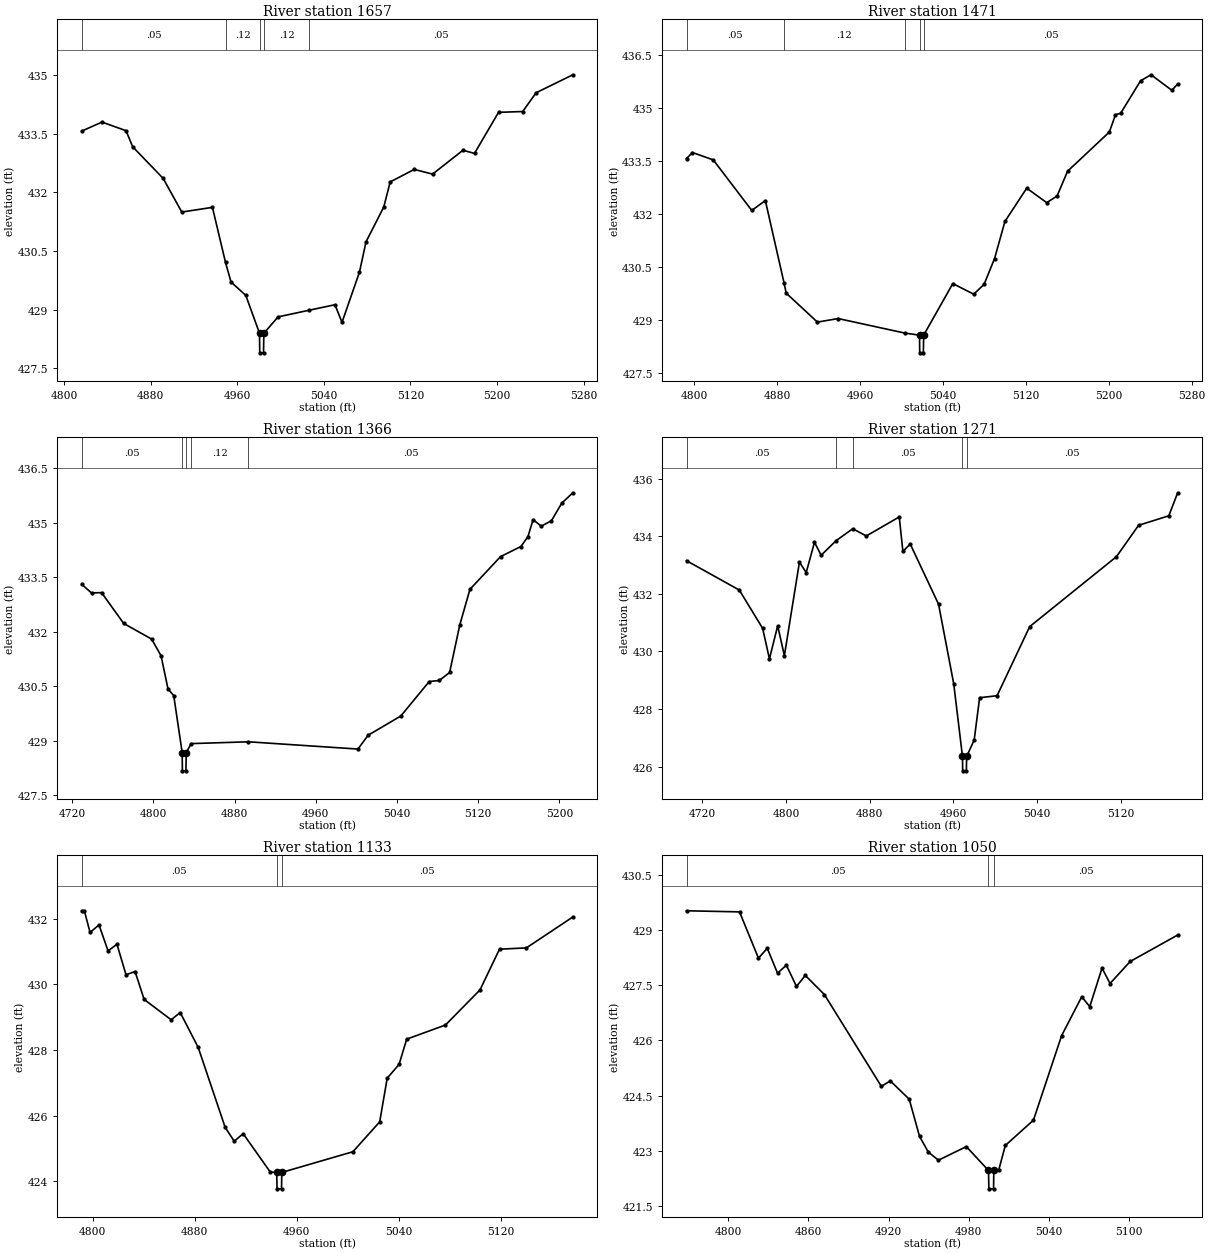
Type RM Length L Ch R = 1,1657,186,186,186
BEGIN DESCRIPTION:
Lacy 038 2894
END DESCRIPTION:
XS GIS Cut Line= 3
      2743530.60      6875313.98      2743609.30      6875479.97
      2743727.73      6875722.62
#Sta/Elev= 30
  4816.3  433.57  4835.1  433.80  4857.3  433.58  4863.4  433.17  4891.6  432.36
  4908.8  431.50  4937.1  431.62  4949.2  430.21  4954.3  429.71  4967.9  429.37
  4980.6  428.40  4980.8  427.90  4984.3  427.90  4984.6  428.40  4997.8  428.82
  5026.5  428.99  5050.3  429.13  5056.8  428.68  5072.9  429.96  5079.0  430.74
  5095.4  431.63  5101.3  432.27  5123.5  432.59  5140.5  432.47  5168.5  433.08
  5179.2  433.00  5201.4  434.05  5223.7  434.07  5236.1  434.55  5270.0  435.01
#Mann=5,-1,0
  4816.3    0.05       0  4949.2    0.12       0  4980.6    0.07       0
  4984.6    0.12       0  5026.5    0.05       0
Bank Sta=4980.6,4984.6
Exp/Cntr=0.3,0.1

Type RM Length L Ch R = 1,1471,105,105,105
BEGIN DESCRIPTION:
Lacy 038 2893
END DESCRIPTION:
XS GIS Cut Line= 3
      2743466.85      6875355.31      2743448.13      6875561.67
      2743477.53      6875826.54
#Sta/Elev= 30
  4792.8  433.56  4798.5  433.73  4818.6  433.52  4855.7  432.09  4868.8  432.37
  4886.9  430.03  4888.9  429.75  4919.0  428.93  4939.1  429.03  5003.2  428.62
  5017.5  428.56  5017.7  428.06  5021.2  428.06  5021.5  428.56  5049.6  430.02
  5069.8  429.72  5079.8  430.00  5089.9  430.73  5099.9  431.78  5120.9  432.72
  5140.2  432.31  5150.2  432.50  5160.3  433.20  5200.6  434.31  5206.5  434.80
  5211.5  434.84  5230.7  435.76  5240.8  435.93  5260.9  435.49  5266.5  435.67
#Mann=5,-1,0
  4792.8    0.05       0  4886.9    0.12       0  5003.2    0.05       0
  5017.5    0.07       0  5021.5    0.05       0
Bank Sta=5017.5,5021.5
Exp/Cntr=0.3,0.1

Type RM Length L Ch R = 1,1366,95,95,95
BEGIN DESCRIPTION:
Lacy 038 2892
END DESCRIPTION:
XS GIS Cut Line= 3
      2743442.46      6875362.50      2743351.56      6875527.86
      2743374.24      6875821.99
#Sta/Elev= 30
  4729.4  433.31  4739.1  433.07  4749.0  433.08  4770.8  432.23  4798.3  431.80
  4807.6  431.34  4814.4  430.43  4820.1  430.24  4828.4  428.67  4828.6  428.17
  4832.1  428.17  4832.4  428.67  4837.2  428.92  4893.6  428.97  5001.5  428.77
  5011.5  429.15  5043.7  429.68  5071.7  430.63  5081.7  430.66  5091.8  430.88
  5101.8  432.19  5111.8  433.17  5141.9  434.07  5162.0  434.35  5168.9  434.62
  5174.0  435.09  5182.0  434.91  5192.1  435.06  5202.1  435.54  5213.1  435.83
#Mann=5,-1,0
  4729.4    0.05       0  4828.4    0.04       0  4832.4    0.05       0
  4837.2    0.12       0  4893.6    0.05       0
Bank Sta=4828.4,4832.4
Exp/Cntr=0.3,0.1

Type RM Length L Ch R = 1,1271,138,138,138
BEGIN DESCRIPTION:
Lacy 038 2891
END DESCRIPTION:
XS GIS Cut Line= 3
      2743419.62      6875352.81      2743291.43      6875510.84
      2743219.63      6875767.40
#Sta/Elev= 30
  4704.8  433.15  4755.3  432.13  4777.6  430.80  4784.1  429.74  4792.0  430.89
  4798.4  429.85  4812.8  433.10  4819.3  432.74  4827.2  433.79  4833.6  433.34
  4848.0  433.85  4863.8  434.26  4876.8  434.01  4908.3  434.67  4911.8  433.47
  4918.8  433.73  4945.9  431.64  4960.4  428.88  4968.8  426.35  4969.0  425.85
  4972.5  425.85  4972.8  426.35  4980.0  426.92  4985.2  428.39  5001.9  428.46
  5033.1  430.86  5116.1  433.29  5137.3  434.38  5166.2  434.71  5174.7  435.51
#Mann=5,-1,0
  4704.8    0.05       0  4848.0    0.12       0  4863.8    0.05       0
  4968.8    0.04       0  4972.8    0.05       0
Bank Sta=4968.8,4972.8
Exp/Cntr=0.3,0.1

Type RM Length L Ch R = 1,1133,83,83,83
BEGIN DESCRIPTION:
Lacy 038 2890
END DESCRIPTION:
XS GIS Cut Line= 3
      2743373.92      6875329.67      2743225.47      6875476.22
      2743130.60      6875625.30
#Sta/Elev= 30
  4791.4  432.24  4793.5  432.24  4798.0  431.58  4805.0  431.81  4812.1  431.02
  4819.1  431.22  4826.2  430.29  4833.3  430.39  4840.4  429.54  4861.6  428.92
  4868.7  429.14  4882.8  428.08  4904.0  425.64  4911.1  425.22  4918.1  425.45
  4939.4  424.28  4944.4  424.27  4944.7  423.77  4948.2  423.77  4948.4  424.27
  5004.2  424.90  5025.2  425.81  5031.1  427.14  5040.4  427.56  5046.4  428.33
  5076.8  428.76  5103.9  429.83  5119.2  431.07  5140.3  431.11  5176.7  432.05
#Mann=3,-1,0
  4791.4    0.05       0  4944.4    0.04       0  4948.4    0.05       0
Bank Sta=4944.4,4948.4
Exp/Cntr=0.3,0.1

Type RM Length L Ch R = 1,1050,144,144,144
BEGIN DESCRIPTION:
Lacy 038 2889
END DESCRIPTION:
XS GIS Cut Line= 3
      2743351.32      6875260.33      2743176.37      6875411.78
      2743102.09      6875526.53
#Sta/Elev= 30
  4768.6  429.53  4808.3  429.50  4822.5  428.24  4829.1  428.51  4836.8  427.83
  4843.4  428.05  4851.0  427.47  4857.6  427.77  4871.9  427.25  4914.6  424.75
  4921.3  424.90  4935.5  424.40  4943.2  423.39  4949.8  422.96  4957.4  422.74
  4978.3  423.11  4994.9  422.46  4995.2  421.96  4998.7  421.96  4998.9  422.46
  5002.5  422.46  5007.5  423.14  5028.6  423.83  5049.7  426.13  5064.8  427.19
  5070.8  426.92  5080.0  427.97  5086.0  427.55  5101.1  428.15  5136.7  428.87
#Mann=3,-1,0
  4768.6    0.05       0  4994.9    0.04       0  4998.9    0.05       0
Bank Sta=4994.9,4998.9
Exp/Cntr=0.3,0.1

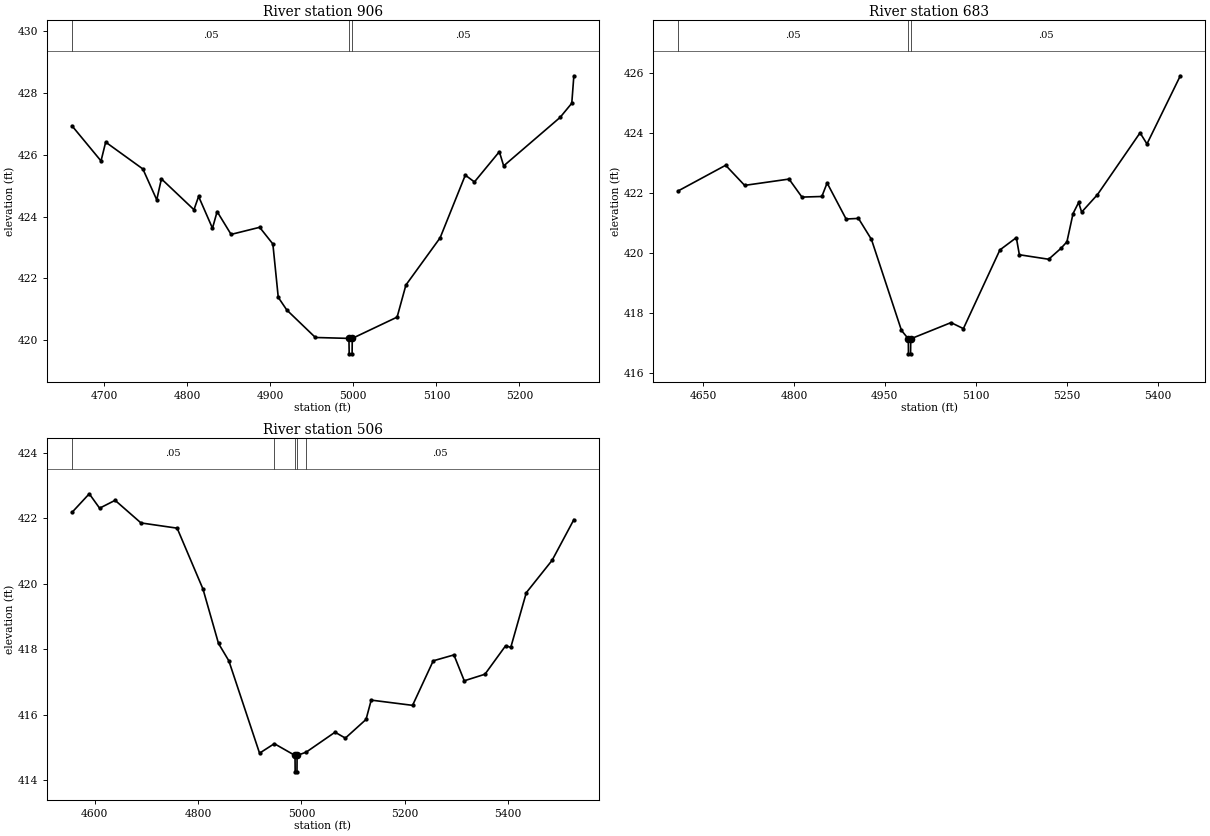
Type RM Length L Ch R = 1,906,223,223,223
BEGIN DESCRIPTION:
Lacy 038 2888
END DESCRIPTION:
XS GIS Cut Line= 3
      2743378.21      6875158.27      2743075.12      6875309.68
      2743010.07      6875567.08
#Sta/Elev= 30
  4661.2  426.94  4696.2  425.80  4701.8  426.41  4746.6  425.54  4763.3  424.54
  4768.9  425.22  4808.1  424.22  4813.7  424.65  4830.4  423.62  4836.0  424.16
  4852.8  423.42  4887.2  423.65  4903.1  423.11  4909.6  421.38  4919.9  420.97
  4954.3  420.08  4994.7  420.05  4995.0  419.55  4998.5  419.55  4998.7  420.05
  5052.7  420.74  5063.3  421.78  5104.5  423.31  5134.8  425.34  5145.8  425.12
  5175.8  426.10  5181.0  425.64  5248.9  427.21  5263.0  427.67  5265.5  428.56
#Mann=3,-1,0
  4661.2    0.05       0  4994.7    0.04       0  4998.7    0.05       0
Bank Sta=4994.7,4998.7
Exp/Cntr=0.3,0.1

Type RM Length L Ch R = 1,683,177,177,177
BEGIN DESCRIPTION:
Lacy 038 2887
END DESCRIPTION:
XS GIS Cut Line= 3
      2743300.48      6875047.97      2742927.07      6875161.89
      2742885.42      6875597.10
#Sta/Elev= 30
  4609.6  422.08  4687.5  422.93  4718.8  422.26  4792.0  422.47  4813.3  421.87
  4846.1  421.89  4854.8  422.34  4886.1  421.14  4906.5  421.16  4927.9  420.46
  4977.4  417.43  4988.7  417.15  4988.9  416.65  4992.4  416.65  4992.7  417.15
  5059.1  417.69  5079.5  417.49  5139.7  420.11  5166.8  420.52  5171.8  419.95
  5220.1  419.80  5240.2  420.16  5250.2  420.38  5260.3  421.32  5269.5  421.69
  5274.5  421.37  5300.5  421.95  5370.8  424.01  5382.2  423.64  5437.2  425.91
#Mann=3,-1,0
  4609.6    0.05       0  4988.7    0.04       0  4992.7    0.05       0
Bank Sta=4988.7,4992.7
Exp/Cntr=0.3,0.1

Type RM Length L Ch R = 1,506,0,0,0
BEGIN DESCRIPTION:
Lacy 038 2886
END DESCRIPTION:
XS GIS Cut Line= 3
      2743279.52      6875015.86      2742835.62      6875016.03
      2742840.69      6875543.00
#Sta/Elev= 30
  4556.1  422.17  4589.6  422.74  4609.6  422.30  4639.6  422.54  4689.6  421.85
  4759.6  421.69  4809.6  419.83  4839.6  418.17  4859.6  417.64  4919.0  414.82
  4947.6  415.11  4987.6  414.75  4987.9  414.25  4991.4  414.25  4991.6  414.75
  5009.1  414.85  5065.0  415.46  5085.0  415.28  5125.0  415.85  5135.0  416.44
  5215.0  416.28  5255.0  417.64  5295.0  417.82  5315.0  417.03  5355.0  417.23
  5395.0  418.10  5405.0  418.05  5435.0  419.72  5485.0  420.71  5527.0  421.95
#Mann=5,-1,0
  4556.1    0.05       0  4947.6    0.12       0  4987.6    0.07       0
  4991.6    0.12       0  5009.1    0.05       0
Bank Sta=4987.6,4991.6
Exp/Cntr=0.3,0.1

Chan Stop Cuts=-1