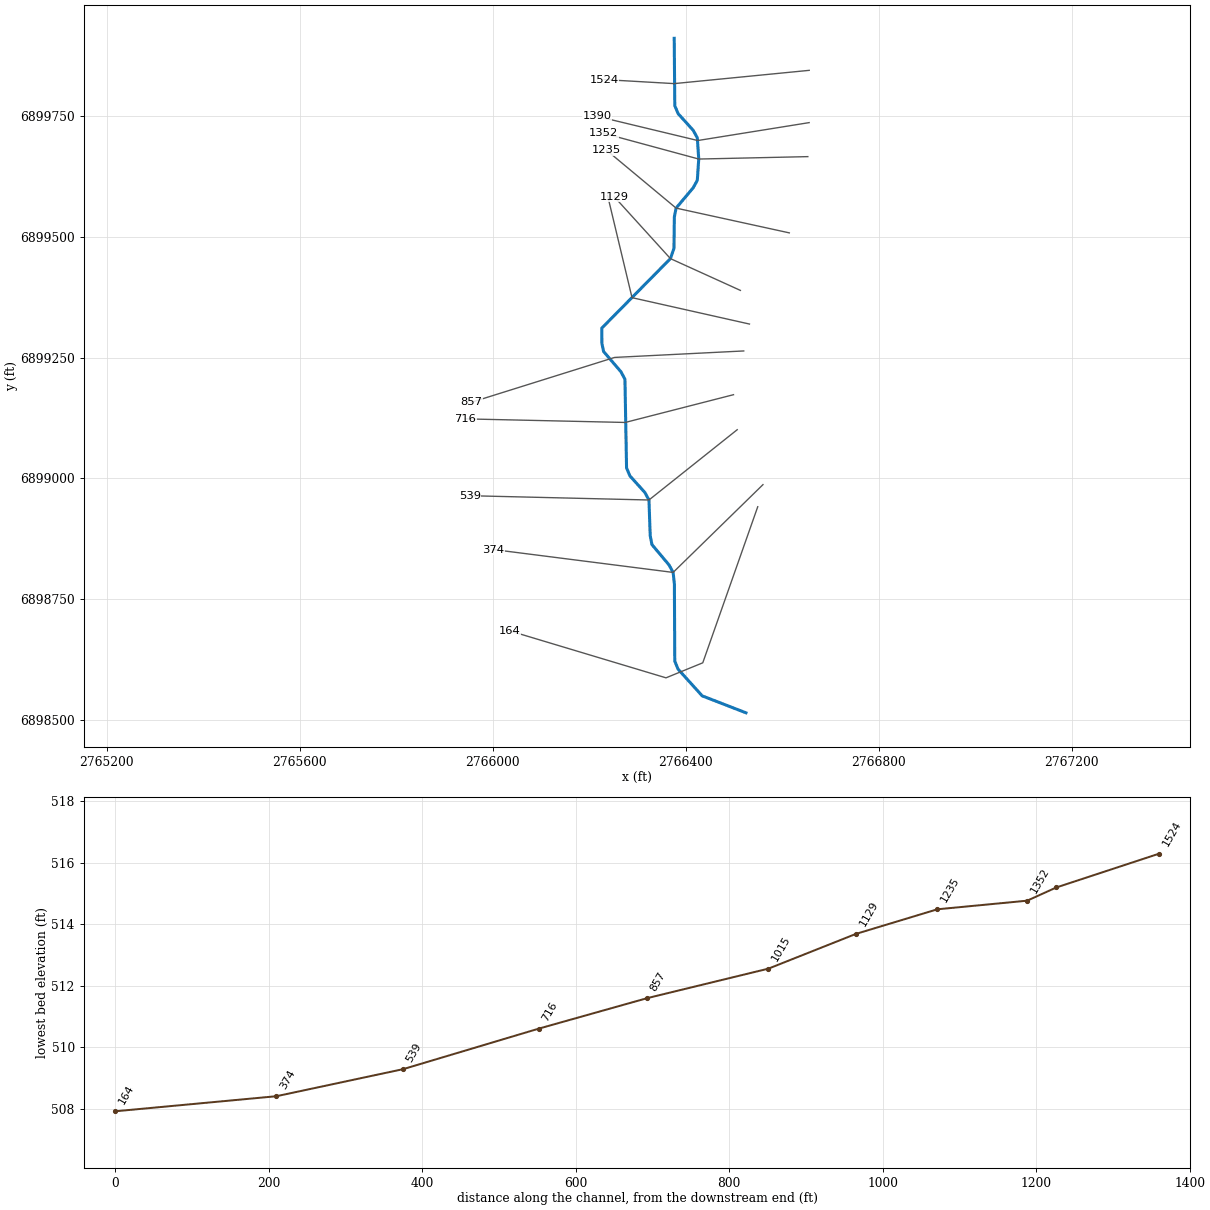
--- Lacy 041.prj (project) ---

Proj Title=Lacy 041 Base Level Engineering
Current Plan=p01
Default Exp/Contr=0.3,0.1
English Units
Geom File=g01
Flow File=f01
Plan File=p01
BEGIN DESCRIPTION:
Lacy 041
END DESCRIPTION:

--- Lacy 041.p01 (plan) ---

Plan Title=Multiple Run
Short Identifier=Multiple
Geom File=g01
Flow File=f01
Subcritical Flow
K Sum by GR= 0
Std Step Tol= 0.01
Critical Tol= 0.01
Num of Std Step Trials= 20
Max Error Tol= 0.3
Flow Tol Ratio= 0.001
Split Flow NTrial= 30
Split Flow Tol= 0.02
Split Flow Ratio= 0.02
Log Output Level= 0
Friction Slope Method= 1
Unsteady Friction Slope Method= 2
Unsteady Bridges Friction Slope Method= 1
Parabolic Critical Depth
Global Vel Dist=  1 , 1 , 1
Global Log Level= 0
CheckData=True
Encroach Param= -1, 0, 0, 0
BEGIN DESCRIPTION:
Multiple Run
END DESCRIPTION:

--- Lacy 041.f01 (steady flow) ---

Flow Title=Multiple
Number of Profiles=7
Profile Names=10-year,25-year,50-year,1pct_min,100-year,1pct_plu,500-year
River Rch & RM= Lacy 041,Reach-1,1524
      61      70      75      41      82     163      95
River Rch & RM= Lacy 041,Reach-1,857
     112     135     151      85     169     338     211
Boundary for River Rch & Prof#=Lacy 041,Reach-1,1
Up Type=0
Dn Type=3
Dn Slope=0.005
Boundary for River Rch & Prof#=Lacy 041,Reach-1,2
Up Type=0
Dn Type=3
Dn Slope=0.005
Boundary for River Rch & Prof#=Lacy 041,Reach-1,3
Up Type=0
Dn Type=3
Dn Slope=0.005
Boundary for River Rch & Prof#=Lacy 041,Reach-1,4
Up Type=0
Dn Type=3
Dn Slope=0.005
Boundary for River Rch & Prof#=Lacy 041,Reach-1,5
Up Type=0
Dn Type=3
Dn Slope=0.005
Boundary for River Rch & Prof#=Lacy 041,Reach-1,6
Up Type=0
Dn Type=3
Dn Slope=0.005
Boundary for River Rch & Prof#=Lacy 041,Reach-1,7
Up Type=0
Dn Type=3
Dn Slope=0.005

--- Lacy 041.g01 (geometry) ---

Geom Title=Existing Conditions

River Reach=Lacy 041,Reach-1
Reach XY= 30
      2766376.00      6899911.00      2766377.17      6899771.48
      2766384.13      6899754.94      2766415.20      6899720.63
      2766423.83      6899705.03      2766426.82      6899661.00
      2766423.83      6899616.97      2766415.19      6899601.37
      2766379.86      6899559.40      2766376.25      6899540.90
      2766375.48      6899476.21      2766368.14      6899454.83
      2766226.00      6899311.00      2766226.12      6899279.20
      2766229.65      6899262.51      2766265.43      6899220.76
      2766273.87      6899205.12      2766277.22      6899021.50
      2766284.14      6899004.94      2766315.11      6898970.63
      2766323.64      6898955.02      2766326.24      6898881.10
      2766329.86      6898862.60      2766365.15      6898820.65
      2766373.74      6898805.06      2766376.35      6898781.15
      2766377.12      6898621.46      2766383.89      6898604.84
      2766433.98      6898549.44      2766524.61      6898514.37

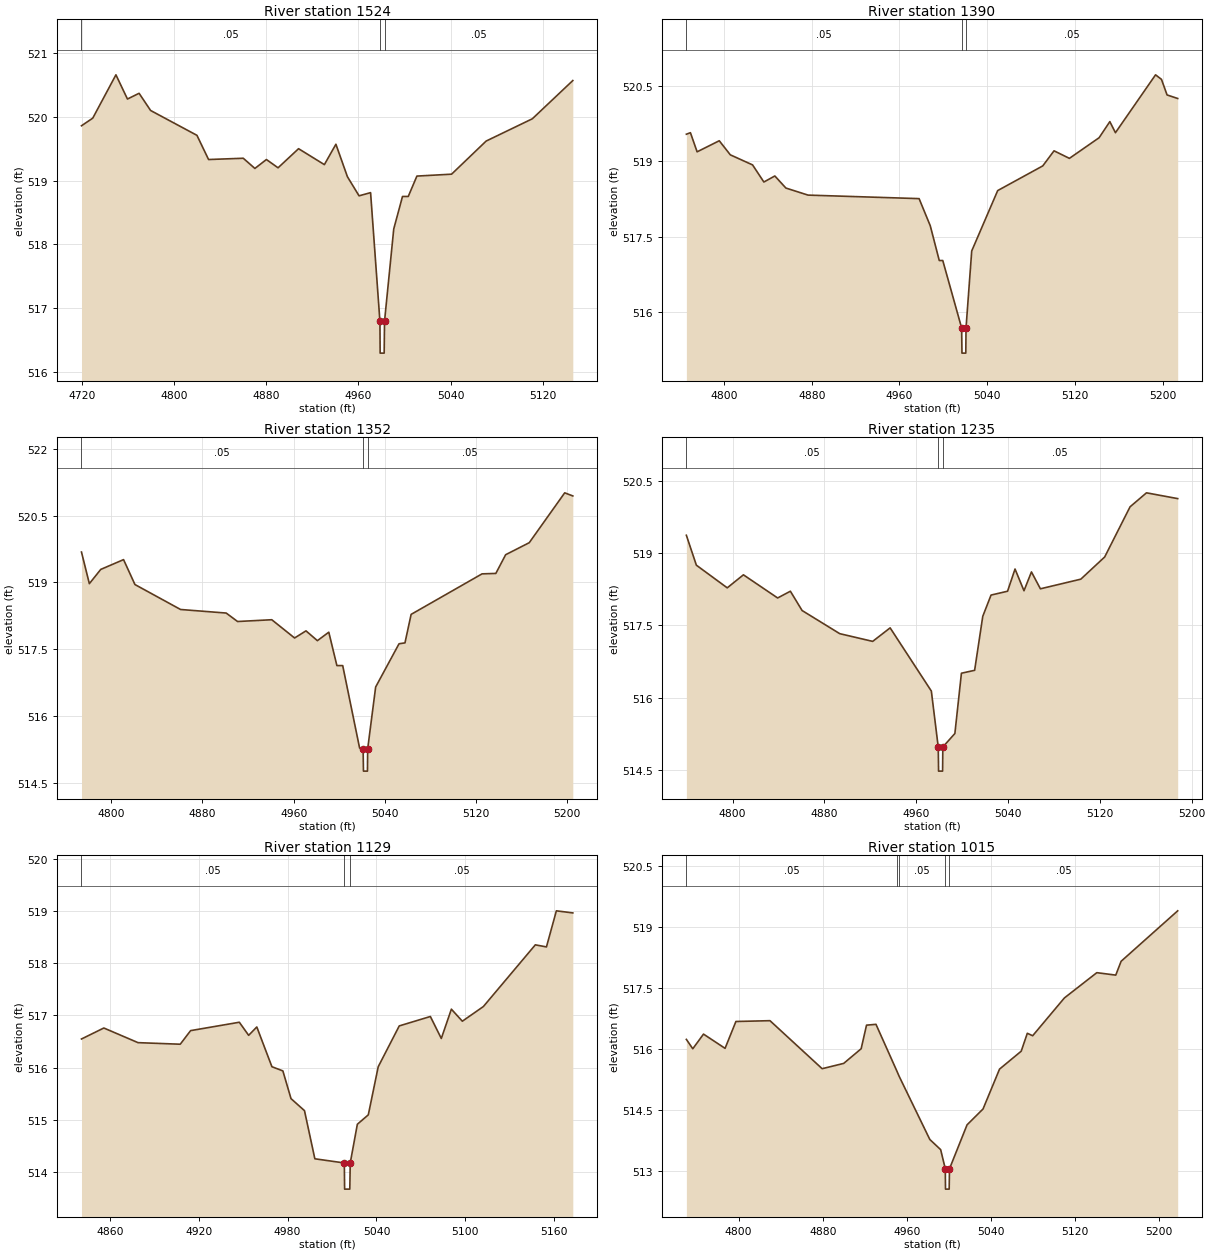
Type RM Length L Ch R = 1,1524,134,134,134
BEGIN DESCRIPTION:
Lacy 041 2841
END DESCRIPTION:
XS GIS Cut Line= 3
      2766655.74      6899844.67      2766375.97      6899817.20
      2766230.93      6899825.53
#Sta/Elev= 30
  4719.7  519.86  4729.5  519.98  4749.6  520.66  4759.6  520.28  4769.7  520.37
  4779.7  520.10  4819.9  519.71  4830.0  519.33  4860.1  519.35  4870.2  519.19
  4880.2  519.33  4890.3  519.20  4908.1  519.50  4930.5  519.25  4940.5  519.57
  4950.5  519.06  4960.6  518.76  4970.6  518.81  4978.7  516.79  4978.9  516.29
  4982.4  516.29  4982.7  516.79  4990.7  518.24  4998.3  518.75  5003.3  518.75
  5010.8  519.07  5040.9  519.10  5070.9  519.62  5111.0  519.97  5146.1  520.57
#Mann=3,-1,0
  4719.7    0.05       0  4978.7    0.04       0  4982.7    0.05       0
Bank Sta=4978.7,4982.7
Exp/Cntr=0.3,0.1

Type RM Length L Ch R = 1,1390,38,38,38
BEGIN DESCRIPTION:
Lacy 041 2840
END DESCRIPTION:
XS GIS Cut Line= 3
      2766655.64      6899736.42      2766424.70      6899699.34
      2766216.33      6899749.40
#Sta/Elev= 30
  4765.6  519.54  4769.3  519.57  4775.4  519.19  4795.6  519.41  4805.7  519.13
  4826.0  518.93  4836.3  518.59  4846.3  518.71  4856.4  518.47  4876.6  518.33
  4977.9  518.26  4988.1  517.72  4996.3  517.03  4999.5  517.03  5016.7  515.69
  5017.0  515.19  5020.5  515.19  5020.7  515.69  5025.9  517.22  5049.6  518.42
  5090.7  518.91  5101.0  519.21  5115.0  519.06  5142.1  519.47  5151.9  519.79
  5157.0  519.57  5193.6  520.72  5199.0  520.63  5204.1  520.32  5213.8  520.25
#Mann=3,-1,0
  4765.6    0.05       0  5016.7    0.04       0  5020.7    0.05       0
Bank Sta=5016.7,5020.7
Exp/Cntr=0.3,0.1

Type RM Length L Ch R = 1,1352,117,117,117
BEGIN DESCRIPTION:
Lacy 041 2839
END DESCRIPTION:
XS GIS Cut Line= 3
      2766652.86      6899666.00      2766426.82      6899661.00
      2766229.14      6899714.53
#Sta/Elev= 30
  4773.9  519.68  4780.8  518.97  4790.8  519.29  4810.8  519.51  4820.8  518.95
  4860.8  518.39  4900.8  518.31  4910.8  518.12  4940.8  518.16  4960.8  517.75
  4970.8  517.91  4980.8  517.69  4990.8  517.88  4997.9  517.13  5003.0  517.13
  5017.8  515.28  5020.9  515.26  5021.2  514.76  5024.7  514.76  5024.9  515.26
  5031.9  516.65  5052.4  517.62  5057.6  517.64  5063.0  518.28  5125.2  519.19
  5137.3  519.20  5145.9  519.62  5166.6  519.89  5197.7  521.01  5204.8  520.94
#Mann=3,-1,0
  4773.9    0.05       0  5020.9    0.04       0  5024.9    0.05       0
Bank Sta=5020.9,5024.9
Exp/Cntr=0.3,0.1

Type RM Length L Ch R = 1,1235,106,106,106
BEGIN DESCRIPTION:
Lacy 041 2838
END DESCRIPTION:
XS GIS Cut Line= 3
      2766614.52      6899508.12      2766379.86      6899559.40
      2766235.49      6899679.50
#Sta/Elev= 30
  4759.8  519.37  4768.5  518.75  4795.4  518.28  4809.5  518.55  4839.3  518.07
  4850.4  518.21  4860.6  517.81  4893.4  517.33  4922.1  517.17  4937.3  517.45
  4973.2  516.14  4979.2  514.98  4979.5  514.48  4983.0  514.48  4983.2  514.98
  4993.7  515.26  4999.4  516.51  5010.9  516.57  5018.0  517.69  5025.2  518.13
  5039.6  518.21  5046.1  518.67  5053.9  518.22  5060.4  518.61  5068.2  518.26
  5103.4  518.46  5124.2  518.92  5146.3  519.96  5160.6  520.25  5187.8  520.13
#Mann=3,-1,0
  4759.8    0.05       0  4979.2    0.05       0  4983.2    0.05       0
Bank Sta=4979.2,4983.2
Exp/Cntr=0.3,0.1

Type RM Length L Ch R = 1,1129,114,114,114
BEGIN DESCRIPTION:
Lacy 041 2837
END DESCRIPTION:
XS GIS Cut Line= 3
      2766513.11      6899389.02      2766368.14      6899454.83
      2766252.09      6899582.58
#Sta/Elev= 30
  4840.8  516.55  4855.9  516.76  4879.0  516.48  4907.5  516.45  4914.5  516.71
  4947.4  516.87  4953.7  516.62  4959.2  516.78  4969.4  516.02  4976.8  515.94
  4982.3  515.41  4991.4  515.18  4998.4  514.26  5018.3  514.18  5018.5  513.68
  5022.0  513.68  5022.3  514.18  5027.1  514.92  5034.5  515.10  5041.2  516.02
  5055.4  516.80  5076.4  516.98  5083.8  516.56  5090.6  517.12  5098.0  516.89
  5112.2  517.17  5147.3  518.35  5154.8  518.31  5161.5  519.00  5172.6  518.96
#Mann=3,-1,0
  4840.8    0.05       0  5018.3    0.05       0  5022.3    0.05       0
Bank Sta=5018.3,5022.3
Exp/Cntr=0.3,0.1

Type RM Length L Ch R = 1,1015,158,158,158
BEGIN DESCRIPTION:
Lacy 041 2836
END DESCRIPTION:
XS GIS Cut Line= 3
      2766531.92      6899319.34      2766288.56      6899373.96
      2766237.87      6899585.76
#Sta/Elev= 30
  4750.3  516.23  4756.4  516.00  4766.6  516.36  4787.1  516.01  4797.4  516.67
  4829.8  516.69  4879.4  515.51  4899.9  515.64  4916.5  516.00  4921.6  516.58
  4930.6  516.60  4950.5  515.45  4952.5  515.33  4981.8  513.77  4992.1  513.52
  4996.5  513.05  4996.7  512.55  5000.2  512.55  5000.5  513.05  5017.2  514.13
  5032.4  514.52  5048.1  515.50  5068.7  515.94  5074.5  516.38  5079.6  516.32
  5109.8  517.25  5140.6  517.87  5158.6  517.81  5163.7  518.15  5217.5  519.39
#Mann=5,-1,0
  4750.3    0.05       0  4950.5    0.12       0  4952.5    0.05       0
  4996.5    0.05       0  5000.5    0.05       0
Bank Sta=4996.5,5000.5
Exp/Cntr=0.3,0.1

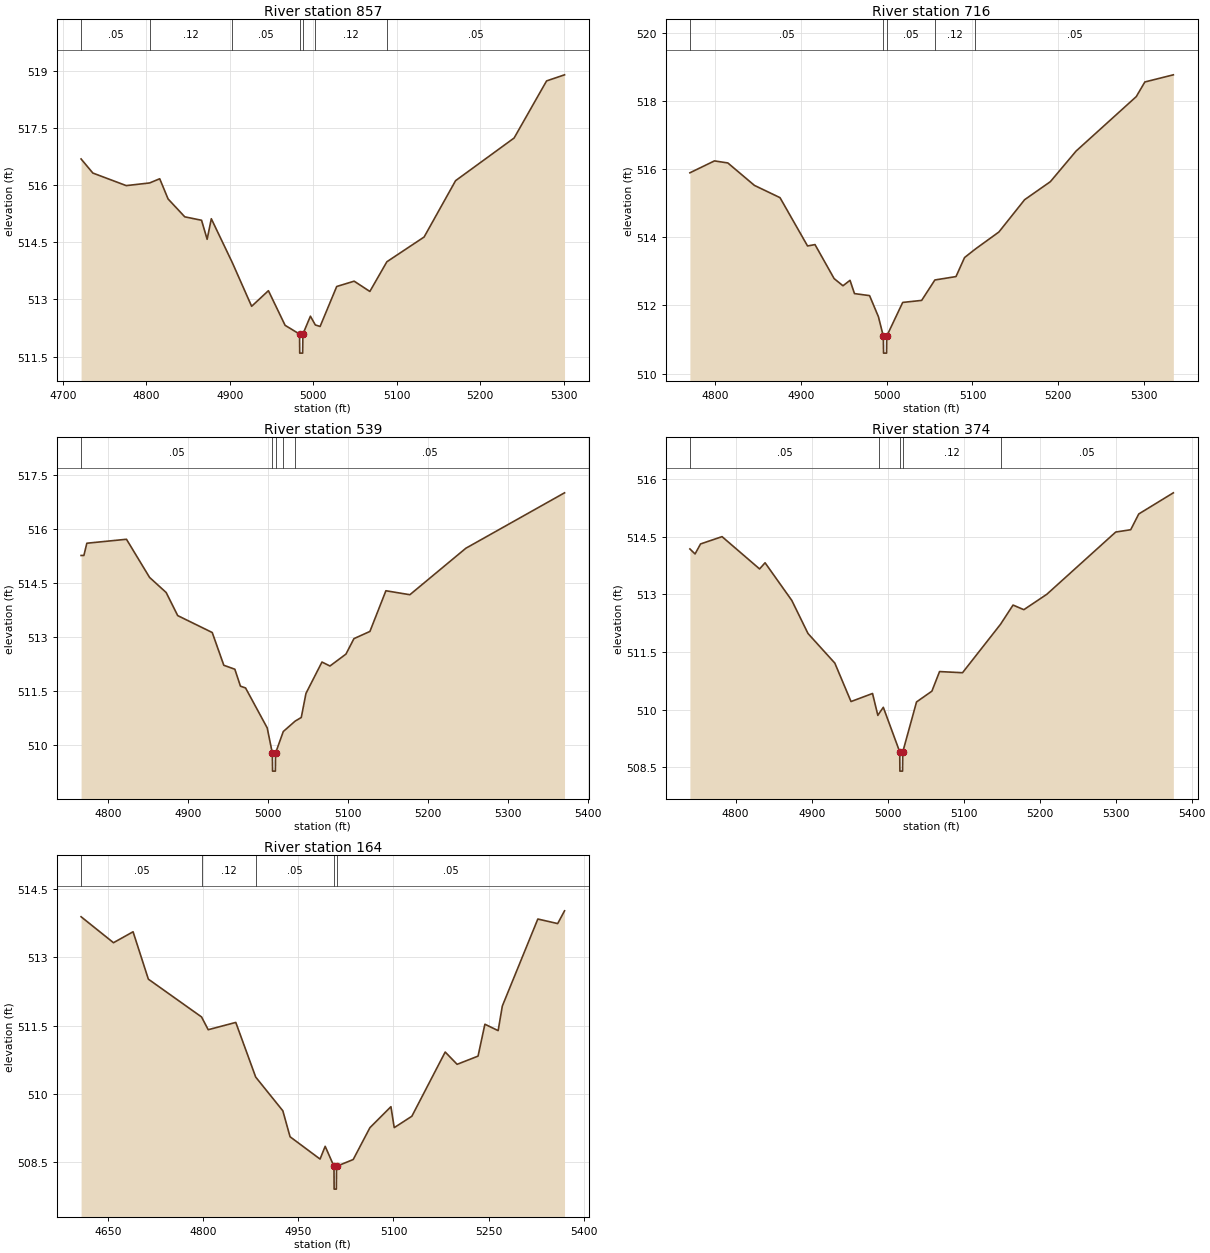
Type RM Length L Ch R = 1,857,141,141,141
BEGIN DESCRIPTION:
Lacy 041 2834
END DESCRIPTION:
XS GIS Cut Line= 3
      2766520.07      6899263.64      2766252.46      6899250.23
      2765955.52      6899157.28
#Sta/Elev= 30
  4721.9  516.69  4736.0  516.32  4776.0  515.99  4804.0  516.06  4816.1  516.17
  4826.1  515.64  4846.1  515.17  4866.2  515.08  4872.9  514.58  4877.9  515.12
  4903.0  513.97  4926.2  512.82  4946.3  513.23  4966.3  512.32  4983.6  512.09
  4983.8  511.59  4987.3  511.59  4987.6  512.09  4996.6  512.56  5002.5  512.33
  5008.2  512.29  5028.1  513.34  5049.0  513.48  5067.8  513.21  5088.2  513.99
  5132.8  514.64  5170.5  516.12  5240.6  517.24  5279.5  518.74  5301.0  518.90
#Mann=7,-1,0
  4721.9    0.05       0  4804.0    0.12       0  4903.0    0.05       0
  4983.6    0.05       0  4987.6    0.05       0  5002.5    0.12       0
  5088.2    0.05       0
Bank Sta=4983.6,4987.6
Exp/Cntr=0.3,0.1

Type RM Length L Ch R = 1,716,177,177,177
BEGIN DESCRIPTION:
Lacy 041 2835
END DESCRIPTION:
XS GIS Cut Line= 3
      2766498.85      6899173.06      2766274.40      6899115.57
      2765942.78      6899122.98
#Sta/Elev= 30
  4770.7  515.90  4799.3  516.25  4814.9  516.19  4845.9  515.53  4875.7  515.17
  4907.8  513.75  4916.5  513.79  4938.8  512.79  4949.1  512.58  4957.3  512.74
  4962.5  512.35  4980.1  512.29  4990.4  511.67  4996.1  511.10  4996.4  510.60
  4999.9  510.60  5000.1  511.10  5018.7  512.09  5040.8  512.15  5056.2  512.75
  5080.8  512.85  5090.8  513.41  5103.4  513.66  5130.8  514.16  5160.8  515.11
  5190.8  515.64  5220.8  516.54  5290.9  518.14  5300.9  518.57  5334.1  518.78
#Mann=5,-1,0
  4770.7    0.05       0  4996.1    0.04       0  5000.1    0.05       0
  5056.2    0.12       0  5103.4    0.05       0
Bank Sta=4996.1,5000.1
Exp/Cntr=0.3,0.1

Type RM Length L Ch R = 1,539,165,165,165
BEGIN DESCRIPTION:
Lacy 041 2833
END DESCRIPTION:
XS GIS Cut Line= 3
      2766506.51      6899100.54      2766323.64      6898955.02
      2765952.55      6898963.89
#Sta/Elev= 30
  4766.3  515.27  4769.8  515.27  4773.5  515.61  4823.1  515.72  4852.0  514.66
  4872.8  514.24  4887.2  513.60  4930.4  513.13  4944.9  512.22  4958.7  512.11
  4965.7  511.64  4972.1  511.59  4999.2  510.48  5005.6  509.78  5005.9  509.28
  5009.4  509.28  5009.6  509.78  5019.3  510.38  5034.2  510.67  5041.8  510.77
  5047.7  511.44  5067.7  512.31  5077.7  512.20  5097.7  512.53  5107.7  512.96
  5127.7  513.16  5147.7  514.29  5177.7  514.18  5247.7  515.47  5371.2  517.01
#Mann=5,-1,0
  4766.3    0.05       0  5005.6    0.04       0  5009.6    0.05       0
  5019.3    0.12       0  5034.2    0.05       0
Bank Sta=5005.6,5009.6
Exp/Cntr=0.3,0.1

Type RM Length L Ch R = 1,374,210,210,210
BEGIN DESCRIPTION:
Lacy 041 2832
END DESCRIPTION:
XS GIS Cut Line= 3
      2766559.91      6898986.84      2766373.74      6898805.06
      2766000.85      6898852.50
#Sta/Elev= 30
  4739.8  514.18  4746.6  514.05  4753.8  514.31  4782.1  514.50  4831.5  513.66
  4838.7  513.82  4873.9  512.84  4895.2  511.98  4930.5  511.21  4951.8  510.21
  4980.1  510.42  4987.1  509.85  4989.0  509.91  4994.3  510.06  5015.9  508.90
  5016.1  508.40  5019.6  508.40  5019.9  508.90  5038.0  510.20  5058.2  510.48
  5068.3  510.99  5098.5  510.96  5148.5  512.22  5165.0  512.72  5179.2  512.60
  5209.4  513.00  5300.1  514.62  5319.8  514.68  5330.4  515.09  5375.9  515.64
#Mann=5,-1,0
  4739.8    0.05       0  4989.0    0.12       0  5015.9    0.07       0
  5019.9    0.12       0  5148.5    0.05       0
Bank Sta=5015.9,5019.9
Exp/Cntr=0.3,0.1

Type RM Length L Ch R = 1,164,0,0,0
BEGIN DESCRIPTION:
Lacy 041 2831
END DESCRIPTION:
XS GIS Cut Line= 4
      2766549.09      6898941.08      2766435.16      6898617.89
      2766358.94      6898586.78      2766035.70      6898683.82
#Sta/Elev= 30
  4607.3  513.89  4658.4  513.32  4689.3  513.56  4713.4  512.52  4797.3  511.69
  4807.8  511.41  4851.3  511.57  4882.7  510.37  4925.5  509.63  4936.9  509.06
  4984.2  508.57  4992.3  508.85  5006.2  508.41  5006.4  507.91  5009.9  507.91
  5010.2  508.41  5036.5  508.56  5062.9  509.26  5096.0  509.72  5101.2  509.26
  5129.0  509.51  5181.6  510.92  5200.4  510.65  5233.4  510.83  5244.2  511.53
  5265.1  511.39  5271.7  511.93  5327.7  513.84  5359.0  513.74  5369.8  514.02
#Mann=5,-1,0
  4607.3    0.05       0  4797.3    0.12       0  4882.7    0.05       0
  5006.2    0.05       0  5010.2    0.05       0
Bank Sta=5006.2,5010.2
Exp/Cntr=0.3,0.1

Chan Stop Cuts=-1