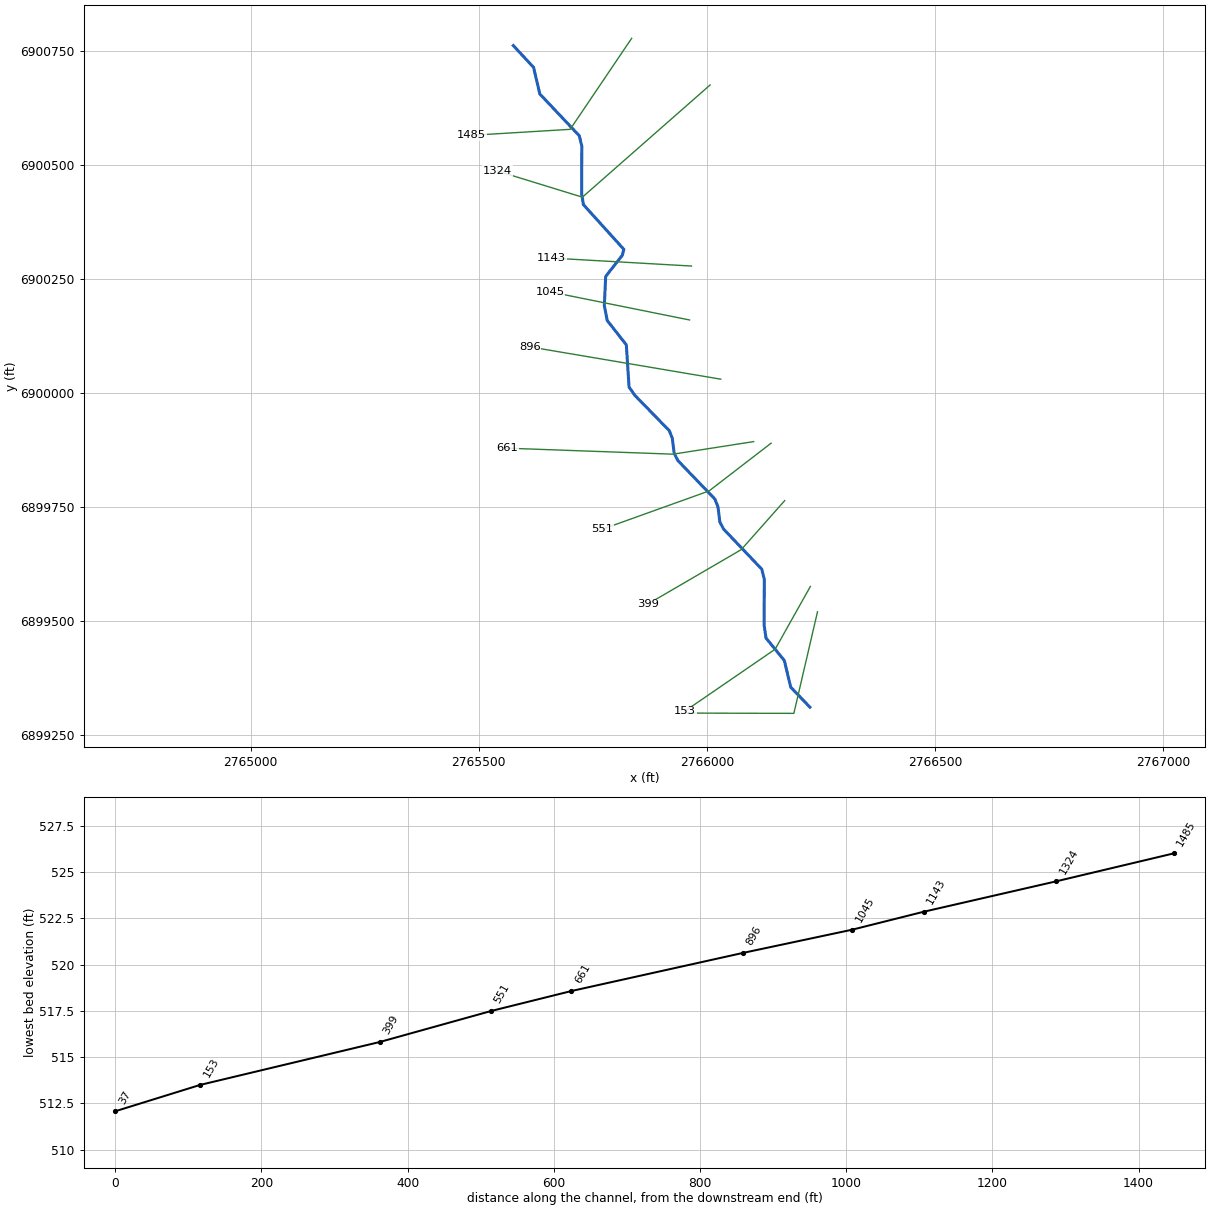
--- Lacy 042.prj (project) ---

Proj Title=Lacy 042 Base Level Engineering
Current Plan=p01
Default Exp/Contr=0.3,0.1
English Units
Geom File=g01
Flow File=f01
Plan File=p01
Y Axis Title=Elevation
X Axis Title(PF)=Main Channel Distance
X Axis Title(XS)=Station
BEGIN DESCRIPTION:
Lacy 042
END DESCRIPTION:
DSS Export Rating Curves= 0
DSS Export Rating Curve Sorted= 0
DSS Export Volume Flow Curves= 0
DXF OffsetX= 0
DXF OffsetY= 0
DXF ScaleX= 1
DXF ScaleY= 10

--- Lacy 042.p01 (plan) ---

Plan Title=Multiple Run
Short Identifier=Multiple
Geom File=g01
Flow File=f01
Subcritical Flow
K Sum by GR= 0
Std Step Tol= 0.01
Critical Tol= 0.01
Num of Std Step Trials= 20
Max Error Tol= 0.3
Flow Tol Ratio= 0.001
Split Flow NTrial= 30
Split Flow Tol= 0.02
Split Flow Ratio= 0.02
Log Output Level= 0
Friction Slope Method= 1
Unsteady Friction Slope Method= 2
Unsteady Bridges Friction Slope Method= 1
Parabolic Critical Depth
Global Vel Dist=  1 , 1 , 1
Global Log Level= 0
CheckData=True
Encroach Param= -1, 0, 0, 0
BEGIN DESCRIPTION:
Multiple Run
END DESCRIPTION:

--- Lacy 042.f01 (steady flow) ---

Flow Title=Multiple
Number of Profiles=7
Profile Names=10-year,25-year,50-year,1pct_min,100-year,1pct_plu,500-year
River Rch & RM= Lacy 042,Reach-1,1485
      32      34      35      18      37      74      40
Boundary for River Rch & Prof#=Lacy 042,Reach-1,1
Up Type=0
Dn Type=3
Dn Slope=0.005
Boundary for River Rch & Prof#=Lacy 042,Reach-1,2
Up Type=0
Dn Type=3
Dn Slope=0.005
Boundary for River Rch & Prof#=Lacy 042,Reach-1,3
Up Type=0
Dn Type=3
Dn Slope=0.005
Boundary for River Rch & Prof#=Lacy 042,Reach-1,4
Up Type=0
Dn Type=3
Dn Slope=0.005
Boundary for River Rch & Prof#=Lacy 042,Reach-1,5
Up Type=0
Dn Type=3
Dn Slope=0.005
Boundary for River Rch & Prof#=Lacy 042,Reach-1,6
Up Type=0
Dn Type=3
Dn Slope=0.005
Boundary for River Rch & Prof#=Lacy 042,Reach-1,7
Up Type=0
Dn Type=3
Dn Slope=0.005

--- Lacy 042.g01 (geometry) ---

Geom Title=Existing Conditions
Program Version=4.10

River Reach=Lacy 042        ,Reach-1
Reach XY= 30
        2765576.        6900761.       2765620.3      6900713.35
      2765634.07      6900654.92      2765720.52      6900563.44
      2765726.02      6900541.01      2765725.74      6900435.89
      2765729.57      6900412.47      2765818.19      6900314.41
      2765814.66      6900301.15      2765778.37      6900255.11
      2765775.42      6900190.96      2765781.68      6900158.69
      2765823.64      6900105.02      2765829.62       6900012.5
      2765842.49      6899994.26      2765917.82      6899917.04
      2765924.45      6899900.36      2765928.54      6899867.05
       2765936.8      6899851.33      2766017.82      6899767.04
      2766024.45      6899750.36      2766028.54      6899717.05
       2766036.8      6899701.33      2766120.52      6899613.44
      2766126.02      6899591.01      2766125.67      6899490.86
      2766129.75      6899462.55      2766169.97      6899413.22
      2766183.91      6899354.85        2766226.        6899311.

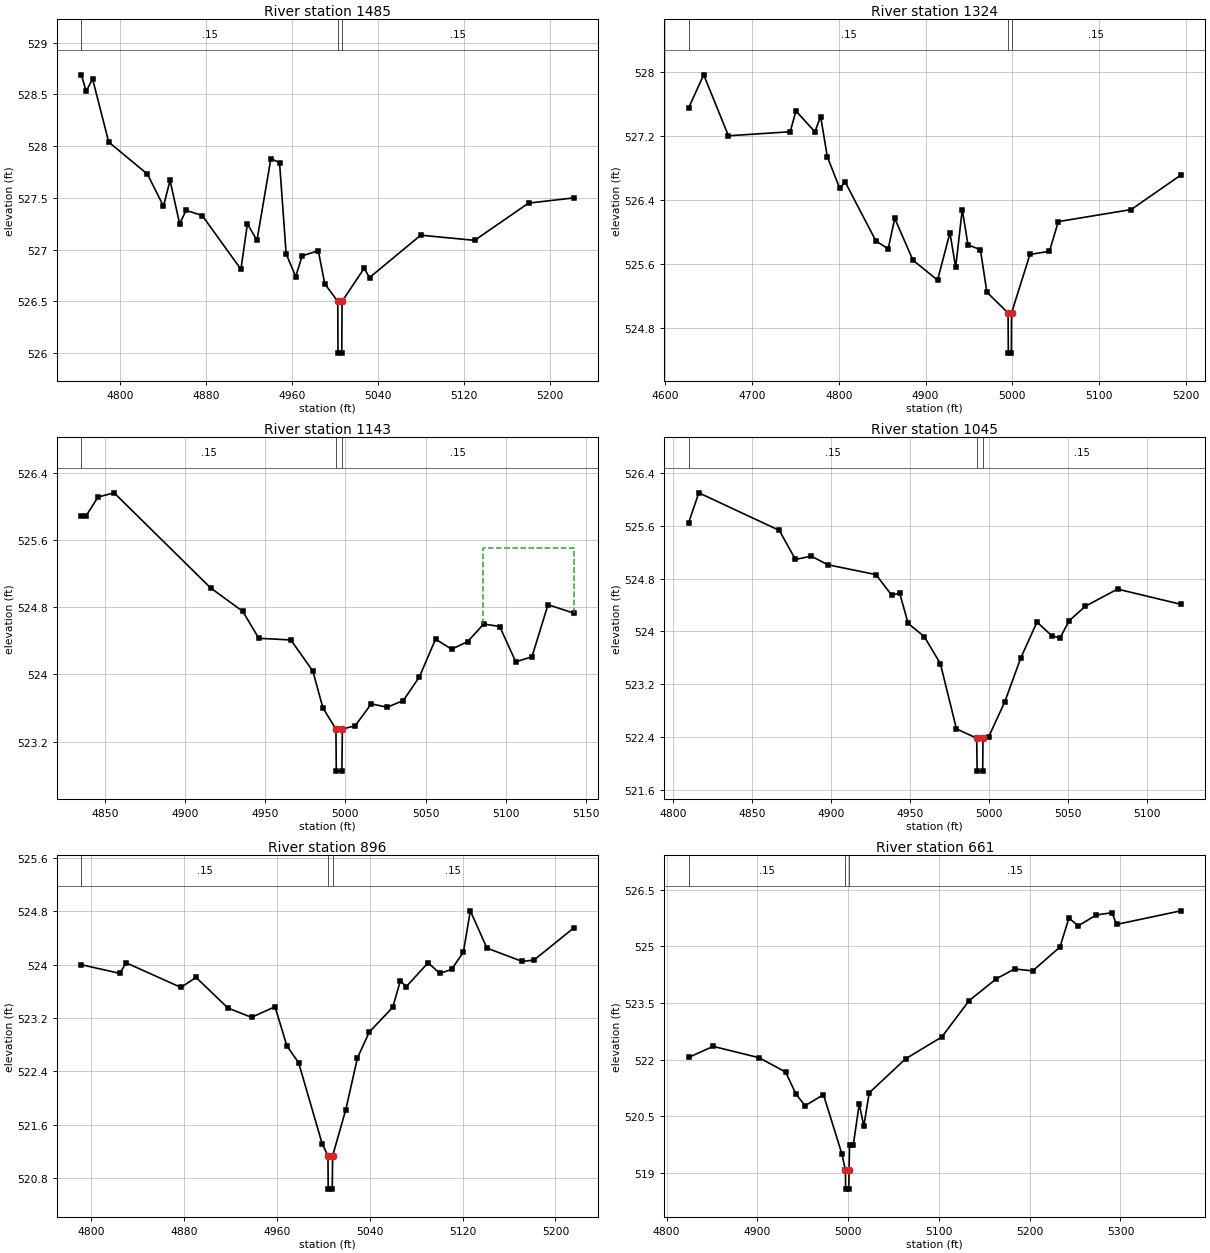
Type RM Length L Ch R = 1 ,1485    ,161,161,161
BEGIN DESCRIPTION:
Lacy 042 2847
END DESCRIPTION:
XS GIS Cut Line= 3
      2765835.29      6900776.93      2765700.53      6900577.49
      2765484.23      6900564.37
#Sta/Elev= 30
  4764.3  528.69  4768.7  528.53  4774.7  528.65  4789.7  528.04  4825.7  527.73
  4840.6  527.42  4846.7  527.67  4855.6  527.25  4861.6  527.38  4876.6  527.33
  4912.6  526.81  4918.6  527.25  4927.5  527.09  4940.4  527.88  4948.5  527.84
  4954.6  526.96  4963.5  526.74  4969.5  526.94  4984.5  526.99  4990.5  526.67
  5002.6   526.5  5002.8     526  5006.3     526  5006.6   526.5  5027.1  526.82
  5032.1  526.73  5079.7  527.14  5129.8  527.09  5179.9  527.45  5221.7   527.5
#Mann= 3 ,-1 , 0
  4764.3     .15       0  5002.6     .05       0  5006.6     .15       0
Bank Sta=5002.6,5006.6
XS Rating Curve= 0 ,0
Exp/Cntr=0.3,0.1

Type RM Length L Ch R = 1 ,1324    ,181,181,181
BEGIN DESCRIPTION:
Lacy 042 2846
END DESCRIPTION:
XS GIS Cut Line= 3
      2766007.19      6900674.68      2765727.29      6900428.78
       2765541.3      6900486.11
#Sta/Elev= 30
    4627  527.55  4644.3  527.96  4672.8   527.2    4744  527.25  4750.6  527.51
  4772.4  527.25  4779.1  527.44  4786.7  526.94  4800.9  526.55  4807.5  526.62
  4842.7  525.89  4856.9  525.79  4864.5  526.17  4885.4  525.65  4913.8   525.4
  4928.1  525.99  4934.7  525.56  4942.3  526.28  4948.9  525.84  4963.2  525.78
  4970.7  525.25  4995.1  524.99  4995.4  524.49  4998.9  524.49  4999.1  524.99
  5020.3  525.72  5042.8  525.76    5053  526.13    5137  526.28  5194.2  526.71
#Mann= 3 ,-1 , 0
    4627     .15       0  4995.1     .05       0  4999.1     .15       0
Bank Sta=4995.1,4999.1
XS Rating Curve= 0 ,0
Exp/Cntr=0.3,0.1

Type RM Length L Ch R = 1 ,1143    ,98,98,98
BEGIN DESCRIPTION:
Lacy 042 2845
END DESCRIPTION:
XS GIS Cut Line= 2
       2765966.4      6900277.86      2765660.09      6900295.32
#Sta/Elev= 28
  4835.4  525.88  4838.1  525.88  4845.8  526.11  4855.8  526.16  4915.9  525.03
    4936  524.75    4946  524.43    4966  524.41  4979.7  524.04    4986   523.6
  4994.1  523.35  4994.3  522.85  4997.8  522.85  4998.1  523.35  5006.1  523.39
  5016.1  523.65  5026.1  523.61  5036.1  523.69  5046.1  523.97  5056.2  524.42
  5066.2   524.3  5076.2  524.39  5086.2   524.6  5096.2  524.57  5106.2  524.15
  5116.3  524.21  5126.3  524.83  5142.2  524.73
#Mann= 3 ,-1 , 0
  4835.4     .15       0  4994.1     .05       0  4998.1     .15       0
#XS Ineff= 2 , 0
       0                    5086       0   525.5
Permanent Ineff=
       F       F
Bank Sta=4994.1,4998.1
XS Rating Curve= 0 ,0
Exp/Cntr=0.3,0.1

Type RM Length L Ch R = 1 ,1045    ,149,149,149
BEGIN DESCRIPTION:
Lacy 042 2843
END DESCRIPTION:
XS GIS Cut Line= 2
      2765962.25      6900159.63       2765656.7      6900221.27
#Sta/Elev= 27
  4809.7  525.65  4816.1   526.1  4867.1  525.53  4877.3  525.09  4887.4  525.14
  4897.7  525.01  4928.3  524.86  4938.2  524.55  4943.3  524.58  4948.7  524.12
  4958.9  523.92  4969.1  523.51  4979.3  522.52  4992.1  522.38  4992.4  521.88
  4995.9  521.88  4996.1  522.38  4999.7   522.4  5009.9  522.93  5020.1   523.6
  5030.3  524.14  5039.8  523.93  5044.9   523.9  5050.7  524.16  5060.9  524.38
  5081.3  524.64  5121.4  524.41
#Mann= 3 ,-1 , 0
  4809.7     .15       0  4992.1     .05       0  4996.1     .15       0
Bank Sta=4992.1,4996.1
XS Rating Curve= 0 ,0
Exp/Cntr=0.3,0.1

Type RM Length L Ch R = 1 ,896     ,235,235,235
BEGIN DESCRIPTION:
Lacy 042 2844
END DESCRIPTION:
XS GIS Cut Line= 2
      2766030.57      6900029.88      2765612.42      6900100.67
#Sta/Elev= 30
  4791.5     524  4824.8  523.87  4829.9  524.03  4877.3  523.66  4890.3  523.81
  4917.8  523.35  4938.1  523.21  4958.4  523.37  4968.6  522.78  4978.7  522.53
    4999  521.31    5004  521.13  5004.2  520.63  5007.7  520.63    5008  521.13
  5019.3  521.82  5029.4   522.6  5039.6  522.99  5059.8  523.36  5066.4  523.76
  5071.4  523.67  5090.3  524.03  5100.4  523.87  5110.5  523.93  5120.7  524.19
  5126.7  524.81    5141  524.25  5171.4  524.05  5181.5  524.07  5215.6  524.55
#Mann= 3 ,-1 , 0
  4791.5     .15       0    5004     .05       0    5008     .15       0
Bank Sta=5004,5008
XS Rating Curve= 0 ,0
Exp/Cntr=0.3,0.1

Type RM Length L Ch R = 1 ,661     ,110,110,110
BEGIN DESCRIPTION:
Lacy 042 2842
END DESCRIPTION:
XS GIS Cut Line= 3
       2766102.7      6899893.06      2765926.14      6899865.52
      2765562.88      6899878.65
#Sta/Elev= 30
  4824.3  522.06  4851.3  522.35  4901.9  522.05  4931.1  521.67  4942.4  521.09
  4952.5  520.78  4972.8  521.07    4993  519.51    4997  519.07  4997.2  518.57
  5000.7  518.57    5001  519.07  5001.5  519.73  5005.6  519.73  5012.2  520.83
  5017.2  520.24  5023.2  521.12  5063.2  522.02  5103.2   522.6  5133.2  523.56
  5163.2  524.14  5183.3   524.4  5203.3  524.35  5233.3  524.98  5243.3  525.75
  5253.3  525.54  5273.3  525.83  5290.7  525.89  5295.7  525.58  5366.5  525.94
#Mann= 3 ,-1 , 0
  4824.3     .15       0    4997     .05       0    5001     .15       0
Bank Sta=4997,5001
XS Rating Curve= 0 ,0
Exp/Cntr=0.3,0.1

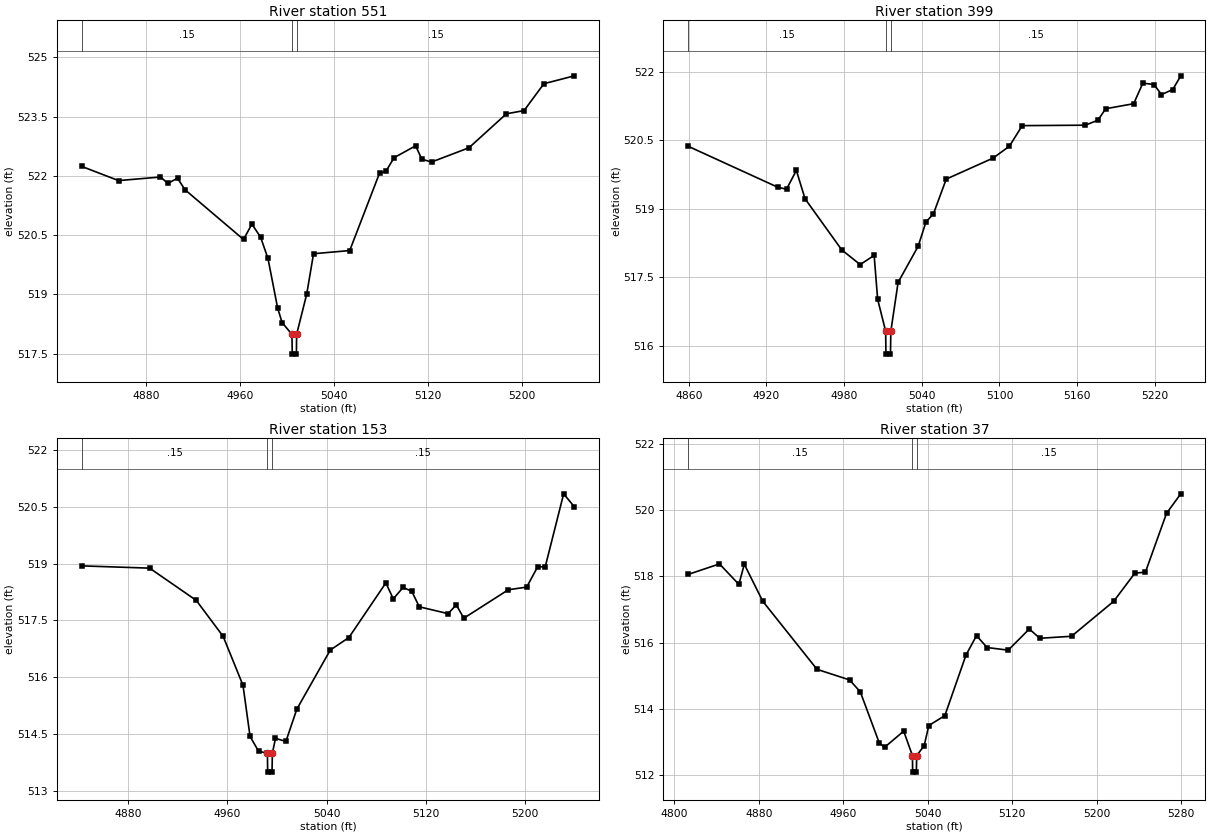
Type RM Length L Ch R = 1 ,551     ,152,152,152
BEGIN DESCRIPTION:
Lacy 042 3489
END DESCRIPTION:
XS GIS Cut Line= 3
      2766140.94      6899889.57      2766004.92      6899784.89
      2765771.61      6899701.21
#Sta/Elev= 30
    4825  522.24  4856.5  521.88  4892.2  521.97  4898.5  521.81  4906.7  521.94
    4913  521.65  4962.9  520.39    4970  520.78  4977.4  520.45  4983.7  519.91
  4991.9  518.66  4995.7  518.29  5004.1  517.99  5004.4  517.49  5007.9  517.49
  5008.1  517.99  5016.7  519.01  5022.5  520.03  5053.3  520.11  5078.7  522.07
    5084  522.11  5091.1  522.46  5109.4  522.76  5114.7  522.42    5123  522.35
  5154.8  522.71  5186.7  523.57  5201.7  523.65  5218.6  524.33  5244.5  524.53
#Mann= 3 ,-1 , 0
    4825     .15       0  5004.1     .05       0  5008.1     .15       0
Bank Sta=5004.1,5008.1
XS Rating Curve= 0 ,0
Exp/Cntr=0.3,0.1

Type RM Length L Ch R = 1 ,399     ,246,246,246
BEGIN DESCRIPTION:
Lacy 042 2851
END DESCRIPTION:
XS GIS Cut Line= 3
       2766170.8      6899763.78      2766075.38      6899656.19
      2765870.68      6899536.97
#Sta/Elev= 30
  4859.4  520.37  4928.9  519.47  4935.5  519.43  4943.1  519.84  4949.8  519.22
  4978.2   518.1  4992.4  517.78  5003.2  517.98  5005.9  517.02  5012.1  516.32
  5012.3  515.82  5015.8  515.82  5016.1  516.32  5021.7  517.39  5037.2  518.18
  5043.2  518.71    5049  518.89  5058.9  519.65  5095.1  520.11  5107.7  520.37
  5117.6  520.82  5166.4  520.83  5176.1  520.94  5182.1  521.19  5203.7   521.3
  5210.8  521.75  5219.4  521.72  5225.2   521.5  5233.9  521.61  5240.1  521.91
#Mann= 3 ,-1 , 0
  4859.4     .15       0  5012.1     .05       0  5016.1     .15       0
Bank Sta=5012.1,5016.1
XS Rating Curve= 0 ,0
Exp/Cntr=0.3,0.1

Type RM Length L Ch R = 1 ,153     ,116,116,116
BEGIN DESCRIPTION:
Lacy 042 2849
END DESCRIPTION:
XS GIS Cut Line= 3
      2766226.96      6899575.51      2766149.77      6899437.99
      2765952.08      6899302.43
#Sta/Elev= 30
  4842.3  518.94  4897.2  518.88  4934.8  518.03  4956.5  517.08  4972.5  515.79
  4978.2  514.44  4985.1  514.05  4992.2     514  4992.4   513.5  4995.9   513.5
  4996.2     514  4998.7  514.39  5007.1  514.31  5015.9  515.16  5042.9  516.72
  5057.9  517.05  5087.7  518.49  5093.7  518.07  5101.6  518.37  5108.6  518.27
  5114.7  517.86  5137.9  517.68  5144.5  517.91  5150.6  517.56  5186.5  518.31
  5201.3  518.38  5210.2  518.92  5216.2  518.91  5231.1  520.84  5239.7   520.5
#Mann= 3 ,-1 , 0
  4842.3     .15       0  4992.2     .05       0  4996.2     .15       0
Bank Sta=4992.2,4996.2
XS Rating Curve= 0 ,0
Exp/Cntr=0.3,0.1

Type RM Length L Ch R = 1 ,37      ,0,0,0
BEGIN DESCRIPTION:
Lacy 042 2848
END DESCRIPTION:
XS GIS Cut Line= 3
       2766242.6      6899519.99      2766190.81      6899297.42
      2765952.53      6899298.04
#Sta/Elev= 30
    4813  518.06  4842.8  518.38  4861.2  517.76  4866.3  518.37  4883.8  517.25
  4935.2  515.19    4966  514.87  4976.2  514.51  4994.1  512.97  4999.2  512.83
  5017.3  513.32  5025.6  512.58  5025.8  512.08  5029.3  512.08  5029.6  512.58
  5036.7  512.88  5041.1  513.49  5056.3  513.79  5076.3  515.62  5086.3  516.21
  5096.3  515.85  5116.3  515.77  5136.3  516.41  5146.3  516.13  5176.3  516.19
  5216.3  517.25  5236.3   518.1  5246.3  518.13  5266.3  519.91  5279.8   520.5
#Mann= 3 ,-1 , 0
    4813     .15       0  5025.6     .05       0  5029.6     .15       0
Bank Sta=5025.6,5029.6
XS Rating Curve= 0 ,0
Exp/Cntr=0.3,0.1

Chan Stop Cuts=-1
Use User Specified Reach Order=0
Composite Channel Slope=5