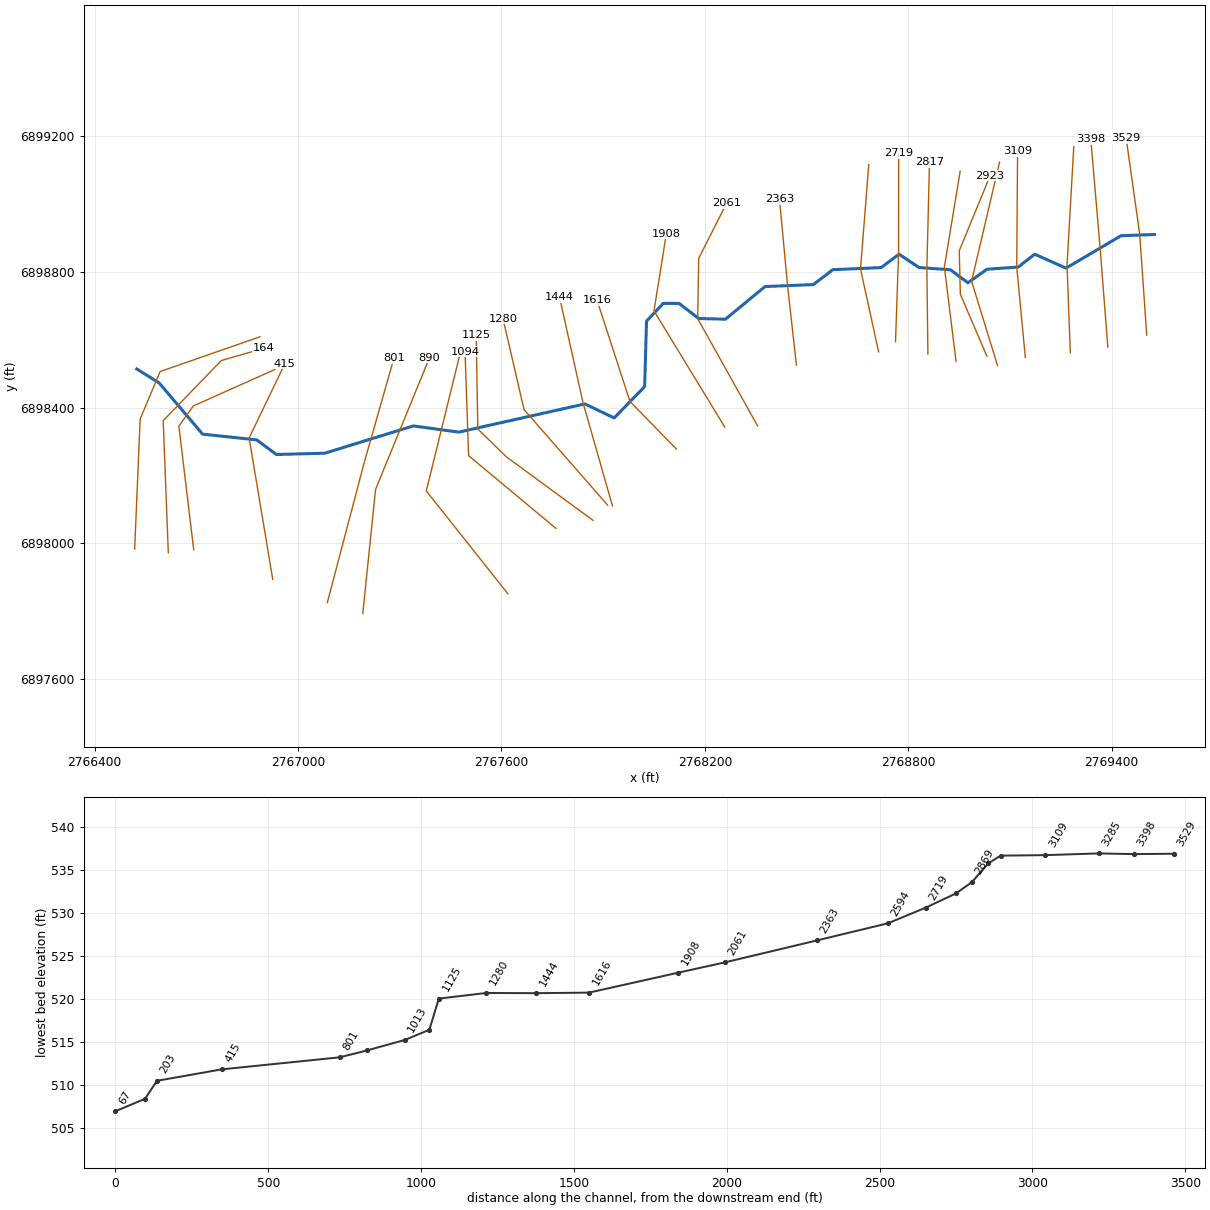
--- Lacy 043.prj (project) ---

Proj Title=Lacy 043 Base Level Engineering
Current Plan=p01
Default Exp/Contr=0.3,0.1
English Units
Geom File=g01
Flow File=f01
Plan File=p01
BEGIN DESCRIPTION:
Lacy 043
END DESCRIPTION:

--- Lacy 043.p01 (plan) ---

Plan Title=Multiple Run
Short Identifier=Multiple
Geom File=g01
Flow File=f01
Subcritical Flow
K Sum by GR= 0
Std Step Tol= 0.01
Critical Tol= 0.01
Num of Std Step Trials= 20
Max Error Tol= 0.3
Flow Tol Ratio= 0.001
Split Flow NTrial= 30
Split Flow Tol= 0.02
Split Flow Ratio= 0.02
Log Output Level= 0
Friction Slope Method= 1
Unsteady Friction Slope Method= 2
Unsteady Bridges Friction Slope Method= 1
Parabolic Critical Depth
Global Vel Dist=  1 , 1 , 1
Global Log Level= 0
CheckData=True
Encroach Param= -1, 0, 0, 0
BEGIN DESCRIPTION:
Multiple Run
END DESCRIPTION:

--- Lacy 043.f01 (steady flow) ---

Flow Title=Multiple
Number of Profiles=7
Profile Names=10-year,25-year,50-year,1pct_min,100-year,1pct_plu,500-year
River Rch & RM= Lacy 043,Reach-1,3529
     158     194     221     126     251     501     323
Boundary for River Rch & Prof#=Lacy 043,Reach-1,1
Up Type=0
Dn Type=3
Dn Slope=0.005
Boundary for River Rch & Prof#=Lacy 043,Reach-1,2
Up Type=0
Dn Type=3
Dn Slope=0.005
Boundary for River Rch & Prof#=Lacy 043,Reach-1,3
Up Type=0
Dn Type=3
Dn Slope=0.005
Boundary for River Rch & Prof#=Lacy 043,Reach-1,4
Up Type=0
Dn Type=3
Dn Slope=0.005
Boundary for River Rch & Prof#=Lacy 043,Reach-1,5
Up Type=0
Dn Type=3
Dn Slope=0.005
Boundary for River Rch & Prof#=Lacy 043,Reach-1,6
Up Type=0
Dn Type=3
Dn Slope=0.005
Boundary for River Rch & Prof#=Lacy 043,Reach-1,7
Up Type=0
Dn Type=3
Dn Slope=0.005

--- Lacy 043.g01 (geometry) ---

Geom Title=Existing Conditions

River Reach=Lacy 043,Reach-1
Reach XY= 30
      2769526.00      6898911.00      2769427.50      6898907.37
      2769265.30      6898811.80      2769172.71      6898852.90
      2769124.50      6898815.09      2769031.90      6898808.45
      2768976.00      6898768.56      2768924.50      6898806.91
      2768831.90      6898813.55      2768772.70      6898852.92
      2768720.14      6898813.47      2768577.57      6898807.21
      2768520.06      6898763.27      2768377.47      6898757.44
      2768260.78      6898661.25      2768181.97      6898663.19
      2768124.22      6898707.67      2768077.39      6898707.97
      2768027.98      6898655.38      2768022.46      6898462.44
      2767932.75      6898370.14      2767846.16      6898411.32
      2767474.15      6898328.17      2767340.24      6898346.51
      2767079.17      6898266.03      2766936.50      6898262.22
      2766878.33      6898305.26      2766718.72      6898322.24
      2766590.53      6898473.25      2766524.61      6898514.37

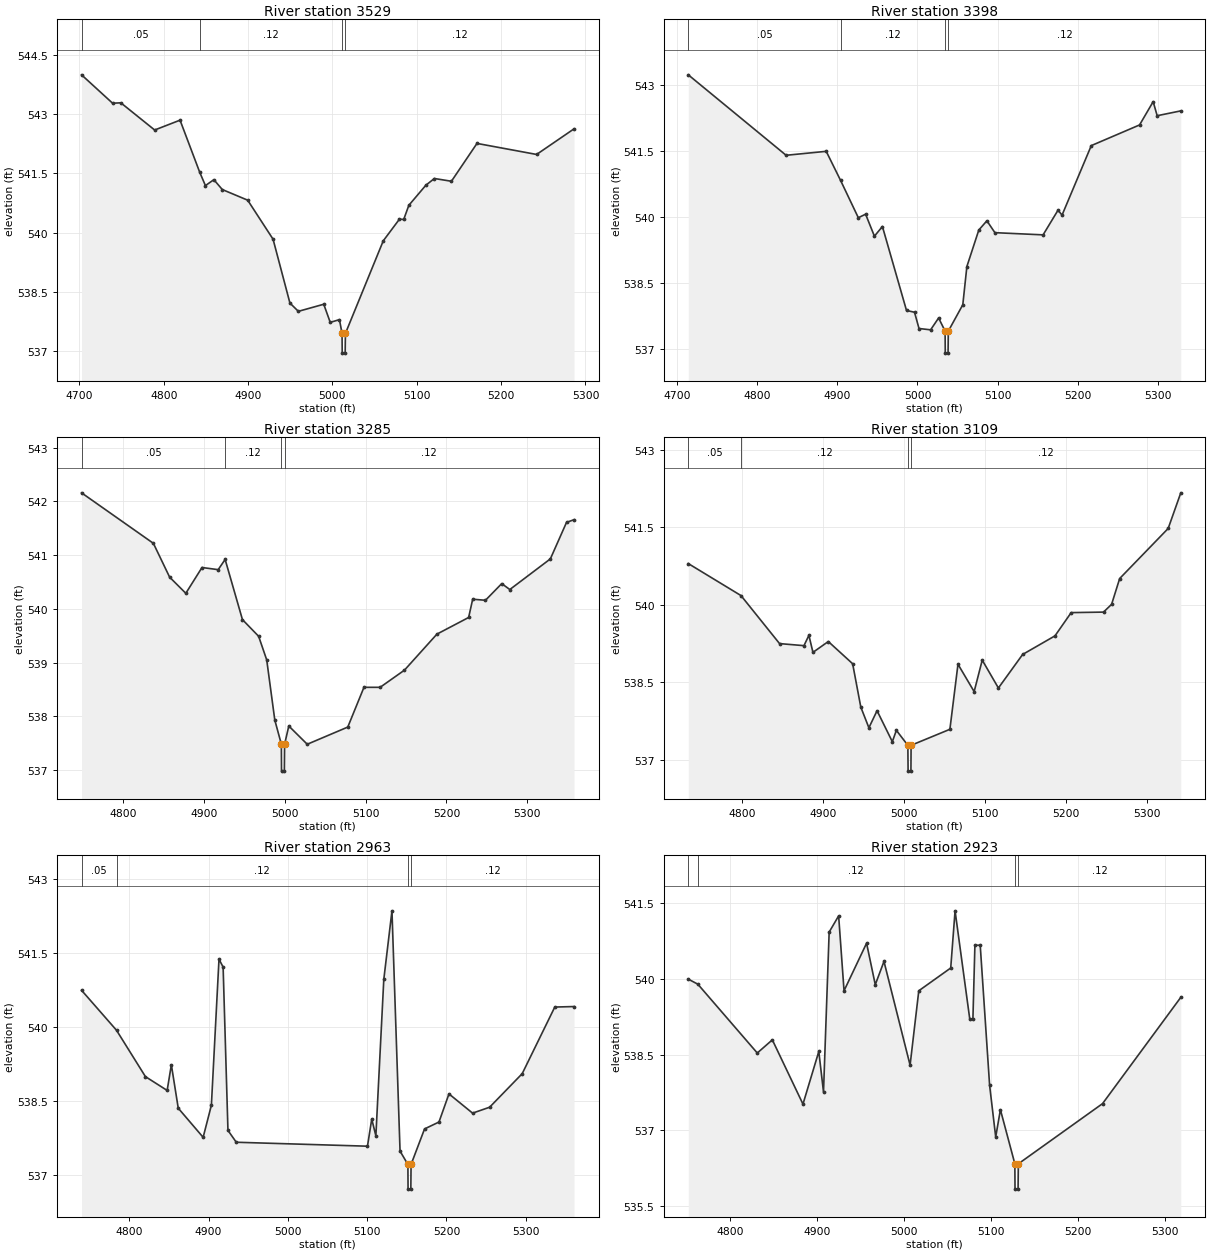
Type RM Length L Ch R = 1,3529,131,131,131
BEGIN DESCRIPTION:
Lacy 043 2813
END DESCRIPTION:
XS GIS Cut Line= 3
      2769503.22      6898614.49      2769482.66      6898911.28
      2769442.64      6899194.97
#Sta/Elev= 30
  4702.5  544.00  4739.3  543.28  4749.1  543.29  4789.2  542.60  4819.3  542.85
  4842.6  541.53  4849.4  541.19  4859.4  541.34  4869.4  541.09  4899.5  540.82
  4929.6  539.83  4949.6  538.21  4959.6  538.00  4989.7  538.18  4997.4  537.72
  5008.3  537.79  5011.4  537.44  5011.6  536.94  5015.1  536.94  5015.4  537.44
  5060.3  539.79  5079.5  540.34  5084.5  540.33  5090.6  540.69  5110.8  541.20
  5120.9  541.37  5141.1  541.30  5171.4  542.26  5242.1  541.98  5286.5  542.63
#Mann=4,-1,0
  4702.5    0.05       0  4842.6    0.12       0  5011.4    0.07       0
  5015.4    0.12       0
Bank Sta=5011.4,5015.4
Exp/Cntr=0.3,0.1

Type RM Length L Ch R = 1,3398,113,113,113
BEGIN DESCRIPTION:
Lacy 043 2812
END DESCRIPTION:
XS GIS Cut Line= 3
      2769388.60      6898579.22      2769366.07      6898867.02
      2769338.22      6899192.35
#Sta/Elev= 30
  4713.7  543.23  4835.9  541.40  4886.0  541.49  4903.9  540.83  4926.1  539.98
  4935.2  540.06  4946.2  539.56  4956.2  539.78  4986.3  537.87  4996.3  537.83
  5001.9  537.46  5016.4  537.43  5026.4  537.70  5034.5  537.40  5034.7  536.90
  5038.2  536.90  5038.5  537.40  5056.6  538.00  5061.7  538.87  5076.6  539.70
  5086.7  539.91  5096.7  539.64  5156.9  539.59  5175.5  540.15  5180.6  540.04
  5217.1  541.62  5277.4  542.09  5294.4  542.62  5299.4  542.30  5328.9  542.41
#Mann=4,-1,0
  4713.7    0.05       0  4903.9    0.12       0  5034.5    0.07       0
  5038.5    0.12       0
Bank Sta=5034.5,5038.5
Exp/Cntr=0.3,0.1

Type RM Length L Ch R = 1,3285,176,176,176
BEGIN DESCRIPTION:
Lacy 043 2811
END DESCRIPTION:
XS GIS Cut Line= 3
      2769277.93      6898562.22      2769268.24      6898820.43
      2769288.17      6899170.27
#Sta/Elev= 30
  4748.9  542.16  4837.7  541.22  4857.8  540.59  4877.8  540.29  4897.8  540.77
  4917.8  540.73  4926.4  540.92  4947.8  539.80  4967.8  539.49  4977.8  539.05
  4987.8  537.93  4995.9  537.48  4996.1  536.98  4999.6  536.98  4999.9  537.48
  5005.1  537.82  5027.9  537.48  5078.0  537.80  5098.0  538.54  5118.0  538.54
  5148.1  538.86  5188.2  539.53  5227.4  539.84  5232.4  540.18  5248.2  540.16
  5268.3  540.47  5278.3  540.36  5328.4  540.93  5348.4  541.61  5357.7  541.66
#Mann=4,-1,0
  4748.9    0.05       0  4926.4    0.12       0  4995.9    0.07       0
  4999.9    0.12       0
Bank Sta=4995.9,4999.9
Exp/Cntr=0.3,0.1

Type RM Length L Ch R = 1,3109,146,146,146
BEGIN DESCRIPTION:
Lacy 043 2810
END DESCRIPTION:
XS GIS Cut Line= 3
      2769145.18      6898548.57      2769119.88      6898815.46
      2769122.42      6899156.56
#Sta/Elev= 30
  4733.2  540.80  4798.4  540.18  4846.1  539.25  4876.3  539.21  4882.4  539.41
  4887.4  539.08  4906.4  539.29  4936.5  538.86  4946.6  538.02  4956.6  537.62
  4966.7  537.95  4985.6  537.35  4990.6  537.57  5004.8  537.28  5005.1  536.78
  5008.6  536.78  5008.8  537.28  5056.8  537.59  5066.8  538.85  5086.8  538.32
  5096.8  538.93  5116.8  538.39  5146.8  539.04  5186.8  539.40  5206.8  539.85
  5246.8  539.86  5256.8  540.01  5266.8  540.51  5326.8  541.48  5342.4  542.17
#Mann=4,-1,0
  4733.2    0.05       0  4798.4    0.12       0  5004.8    0.07       0
  5008.8    0.12       0
Bank Sta=5004.8,5008.8
Exp/Cntr=0.3,0.1

Type RM Length L Ch R = 1,2963,40,40,40
BEGIN DESCRIPTION:
Lacy 043 2809
END DESCRIPTION:
XS GIS Cut Line= 3
      2769063.28      6898524.43      2768986.73      6898773.20
      2769069.33      6899124.64
#Sta/Elev= 30
  4739.7  540.75  4783.8  539.94  4820.3  539.00  4847.7  538.72  4853.0  539.24
  4861.7  538.36  4893.1  537.77  4903.5  538.42  4913.1  541.38  4918.3  541.22
  4924.4  537.91  4934.9  537.67  5100.4  537.59  5105.8  538.14  5111.0  537.80
  5121.0  540.97  5131.3  542.36  5141.5  537.49  5151.4  537.22  5151.6  536.72
  5155.1  536.72  5155.4  537.22  5172.4  537.94  5190.6  538.08  5203.2  538.65
  5233.0  538.26  5254.5  538.38  5295.6  539.06  5336.7  540.41  5361.0  540.42
#Mann=4,-1,0
  4739.7    0.05       0  4783.8    0.12       0  5151.4    0.07       0
  5155.4    0.12       0
Bank Sta=5151.4,5155.4
Exp/Cntr=0.3,0.1

Type RM Length L Ch R = 1,2923,54,54,54
BEGIN DESCRIPTION:
Lacy 043 2808
END DESCRIPTION:
XS GIS Cut Line= 4
      2769031.80      6898552.20      2768953.59      6898734.72
      2768950.41      6898863.22      2769041.35      6899084.12
#Sta/Elev= 30
  4752.3  539.99  4763.3  539.89  4831.6  538.53  4848.9  538.79  4884.1  537.52
  4902.3  538.56  4907.7  537.76  4914.2  540.92  4925.1  541.24  4931.3  539.76
  4957.2  540.70  4967.2  539.88  4977.2  540.34  5007.2  538.29  5017.2  539.76
  5053.9  540.21  5058.9  541.34  5075.8  539.20  5079.4  539.20  5081.7  540.66
  5087.8  540.66  5098.6  537.89  5105.6  536.87  5111.0  537.41  5127.6  536.34
  5127.8  535.84  5131.3  535.84  5131.6  536.34  5228.4  537.53  5318.3  539.63
#Mann=4,-1,0
  4752.3    0.05       0  4763.3    0.12       0  5127.6    0.07       0
  5131.6    0.12       0
Bank Sta=5127.6,5131.6
Exp/Cntr=0.3,0.1

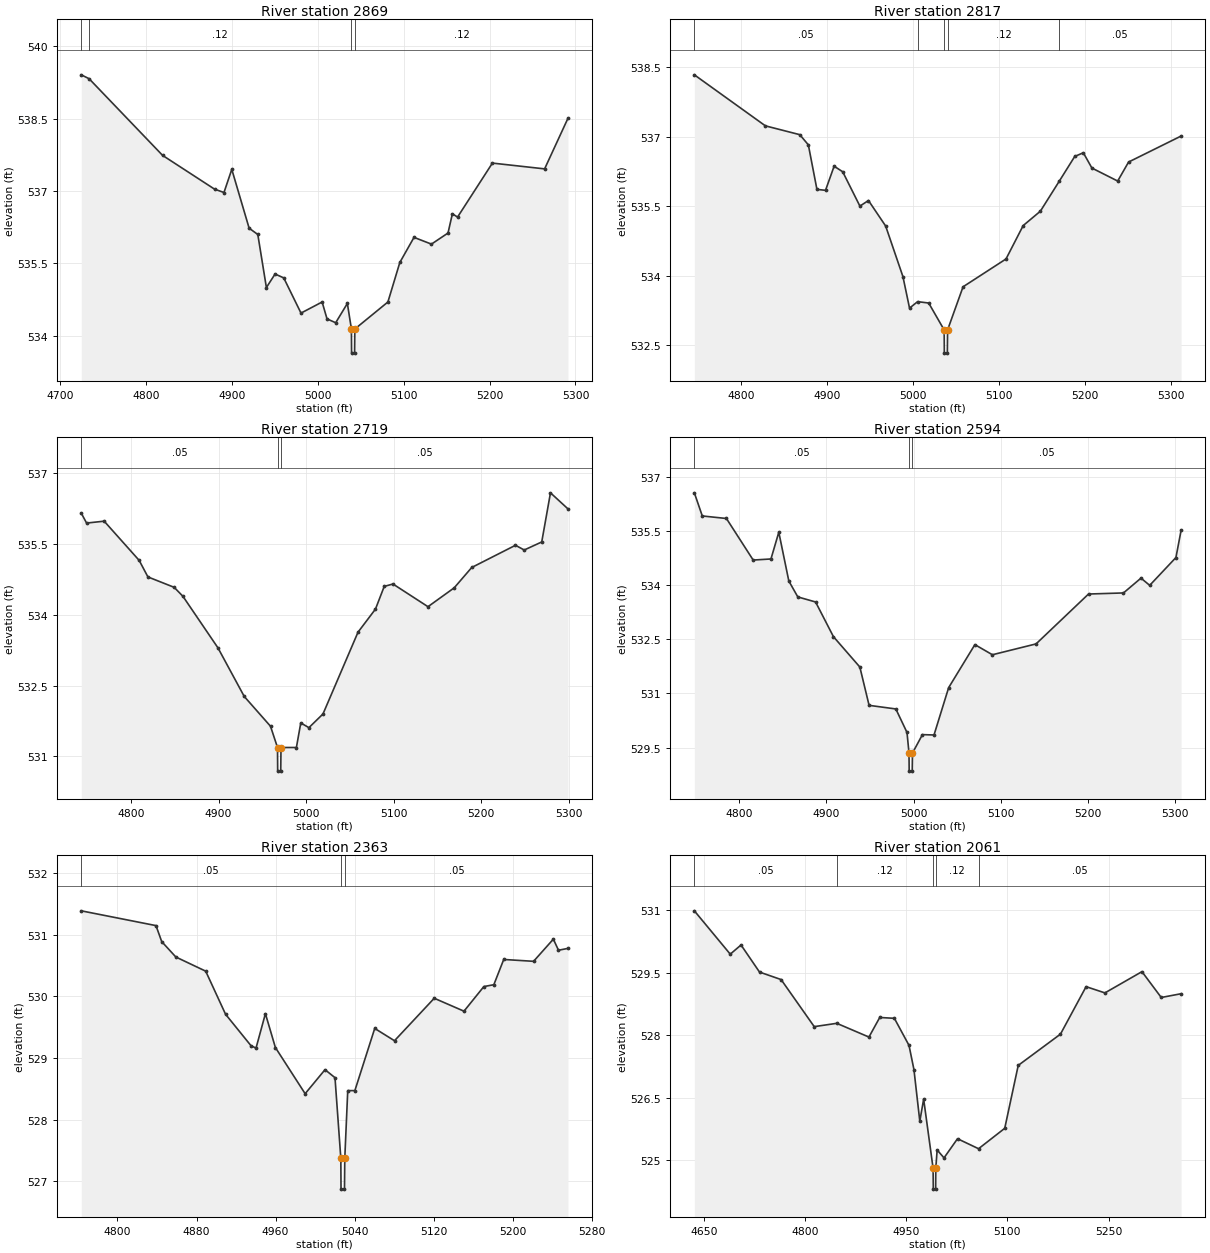
Type RM Length L Ch R = 1,2869,52,52,52
BEGIN DESCRIPTION:
Lacy 043 2807
END DESCRIPTION:
XS GIS Cut Line= 3
      2768940.88      6898537.00      2768906.50      6898815.38
      2768953.06      6899097.87
#Sta/Elev= 30
  4724.5  539.41  4733.6  539.33  4819.2  537.74  4879.7  537.04  4890.7  536.97
  4899.8  537.45  4920.0  536.23  4930.1  536.10  4940.1  535.00  4950.2  535.28
  4960.3  535.20  4980.4  534.47  5005.0  534.70  5010.7  534.35  5020.8  534.27
  5034.4  534.67  5039.1  534.14  5039.3  533.64  5042.8  533.64  5043.1  534.14
  5081.6  534.70  5095.5  535.52  5112.0  536.04  5132.3  535.90  5151.6  536.13
  5156.7  536.53  5162.7  536.46  5203.3  537.58  5264.1  537.46  5291.3  538.51
#Mann=4,-1,0
  4724.5    0.05       0  4733.6    0.12       0  5039.1    0.07       0
  5043.1    0.12       0
Bank Sta=5039.1,5043.1
Exp/Cntr=0.3,0.1

Type RM Length L Ch R = 1,2817,98,98,98
BEGIN DESCRIPTION:
Lacy 043 2806
END DESCRIPTION:
XS GIS Cut Line= 3
      2768857.86      6898558.27      2768854.90      6898811.50
      2768862.55      6899124.76
#Sta/Elev= 30
  4745.6  538.33  4828.3  537.23  4868.3  537.04  4878.3  536.82  4888.3  535.86
  4898.3  535.84  4908.3  536.36  4918.3  536.24  4938.3  535.50  4948.3  535.62
  4968.3  535.07  4988.4  533.98  4996.1  533.30  5005.5  533.44  5018.4  533.41
  5036.4  532.83  5036.6  532.33  5040.1  532.33  5040.4  532.83  5058.4  533.76
  5108.4  534.36  5128.4  535.08  5148.4  535.39  5170.5  536.04  5188.4  536.57
  5198.4  536.65  5208.4  536.32  5238.4  536.04  5251.1  536.45  5312.2  537.01
#Mann=5,-1,0
  4745.6    0.05       0  5005.5    0.12       0  5036.4    0.05       0
  5040.4    0.12       0  5170.5    0.05       0
Bank Sta=5036.4,5040.4
Exp/Cntr=0.3,0.1

Type RM Length L Ch R = 1,2719,125,125,125
BEGIN DESCRIPTION:
Lacy 043 2804
END DESCRIPTION:
XS GIS Cut Line= 3
      2768762.37      6898594.86      2768771.34      6898854.90
      2768771.71      6899151.00
#Sta/Elev= 30
  4743.0  536.15  4749.1  535.94  4769.2  535.98  4809.2  535.15  4819.2  534.80
  4849.2  534.58  4859.2  534.39  4899.2  533.30  4929.3  532.27  4959.3  531.64
  4967.3  531.19  4967.5  530.69  4971.0  530.69  4971.3  531.19  4988.9  531.19
  4993.9  531.71  5003.2  531.61  5019.3  531.90  5059.3  533.63  5079.3  534.12
  5089.3  534.60  5099.3  534.65  5139.3  534.17  5169.3  534.57  5189.3  535.00
  5239.3  535.47  5249.3  535.37  5269.3  535.54  5279.3  536.58  5299.3  536.24
#Mann=3,-1,0
  4743.0    0.05       0  4967.3    0.05       0  4971.3    0.05       0
Bank Sta=4967.3,4971.3
Exp/Cntr=0.3,0.1

Type RM Length L Ch R = 1,2594,231,231,231
BEGIN DESCRIPTION:
Lacy 043 2805
END DESCRIPTION:
XS GIS Cut Line= 3
      2768712.51      6898565.08      2768659.18      6898809.26
      2768683.38      6899116.87
#Sta/Elev= 30
  4748.4  536.55  4757.5  535.91  4785.2  535.84  4815.9  534.69  4836.3  534.72
  4845.3  535.46  4856.8  534.11  4867.1  533.67  4887.5  533.53  4908.0  532.57
  4938.3  531.73  4948.9  530.67  4979.6  530.57  4992.4  529.92  4994.7  529.35
  4994.9  528.85  4998.4  528.85  4998.7  529.35  5010.1  529.86  5023.4  529.85
  5040.2  531.16  5070.3  532.35  5090.4  532.07  5140.5  532.37  5200.7  533.75
  5240.8  533.78  5260.9  534.19  5270.9  533.99  5301.0  534.76  5306.9  535.51
#Mann=3,-1,0
  4748.4    0.05       0  4994.7    0.05       0  4998.7    0.05       0
Bank Sta=4994.7,4998.7
Exp/Cntr=0.3,0.1

Type RM Length L Ch R = 1,2363,302,302,302
BEGIN DESCRIPTION:
Lacy 043 2803
END DESCRIPTION:
XS GIS Cut Line= 3
      2768470.12      6898525.86      2768443.92      6898760.43
      2768420.12      6899015.70
#Sta/Elev= 30
  4763.4  531.39  4839.0  531.15  4844.8  530.89  4859.1  530.64  4889.3  530.41
  4909.4  529.71  4935.1  529.20  4940.2  529.16  4949.7  529.72  4959.8  529.17
  4989.9  528.42  5010.0  528.81  5020.1  528.68  5026.0  527.37  5026.2  526.87
  5029.7  526.87  5030.0  527.37  5033.0  528.47  5040.2  528.47  5060.3  529.48
  5080.3  529.28  5120.5  529.97  5150.6  529.76  5170.7  530.16  5180.8  530.19
  5190.8  530.60  5221.0  530.57  5241.0  530.93  5246.2  530.75  5255.8  530.78
#Mann=3,-1,0
  4763.4    0.05       0  5026.0    0.05       0  5030.0    0.05       0
Bank Sta=5026,5030
Exp/Cntr=0.3,0.1

Type RM Length L Ch R = 1,2061,153,153,153
BEGIN DESCRIPTION:
Lacy 043 2802
END DESCRIPTION:
XS GIS Cut Line= 4
      2768355.40      6898346.80      2768178.91      6898662.87
      2768181.86      6898840.46      2768264.03      6899002.73
#Sta/Elev= 30
  4636.0  530.99  4689.2  529.95  4705.2  530.17  4732.6  529.52  4764.6  529.34
  4813.7  528.21  4847.1  528.29  4894.8  527.96  4910.8  528.43  4932.5  528.41
  4954.2  527.76  4961.5  527.18  4970.2  525.94  4975.9  526.47  4989.9  524.81
  4990.2  524.31  4993.7  524.31  4993.9  524.81  4995.9  525.25  5006.1  525.06
  5026.1  525.52  5057.3  525.28  5096.1  525.77  5116.1  527.28  5178.7  528.03
  5216.7  529.17  5244.6  529.02  5299.5  529.53  5328.1  528.91  5357.5  529.00
#Mann=5,-1,0
  4636.0    0.05       0  4847.1    0.12       0  4989.9    0.07       0
  4993.9    0.12       0  5057.3    0.05       0
Bank Sta=4989.9,4993.9
Exp/Cntr=0.3,0.1

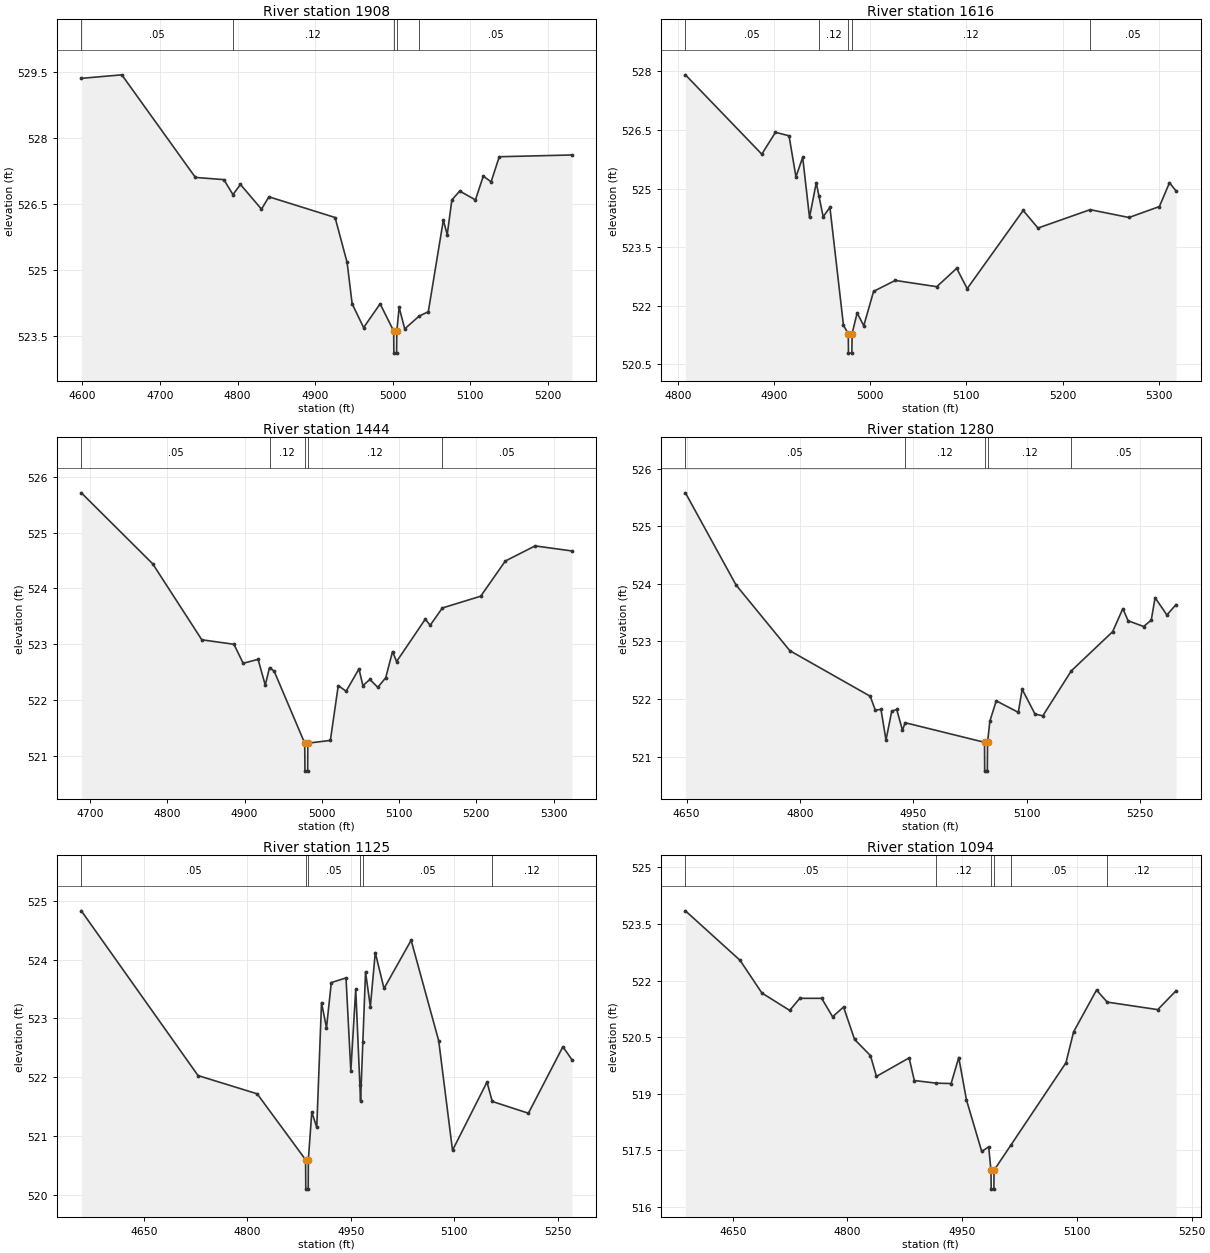
Type RM Length L Ch R = 1,1908,292,292,292
BEGIN DESCRIPTION:
Lacy 043 2801
END DESCRIPTION:
XS GIS Cut Line= 3
      2768258.98      6898342.81      2768050.03      6898685.67
      2768086.55      6898913.85
#Sta/Elev= 30
  4598.6  529.35  4650.8  529.43  4745.7  527.10  4782.4  527.05  4794.1  526.71
  4803.8  526.94  4830.9  526.38  4840.5  526.66  4925.8  526.19  4941.3  525.17
  4947.8  524.23  4962.6  523.69  4983.9  524.23  5001.4  523.61  5001.6  523.11
  5005.1  523.11  5005.4  523.61  5008.4  524.15  5015.6  523.66  5034.1  523.95
  5046.0  524.05  5065.4  526.13  5070.4  525.80  5076.4  526.59  5086.5  526.79
  5106.8  526.59  5116.9  527.13  5127.0  527.00  5137.5  527.57  5231.2  527.61
#Mann=5,-1,0
  4598.6    0.05       0  4794.1    0.12       0  5001.4    0.07       0
  5005.4    0.12       0  5034.1    0.05       0
Bank Sta=5001.4,5005.4
Exp/Cntr=0.3,0.1

Type RM Length L Ch R = 1,1616,172,172,172
BEGIN DESCRIPTION:
Lacy 043 2800
END DESCRIPTION:
XS GIS Cut Line= 3
      2768115.82      6898278.46      2767979.23      6898418.52
      2767881.96      6898717.46
#Sta/Elev= 30
  4807.9  527.91  4887.3  525.88  4901.5  526.44  4915.6  526.35  4922.8  525.30
  4929.8  525.80  4936.9  524.26  4943.9  525.15  4946.6  524.82  4951.1  524.28
  4958.1  524.52  4972.2  521.50  4977.2  521.29  4977.4  520.79  4980.9  520.79
  4981.2  521.29  4986.4  521.82  4993.3  521.49  5003.5  522.37  5026.0  522.65
  5069.2  522.49  5089.9  522.96  5100.8  522.44  5159.0  524.44  5174.4  523.99
  5228.6  524.46  5269.0  524.26  5300.6  524.54  5311.1  525.15  5317.9  524.94
#Mann=5,-1,0
  4807.9    0.05       0  4946.6    0.12       0  4977.2    0.07       0
  4981.2    0.12       0  5228.6    0.05       0
Bank Sta=4977.2,4981.2
Exp/Cntr=0.3,0.1

Type RM Length L Ch R = 1,1444,164,164,164
BEGIN DESCRIPTION:
Lacy 043 2799
END DESCRIPTION:
XS GIS Cut Line= 3
      2767927.40      6898110.96      2767840.36      6898416.24
      2767771.48      6898726.33
#Sta/Elev= 30
  4688.7  525.71  4781.1  524.44  4844.7  523.08  4886.3  523.00  4898.2  522.66
  4917.5  522.73  4926.8  522.27  4932.3  522.58  4938.3  522.52  4977.9  521.23
  4978.2  520.73  4981.7  520.73  4981.9  521.23  5011.1  521.28  5021.3  522.26
  5031.5  522.16  5048.1  522.56  5053.2  522.26  5062.2  522.37  5072.5  522.23
  5082.7  522.40  5091.6  522.87  5096.8  522.69  5134.0  523.45  5140.3  523.34
  5156.1  523.65  5205.7  523.86  5237.6  524.49  5276.1  524.76  5323.8  524.67
#Mann=5,-1,0
  4688.7    0.05       0  4932.3    0.12       0  4977.9    0.07       0
  4981.9    0.12       0  5156.1    0.05       0
Bank Sta=4977.9,4981.9
Exp/Cntr=0.3,0.1

Type RM Length L Ch R = 1,1280,155,155,155
BEGIN DESCRIPTION:
Lacy 043 3493
END DESCRIPTION:
XS GIS Cut Line= 3
      2767913.05      6898113.18      2767666.75      6898394.77
      2767604.70      6898662.77
#Sta/Elev= 30
  4648.4  525.58  4715.4  523.98  4786.6  522.84  4892.9  522.05  4899.6  521.81
  4907.2  521.82  4913.8  521.29  4921.4  521.79  4928.0  521.82  4935.6  521.46
  4939.2  521.59  5044.2  521.25  5044.4  520.75  5047.9  520.75  5048.2  521.25
  5051.3  521.62  5059.7  521.97  5088.9  521.77  5094.0  522.17  5111.0  521.74
  5121.3  521.71  5159.0  522.49  5213.7  523.17  5227.2  523.57  5234.2  523.36
  5254.7  523.26  5264.8  523.37  5269.9  523.76  5285.5  523.46  5297.6  523.64
#Mann=5,-1,0
  4648.4    0.05       0  4939.2    0.12       0  5044.2    0.07       0
  5048.2    0.12       0  5159.0    0.05       0
Bank Sta=5044.2,5048.2
Exp/Cntr=0.3,0.1

Type RM Length L Ch R = 1,1125,31,31,31
BEGIN DESCRIPTION:
Lacy 043 2797
END DESCRIPTION:
XS GIS Cut Line= 4
      2767870.21      6898067.92      2767614.07      6898255.77
      2767530.44      6898337.45      2767525.62      6898614.07
#Sta/Elev= 30
  4559.2  524.83  4728.4  522.03  4814.1  521.72  4884.3  520.60  4884.6  520.10
  4888.1  520.10  4888.3  520.60  4893.3  521.41  4900.5  521.15  4907.4  523.27
  4914.6  522.84  4921.6  523.61  4942.9  523.69  4949.9  522.11  4957.0  523.50
  4963.0  521.87  4964.0  521.60  4967.3  522.60  4971.2  523.79  4978.2  523.20
  4985.3  524.12  4998.0  523.51  5037.3  524.33  5077.3  522.62  5097.3  520.76
  5147.3  521.92  5154.9  521.59  5207.3  521.39  5257.3  522.52  5270.4  522.30
#Mann=6,-1,0
  4559.2    0.05       0  4884.3    0.04       0  4888.3    0.05       0
  4963.0    0.12       0  4967.3    0.05       0  5154.9    0.12       0
Bank Sta=4884.3,4888.3
Exp/Cntr=0.3,0.1

Type RM Length L Ch R = 1,1094,81,81,81
BEGIN DESCRIPTION:
Lacy 043 2796
END DESCRIPTION:
XS GIS Cut Line= 3
      2767760.77      6898044.46      2767503.24      6898258.77
      2767492.77      6898564.85
#Sta/Elev= 30
  4588.2  523.85  4659.5  522.54  4688.2  521.67  4724.5  521.21  4737.7  521.53
  4766.3  521.53  4780.6  521.04  4794.9  521.30  4809.3  520.44  4830.1  520.01
  4837.9  519.46  4880.6  519.95  4887.4  519.35  4916.2  519.28  4935.5  519.27
  4945.5  519.96  4955.5  518.84  4975.5  517.47  4984.6  517.59  4987.6  516.97
  4987.9  516.47  4991.4  516.47  4991.6  516.97  5013.4  517.63  5085.6  519.82
  5095.6  520.64  5125.6  521.75  5139.5  521.43  5205.6  521.23  5229.5  521.73
#Mann=6,-1,0
  4588.2    0.05       0  4916.2    0.12       0  4987.6    0.07       0
  4991.6    0.12       0  5013.4    0.05       0  5139.5    0.12       0
Bank Sta=4987.6,4991.6
Exp/Cntr=0.3,0.1

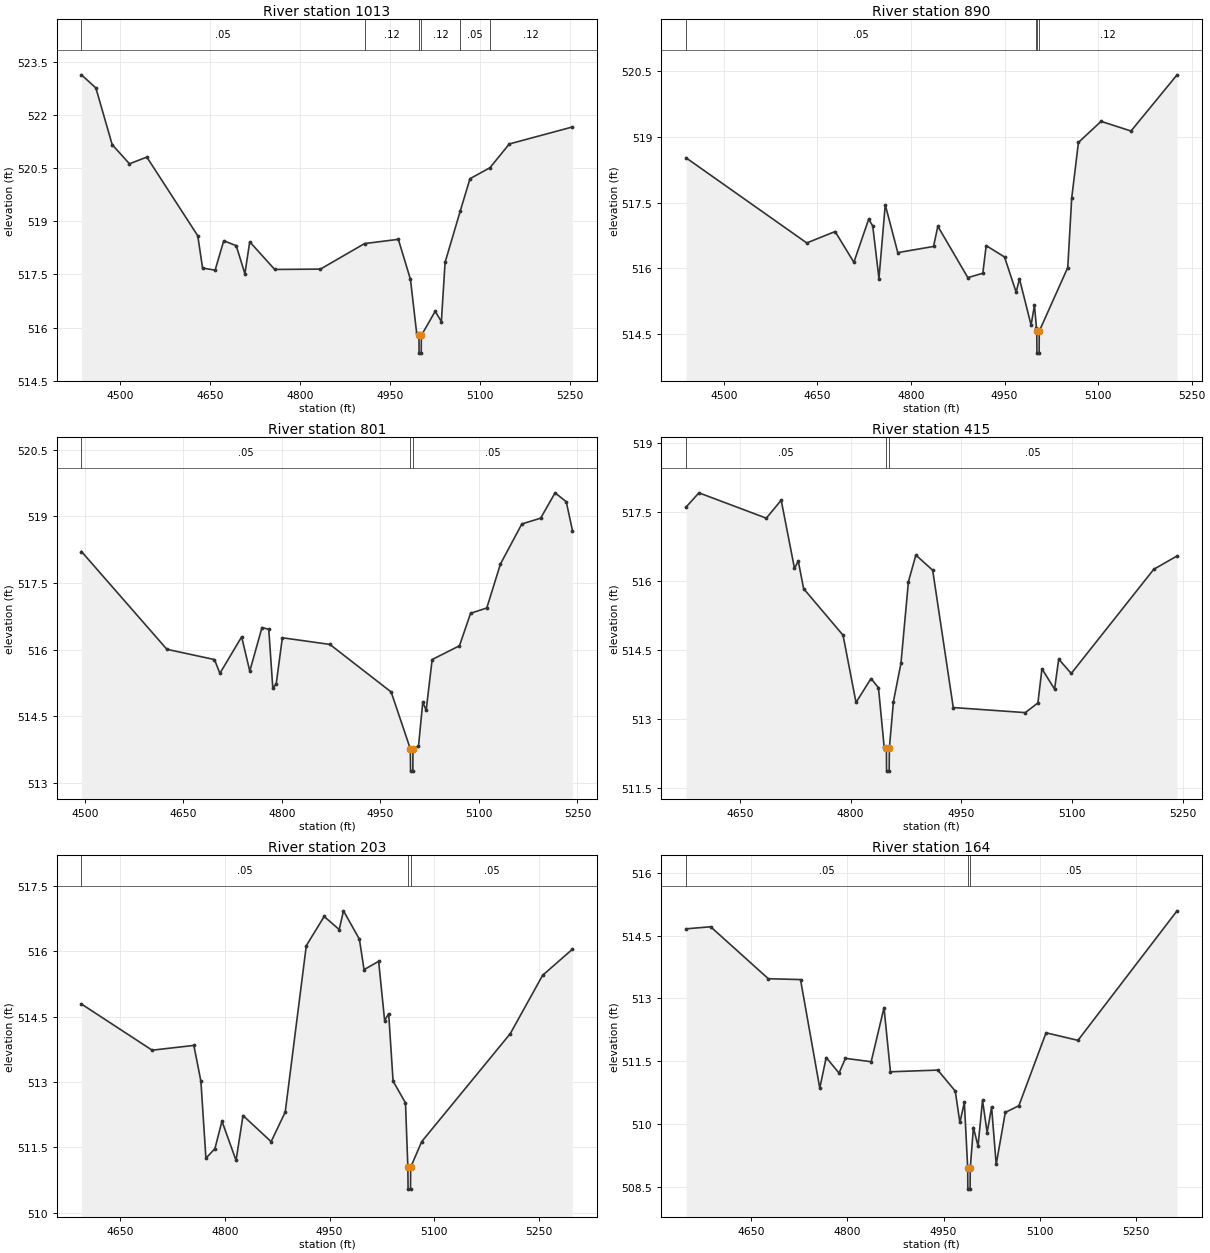
Type RM Length L Ch R = 1,1013,123,123,123
BEGIN DESCRIPTION:
Lacy 043 2795
END DESCRIPTION:
XS GIS Cut Line= 3
      2767619.22      6897851.36      2767378.54      6898154.73
      2767481.42      6898573.22
#Sta/Elev= 30
  4436.1  523.13  4460.1  522.76  4487.3  521.16  4516.1  520.62  4545.0  520.81
  4629.9  518.59  4637.9  517.68  4658.8  517.62  4673.2  518.45  4694.0  518.31
  4708.4  517.52  4716.5  518.42  4758.1  517.64  4834.3  517.65  4907.8  518.37
  4964.1  518.49  4984.3  517.36  4994.6  515.85  4998.5  515.78  4998.7  515.28
  5002.2  515.28  5002.5  515.78  5025.5  516.46  5035.8  516.17  5042.0  517.84
  5067.3  519.29  5083.5  520.20  5116.8  520.51  5149.0  521.18  5254.3  521.66
#Mann=6,-1,0
  4436.1    0.05       0  4907.8    0.12       0  4998.5    0.07       0
  5002.5    0.12       0  5067.3    0.05       0  5116.8    0.12       0
Bank Sta=4998.5,5002.5
Exp/Cntr=0.3,0.1

Type RM Length L Ch R = 1,890,89,89,89
BEGIN DESCRIPTION:
Lacy 043 2793
END DESCRIPTION:
XS GIS Cut Line= 3
      2767191.21      6897793.28      2767228.81      6898159.06
      2767387.75      6898547.28
#Sta/Elev= 30
  4439.3  518.52  4632.9  516.58  4678.3  516.84  4708.4  516.14  4732.1  517.12
  4738.6  516.97  4748.6  515.77  4758.7  517.45  4778.8  516.36  4836.1  516.50
  4843.0  516.96  4891.1  515.79  4915.1  515.89  4920.5  516.52  4949.9  516.26
  4968.5  515.46  4973.9  515.76  4992.5  514.71  4997.9  515.16  5001.1  514.65
  5001.6  514.57  5001.9  514.07  5005.4  514.07  5005.6  514.57  5051.3  516.02
  5057.6  517.60  5068.4  518.87  5104.7  519.35  5152.7  519.13  5226.5  520.41
#Mann=4,-1,0
  4439.3    0.05       0  5001.1    0.12       0  5001.6    0.04       0
  5005.6    0.12       0
Bank Sta=5001.6,5005.6
Exp/Cntr=0.3,0.1

Type RM Length L Ch R = 1,801,386,386,386
BEGIN DESCRIPTION:
Lacy 043 2792
END DESCRIPTION:
XS GIS Cut Line= 3
      2767086.48      6897825.17      2767196.16      6898241.39
      2767283.20      6898546.49
#Sta/Elev= 30
  4494.8  518.21  4624.9  516.01  4697.3  515.78  4705.6  515.47  4738.7  516.29
  4751.1  515.52  4769.7  516.50  4780.0  516.46  4786.2  515.13  4791.4  515.24
  4800.7  516.27  4873.1  516.12  4966.4  515.05  4995.6  513.77  4995.9  513.27
  4999.4  513.27  4999.6  513.77  5008.0  513.83  5014.5  514.82  5019.7  514.64
  5028.8  515.78  5070.4  516.09  5087.3  516.82  5112.0  516.94  5132.8  517.93
  5165.4  518.83  5194.0  518.96  5216.0  519.53  5233.0  519.33  5242.5  518.68
#Mann=3,-1,0
  4494.8    0.05       0  4995.6    0.04       0  4999.6    0.05       0
Bank Sta=4995.6,4999.6
Exp/Cntr=0.3,0.1

Type RM Length L Ch R = 1,415,212,212,212
BEGIN DESCRIPTION:
Lacy 043 2778
END DESCRIPTION:
XS GIS Cut Line= 3
      2766925.68      6897893.73      2766855.96      6898310.95
      2766961.09      6898529.47
#Sta/Elev= 30
  4577.0  517.60  4594.5  517.91  4685.8  517.36  4706.0  517.75  4724.0  516.27
  4729.1  516.43  4736.4  515.83  4789.8  514.82  4807.4  513.36  4827.7  513.88
  4837.8  513.68  4845.5  512.40  4848.6  512.37  4848.8  511.87  4852.3  511.87
  4852.6  512.37  4858.1  513.38  4868.3  514.21  4878.4  515.98  4888.5  516.56
  4911.3  516.23  4939.2  513.25  5036.8  513.14  5053.9  513.35  5059.4  514.09
  5076.5  513.65  5082.1  514.30  5099.1  513.99  5210.9  516.25  5242.5  516.54
#Mann=3,-1,0
  4577.0    0.05       0  4848.6    0.04       0  4852.6    0.05       0
Bank Sta=4848.6,4852.6
Exp/Cntr=0.3,0.1

Type RM Length L Ch R = 1,203,39,39,39
BEGIN DESCRIPTION:
Lacy 043 3492
END DESCRIPTION:
XS GIS Cut Line= 4
      2766692.55      6897981.03      2766648.72      6898345.83
      2766691.25      6898405.33      2766931.70      6898512.71
#Sta/Elev= 30
  4594.3  514.79  4695.6  513.73  4755.4  513.84  4765.5  513.02  4772.7  511.25
  4785.6  511.47  4795.7  512.10  4815.9  511.20  4825.9  512.23  4866.2  511.63
  4886.4  512.31  4916.6  516.13  4942.2  516.80  4963.8  516.50  4969.9  516.93
  4992.7  516.28  4999.4  515.58  5020.3  515.77  5028.9  514.41  5034.7  514.57
  5041.0  513.02  5058.8  512.52  5062.2  511.04  5062.5  510.54  5066.0  510.54
  5066.2  511.04  5082.0  511.63  5209.0  514.11  5255.4  515.45  5298.2  516.05
#Mann=3,-1,0
  4594.3    0.05       0  5062.2    0.05       0  5066.2    0.05       0
Bank Sta=5062.2,5066.2
Exp/Cntr=0.3,0.1

Type RM Length L Ch R = 1,164,97,97,97
BEGIN DESCRIPTION:
Lacy 043 3490
END DESCRIPTION:
XS GIS Cut Line= 4
      2766617.59      6897972.76      2766602.49      6898362.01
      2766774.10      6898539.43      2766897.83      6898574.94
#Sta/Elev= 30
  4548.8  514.66  4587.1  514.71  4677.1  513.47  4727.2  513.45  4757.2  510.86
  4767.2  511.59  4787.2  511.22  4797.2  511.57  4837.3  511.49  4857.3  512.78
  4867.3  511.25  4941.1  511.29  4968.3  510.79  4975.5  510.04  4982.5  510.52
  4987.7  508.95  4987.9  508.45  4991.4  508.45  4991.7  508.95  4996.6  509.92
  5003.8  509.48  5010.8  510.57  5018.0  509.80  5024.9  510.41  5032.1  509.04
  5046.3  510.28  5067.4  510.44  5109.8  512.18  5159.5  512.00  5313.9  515.09
#Mann=3,-1,0
  4548.8    0.05       0  4987.7    0.05       0  4991.7    0.05       0
Bank Sta=4987.7,4991.7
Exp/Cntr=0.3,0.1

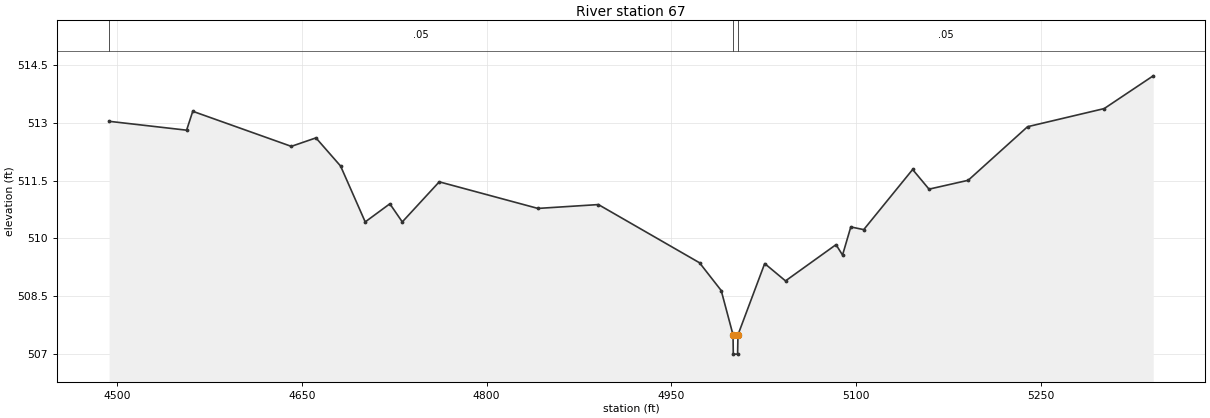
Type RM Length L Ch R = 1,67,0,0,0
BEGIN DESCRIPTION:
Lacy 043 3491
END DESCRIPTION:
XS GIS Cut Line= 4
      2766518.34      6897983.26      2766534.54      6898366.83
      2766593.42      6898506.83      2766887.90      6898609.35
#Sta/Elev= 30
  4493.5  513.04  4556.4  512.81  4561.4  513.30  4641.4  512.39  4661.4  512.61
  4681.4  511.88  4701.4  510.43  4721.4  510.90  4731.5  510.43  4761.5  511.47
  4841.6  510.78  4890.7  510.88  4972.8  509.37  4990.4  508.65  5000.0  507.50
  5000.2  507.00  5003.7  507.00  5004.0  507.50  5025.7  509.35  5042.6  508.90
  5083.6  509.84  5088.9  509.57  5095.6  510.30  5106.1  510.23  5145.8  511.79
  5159.1  511.28  5190.9  511.51  5239.1  512.90  5301.3  513.37  5341.1  514.22
#Mann=3,-1,0
  4493.5    0.05       0  5000.0    0.05       0  5004.0    0.05       0
Bank Sta=5000,5004
Exp/Cntr=0.3,0.1

Chan Stop Cuts=-1