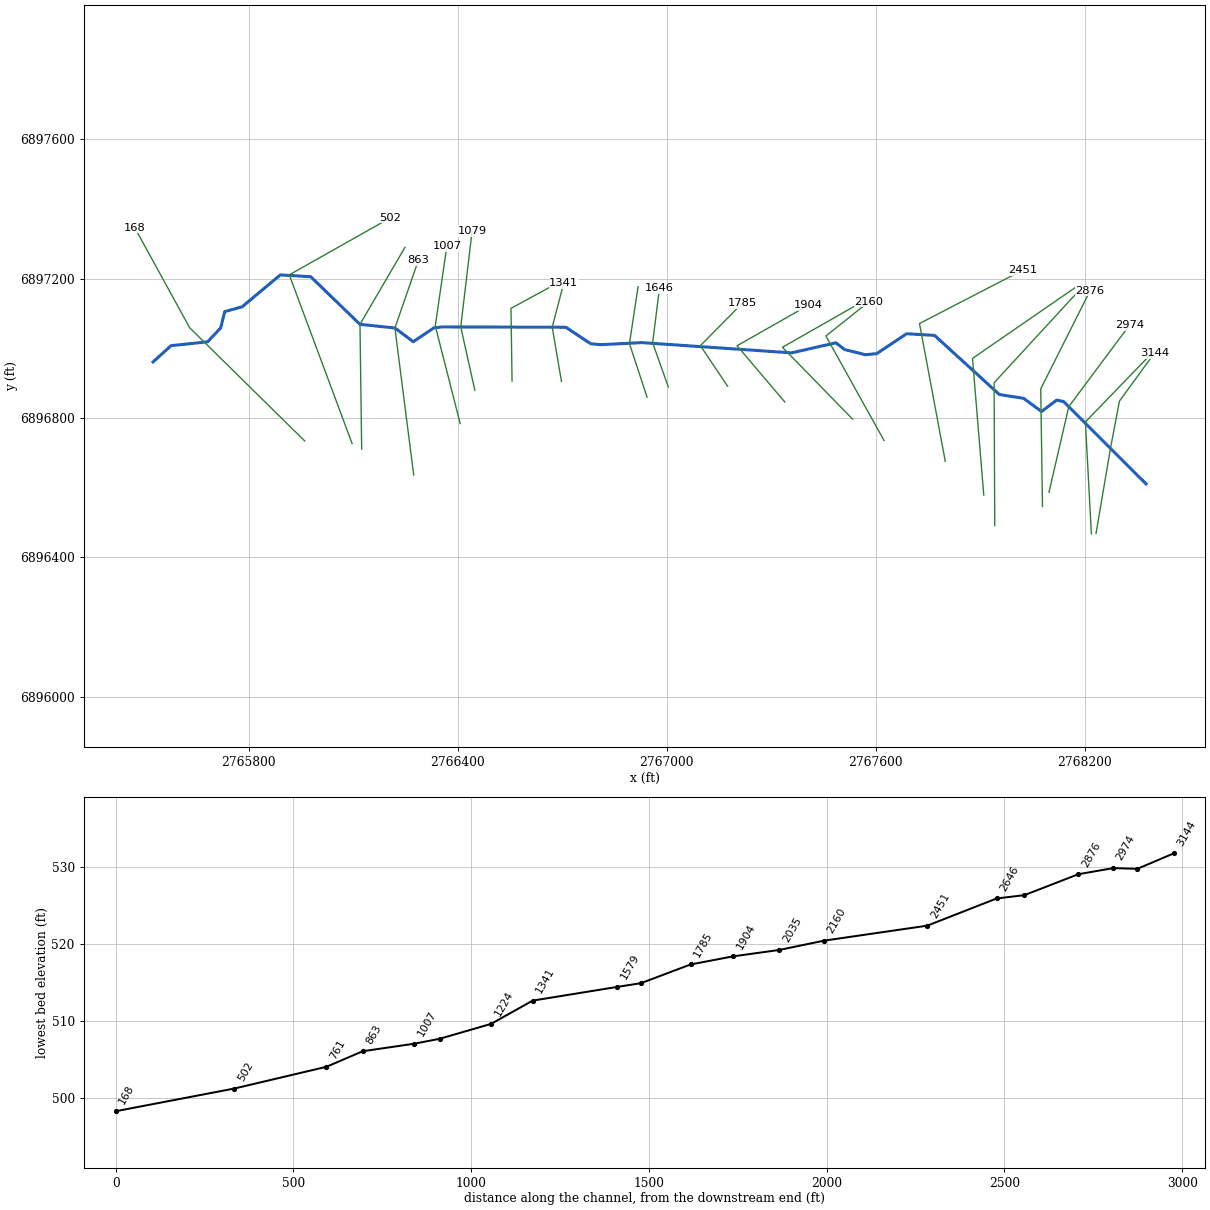
--- Lacy 045.prj (project) ---

Proj Title=Lacy 045 Base Level Engineering
Current Plan=p01
Default Exp/Contr=0.3,0.1
English Units
Geom File=g01
Flow File=f01
Plan File=p01
Y Axis Title=Elevation
X Axis Title(PF)=Main Channel Distance
X Axis Title(XS)=Station
BEGIN DESCRIPTION:
Lacy 045
END DESCRIPTION:
DSS Export Rating Curves= 0
DSS Export Rating Curve Sorted= 0
DSS Export Volume Flow Curves= 0
DXF OffsetX= 0
DXF OffsetY= 0
DXF ScaleX= 1
DXF ScaleY= 10

--- Lacy 045.p01 (plan) ---

Plan Title=Multiple Run
Short Identifier=Multiple
Geom File=g01
Flow File=f01
Subcritical Flow
K Sum by GR= 0
Std Step Tol= 0.01
Critical Tol= 0.01
Num of Std Step Trials= 20
Max Error Tol= 0.3
Flow Tol Ratio= 0.001
Split Flow NTrial= 30
Split Flow Tol= 0.02
Split Flow Ratio= 0.02
Log Output Level= 0
Friction Slope Method= 1
Unsteady Friction Slope Method= 2
Unsteady Bridges Friction Slope Method= 1
Parabolic Critical Depth
Global Vel Dist=  1 , 1 , 1
Global Log Level= 0
CheckData=True
Encroach Param= -1, 0, 0, 0
BEGIN DESCRIPTION:
Multiple Run
END DESCRIPTION:

--- Lacy 045.f01 (steady flow) ---

Flow Title=Multiple
Number of Profiles=7
Profile Names=10-year,25-year,50-year,1pct_min,100-year,1pct_plu,500-year
River Rch & RM= Lacy 045,Reach-1,3144
      69      79      86      47      94     188     112
River Rch & RM= Lacy 045,Reach-1,1079
     158     195     223     127     254     507     329
Boundary for River Rch & Prof#=Lacy 045,Reach-1,1
Up Type=0
Dn Type=3
Dn Slope=0.005
Boundary for River Rch & Prof#=Lacy 045,Reach-1,2
Up Type=0
Dn Type=3
Dn Slope=0.005
Boundary for River Rch & Prof#=Lacy 045,Reach-1,3
Up Type=0
Dn Type=3
Dn Slope=0.005
Boundary for River Rch & Prof#=Lacy 045,Reach-1,4
Up Type=0
Dn Type=3
Dn Slope=0.005
Boundary for River Rch & Prof#=Lacy 045,Reach-1,5
Up Type=0
Dn Type=3
Dn Slope=0.005
Boundary for River Rch & Prof#=Lacy 045,Reach-1,6
Up Type=0
Dn Type=3
Dn Slope=0.005
Boundary for River Rch & Prof#=Lacy 045,Reach-1,7
Up Type=0
Dn Type=3
Dn Slope=0.005

--- Lacy 045.g01 (geometry) ---

Geom Title=Existing Conditions
Program Version=4.10

River Reach=Lacy 045        ,Reach-1
Reach XY= 30
        2768376.        6896611.      2768139.34      6896847.35
      2768119.34       6896851.4      2768076.09      6896818.78
      2768024.35      6896856.56      2767954.91      6896867.54
      2767768.86      6897037.17      2767688.64      6897041.96
      2767602.74      6896984.79      2767571.03      6896981.67
      2767511.14      6896996.27      2767485.57       6897015.9
       2767358.8      6896987.05      2766928.45      6897016.45
      2766810.84      6897010.53      2766781.94      6897013.25
      2766710.78      6897060.48       2766355.7      6897061.53
      2766331.77      6897058.66       2766272.7      6897019.04
       2766220.1      6897058.45      2766119.83      6897068.86
      2765978.43       6897205.6      2765891.22      6897210.76
      2765781.74       6897119.3      2765731.63      6897105.35
      2765720.12      6897058.76      2765682.45      6897018.77
      2765577.41      6897007.61        2765526.        6896961.

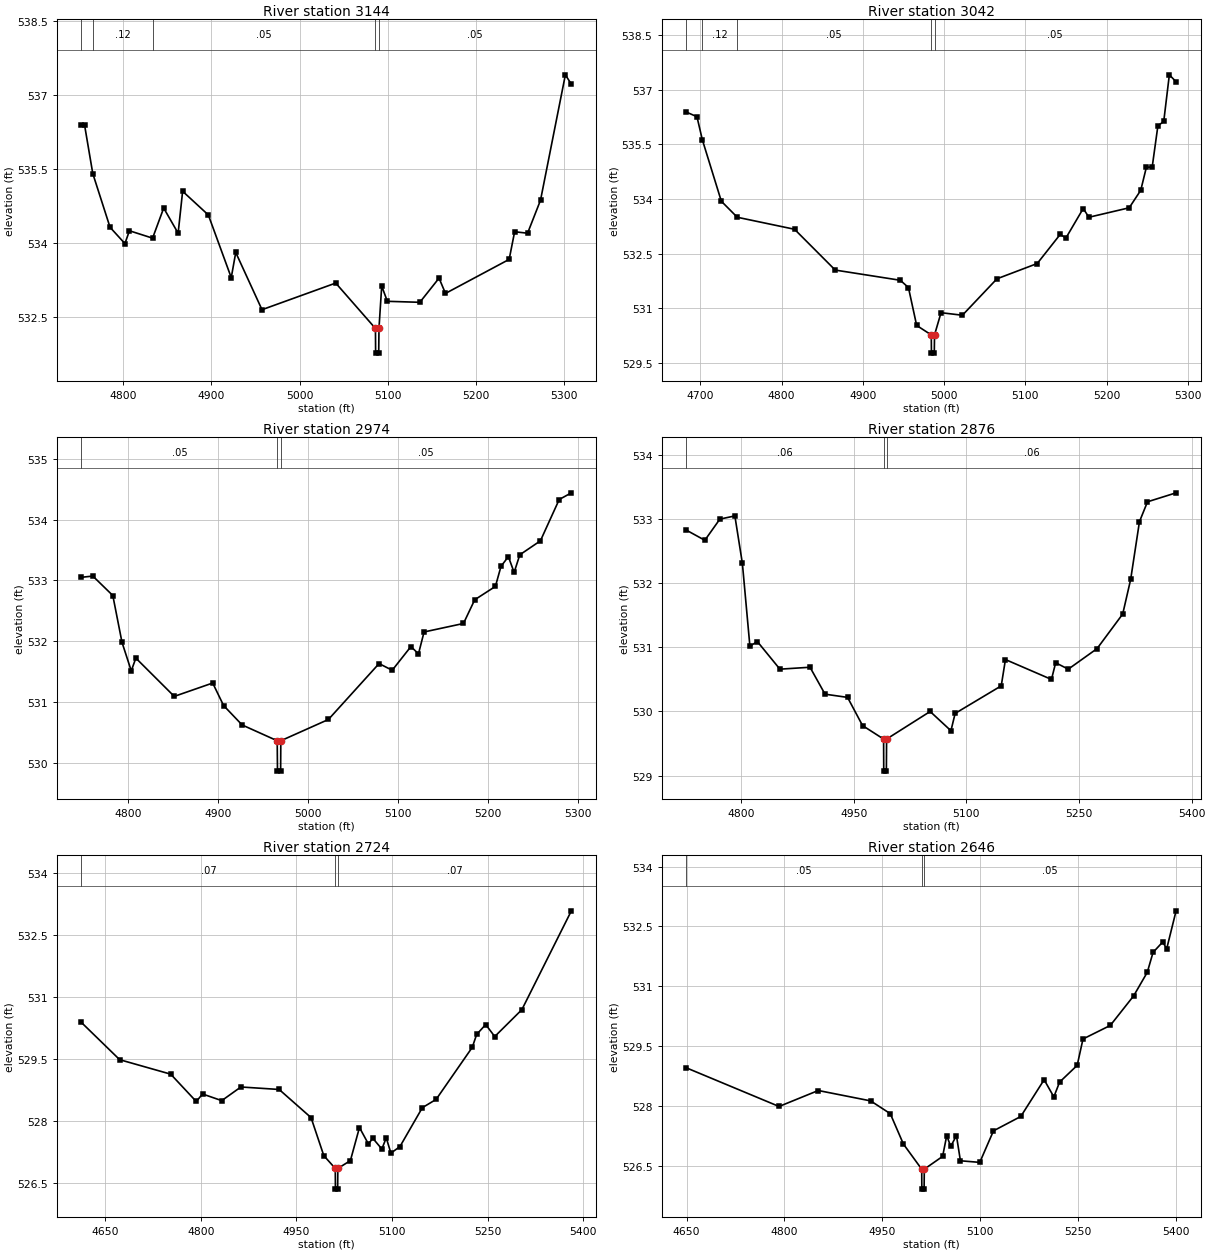
Type RM Length L Ch R = 1 ,3144    ,102,102,102
BEGIN DESCRIPTION:
Lacy 045 2492
END DESCRIPTION:
XS GIS Cut Line= 4
      2768232.46      6896468.92      2768273.91      6896713.55
       2768299.6      6896848.56      2768400.03      6896986.53
#Sta/Elev= 30
  4752.4  536.39    4756  536.39  4765.3  535.41  4784.9  534.32  4801.8  533.99
  4806.9  534.25  4833.2   534.1  4845.8  534.71  4862.2   534.2  4867.3  535.05
  4896.5  534.57  4922.5   533.3  4927.6  533.81  4957.4  532.65  5041.1  533.19
  5086.2  532.27  5086.4  531.77  5089.9  531.77  5090.2  532.27  5093.3  533.13
  5099.7  532.82  5136.6   532.8  5158.4  533.29  5165.7  532.98    5238  533.67
  5244.2  534.23  5258.9   534.2  5273.6  534.87  5301.8  537.41  5308.6  537.22
#Mann= 5 ,-1 , 0
  4752.4     .05       0  4765.3     .12       0  4833.2     .05       0
  5086.2     .04       0  5090.2     .05       0
Bank Sta=5086.2,5090.2
XS Rating Curve= 0 ,0
Exp/Cntr=0.3,0.1

Type RM Length L Ch R = 1 ,3042    ,68,68,68
BEGIN DESCRIPTION:
Lacy 045 2491
END DESCRIPTION:
XS GIS Cut Line= 3
      2768219.02      6896467.74      2768201.86      6896788.79
      2768397.49      6896991.19
#Sta/Elev= 30
  4682.6  536.39  4695.9  536.26  4702.5  535.63  4725.9  533.94  4745.5   533.5
    4816  533.17  4866.1  532.05  4946.2  531.77  4956.2  531.57  4966.3  530.53
  4984.3  530.27  4984.5  529.77    4988  529.77  4988.3  530.27  4996.3  530.88
  5022.6  530.81  5065.1  531.81  5114.7  532.23    5143  533.03    5150  532.93
  5171.3  533.74  5178.3   533.5  5227.9  533.76  5242.1  534.24    5249  534.87
  5256.2  534.88  5263.2  536.01  5270.4  536.13  5277.3  537.41  5285.6  537.22
#Mann= 5 ,-1 , 0
  4682.6     .05       0  4702.5     .12       0  4745.5     .05       0
  4984.3     .04       0  4988.3     .05       0
Bank Sta=4984.3,4988.3
XS Rating Curve= 0 ,0
Exp/Cntr=0.3,0.1

Type RM Length L Ch R = 1 ,2974    ,98,98,98
BEGIN DESCRIPTION:
Lacy 045 2490
END DESCRIPTION:
XS GIS Cut Line= 3
      2768097.37      6896587.03       2768154.2      6896832.72
      2768328.88      6897067.11
#Sta/Elev= 30
    4748  533.05  4760.7  533.07  4782.9  532.75  4793.1  531.98  4803.4  531.51
  4808.5  531.72  4851.2  531.09  4893.9  531.31    4906  530.94  4926.6  530.62
  4965.6  530.36  4965.9  529.86  4969.4  529.86  4969.6  530.36  5022.5  530.71
  5078.8  531.63  5093.4  531.52  5114.2  531.91  5122.6  531.79  5128.8  532.15
  5172.6  532.29  5185.1  532.68  5208.1   532.9  5214.3  533.23  5222.5  533.39
  5228.9  533.13  5235.2  533.42  5258.1  533.65    5279  534.33  5292.5  534.44
#Mann= 3 ,-1 , 0
    4748     .05       0  4965.6     .04       0  4969.6     .05       0
Bank Sta=4965.6,4969.6
XS Rating Curve= 0 ,0
Exp/Cntr=0.3,0.1

Type RM Length L Ch R = 1 ,2876    ,152,152,152
BEGIN DESCRIPTION:
Lacy 045 3217
END DESCRIPTION:
XS GIS Cut Line= 3
      2768078.69      6896546.07      2768073.65      6896883.62
      2768215.18      6897165.05
#Sta/Elev= 30
  4726.7  532.83  4751.6  532.67  4771.6     533  4791.6  533.05  4801.6  532.31
  4811.6  531.02  4821.6  531.09  4851.6  530.66  4891.7  530.69  4911.7  530.27
  4941.7  530.22  4961.7  529.78  4989.7  529.57  4989.9  529.07  4993.4  529.07
  4993.7  529.57  5051.7     530  5079.4   529.7    5085  529.97  5146.4   530.4
    5152  530.81  5213.3   530.5  5218.9  530.76  5235.7  530.66    5274  530.98
  5308.2  531.52  5318.8  532.06  5330.5  532.96  5341.2  533.27  5379.3  533.41
#Mann= 3 ,-1 , 0
  4726.7     .06       0  4989.7     .03       0  4993.7     .06       0
Bank Sta=4989.7,4993.7
XS Rating Curve= 0 ,0
Exp/Cntr=0.3,0.1

Type RM Length L Ch R = 1 ,2724    ,78,78,78
BEGIN DESCRIPTION:
Lacy 045 3449
END DESCRIPTION:
XS GIS Cut Line= 3
      2767941.72      6896491.01      2767939.84      6896901.17
      2768182.27       6897164.5
#Sta/Elev= 30
    4613  530.38    4673  529.48    4753  529.13    4793  528.47    4803  528.65
    4833  528.49    4863  528.82    4923  528.76    4973  528.08    4993  527.16
    5011  526.85  5011.2  526.35  5014.7  526.35    5015  526.85  5034.7  527.04
  5048.9  527.84    5063  527.44  5069.8  527.58    5084  527.32  5090.9  527.59
  5098.2  527.22  5112.4  527.38  5147.5  528.32  5169.1  528.52  5225.8  529.78
  5232.6  530.09  5246.8  530.33    5261  530.04  5303.5  530.69  5381.1  533.08
#Mann= 3 ,-1 , 0
    4613     .07       0    5011     .03       0    5015     .07       0
Bank Sta=5011,5015
XS Rating Curve= 0 ,0
Exp/Cntr=0.3,0.1

Type RM Length L Ch R = 1 ,2646    ,195,195,195
BEGIN DESCRIPTION:
Lacy 045 2489
END DESCRIPTION:
XS GIS Cut Line= 3
      2767910.22      6896578.97       2767877.8      6896971.02
       2768172.6      6897174.34
#Sta/Elev= 30
  4649.4  528.96  4791.9  527.99  4852.1  528.39  4932.4  528.13  4962.5  527.81
  4982.6  527.05  5010.7  526.42  5010.9  525.92  5014.4  525.92  5014.7  526.42
  5042.8  526.74  5049.1  527.26  5055.2  526.99    5064  527.26  5070.1  526.63
  5099.8  526.59  5120.8  527.38  5162.7  527.74  5198.5  528.66  5213.4  528.23
  5222.2   528.6  5249.2  529.02  5258.1  529.68    5300  530.02  5335.8  530.76
  5356.7  531.35  5365.6  531.85  5380.4  532.11  5386.5  531.94  5400.9  532.89
#Mann= 3 ,-1 , 0
  4649.4     .05       0  5010.7     .04       0  5014.7     .05       0
Bank Sta=5010.7,5014.7
XS Rating Curve= 0 ,0
Exp/Cntr=0.3,0.1

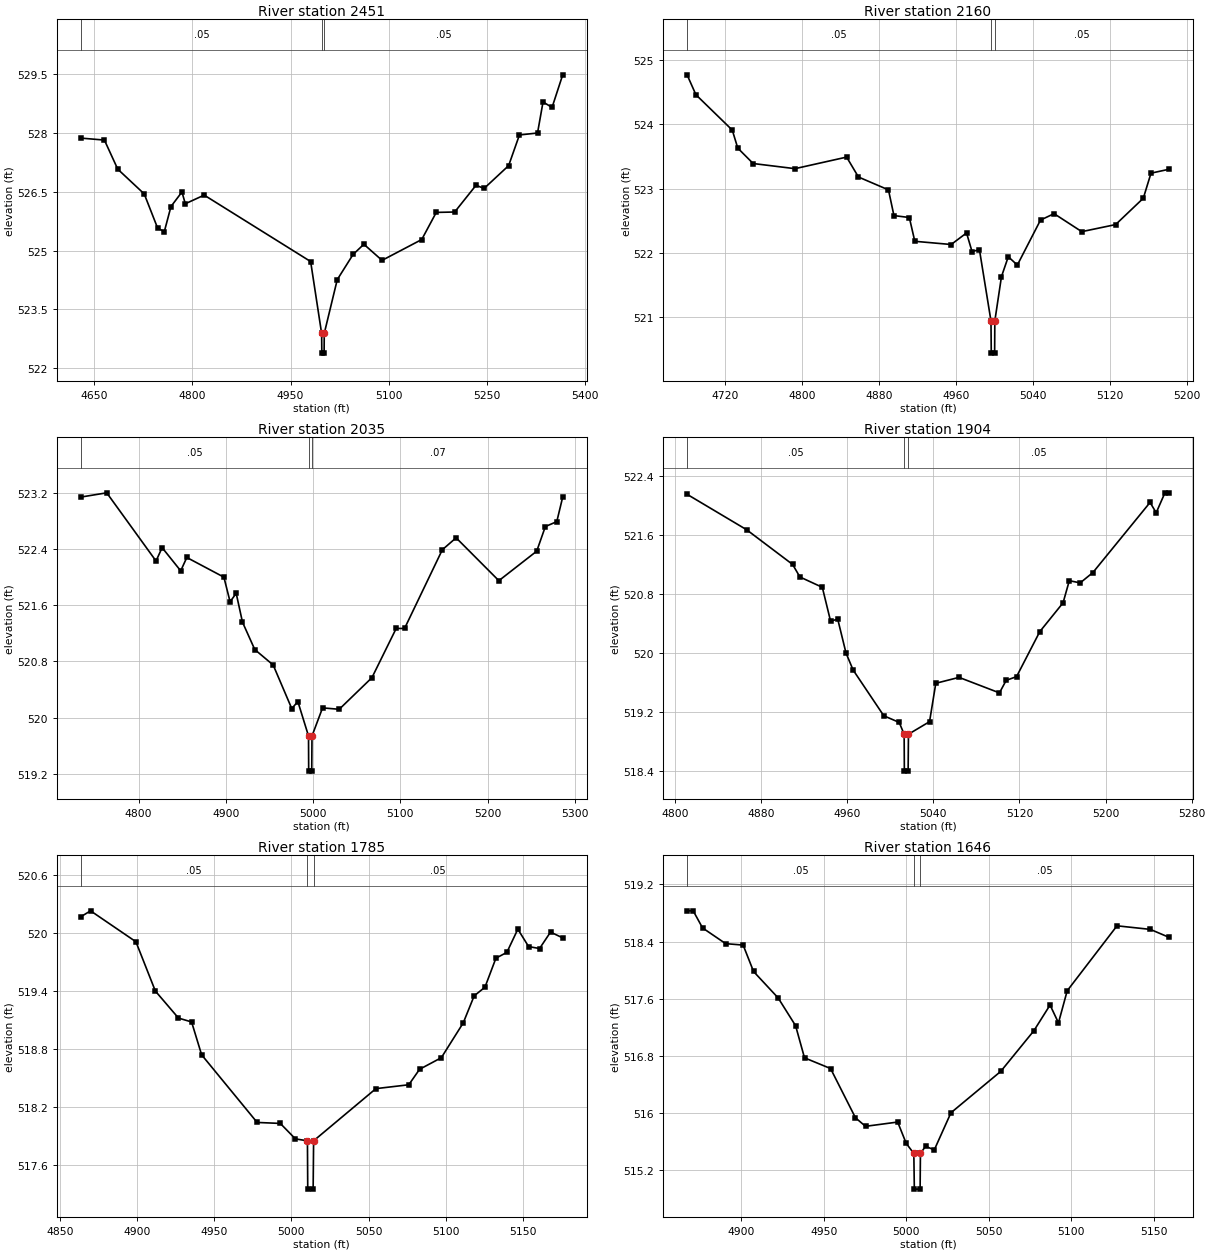
Type RM Length L Ch R = 1 ,2451    ,291,291,291
BEGIN DESCRIPTION:
Lacy 045 2488
END DESCRIPTION:
XS GIS Cut Line= 3
      2767799.67      6896675.79      2767725.73      6897071.23
      2768022.72      6897224.94
#Sta/Elev= 30
  4629.5  527.86  4665.3  527.81  4685.7  527.07  4726.2  526.44  4746.7  525.57
  4756.9  525.48  4767.1  526.12  4783.9  526.49    4789  526.19  4817.9  526.41
  4980.7  524.72  4997.5  522.89  4997.8  522.39  5001.3  522.39  5001.5  522.89
  5021.4  524.26  5045.6   524.9  5062.1  525.16  5089.9  524.75  5150.6  525.28
  5172.8  525.97    5201  525.98  5233.6  526.66    5246  526.58  5283.5  527.16
    5300  527.94  5327.7  527.99  5336.1  528.78  5349.9  528.64  5366.2  529.47
#Mann= 3 ,-1 , 0
  4629.5     .05       0  4997.5     .04       0  5001.5     .05       0
Bank Sta=4997.5,5001.5
XS Rating Curve= 0 ,0
Exp/Cntr=0.3,0.1

Type RM Length L Ch R = 1 ,2160    ,125,125,125
BEGIN DESCRIPTION:
Lacy 045 3452
END DESCRIPTION:
XS GIS Cut Line= 3
      2767624.04      6896735.32      2767457.13      6897035.37
      2767580.26      6897133.65
#Sta/Elev= 30
  4680.6  524.77  4689.8  524.46  4727.6  523.91  4733.3  523.63  4749.3  523.39
  4792.8  523.31  4846.5  523.49  4858.8  523.18    4890  522.98  4895.7  522.58
  4911.7  522.55  4917.4  522.18  4955.2  522.13  4971.2  522.31  4976.9  522.02
  4984.6  522.05  4996.6  520.94  4996.9  520.44  5000.4  520.44  5000.6  520.94
  5007.5  521.63  5014.6  521.94    5024  521.81  5048.1  522.51  5062.2  522.61
    5091  522.33  5126.2  522.44    5155  522.85    5163  523.24  5181.5   523.3
#Mann= 3 ,-1 , 0
  4680.6     .05       0  4996.6     .03       0  5000.6     .05       0
Bank Sta=4996.6,5000.6
XS Rating Curve= 0 ,0
Exp/Cntr=0.3,0.1

Type RM Length L Ch R = 1 ,2035    ,131,131,131
BEGIN DESCRIPTION:
Lacy 045 3451
END DESCRIPTION:
XS GIS Cut Line= 3
      2767533.59      6896796.98      2767332.35      6897003.06
       2767561.9      6897133.77
#Sta/Elev= 30
    4734  523.14  4763.5   523.2    4820  522.23    4827  522.42  4848.3  522.09
  4855.3  522.28  4897.8     522  4904.9  521.65  4911.9  521.77  4919.1  521.36
  4933.2  520.97  4954.3  520.75  4975.6  520.13  4982.6  520.23  4994.8  519.74
    4995  519.24  4998.5  519.24  4998.8  519.74  5010.9  520.14    5030  520.12
  5067.5  520.57  5095.3  521.27  5104.9  521.27  5148.2  522.39    5164  522.56
    5213  521.95  5256.4  522.37  5266.3  522.72  5279.4  522.79  5286.2  523.14
#Mann= 3 ,-1 , 0
    4734     .05       0  4994.8     .03       0  4998.8     .07       0
Bank Sta=4994.8,4998.8
XS Rating Curve= 0 ,0
Exp/Cntr=0.3,0.1

Type RM Length L Ch R = 1 ,1904    ,119,119,119
BEGIN DESCRIPTION:
Lacy 045 3450
END DESCRIPTION:
XS GIS Cut Line= 3
      2767338.95      6896846.31      2767202.08      6897007.42
      2767407.29      6897123.98
#Sta/Elev= 30
  4811.3  522.15  4866.6  521.67  4909.3   521.2  4916.1  521.03  4936.9  520.89
  4944.6  520.43  4951.2  520.46  4958.9     520  4965.5  519.77    4994  519.15
  5008.3  519.06  5012.9   518.9  5013.1   518.4  5016.6   518.4  5016.9   518.9
  5036.5  519.07  5042.3  519.59  5063.9  519.67  5101.4  519.46  5107.7  519.63
  5117.3  519.68  5138.9  520.29  5160.5  520.68  5166.3  520.98  5176.4  520.95
  5188.2  521.09  5241.3  522.04    5247   521.9  5255.1  522.17  5258.7  522.17
#Mann= 3 ,-1 , 0
  4811.3     .05       0  5012.9     .04       0  5016.9     .05       0
Bank Sta=5012.9,5016.9
XS Rating Curve= 0 ,0
Exp/Cntr=0.3,0.1

Type RM Length L Ch R = 1 ,1785    ,139,139,139
BEGIN DESCRIPTION:
Lacy 045 3448
END DESCRIPTION:
XS GIS Cut Line= 3
      2767174.89      6896891.47      2767096.85      6897007.63
      2767217.89      6897130.33
#Sta/Elev= 28
  4863.6  520.17  4869.8  520.23  4899.2  519.91  4911.8   519.4  4926.8  519.12
  4935.3  519.08  4941.8  518.74  4977.8  518.04  4992.8  518.03  5002.6  517.87
  5010.4  517.85  5010.6  517.35  5014.1  517.35  5014.4  517.85  5054.8  518.39
  5076.1  518.43  5083.1  518.59  5097.2  518.71  5111.4  519.07  5118.5  519.35
  5125.5  519.44  5132.6  519.74  5139.7   519.8  5146.8  520.04  5153.8  519.86
  5160.9  519.84    5168  520.01  5175.9  519.95
#Mann= 3 ,-1 , 0
  4863.6     .05       0  5010.4     .04       0  5014.4     .05       0
Bank Sta=5010.4,5014.4
XS Rating Curve= 0 ,0
Exp/Cntr=0.3,0.1

Type RM Length L Ch R = 1 ,1646    ,67,67,67
BEGIN DESCRIPTION:
Lacy 045 3447
END DESCRIPTION:
XS GIS Cut Line= 3
      2767004.78      6896888.97      2766959.81      6897015.97
      2766979.35      6897172.12
#Sta/Elev= 29
  4867.1  518.83  4870.8  518.83  4876.5  518.59  4890.5  518.37  4901.1  518.35
  4907.4  517.98  4922.3  517.61  4932.9  517.22  4938.3  516.77  4954.1  516.62
  4969.2  515.93  4975.3  515.81  4994.8  515.87    5000  515.57  5004.6  515.43
  5004.9  514.93  5008.4  514.93  5008.6  515.43  5011.7  515.53    5017  515.48
  5027.1     516  5057.3  516.58  5077.4  517.15  5087.2  517.51  5092.3  517.26
  5097.6  517.71  5127.8  518.62    5148  518.57  5159.2  518.46
#Mann= 3 ,-1 , 0
  4867.1     .05       0  5004.6     .04       0  5008.6     .05       0
Bank Sta=5004.6,5008.6
XS Rating Curve= 0 ,0
Exp/Cntr=0.3,0.1

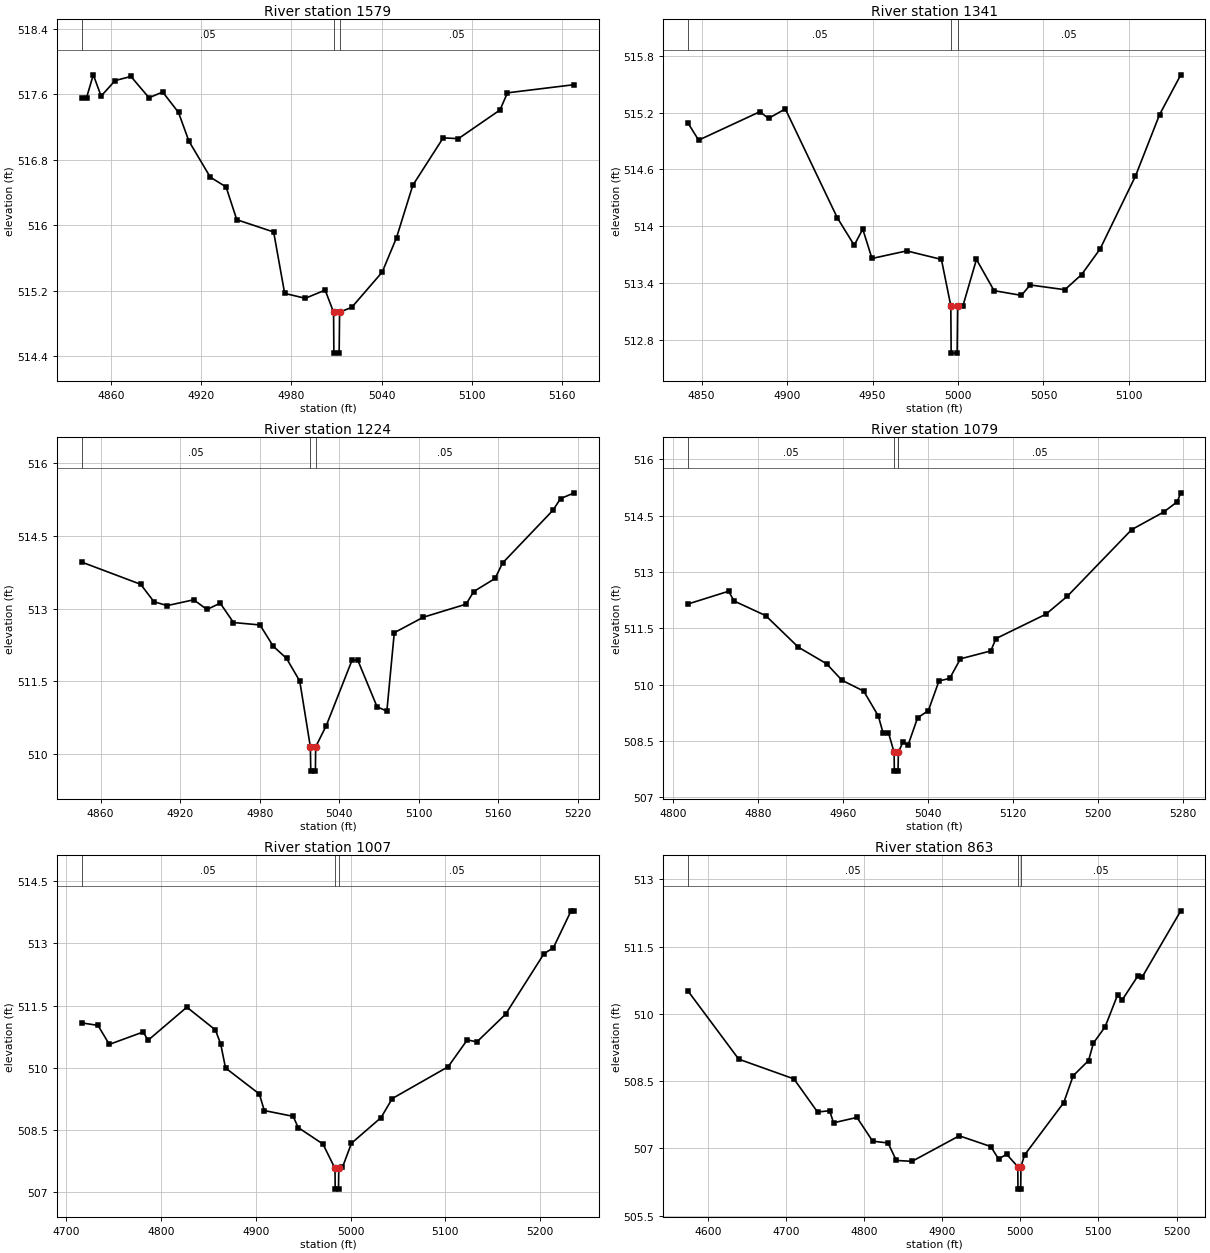
Type RM Length L Ch R = 1 ,1579    ,238,238,238
BEGIN DESCRIPTION:
Lacy 045 3446
END DESCRIPTION:
XS GIS Cut Line= 3
      2766943.82      6896859.82      2766893.23      6897013.49
      2766918.07      6897177.13
#Sta/Elev= 30
  4840.6  517.56  4843.9  517.56  4848.4  517.84  4853.6  517.58  4862.9  517.77
  4873.4  517.82  4885.4  517.56  4894.5  517.63    4905  517.38  4911.9  517.03
  4926.1  516.59  4936.6  516.47  4943.7  516.07  4968.2  515.92  4975.5  515.17
  4989.2  515.11  5002.4  515.21    5008  514.94  5008.2  514.44  5011.7  514.44
    5012  514.94  5020.1     515  5040.3  515.43  5049.8  515.85  5060.6  516.49
  5080.8  517.07  5090.9  517.06  5118.5  517.41  5123.5  517.62  5167.9  517.72
#Mann= 3 ,-1 , 0
  4840.6     .05       0    5008     .04       0    5012     .05       0
Bank Sta=5008,5012
XS Rating Curve= 0 ,0
Exp/Cntr=0.3,0.1

Type RM Length L Ch R = 1 ,1341    ,117,117,117
BEGIN DESCRIPTION:
Lacy 045 3444
END DESCRIPTION:
XS GIS Cut Line= 3
       2766698.1      6896904.89      2766671.57      6897060.76
      2766704.47      6897186.62
#Sta/Elev= 26
  4842.1  515.09  4848.3  514.91  4884.1  515.21  4889.2  515.14    4899  515.24
  4929.4  514.09  4939.3   513.8  4944.3  513.97  4949.7  513.66    4970  513.74
  4990.3  513.65  4995.8  513.16    4996  512.66  4999.5  512.66  4999.8  513.16
  5002.9  513.16  5010.8  513.65  5021.1  513.32  5037.1  513.27  5042.2  513.38
  5062.5  513.33  5072.3  513.49  5083.1  513.76  5103.8  514.53  5117.9  515.18
  5130.3   515.6
#Mann= 3 ,-1 , 0
  4842.1     .05       0  4995.8     .04       0  4999.8     .05       0
Bank Sta=4995.8,4999.8
XS Rating Curve= 0 ,0
Exp/Cntr=0.3,0.1

Type RM Length L Ch R = 1 ,1224    ,145,145,145
BEGIN DESCRIPTION:
Lacy 045 2483
END DESCRIPTION:
XS GIS Cut Line= 3
      2766556.27      6896906.38      2766553.26      6897114.77
      2766696.69      6897192.82
#Sta/Elev= 30
  4845.6  513.96  4890.2   513.5  4900.2  513.14  4910.2  513.06  4930.2  513.18
  4940.2  512.98  4950.2  513.11  4960.2  512.71  4980.2  512.66  4990.2  512.22
  5000.2  511.97  5010.2   511.5  5018.2  510.14  5018.5  509.64    5022  509.64
  5022.2  510.14  5030.2  510.58  5049.6  511.93    5054  511.93  5068.5  510.97
  5075.9  510.88  5081.5   512.5  5103.4  512.82  5135.7  513.09  5141.4  513.35
  5157.5  513.62  5163.2  513.94  5201.2  515.03  5206.9  515.27  5217.3  515.39
#Mann= 3 ,-1 , 0
  4845.6     .05       0  5018.2     .05       0  5022.2     .05       0
Bank Sta=5018.2,5022.2
XS Rating Curve= 0 ,0
Exp/Cntr=0.3,0.1

Type RM Length L Ch R = 1 ,1079    ,72,72,72
BEGIN DESCRIPTION:
Lacy 045 2482
END DESCRIPTION:
XS GIS Cut Line= 3
      2766449.49      6896879.66      2766409.01      6897061.63
      2766441.69      6897336.88
#Sta/Elev= 30
  4814.1  512.15  4852.3  512.49  4857.4  512.23  4887.2  511.84  4917.9     511
  4944.4  510.56  4958.9  510.12  4979.4  509.83  4993.1  509.17  4997.6  508.72
  5002.7  508.72    5008   508.2  5008.2   507.7  5011.7   507.7    5012   508.2
  5016.2  508.47  5021.2   508.4  5030.1  509.12  5040.2  509.31  5050.2   510.1
  5060.3  510.17  5070.4  510.69  5098.9   510.9  5103.9  511.23  5150.9  511.88
  5171.1  512.36  5231.5  514.13  5261.7   514.6  5274.3  514.87  5277.7  515.11
#Mann= 3 ,-1 , 0
  4814.1     .05       0    5008     .04       0    5012     .05       0
Bank Sta=5008,5012
XS Rating Curve= 0 ,0
Exp/Cntr=0.3,0.1

Type RM Length L Ch R = 1 ,1007    ,144,144,144
BEGIN DESCRIPTION:
Lacy 045 2481
END DESCRIPTION:
XS GIS Cut Line= 3
       2766407.4      6896784.23      2766335.92      6897064.35
       2766369.1      6897292.76
#Sta/Elev= 30
  4716.1  511.08  4733.4  511.02  4745.4  510.56  4781.1  510.86  4786.3  510.66
  4827.2  511.46  4857.3  510.91  4862.9  510.57    4868  509.99  4903.7  509.36
  4908.9  508.96  4939.4  508.82  4944.6  508.55  4970.8  508.15  4983.5  507.56
  4983.7  507.06  4987.2  507.06  4987.5  507.56  4991.4  507.59  5000.9  508.17
  5032.1  508.79  5043.9  509.25  5102.9  510.02  5123.1  510.67  5133.2  510.62
  5163.5  511.29  5203.9  512.75    5214   512.9  5232.6  513.79    5236  513.79
#Mann= 3 ,-1 , 0
  4716.1     .05       0  4983.5     .04       0  4987.5     .05       0
Bank Sta=4983.5,4987.5
XS Rating Curve= 0 ,0
Exp/Cntr=0.3,0.1

Type RM Length L Ch R = 1 ,863     ,102,102,102
BEGIN DESCRIPTION:
Lacy 045 2480
END DESCRIPTION:
XS GIS Cut Line= 3
      2766274.02      6896636.58       2766220.1      6897058.45
      2766287.28      6897252.55
#Sta/Elev= 30
  4574.7  510.51  4639.6  508.99  4710.2  508.55  4740.5  507.81  4755.9  507.84
    4761  507.57  4790.9  507.69    4811  507.16  4830.7  507.12  4841.3  506.73
  4861.4  506.71  4921.9  507.28  4962.2  507.04  4972.3  506.76  4982.4  506.87
  4996.8  506.59    4997  506.09  5000.5  506.09  5000.8  506.59  5005.4  506.85
  5055.6  508.02  5067.7  508.62  5087.4  508.96  5093.6  509.35  5108.5  509.71
  5124.7  510.43    5130   510.3  5150.6  510.85  5155.9  510.82  5205.4   512.3
#Mann= 3 ,-1 , 0
  4574.7     .05       0  4996.8     .04       0  5000.8     .05       0
Bank Sta=4996.8,5000.8
XS Rating Curve= 0 ,0
Exp/Cntr=0.3,0.1

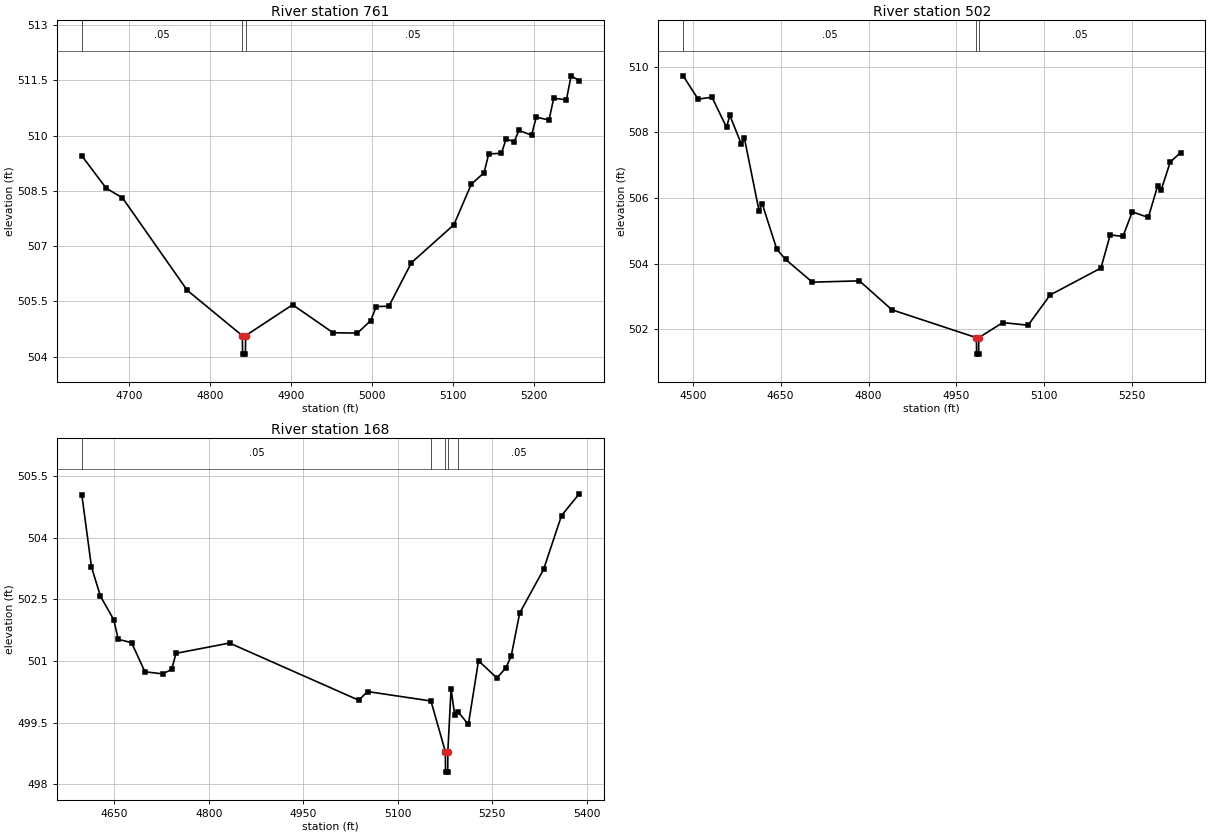
Type RM Length L Ch R = 1 ,761     ,259,259,259
BEGIN DESCRIPTION:
Lacy 045 2479
END DESCRIPTION:
XS GIS Cut Line= 3
       2766124.7      6896710.79      2766119.83      6897068.86
      2766248.86      6897289.85
#Sta/Elev= 30
  4641.9  509.45  4672.1  508.57  4692.1  508.31  4772.1   505.8  4840.1  504.57
  4840.4  504.07  4843.9  504.07  4844.1  504.57  4902.1  505.41  4952.1  504.65
  4982.1  504.64  4998.6  504.98  5005.3  505.36    5021  505.37  5048.8  506.55
  5101.2  507.58  5122.7  508.68  5138.4  508.99  5144.2   509.5  5159.9  509.52
  5165.7  509.91  5175.6  509.83  5181.4  510.14  5197.1  510.01  5202.9   510.5
  5218.6  510.42  5224.4  511.01  5240.1  510.97  5245.9  511.62  5255.9  511.49
#Mann= 3 ,-1 , 0
  4641.9     .05       0  4840.1     .04       0  4844.1     .05       0
Bank Sta=4840.1,4844.1
XS Rating Curve= 0 ,0
Exp/Cntr=0.3,0.1

Type RM Length L Ch R = 1 ,502     ,334,334,334
BEGIN DESCRIPTION:
Lacy 045 2477
END DESCRIPTION:
XS GIS Cut Line= 3
      2766097.12      6896726.99      2765916.95      6897210.94
      2766206.65      6897374.34
#Sta/Elev= 30
  4483.6  509.72  4509.2  509.01  4532.8  509.07  4557.8  508.15  4563.2  508.52
  4582.8  507.65  4588.2  507.82  4613.2  505.61  4618.5  505.83  4643.5  504.44
  4658.6  504.13  4704.2  503.44  4784.5  503.48  4839.9   502.6  4984.2  501.75
  4984.5  501.25    4988  501.25  4988.2  501.75  5029.1  502.21  5072.4  502.13
    5110  503.05  5196.7  503.87  5212.6  504.88  5234.2  504.83  5250.2  505.58
  5277.6  505.41  5293.5  506.37  5299.2  506.23  5315.1   507.1  5332.6  507.38
#Mann= 3 ,-1 , 0
  4483.6     .05       0  4984.2     .04       0  4988.2     .05       0
Bank Sta=4984.2,4988.2
XS Rating Curve= 0 ,0
Exp/Cntr=0.3,0.1

Type RM Length L Ch R = 1 ,168     ,0,0,0
BEGIN DESCRIPTION:
Lacy 045 2478
END DESCRIPTION:
XS GIS Cut Line= 3
      2765961.09       6896734.3      2765630.95      6897059.19
       2765473.8      6897345.62
#Sta/Elev= 30
  4598.2  505.05  4613.6  503.29  4627.8  502.58  4648.9  502.01  4656.1  501.53
  4677.2  501.45  4698.5  500.74  4726.8  500.69  4740.9   500.8  4747.9  501.19
  4832.8  501.44  5037.9  500.05  5052.1  500.26  5152.7  500.03  5175.5   498.8
  5175.8   498.3  5179.3   498.3  5179.5   498.8  5184.6  500.33  5190.3  499.69
  5195.6  499.77  5212.1  499.46  5228.2  501.01  5257.4  500.59  5271.8  500.84
  5280.2  501.13  5293.6  502.17  5331.5  503.23    5360  504.54  5388.1  505.07
#Mann= 5 ,-1 , 0
  4598.2     .05       0  5152.7     .12       0  5175.5     .05       0
  5179.5     .12       0  5195.6     .05       0
Bank Sta=5175.5,5179.5
XS Rating Curve= 0 ,0
Exp/Cntr=0.3,0.1

Chan Stop Cuts=-1
Use User Specified Reach Order=0
Composite Channel Slope=5