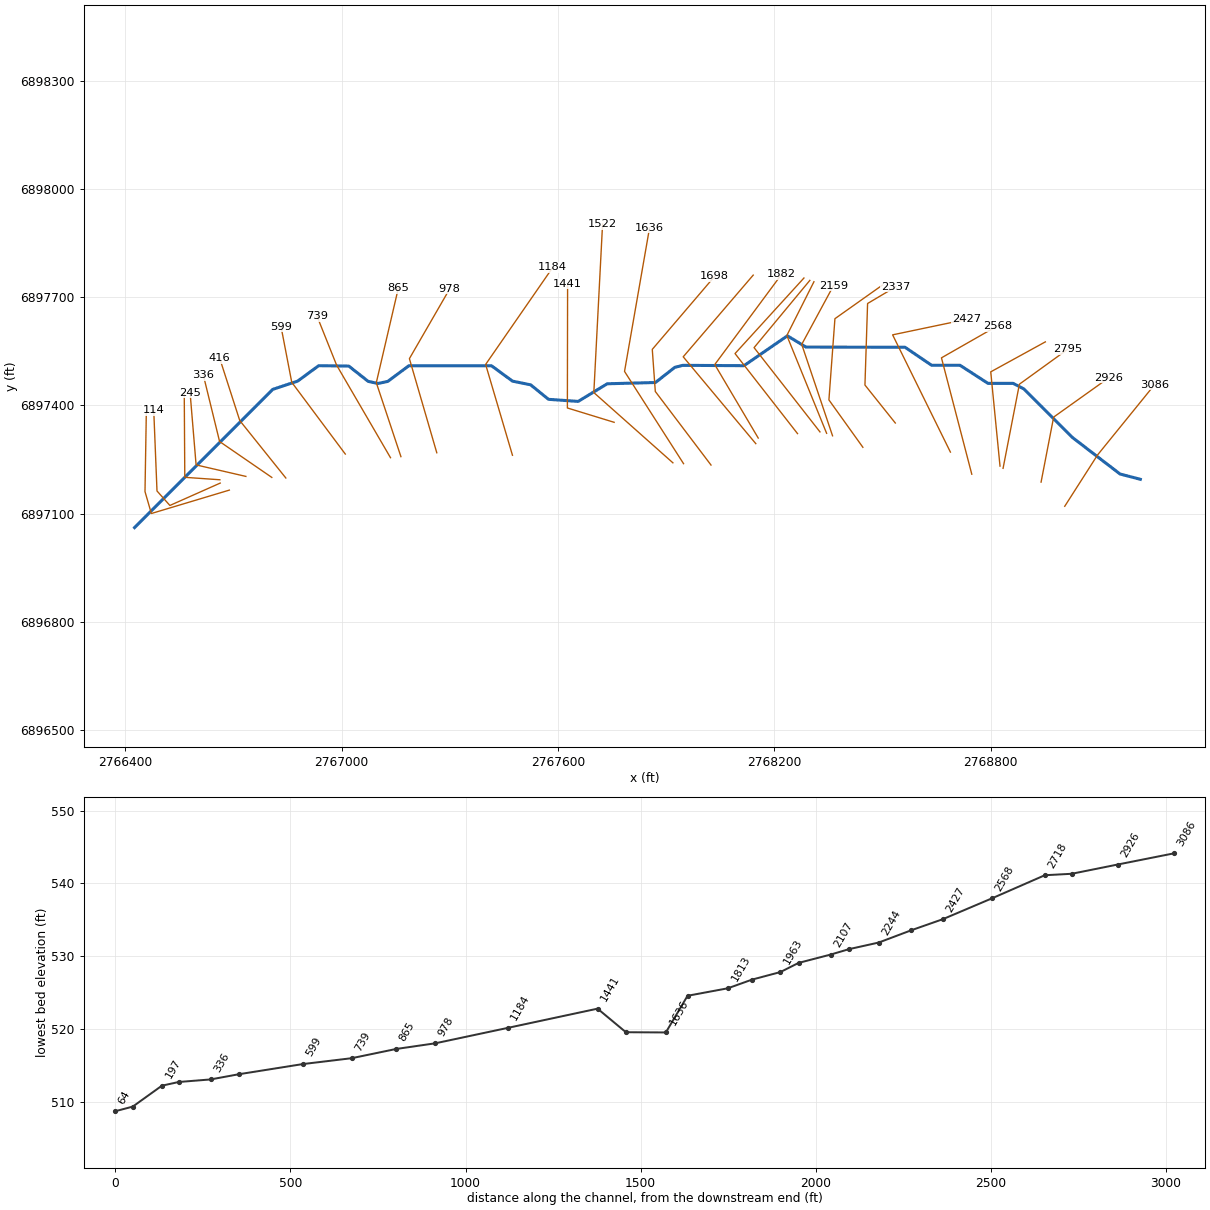
--- Lacy 046.prj (project) ---

Proj Title=Lacy 046 Base Level Engineering
Current Plan=p01
Default Exp/Contr=0.3,0.1
English Units
Geom File=g01
Flow File=f01
Plan File=p01
Y Axis Title=Elevation
X Axis Title(PF)=Main Channel Distance
X Axis Title(XS)=Station
BEGIN DESCRIPTION:
Lacy 046
END DESCRIPTION:
DSS Export Rating Curves= 0
DSS Export Rating Curve Sorted= 0
DSS Export Volume Flow Curves= 0
DXF OffsetX= 0
DXF OffsetY= 0
DXF ScaleX= 1
DXF ScaleY= 10

--- Lacy 046.p01 (plan) ---

Plan Title=Multiple Run
Short Identifier=Multiple
Geom File=g01
Flow File=f01
Subcritical Flow
K Sum by GR= 0
Std Step Tol= 0.01
Critical Tol= 0.01
Num of Std Step Trials= 20
Max Error Tol= 0.3
Flow Tol Ratio= 0.001
Split Flow NTrial= 30
Split Flow Tol= 0.02
Split Flow Ratio= 0.02
Log Output Level= 0
Friction Slope Method= 1
Unsteady Friction Slope Method= 2
Unsteady Bridges Friction Slope Method= 1
Parabolic Critical Depth
Global Vel Dist=  1 , 1 , 1
Global Log Level= 0
CheckData=True
Encroach Param= -1, 0, 0, 0
BEGIN DESCRIPTION:
Multiple Run
END DESCRIPTION:

--- Lacy 046.f01 (steady flow) ---

Flow Title=Multiple
Number of Profiles=7
Profile Names=10-year,25-year,50-year,1pct_min,100-year,1pct_plu,500-year
River Rch & RM= Lacy 046,Reach-1,3086
      56      63      68      37      74     147      85
Boundary for River Rch & Prof#=Lacy 046,Reach-1,1
Up Type=0
Dn Type=3
Dn Slope=0.005
Boundary for River Rch & Prof#=Lacy 046,Reach-1,2
Up Type=0
Dn Type=3
Dn Slope=0.005
Boundary for River Rch & Prof#=Lacy 046,Reach-1,3
Up Type=0
Dn Type=3
Dn Slope=0.005
Boundary for River Rch & Prof#=Lacy 046,Reach-1,4
Up Type=0
Dn Type=3
Dn Slope=0.005
Boundary for River Rch & Prof#=Lacy 046,Reach-1,5
Up Type=0
Dn Type=3
Dn Slope=0.005
Boundary for River Rch & Prof#=Lacy 046,Reach-1,6
Up Type=0
Dn Type=3
Dn Slope=0.005
Boundary for River Rch & Prof#=Lacy 046,Reach-1,7
Up Type=0
Dn Type=3
Dn Slope=0.005

--- Lacy 046.g01 (geometry) ---

Geom Title=Existing Conditions
Program Version=4.10

River Reach=Lacy 046        ,Reach-1
Reach XY= 30
      2769214.43      6897194.95      2769158.12      6897209.64
        2769026.        6897311.      2768891.61      6897445.39
      2768861.72        6897461.      2768791.87        6897461.
      2768714.64        6897511.      2768635.77        6897511.
      2768562.09        6897561.      2768287.46      6897561.51
      2768235.94       6897592.7      2768115.54      6897509.88
      2767946.03      6897510.93      2767923.67      6897505.25
      2767870.06      6897463.27      2767736.51      6897459.77
       2767655.9       6897410.9      2767573.68      6897416.65
      2767524.27      6897456.81      2767473.82      6897467.12
       2767415.5       6897509.8       2767186.5      6897509.76
      2767128.18      6897466.38        2767101.       6897460.6
      2767073.82      6897466.38      2767020.03      6897508.81
      2766936.54      6897509.92      2766878.17      6897467.15
      2766809.32      6897444.36        2766426.        6897061.

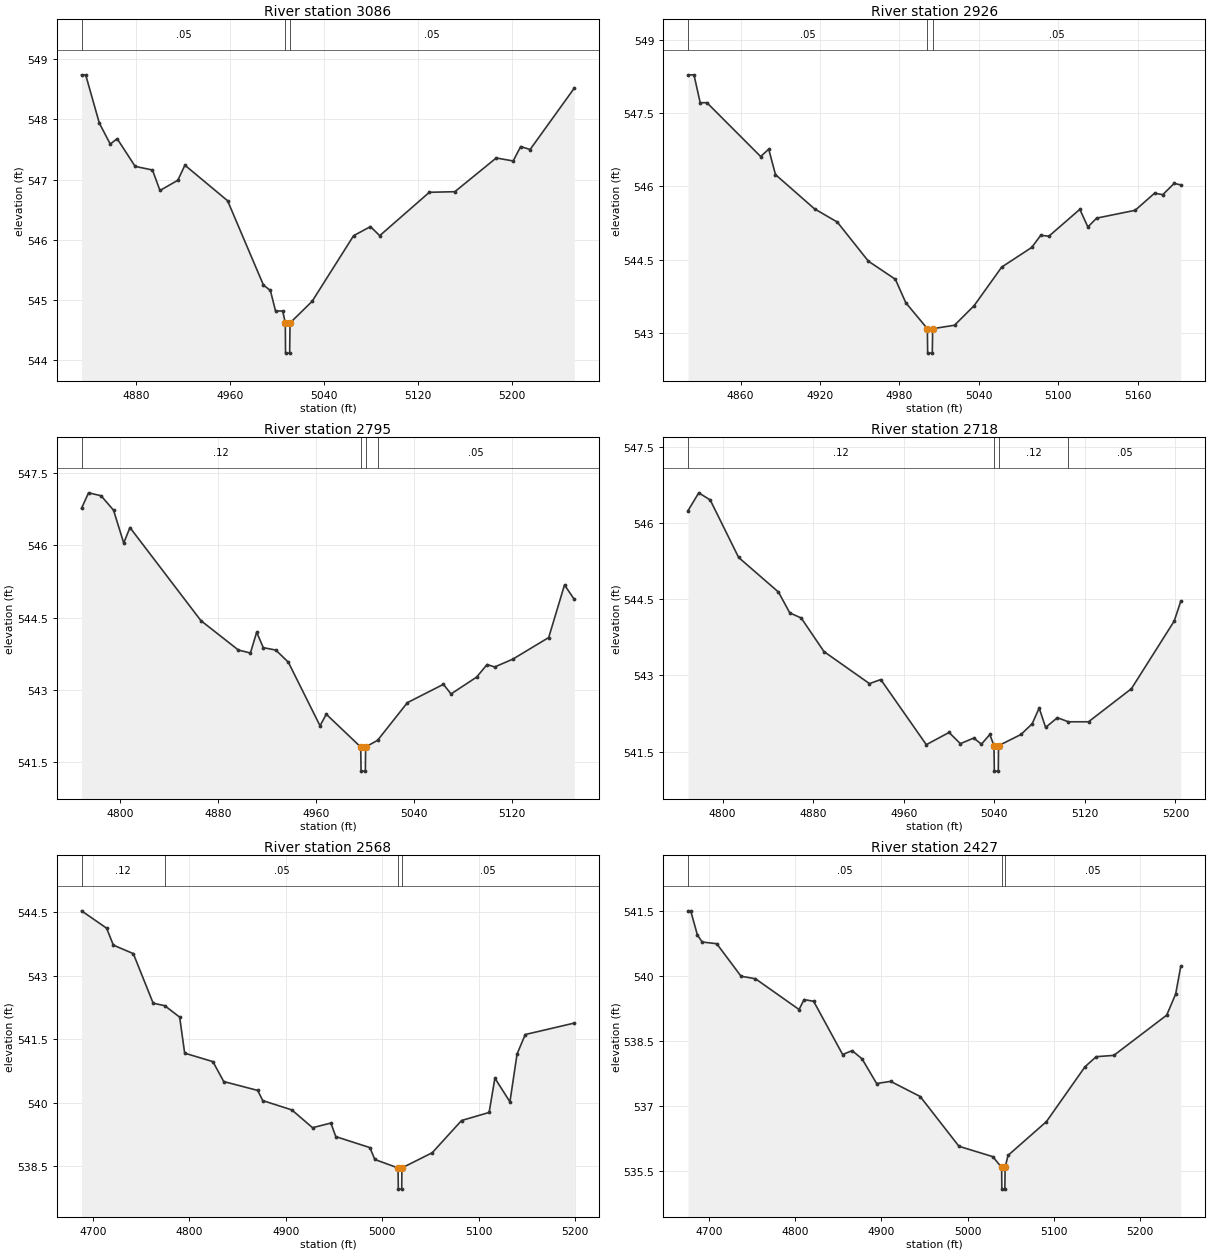
Type RM Length L Ch R = 1 ,3086    ,160,160,160
BEGIN DESCRIPTION:
Lacy 046 3400
END DESCRIPTION:
XS GIS Cut Line= 3
      2769004.82      6897120.17      2769095.75      6897262.34
      2769253.45      6897456.76
#Sta/Elev= 30
  4833.8  548.74  4837.3  548.74  4848.9  547.94  4858.2  547.59  4864.1  547.68
  4879.4  547.22  4894.1  547.16  4900.5  546.82  4915.7  546.99  4921.7  547.24
    4958  546.65  4988.5  545.25  4994.4  545.16  4998.8  544.82  5004.9  544.82
  5007.1  544.62  5007.3  544.12  5010.8  544.12  5011.1  544.62  5029.9  544.98
  5065.2  546.07  5079.5  546.22  5087.4  546.07  5129.6  546.79  5151.3   546.8
  5186.5  547.36  5200.9  547.31  5207.3  547.55  5215.3   547.5  5252.9  548.52
#Mann= 3 ,-1 , 0
  4833.8     .05       0  5007.1     .04       0  5011.1     .05       0
Bank Sta=5007.1,5011.1
XS Rating Curve= 0 ,0
Exp/Cntr=0.3,0.1

Type RM Length L Ch R = 1 ,2926    ,131,131,131
BEGIN DESCRIPTION:
Lacy 046 3399
END DESCRIPTION:
XS GIS Cut Line= 3
      2768939.22      6897187.13      2768974.06      6897367.39
      2769127.81      6897476.97
#Sta/Elev= 30
  4820.2  548.28  4824.7  548.28  4829.4  547.71  4834.5  547.71  4875.1  546.61
  4881.2  546.76  4886.3  546.24  4915.8  545.54    4933  545.27  4956.5  544.47
  4976.9   544.1  4984.8  543.62  5001.1  543.09  5001.3  542.59  5004.8  542.59
  5005.1  543.09  5021.6  543.16  5036.4  543.56  5057.3  544.35  5079.9  544.75
  5086.8     545  5092.9  544.98  5116.3  545.53  5122.4  545.17    5129  545.35
  5158.1  545.51  5172.8  545.86    5179  545.83  5187.6  546.06  5192.6  546.03
#Mann= 3 ,-1 , 0
  4820.2     .05       0  5001.1     .04       0  5005.1     .05       0
Bank Sta=5001.1,5005.1
XS Rating Curve= 0 ,0
Exp/Cntr=0.3,0.1

Type RM Length L Ch R = 1 ,2795    ,77,77,77
BEGIN DESCRIPTION:
Lacy 046 3398
END DESCRIPTION:
XS GIS Cut Line= 3
      2768833.85      6897225.37      2768879.12      6897458.56
      2769012.45        6897555.
#Sta/Elev= 30
  4768.6  546.77  4774.3  547.09  4784.5  547.03  4794.7  546.73    4803  546.05
  4808.1  546.37    4866  544.44  4896.6  543.83  4906.4  543.77  4911.5   544.2
  4916.9  543.88  4927.1  543.83  4937.3  543.58  4963.2  542.26  4968.3   542.5
  4996.4  541.82  4996.7  541.32  5000.2  541.32  5000.4  541.82  5010.2  541.96
  5034.5  542.74  5063.9  543.12  5070.1  542.92    5091  543.27  5099.5  543.53
  5105.7  543.48  5120.4  543.64  5149.8  544.09  5162.7  545.18  5170.7  544.88
#Mann= 4 ,-1 , 0
  4768.6     .12       0  4996.4     .07       0  5000.4     .12       0
  5010.2     .05       0
Bank Sta=4996.4,5000.4
XS Rating Curve= 0 ,0
Exp/Cntr=0.3,0.1

Type RM Length L Ch R = 1 ,2718    ,150,150,150
BEGIN DESCRIPTION:
Lacy 046 3460
END DESCRIPTION:
XS GIS Cut Line= 3
      2768825.38      6897231.51      2768799.67      6897492.84
      2768951.07      6897575.94
#Sta/Elev= 30
  4769.4  546.24  4778.9  546.59    4789  546.45  4814.1  545.32  4849.3  544.64
  4859.3  544.23  4869.4  544.13  4889.5  543.47  4929.7  542.84  4939.7  542.92
  4979.9  541.64    5000  541.88    5010  541.66  5021.8  541.77  5028.6  541.65
    5036  541.84  5039.7  541.62    5040  541.12  5043.5  541.12  5043.7  541.62
  5063.5  541.84  5073.4  542.05  5079.6  542.36  5085.3  541.98  5095.7  542.17
  5105.4  542.09  5123.2  542.09  5161.1  542.74  5198.9  544.07  5204.7  544.46
#Mann= 4 ,-1 , 0
  4769.4     .12       0  5039.7     .07       0  5043.7     .12       0
  5105.4     .05       0
Bank Sta=5039.7,5043.7
XS Rating Curve= 0 ,0
Exp/Cntr=0.3,0.1

Type RM Length L Ch R = 1 ,2568    ,141,141,141
BEGIN DESCRIPTION:
Lacy 046 3459
END DESCRIPTION:
XS GIS Cut Line= 3
       2768747.1      6897209.08      2768663.05      6897531.68
      2768817.57       6897619.9
#Sta/Elev= 30
    4688  544.53    4714  544.12    4721  543.72  4741.7  543.52  4762.3  542.35
  4774.4  542.29  4789.8  542.02    4795  541.17  4824.3  540.97  4835.5   540.5
  4870.8  540.29    4876  540.05  4906.2  539.83  4927.7  539.41  4946.7  539.52
  4951.8   539.2  4987.2  538.94  4992.3  538.66  5016.4  538.46  5016.7  537.96
  5020.2  537.96  5020.4  538.46  5051.9  538.82  5082.3  539.58  5110.9  539.77
  5116.9  540.58  5132.5  540.02  5139.9  541.15  5148.4  541.61  5199.3  541.88
#Mann= 4 ,-1 , 0
    4688     .12       0  4774.4     .05       0  5016.4     .05       0
  5020.4     .05       0
Bank Sta=5016.4,5020.4
XS Rating Curve= 0 ,0
Exp/Cntr=0.3,0.1

Type RM Length L Ch R = 1 ,2427    ,90,90,90
BEGIN DESCRIPTION:
Lacy 046 3458
END DESCRIPTION:
XS GIS Cut Line= 3
      2768687.83      6897270.37      2768527.65      6897595.44
      2768731.92      6897638.21
#Sta/Elev= 30
    4676  541.51  4679.1  541.51  4686.9  540.95  4692.4  540.79  4709.3  540.75
  4737.4     540  4754.2  539.94  4804.7  539.23  4810.5  539.46  4821.6  539.42
  4855.2  538.19  4866.2  538.28  4877.7  538.09  4894.6  537.52  4910.8  537.57
  4945.1  537.22    4990  536.07  5029.3  535.83  5039.5  535.58  5039.7  535.08
  5043.2  535.08  5043.5  535.58  5046.9  535.86  5091.4  536.64  5136.2  537.91
  5149.1  538.14  5169.5  538.17  5230.8   539.1  5241.2  539.59  5247.1  540.23
#Mann= 3 ,-1 , 0
    4676     .05       0  5039.5     .04       0  5043.5     .05       0
Bank Sta=5039.5,5043.5
XS Rating Curve= 0 ,0
Exp/Cntr=0.3,0.1

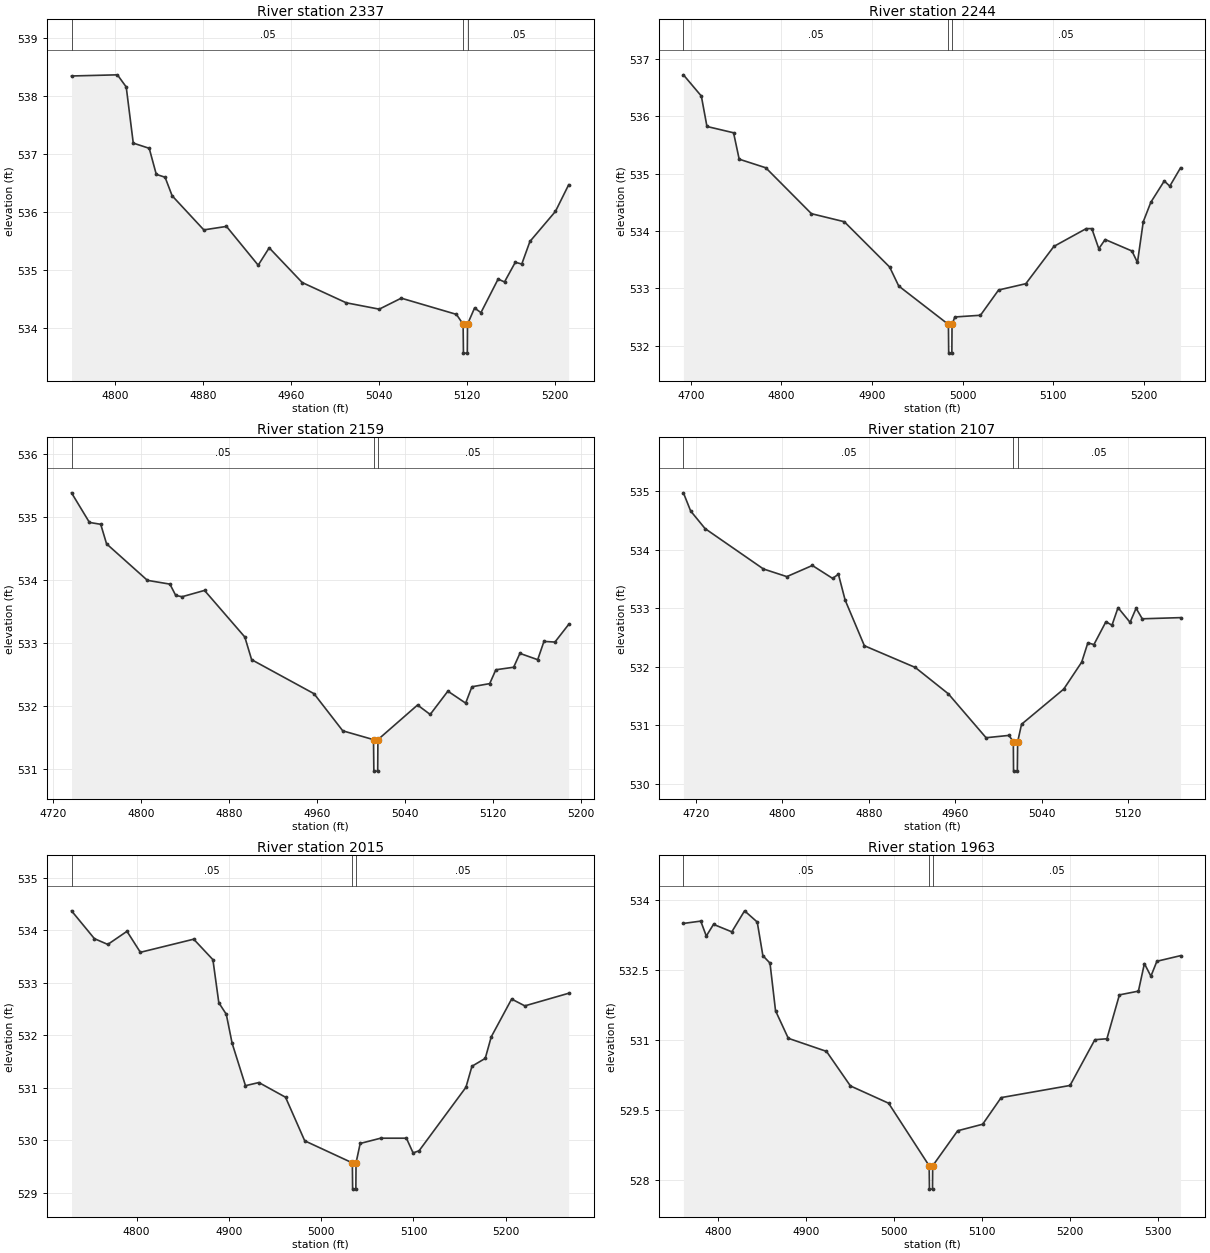
Type RM Length L Ch R = 1 ,2337    ,93,93,93
BEGIN DESCRIPTION:
Lacy 046 3397
END DESCRIPTION:
XS GIS Cut Line= 4
       2768535.1      6897350.96      2768450.93      6897456.29
      2768458.25       6897682.3      2768536.31      6897728.56
#Sta/Elev= 30
  4760.4  538.35  4802.1  538.37  4810.1  538.16  4816.5  537.19    4831   537.1
  4837.4  536.65  4845.4   536.6  4851.8  536.28  4880.6  535.69  4901.2  535.75
    4930  535.08    4940  535.38    4970  534.78    5010  534.43    5040  534.32
    5060  534.51  5110.1  534.23  5116.2  534.06  5116.5  533.56    5120  533.56
  5120.2  534.06  5126.6  534.34  5132.4  534.26    5148  534.84  5153.8  534.79
  5163.6  535.13  5169.5   535.1  5176.9  535.49  5200.1  536.01  5212.1  536.47
#Mann= 3 ,-1 , 0
  4760.4     .05       0  5116.2     .04       0  5120.2     .05       0
Bank Sta=5116.2,5120.2
XS Rating Curve= 0 ,0
Exp/Cntr=0.3,0.1

Type RM Length L Ch R = 1 ,2244    ,85,85,85
BEGIN DESCRIPTION:
Lacy 046 3396
END DESCRIPTION:
XS GIS Cut Line= 4
      2768445.22      6897283.66      2768351.05      6897415.02
       2768367.7      6897640.18      2768499.66      6897733.62
#Sta/Elev= 30
  4691.7  536.72  4711.5  536.35  4717.7  535.82  4747.1  535.71  4753.3  535.25
  4782.7   535.1  4833.1   534.3  4869.4  534.16  4919.5  533.37  4929.5  533.04
  4984.4  532.37  4984.7  531.87  4988.2  531.87  4988.4  532.37  4991.5   532.5
  5019.8  532.53  5039.8  532.97  5069.9  533.08  5100.9  533.73  5136.6  534.04
  5142.8  534.04  5150.5  533.69  5157.5  533.85  5187.1  533.65  5193.2  533.45
  5199.6  534.16    5208   534.5  5222.8  534.87  5228.9  534.78  5240.8   535.1
#Mann= 3 ,-1 , 0
  4691.7     .05       0  4984.4     .04       0  4988.4     .05       0
Bank Sta=4984.4,4988.4
XS Rating Curve= 0 ,0
Exp/Cntr=0.3,0.1

Type RM Length L Ch R = 1 ,2159    ,52,52,52
BEGIN DESCRIPTION:
Lacy 046 3395
END DESCRIPTION:
XS GIS Cut Line= 3
      2768361.12      6897315.56      2768275.67      6897569.02
      2768363.77      6897731.95
#Sta/Elev= 30
  4736.5  535.38  4752.8  534.91  4763.1  534.88  4768.4  534.57  4805.6  533.99
  4826.1  533.93  4831.4  533.75  4837.2  533.73  4857.6  533.83  4894.3  533.09
  4900.5  532.73  4957.3  532.19  4983.5   531.6  5011.5  531.46  5011.8  530.96
  5015.3  530.96  5015.5  531.46  5051.6  532.01  5063.1  531.86  5079.2  532.23
  5095.4  532.04  5101.1   532.3  5117.3  532.35  5122.9  532.57  5139.1  532.61
  5144.8  532.83    5161  532.73  5166.7  533.02  5176.7  533.01  5189.2  533.29
#Mann= 3 ,-1 , 0
  4736.5     .05       0  5011.5     .04       0  5015.5     .05       0
Bank Sta=5011.5,5015.5
XS Rating Curve= 0 ,0
Exp/Cntr=0.3,0.1

Type RM Length L Ch R = 1 ,2107    ,92,92,92
BEGIN DESCRIPTION:
Lacy 046 3455
END DESCRIPTION:
XS GIS Cut Line= 3
      2768344.65      6897322.49      2768234.38       6897593.6
      2768309.52      6897742.65
#Sta/Elev= 30
  4708.7  534.97  4715.4  534.66  4728.7  534.36  4782.7  533.67  4804.3  533.54
  4827.9  533.73  4846.6  533.51    4852  533.58  4858.2  533.14    4876  532.36
    4923  531.99  4953.6  531.54  4988.5  530.79  5009.7  530.83  5013.7  530.72
  5013.9  530.22  5017.4  530.22  5017.7  530.72  5021.3  531.02  5060.3  531.62
  5076.9  532.08  5082.6  532.41  5088.2  532.38  5099.3  532.77  5104.9  532.71
  5110.5  533.01  5121.6  532.76  5127.2     533  5132.9  532.82  5168.3  532.84
#Mann= 3 ,-1 , 0
  4708.7     .05       0  5013.7     .04       0  5017.7     .05       0
Bank Sta=5013.7,5017.7
XS Rating Curve= 0 ,0
Exp/Cntr=0.3,0.1

Type RM Length L Ch R = 1 ,2015    ,52,52,52
BEGIN DESCRIPTION:
Lacy 046 3454
END DESCRIPTION:
XS GIS Cut Line= 3
      2768326.23      6897326.36      2768143.55      6897559.97
      2768298.12      6897746.36
#Sta/Elev= 30
  4729.5  534.37  4754.3  533.84  4768.8  533.73  4789.6  533.98  4804.1  533.58
  4861.9  533.83  4882.7  533.44  4889.1  532.62  4897.2   532.4  4903.5  531.85
    4918  531.04  4932.5   531.1  4961.4  530.82  4982.2  529.99  5033.8  529.57
  5034.1  529.07  5037.6  529.07  5037.8  529.57  5042.3  529.94  5064.5  530.04
  5092.4  530.04  5099.6  529.76  5106.1   529.8  5156.9  531.01  5163.4  531.41
  5177.8  531.56  5184.3  531.97  5206.4  532.69  5220.7  532.56  5268.2   532.8
#Mann= 3 ,-1 , 0
  4729.5     .05       0  5033.8     .04       0  5037.8     .05       0
Bank Sta=5033.8,5037.8
XS Rating Curve= 0 ,0
Exp/Cntr=0.3,0.1

Type RM Length L Ch R = 1 ,1963    ,81,81,81
BEGIN DESCRIPTION:
Lacy 046 3453
END DESCRIPTION:
XS GIS Cut Line= 3
        2768264.      6897321.59      2768090.79      6897543.51
      2768281.81      6897752.98
#Sta/Elev= 30
  4760.5   533.5  4780.2  533.55  4786.5  533.23  4794.7  533.48  4815.5  533.32
    4830  533.77  4844.4  533.53  4850.8  532.81  4858.9  532.65  4865.2  531.63
  4879.7  531.04  4923.1  530.76  4950.3  530.02  4993.7  529.65  5039.8  528.31
  5040.1  527.81  5043.6  527.81  5043.8  528.31  5072.2  529.06  5100.6   529.2
  5121.6  529.77  5199.9  530.03  5228.1  531.01  5241.8  531.03    5256  531.97
  5277.6  532.05  5284.4  532.64  5291.8  532.37  5298.6  532.69  5325.5  532.81
#Mann= 3 ,-1 , 0
  4760.5     .05       0  5039.8     .04       0  5043.8     .05       0
Bank Sta=5039.8,5043.8
XS Rating Curve= 0 ,0
Exp/Cntr=0.3,0.1

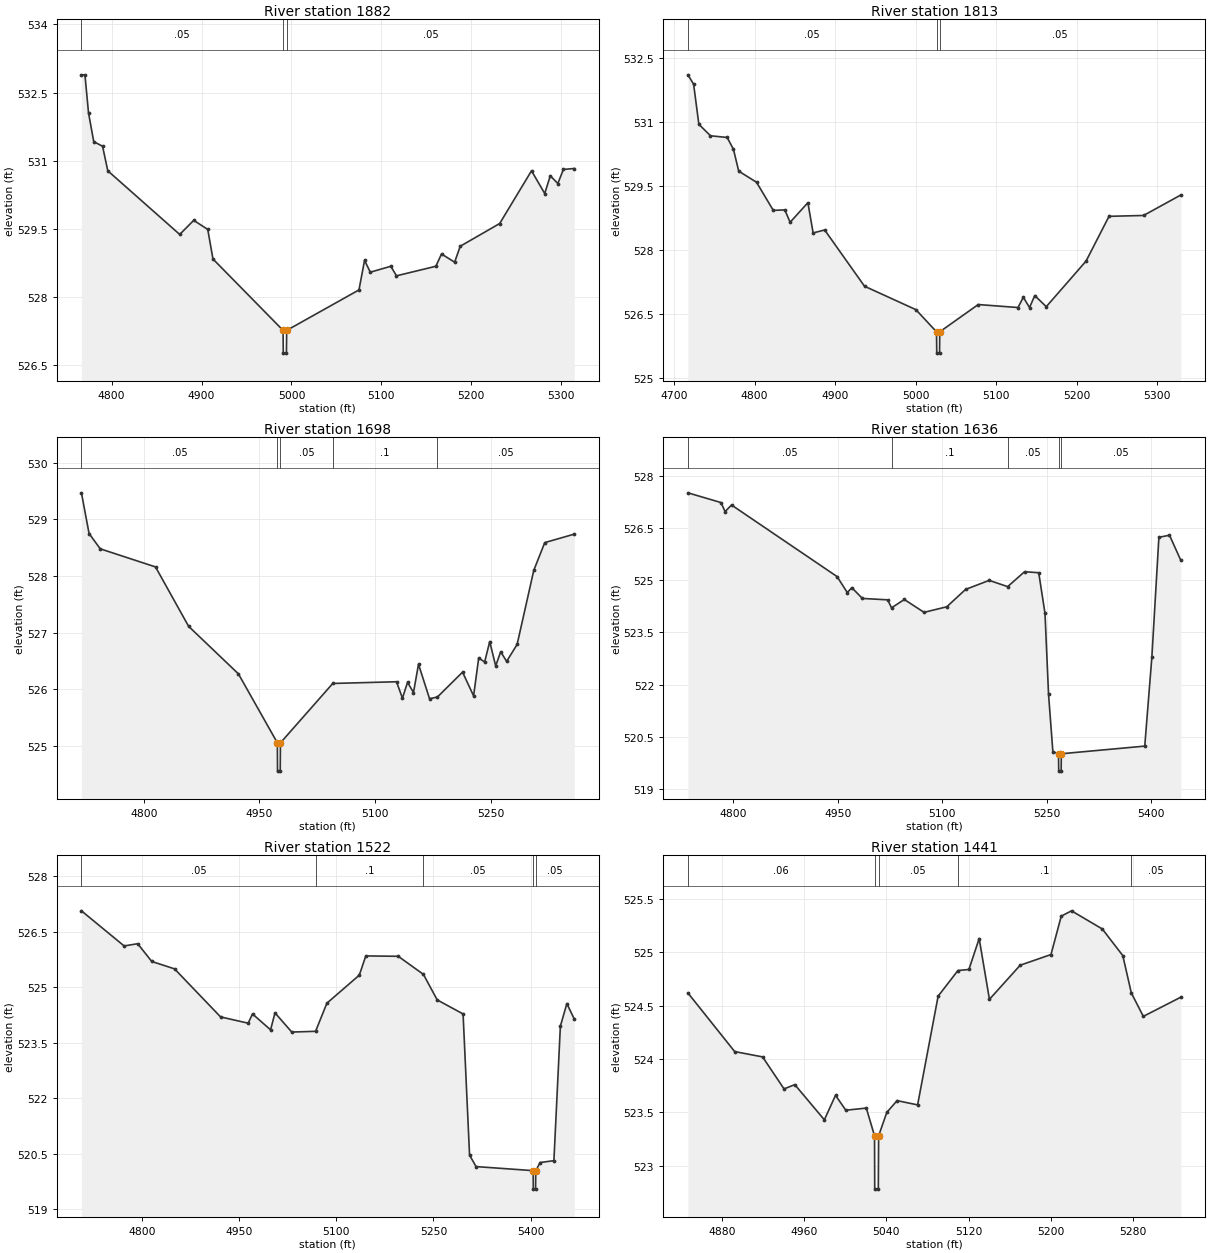
Type RM Length L Ch R = 1 ,1882    ,69,69,69
BEGIN DESCRIPTION:
Lacy 046 3394
END DESCRIPTION:
XS GIS Cut Line= 3
      2768155.08      6897309.32      2768034.56      6897513.06
      2768219.95      6897763.36
#Sta/Elev= 30
  4766.4  532.89  4770.3  532.89  4774.3  532.05  4780.1  531.42  4789.9  531.32
  4795.7  530.78  4875.7  529.38  4891.3  529.69  4906.9  529.49  4912.7  528.84
  4990.7  527.27  4990.9  526.77  4994.4  526.77  4994.7  527.27  5075.1  528.16
  5081.3  528.81  5087.7  528.55  5110.5  528.68  5116.8  528.47  5160.6  528.68
  5166.9  528.95  5181.5  528.77  5187.7  529.12  5231.6  529.62    5267  530.78
  5281.7  530.28  5287.9  530.67  5296.3   530.5  5302.5  530.81  5314.6  530.83
#Mann= 3 ,-1 , 0
  4766.4     .05       0  4990.7     .04       0  4994.7     .05       0
Bank Sta=4990.7,4994.7
XS Rating Curve= 0 ,0
Exp/Cntr=0.3,0.1

Type RM Length L Ch R = 1 ,1813    ,115,115,115
BEGIN DESCRIPTION:
Lacy 046 3457
END DESCRIPTION:
XS GIS Cut Line= 3
       2768148.3       6897293.8      2767947.11      6897534.55
      2768141.16      6897761.04
#Sta/Elev= 30
  4717.2  532.11  4724.3  531.89  4730.8  530.95  4745.2  530.68    4766  530.64
  4773.8  530.36  4780.3  529.85  4802.4  529.59  4823.2  528.93  4837.6  528.94
  4844.1  528.65  4866.2  529.11  4872.7   528.4    4887  528.47  4936.5  527.15
  5000.3   526.6  5025.9  526.08  5026.2  525.58  5029.7  525.58  5029.9  526.08
  5077.7  526.72  5127.1  526.65  5133.7  526.89  5141.4  526.65  5147.9  526.93
  5162.2  526.67  5211.6  527.74  5240.1  528.79    5283  528.81  5329.2  529.29
#Mann= 3 ,-1 , 0
  4717.2     .05       0  5025.9     .04       0  5029.9     .05       0
Bank Sta=5025.9,5029.9
XS Rating Curve= 0 ,0
Exp/Cntr=0.3,0.1

Type RM Length L Ch R = 1 ,1698    ,62,62,62
BEGIN DESCRIPTION:
Lacy 046 3456
END DESCRIPTION:
XS GIS Cut Line= 4
      2768024.19      6897234.45      2767869.73      6897438.47
      2767861.35      6897555.16      2768033.96      6897757.32
#Sta/Elev= 30
  4719.3  529.47  4729.2  528.75  4743.7  528.48  4815.3  528.16  4858.2  527.11
  4922.7  526.27  4973.2  525.05  4973.4  524.55  4976.9  524.55  4977.2  525.05
    5045   526.1  5127.6  526.13  5135.3  525.84  5141.9  526.12  5149.6  525.94
  5156.1  526.44  5170.4  525.83  5180.6  525.86  5213.2   526.3  5227.5  525.88
  5234.1  526.55  5241.8  526.48  5248.4  526.84  5256.1  526.41  5262.6  526.66
  5270.3  526.49  5283.9  526.79  5305.5   528.1  5319.7  528.59    5358  528.74
#Mann= 5 ,-1 , 0
  4719.3     .05       0  4973.2     .04       0  4977.2     .05       0
    5045      .1       0  5180.6     .05       0
Bank Sta=4973.2,4977.2
XS Rating Curve= 0 ,0
Exp/Cntr=0.3,0.1

Type RM Length L Ch R = 1 ,1636    ,114,114,114
BEGIN DESCRIPTION:
Lacy 046 3442
END DESCRIPTION:
XS GIS Cut Line= 3
      2767948.06      6897238.26      2767784.42      6897494.03
      2767853.78      6897891.89
#Sta/Elev= 30
  4734.9  527.52  4782.4  527.24  4788.3  526.98  4797.5  527.17    4949  525.11
  4963.7  524.65  4970.2  524.79  4985.4  524.48  5021.7  524.44  5027.2  524.21
  5045.6  524.45  5073.9  524.08  5106.5  524.24  5133.5  524.74  5167.4     525
  5193.9  524.82  5218.2  525.25  5238.5  525.22  5247.5  524.05  5252.6  521.72
  5258.8  520.07  5266.9  520.01  5267.2  519.51  5270.7  519.51  5270.9  520.01
  5390.7  520.23  5400.9  522.79    5411  526.24  5426.2   526.3  5442.4  525.58
#Mann= 5 ,-1 , 0
  4734.9     .05       0  5027.2      .1       0  5193.9     .05       0
  5266.9     .04       0  5270.9     .05       0
Bank Sta=5266.9,5270.9
XS Rating Curve= 0 ,0
Exp/Cntr=0.3,0.1

Type RM Length L Ch R = 1 ,1522    ,81,81,81
BEGIN DESCRIPTION:
Lacy 046 3393
END DESCRIPTION:
XS GIS Cut Line= 3
      2767918.49      6897240.65      2767699.32      6897435.34
      2767723.53      6897902.46
#Sta/Elev= 30
  4706.6  527.07  4772.5  526.12  4793.4  526.18  4815.2   525.7  4850.3   525.5
  4921.4   524.2    4964  524.03  4970.7  524.28  4998.6  523.85  5005.4  524.31
  5031.3  523.79  5068.1  523.81  5085.5  524.57  5135.6  525.33  5145.6  525.85
  5195.7  525.84  5234.6  525.35  5255.8  524.66  5295.8  524.28  5305.8  520.46
  5315.8  520.15    5404  520.04  5404.2  519.54  5407.7  519.54    5408  520.04
  5414.8  520.26    5436  520.31    5446  523.95    5456  524.56  5467.5  524.14
#Mann= 5 ,-1 , 0
  4706.6     .05       0  5068.1      .1       0  5234.6     .05       0
    5404     .04       0    5408     .05       0
Bank Sta=5404,5408
XS Rating Curve= 0 ,0
Exp/Cntr=0.3,0.1

Type RM Length L Ch R = 1 ,1441    ,257,257,257
BEGIN DESCRIPTION:
Lacy 046 3392
END DESCRIPTION:
XS GIS Cut Line= 3
       2767755.6      6897352.96      2767625.96       6897392.7
      2767626.59       6897737.5
#Sta/Elev= 30
  4846.5  524.62  4892.1  524.07  4919.3  524.02  4940.2  523.72  4950.7  523.76
  4979.5  523.43  4990.4  523.66  5000.4  523.52  5020.4  523.54  5028.4  523.28
  5028.6  522.78  5032.1  522.78  5032.4  523.28  5040.4   523.5  5050.4  523.61
  5070.4  523.57  5090.4  524.59  5109.7  524.83  5120.4  524.84  5130.4  525.13
  5140.4  524.56  5170.4  524.88  5200.4  524.98  5210.4  525.34  5220.4  525.39
  5250.4  525.22  5270.4  524.97  5278.7  524.62  5290.4   524.4  5326.9  524.58
#Mann= 5 ,-1 , 0
  4846.5     .06       0  5028.4     .03       0  5032.4     .05       0
  5109.7      .1       0  5278.7     .05       0
Bank Sta=5028.4,5032.4
XS Rating Curve= 0 ,0
Exp/Cntr=0.3,0.1

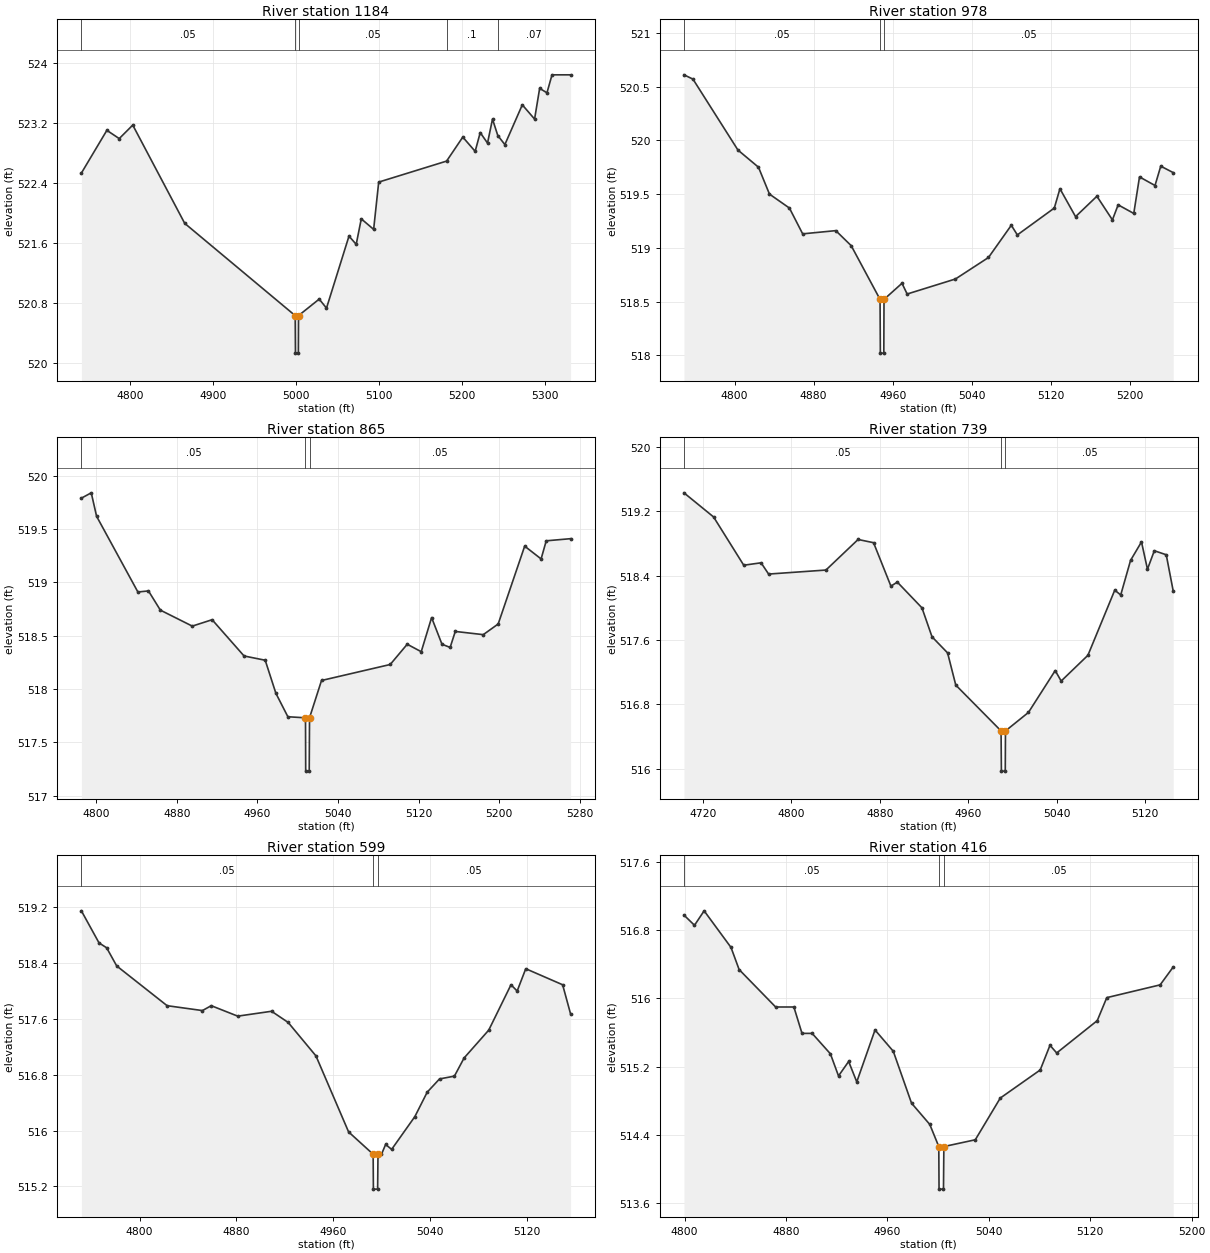
Type RM Length L Ch R = 1 ,1184    ,206,206,206
BEGIN DESCRIPTION:
Lacy 046 3391
END DESCRIPTION:
XS GIS Cut Line= 3
      2767473.73       6897261.6      2767399.34      6897513.41
      2767585.35      6897782.15
#Sta/Elev= 30
  4741.2  522.53  4771.9   523.1  4786.8  522.99  4803.1  523.17  4865.7  521.86
  4998.8  520.63  4999.1  520.13  5002.6  520.13  5002.8  520.63  5027.7  520.85
  5036.5  520.73  5063.6  521.69  5072.3  521.58  5078.4  521.92  5093.3  521.78
  5099.4  522.41  5181.2  522.69  5200.7  523.01  5215.6  522.82  5221.7  523.07
  5230.5  522.93  5236.5  523.25  5242.9  523.03  5251.4  522.91  5272.4  523.44
  5287.2  523.25  5293.3  523.66  5302.1   523.6  5308.2  523.84  5330.6  523.84
#Mann= 5 ,-1 , 0
  4741.2     .05       0  4998.8     .03       0  5002.8     .05       0
  5181.2      .1       0  5242.9     .07       0
Bank Sta=4998.8,5002.8
XS Rating Curve= 0 ,0
Exp/Cntr=0.3,0.1

Type RM Length L Ch R = 1 ,978     ,113,113,113
BEGIN DESCRIPTION:
Lacy 046 3390
END DESCRIPTION:
XS GIS Cut Line= 3
      2767263.91      6897268.56      2767188.01      6897529.46
      2767299.65      6897722.84
#Sta/Elev= 30
  4748.8  520.61  4757.9  520.57  4803.4  519.91  4824.2  519.75  4835.3   519.5
  4855.5  519.37  4868.9  519.13  4902.4  519.16    4918  519.02  4947.2  518.52
  4947.5  518.02    4951  518.02  4951.2  518.52  4969.4  518.67  4974.6  518.57
  5023.5  518.71  5056.9  518.91    5080  519.21  5086.1  519.12  5123.5  519.37
  5129.2  519.55    5145  519.29  5166.6  519.48  5182.3  519.26  5188.1   519.4
  5203.9  519.32  5209.7  519.66  5225.4  519.58  5231.2  519.76  5243.8   519.7
#Mann= 3 ,-1 , 0
  4748.8     .05       0  4947.2     .04       0  4951.2     .05       0
Bank Sta=4947.2,4951.2
XS Rating Curve= 0 ,0
Exp/Cntr=0.3,0.1

Type RM Length L Ch R = 1 ,865     ,126,126,126
BEGIN DESCRIPTION:
Lacy 046 2487
END DESCRIPTION:
XS GIS Cut Line= 3
      2767164.49      6897257.79      2767096.28      6897462.79
      2767157.46      6897725.41
#Sta/Elev= 30
  4785.3  519.79  4795.1  519.84  4800.4  519.62  4841.4  518.91  4851.9  518.92
  4863.7  518.74  4895.4  518.59  4915.1  518.65  4946.8  518.31  4967.8  518.27
  4978.4  517.96  4990.3  517.74  5007.8  517.73    5008  517.23  5011.5  517.23
  5011.8  517.73  5023.7  518.08  5091.9  518.23  5108.8  518.42  5122.7  518.35
    5133  518.67  5143.3  518.42  5151.4  518.39  5156.5  518.54  5184.3  518.51
  5199.1  518.61  5225.4  519.34  5241.7  519.22  5246.8  519.39    5271  519.41
#Mann= 3 ,-1 , 0
  4785.3     .05       0  5007.8     .04       0  5011.8     .05       0
Bank Sta=5007.8,5011.8
XS Rating Curve= 0 ,0
Exp/Cntr=0.3,0.1

Type RM Length L Ch R = 1 ,739     ,140,140,140
BEGIN DESCRIPTION:
Lacy 046 2486
END DESCRIPTION:
XS GIS Cut Line= 3
       2767135.6      6897254.82      2766986.05      6897511.77
      2766932.04      6897646.87
#Sta/Elev= 30
  4702.7  519.43  4729.5  519.13  4756.8  518.53  4772.5  518.56  4779.3  518.42
  4831.2  518.47  4860.3  518.85  4874.3  518.81    4890  518.27  4895.8  518.32
  4918.1     518  4927.2  517.64  4941.3  517.44  4948.7  517.04  4989.7  516.47
    4990  515.97  4993.5  515.97  4993.7  516.47  5014.5   516.7  5038.7  517.22
  5044.1  517.09  5068.3  517.41  5092.6  518.22    5098  518.16  5106.9  518.59
  5116.8  518.82  5122.2  518.48  5128.4  518.71  5139.2  518.66  5145.5  518.21
#Mann= 3 ,-1 , 0
  4702.7     .05       0  4989.7     .03       0  4993.7     .05       0
Bank Sta=4989.7,4993.7
XS Rating Curve= 0 ,0
Exp/Cntr=0.3,0.1

Type RM Length L Ch R = 1 ,599     ,183,183,183
BEGIN DESCRIPTION:
Lacy 046 2485
END DESCRIPTION:
XS GIS Cut Line= 3
      2767010.26      6897264.94      2766861.86      6897463.89
      2766832.26      6897617.46
#Sta/Elev= 30
  4751.8  519.15  4766.4  518.69  4772.7  518.62    4781  518.36  4822.7  517.79
  4851.9  517.72  4859.2  517.79  4881.1  517.64  4909.1  517.71  4922.8  517.55
  4945.8  517.07  4972.8  515.98  4993.1  515.66  4993.3  515.16  4996.8  515.16
  4997.1  515.66    5000  515.66  5003.4   515.8  5008.4  515.73  5027.6   516.2
  5037.8  516.55    5048  516.74  5060.3  516.78  5068.3  517.04  5088.7  517.44
  5107.1  518.09  5112.2     518  5119.3  518.32  5149.8  518.09  5156.4  517.67
#Mann= 3 ,-1 , 0
  4751.8     .05       0  4993.1     .03       0  4997.1     .05       0
Bank Sta=4993.1,4997.1
XS Rating Curve= 0 ,0
Exp/Cntr=0.3,0.1

Type RM Length L Ch R = 1 ,416     ,80,80,80
BEGIN DESCRIPTION:
Lacy 046 2484
END DESCRIPTION:
XS GIS Cut Line= 3
       2766845.4      6897198.58      2766717.65       6897357.9
      2766661.97      6897530.84
#Sta/Elev= 30
  4799.5  516.98  4807.8  516.86  4815.4  517.03  4836.6   516.6    4843  516.34
  4871.8   515.9  4886.2   515.9  4892.6  515.59  4900.6  515.59    4915  515.35
  4921.4  515.09  4929.4  515.26  4935.8  515.02  4950.2  515.63  4964.6  515.38
    4979  514.77  4993.4  514.52  5000.5  514.26  5000.7  513.76  5004.2  513.76
  5004.5  514.26  5029.3  514.34    5049  514.83  5080.5  515.16  5088.2  515.45
  5093.5  515.36  5125.5  515.74    5133  516.01  5175.1  516.16  5185.4  516.37
#Mann= 3 ,-1 , 0
  4799.5     .05       0  5000.5     .04       0  5004.5     .05       0
Bank Sta=5000.5,5004.5
XS Rating Curve= 0 ,0
Exp/Cntr=0.3,0.1

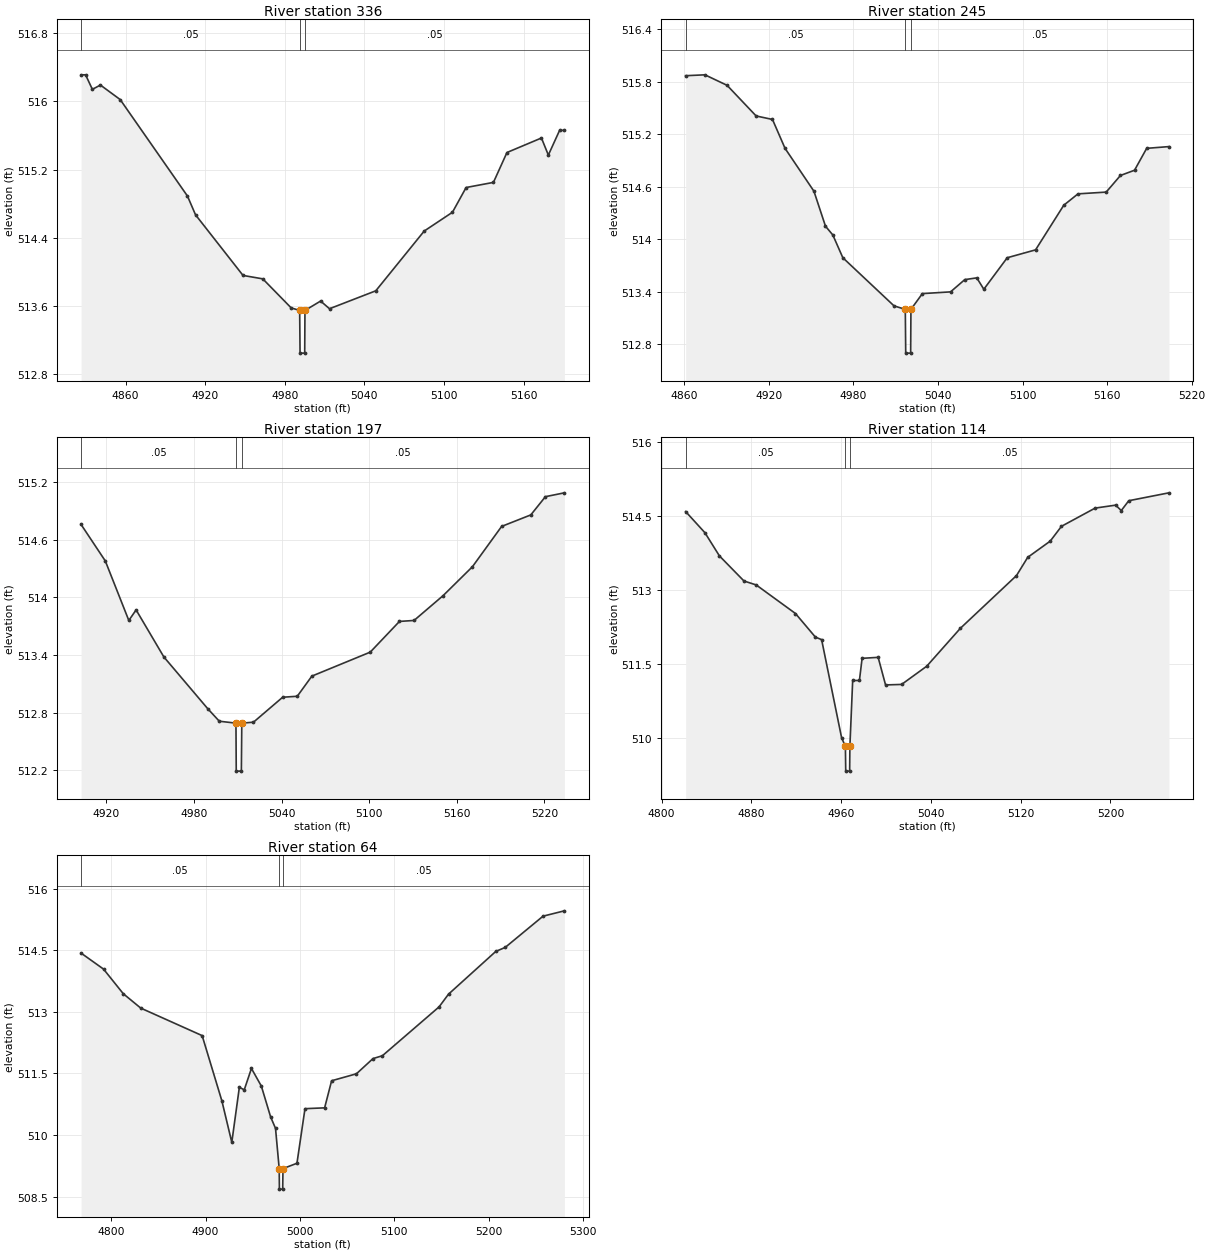
Type RM Length L Ch R = 1 ,336     ,91,91,91
BEGIN DESCRIPTION:
Lacy 046 3389
END DESCRIPTION:
XS GIS Cut Line= 3
      2766806.55      6897200.17       2766661.8      6897299.67
      2766616.94      6897483.01
#Sta/Elev= 26
  4826.4  516.31  4829.8  516.31  4834.9  516.14    4841  516.19  4855.9  516.02
  4906.6  514.89  4912.7  514.67  4948.5  513.96  4963.4  513.92  4984.8  513.58
  4991.2  513.55  4991.5  513.05    4995  513.05  4995.2  513.55    5007  513.66
  5013.7  513.57  5048.6  513.78  5085.1  514.48  5106.4   514.7  5116.7  514.99
  5137.3  515.05  5147.5   515.4  5173.5  515.57  5178.7  515.37  5187.2  515.66
  5190.8  515.66
#Mann= 3 ,-1 , 0
  4826.4     .05       0  4991.2     .04       0  4995.2     .05       0
Bank Sta=4991.2,4995.2
XS Rating Curve= 0 ,0
Exp/Cntr=0.3,0.1

Type RM Length L Ch R = 1 ,245     ,48,48,48
BEGIN DESCRIPTION:
Lacy 046 3388
END DESCRIPTION:
XS GIS Cut Line= 3
      2766734.67      6897202.97      2766596.67      6897234.85
      2766579.99      6897435.32
#Sta/Elev= 29
    4861  515.87  4874.7  515.88  4890.4  515.76    4911  515.41  4922.6  515.37
  4931.5  515.04    4952  514.55  4960.2  514.15  4965.4  514.05  4972.5  513.79
  5008.8  513.24  5016.8   513.2  5017.1   512.7  5020.6   512.7  5020.8   513.2
  5028.9  513.38  5048.9   513.4    5059  513.54  5067.5  513.56  5072.5  513.43
  5089.1  513.79  5109.2  513.88  5129.2  514.39  5139.3  514.52  5159.3  514.54
  5169.4  514.73  5179.4  514.79    5188  515.04  5203.8  515.06
#Mann= 3 ,-1 , 0
    4861     .05       0  5016.8     .04       0  5020.8     .05       0
Bank Sta=5016.8,5020.8
XS Rating Curve= 0 ,0
Exp/Cntr=0.3,0.1

Type RM Length L Ch R = 1 ,197     ,83,83,83
BEGIN DESCRIPTION:
Lacy 046 3445
END DESCRIPTION:
XS GIS Cut Line= 3
       2766662.6      6897193.65      2766565.33      6897200.46
      2766563.82      6897434.04
#Sta/Elev= 24
  4902.6  514.76  4919.2  514.38  4935.3  513.76  4940.3  513.87  4959.3  513.38
  4989.4  512.84  4997.3  512.71  5008.7  512.69  5008.9  512.19  5012.4  512.19
  5012.7  512.69  5020.7   512.7  5040.7  512.96  5050.7  512.97  5060.7  513.18
  5100.7  513.43  5120.7  513.75  5130.7  513.76  5150.7  514.02  5170.7  514.32
  5190.7  514.74  5210.7  514.86  5220.7  515.05  5233.7  515.09
#Mann= 3 ,-1 , 0
  4902.6     .05       0  5008.7     .05       0  5012.7     .05       0
Bank Sta=5008.7,5012.7
XS Rating Curve= 0 ,0
Exp/Cntr=0.3,0.1

Type RM Length L Ch R = 1 ,114     ,50,50,50
BEGIN DESCRIPTION:
Lacy 046 3387
END DESCRIPTION:
XS GIS Cut Line= 4
      2766663.52      6897184.45      2766524.01      6897122.42
      2766488.28      6897162.56      2766479.21      6897386.76
#Sta/Elev= 30
  4821.4  514.59  4838.6  514.16  4851.5  513.69  4873.4  513.18  4884.3   513.1
  4919.3  512.52  4937.1  512.04  4942.6  511.99  4960.4     510  4963.8  509.82
  4964.1  509.32  4967.6  509.32  4967.8  509.82  4970.3  511.16  4976.3  511.16
  4978.7  511.61    4993  511.63  4999.6  511.07  5013.9  511.08  5036.3  511.45
  5066.3  512.22  5116.3  513.29  5126.3  513.66  5146.4  513.99  5156.4  514.29
  5186.4  514.66  5204.7  514.72  5209.7  514.61  5216.4  514.81  5252.2  514.97
#Mann= 3 ,-1 , 0
  4821.4     .05       0  4963.8     .05       0  4967.8     .05       0
Bank Sta=4963.8,4967.8
XS Rating Curve= 0 ,0
Exp/Cntr=0.3,0.1

Type RM Length L Ch R = 1 ,64      ,0,0,0
BEGIN DESCRIPTION:
Lacy 046 3386
END DESCRIPTION:
XS GIS Cut Line= 4
      2766688.83      6897164.99      2766472.62      6897100.11
        2766455.       6897160.9      2766458.72      6897383.64
#Sta/Elev= 30
  4768.2  514.43    4792  514.04  4812.9  513.44  4831.4  513.09  4896.4  512.42
  4917.3  510.83  4927.8  509.82  4935.8  511.16    4941   511.1  4948.6  511.62
  4959.1  511.19  4968.9  510.44  4974.1  510.16    4978  509.18  4978.2  508.68
  4981.7  508.68    4982  509.18  4996.8  509.31  5005.3  510.64  5026.1  510.66
  5033.5  511.32  5059.8  511.49  5077.3  511.86  5087.3  511.93  5147.3  513.12
  5157.3  513.43  5207.3  514.47  5217.4  514.57  5257.4  515.33    5280  515.46
#Mann= 3 ,-1 , 0
  4768.2     .05       0    4978     .04       0    4982     .05       0
Bank Sta=4978,4982
XS Rating Curve= 0 ,0
Exp/Cntr=0.3,0.1

Chan Stop Cuts=-1
Use User Specified Reach Order=0
Composite Channel Slope=5