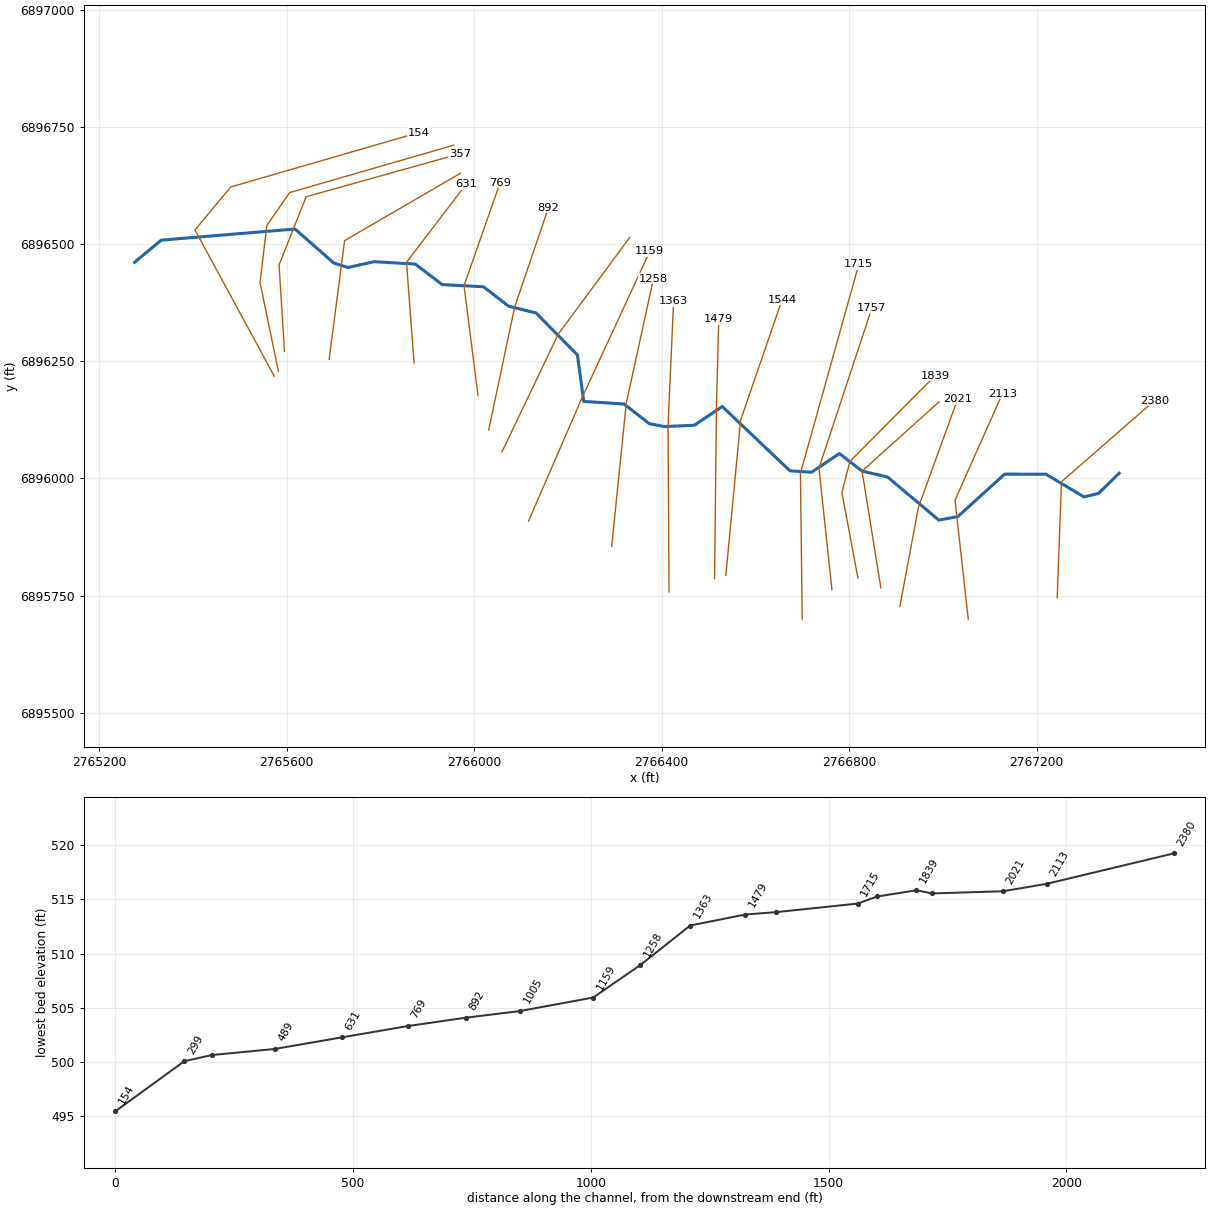
--- Lacy 047.prj (project) ---

Proj Title=Lacy 047 Base Level Engineering
Current Plan=p01
Default Exp/Contr=0.3,0.1
English Units
Geom File=g01
Flow File=f01
Plan File=p01
Y Axis Title=Elevation
X Axis Title(PF)=Main Channel Distance
X Axis Title(XS)=Station
BEGIN DESCRIPTION:
Lacy 047
END DESCRIPTION:
DSS Export Rating Curves= 0
DSS Export Rating Curve Sorted= 0
DSS Export Volume Flow Curves= 0
DXF OffsetX= 0
DXF OffsetY= 0
DXF ScaleX= 1
DXF ScaleY= 10

--- Lacy 047.p01 (plan) ---

Plan Title=Multiple Run
Short Identifier=Multiple
Geom File=g01
Flow File=f01
Subcritical Flow
K Sum by GR= 0
Std Step Tol= 0.01
Critical Tol= 0.01
Num of Std Step Trials= 20
Max Error Tol= 0.3
Flow Tol Ratio= 0.001
Split Flow NTrial= 30
Split Flow Tol= 0.02
Split Flow Ratio= 0.02
Log Output Level= 0
Friction Slope Method= 1
Unsteady Friction Slope Method= 2
Unsteady Bridges Friction Slope Method= 1
Parabolic Critical Depth
Global Vel Dist=  1 , 1 , 1
Global Log Level= 0
CheckData=True
Encroach Param= -1, 0, 0, 0
BEGIN DESCRIPTION:
Multiple Run
END DESCRIPTION:

--- Lacy 047.f01 (steady flow) ---

Flow Title=Multiple
Number of Profiles=7
Profile Names=10-year,25-year,50-year,1pct_min,100-year,1pct_plu,500-year
River Rch & RM= Lacy 047,Reach-1,2380
     132     160     181     103     205     408     261
Boundary for River Rch & Prof#=Lacy 047,Reach-1,1
Up Type=0
Dn Type=3
Dn Slope=0.005
Boundary for River Rch & Prof#=Lacy 047,Reach-1,2
Up Type=0
Dn Type=3
Dn Slope=0.005
Boundary for River Rch & Prof#=Lacy 047,Reach-1,3
Up Type=0
Dn Type=3
Dn Slope=0.005
Boundary for River Rch & Prof#=Lacy 047,Reach-1,4
Up Type=0
Dn Type=3
Dn Slope=0.005
Boundary for River Rch & Prof#=Lacy 047,Reach-1,5
Up Type=0
Dn Type=3
Dn Slope=0.005
Boundary for River Rch & Prof#=Lacy 047,Reach-1,6
Up Type=0
Dn Type=3
Dn Slope=0.005
Boundary for River Rch & Prof#=Lacy 047,Reach-1,7
Up Type=0
Dn Type=3
Dn Slope=0.005

--- Lacy 047.g01 (geometry) ---

Geom Title=Existing Conditions
Program Version=4.10

River Reach=Lacy 047        ,Reach-1
Reach XY= 30
        2767376.        6896011.      2767332.15      6895967.95
      2767300.95      6895960.39      2767220.04      6896008.82
      2767131.89      6896009.03      2767032.04      6895918.48
      2766991.36       6895910.9      2766882.04      6896002.86
      2766827.65      6896015.45      2766779.31      6896052.93
      2766719.95      6896012.98      2766673.71      6896016.12
      2766529.42       6896153.2      2766470.11      6896113.37
      2766405.96      6896110.42      2766373.69      6896116.68
      2766319.93       6896158.6      2766234.01      6896164.03
      2766220.45      6896263.38      2766132.08      6896352.87
      2766073.83      6896367.14      2766020.03      6896408.67
      2765931.97      6896413.35       2765874.4      6896457.14
      2765786.47      6896462.16      2765730.97      6896449.78
      2765700.67      6896459.42      2765618.22      6896531.86
      2765332.73      6896508.17        2765276.        6896461.

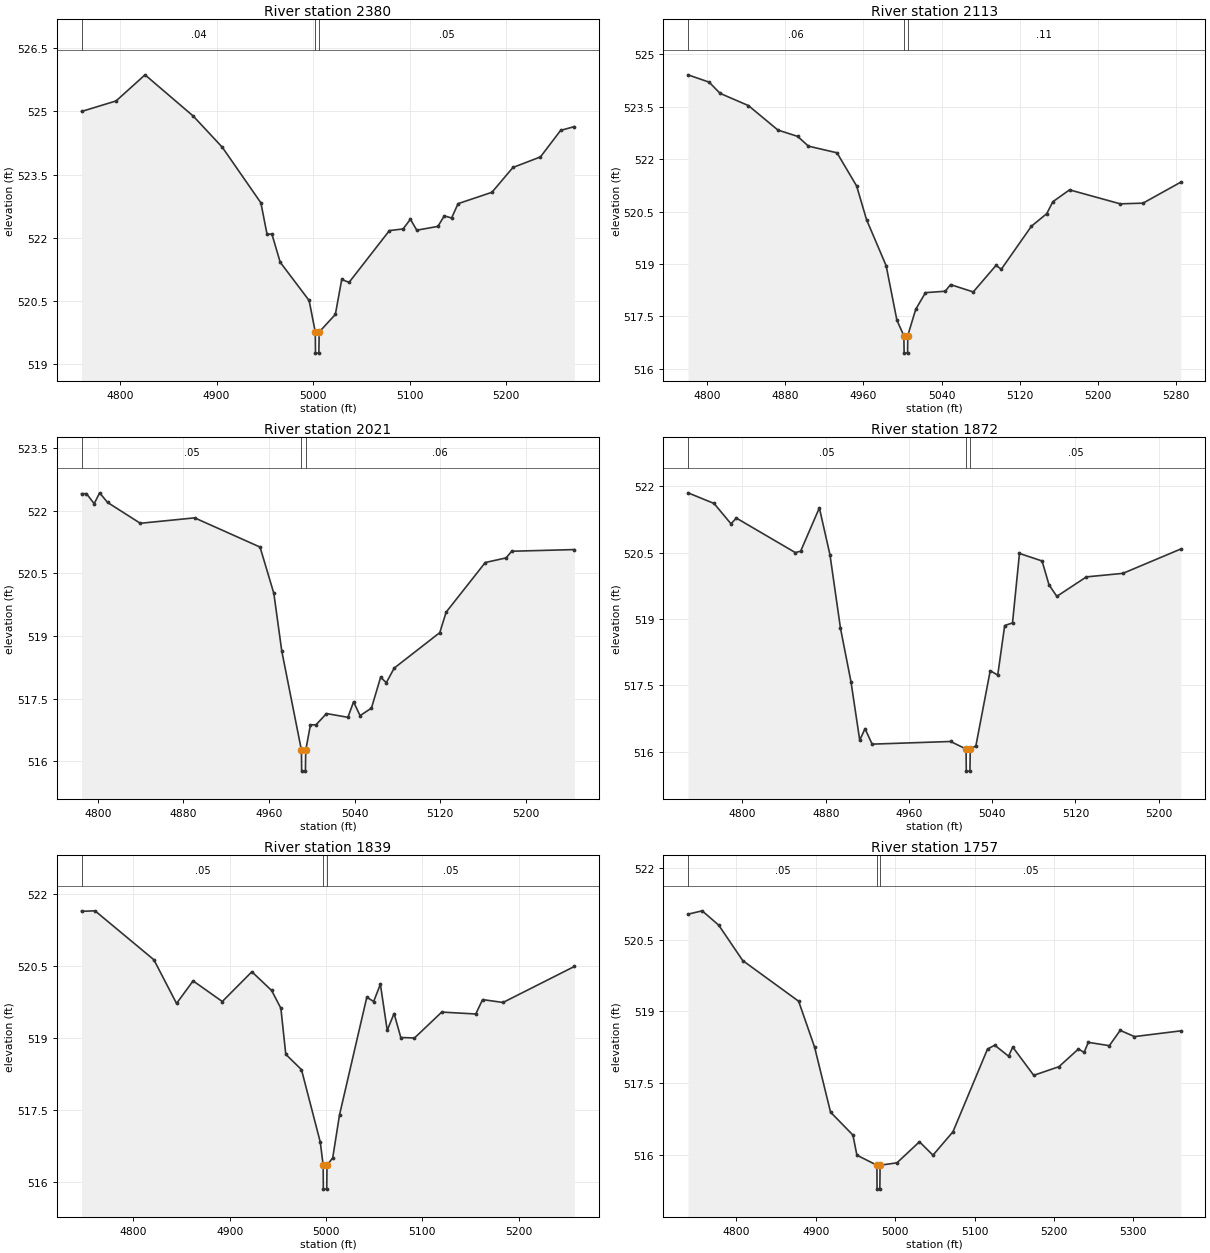
Type RM Length L Ch R = 1 ,2380    ,267,267,267
BEGIN DESCRIPTION:
Lacy 047 2747
END DESCRIPTION:
XS GIS Cut Line= 3
      2767243.95      6895745.23      2767252.96      6895992.67
      2767451.29      6896165.71
#Sta/Elev= 30
    4760     525  4795.8  525.25  4825.8  525.87  4875.8  524.89  4905.9  524.15
  4945.9  522.83  4952.3  522.08  4957.3  522.09  4965.9  521.42  4995.9  520.51
  5002.3  519.76  5002.5  519.26    5006  519.26  5006.3  519.76  5023.1  520.18
  5029.7  521.01  5037.3  520.94  5079.1  522.17  5093.3  522.21  5100.9  522.44
  5107.5  522.18  5129.4  522.27    5136  522.52  5143.6  522.47  5150.3  522.81
  5185.4  523.08  5207.2  523.67  5235.7  523.92  5256.6  524.55  5270.8  524.64
#Mann= 3 ,-1 , 0
    4760     .04       0  5002.3     .08       0  5006.3     .05       0
Bank Sta=5002.3,5006.3
XS Rating Curve= 0 ,0
Exp/Cntr=0.3,0.1

Type RM Length L Ch R = 1 ,2113    ,92,92,92
BEGIN DESCRIPTION:
Lacy 047 2749
END DESCRIPTION:
XS GIS Cut Line= 3
      2767054.19      6895699.54      2767025.93      6895953.42
      2767127.01       6896180.6
#Sta/Elev= 30
  4780.6  524.41  4802.2   524.2  4813.4  523.88  4842.4  523.53  4872.6  522.83
  4892.7  522.65  4903.8  522.37    4933  522.18  4953.1  521.23  4963.2  520.27
  4983.3  518.95  4994.3  517.39  5001.4  516.95  5001.7  516.45  5005.2  516.45
  5005.4  516.95  5013.5   517.7  5023.5  518.18  5043.7  518.22  5049.2  518.41
  5072.4   518.2  5095.7  518.96  5101.1  518.85  5131.9  520.08  5147.6  520.44
  5153.8  520.78  5170.9  521.12  5222.8  520.72  5246.1  520.74  5284.7  521.34
#Mann= 3 ,-1 , 0
  4780.6     .06       0  5001.4     .03       0  5005.4     .11       0
Bank Sta=5001.4,5005.4
XS Rating Curve= 0 ,0
Exp/Cntr=0.3,0.1

Type RM Length L Ch R = 1 ,2021    ,149,149,149
BEGIN DESCRIPTION:
Lacy 047 2746
END DESCRIPTION:
XS GIS Cut Line= 3
      2766908.31      6895727.08      2766947.97       6895938.6
      2767031.61       6896169.2
#Sta/Elev= 30
  4784.8  522.41  4789.4  522.41  4796.6  522.17  4801.7  522.43  4809.1   522.2
  4839.7   521.7  4890.5  521.83  4951.6  521.13  4964.5  520.02  4971.9  518.64
  4990.3  516.26  4990.5  515.76    4994  515.76  4994.3  516.26  4998.7  516.87
  5003.9  516.87  5013.7  517.14  5033.7  517.05    5039  517.42  5045.1  517.09
  5055.7  517.27  5064.3  518.01  5069.6  517.88    5077  518.23  5119.6  519.08
  5125.5  519.57  5162.1  520.76  5181.5  520.87  5186.8  521.03  5245.3  521.07
#Mann= 3 ,-1 , 0
  4784.8     .05       0  4990.3     .03       0  4994.3     .06       0
Bank Sta=4990.3,4994.3
XS Rating Curve= 0 ,0
Exp/Cntr=0.3,0.1

Type RM Length L Ch R = 1 ,1872    ,33,33,33
BEGIN DESCRIPTION:
Lacy 047 2745
END DESCRIPTION:
XS GIS Cut Line= 3
      2766867.75      6895766.36      2766827.65      6896015.45
      2766992.13      6896163.35
#Sta/Elev= 30
  4747.7  521.85  4772.7  521.61    4789  521.15  4794.1  521.28  4850.8   520.5
  4855.9  520.53  4873.9  521.51  4884.1  520.45  4894.2  518.79  4904.3  517.58
  4912.7  516.26  4917.8  516.52  4924.6  516.17    5000  516.23  5014.9  516.06
  5015.1  515.56  5018.6  515.56  5018.9  516.06  5024.3  516.13  5038.1  517.83
  5045.3  517.73    5052  518.85  5059.5  518.91  5066.2  520.48  5087.9  520.31
  5094.6  519.77  5102.1  519.51  5130.5  519.95  5165.6  520.03  5221.2  520.58
#Mann= 3 ,-1 , 0
  4747.7     .05       0  5014.9     .04       0  5018.9     .05       0
Bank Sta=5014.9,5018.9
XS Rating Curve= 0 ,0
Exp/Cntr=0.3,0.1

Type RM Length L Ch R = 1 ,1839    ,82,82,82
BEGIN DESCRIPTION:
Lacy 047 2744
END DESCRIPTION:
XS GIS Cut Line= 4
      2766818.83      6895787.22      2766784.63      6895969.55
       2766801.5      6896035.73      2766983.06      6896218.61
#Sta/Elev= 30
  4746.2  521.64  4760.2  521.65  4821.3  520.63  4844.8  519.72    4862  520.19
  4892.3  519.76    4923  520.38  4943.5  519.99  4953.1  519.62  4958.2  518.66
  4974.5  518.34    4994  516.83    4997  516.35  4997.2  515.85  5000.7  515.85
    5001  516.35  5006.9   516.5    5014   517.4  5042.3  519.85  5049.4  519.76
  5056.4  520.12  5063.5  519.16  5070.6  519.51  5077.6  519.01  5091.8     519
  5120.1  519.54  5155.4   519.5  5162.5   519.8  5183.7  519.74  5257.7  520.49
#Mann= 3 ,-1 , 0
  4746.2     .05       0    4997     .04       0    5001     .05       0
Bank Sta=4997,5001
XS Rating Curve= 0 ,0
Exp/Cntr=0.3,0.1

Type RM Length L Ch R = 1 ,1757    ,42,42,42
BEGIN DESCRIPTION:
Lacy 047 2743
END DESCRIPTION:
XS GIS Cut Line= 3
      2766763.34      6895762.48      2766735.67      6896021.91
      2766848.62      6896363.41
#Sta/Elev= 30
  4739.1  521.03  4756.9   521.1  4777.8   520.8    4808  520.06  4878.4  519.21
  4898.5  518.25  4918.6  516.89  4946.8  516.41  4951.8  515.99    4977  515.78
  4977.2  515.28  4980.7  515.28    4981  515.78  5002.2  515.83  5030.6  516.27
  5047.6  515.99  5072.8  516.48  5116.3  518.21  5125.4  518.29  5142.8  518.06
  5148.1  518.25  5174.5  517.66  5206.2  517.84  5230.8  518.21    5238  518.14
  5243.2  518.35  5269.7  518.28  5283.4   518.6  5301.4  518.47  5359.7  518.59
#Mann= 3 ,-1 , 0
  4739.1     .05       0    4977     .04       0    4981     .05       0
Bank Sta=4977,4981
XS Rating Curve= 0 ,0
Exp/Cntr=0.3,0.1

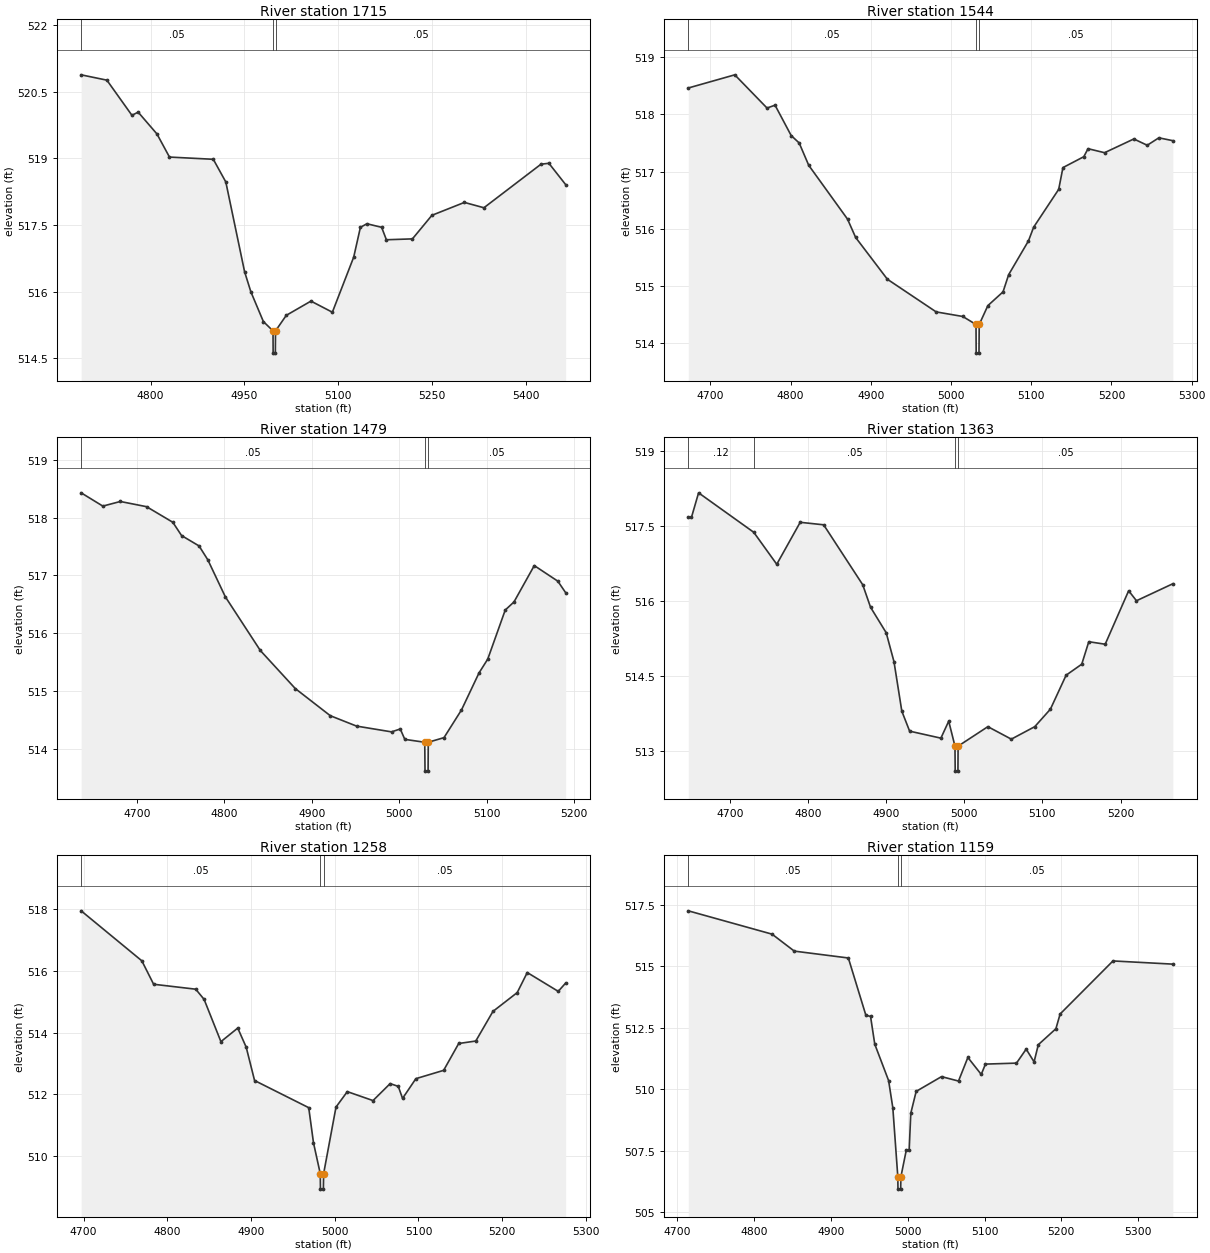
Type RM Length L Ch R = 1 ,1715    ,171,171,171
BEGIN DESCRIPTION:
Lacy 047 2742
END DESCRIPTION:
XS GIS Cut Line= 3
      2766699.98       6895699.9      2766696.16      6896010.68
      2766820.79      6896456.79
#Sta/Elev= 30
  4689.2  520.88  4730.3  520.76  4770.3  519.97  4780.3  520.04  4810.3  519.55
  4830.3  519.03  4900.3  518.98  4920.3  518.47  4950.3  516.45  4960.3     516
  4980.3  515.33  4995.7  515.12  4995.9  514.62  4999.4  514.62  4999.7  515.12
  5016.9  515.47  5056.3  515.79  5090.5  515.54  5124.6  516.78  5135.3  517.45
  5145.7  517.53  5169.2  517.45  5176.8  517.17  5218.4  517.19  5249.5  517.72
  5301.4  518.01  5332.6  517.89  5423.8  518.87  5436.4  518.89  5463.2  518.41
#Mann= 3 ,-1 , 0
  4689.2     .05       0  4995.7     .04       0  4999.7     .05       0
Bank Sta=4995.7,4999.7
XS Rating Curve= 0 ,0
Exp/Cntr=0.3,0.1

Type RM Length L Ch R = 1 ,1544    ,65,65,65
BEGIN DESCRIPTION:
Lacy 047 2734
END DESCRIPTION:
XS GIS Cut Line= 3
      2766537.08      6895793.28      2766568.53      6896123.98
      2766657.09      6896381.16
#Sta/Elev= 30
  4672.3  518.46  4730.3  518.69  4770.5  518.11  4780.5  518.16  4800.6  517.63
  4810.6   517.5  4822.5  517.11  4870.9  516.17    4881  515.85  4920.6  515.12
  4981.4  514.55  5014.6  514.47  5031.1  514.33  5031.3  513.83  5034.8  513.83
  5035.1  514.33  5045.9  514.66  5064.8   514.9  5071.8   515.2  5096.5  515.79
    5103  516.03  5134.2  516.69  5139.5  517.07  5165.5  517.26  5170.8   517.4
  5191.4  517.33  5227.9  517.57  5244.6  517.46  5259.1  517.59  5276.5  517.54
#Mann= 3 ,-1 , 0
  4672.3     .05       0  5031.1     .04       0  5035.1     .05       0
Bank Sta=5031.1,5035.1
XS Rating Curve= 0 ,0
Exp/Cntr=0.3,0.1

Type RM Length L Ch R = 1 ,1479    ,116,116,116
BEGIN DESCRIPTION:
Lacy 047 2733
END DESCRIPTION:
XS GIS Cut Line= 3
      2766513.06      6895786.23      2766517.12      6896156.48
        2766522.      6896340.04
#Sta/Elev= 29
  4636.3  518.43  4661.1   518.2  4681.1  518.28  4711.1  518.19  4741.1  517.92
  4751.1  517.69  4771.1  517.51  4781.1  517.27  4801.1  516.63  4841.1   515.7
  4881.1  515.04  4921.1  514.57  4951.1  514.39  4991.1  514.29  5001.1  514.34
  5006.3  514.16  5029.1  514.11  5029.4  513.61  5032.9  513.61  5033.1  514.11
  5051.1  514.19  5071.1  514.67  5091.1  515.31  5101.1  515.55  5121.1   516.4
  5131.1  516.54  5154.3  517.17  5181.2   516.9  5190.2   516.7
#Mann= 3 ,-1 , 0
  4636.3     .05       0  5029.1     .04       0  5033.1     .05       0
Bank Sta=5029.1,5033.1
XS Rating Curve= 0 ,0
Exp/Cntr=0.3,0.1

Type RM Length L Ch R = 1 ,1363    ,105,105,105
BEGIN DESCRIPTION:
Lacy 047 2730
END DESCRIPTION:
XS GIS Cut Line= 3
      2766415.86      6895757.78      2766413.75      6896111.07
      2766425.59      6896377.41
#Sta/Elev= 30
    4647  517.67  4651.1  517.67  4660.2  518.16  4730.8  517.37  4760.2  516.73
  4790.2  517.57  4820.2  517.52  4870.2  516.32  4880.2  515.87  4900.2  515.36
  4910.2  514.78  4920.2  513.79  4930.2  513.39  4970.2  513.25  4980.2  513.59
  4988.2  513.09  4988.5  512.59    4992  512.59  4992.2  513.09  5030.3  513.48
  5060.3  513.23  5090.3  513.48  5110.3  513.83  5130.4  514.51  5150.4  514.73
  5159.4  515.18  5180.4  515.13  5210.4   516.2  5220.4     516  5266.9  516.34
#Mann= 4 ,-1 , 0
    4647     .12       0  4730.8     .05       0  4988.2     .05       0
  4992.2     .05       0
Bank Sta=4988.2,4992.2
XS Rating Curve= 0 ,0
Exp/Cntr=0.3,0.1

Type RM Length L Ch R = 1 ,1258    ,99,99,99
BEGIN DESCRIPTION:
Lacy 047 2732
END DESCRIPTION:
XS GIS Cut Line= 3
      2766293.57      6895854.82      2766324.55      6896159.52
      2766382.63      6896425.89
#Sta/Elev= 30
    4697  517.95  4769.5  516.33  4783.6  515.57  4833.9  515.41  4843.9  515.08
    4864  513.71  4884.1  514.15  4894.2  513.53  4904.2  512.45  4968.9  511.57
  4974.6  510.43  4982.7  509.43  4982.9  508.93  4986.4  508.93  4986.7  509.43
  5001.5  511.59    5015  512.09  5045.7   511.8  5066.2  512.35  5075.9  512.26
    5081  511.87  5096.9  512.51  5130.1  512.78  5148.1  513.65  5168.5  513.73
    5189  514.69    5218   515.3    5230  515.95    5267  515.34  5275.9  515.61
#Mann= 3 ,-1 , 0
    4697     .05       0  4982.7     .05       0  4986.7     .05       0
Bank Sta=4982.7,4986.7
XS Rating Curve= 0 ,0
Exp/Cntr=0.3,0.1

Type RM Length L Ch R = 1 ,1159    ,154,154,154
BEGIN DESCRIPTION:
Lacy 047 2731
END DESCRIPTION:
XS GIS Cut Line= 3
      2766116.25      6895908.92      2766230.73       6896172.8
      2766374.86      6896484.22
#Sta/Elev= 30
  4714.3  517.26  4823.4  516.31  4852.3  515.62  4922.7  515.34  4945.5  513.01
  4951.6  512.96  4957.1  511.83  4975.1  510.35  4980.6  509.24  4987.1  506.43
  4987.3  505.93  4990.8  505.93  4991.1  506.43  4998.2  507.53  5001.9  507.53
    5004  509.02    5011  509.91    5044  510.51  5066.1  510.33  5078.3  511.29
  5095.7   510.6  5101.2  511.02  5141.6  511.06  5154.2  511.63  5164.5  511.11
    5170  511.81  5192.9  512.46  5198.4  513.06  5267.2  515.22  5345.1  515.09
#Mann= 3 ,-1 , 0
  4714.3     .05       0  4987.1     .05       0  4991.1     .05       0
Bank Sta=4987.1,4991.1
XS Rating Curve= 0 ,0
Exp/Cntr=0.3,0.1

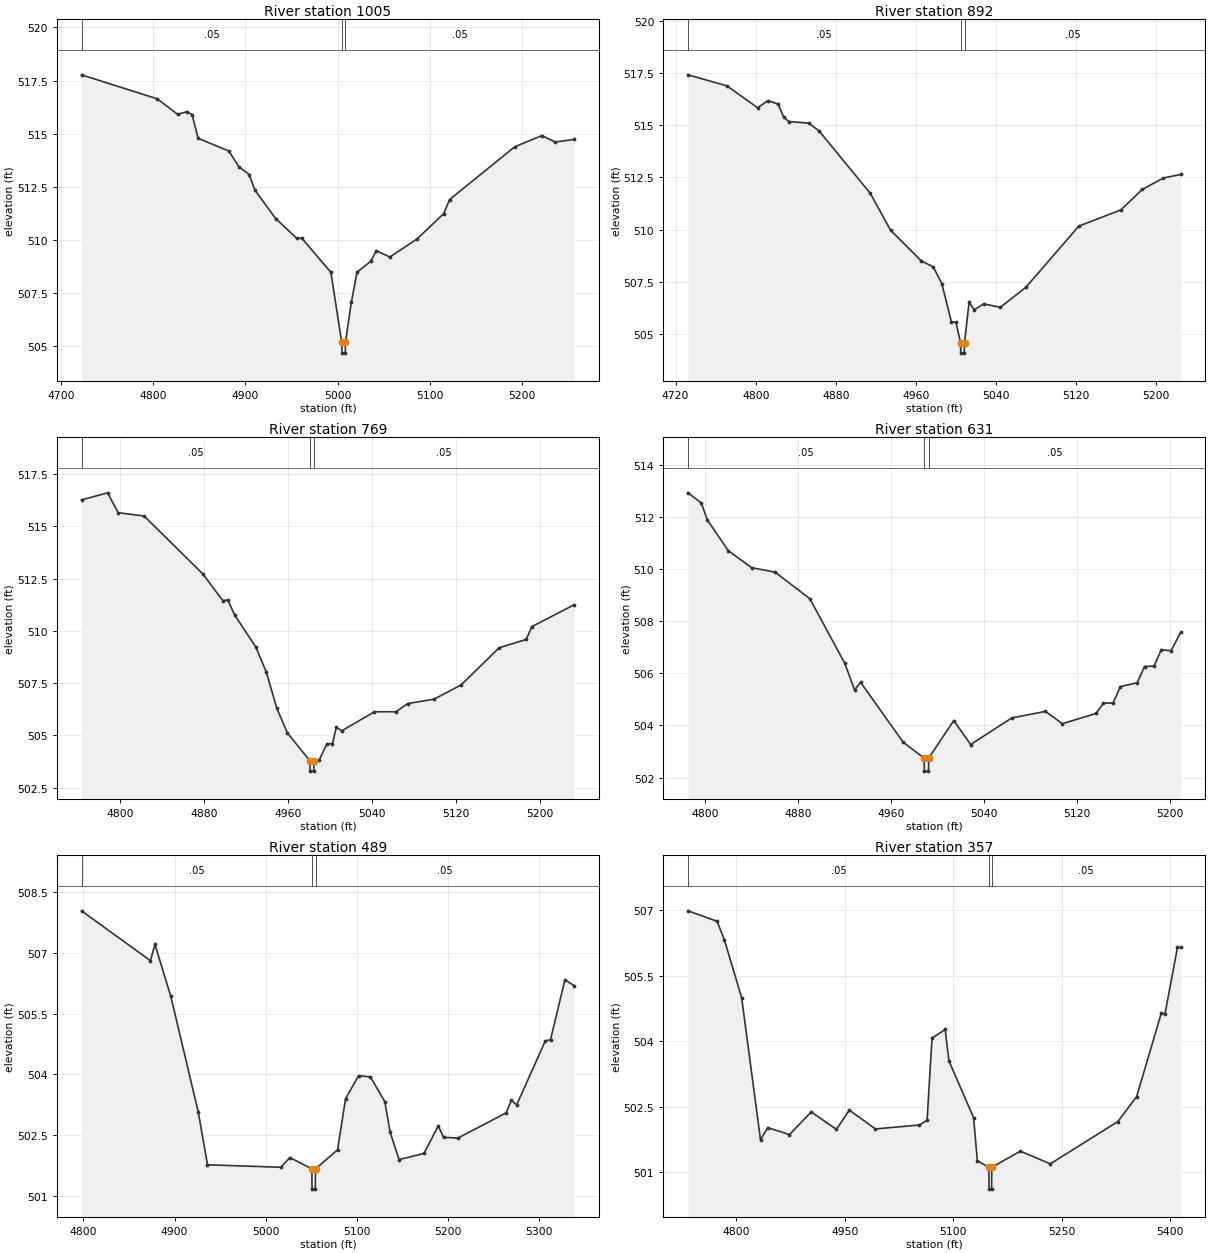
Type RM Length L Ch R = 1 ,1005    ,113,113,113
BEGIN DESCRIPTION:
Lacy 047 2741
END DESCRIPTION:
XS GIS Cut Line= 3
      2766059.78      6896056.86      2766179.45      6896307.45
      2766332.18      6896514.02
#Sta/Elev= 30
  4722.3  517.77  4804.5  516.64  4826.6  515.91  4836.7  516.04  4842.2   515.9
  4848.8  514.78    4882  514.19  4893.1  513.44  4904.2  513.08  4910.3  512.35
  4932.9  511.01  4955.6  510.09  4961.2  510.09  4992.8  508.48  5004.6  505.18
  5004.9  504.68  5008.4  504.68  5008.6  505.18    5015  507.08  5021.2  508.49
  5035.9  508.99  5042.1   509.5  5056.7   509.2    5086  510.04  5115.2  511.24
  5121.5   511.9  5192.4  514.39  5221.7  514.91  5236.3  514.61  5256.9  514.73
#Mann= 3 ,-1 , 0
  4722.3     .05       0  5004.6     .04       0  5008.6     .05       0
Bank Sta=5004.6,5008.6
XS Rating Curve= 0 ,0
Exp/Cntr=0.3,0.1

Type RM Length L Ch R = 1 ,892     ,123,123,123
BEGIN DESCRIPTION:
Lacy 047 2740
END DESCRIPTION:
XS GIS Cut Line= 3
      2766031.16      6896102.95      2766086.41      6896364.79
      2766158.64      6896577.46
#Sta/Elev= 30
  4732.4  517.42  4771.3  516.89  4801.9  515.84  4812.2  516.18  4822.4  516.02
    4828  515.39  4833.1  515.18    4853   515.1  4863.3  514.73  4914.4  511.74
  4934.8  509.96  4965.5  508.49  4977.3  508.21  4985.9  507.41  4995.5  505.56
    5000  505.56  5004.6  504.57  5004.8  504.07  5008.3  504.07  5008.6  504.57
  5013.1   506.5  5018.3  506.15  5027.7  506.43  5044.4  506.27  5069.9  507.23
  5122.7  510.16  5164.7  510.94  5186.1  511.92  5207.2  512.47  5224.6  512.64
#Mann= 3 ,-1 , 0
  4732.4     .05       0  5004.6     .05       0  5008.6     .05       0
Bank Sta=5004.6,5008.6
XS Rating Curve= 0 ,0
Exp/Cntr=0.3,0.1

Type RM Length L Ch R = 1 ,769     ,138,138,138
BEGIN DESCRIPTION:
Lacy 047 2739
END DESCRIPTION:
XS GIS Cut Line= 3
      2766008.45      6896176.36      2765978.62      6896410.87
      2766055.55      6896630.91
#Sta/Elev= 30
  4763.6  516.26  4788.4   516.6  4798.5  515.65  4823.2  515.49  4879.2  512.72
  4898.1  511.45  4903.1  511.47  4909.4  510.76  4929.6  509.23  4939.6  508.03
  4949.7  506.29  4959.8  505.11  4981.1  503.79  4981.3  503.29  4984.8  503.29
  4985.1  503.79    4990  503.82  4997.5   504.6  5002.7   504.6  5006.3  505.38
  5011.6  505.22  5042.7  506.13  5063.1  506.13  5074.3  506.52  5099.4  506.73
  5125.2  507.41  5161.5  509.19  5187.3  509.59  5192.6   510.2  5233.1  511.25
#Mann= 3 ,-1 , 0
  4763.6     .05       0  4981.1     .04       0  4985.1     .05       0
Bank Sta=4981.1,4985.1
XS Rating Curve= 0 ,0
Exp/Cntr=0.3,0.1

Type RM Length L Ch R = 1 ,631     ,142,142,142
BEGIN DESCRIPTION:
Lacy 047 2738
END DESCRIPTION:
XS GIS Cut Line= 3
      2765871.99      6896246.36       2765855.9      6896460.75
       2765982.8      6896627.06
#Sta/Elev= 30
    4785  512.92  4796.5  512.53  4801.5  511.89  4819.7   510.7  4839.8  510.05
  4859.9  509.88  4889.9  508.86    4920  506.38  4928.4  505.36  4933.5  505.66
  4970.2  503.36  4988.2  502.75  4988.5  502.25    4992  502.25  4992.2  502.75
  5013.8  504.19  5028.3  503.27  5063.7  504.29  5092.7  504.54  5107.3  504.07
  5136.3  504.46  5142.6  504.86  5150.9  504.86  5157.2  505.49  5171.7  505.64
    5178  506.26  5186.2  506.28  5192.5  506.91  5200.8  506.86  5209.2  507.58
#Mann= 3 ,-1 , 0
    4785     .05       0  4988.2     .04       0  4992.2     .05       0
Bank Sta=4988.2,4992.2
XS Rating Curve= 0 ,0
Exp/Cntr=0.3,0.1

Type RM Length L Ch R = 1 ,489     ,132,132,132
BEGIN DESCRIPTION:
Lacy 047 2737
END DESCRIPTION:
XS GIS Cut Line= 3
      2765690.87      6896253.82      2765723.86      6896507.14
      2765970.82      6896650.67
#Sta/Elev= 30
  4797.9  508.04  4873.5  506.81  4878.5  507.21  4895.9  505.93  4926.1  503.07
  4936.2  501.77  5016.9  501.71  5026.6  501.95  5050.8  501.67    5051  501.17
  5054.5  501.17  5054.8  501.67    5079  502.14  5087.8   503.4  5102.1  503.97
  5115.1  503.94  5130.9  503.33  5136.8  502.57  5146.6   501.9  5173.9  502.05
  5189.6  502.73  5195.4  502.45  5211.1  502.43    5264  503.05  5269.9  503.36
  5275.7  503.25  5307.2  504.83  5312.9  504.86  5328.7  506.34    5339  506.19
#Mann= 3 ,-1 , 0
  4797.9     .05       0  5050.8     .04       0  5054.8     .05       0
Bank Sta=5050.8,5054.8
XS Rating Curve= 0 ,0
Exp/Cntr=0.3,0.1

Type RM Length L Ch R = 1 ,357     ,58,58,58
BEGIN DESCRIPTION:
Lacy 047 2736
END DESCRIPTION:
XS GIS Cut Line= 4
      2765595.56      6896270.91      2765584.04      6896455.25
      2765641.84      6896600.74       2765969.8      6896692.49
#Sta/Elev= 30
  4733.2  506.99  4773.4  506.75  4783.4  506.33  4807.4     505  4833.5  501.74
  4843.5  502.02  4873.6  501.86  4903.6  502.38  4938.5  501.98  4956.4  502.42
  4992.5  501.99  5053.2  502.08    5064  502.19  5070.8  504.07    5089  504.27
  5094.2  503.55  5128.3  502.25  5133.5  501.26  5149.5  501.11  5149.7  500.61
  5153.2  500.61  5153.5  501.11    5193  501.48  5234.5  501.19    5328  502.16
  5353.9  502.73    5388  504.64  5393.2  504.63  5410.4  506.15    5415  506.15
#Mann= 3 ,-1 , 0
  4733.2     .05       0  5149.5     .05       0  5153.5     .05       0
Bank Sta=5149.5,5153.5
XS Rating Curve= 0 ,0
Exp/Cntr=0.3,0.1

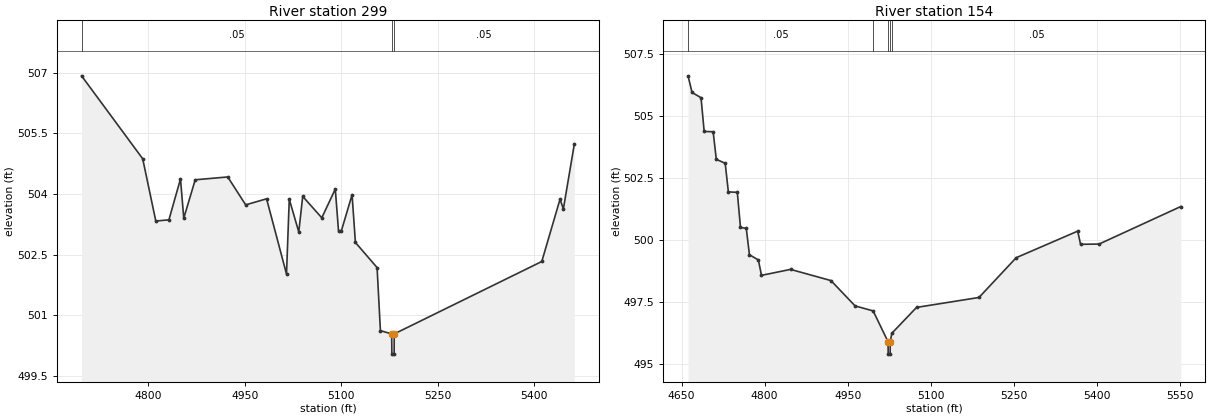
Type RM Length L Ch R = 1 ,299     ,145,145,145
BEGIN DESCRIPTION:
Lacy 047 3455
END DESCRIPTION:
XS GIS Cut Line= 5
      2765582.73      6896227.88      2765543.47       6896417.5
      2765557.77        6896539.      2765606.75      6896609.64
      2765956.98      6896710.82
#Sta/Elev= 30
  4696.1  506.92  4791.2  504.87  4811.6  503.33    4832  503.36    4850  504.37
  4855.1   503.4  4872.9  504.35  4923.5  504.42  4951.4  503.73  4983.9  503.88
  5014.9  502.02  5019.2  503.87    5034  503.06  5040.1  503.94  5069.8  503.41
  5090.8  504.12  5095.8  503.09  5100.3  503.09  5116.9  503.98  5122.1   502.8
  5155.8  502.18    5161  500.62  5178.5  500.54  5178.8  500.04  5182.3  500.04
  5182.5  500.54    5412  502.33  5440.4  503.87  5445.6  503.63  5462.6  505.23
#Mann= 3 ,-1 , 0
  4696.1     .05       0  5178.5     .04       0  5182.5     .05       0
Bank Sta=5178.5,5182.5
XS Rating Curve= 0 ,0
Exp/Cntr=0.3,0.1

Type RM Length L Ch R = 1 ,154     ,0,0,0
BEGIN DESCRIPTION:
Lacy 047 3457
END DESCRIPTION:
XS GIS Cut Line= 4
      2765573.73      6896218.15      2765404.67      6896529.79
       2765480.8      6896621.51       2765881.2      6896737.49
#Sta/Elev= 30
  4661.5  506.61  4668.8  505.94    4685  505.73  4690.7  504.37  4706.9  504.36
  4712.6  503.25  4728.7  503.09  4734.4  501.94  4750.6  501.92  4756.3  500.51
  4766.8  500.47  4772.5  499.41  4788.6   499.2  4794.3  498.58  4846.8  498.82
  4919.8  498.37  4963.5  497.35  4996.1  497.15    5023  495.91  5023.3  495.41
  5026.8  495.41    5027  495.91  5029.9  496.25  5074.5  497.29  5187.4  497.69
  5254.6  499.29  5365.8  500.36    5371  499.83  5404.5  499.84  5552.1  501.35
#Mann= 5 ,-1 , 0
  4661.5     .05       0  4996.1     .12       0    5023     .07       0
    5027     .12       0  5029.9     .05       0
Bank Sta=5023,5027
XS Rating Curve= 0 ,0
Exp/Cntr=0.3,0.1

Chan Stop Cuts=-1
Use User Specified Reach Order=0
Composite Channel Slope=5