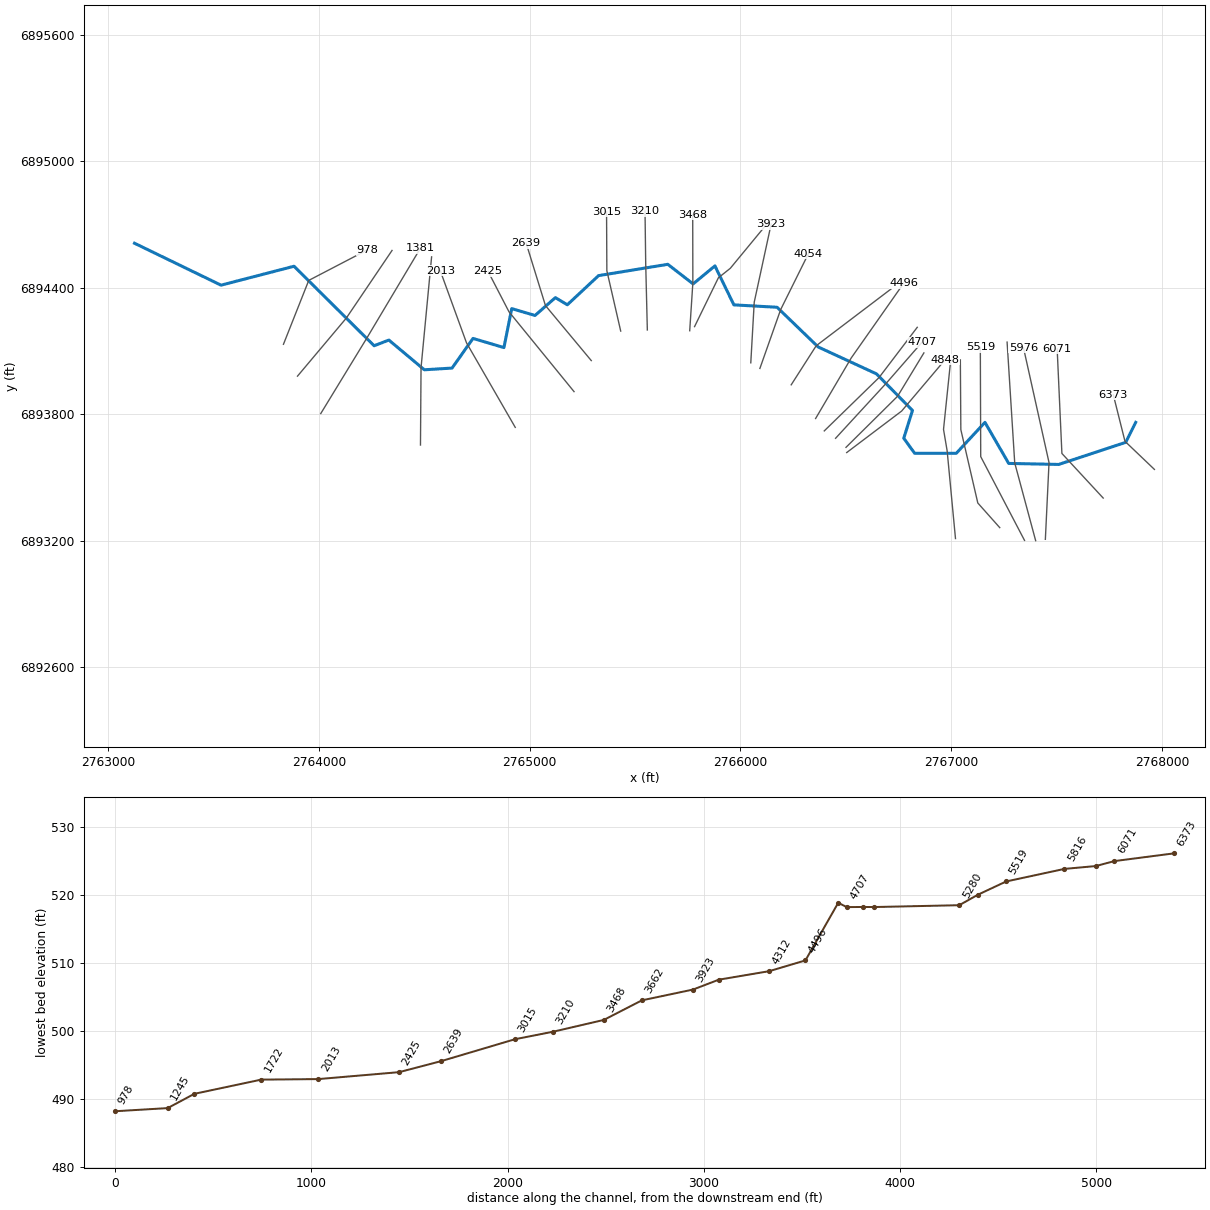
--- Lacy 048.prj (project) ---

Proj Title=Lacy 048 Base Level Engineering
Current Plan=p01
Default Exp/Contr=0.3,0.1
English Units
Geom File=g01
Flow File=f01
Plan File=p01
BEGIN DESCRIPTION:
Lacy 048
END DESCRIPTION:

--- Lacy 048.p01 (plan) ---

Plan Title=Multiple Run
Short Identifier=Multiple
Geom File=g01
Flow File=f01
Subcritical Flow
K Sum by GR= 0
Std Step Tol= 0.01
Critical Tol= 0.01
Num of Std Step Trials= 20
Max Error Tol= 0.3
Flow Tol Ratio= 0.001
Split Flow NTrial= 30
Split Flow Tol= 0.02
Split Flow Ratio= 0.02
Log Output Level= 0
Friction Slope Method= 1
Unsteady Friction Slope Method= 2
Unsteady Bridges Friction Slope Method= 1
Parabolic Critical Depth
Global Vel Dist=  1 , 1 , 1
Global Log Level= 0
CheckData=True
Encroach Param= -1, 0, 0, 0
BEGIN DESCRIPTION:
Multiple Run
END DESCRIPTION:

--- Lacy 048.f01 (steady flow) ---

Flow Title=Multiple
Number of Profiles=7
Profile Names=10-year,25-year,50-year,1pct_min,100-year,1pct_plu,500-year
River Rch & RM= Lacy 048,Reach-1,6373
     239     302     350     203     404     806     538
Boundary for River Rch & Prof#=Lacy 048,Reach-1,1
Up Type=0
Dn Type=3
Dn Slope=0.005
Boundary for River Rch & Prof#=Lacy 048,Reach-1,2
Up Type=0
Dn Type=3
Dn Slope=0.005
Boundary for River Rch & Prof#=Lacy 048,Reach-1,3
Up Type=0
Dn Type=3
Dn Slope=0.005
Boundary for River Rch & Prof#=Lacy 048,Reach-1,4
Up Type=0
Dn Type=3
Dn Slope=0.005
Boundary for River Rch & Prof#=Lacy 048,Reach-1,5
Up Type=0
Dn Type=3
Dn Slope=0.005
Boundary for River Rch & Prof#=Lacy 048,Reach-1,6
Up Type=0
Dn Type=3
Dn Slope=0.005
Boundary for River Rch & Prof#=Lacy 048,Reach-1,7
Up Type=0
Dn Type=3
Dn Slope=0.005

--- Lacy 048.g01 (geometry) ---

Geom Title=Existing Conditions

River Reach=Lacy 048,Reach-1
Reach XY= 30
      2767876.00      6893761.00      2767828.66      6893666.33
      2767510.78      6893561.52      2767273.26      6893566.34
      2767160.72      6893761.19      2767024.75      6893614.45
      2766827.22      6893614.43      2766775.47      6893685.87
      2766816.87      6893817.74      2766646.09      6893991.21
      2766369.55      6894118.75      2766174.45      6894307.25
      2765969.48      6894318.68      2765879.62      6894503.51
      2765776.01      6894418.11      2765656.02      6894511.04
      2765327.50      6894457.39      2765179.33      6894319.00
      2765122.67      6894352.97      2765026.09      6894268.37
      2764915.59      6894300.80      2764878.62      6894115.99
      2764731.86      6894159.45      2764632.47      6894018.69
      2764500.89      6894010.68      2764332.67      6894151.70
      2764262.67      6894124.65      2763882.74      6894501.87
      2763536.44      6894412.05      2763126.00      6894611.00

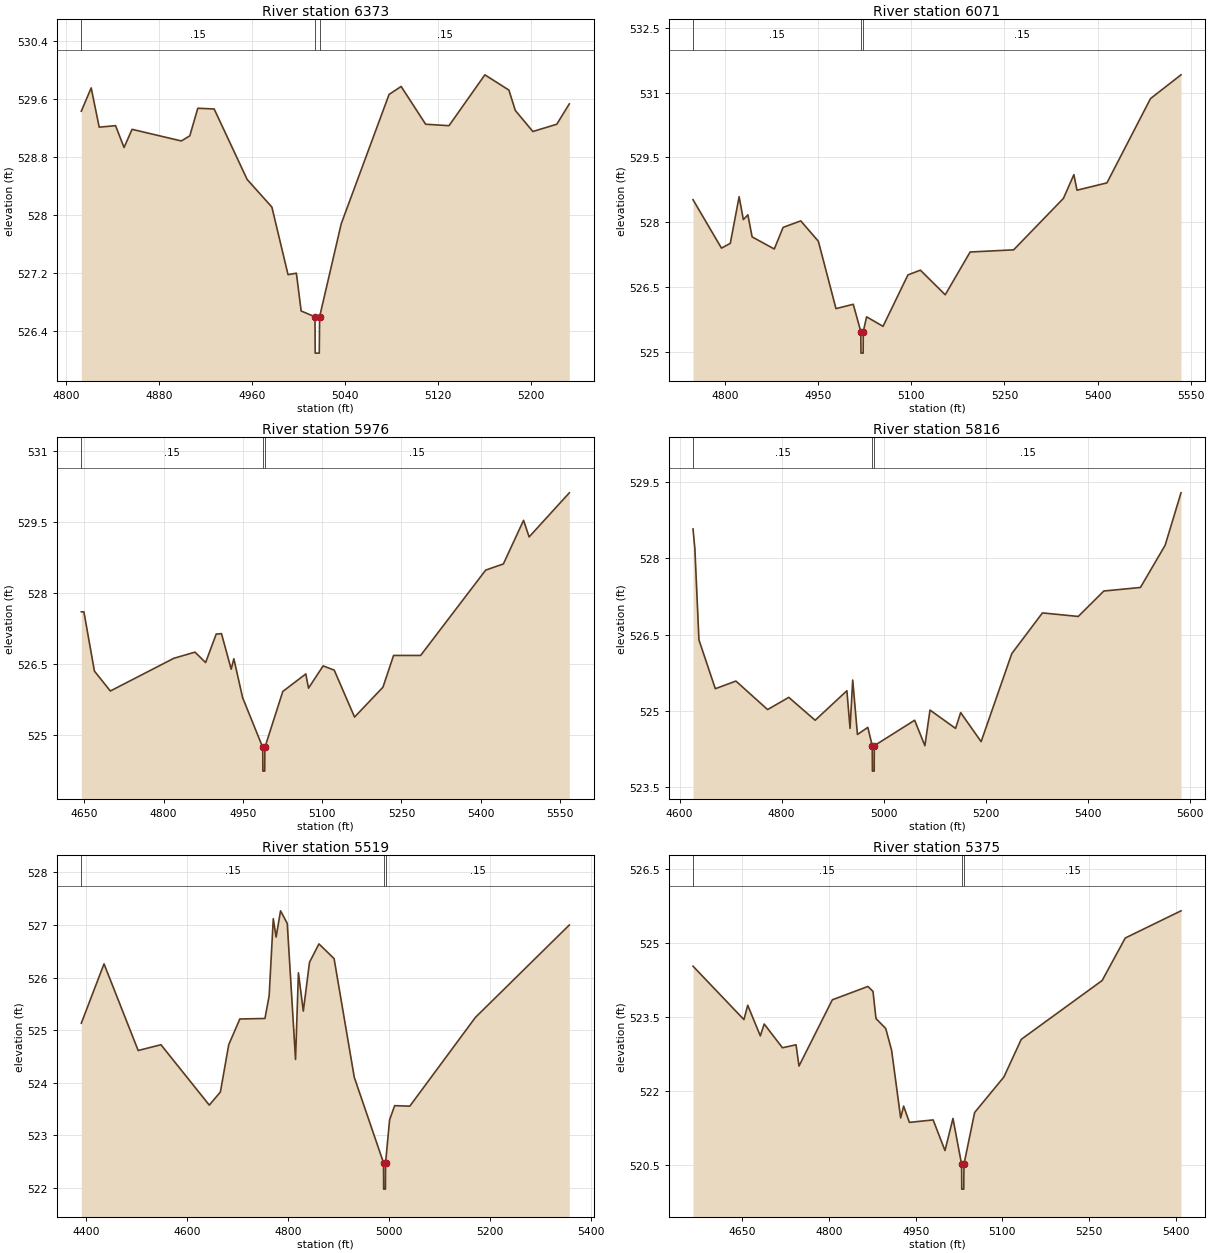
Type RM Length L Ch R = 1,6373,302,302,302
BEGIN DESCRIPTION:
Lacy 048 2722
END DESCRIPTION:
XS GIS Cut Line= 3
      2767964.73      6893537.88      2767825.06      6893671.22
      2767769.76      6893891.48
#Sta/Elev= 30
  4813.0  529.43  4821.5  529.75  4828.4  529.21  4842.5  529.23  4849.8  528.93
  4856.7  529.18  4899.1  529.02  4906.4  529.09  4913.3  529.47  4927.4  529.46
  4955.8  528.49  4977.1  528.11  4991.0  527.18  4998.2  527.20  5002.3  526.68
  5014.2  526.60  5014.4  526.10  5017.9  526.10  5018.2  526.60  5036.8  527.88
  5078.0  529.66  5088.4  529.77  5109.5  529.25  5129.6  529.23  5160.5  529.93
  5181.2  529.72  5186.7  529.44  5201.8  529.15  5222.4  529.25  5233.2  529.53
#Mann=3,-1,0
  4813.0    0.15       0  5014.2    0.05       0  5018.2    0.15       0
Bank Sta=5014.2,5018.2
Exp/Cntr=0.3,0.1

Type RM Length L Ch R = 1,6071,95,95,95
BEGIN DESCRIPTION:
Lacy 048 3471
END DESCRIPTION:
XS GIS Cut Line= 3
      2767721.71      6893401.95      2767525.79      6893613.60
      2767503.27      6894110.08
#Sta/Elev= 30
  4748.8  528.52  4794.6  527.40  4808.8  527.51  4823.0  528.59  4829.8  528.06
  4837.1  528.17  4843.9  527.66  4879.6  527.38  4893.8  527.88  4922.2  528.03
  4950.5  527.56  4978.9  526.00  5006.7  526.10  5018.8  525.47  5019.1  524.97
  5022.6  524.97  5022.8  525.47  5028.2  525.81  5054.6  525.59  5094.7  526.78
  5114.7  526.89  5154.7  526.32  5194.8  527.31  5264.8  527.36  5344.9  528.55
  5361.8  529.10  5366.8  528.74  5415.0  528.91  5485.1  530.86  5534.2  531.41
#Mann=3,-1,0
  4748.8    0.15       0  5018.8    0.05       0  5022.8    0.15       0
Bank Sta=5018.8,5022.8
Exp/Cntr=0.3,0.1

Type RM Length L Ch R = 1,5976,160,160,160
BEGIN DESCRIPTION:
Lacy 048 2719
END DESCRIPTION:
XS GIS Cut Line= 3
      2767447.30      6893206.20      2767464.71      6893570.28
      2767343.43      6894115.46
#Sta/Elev= 30
  4644.5  527.60  4649.4  527.60  4669.3  526.35  4699.4  525.93  4819.5  526.62
  4859.5  526.75  4879.6  526.53  4899.6  527.13  4909.6  527.14  4928.0  526.39
  4933.0  526.61  4949.6  525.79  4987.7  524.74  4987.9  524.24  4991.4  524.24
  4991.7  524.74  5025.6  525.92  5069.1  526.29  5074.2  525.99  5101.9  526.46
  5122.9  526.37  5161.3  525.38  5215.0  526.01  5235.1  526.68  5286.3  526.68
  5409.3  528.48  5442.8  528.61  5481.0  529.53  5491.5  529.18  5567.5  530.11
#Mann=3,-1,0
  4644.5    0.15       0  4987.7    0.05       0  4991.7    0.15       0
Bank Sta=4987.7,4991.7
Exp/Cntr=0.3,0.1

Type RM Length L Ch R = 1,5816,297,297,297
BEGIN DESCRIPTION:
Lacy 048 2721
END DESCRIPTION:
XS GIS Cut Line= 3
      2767401.26      6893199.79      2767301.93      6893568.86
      2767265.78      6894142.02
#Sta/Elev= 30
  4626.3  528.58  4630.0  528.18  4637.9  526.40  4670.0  525.44  4710.4  525.59
  4772.5  525.03  4814.0  525.27  4865.7  524.82  4927.9  525.40  4934.1  524.66
  4939.3  525.61  4948.6  524.54  4968.9  524.68  4977.6  524.32  4977.9  523.82
  4981.4  523.82  4981.6  524.32  5060.7  524.82  5080.8  524.32  5090.8  525.02
  5140.9  524.66  5150.9  524.97  5191.0  524.40  5251.1  526.13  5311.2  526.93
  5381.4  526.86  5431.5  527.36  5503.3  527.43  5551.7  528.26  5582.8  529.29
#Mann=3,-1,0
  4626.3    0.15       0  4977.6    0.05       0  4981.6    0.15       0
Bank Sta=4977.6,4981.6
Exp/Cntr=0.3,0.1

Type RM Length L Ch R = 1,5519,144,144,144
BEGIN DESCRIPTION:
Lacy 048 2720
END DESCRIPTION:
XS GIS Cut Line= 3
      2767348.40      6893201.15      2767140.59      6893598.65
      2767138.77      6894117.11
#Sta/Elev= 30
  4390.9  525.13  4435.9  526.26  4503.6  524.61  4548.7  524.72  4644.5  523.57
  4666.5  523.82  4683.0  524.72  4705.0  525.21  4754.8  525.22  4763.1  525.65
  4771.3  527.12  4776.9  526.77  4785.7  527.27  4799.0  527.03  4815.4  524.44
  4821.1  526.09  4830.8  525.36  4843.1  526.29  4861.8  526.64  4891.8  526.36
  4931.8  524.10  4989.8  522.47  4990.0  521.97  4993.5  521.97  4993.8  522.47
  5001.8  523.29  5011.8  523.56  5041.8  523.55  5171.8  525.24  5357.9  527.00
#Mann=3,-1,0
  4390.9    0.15       0  4989.8    0.05       0  4993.8    0.15       0
Bank Sta=4989.8,4993.8
Exp/Cntr=0.3,0.1

Type RM Length L Ch R = 1,5375,95,95,95
BEGIN DESCRIPTION:
Lacy 048 3470
END DESCRIPTION:
XS GIS Cut Line= 4
      2767230.85      6893261.70      2767126.77      6893378.61
      2767046.32      6893726.46      2767043.99      6894057.49
#Sta/Elev= 30
  4564.7  524.53  4652.8  523.45  4659.4  523.74  4681.2  523.12  4687.9  523.36
  4719.5  522.88  4743.0  522.94  4748.1  522.51  4805.8  523.85  4867.4  524.12
  4876.2  524.02  4881.4  523.47  4898.2  523.27  4908.4  522.83  4924.1  521.46
  4929.2  521.70  4939.2  521.37  4980.3  521.42  5000.8  520.80  5014.6  521.45
  5029.6  520.52  5029.8  520.02  5033.3  520.02  5033.6  520.52  5052.1  521.57
  5102.8  522.29  5132.8  523.05  5272.8  524.24  5312.8  525.10  5409.3  525.65
#Mann=3,-1,0
  4564.7    0.15       0  5029.6    0.05       0  5033.6    0.15       0
Bank Sta=5029.6,5033.6
Exp/Cntr=0.3,0.1

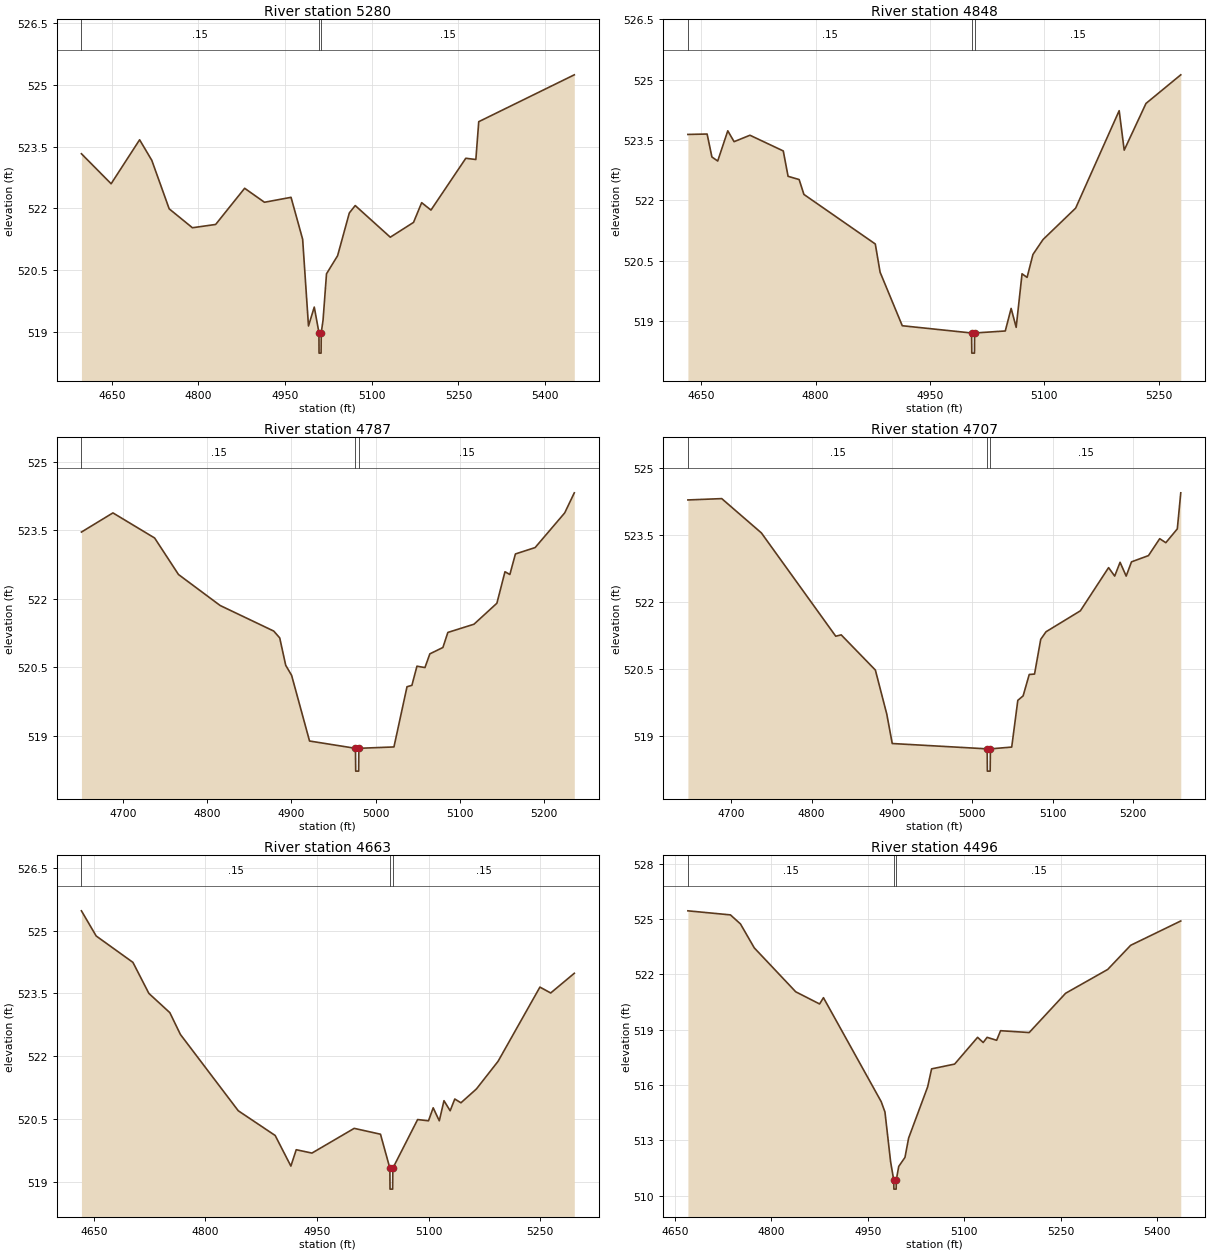
Type RM Length L Ch R = 1,5280,432,432,432
BEGIN DESCRIPTION:
Lacy 048 3469
END DESCRIPTION:
XS GIS Cut Line= 4
      2767020.93      6893209.79      2766981.32      6893626.14
      2766964.14      6893727.89      2766998.32      6894057.80
#Sta/Elev= 30
  4597.5  523.33  4648.9  522.60  4698.2  523.67  4719.3  523.17  4749.4  521.99
  4789.6  521.53  4829.8  521.61  4880.0  522.49  4914.3  522.15  4960.3  522.27
  4980.4  521.25  4990.5  519.14  5000.5  519.60  5008.6  518.98  5008.8  518.48
  5012.3  518.48  5012.6  518.98  5015.7  519.28  5021.7  520.41  5040.9  520.85
  5061.2  521.89  5071.4  522.07  5132.1  521.30  5172.3  521.66  5186.4  522.14
  5202.5  521.96  5262.8  523.22  5280.2  523.19  5285.2  524.11  5450.6  525.25
#Mann=3,-1,0
  4597.5    0.15       0  5008.6    0.05       0  5012.6    0.15       0
Bank Sta=5008.6,5012.6
Exp/Cntr=0.3,0.1

Type RM Length L Ch R = 1,4848,61,61,61
BEGIN DESCRIPTION:
Lacy 048 3468
END DESCRIPTION:
XS GIS Cut Line= 3
      2766504.83      6893617.85      2766765.46      6893814.78
      2766972.12      6894058.88
#Sta/Elev= 30
  4632.4  523.64  4657.6  523.65  4663.9  523.08  4671.5  522.98  4684.7  523.73
  4693.0  523.46  4713.8  523.62  4757.5  523.23  4763.8  522.60  4778.3  522.52
  4784.6  522.15  4878.2  520.92  4884.5  520.22  4913.6  518.89  5004.5  518.71
  5004.8  518.21  5008.3  518.21  5008.5  518.71  5048.7  518.76  5056.4  519.32
  5063.0  518.85  5070.7  520.18  5077.3  520.09  5085.0  520.66  5098.2  521.03
  5141.0  521.81  5198.1  524.23  5204.7  523.25  5233.3  524.41  5278.9  525.12
#Mann=3,-1,0
  4632.4    0.15       0  5004.5    0.05       0  5008.5    0.15       0
Bank Sta=5004.5,5008.5
Exp/Cntr=0.3,0.1

Type RM Length L Ch R = 1,4787,80,80,80
BEGIN DESCRIPTION:
Lacy 048 2714
END DESCRIPTION:
XS GIS Cut Line= 3
      2766501.47      6893642.63      2766746.30      6893885.06
      2766871.02      6894090.75
#Sta/Elev= 30
  4650.8  523.46  4688.2  523.88  4737.7  523.33  4766.0  522.53  4815.5  521.85
  4879.1  521.29  4886.2  521.14  4893.3  520.54  4900.3  520.32  4921.6  518.88
  4976.1  518.72  4976.4  518.22  4979.9  518.22  4980.1  518.72  5021.8  518.75
  5037.3  520.07  5043.1  520.10  5049.1  520.52  5058.6  520.49  5064.4  520.79
  5079.9  520.93  5085.8  521.26  5116.8  521.44  5144.0  521.90  5153.6  522.59
  5159.4  522.53  5166.0  522.98  5189.4  523.12  5224.5  523.88  5235.9  524.32
#Mann=3,-1,0
  4650.8    0.15       0  4976.1    0.05       0  4980.1    0.15       0
Bank Sta=4976.1,4980.1
Exp/Cntr=0.3,0.1

Type RM Length L Ch R = 1,4707,44,44,44
BEGIN DESCRIPTION:
Lacy 048 2715
END DESCRIPTION:
XS GIS Cut Line= 3
      2766452.01      6893685.57      2766694.13      6893948.72
      2766862.07      6894141.28
#Sta/Elev= 30
  4646.2  524.29  4688.3  524.32  4737.6  523.55  4830.1  521.23  4836.9  521.26
  4879.4  520.47  4893.6  519.48  4900.4  518.82  5018.5  518.70  5018.7  518.20
  5022.2  518.20  5022.5  518.70  5049.0  518.74  5056.6  519.79  5063.2  519.89
  5070.8  520.37  5077.4  520.38  5085.1  521.16  5091.7  521.33  5134.4  521.80
  5169.5  522.77  5177.1  522.58  5183.8  522.89  5191.4  522.58  5198.0  522.90
  5219.1  523.04  5233.1  523.42  5240.7  523.33  5255.0  523.64  5259.3  524.45
#Mann=3,-1,0
  4646.2    0.15       0  5018.5    0.05       0  5022.5    0.15       0
Bank Sta=5018.5,5022.5
Exp/Cntr=0.3,0.1

Type RM Length L Ch R = 1,4663,167,167,167
BEGIN DESCRIPTION:
Lacy 048 2716
END DESCRIPTION:
XS GIS Cut Line= 3
      2766398.36      6893720.64      2766658.31      6893973.81
      2766839.46      6894212.11
#Sta/Elev= 30
  4633.4  525.47  4653.2  524.87  4702.6  524.24  4724.0  523.50  4752.2  523.04
  4766.4  522.52  4844.1  520.70  4893.7  520.11  4914.8  519.38  4922.0  519.77
  4943.1  519.69  4999.9  520.28  5035.2  520.14  5047.8  519.33  5048.0  518.83
  5051.5  518.83  5051.8  519.33  5085.1  520.49  5099.7  520.46  5106.0  520.77
  5114.2  520.46  5120.5  520.94  5128.8  520.70  5135.0  520.98  5143.3  520.89
  5164.1  521.22  5193.2  521.88  5249.4  523.65  5263.9  523.51  5295.6  523.98
#Mann=3,-1,0
  4633.4    0.15       0  5047.8    0.05       0  5051.8    0.15       0
Bank Sta=5047.8,5051.8
Exp/Cntr=0.3,0.1

Type RM Length L Ch R = 1,4496,184,184,184
BEGIN DESCRIPTION:
Lacy 048 2717
END DESCRIPTION:
XS GIS Cut Line= 3
      2766357.31      6893779.39      2766526.21      6894066.67
      2766774.91      6894420.94
#Sta/Elev= 30
  4670.3  525.45  4736.4  525.23  4752.0  524.74  4773.5  523.44  4837.9  521.06
  4875.0  520.40  4881.0  520.74  4970.8  515.10  4976.6  514.54  4985.4  511.84
  4990.2  510.86  4990.5  510.36  4994.0  510.36  4994.2  510.86  4998.0  511.59
  5007.7  512.08  5013.4  513.13  5043.0  515.91  5049.1  516.88  5084.9  517.14
  5120.6  518.59  5129.3  518.31  5135.4  518.59  5150.2  518.43  5156.3  518.95
  5200.8  518.85  5257.4  520.98  5322.8  522.27  5358.5  523.58  5436.4  524.90
#Mann=3,-1,0
  4670.3    0.15       0  4990.2    0.05       0  4994.2    0.15       0
Bank Sta=4990.2,4994.2
Exp/Cntr=0.3,0.1

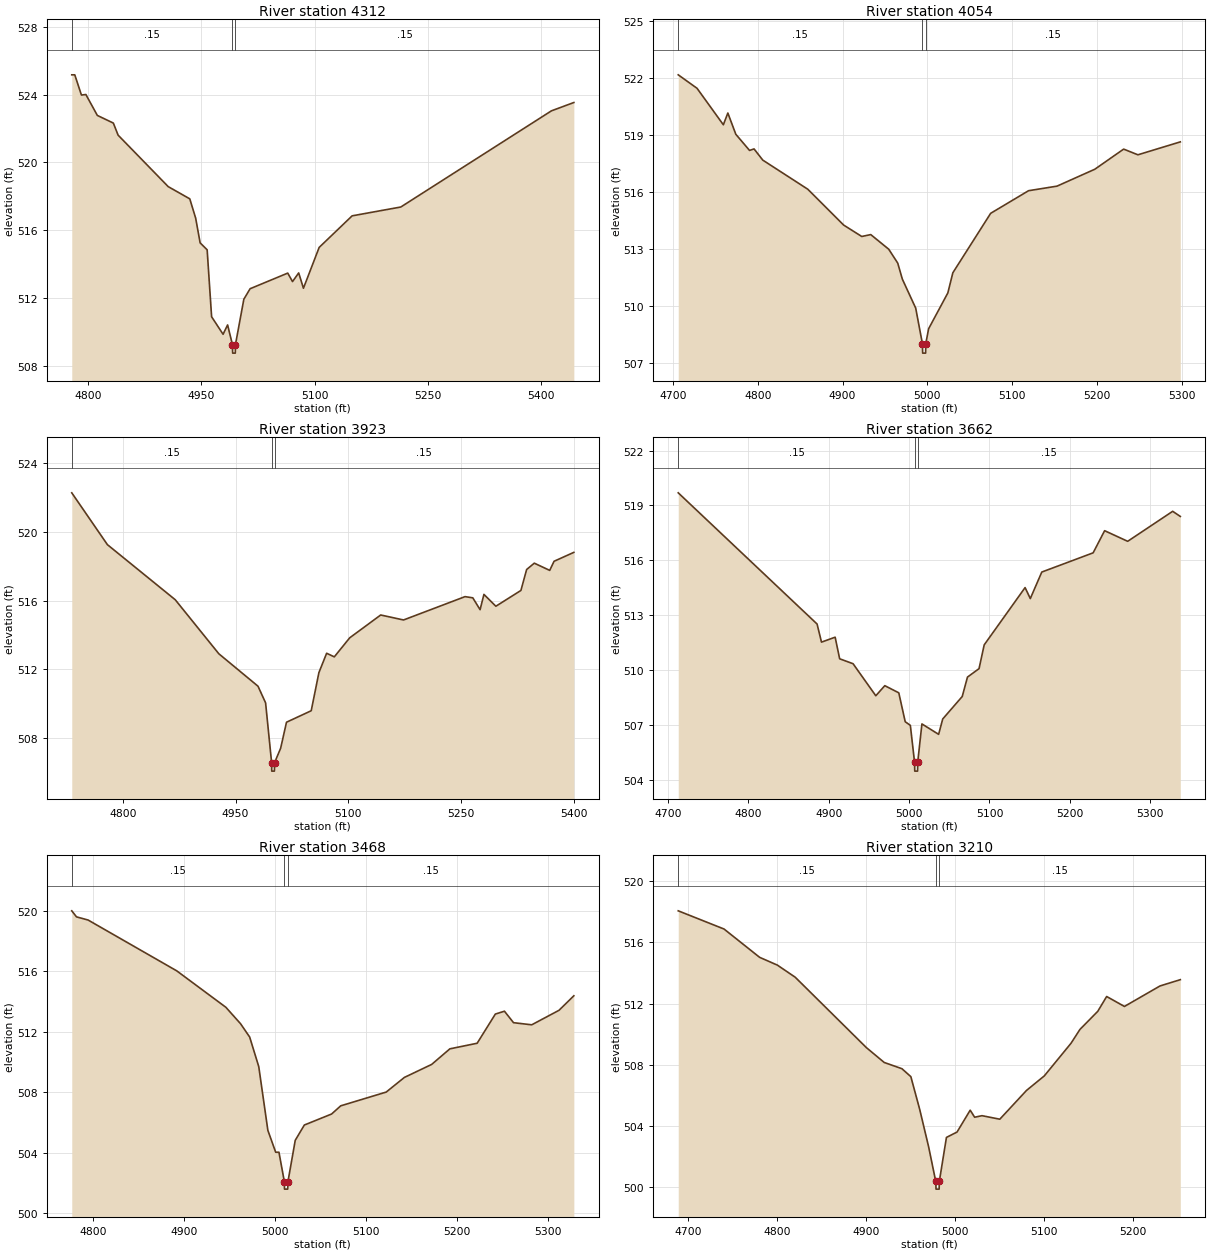
Type RM Length L Ch R = 1,4312,258,258,258
BEGIN DESCRIPTION:
Lacy 048 2711
END DESCRIPTION:
XS GIS Cut Line= 3
      2766241.51      6893939.30      2766360.14      6894124.66
      2766714.83      6894393.77
#Sta/Elev= 30
  4778.1  525.16  4782.1  525.16  4790.9  523.97  4796.8  524.00  4812.0  522.77
  4833.2  522.32  4839.5  521.61  4905.9  518.58  4934.5  517.86  4942.3  516.72
  4948.2  515.27  4957.5  514.86  4963.4  510.92  4978.6  509.89  4984.6  510.44
  4991.0  509.28  4991.3  508.78  4994.8  508.78  4995.0  509.28  5006.1  511.95
  5014.4  512.57  5064.3  513.49  5070.6  512.99  5078.8  513.50  5085.1  512.60
  5105.9  515.00  5149.6  516.86  5214.1  517.38  5413.7  523.04  5443.4  523.53
#Mann=3,-1,0
  4778.1    0.15       0  4991.0    0.05       0  4995.0    0.15       0
Bank Sta=4991,4995
Exp/Cntr=0.3,0.1

Type RM Length L Ch R = 1,4054,131,131,131
BEGIN DESCRIPTION:
Lacy 048 2710
END DESCRIPTION:
XS GIS Cut Line= 3
      2766092.91      6894017.00      2766191.63      6894296.55
      2766322.97      6894561.29
#Sta/Elev= 30
  4706.2  522.17  4728.4  521.46  4759.4  519.54  4764.7  520.16  4774.1  519.04
  4790.3  518.19  4795.6  518.27  4805.9  517.68  4858.9  516.15  4901.3  514.26
  4922.6  513.66  4933.2  513.76  4954.4  512.99  4965.0  512.26  4970.5  511.41
  4986.2  509.89  4994.1  508.02  4994.4  507.52  4997.9  507.52  4998.1  508.02
  5001.4  508.80  5024.1  510.69  5030.0  511.75  5074.6  514.88  5119.3  516.07
  5152.8  516.31  5197.4  517.20  5231.4  518.26  5248.2  517.96  5298.2  518.64
#Mann=3,-1,0
  4706.2    0.15       0  4994.1    0.05       0  4998.1    0.15       0
Bank Sta=4994.1,4998.1
Exp/Cntr=0.3,0.1

Type RM Length L Ch R = 1,3923,261,261,261
BEGIN DESCRIPTION:
Lacy 048 2709
END DESCRIPTION:
XS GIS Cut Line= 3
      2766049.72      6894043.65      2766066.10      6894331.55
      2766146.42      6894702.39
#Sta/Elev= 30
  4732.1  522.29  4779.5  519.27  4869.7  516.06  4927.7  512.91  4979.8  511.02
  4989.9  510.05  4997.9  506.57  4998.1  506.07  5001.6  506.07  5001.9  506.57
  5009.9  507.40  5017.7  508.92  5050.6  509.59  5060.8  511.81  5071.1  512.94
  5081.3  512.73  5101.8  513.84  5143.0  515.17  5173.4  514.88  5255.2  516.24
  5265.5  516.17  5275.2  515.48  5280.3  516.37  5296.2  515.68  5329.5  516.60
  5337.1  517.82  5347.3  518.19  5367.8  517.77  5373.6  518.30  5399.9  518.82
#Mann=3,-1,0
  4732.1    0.15       0  4997.9    0.05       0  5001.9    0.15       0
Bank Sta=4997.9,5001.9
Exp/Cntr=0.3,0.1

Type RM Length L Ch R = 1,3662,194,194,194
BEGIN DESCRIPTION:
Lacy 048 2708
END DESCRIPTION:
XS GIS Cut Line= 4
      2765782.94      6894215.45      2765895.92      6894447.03
      2765952.66      6894492.25      2766140.15      6894719.59
#Sta/Elev= 30
  4712.6  519.69  4885.4  512.52  4890.9  511.53  4907.9  511.80  4913.5  510.62
  4930.2  510.35  4958.5  508.60  4969.7  509.15  4987.1  508.76  4995.1  507.18
  5001.5  506.98  5006.7  504.98  5007.0  504.48  5010.5  504.48  5010.7  504.98
  5015.9  507.06  5036.7  506.49  5041.8  507.33  5066.1  508.56  5072.6  509.62
  5087.0  510.08  5093.4  511.38  5144.3  514.51  5150.8  513.91  5165.1  515.36
  5229.0  516.41  5243.3  517.62  5272.0  517.04  5328.0  518.68  5337.5  518.40
#Mann=3,-1,0
  4712.6    0.15       0  5006.7    0.05       0  5010.7    0.15       0
Bank Sta=5006.7,5010.7
Exp/Cntr=0.3,0.1

Type RM Length L Ch R = 1,3468,258,258,258
BEGIN DESCRIPTION:
Lacy 048 2707
END DESCRIPTION:
XS GIS Cut Line= 3
      2765759.96      6894195.83      2765774.90      6894423.09
      2765774.21      6894747.34
#Sta/Elev= 30
  4776.4  520.01  4781.6  519.61  4794.4  519.40  4891.8  516.04  4945.8  513.63
  4962.0  512.54  4972.0  511.66  4982.0  509.70  4992.0  505.49  5000.6  504.04
  5004.2  504.04  5010.1  502.10  5010.3  501.60  5013.8  501.60  5014.1  502.10
  5022.1  504.83  5032.1  505.84  5062.1  506.57  5072.1  507.11  5122.1  508.02
  5142.1  508.99  5172.1  509.85  5192.1  510.88  5222.1  511.25  5242.1  513.18
  5252.1  513.37  5262.1  512.61  5282.1  512.47  5312.1  513.43  5328.4  514.39
#Mann=3,-1,0
  4776.4    0.15       0  5010.1    0.05       0  5014.1    0.15       0
Bank Sta=5010.1,5014.1
Exp/Cntr=0.3,0.1

Type RM Length L Ch R = 1,3210,195,195,195
BEGIN DESCRIPTION:
Lacy 048 2706
END DESCRIPTION:
XS GIS Cut Line= 3
      2765558.93      6894199.56      2765551.21      6894512.83
      2765547.96      6894763.84
#Sta/Elev= 30
  4689.2  518.06  4740.7  516.87  4780.7  515.02  4800.7  514.51  4820.7  513.72
  4900.7  509.12  4920.7  508.15  4940.7  507.74  4950.7  507.22  4960.7  505.07
  4970.7  502.63  4978.7  500.37  4979.0  499.87  4982.5  499.87  4982.7  500.37
  4990.7  503.25  5002.6  503.60  5017.4  505.03  5022.4  504.57  5030.7  504.67
  5050.7  504.44  5080.7  506.32  5100.7  507.27  5130.7  509.40  5140.8  510.31
  5160.8  511.49  5170.8  512.46  5190.8  511.81  5230.8  513.15  5253.6  513.56
#Mann=3,-1,0
  4689.2    0.15       0  4978.7    0.05       0  4982.7    0.15       0
Bank Sta=4978.7,4982.7
Exp/Cntr=0.3,0.1

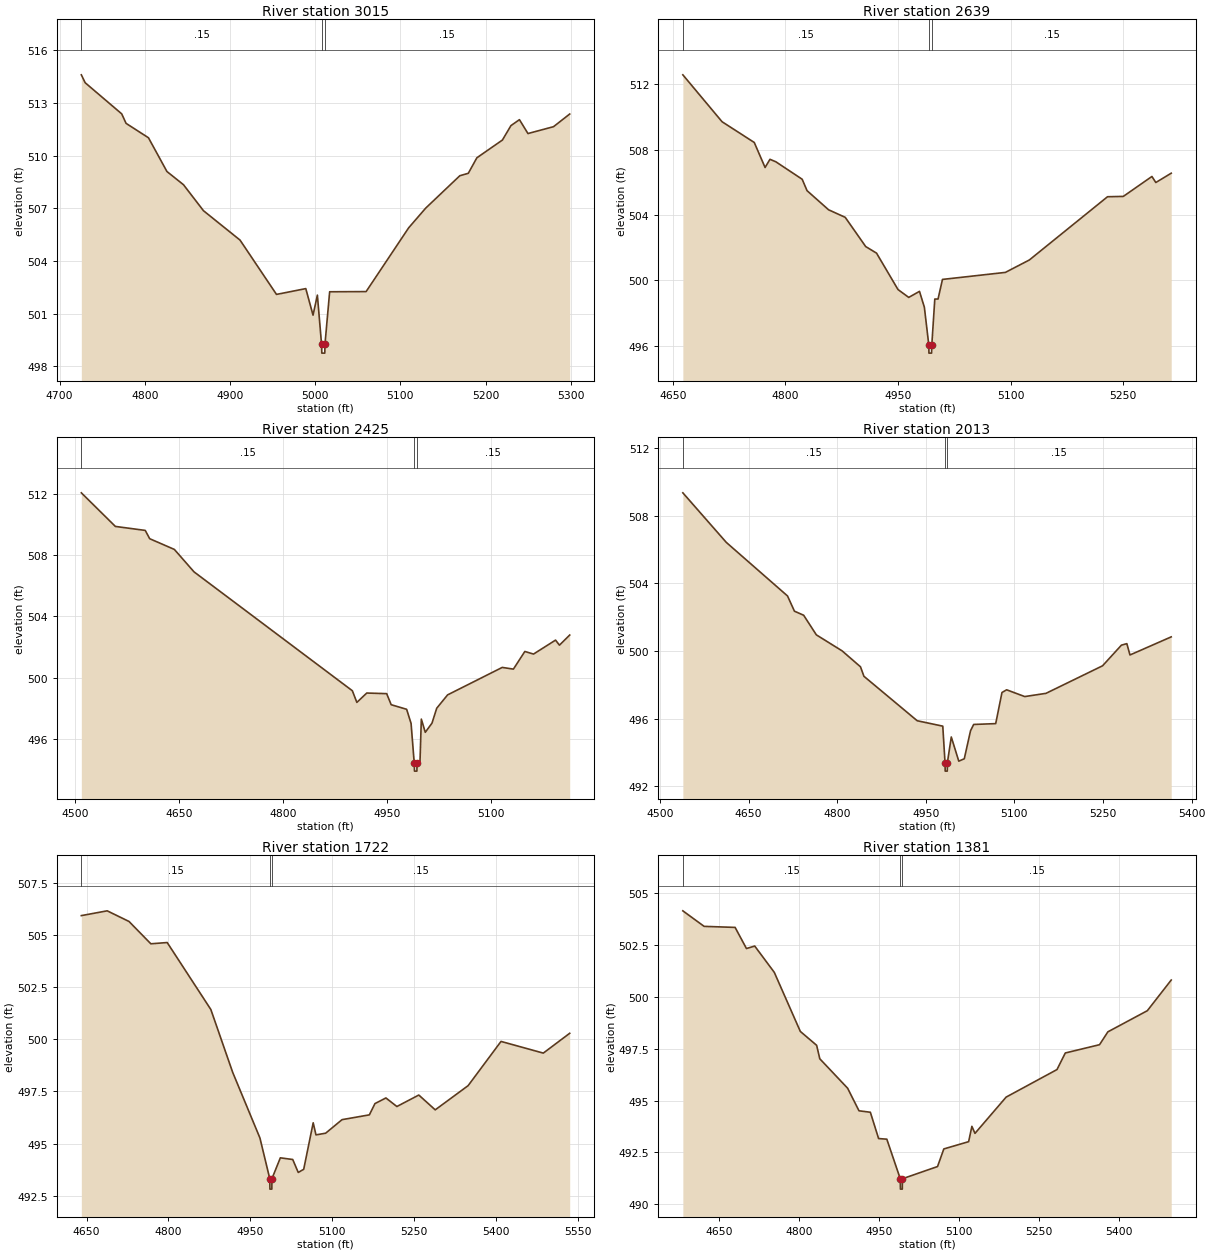
Type RM Length L Ch R = 1,3015,376,376,376
BEGIN DESCRIPTION:
Lacy 048 3467
END DESCRIPTION:
XS GIS Cut Line= 3
      2765432.61      6894194.18      2765366.86      6894480.64
      2765365.48      6894760.02
#Sta/Elev= 30
  4725.5  514.59  4730.0  514.14  4772.9  512.37  4778.0  511.83  4804.3  511.01
  4826.0  509.09  4845.4  508.34  4868.9  506.86  4911.8  505.19  4954.6  502.10
  4989.0  502.43  4997.5  500.92  5002.6  502.06  5007.5  499.26  5007.8  498.76
  5011.3  498.76  5011.5  499.26  5017.0  502.25  5059.8  502.26  5109.8  505.89
  5129.8  507.01  5169.8  508.85  5179.8  508.99  5189.8  509.87  5219.8  510.88
  5229.8  511.70  5239.8  512.04  5249.8  511.25  5279.8  511.64  5298.8  512.36
#Mann=3,-1,0
  4725.5    0.15       0  5007.5    0.05       0  5011.5    0.15       0
Bank Sta=5007.5,5011.5
Exp/Cntr=0.3,0.1

Type RM Length L Ch R = 1,2639,214,214,214
BEGIN DESCRIPTION:
Lacy 048 3466
END DESCRIPTION:
XS GIS Cut Line= 3
      2765292.98      6894054.22      2765075.55      6894315.33
      2764983.86      6894612.00
#Sta/Elev= 30
  4663.5  512.57  4715.7  509.70  4758.6  508.43  4773.0  506.90  4779.5  507.40
  4787.3  507.25  4822.4  506.18  4828.9  505.48  4857.6  504.31  4879.7  503.85
  4907.0  502.06  4921.4  501.66  4950.0  499.43  4964.3  498.95  4978.6  499.32
  4985.1  498.35  4991.0  496.04  4991.2  495.54  4994.7  495.54  4995.0  496.04
  4999.0  498.85  5003.3  498.85  5009.2  500.05  5093.0  500.48  5124.9  501.24
  5229.0  505.11  5250.0  505.13  5288.1  506.35  5293.3  505.98  5313.8  506.55
#Mann=3,-1,0
  4663.5    0.15       0  4991.0    0.05       0  4995.0    0.15       0
Bank Sta=4991,4995
Exp/Cntr=0.3,0.1

Type RM Length L Ch R = 1,2425,412,412,412
BEGIN DESCRIPTION:
Lacy 048 2703
END DESCRIPTION:
XS GIS Cut Line= 3
      2765211.20      6893906.97      2764902.66      6894285.58
      2764803.31      6894477.37
#Sta/Elev= 30
  4509.5  512.06  4558.6  509.87  4601.7  509.61  4608.1  509.07  4643.7  508.37
  4672.0  506.91  4900.4  499.16  4906.9  498.40  4921.2  499.01  4949.9  498.97
  4956.4  498.25  4978.7  497.95  4985.1  497.03  4989.7  494.42  4990.0  493.92
  4993.5  493.92  4993.7  494.42  4997.9  494.42  4999.9  497.31  5005.6  496.45
  5015.3  497.05  5022.1  498.02  5037.8  498.89  5116.6  500.68  5132.7  500.57
  5149.2  501.72  5161.7  501.55  5193.5  502.46  5199.1  502.13  5213.9  502.79
#Mann=3,-1,0
  4509.5    0.15       0  4989.7    0.05       0  4993.7    0.15       0
Bank Sta=4989.7,4993.7
Exp/Cntr=0.3,0.1

Type RM Length L Ch R = 1,2013,291,291,291
BEGIN DESCRIPTION:
Lacy 048 2702
END DESCRIPTION:
XS GIS Cut Line= 3
      2764932.27      6893737.34      2764700.93      6894138.61
      2764576.64      6894480.23
#Sta/Elev= 30
  4538.7  509.36  4612.2  506.43  4715.9  503.26  4727.6  502.36  4743.2  502.12
  4764.7  500.96  4808.4  500.01  4839.4  499.07  4845.2  498.51  4935.4  495.88
  4978.7  495.56  4982.5  493.40  4982.8  492.90  4986.3  492.90  4986.5  493.40
  4993.1  494.92  5005.8  493.49  5015.1  493.63  5025.7  495.29  5031.0  495.66
  5068.3  495.71  5078.9  497.55  5086.8  497.71  5117.4  497.31  5153.4  497.50
  5249.2  499.13  5281.1  500.35  5290.3  500.44  5295.6  499.77  5365.4  500.84
#Mann=3,-1,0
  4538.7    0.15       0  4982.5    0.05       0  4986.5    0.15       0
Bank Sta=4982.5,4986.5
Exp/Cntr=0.3,0.1

Type RM Length L Ch R = 1,1722,341,341,341
BEGIN DESCRIPTION:
Lacy 048 2701
END DESCRIPTION:
XS GIS Cut Line= 3
      2764482.59      6893653.56      2764485.29      6894020.73
      2764535.39      6894546.37
#Sta/Elev= 30
  4640.3  505.93  4687.7  506.16  4727.7  505.65  4767.7  504.58  4797.7  504.64
  4877.7  501.43  4917.7  498.42  4967.7  495.27  4985.7  493.32  4986.0  492.82
  4989.5  492.82  4989.7  493.32  5005.1  494.32  5027.8  494.24  5037.9  493.62
  5047.9  493.77  5065.3  496.00  5070.4  495.42  5088.1  495.50  5118.2  496.15
  5168.3  496.38  5178.5  496.92  5198.6  497.19  5218.7  496.78  5258.9  497.33
  5289.0  496.62  5349.3  497.78  5409.6  499.90  5487.1  499.34  5535.5  500.29
#Mann=3,-1,0
  4640.3    0.15       0  4985.7    0.05       0  4989.7    0.15       0
Bank Sta=4985.7,4989.7
Exp/Cntr=0.3,0.1

Type RM Length L Ch R = 1,1381,136,136,136
BEGIN DESCRIPTION:
Lacy 048 2700
END DESCRIPTION:
XS GIS Cut Line= 3
      2764009.58      6893802.98      2764229.51      6894163.38
      2764482.24      6894587.36
#Sta/Elev= 30
  4582.0  504.16  4621.9  503.41  4680.0  503.36  4701.3  502.34  4716.8  502.46
  4753.5  501.19  4802.3  498.34  4832.9  497.67  4838.8  497.02  4891.0  495.60
  4912.3  494.51  4933.6  494.44  4949.1  493.17  4964.5  493.14  4989.7  491.23
  4990.0  490.73  4993.5  490.73  4993.7  491.23  5059.6  491.82  5071.4  492.67
  5117.9  493.02  5124.0  493.76  5129.8  493.42  5188.2  495.17  5283.6  496.50
  5299.2  497.30  5363.4  497.70  5379.0  498.32  5453.0  499.34  5497.8  500.82
#Mann=3,-1,0
  4582.0    0.15       0  4989.7    0.05       0  4993.7    0.15       0
Bank Sta=4989.7,4993.7
Exp/Cntr=0.3,0.1

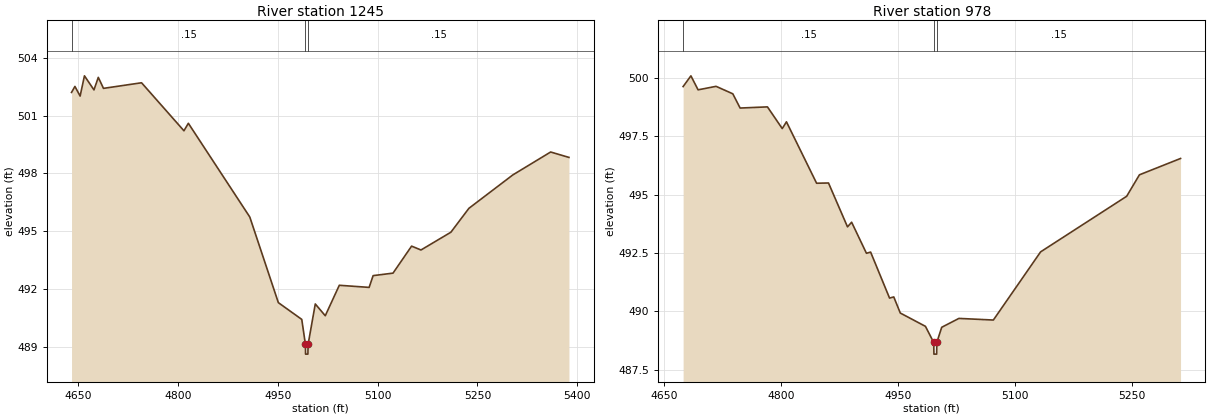
Type RM Length L Ch R = 1,1245,267,267,267
BEGIN DESCRIPTION:
Lacy 048 2699
END DESCRIPTION:
XS GIS Cut Line= 3
      2763899.13      6893980.44      2764130.71      6894255.81
      2764347.68      6894576.87
#Sta/Elev= 30
  4640.2  502.20  4645.3  502.51  4653.1  502.01  4659.6  503.06  4673.9  502.33
  4680.4  502.98  4688.2  502.41  4745.4  502.70  4809.1  500.21  4815.7  500.60
  4908.0  495.74  4950.9  491.30  4986.1  490.43  4991.6  489.13  4991.8  488.63
  4995.3  488.63  4995.6  489.13  5006.4  491.23  5021.4  490.62  5042.5  492.20
  5087.3  492.09  5093.3  492.70  5123.2  492.83  5151.1  494.23  5165.2  494.03
  5210.1  494.95  5237.2  496.19  5303.1  497.92  5360.0  499.11  5387.5  498.83
#Mann=3,-1,0
  4640.2    0.15       0  4991.6    0.05       0  4995.6    0.15       0
Bank Sta=4991.6,4995.6
Exp/Cntr=0.3,0.1

Type RM Length L Ch R = 1,978,0,0,0
BEGIN DESCRIPTION:
Lacy 048 2698
END DESCRIPTION:
XS GIS Cut Line= 3
      2763832.55      6894131.66      2763952.51      6894434.68
      2764230.03      6894579.22
#Sta/Elev= 30
  4674.1  499.63  4684.1  500.09  4693.3  499.49  4716.4  499.64  4737.9  499.32
  4747.3  498.71  4782.4  498.76  4801.4  497.83  4806.8  498.12  4845.5  495.49
  4860.8  495.50  4885.2  493.62  4890.5  493.82  4909.5  492.49  4914.9  492.54
  4939.2  490.57  4944.6  490.62  4953.0  489.93  4985.3  489.36  4995.9  488.67
  4996.2  488.17  4999.7  488.17  4999.9  488.67  5006.2  489.32  5028.3  489.70
  5072.5  489.63  5133.2  492.55  5243.7  494.93  5260.1  495.85  5312.9  496.55
#Mann=3,-1,0
  4674.1    0.15       0  4995.9    0.05       0  4999.9    0.15       0
Bank Sta=4995.9,4999.9
Exp/Cntr=0.3,0.1

Chan Stop Cuts=-1