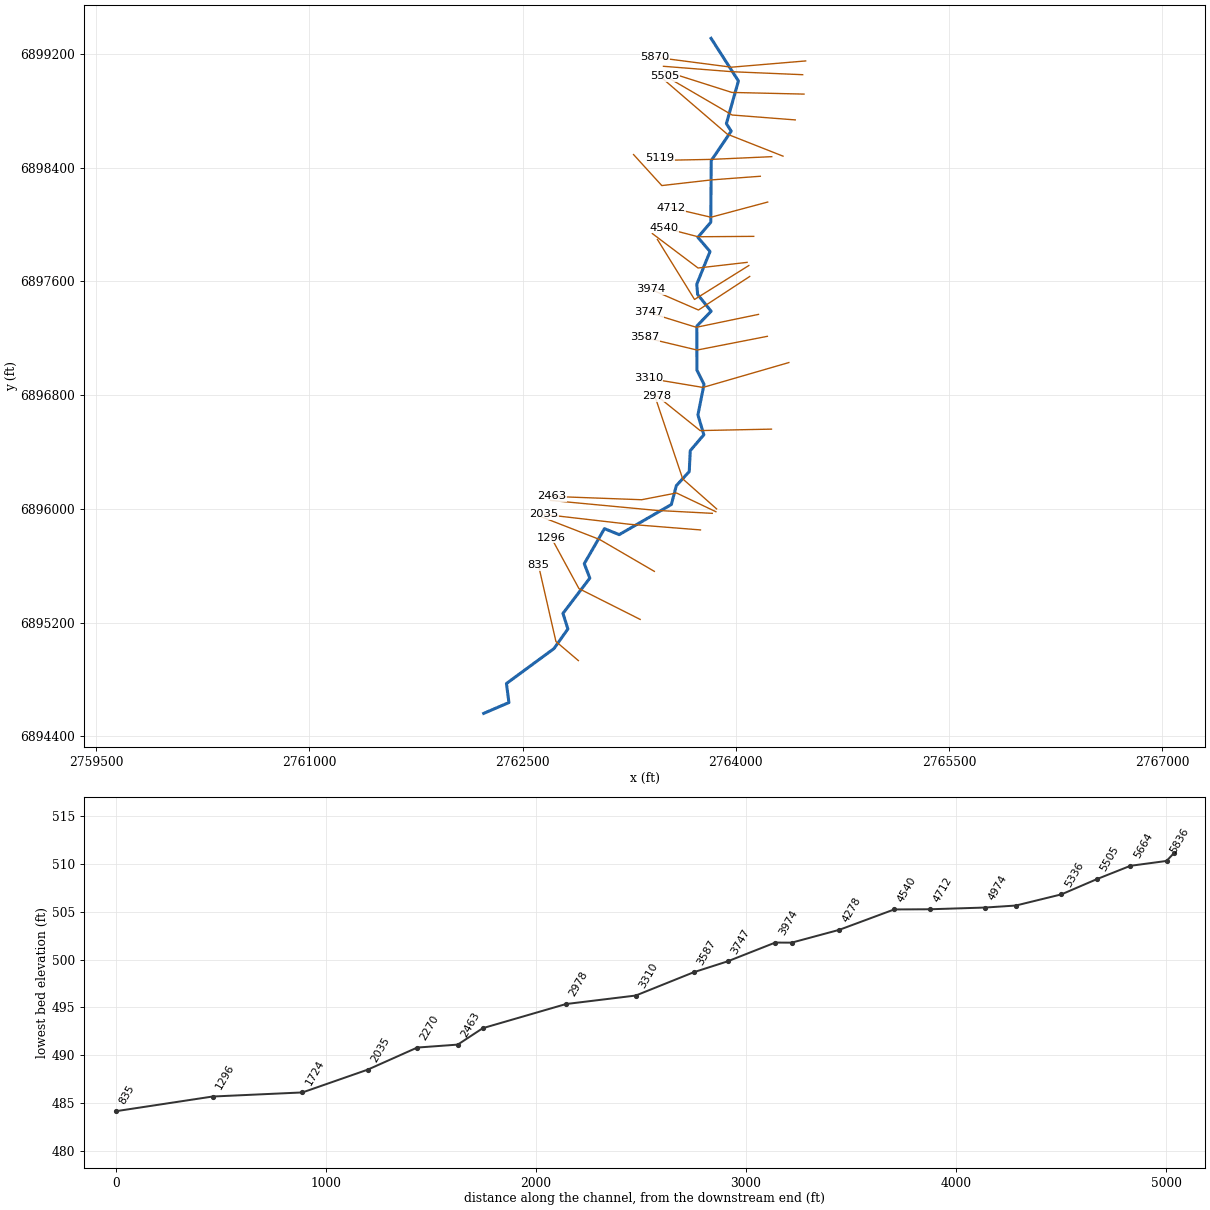
--- Lacy 049.prj (project) ---

Proj Title=Lacy 049 Base Level Engineering
Current Plan=p01
Default Exp/Contr=0.3,0.1
English Units
Geom File=g01
Flow File=f01
Plan File=p01
BEGIN DESCRIPTION:
Lacy 049
END DESCRIPTION:

--- Lacy 049.p01 (plan) ---

Plan Title=Multiple Run
Short Identifier=Multiple
Geom File=g01
Flow File=f01
Subcritical Flow
K Sum by GR= 0
Std Step Tol= 0.01
Critical Tol= 0.01
Num of Std Step Trials= 20
Max Error Tol= 0.3
Flow Tol Ratio= 0.001
Split Flow NTrial= 30
Split Flow Tol= 0.02
Split Flow Ratio= 0.02
Log Output Level= 0
Friction Slope Method= 1
Unsteady Friction Slope Method= 2
Unsteady Bridges Friction Slope Method= 1
Parabolic Critical Depth
Global Vel Dist=  1 , 1 , 1
Global Log Level= 0
CheckData=True
Encroach Param= -1, 0, 0, 0
BEGIN DESCRIPTION:
Multiple Run
END DESCRIPTION:

--- Lacy 049.f01 (steady flow) ---

Flow Title=Multiple
Number of Profiles=7
Profile Names=10-year,25-year,50-year,1pct_min,100-year,1pct_plu,500-year
River Rch & RM= Lacy 049,Reach-1,5870
     267     340     397     230     460     917     617
River Rch & RM= Lacy 049,Reach-1,2463
     335     433     509     298     594    1186     811
Boundary for River Rch & Prof#=Lacy 049,Reach-1,1
Up Type=0
Dn Type=3
Dn Slope=0.005
Boundary for River Rch & Prof#=Lacy 049,Reach-1,2
Up Type=0
Dn Type=3
Dn Slope=0.005
Boundary for River Rch & Prof#=Lacy 049,Reach-1,3
Up Type=0
Dn Type=3
Dn Slope=0.005
Boundary for River Rch & Prof#=Lacy 049,Reach-1,4
Up Type=0
Dn Type=3
Dn Slope=0.005
Boundary for River Rch & Prof#=Lacy 049,Reach-1,5
Up Type=0
Dn Type=3
Dn Slope=0.005
Boundary for River Rch & Prof#=Lacy 049,Reach-1,6
Up Type=0
Dn Type=3
Dn Slope=0.005
Boundary for River Rch & Prof#=Lacy 049,Reach-1,7
Up Type=0
Dn Type=3
Dn Slope=0.005

--- Lacy 049.g01 (geometry) ---

Geom Title=Existing Conditions

River Reach=Lacy 049,Reach-1
Reach XY= 30
      2763826.00      6899311.00      2764018.47      6899011.01
      2763933.80      6898710.90      2763967.76      6898657.77
      2763827.05      6898450.56      2763823.92      6898016.85
      2763733.11      6897911.00      2763818.66      6897811.10
      2763725.39      6897581.04      2763731.41      6897508.58
      2763826.49      6897390.77      2763725.68      6897286.20
      2763726.52      6896976.22      2763776.43      6896876.18
      2763733.56      6896661.00      2763775.05      6896521.49
      2763679.56      6896409.53      2763672.44      6896262.47
      2763581.54      6896163.42      2763546.57      6896030.59
      2763179.38      6895818.60      2763076.00      6895861.00
      2762933.83      6895614.40      2762972.83      6895512.65
      2762783.83      6895264.40      2762818.48      6895154.96
      2762720.38      6895016.62      2762386.07      6894770.99
      2762403.70      6894637.27      2762226.00      6894561.00

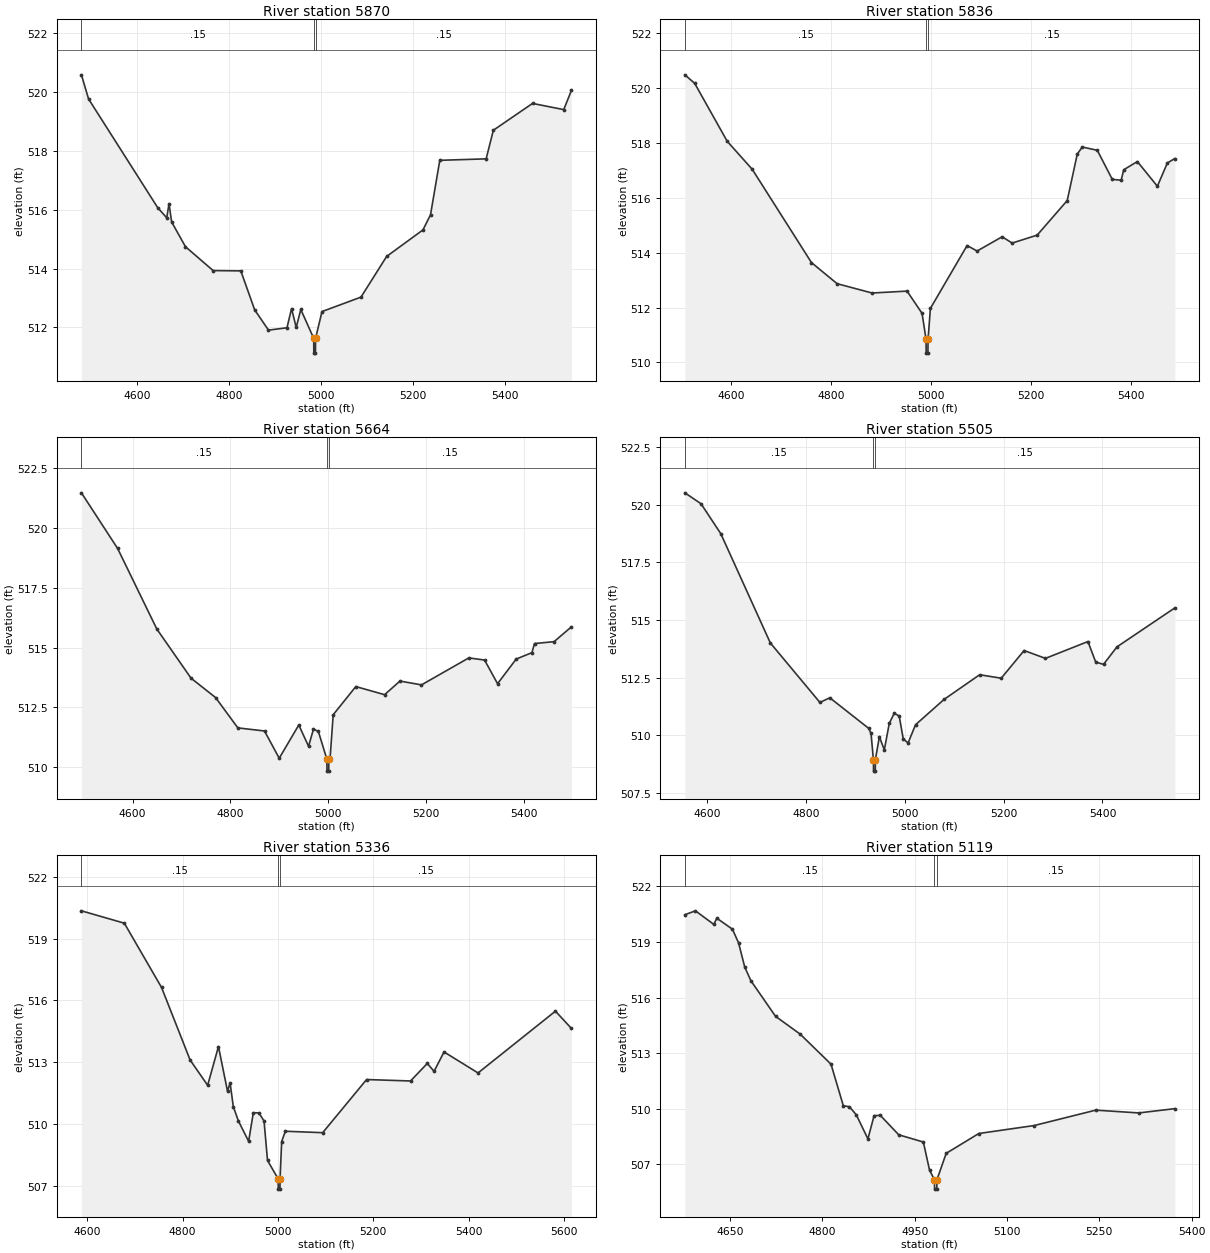
Type RM Length L Ch R = 1,5870,34,34,34
BEGIN DESCRIPTION:
Lacy 049 3472
END DESCRIPTION:
XS GIS Cut Line= 3
      2764491.51      6899151.95      2763969.07      6899107.93
      2763432.09      6899177.86
#Sta/Elev= 30
  4478.5  520.57  4494.1  519.75  4644.6  516.06  4664.1  515.72  4669.1  516.20
  4674.7  515.58  4704.8  514.74  4765.0  513.93  4825.2  513.92  4855.3  512.60
  4885.4  511.91  4925.6  511.99  4935.6  512.64  4945.7  512.00  4955.7  512.61
  4983.8  511.63  4984.0  511.13  4987.5  511.13  4987.8  511.63  5001.8  512.54
  5086.6  513.03  5142.4  514.41  5221.4  515.31  5237.8  515.82  5258.0  517.67
  5358.8  517.72  5374.5  518.69  5459.7  519.60  5527.6  519.39  5544.3  520.04
#Mann=3,-1,0
  4478.5    0.15       0  4983.8    0.05       0  4987.8    0.15       0
Bank Sta=4983.8,4987.8
Exp/Cntr=0.3,0.1

Type RM Length L Ch R = 1,5836,172,172,172
BEGIN DESCRIPTION:
Lacy 049 2687
END DESCRIPTION:
XS GIS Cut Line= 3
      2764470.75      6899055.17      2763977.48      6899075.95
      2763491.09      6899114.22
#Sta/Elev= 30
  4507.1  520.48  4526.8  520.17  4591.9  518.06  4642.0  517.04  4760.7  513.64
  4812.1  512.87  4882.2  512.53  4952.2  512.60  4982.3  511.79  4990.3  510.84
  4990.5  510.34  4994.0  510.34  4994.3  510.84  4999.0  511.97  5072.5  514.26
  5092.6  514.06  5142.7  514.58  5162.8  514.35  5212.9  514.64  5273.1  515.90
  5293.2  517.59  5303.2  517.85  5333.3  517.73  5363.4  516.67  5381.2  516.64
  5386.2  517.02  5413.6  517.32  5453.7  516.42  5473.7  517.27  5488.7  517.43
#Mann=3,-1,0
  4507.1    0.15       0  4990.3    0.05       0  4994.3    0.15       0
Bank Sta=4990.3,4994.3
Exp/Cntr=0.3,0.1

Type RM Length L Ch R = 1,5664,159,159,159
BEGIN DESCRIPTION:
Lacy 049 2686
END DESCRIPTION:
XS GIS Cut Line= 3
      2764479.98      6898918.59      2763972.26      6898930.35
      2763502.22      6899079.86
#Sta/Elev= 30
  4495.6  521.48  4569.6  519.15  4649.6  515.78  4719.6  513.72  4769.7  512.91
  4815.2  511.64  4869.7  511.51  4899.7  510.37  4939.7  511.76  4959.7  510.87
  4969.7  511.59  4979.7  511.49  4997.1  510.33  4997.3  509.83  5000.8  509.83
  5001.1  510.33  5003.5  510.33  5010.0  512.19  5056.2  513.37  5115.0  513.03
  5146.4  513.60  5190.4  513.44  5287.1  514.57  5319.3  514.48  5345.8  513.49
  5383.8  514.52  5416.0  514.79  5421.3  515.17  5461.3  515.25  5496.7  515.87
#Mann=3,-1,0
  4495.6    0.15       0  4997.1    0.05       0  5001.1    0.15       0
Bank Sta=4997.1,5001.1
Exp/Cntr=0.3,0.1

Type RM Length L Ch R = 1,5505,169,169,169
BEGIN DESCRIPTION:
Lacy 049 2685
END DESCRIPTION:
XS GIS Cut Line= 3
      2764418.49      6898736.96      2763974.62      6898771.43
      2763502.38      6899046.47
#Sta/Elev= 30
  4554.8  520.51  4587.4  520.04  4627.5  518.74  4727.8  514.00  4828.1  511.42
  4848.2  511.62  4926.6  510.30  4931.6  510.08  4936.4  508.94  4936.7  508.44
  4940.2  508.44  4940.4  508.94  4948.5  509.93  4958.5  509.36  4968.5  510.51
  4978.6  510.95  4988.6  510.83  4996.8  509.84  5006.6  509.66  5021.6  510.45
  5079.4  511.55  5151.4  512.62  5195.1  512.47  5241.4  513.67  5284.6  513.33
  5370.6  514.06  5386.3  513.17  5402.1  513.07  5429.4  513.83  5546.5  515.52
#Mann=3,-1,0
  4554.8    0.15       0  4936.4    0.05       0  4940.4    0.15       0
Bank Sta=4936.4,4940.4
Exp/Cntr=0.3,0.1

Type RM Length L Ch R = 1,5336,217,217,217
BEGIN DESCRIPTION:
Lacy 049 2684
END DESCRIPTION:
XS GIS Cut Line= 3
      2764332.33      6898482.00      2763939.88      6898636.87
      2763480.49      6899032.08
#Sta/Elev= 30
  4587.8  520.35  4677.8  519.75  4755.9  516.63  4815.8  513.11  4852.6  511.88
  4875.3  513.76  4894.3  511.59  4899.7  512.00  4906.4  510.85  4917.1  510.15
  4938.6  509.16  4948.4  510.55  4960.1  510.54  4970.9  510.15  4978.2  508.23
  5000.5  507.34  5000.8  506.84  5004.3  506.84  5004.5  507.34  5007.9  509.15
  5015.6  509.65  5093.9  509.58  5186.0  512.16  5278.2  512.09  5313.3  512.94
  5327.6  512.56  5348.5  513.50  5419.8  512.48  5582.2  515.48  5615.7  514.64
#Mann=3,-1,0
  4587.8    0.15       0  5000.5    0.05       0  5004.5    0.15       0
Bank Sta=5000.5,5004.5
Exp/Cntr=0.3,0.1

Type RM Length L Ch R = 1,5119,145,145,145
BEGIN DESCRIPTION:
Lacy 049 2683
END DESCRIPTION:
XS GIS Cut Line= 4
      2764253.23      6898478.32      2763826.93      6898459.18
      2763494.19      6898452.74      2763462.58      6898471.51
#Sta/Elev= 30
  4576.4  520.47  4593.6  520.68  4623.4  519.95  4628.4  520.28  4653.7  519.69
  4663.7  518.95  4673.7  517.65  4683.7  516.91  4723.8  514.99  4763.8  514.03
  4813.9  512.41  4833.9  510.17  4843.9  510.11  4855.0  509.68  4873.9  508.38
  4883.9  509.63  4894.0  509.65  4924.0  508.60  4964.0  508.21  4974.0  506.70
  4982.0  506.17  4982.3  505.67  4985.8  505.67  4986.0  506.17  5001.1  507.60
  5054.1  508.67  5144.1  509.10  5244.1  509.93  5314.1  509.78  5372.7  510.01
#Mann=3,-1,0
  4576.4    0.15       0  4982.0    0.05       0  4986.0    0.15       0
Bank Sta=4982,4986
Exp/Cntr=0.3,0.1

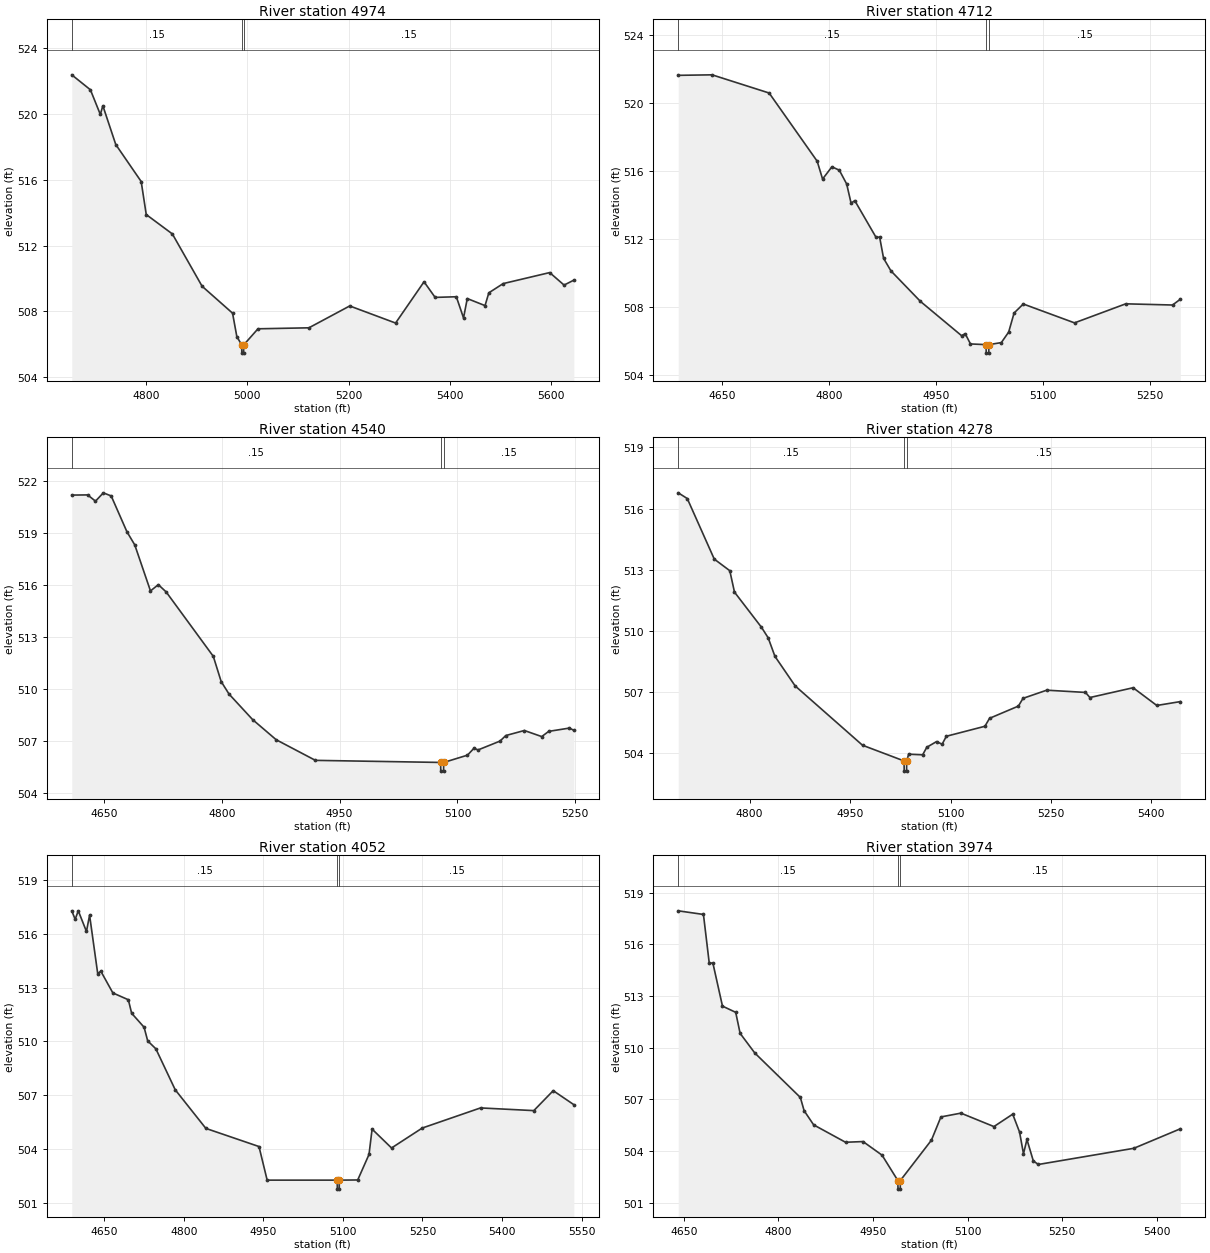
Type RM Length L Ch R = 1,4974,262,262,262
BEGIN DESCRIPTION:
Lacy 049 2680
END DESCRIPTION:
XS GIS Cut Line= 4
      2764172.70      6898340.55      2763827.25      6898314.74
      2763479.19      6898275.01      2763280.61      6898493.12
#Sta/Elev= 30
  4653.2  522.39  4690.0  521.48  4709.6  519.98  4714.6  520.51  4740.1  518.15
  4790.3  515.90  4800.3  513.89  4851.9  512.71  4910.6  509.53  4970.8  507.89
  4979.2  506.47  4988.8  505.96  4989.1  505.46  4992.6  505.46  4992.8  505.96
  5021.0  506.94  5121.6  507.00  5202.2  508.33  5292.8  507.29  5349.0  509.80
  5370.9  508.85  5412.8  508.89  5427.0  507.60  5434.4  508.78  5469.5  508.35
  5477.0  509.13  5505.3  509.69  5597.2  510.36  5625.6  509.60  5644.9  509.90
#Mann=3,-1,0
  4653.2    0.15       0  4988.8    0.05       0  4992.8    0.15       0
Bank Sta=4988.8,4992.8
Exp/Cntr=0.3,0.1

Type RM Length L Ch R = 1,4712,172,172,172
BEGIN DESCRIPTION:
Lacy 049 2682
END DESCRIPTION:
XS GIS Cut Line= 3
      2764224.40      6898158.96      2763825.20      6898052.16
      2763541.45      6898118.75
#Sta/Elev= 30
  4588.1  521.62  4635.6  521.65  4715.7  520.58  4783.1  516.57  4790.7  515.52
  4803.8  516.24  4814.2  516.04  4824.5  515.23  4830.7  514.10  4835.9  514.25
  4865.6  512.10  4870.8  512.10  4876.3  510.86  4886.6  510.12  4928.1  508.32
  4985.7  506.31  4990.9  506.42  4998.3  505.82  5020.2  505.78  5020.4  505.28
  5023.9  505.28  5024.2  505.78  5041.6  505.90  5051.9  506.52  5059.5  507.64
  5072.4  508.17  5144.3  507.06  5216.2  508.18  5281.9  508.11  5292.8  508.45
#Mann=3,-1,0
  4588.1    0.15       0  5020.2    0.05       0  5024.2    0.15       0
Bank Sta=5020.2,5024.2
Exp/Cntr=0.3,0.1

Type RM Length L Ch R = 1,4540,262,262,262
BEGIN DESCRIPTION:
Lacy 049 2681
END DESCRIPTION:
XS GIS Cut Line= 3
      2764126.22      6897917.55      2763734.72      6897914.85
      2763495.01      6897977.26
#Sta/Elev= 30
  4609.0  521.16  4629.2  521.17  4639.2  520.81  4649.2  521.29  4659.2  521.11
  4679.2  519.05  4689.2  518.29  4709.2  515.64  4719.2  516.00  4729.2  515.58
  4789.2  511.87  4799.2  510.42  4809.2  509.70  4839.2  508.23  4869.2  507.07
  4919.2  505.88  5078.6  505.76  5078.8  505.26  5082.3  505.26  5082.6  505.76
  5112.8  506.18  5121.1  506.58  5126.2  506.48  5154.2  506.99  5161.6  507.31
  5185.2  507.60  5207.3  507.25  5216.2  507.55  5242.6  507.74  5248.2  507.61
#Mann=3,-1,0
  4609.0    0.15       0  5078.6    0.05       0  5082.6    0.15       0
Bank Sta=5078.6,5082.6
Exp/Cntr=0.3,0.1

Type RM Length L Ch R = 1,4278,226,226,226
BEGIN DESCRIPTION:
Lacy 049 2679
END DESCRIPTION:
XS GIS Cut Line= 3
      2764079.44      6897734.56      2763734.26      6897694.90
      2763412.91      6897937.03
#Sta/Elev= 30
  4693.4  516.77  4706.9  516.49  4747.2  513.52  4770.4  512.95  4777.4  511.90
  4817.6  510.18  4827.7  509.66  4837.8  508.75  4868.0  507.30  4968.6  504.39
  5030.6  503.62  5030.9  503.12  5034.4  503.12  5034.6  503.62  5037.5  503.95
  5058.4  503.92  5064.6  504.29  5079.2  504.57  5087.5  504.44  5093.8  504.83
  5151.4  505.32  5158.3  505.71  5201.4  506.31  5208.3  506.69  5243.7  507.09
  5301.6  506.98  5308.2  506.73  5372.7  507.21  5408.1  506.34  5443.2  506.53
#Mann=3,-1,0
  4693.4    0.15       0  5030.6    0.05       0  5034.6    0.15       0
Bank Sta=5030.6,5034.6
Exp/Cntr=0.3,0.1

Type RM Length L Ch R = 1,4052,78,78,78
BEGIN DESCRIPTION:
Lacy 049 2678
END DESCRIPTION:
XS GIS Cut Line= 3
      2764091.71      6897712.37      2763709.70      6897473.64
      2763448.55      6897895.84
#Sta/Elev= 30
  4588.6  517.27  4595.0  516.80  4600.9  517.27  4616.3  516.12  4622.2  517.03
  4637.5  513.78  4643.4  513.91  4666.1  512.70  4695.3  512.32  4701.5  511.57
  4725.0  510.79  4731.8  510.03  4747.2  509.59  4783.7  507.31  4841.5  505.16
  4941.7  504.15  4957.1  502.28  5089.2  502.28  5089.5  501.78  5093.0  501.78
  5093.2  502.28  5127.9  502.29  5149.2  503.71  5155.0  505.12  5191.7  504.07
  5249.6  505.18  5359.5  506.30  5460.0  506.15  5496.6  507.26  5535.5  506.48
#Mann=3,-1,0
  4588.6    0.15       0  5089.2    0.05       0  5093.2    0.15       0
Bank Sta=5089.2,5093.2
Exp/Cntr=0.3,0.1

Type RM Length L Ch R = 1,3974,227,227,227
BEGIN DESCRIPTION:
Lacy 049 2677
END DESCRIPTION:
XS GIS Cut Line= 3
      2764098.15      6897635.44      2763737.31      6897399.27
      2763401.95      6897544.72
#Sta/Elev= 30
  4640.9  517.94  4680.9  517.73  4690.0  514.94  4696.0  514.89  4711.1  512.41
  4732.1  512.05  4739.1  510.83  4762.4  509.69  4834.7  507.11  4840.7  506.34
  4855.8  505.52  4906.4  504.51  4934.2  504.55  4964.4  503.76  4989.4  502.29
  4989.7  501.79  4993.2  501.79  4993.4  502.29  5042.7  504.63  5057.8  505.98
  5089.5  506.20  5141.9  505.42  5171.7  506.14  5182.6  505.10  5188.8  503.84
  5194.3  504.67  5204.4  503.43  5212.3  503.22  5364.0  504.16  5437.7  505.29
#Mann=3,-1,0
  4640.9    0.15       0  4989.4    0.05       0  4993.4    0.15       0
Bank Sta=4989.4,4993.4
Exp/Cntr=0.3,0.1

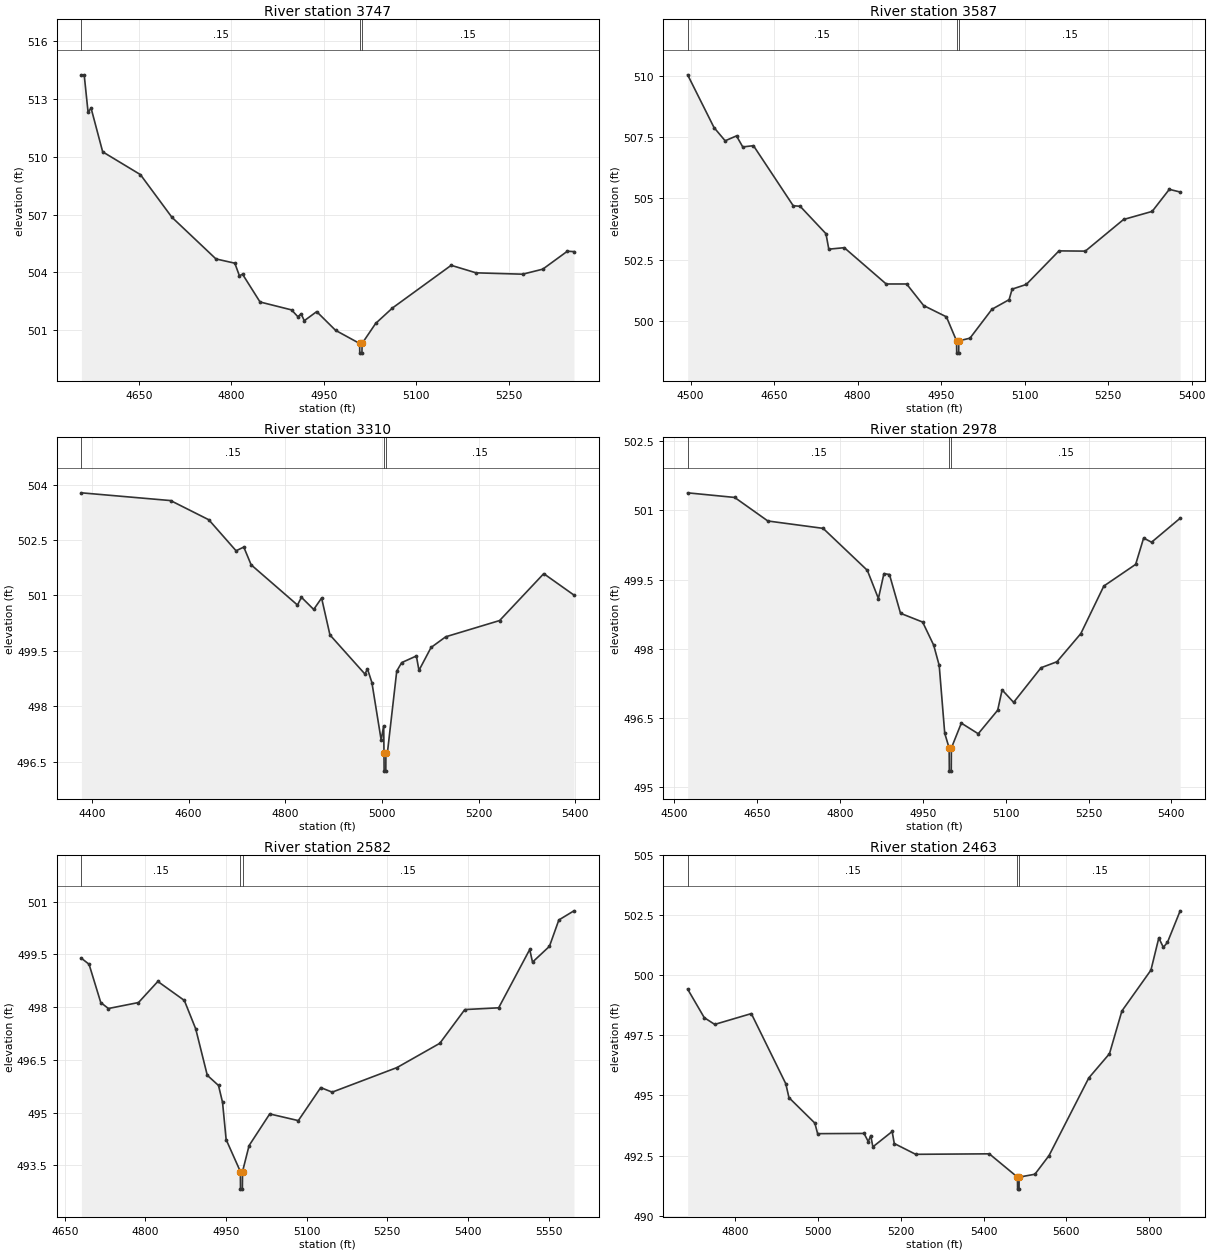
Type RM Length L Ch R = 1,3747,160,160,160
BEGIN DESCRIPTION:
Lacy 049 2676
END DESCRIPTION:
XS GIS Cut Line= 3
      2764159.75      6897368.53      2763721.97      6897277.66
      2763385.79      6897381.96
#Sta/Elev= 30
  4556.7  514.24  4561.2  514.24  4567.4  512.33  4572.5  512.50  4591.2  510.25
  4652.4  509.07  4703.5  506.86  4775.0  504.70  4805.6  504.48  4813.0  503.83
  4818.1  503.91  4846.5  502.47  4897.6  502.06  4907.8  501.71  4913.2  501.85
  4918.3  501.50  4938.4  501.97  4969.1  501.00  5008.1  500.32  5008.3  499.82
  5011.8  499.82  5012.1  500.32  5034.1  501.36  5061.4  502.16  5156.6  504.37
  5197.0  503.98  5272.6  503.91  5305.2  504.17  5345.1  505.10  5355.8  505.08
#Mann=3,-1,0
  4556.7    0.15       0  5008.1    0.05       0  5012.1    0.15       0
Bank Sta=5008.1,5012.1
Exp/Cntr=0.3,0.1

Type RM Length L Ch R = 1,3587,277,277,277
BEGIN DESCRIPTION:
Lacy 049 2675
END DESCRIPTION:
XS GIS Cut Line= 3
      2764222.15      6897214.19      2763727.73      6897117.61
      2763357.07      6897205.92
#Sta/Elev= 30
  4494.6  510.04  4542.0  507.89  4562.0  507.35  4582.4  507.55  4593.6  507.10
  4612.9  507.15  4684.3  504.70  4696.7  504.68  4743.1  503.56  4748.2  502.93
  4776.0  502.99  4851.3  501.51  4888.0  501.51  4918.6  500.63  4959.5  500.17
  4977.7  499.19  4978.0  498.69  4981.5  498.69  4981.7  499.19  5001.8  499.30
  5041.3  500.48  5072.1  500.87  5077.5  501.30  5102.9  501.49  5161.7  502.86
  5209.0  502.85  5277.7  504.14  5329.1  504.47  5359.9  505.37  5379.4  505.26
#Mann=3,-1,0
  4494.6    0.15       0  4977.7    0.05       0  4981.7    0.15       0
Bank Sta=4977.7,4981.7
Exp/Cntr=0.3,0.1

Type RM Length L Ch R = 1,3310,332,332,332
BEGIN DESCRIPTION:
Lacy 049 2674
END DESCRIPTION:
XS GIS Cut Line= 3
      2764373.36      6897029.58      2763769.03      6896854.52
      2763384.31      6896918.67
#Sta/Elev= 30
  4378.3  503.78  4562.9  503.57  4641.9  503.05  4698.3  502.21  4714.3  502.31
  4729.5  501.83  4825.4  500.74  4833.6  500.95  4859.0  500.62  4875.3  500.93
  4892.6  499.93  4965.0  498.87  4970.2  499.01  4979.4  498.64  4998.6  497.08
  5003.8  497.47  5004.4  496.74  5004.7  496.24  5008.2  496.24  5008.4  496.74
  5011.5  496.74  5030.8  498.95  5041.0  499.18  5071.4  499.36  5076.8  498.97
  5101.8  499.59  5132.2  499.88  5243.7  500.32  5335.0  501.59  5397.5  501.01
#Mann=3,-1,0
  4378.3    0.15       0  5004.4    0.05       0  5008.4    0.15       0
Bank Sta=5004.4,5008.4
Exp/Cntr=0.3,0.1

Type RM Length L Ch R = 1,2978,396,396,396
BEGIN DESCRIPTION:
Lacy 049 2672
END DESCRIPTION:
XS GIS Cut Line= 3
      2764251.04      6896561.14      2763748.99      6896550.96
      2763445.98      6896794.66
#Sta/Elev= 30
  4524.8  501.38  4609.9  501.28  4669.9  500.77  4769.9  500.61  4849.9  499.70
  4869.9  499.09  4879.9  499.63  4889.9  499.61  4909.9  498.77  4949.9  498.58
  4969.9  498.08  4979.9  497.64  4989.9  496.17  4997.9  495.85  4998.2  495.35
  5001.7  495.35  5001.9  495.85  5019.9  496.39  5050.5  496.16  5085.7  496.67
  5093.7  497.11  5114.5  496.84  5164.1  497.59  5192.9  497.72  5236.1  498.33
  5277.7  499.36  5335.3  499.83  5349.7  500.40  5364.1  500.31  5415.8  500.83
#Mann=3,-1,0
  4524.8    0.15       0  4997.9    0.05       0  5001.9    0.15       0
Bank Sta=4997.9,5001.9
Exp/Cntr=0.3,0.1

Type RM Length L Ch R = 1,2582,119,119,119
BEGIN DESCRIPTION:
Lacy 049 2673
END DESCRIPTION:
XS GIS Cut Line= 3
      2763865.17      6895999.67      2763626.35      6896211.46
      2763435.94      6896777.60
#Sta/Elev= 30
  4680.8  499.39  4695.0  499.22  4716.8  498.13  4731.0  497.96  4787.0  498.13
  4823.0  498.73  4872.3  498.19  4893.5  497.38  4915.0  496.06  4935.9  495.77
  4943.4  495.29  4950.1  494.23  4976.6  493.32  4976.8  492.82  4980.3  492.82
  4980.6  493.32  4992.8  494.06  5031.2  494.96  5084.4  494.77  5126.1  495.71
  5147.4  495.58  5268.1  496.28  5347.7  496.97  5394.2  497.93  5457.2  497.98
  5515.0  499.64  5520.2  499.28  5551.7  499.73  5569.2  500.48  5597.3  500.74
#Mann=3,-1,0
  4680.8    0.15       0  4976.6    0.05       0  4980.6    0.15       0
Bank Sta=4976.6,4980.6
Exp/Cntr=0.3,0.1

Type RM Length L Ch R = 1,2463,193,193,193
BEGIN DESCRIPTION:
Lacy 049 2689
END DESCRIPTION:
XS GIS Cut Line= 4
      2763860.04      6895980.01      2763582.57      6896111.91
      2763337.35      6896064.32      2762705.40      6896087.77
#Sta/Elev= 30
  4685.3  499.43  4725.5  498.24  4750.7  497.96  4839.1  498.41  4922.3  495.49
  4930.0  494.91  4992.5  493.85  4999.2  493.41  5111.3  493.42  5121.5  493.08
  5127.5  493.33  5132.6  492.86  5179.2  493.50  5184.3  493.00  5236.0  492.55
  5413.8  492.57  5481.8  491.60  5482.1  491.10  5485.6  491.10  5485.8  491.60
  5523.9  491.72  5558.1  492.50  5654.0  495.73  5704.0  496.74  5734.0  498.52
  5804.1  500.22  5823.1  501.56  5834.1  501.17  5844.1  501.38  5874.7  502.69
#Mann=3,-1,0
  4685.3    0.15       0  5481.8    0.05       0  5485.8    0.15       0
Bank Sta=5481.8,5485.8
Exp/Cntr=0.3,0.1

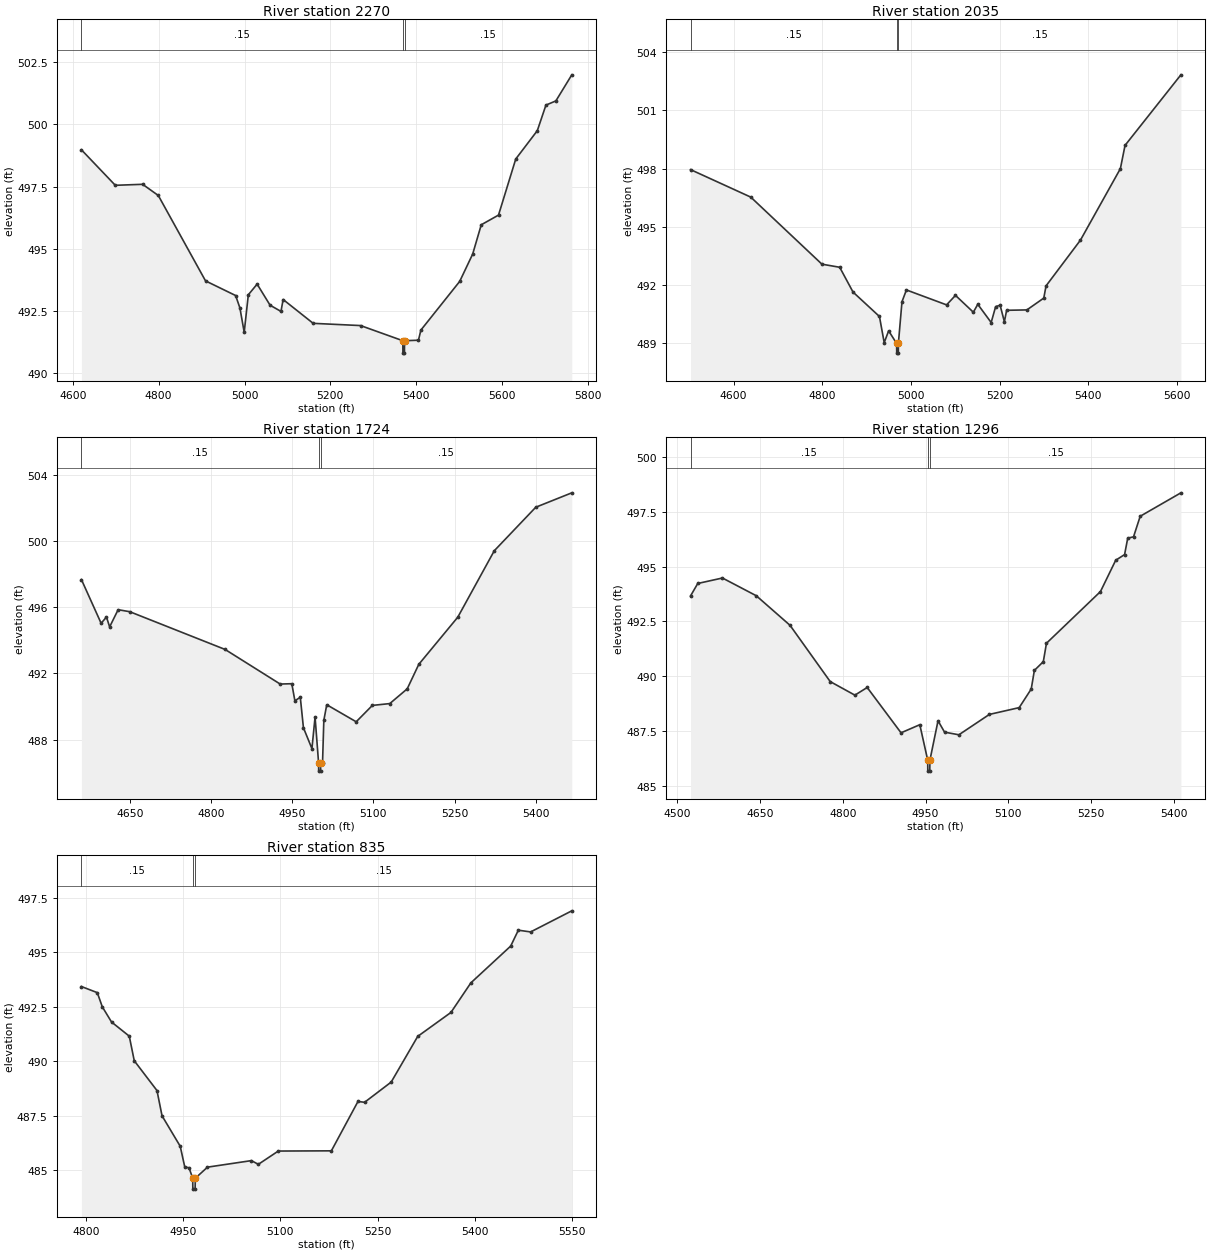
Type RM Length L Ch R = 1,2270,235,235,235
BEGIN DESCRIPTION:
Lacy 049 2671
END DESCRIPTION:
XS GIS Cut Line= 3
      2763834.81      6895968.58      2763441.97      6895989.24
      2762695.97      6896059.67
#Sta/Elev= 30
  4620.0  498.98  4698.9  497.55  4762.6  497.59  4799.1  497.14  4909.2  493.70
  4979.3  493.11  4989.3  492.61  4999.3  491.63  5008.9  493.14  5029.4  493.57
  5059.6  492.72  5085.0  492.47  5090.0  492.95  5160.0  491.99  5270.5  491.90
  5368.9  491.29  5369.2  490.79  5372.7  490.79  5372.9  491.29  5405.3  491.31
  5411.1  491.72  5501.5  493.68  5531.7  494.78  5551.7  495.96  5591.9  496.35
  5632.1  498.61  5682.3  499.75  5702.4  500.78  5725.6  500.95  5762.7  502.00
#Mann=3,-1,0
  4620.0    0.15       0  5368.9    0.05       0  5372.9    0.15       0
Bank Sta=5368.9,5372.9
Exp/Cntr=0.3,0.1

Type RM Length L Ch R = 1,2035,311,311,311
BEGIN DESCRIPTION:
Lacy 049 2670
END DESCRIPTION:
XS GIS Cut Line= 3
      2763751.48      6895851.81      2763255.85      6895891.29
      2762650.86      6895961.13
#Sta/Elev= 30
  4502.8  497.95  4638.7  496.53  4799.2  493.07  4839.3  492.91  4869.4  491.63
  4929.0  490.37  4939.7  489.02  4949.7  489.63  4967.7  488.98  4968.0  488.48
  4971.5  488.48  4971.7  488.98  4979.8  491.13  4989.8  491.74  5080.4  490.97
  5100.5  491.46  5140.8  490.59  5150.8  491.00  5181.0  490.06  5191.1  490.88
  5201.2  490.95  5210.8  490.10  5215.9  490.69  5261.6  490.71  5299.7  491.32
  5304.8  491.95  5382.4  494.31  5472.5  498.00  5483.0  499.20  5609.0  502.84
#Mann=3,-1,0
  4502.8    0.15       0  4967.7    0.05       0  4971.7    0.15       0
Bank Sta=4967.7,4971.7
Exp/Cntr=0.3,0.1

Type RM Length L Ch R = 1,1724,428,428,428
BEGIN DESCRIPTION:
Lacy 049 2669
END DESCRIPTION:
XS GIS Cut Line= 3
      2763426.84      6895560.24      2763041.84      6895784.58
      2762612.45      6895951.54
#Sta/Elev= 30
  4560.4  497.66  4596.8  495.02  4606.7  495.40  4612.5  494.80  4628.2  495.84
  4649.7  495.72  4825.9  493.44  4927.7  491.35  4949.2  491.37  4954.9  490.34
  4964.9  490.55  4970.7  488.71  4986.4  487.45  4992.2  489.36  4998.7  486.59
  4998.9  486.09  5002.4  486.09  5002.7  486.59  5006.0  486.59  5008.4  489.16
  5013.8  490.10  5068.2  489.07  5098.1  490.06  5130.3  490.17  5162.5  491.06
  5183.9  492.54  5256.0  495.39  5323.4  499.40  5400.1  502.03  5466.7  502.90
#Mann=3,-1,0
  4560.4    0.15       0  4998.7    0.05       0  5002.7    0.15       0
Bank Sta=4998.7,5002.7
Exp/Cntr=0.3,0.1

Type RM Length L Ch R = 1,1296,461,461,461
BEGIN DESCRIPTION:
Lacy 049 2668
END DESCRIPTION:
XS GIS Cut Line= 3
      2763326.99      6895222.24      2762896.33      6895438.97
      2762702.40      6895795.75
#Sta/Elev= 30
  4524.3  493.66  4537.4  494.23  4582.1  494.48  4643.4  493.67  4704.5  492.32
  4777.3  489.75  4822.0  489.13  4844.3  489.48  4905.6  487.41  4939.6  487.78
  4953.9  486.16  4954.1  485.66  4957.6  485.66  4957.9  486.16  4972.6  487.96
  4984.4  487.44  5010.4  487.32  5065.6  488.25  5119.6  488.56  5141.4  489.41
  5147.1  490.26  5163.3  490.66  5169.0  491.50  5266.8  493.86  5294.4  495.29
  5310.5  495.55  5316.2  496.30  5326.7  496.36  5338.8  497.30  5412.5  498.37
#Mann=3,-1,0
  4524.3    0.15       0  4953.9    0.05       0  4957.9    0.15       0
Bank Sta=4953.9,4957.9
Exp/Cntr=0.3,0.1

Type RM Length L Ch R = 1,835,0,0,0
BEGIN DESCRIPTION:
Lacy 049 2667
END DESCRIPTION:
XS GIS Cut Line= 3
      2762892.25      6894932.33      2762734.30      6895066.74
      2762611.80      6895603.03
#Sta/Elev= 30
  4792.6  493.43  4817.1  493.15  4824.8  492.50  4839.1  491.80  4866.5  491.15
  4874.2  490.02  4909.3  488.65  4917.1  487.49  4945.2  486.09  4952.2  485.14
  4958.8  485.10  4964.5  484.62  4964.7  484.12  4968.2  484.12  4968.5  484.62
  4987.3  485.13  5055.1  485.43  5065.9  485.26  5096.7  485.87  5178.7  485.88
  5219.8  488.15  5230.0  488.11  5271.1  489.04  5312.1  491.14  5363.4  492.24
  5394.2  493.60  5455.7  495.29  5467.5  496.02  5486.5  495.94  5550.1  496.91
#Mann=3,-1,0
  4792.6    0.15       0  4964.5    0.05       0  4968.5    0.15       0
Bank Sta=4964.5,4968.5
Exp/Cntr=0.3,0.1

Chan Stop Cuts=-1