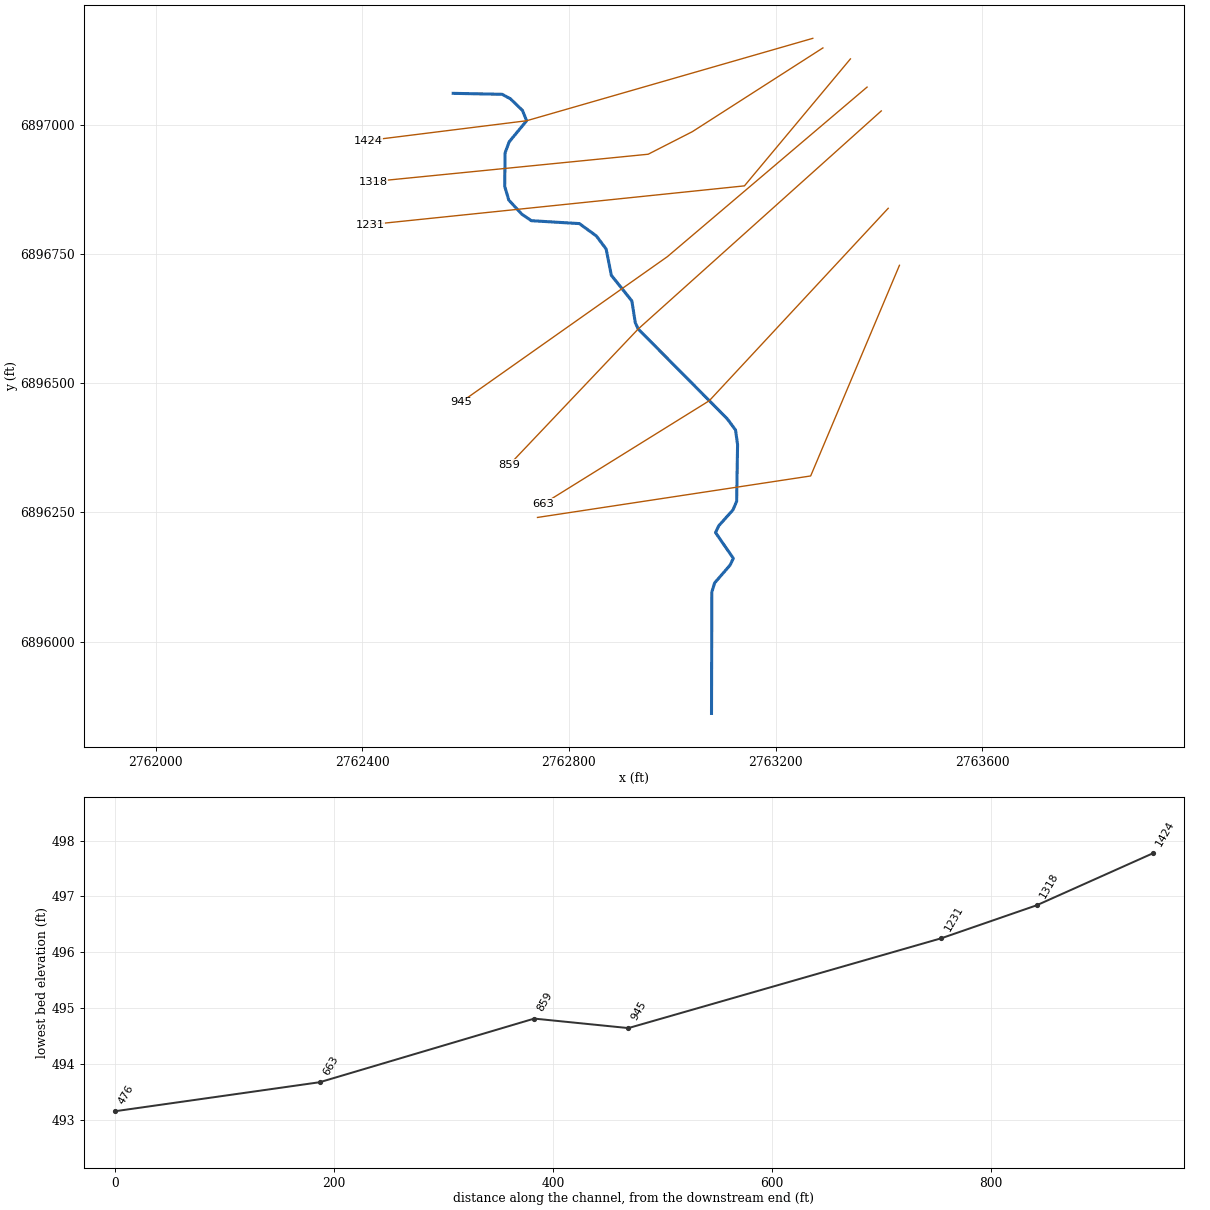
--- Lacy 050.prj (project) ---

Proj Title=Lacy 050 Base Level Engineering
Current Plan=p01
Default Exp/Contr=0.3,0.1
English Units
Geom File=g01
Flow File=f01
Plan File=p01
BEGIN DESCRIPTION:
Lacy 050
END DESCRIPTION:

--- Lacy 050.p01 (plan) ---

Plan Title=Multiple Run
Short Identifier=Multiple
Geom File=g01
Flow File=f01
Subcritical Flow
K Sum by GR= 0
Std Step Tol= 0.01
Critical Tol= 0.01
Num of Std Step Trials= 20
Max Error Tol= 0.3
Flow Tol Ratio= 0.001
Split Flow NTrial= 30
Split Flow Tol= 0.02
Split Flow Ratio= 0.02
Log Output Level= 0
Friction Slope Method= 1
Unsteady Friction Slope Method= 2
Unsteady Bridges Friction Slope Method= 1
Parabolic Critical Depth
Global Vel Dist=  1 , 1 , 1
Global Log Level= 0
CheckData=True
Encroach Param= -1, 0, 0, 0
BEGIN DESCRIPTION:
Multiple Run
END DESCRIPTION:

--- Lacy 050.f01 (steady flow) ---

Flow Title=Multiple
Number of Profiles=7
Profile Names=10-year,25-year,50-year,1pct_min,100-year,1pct_plu,500-year
River Rch & RM= Lacy 050,Reach-1,1424
     117     141     158      89     178     355     223
Boundary for River Rch & Prof#=Lacy 050,Reach-1,1
Up Type=0
Dn Type=3
Dn Slope=0.005
Boundary for River Rch & Prof#=Lacy 050,Reach-1,2
Up Type=0
Dn Type=3
Dn Slope=0.005
Boundary for River Rch & Prof#=Lacy 050,Reach-1,3
Up Type=0
Dn Type=3
Dn Slope=0.005
Boundary for River Rch & Prof#=Lacy 050,Reach-1,4
Up Type=0
Dn Type=3
Dn Slope=0.005
Boundary for River Rch & Prof#=Lacy 050,Reach-1,5
Up Type=0
Dn Type=3
Dn Slope=0.005
Boundary for River Rch & Prof#=Lacy 050,Reach-1,6
Up Type=0
Dn Type=3
Dn Slope=0.005
Boundary for River Rch & Prof#=Lacy 050,Reach-1,7
Up Type=0
Dn Type=3
Dn Slope=0.005

--- Lacy 050.g01 (geometry) ---

Geom Title=Existing Conditions

River Reach=Lacy 050,Reach-1
Reach XY= 30
      2762576.00      6897061.00      2762670.71      6897059.15
      2762686.64      6897050.58      2762709.97      6897028.15
      2762718.23      6897007.98      2762684.42      6896967.19
      2762676.52      6896945.78      2762675.75      6896880.94
      2762683.63      6896854.50      2762708.78      6896827.27
      2762727.25      6896814.52      2762820.29      6896808.92
      2762853.19      6896784.95      2762872.15      6896759.61
      2762882.11      6896708.84      2762921.81      6896659.27
      2762928.50      6896617.04      2762934.14      6896604.94
      2763106.40      6896431.16      2763122.47      6896409.53
      2763126.46      6896381.17      2763124.64      6896271.44
      2763117.57      6896254.81      2763090.07      6896224.16
      2763083.80      6896210.90      2763118.21      6896161.10
      2763111.93      6896147.84      2763082.00      6896113.45
      2763076.65      6896095.84      2763076.00      6895861.00

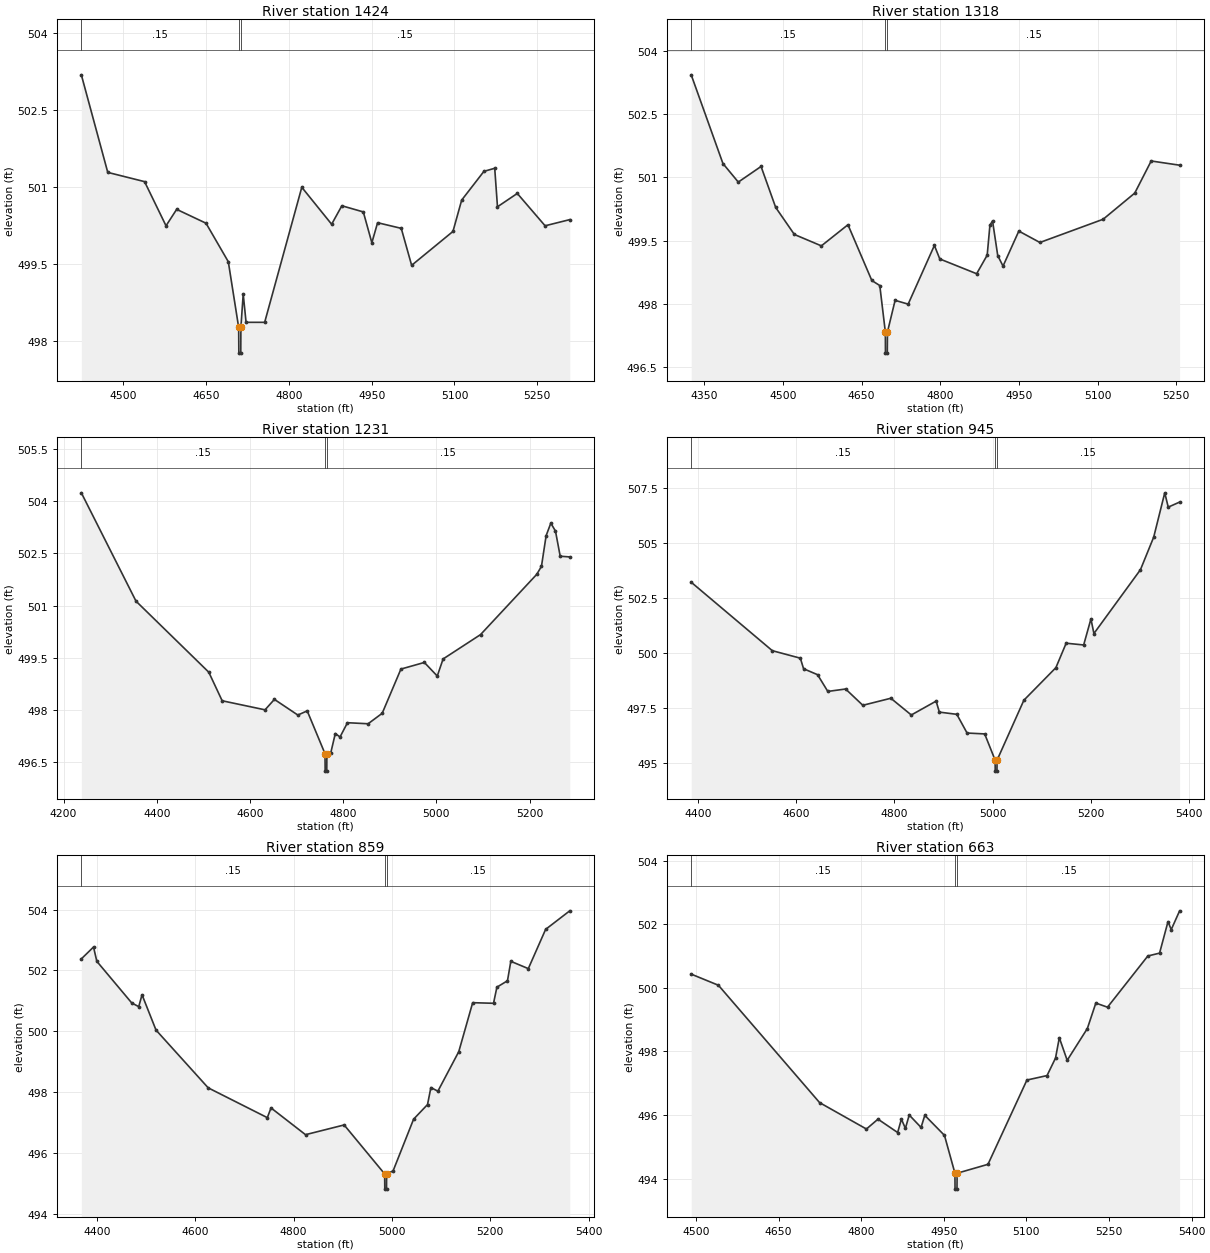
Type RM Length L Ch R = 1,1424,106,106,106
BEGIN DESCRIPTION:
Lacy 050 2695
END DESCRIPTION:
XS GIS Cut Line= 3
      2763272.03      6897167.46      2762718.23      6897007.98
      2762411.61      6896969.69
#Sta/Elev= 30
  4423.7  503.19  4471.6  501.29  4538.3  501.11  4577.2  500.25  4596.5  500.57
  4649.7  500.30  4690.1  499.55  4708.9  498.27  4709.2  497.77  4712.7  497.77
  4712.9  498.27  4717.1  498.92  4722.3  498.37  4756.0  498.37  4823.3  501.00
  4877.4  500.28  4895.9  500.64  4934.8  500.52  4950.3  499.92  4960.7  500.31
  5003.6  500.20  5022.4  499.48  5097.3  500.14  5113.1  500.75  5153.4  501.31
  5173.0  501.37  5178.0  500.62  5213.9  500.88  5264.3  500.25  5309.0  500.37
#Mann=3,-1,0
  4423.7    0.15       0  4708.9    0.05       0  4712.9    0.15       0
Bank Sta=4708.9,4712.9
Exp/Cntr=0.3,0.1

Type RM Length L Ch R = 1,1318,87,87,87
BEGIN DESCRIPTION:
Lacy 050 2694
END DESCRIPTION:
XS GIS Cut Line= 4
      2763291.58      6897148.89      2763038.90      6896986.82
      2762953.44      6896943.16      2762420.92      6896890.26
#Sta/Elev= 30
  4325.2  503.43  4385.7  501.33  4415.0  500.89  4458.4  501.26  4486.3  500.29
  4521.9  499.65  4573.4  499.38  4624.1  499.88  4669.6  498.56  4684.8  498.44
  4695.4  497.34  4695.6  496.84  4699.1  496.84  4699.4  497.34  4714.0  498.09
  4738.9  498.00  4788.9  499.39  4799.2  499.07  4869.5  498.72  4889.6  499.16
  4894.8  499.87  4899.8  499.97  4909.7  499.15  4919.8  498.90  4949.9  499.73
  4990.1  499.46  5110.7  500.01  5171.0  500.63  5202.3  501.39  5256.5  501.29
#Mann=3,-1,0
  4325.2    0.15       0  4695.4    0.05       0  4699.4    0.15       0
Bank Sta=4695.4,4699.4
Exp/Cntr=0.3,0.1

Type RM Length L Ch R = 1,1231,286,286,286
BEGIN DESCRIPTION:
Lacy 050 2693
END DESCRIPTION:
XS GIS Cut Line= 3
      2763344.87      6897127.67      2763139.74      6896881.93
      2762415.61      6896807.00
#Sta/Elev= 30
  4238.1  504.24  4355.4  501.13  4511.6  499.09  4540.3  498.27  4632.3  498.01
  4652.4  498.31  4702.7  497.86  4722.8  497.98  4761.0  496.75  4761.3  496.25
  4764.8  496.25  4765.0  496.75  4773.1  496.76  4783.1  497.33  4793.2  497.23
  4809.2  497.64  4853.5  497.61  4883.7  497.91  4923.9  499.18  4974.2  499.37
  5001.9  498.98  5014.4  499.47  5094.8  500.17  5215.4  501.90  5225.5  502.13
  5235.5  503.01  5245.6  503.37  5255.6  503.14  5265.7  502.42  5286.2  502.40
#Mann=3,-1,0
  4238.1    0.15       0  4761.0    0.05       0  4765.0    0.15       0
Bank Sta=4761,4765
Exp/Cntr=0.3,0.1

Type RM Length L Ch R = 1,945,86,86,86
BEGIN DESCRIPTION:
Lacy 050 2696
END DESCRIPTION:
XS GIS Cut Line= 3
      2763377.04      6897073.07      2762990.58      6896744.91
      2762591.23      6896463.21
#Sta/Elev= 30
  4385.6  503.22  4551.0  500.11  4608.1  499.77  4614.7  499.29  4643.2  499.02
  4664.1  498.26  4700.4  498.37  4735.5  497.63  4792.6  497.95  4834.3  497.19
  4884.9  497.82  4891.5  497.32  4927.1  497.22  4948.0  496.37  4983.9  496.33
  5005.2  495.14  5005.4  494.64  5008.9  494.64  5009.2  495.14  5063.8  497.86
  5129.1  499.34  5150.0  500.45  5185.7  500.37  5200.5  501.55  5206.6  500.89
  5301.5  503.79  5328.5  505.27  5351.0  507.28  5358.1  506.63  5381.3  506.86
#Mann=3,-1,0
  4385.6    0.15       0  5005.2    0.05       0  5009.2    0.15       0
Bank Sta=5005.2,5009.2
Exp/Cntr=0.3,0.1

Type RM Length L Ch R = 1,859,196,196,196
BEGIN DESCRIPTION:
Lacy 050 2692
END DESCRIPTION:
XS GIS Cut Line= 3
      2763404.57      6897026.99      2762934.14      6896604.94
      2762685.16      6896342.58
#Sta/Elev= 30
  4368.0  502.38  4392.8  502.77  4399.5  502.30  4470.6  500.93  4484.8  500.81
  4491.5  501.20  4519.9  500.04  4626.1  498.14  4746.4  497.16  4753.9  497.48
  4824.1  496.60  4902.7  496.92  4985.1  495.31  4985.4  494.81  4988.9  494.81
  4989.1  495.31  5002.3  495.41  5044.0  497.11  5072.3  497.59  5079.2  498.15
  5093.4  498.03  5135.9  499.33  5164.2  500.94  5206.6  500.92  5213.5  501.45
  5235.0  501.66  5241.8  502.30  5277.4  502.06  5312.6  503.35  5361.7  503.96
#Mann=3,-1,0
  4368.0    0.15       0  4985.1    0.05       0  4989.1    0.15       0
Bank Sta=4985.1,4989.1
Exp/Cntr=0.3,0.1

Type RM Length L Ch R = 1,663,187,187,187
BEGIN DESCRIPTION:
Lacy 050 2690
END DESCRIPTION:
XS GIS Cut Line= 3
      2763417.99      6896838.53      2763071.74      6896466.12
      2762750.52      6896266.50
#Sta/Elev= 30
  4491.5  500.43  4540.9  500.08  4724.6  496.39  4809.6  495.56  4830.6  495.87
  4866.3  495.45  4873.1  495.87  4880.4  495.58  4887.3  496.00  4908.8  495.61
  4915.6  495.99  4951.3  495.36  4970.3  494.17  4970.5  493.67  4974.0  493.67
  4974.3  494.17  5030.3  494.45  5101.0  497.10  5137.5  497.24  5152.9  497.79
  5159.8  498.43  5174.1  497.72  5210.7  498.72  5226.1  499.52  5247.3  499.39
  5320.5  501.00  5341.8  501.09  5357.1  502.08  5363.0  501.83  5378.2  502.42
#Mann=3,-1,0
  4491.5    0.15       0  4970.3    0.05       0  4974.3    0.15       0
Bank Sta=4970.3,4974.3
Exp/Cntr=0.3,0.1

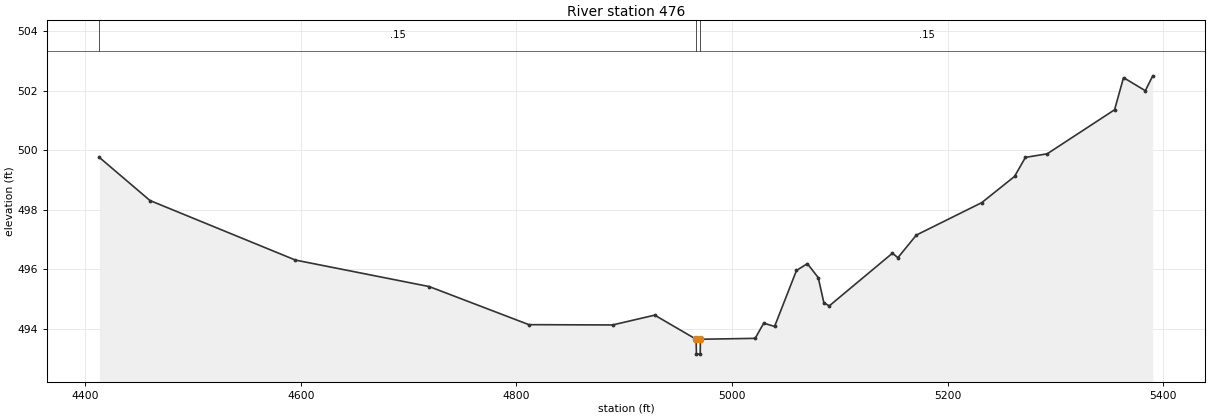
Type RM Length L Ch R = 1,476,0,0,0
BEGIN DESCRIPTION:
Lacy 050 2691
END DESCRIPTION:
XS GIS Cut Line= 3
      2763439.75      6896728.20      2763267.92      6896320.50
      2762739.22      6896240.19
#Sta/Elev= 30
  4413.1  499.76  4460.1  498.31  4595.0  496.31  4719.1  495.42  4811.6  494.14
  4889.2  494.13  4928.3  494.46  4966.7  493.65  4967.0  493.15  4970.5  493.15
  4970.7  493.65  5021.5  493.68  5029.4  494.19  5039.5  494.08  5059.8  495.96
  5069.9  496.19  5080.0  495.72  5085.2  494.88  5090.2  494.77  5148.8  496.54
  5153.9  496.39  5171.0  497.15  5231.7  498.24  5262.1  499.12  5272.2  499.76
  5292.4  499.88  5354.9  501.36  5363.2  502.44  5383.4  502.00  5390.3  502.50
#Mann=3,-1,0
  4413.1    0.15       0  4966.7    0.05       0  4970.7    0.15       0
Bank Sta=4966.7,4970.7
Exp/Cntr=0.3,0.1

Chan Stop Cuts=-1