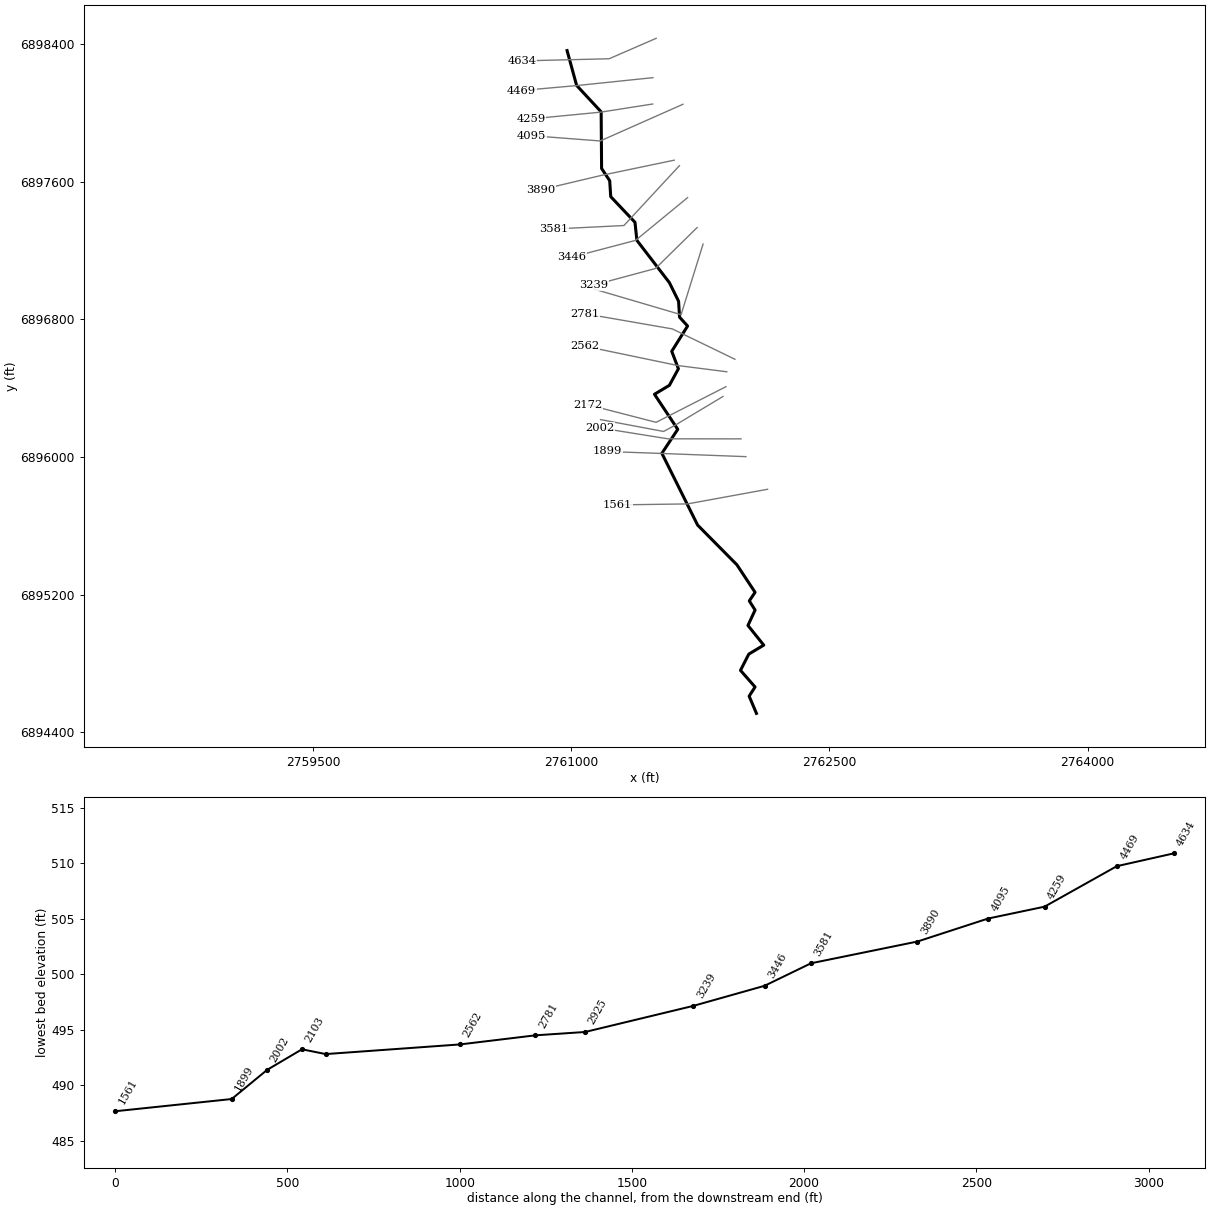
--- Lacy 051.prj (project) ---

Proj Title=Lacy 051 Base Level Engineering
Current Plan=p01
Default Exp/Contr=0.3,0.1
English Units
Geom File=g01
Flow File=f01
Plan File=p01
BEGIN DESCRIPTION:
Lacy 051
END DESCRIPTION:

--- Lacy 051.p01 (plan) ---

Plan Title=Multiple Run
Short Identifier=Multiple
Geom File=g01
Flow File=f01
Subcritical Flow
K Sum by GR= 0
Std Step Tol= 0.01
Critical Tol= 0.01
Num of Std Step Trials= 20
Max Error Tol= 0.3
Flow Tol Ratio= 0.001
Split Flow NTrial= 30
Split Flow Tol= 0.02
Split Flow Ratio= 0.02
Log Output Level= 0
Friction Slope Method= 1
Unsteady Friction Slope Method= 2
Unsteady Bridges Friction Slope Method= 1
Parabolic Critical Depth
Global Vel Dist=  1 , 1 , 1
Global Log Level= 0
CheckData=True
Encroach Param= -1, 0, 0, 0
BEGIN DESCRIPTION:
Multiple Run
END DESCRIPTION:

--- Lacy 051.f01 (steady flow) ---

Flow Title=Multiple
Number of Profiles=7
Profile Names=10-year,25-year,50-year,1pct_min,100-year,1pct_plu,500-year
River Rch & RM= Lacy 051,Reach-1,4634
      87     103     114      63     126     252     154
River Rch & RM= Lacy 051,Reach-1,2781
     200     250     288     165     330     658     432
Boundary for River Rch & Prof#=Lacy 051,Reach-1,1
Up Type=0
Dn Type=3
Dn Slope=0.005
Boundary for River Rch & Prof#=Lacy 051,Reach-1,2
Up Type=0
Dn Type=3
Dn Slope=0.005
Boundary for River Rch & Prof#=Lacy 051,Reach-1,3
Up Type=0
Dn Type=3
Dn Slope=0.005
Boundary for River Rch & Prof#=Lacy 051,Reach-1,4
Up Type=0
Dn Type=3
Dn Slope=0.005
Boundary for River Rch & Prof#=Lacy 051,Reach-1,5
Up Type=0
Dn Type=3
Dn Slope=0.005
Boundary for River Rch & Prof#=Lacy 051,Reach-1,6
Up Type=0
Dn Type=3
Dn Slope=0.005
Boundary for River Rch & Prof#=Lacy 051,Reach-1,7
Up Type=0
Dn Type=3
Dn Slope=0.005

--- Lacy 051.g01 (geometry) ---

Geom Title=Existing Conditions

River Reach=Lacy 051,Reach-1
Reach XY= 30
      2760976.00      6898361.00      2761031.52      6898158.57
      2761173.94      6898005.15      2761176.52      6897676.22
      2761223.64      6897605.02      2761229.61      6897512.50
      2761370.48      6897363.43      2761381.54      6897258.58
      2761570.16      6897013.29      2761623.70      6896905.05
      2761629.39      6896812.40      2761676.00      6896761.00
      2761584.05      6896614.31      2761622.64      6896512.71
      2761570.35      6896416.61      2761483.70      6896364.64
      2761618.90      6896161.00      2761526.70      6896021.70
      2761734.14      6895604.94      2761962.37      6895374.21
      2762068.00      6895214.33      2762034.56      6895164.34
      2762068.19      6895111.09      2762026.66      6895021.64
      2762118.47      6894907.43      2762031.62      6894855.38
      2761983.30      6894760.94      2762068.00      6894664.34
      2762033.58      6894611.07      2762076.00      6894511.00

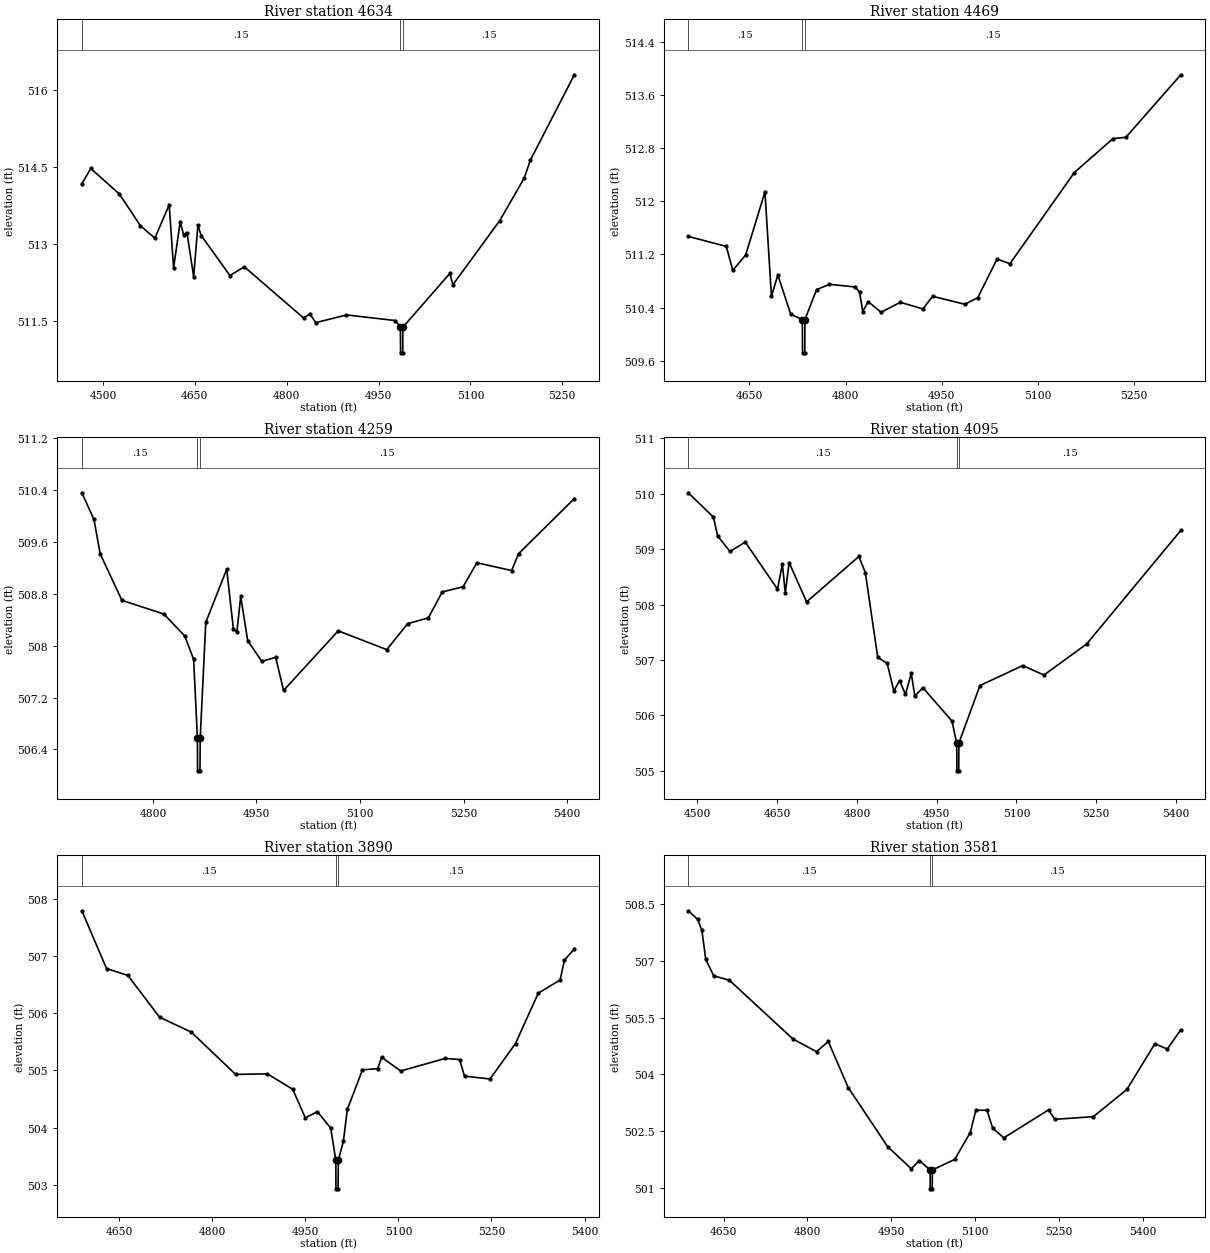
Type RM Length L Ch R = 1,4634,165,165,165
BEGIN DESCRIPTION:
Lacy 051 3476
END DESCRIPTION:
XS GIS Cut Line= 3
      2761493.40      6898432.15      2761220.53      6898313.52
      2760714.12      6898301.11
#Sta/Elev= 30
  4465.6  514.17  4480.1  514.47  4527.0  513.97  4561.3  513.35  4584.8  513.11
  4608.2  513.76  4615.4  512.53  4626.2  513.43  4631.6  513.18  4637.2  513.22
  4648.1  512.36  4655.1  513.36  4660.5  513.16  4707.4  512.38  4730.9  512.55
  4827.7  511.55  4837.7  511.63  4847.7  511.46  4897.7  511.61  4977.7  511.50
  4985.7  511.37  4986.0  510.87  4989.5  510.87  4989.7  511.37  5066.4  512.42
  5071.4  512.20  5147.8  513.45  5187.8  514.28  5197.8  514.63  5269.7  516.30
#Mann=3,-1,0
  4465.6    0.15       0  4985.7    0.05       0  4989.7    0.15       0
Bank Sta=4985.7,4989.7
Exp/Cntr=0.3,0.1

Type RM Length L Ch R = 1,4469,210,210,210
BEGIN DESCRIPTION:
Lacy 051 2660
END DESCRIPTION:
XS GIS Cut Line= 3
      2761474.89      6898203.74      2761030.69      6898157.64
      2760710.65      6898129.04
#Sta/Elev= 30
  4554.9  511.47  4614.1  511.32  4624.2  510.96  4644.3  511.19  4674.4  512.14
  4684.5  510.57  4694.5  510.89  4714.6  510.30  4732.7  510.22  4733.0  509.72
  4736.5  509.72  4736.7  510.22  4754.9  510.67  4775.0  510.75  4815.2  510.71
  4821.9  510.63  4826.9  510.34  4835.3  510.49  4855.4  510.33  4885.6  510.48
  4920.6  510.38  4935.8  510.57  4986.1  510.45  5006.3  510.55  5036.3  511.13
  5056.4  511.06  5156.8  512.43  5217.0  512.94  5237.1  512.96  5322.8  513.90
#Mann=3,-1,0
  4554.9    0.15       0  4732.7    0.05       0  4736.7    0.15       0
Bank Sta=4732.7,4736.7
Exp/Cntr=0.3,0.1

Type RM Length L Ch R = 1,4259,164,164,164
BEGIN DESCRIPTION:
Lacy 051 2661
END DESCRIPTION:
XS GIS Cut Line= 3
      2761473.30      6898050.72      2761172.32      6898003.51
      2760765.59      6897964.11
#Sta/Elev= 30
  4697.1  510.36  4714.6  509.95  4723.6  509.42  4755.1  508.70  4815.8  508.49
  4846.2  508.15  4859.0  507.79  4864.5  506.57  4864.7  506.07  4868.2  506.07
  4868.5  506.57  4876.6  508.36  4906.9  509.18  4916.6  508.26  4921.6  508.21
  4927.2  508.76  4937.3  508.08  4957.6  507.76  4977.8  507.82  4989.3  507.31
  5068.4  508.23  5138.7  507.94  5168.9  508.34  5199.0  508.43  5219.1  508.83
  5249.2  508.91  5269.3  509.28  5319.6  509.16  5329.6  509.42  5410.4  510.27
#Mann=3,-1,0
  4697.1    0.15       0  4864.5    0.05       0  4868.5    0.15       0
Bank Sta=4864.5,4868.5
Exp/Cntr=0.3,0.1

Type RM Length L Ch R = 1,4095,205,205,205
BEGIN DESCRIPTION:
Lacy 051 3475
END DESCRIPTION:
XS GIS Cut Line= 3
      2761649.28      6898049.26      2761168.46      6897835.98
      2760769.45      6897866.75
#Sta/Elev= 30
  4482.8  510.02  4530.1  509.58  4537.9  509.24  4561.2  508.96  4589.9  509.13
  4650.5  508.28  4659.7  508.73  4665.2  508.21  4672.4  508.76  4705.2  508.05
  4803.6  508.87  4815.7  508.58  4839.0  507.05  4856.8  506.94  4869.3  506.44
  4880.1  506.63  4891.2  506.38  4902.1  506.76  4908.8  506.35  4924.0  506.50
  4978.6  505.90  4987.6  505.50  4987.9  505.00  4991.4  505.00  4991.6  505.50
  5031.3  506.54  5111.6  506.90  5151.7  506.73  5231.9  507.29  5409.0  509.34
#Mann=3,-1,0
  4482.8    0.15       0  4987.6    0.05       0  4991.6    0.15       0
Bank Sta=4987.6,4991.6
Exp/Cntr=0.3,0.1

Type RM Length L Ch R = 1,3890,309,309,309
BEGIN DESCRIPTION:
Lacy 051 3473
END DESCRIPTION:
XS GIS Cut Line= 3
      2761598.61      6897724.39      2761178.51      6897636.76
      2760823.76      6897552.76
#Sta/Elev= 30
  4589.8  507.79  4629.6  506.78  4664.0  506.66  4715.0  505.93  4766.1  505.67
  4837.6  504.93  4888.7  504.94  4929.7  504.67  4950.0  504.17  4969.5  504.28
  4990.9  503.99  4999.1  503.43  4999.3  502.93  5002.8  502.93  5003.1  503.43
  5011.3  503.76  5017.7  504.32  5042.1  505.01  5066.7  505.03  5072.9  505.23
  5103.7  504.99  5175.7  505.21  5198.6  505.19  5206.5  504.90  5247.6  504.85
  5288.7  505.47  5325.4  506.35  5360.6  506.58  5367.6  506.93  5383.5  507.12
#Mann=3,-1,0
  4589.8    0.15       0  4999.1    0.05       0  5003.1    0.15       0
Bank Sta=4999.1,5003.1
Exp/Cntr=0.3,0.1

Type RM Length L Ch R = 1,3581,135,135,135
BEGIN DESCRIPTION:
Lacy 051 3474
END DESCRIPTION:
XS GIS Cut Line= 3
      2761628.69      6897692.55      2761306.32      6897344.77
      2760899.62      6897324.67
#Sta/Elev= 30
  4587.0  508.33  4603.9  508.10  4611.3  507.81  4618.1  507.05  4632.3  506.61
  4660.6  506.49  4774.0  504.94  4816.5  504.60  4837.5  504.87  4873.2  503.65
  4943.6  502.09  4986.1  501.50  5000.2  501.72  5019.8  501.47  5020.0  500.97
  5023.5  500.97  5023.8  501.47  5063.9  501.75  5091.6  502.46  5101.6  503.05
  5121.6  503.05  5131.6  502.58  5151.6  502.32  5231.7  503.06  5242.8  502.81
  5311.8  502.88  5371.9  503.60  5422.0  504.81  5444.2  504.67  5468.4  505.18
#Mann=3,-1,0
  4587.0    0.15       0  5019.8    0.05       0  5023.8    0.15       0
Bank Sta=5019.8,5023.8
Exp/Cntr=0.3,0.1

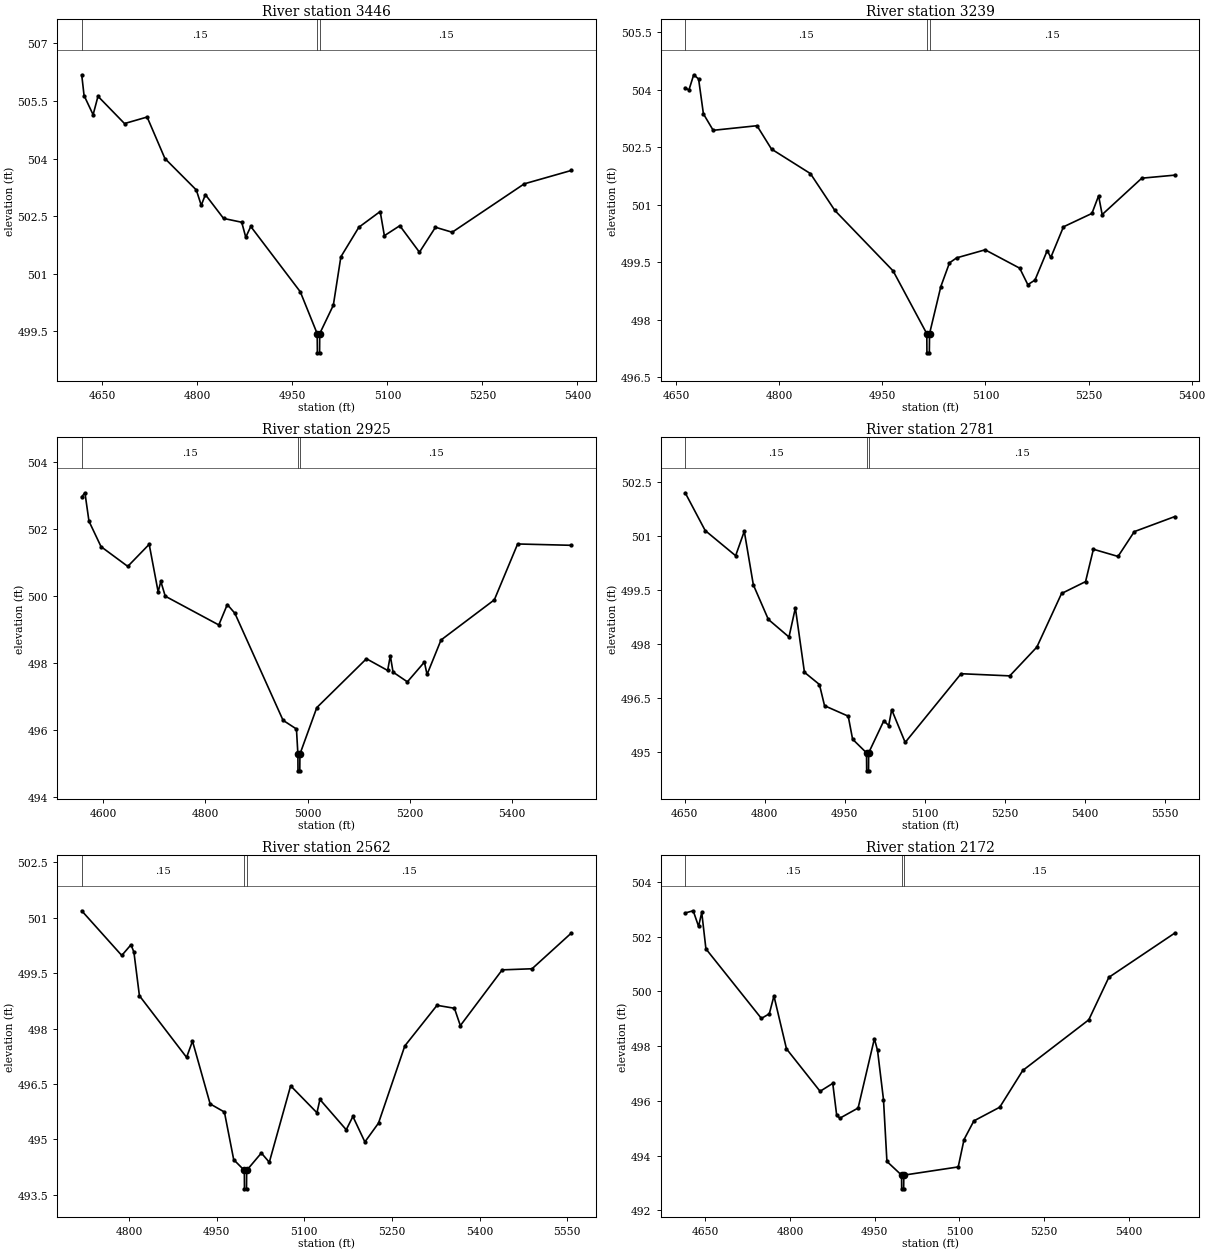
Type RM Length L Ch R = 1,3446,207,207,207
BEGIN DESCRIPTION:
Lacy 051 2657
END DESCRIPTION:
XS GIS Cut Line= 3
      2761675.83      6897506.72      2761373.90      6897258.57
      2761003.82      6897161.19
#Sta/Elev= 30
  4617.2  506.18  4620.9  505.64  4635.2  505.14  4642.9  505.62  4684.8  504.91
  4720.5  505.08  4748.6  504.00  4798.2  503.18  4806.0  502.78  4812.5  503.06
  4841.2  502.44  4869.9  502.34  4876.3  501.95  4884.2  502.23  4962.4  500.53
  4989.1  499.44  4989.4  498.94  4992.9  498.94  4993.1  499.44  5014.6  500.18
  5026.5  501.44  5054.9  502.21  5088.6  502.62  5095.2  501.99  5119.6  502.25
  5150.6  501.56  5175.9  502.21  5202.3  502.08  5316.1  503.34  5390.7  503.69
#Mann=3,-1,0
  4617.2    0.15       0  4989.1    0.05       0  4993.1    0.15       0
Bank Sta=4989.1,4993.1
Exp/Cntr=0.3,0.1

Type RM Length L Ch R = 1,3239,314,314,314
BEGIN DESCRIPTION:
Lacy 051 2650
END DESCRIPTION:
XS GIS Cut Line= 3
      2761731.38      6897333.14      2761489.36      6897095.15
      2761129.48      6896998.36
#Sta/Elev= 30
  4663.5  504.05  4668.9  503.99  4675.9  504.39  4683.0  504.28  4690.0  503.37
  4704.2  502.94  4767.9  503.06  4789.0  502.45  4845.6  501.81  4881.0  500.85
  4965.8  499.27  5014.8  497.63  5015.0  497.13  5018.5  497.13  5018.8  497.63
  5035.2  498.86  5047.8  499.48  5058.2  499.61  5099.6  499.82  5149.9  499.34
  5161.7  498.91  5172.1  499.03  5189.9  499.80  5195.1  499.62  5213.5  500.42
  5254.9  500.77  5264.6  501.23  5269.8  500.74  5327.4  501.69  5375.6  501.77
#Mann=3,-1,0
  4663.5    0.15       0  5014.8    0.05       0  5018.8    0.15       0
Bank Sta=5014.8,5018.8
Exp/Cntr=0.3,0.1

Type RM Length L Ch R = 1,2925,144,144,144
BEGIN DESCRIPTION:
Lacy 051 2649
END DESCRIPTION:
XS GIS Cut Line= 3
      2761766.01      6897237.05      2761638.20      6896826.90
      2761131.19      6896976.07
#Sta/Elev= 30
  4558.0  502.97  4564.3  503.09  4572.2  502.24  4595.8  501.48  4648.1  500.89
  4690.0  501.55  4707.5  500.13  4712.8  500.44  4721.4  500.00  4826.2  499.14
  4842.8  499.75  4857.6  499.49  4951.9  496.29  4978.1  496.03  4980.9  495.28
  4981.1  494.78  4984.6  494.78  4984.9  495.28  5017.9  496.67  5115.0  498.13
  5156.5  497.78  5161.7  498.22  5167.1  497.73  5195.1  497.44  5228.4  498.03
  5233.6  497.66  5260.9  498.69  5365.2  499.89  5410.8  501.56  5516.1  501.52
#Mann=3,-1,0
  4558.0    0.15       0  4980.9    0.05       0  4984.9    0.15       0
Bank Sta=4980.9,4984.9
Exp/Cntr=0.3,0.1

Type RM Length L Ch R = 1,2781,219,219,219
BEGIN DESCRIPTION:
Lacy 051 2648
END DESCRIPTION:
XS GIS Cut Line= 3
      2761951.07      6896567.87      2761587.42      6896744.26
      2761080.89      6896832.27
#Sta/Elev= 30
  4650.8  502.21  4688.3  501.16  4745.4  500.46  4761.6  501.14  4778.6  499.65
  4806.7  498.69  4845.4  498.20  4857.4  499.01  4874.4  497.22  4902.5  496.88
  4912.1  496.29  4956.5  496.00  4964.7  495.36  4990.8  494.98  4991.1  494.48
  4994.6  494.48  4994.8  494.98  5023.2  495.87  5032.4  495.74  5038.0  496.18
  5063.3  495.27  5168.1  497.18  5259.4  497.12  5310.2  497.92  5356.5  499.41
  5401.5  499.74  5416.2  500.64  5462.4  500.44  5492.9  501.13  5569.1  501.55
#Mann=3,-1,0
  4650.8    0.15       0  4990.8    0.05       0  4994.8    0.15       0
Bank Sta=4990.8,4994.8
Exp/Cntr=0.3,0.1

Type RM Length L Ch R = 1,2562,390,390,390
BEGIN DESCRIPTION:
Lacy 051 2645
END DESCRIPTION:
XS GIS Cut Line= 3
      2761903.94      6896495.27      2761618.85      6896531.58
      2761079.98      6896643.70
#Sta/Elev= 30
  4719.3  501.19  4787.8  499.98  4803.6  500.27  4808.6  500.07  4818.0  498.89
  4898.7  497.22  4908.8  497.66  4939.0  495.96  4963.4  495.74  4979.3  494.45
  4997.5  494.16  4997.7  493.66  5001.2  493.66  5001.5  494.16  5026.6  494.63
  5040.2  494.38  5076.7  496.45  5121.7  495.72  5126.8  496.08  5171.8  495.26
  5183.2  495.62  5203.7  494.93  5227.0  495.44  5272.0  497.53  5327.1  498.63
  5356.9  498.55  5367.0  498.08  5438.6  499.59  5489.7  499.62  5557.1  500.59
#Mann=3,-1,0
  4719.3    0.15       0  4997.5    0.05       0  5001.5    0.15       0
Bank Sta=4997.5,5001.5
Exp/Cntr=0.3,0.1

Type RM Length L Ch R = 1,2172,69,69,69
BEGIN DESCRIPTION:
Lacy 051 2646
END DESCRIPTION:
XS GIS Cut Line= 3
      2761898.68      6896408.55      2761493.11      6896201.62
      2761094.57      6896304.44
#Sta/Elev= 30
  4614.5  502.86  4628.7  502.94  4638.2  502.37  4643.8  502.88  4651.2  501.55
  4749.4  499.01  4763.4  499.18  4771.6  499.83  4793.8  497.90  4853.3  496.35
  4875.7  496.64  4882.7  495.47  4888.4  495.37  4920.6  495.74  4949.4  498.27
  4955.0  497.84  4965.5  496.05  4971.6  493.79  4997.5  493.29  4997.7  492.79
  5001.2  492.79  5001.5  493.29  5097.8  493.59  5108.1  494.59  5125.5  495.27
  5171.3  495.77  5212.0  497.11  5328.9  498.96  5364.4  500.51  5481.4  502.13
#Mann=3,-1,0
  4614.5    0.15       0  4997.5    0.05       0  5001.5    0.15       0
Bank Sta=4997.5,5001.5
Exp/Cntr=0.3,0.1

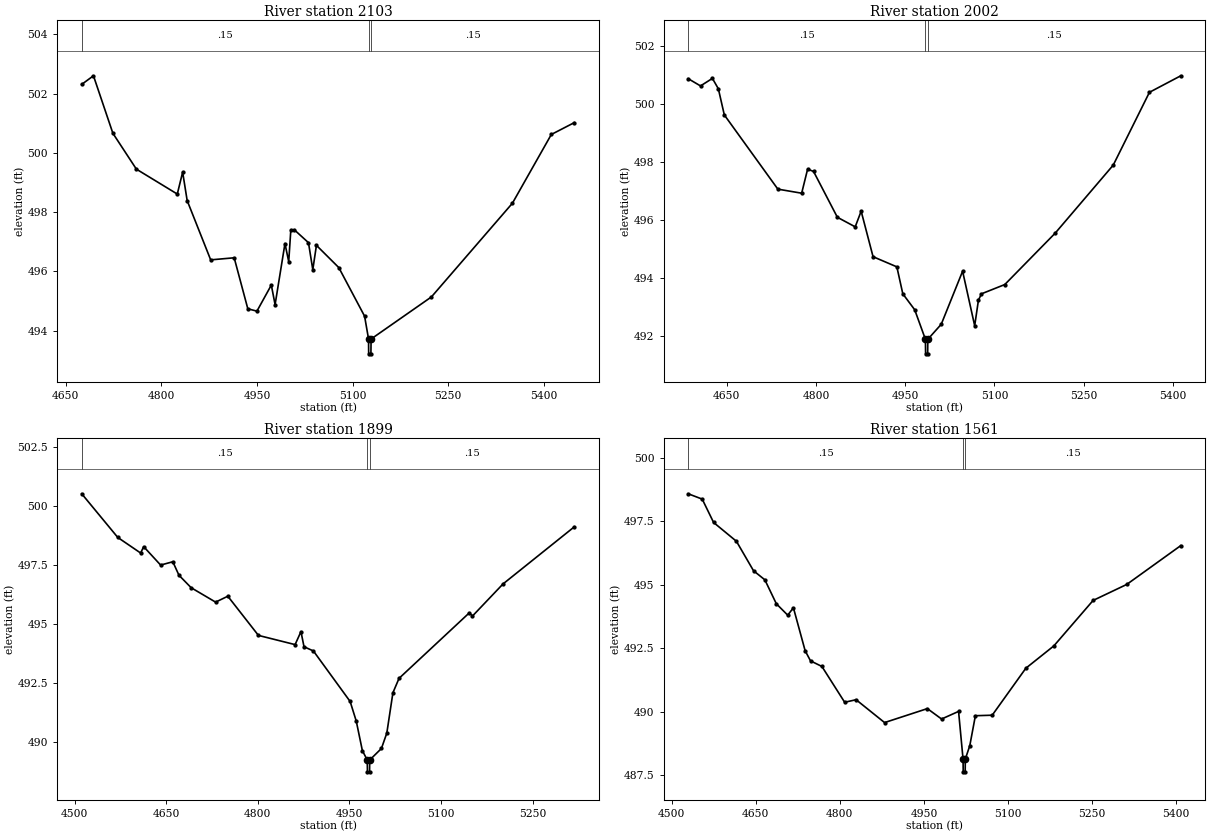
Type RM Length L Ch R = 1,2103,101,101,101
BEGIN DESCRIPTION:
Lacy 051 2644
END DESCRIPTION:
XS GIS Cut Line= 4
      2761881.78      6896351.88      2761599.91      6896182.59
      2761536.58      6896148.57      2761170.49      6896217.44
#Sta/Elev= 30
  4674.9  502.31  4693.3  502.60  4723.8  500.66  4760.7  499.45  4824.9  498.61
  4833.3  499.35  4840.4  498.39  4877.3  496.39  4914.2  496.46  4935.6  494.74
  4949.9  494.66  4972.5  495.54  4978.4  494.88  4993.9  496.94  4999.8  496.33
  5003.1  497.40  5008.8  497.40  5030.8  496.97  5037.6  496.06  5043.3  496.88
  5078.4  496.13  5118.9  494.49  5125.1  493.72  5125.3  493.22  5128.8  493.22
  5129.1  493.72  5223.8  495.14  5350.9  498.30  5412.0  500.62  5448.1  501.02
#Mann=3,-1,0
  4674.9    0.15       0  5125.1    0.05       0  5129.1    0.15       0
Bank Sta=5125.1,5129.1
Exp/Cntr=0.3,0.1

Type RM Length L Ch R = 1,2002,103,103,103
BEGIN DESCRIPTION:
Lacy 051 2643
END DESCRIPTION:
XS GIS Cut Line= 3
      2761986.75      6896105.49      2761561.46      6896105.88
      2761163.94      6896169.74
#Sta/Elev= 30
  4585.2  500.86  4605.9  500.61  4625.9  500.87  4635.9  500.51  4645.9  499.61
  4735.9  497.05  4775.9  496.91  4785.9  497.74  4795.9  497.66  4835.9  496.08
  4865.9  495.75  4875.9  496.29  4895.9  494.72  4935.9  494.37  4945.9  493.44
  4965.9  492.89  4983.9  491.87  4984.2  491.37  4987.7  491.37  4987.9  491.87
  5010.5  492.39  5046.4  494.22  5066.7  492.34  5073.0  493.22  5078.1  493.44
  5117.3  493.76  5201.9  495.53  5299.6  497.88  5360.4  500.39  5413.1  500.96
#Mann=3,-1,0
  4585.2    0.15       0  4983.9    0.05       0  4987.9    0.15       0
Bank Sta=4983.9,4987.9
Exp/Cntr=0.3,0.1

Type RM Length L Ch R = 1,1899,338,338,338
BEGIN DESCRIPTION:
Lacy 051 2640
END DESCRIPTION:
XS GIS Cut Line= 3
      2762014.97      6896002.27      2761528.71      6896020.65
      2761209.33      6896032.20
#Sta/Elev= 30
  4511.8  500.52  4570.8  498.67  4608.2  498.01  4613.2  498.28  4640.9  497.50
  4660.9  497.64  4670.9  497.07  4690.9  496.54  4730.9  495.93  4750.9  496.18
  4801.0  494.52  4861.0  494.13  4870.6  494.68  4875.6  494.04  4891.0  493.86
  4951.1  491.72  4961.1  490.89  4971.1  489.64  4979.1  489.24  4979.4  488.74
  4982.9  488.74  4983.1  489.24  5002.3  489.73  5011.1  490.38  5021.1  492.09
  5031.1  492.70  5146.3  495.48  5151.3  495.34  5201.3  496.70  5318.0  499.12
#Mann=3,-1,0
  4511.8    0.15       0  4979.1    0.05       0  4983.1    0.15       0
Bank Sta=4979.1,4983.1
Exp/Cntr=0.3,0.1

Type RM Length L Ch R = 1,1561,0,0,0
BEGIN DESCRIPTION:
Lacy 051 2642
END DESCRIPTION:
XS GIS Cut Line= 3
      2762140.60      6895812.68      2761675.22      6895727.67
      2761269.64      6895722.05
#Sta/Elev= 30
  4529.5  498.59  4554.5  498.38  4574.8  497.46  4615.5  496.72  4646.0  495.56
  4666.3  495.20  4686.7  494.26  4707.0  493.81  4717.2  494.10  4738.1  492.41
  4747.7  492.01  4768.0  491.79  4808.6  490.38  4829.0  490.48  4879.8  489.58
  4956.1  490.13  4981.5  489.72  5011.8  490.02  5019.8  488.14  5020.1  487.64
  5023.6  487.64  5023.8  488.14  5031.8  488.67  5041.8  489.85  5071.8  489.87
  5131.8  491.72  5181.8  492.60  5251.8  494.39  5311.8  495.02  5408.2  496.55
#Mann=3,-1,0
  4529.5    0.15       0  5019.8    0.05       0  5023.8    0.15       0
Bank Sta=5019.8,5023.8
Exp/Cntr=0.3,0.1

Chan Stop Cuts=-1