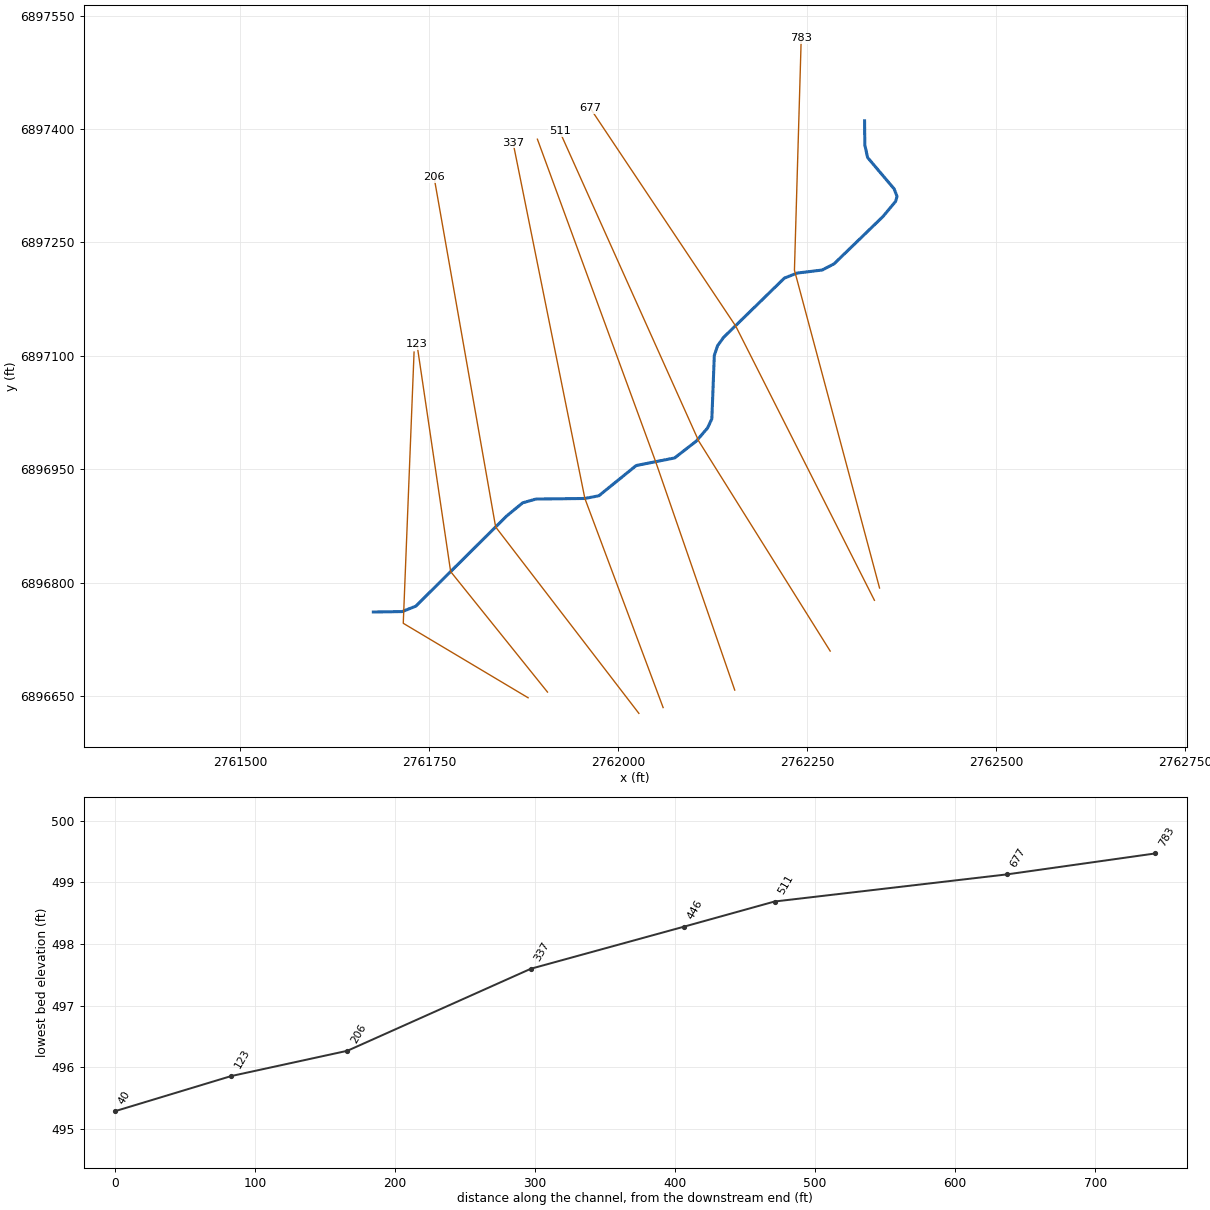
--- Lacy 052.prj (project) ---

Proj Title=Lacy 052 Base Level Engineering
Current Plan=p01
Default Exp/Contr=0.3,0.1
English Units
Geom File=g01
Flow File=f01
Plan File=p01
BEGIN DESCRIPTION:
Lacy 052
END DESCRIPTION:

--- Lacy 052.p01 (plan) ---

Plan Title=Multiple Run
Short Identifier=Multiple
Geom File=g01
Flow File=f01
Subcritical Flow
K Sum by GR= 0
Std Step Tol= 0.01
Critical Tol= 0.01
Num of Std Step Trials= 20
Max Error Tol= 0.3
Flow Tol Ratio= 0.001
Split Flow NTrial= 30
Split Flow Tol= 0.02
Split Flow Ratio= 0.02
Log Output Level= 0
Friction Slope Method= 1
Unsteady Friction Slope Method= 2
Unsteady Bridges Friction Slope Method= 1
Parabolic Critical Depth
Global Vel Dist=  1 , 1 , 1
Global Log Level= 0
CheckData=True
Encroach Param= -1, 0, 0, 0
BEGIN DESCRIPTION:
Multiple Run
END DESCRIPTION:

--- Lacy 052.f01 (steady flow) ---

Flow Title=Multiple
Number of Profiles=7
Profile Names=10-year,25-year,50-year,1pct_min,100-year,1pct_plu,500-year
River Rch & RM= Lacy 052,Reach-1,783
      79      93     102      56     113     225     136
Boundary for River Rch & Prof#=Lacy 052,Reach-1,1
Up Type=0
Dn Type=3
Dn Slope=0.005
Boundary for River Rch & Prof#=Lacy 052,Reach-1,2
Up Type=0
Dn Type=3
Dn Slope=0.005
Boundary for River Rch & Prof#=Lacy 052,Reach-1,3
Up Type=0
Dn Type=3
Dn Slope=0.005
Boundary for River Rch & Prof#=Lacy 052,Reach-1,4
Up Type=0
Dn Type=3
Dn Slope=0.005
Boundary for River Rch & Prof#=Lacy 052,Reach-1,5
Up Type=0
Dn Type=3
Dn Slope=0.005
Boundary for River Rch & Prof#=Lacy 052,Reach-1,6
Up Type=0
Dn Type=3
Dn Slope=0.005
Boundary for River Rch & Prof#=Lacy 052,Reach-1,7
Up Type=0
Dn Type=3
Dn Slope=0.005

--- Lacy 052.g01 (geometry) ---

Geom Title=Existing Conditions

River Reach=Lacy 052,Reach-1
Reach XY= 27
      2762326.00      6897411.00      2762326.32      6897379.12
      2762330.02      6897362.36      2762365.12      6897320.89
      2762368.96      6897310.92      2762367.03      6897304.27
      2762350.31      6897284.26      2762285.72      6897221.78
      2762269.97      6897213.54      2762236.64      6897209.46
      2762219.93      6897202.85      2762139.39      6897124.33
      2762131.52      6897113.44      2762127.17      6897100.52
      2762123.92      6897016.71      2762118.25      6897004.54
      2762103.28      6896987.10      2762074.61      6896964.84
      2762023.85      6896954.85      2761974.42      6896914.83
      2761955.90      6896911.24      2761891.22      6896910.48
      2761873.57      6896905.48      2761852.48      6896888.12
      2761732.21      6896768.76      2761714.16      6896761.59
      2761676.00      6896761.00

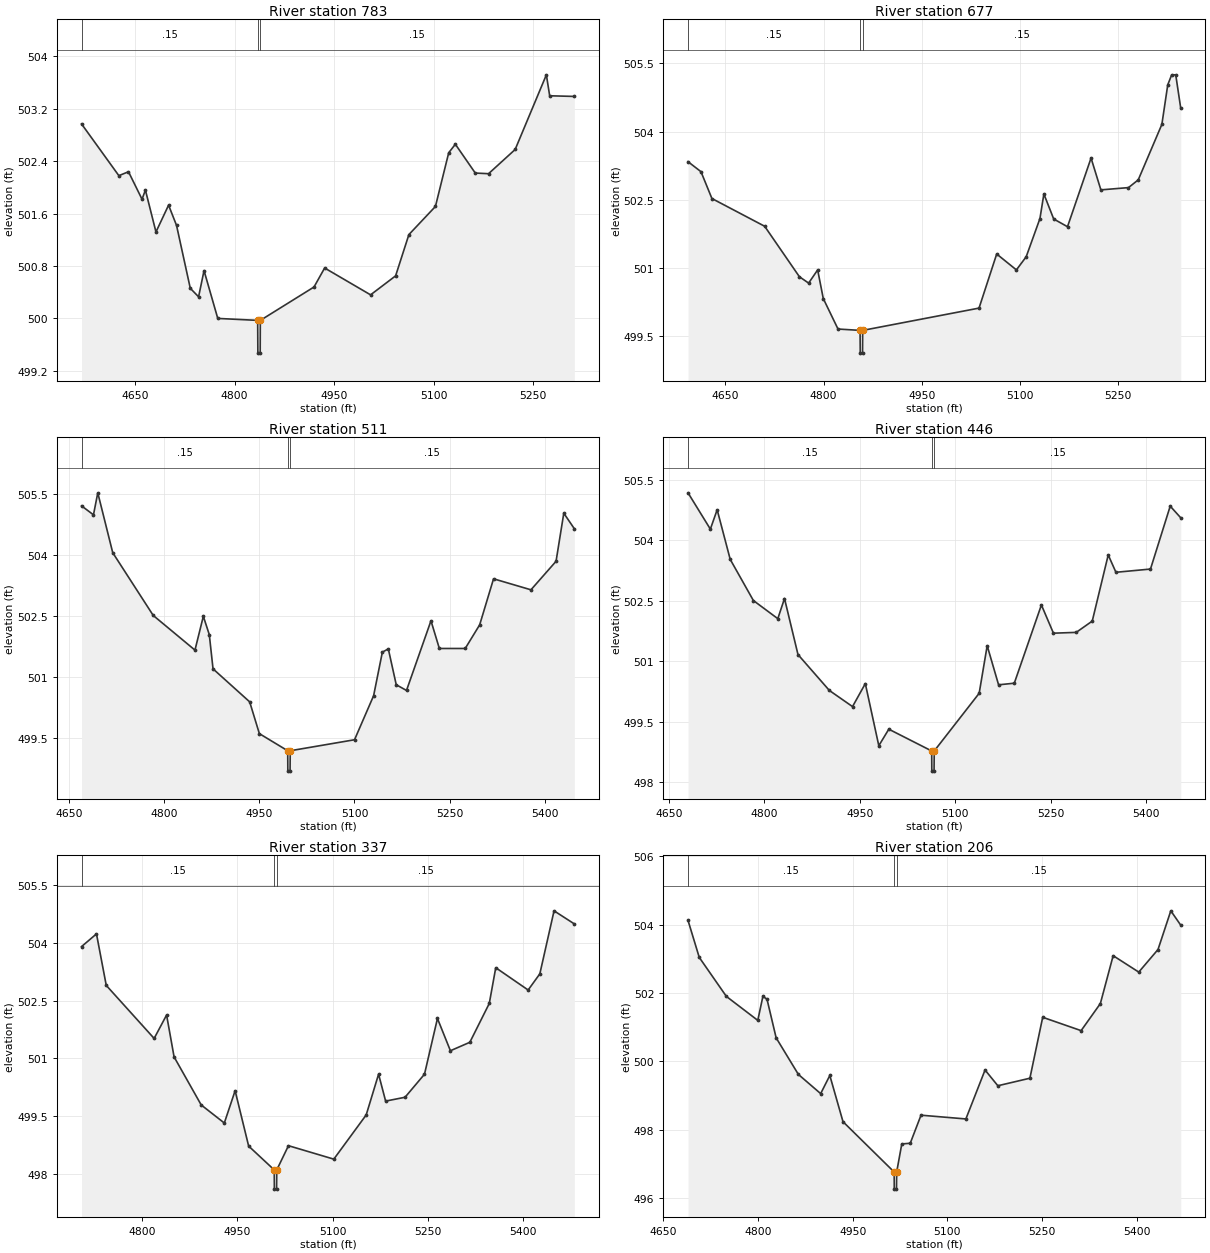
Type RM Length L Ch R = 1,783,106,106,106
BEGIN DESCRIPTION:
Lacy 052 3478
END DESCRIPTION:
XS GIS Cut Line= 3
      2762345.81      6896792.75      2762233.20      6897213.38
      2762242.17      6897520.10
#Sta/Elev= 30
  4569.5  502.97  4625.7  502.18  4640.2  502.24  4660.6  501.82  4665.7  501.96
  4681.6  501.32  4700.6  501.73  4712.6  501.42  4733.3  500.46  4745.8  500.33
  4754.0  500.73  4774.7  500.00  4834.8  499.97  4835.1  499.47  4838.6  499.47
  4838.8  499.97  4919.7  500.48  4935.7  500.77  5004.9  500.36  5042.6  500.65
  5062.6  501.28  5102.6  501.71  5122.6  502.53  5132.6  502.66  5162.6  502.22
  5182.6  502.21  5222.7  502.58  5269.7  503.72  5274.7  503.40  5311.8  503.39
#Mann=3,-1,0
  4569.5    0.15       0  4834.8    0.05       0  4838.8    0.15       0
Bank Sta=4834.8,4838.8
Exp/Cntr=0.3,0.1

Type RM Length L Ch R = 1,677,166,166,166
BEGIN DESCRIPTION:
Lacy 052 2655
END DESCRIPTION:
XS GIS Cut Line= 3
      2762339.02      6896776.51      2762155.58      6897139.19
      2761963.17      6897427.44
#Sta/Elev= 30
  4592.9  503.34  4612.7  503.12  4629.4  502.53  4710.0  501.92  4763.1  500.81
  4777.2  500.67  4791.0  500.96  4799.6  500.33  4822.1  499.66  4855.8  499.63
  4856.1  499.13  4859.6  499.13  4859.8  499.63  5037.6  500.12  5064.6  501.31
  5094.7  500.96  5109.7  501.25  5130.7  502.09  5136.7  502.63  5151.7  502.08
  5172.8  501.91  5208.8  503.42  5223.8  502.72  5266.0  502.77  5280.9  502.94
  5317.0  504.16  5326.0  505.03  5332.0  505.25  5338.2  505.25  5345.9  504.51
#Mann=3,-1,0
  4592.9    0.15       0  4855.8    0.05       0  4859.8    0.15       0
Bank Sta=4855.8,4859.8
Exp/Cntr=0.3,0.1

Type RM Length L Ch R = 1,511,65,65,65
BEGIN DESCRIPTION:
Lacy 052 2654
END DESCRIPTION:
XS GIS Cut Line= 3
      2762280.50      6896709.33      2762106.50      6896987.32
      2761922.43      6897397.24
#Sta/Elev= 30
  4669.5  505.20  4688.3  504.98  4695.1  505.52  4718.7  504.05  4782.6  502.51
  4848.4  501.66  4861.6  502.49  4871.0  502.04  4876.9  501.20  4934.7  500.39
  4950.0  499.61  4994.7  499.19  4994.9  498.69  4998.4  498.69  4998.7  499.19
  5100.1  499.46  5130.2  500.54  5144.0  501.61  5153.4  501.69  5165.9  500.81
  5182.1  500.67  5220.7  502.38  5233.9  501.70  5274.7  501.70  5297.5  502.28
  5319.4  503.41  5378.4  503.14  5418.0  503.84  5430.2  505.02  5446.8  504.64
#Mann=3,-1,0
  4669.5    0.15       0  4994.7    0.05       0  4998.7    0.15       0
Bank Sta=4994.7,4998.7
Exp/Cntr=0.3,0.1

Type RM Length L Ch R = 1,446,109,109,109
BEGIN DESCRIPTION:
Lacy 052 2653
END DESCRIPTION:
XS GIS Cut Line= 3
      2762154.19      6896657.71      2762049.56      6896959.91
      2761893.09      6897386.63
#Sta/Elev= 30
  4680.2  505.18  4715.3  504.28  4726.0  504.76  4746.5  503.53  4782.9  502.51
  4821.3  502.06  4831.8  502.56  4853.0  501.17  4902.3  500.28  4938.7  499.88
  4958.8  500.45  4980.0  498.91  4995.7  499.32  5063.1  498.78  5063.3  498.28
  5066.8  498.28  5067.1  498.78  5137.7  500.21  5150.3  501.39  5168.2  500.42
  5192.9  500.46  5235.5  502.40  5254.4  501.70  5290.2  501.72  5315.4  502.00
  5340.5  503.64  5352.6  503.21  5406.9  503.29  5437.9  504.85  5454.5  504.56
#Mann=3,-1,0
  4680.2    0.15       0  5063.1    0.05       0  5067.1    0.15       0
Bank Sta=5063.1,5067.1
Exp/Cntr=0.3,0.1

Type RM Length L Ch R = 1,337,131,131,131
BEGIN DESCRIPTION:
Lacy 052 2652
END DESCRIPTION:
XS GIS Cut Line= 3
      2762059.44      6896634.57      2761955.90      6896911.24
      2761860.85      6897382.24
#Sta/Elev= 30
  4704.6  503.91  4728.1  504.24  4743.5  502.90  4818.9  501.52  4838.5  502.13
  4850.3  501.04  4893.0  499.79  4929.4  499.32  4946.4  500.16  4967.7  498.72
  5008.0  498.10  5008.2  497.60  5011.7  497.60  5012.0  498.10  5030.4  498.73
  5101.8  498.38  5152.8  499.53  5172.3  500.59  5183.4  499.89  5214.0  499.99
  5244.6  500.59  5265.0  502.04  5285.4  501.20  5316.0  501.42  5346.6  502.43
  5356.8  503.36  5407.8  502.78  5426.2  503.20  5448.6  504.84  5480.5  504.50
#Mann=3,-1,0
  4704.6    0.15       0  5008.0    0.05       0  5012.0    0.15       0
Bank Sta=5008,5012
Exp/Cntr=0.3,0.1

Type RM Length L Ch R = 1,206,83,83,83
BEGIN DESCRIPTION:
Lacy 052 2651
END DESCRIPTION:
XS GIS Cut Line= 3
      2762027.36      6896626.88      2761837.82      6896873.58
      2761756.33      6897336.56
#Sta/Elev= 30
  4688.9  504.12  4706.7  503.04  4749.7  501.90  4799.5  501.20  4807.6  501.90
  4814.1  501.82  4828.6  500.69  4863.9  499.62  4899.2  499.06  4913.7  499.59
  4934.6  498.24  5015.7  496.77  5015.9  496.27  5019.4  496.27  5019.7  496.77
  5027.8  497.59  5041.2  497.61  5058.3  498.43  5129.4  498.32  5159.8  499.75
  5180.1  499.29  5230.9  499.51  5251.2  501.29  5312.1  500.90  5342.6  501.69
  5362.9  503.09  5403.5  502.61  5434.0  503.27  5454.3  504.40  5470.1  503.98
#Mann=3,-1,0
  4688.9    0.15       0  5015.7    0.05       0  5019.7    0.15       0
Bank Sta=5015.7,5019.7
Exp/Cntr=0.3,0.1

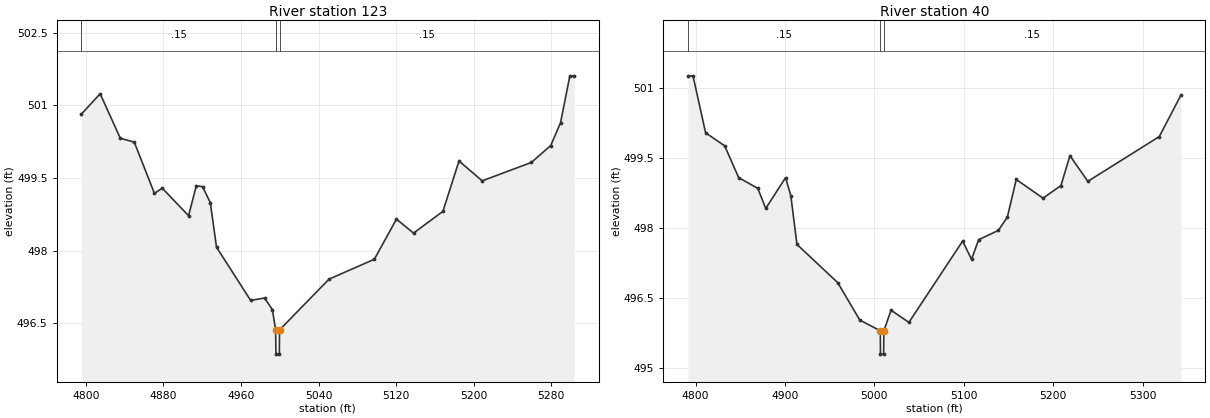
Type RM Length L Ch R = 1,123,83,83,83
BEGIN DESCRIPTION:
Lacy 052 2647
END DESCRIPTION:
XS GIS Cut Line= 3
      2761906.40      6896655.09      2761778.29      6896814.50
      2761733.79      6897115.02
#Sta/Elev= 30
  4795.5  500.82  4814.8  501.24  4835.6  500.32  4850.0  500.24  4870.8  499.18
  4878.8  499.29  4906.0  498.72  4914.0  499.34  4920.4  499.32  4928.4  498.99
  4934.8  498.07  4970.0  496.97  4984.4  497.02  4992.4  496.78  4995.8  496.36
  4996.1  495.86  4999.6  495.86  4999.8  496.36  5050.9  497.41  5097.6  497.82
  5120.4  498.65  5138.0  498.36  5168.3  498.81  5184.9  499.85  5208.8  499.44
  5259.5  499.82  5279.5  500.17  5289.6  500.64  5299.2  501.61  5303.8  501.61
#Mann=3,-1,0
  4795.5    0.15       0  4995.8    0.05       0  4999.8    0.15       0
Bank Sta=4995.8,4999.8
Exp/Cntr=0.3,0.1

Type RM Length L Ch R = 1,40,0,0,0
BEGIN DESCRIPTION:
Lacy 052 3488
END DESCRIPTION:
XS GIS Cut Line= 3
      2761880.78      6896647.54      2761715.59      6896746.08
      2761729.89      6897104.95
#Sta/Elev= 30
  4791.3  501.25  4797.0  501.25  4811.1  500.03  4832.5  499.75  4848.1  499.07
  4869.5  498.84  4878.4  498.41  4900.6  499.07  4906.5  498.68  4913.3  497.64
  4959.0  496.82  4983.6  496.02  5006.6  495.79  5006.8  495.29  5010.3  495.29
  5010.6  495.79  5018.6  496.23  5038.6  495.97  5098.7  497.71  5108.7  497.32
  5116.6  497.74  5138.7  497.94  5148.7  498.22  5158.7  499.03  5188.7  498.63
  5208.7  498.90  5218.8  499.54  5238.8  498.99  5318.8  499.95  5342.8  500.83
#Mann=3,-1,0
  4791.3    0.15       0  5006.6    0.05       0  5010.6    0.15       0
Bank Sta=5006.6,5010.6
Exp/Cntr=0.3,0.1

Chan Stop Cuts=-1