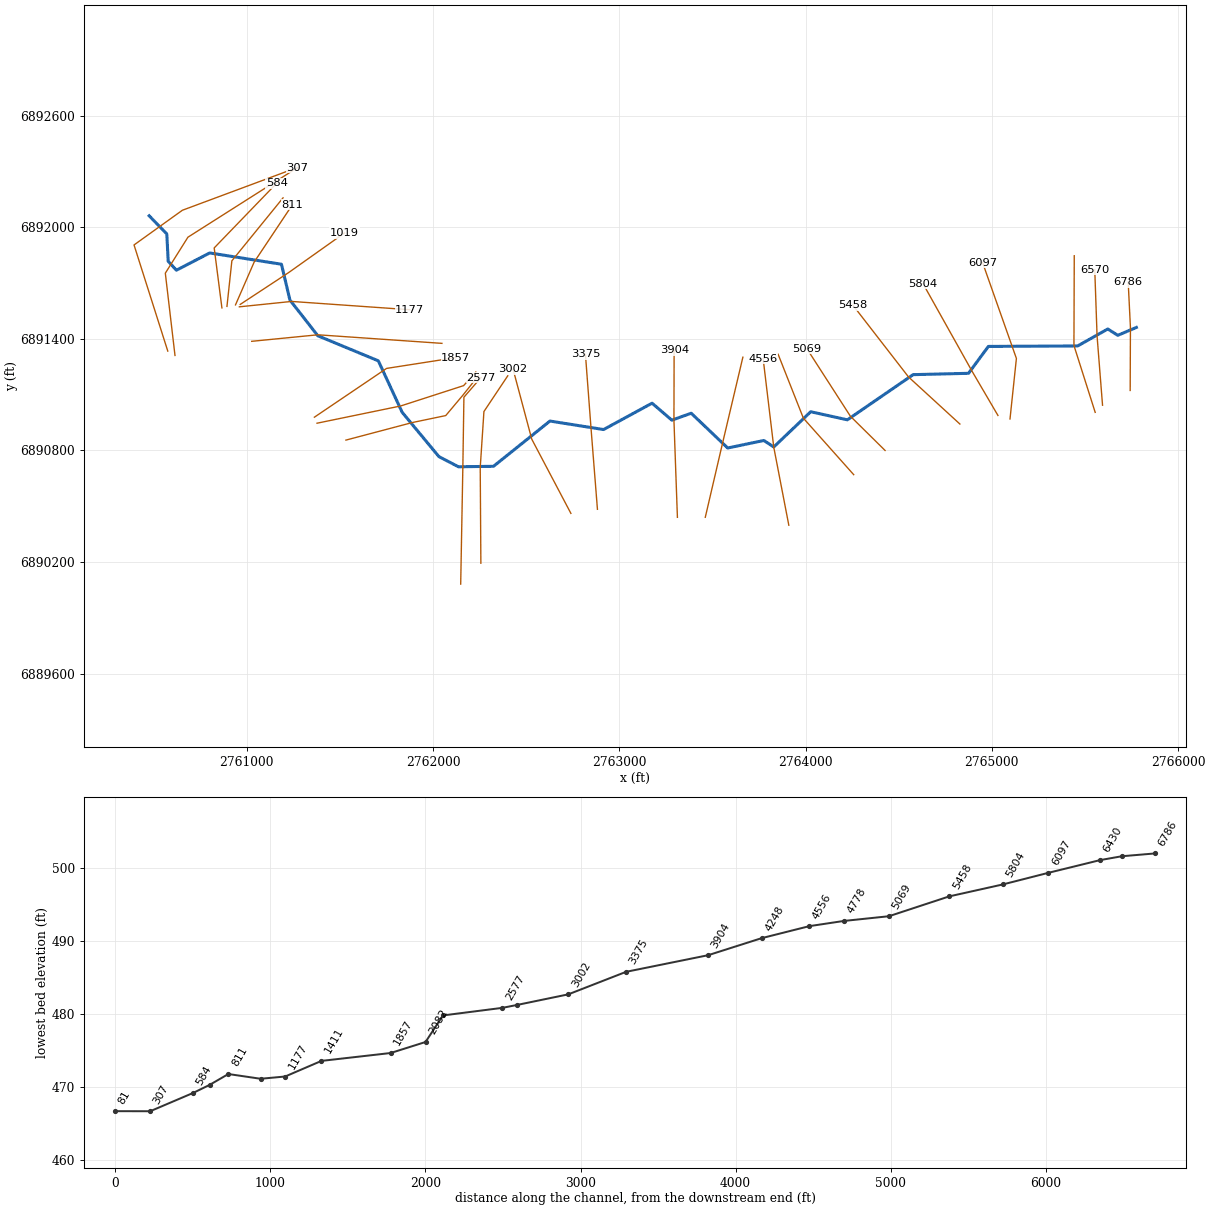
--- Lacy 053.prj (project) ---

Proj Title=Lacy 053 Base Level Engineering
Current Plan=p01
Default Exp/Contr=0.3,0.1
English Units
Geom File=g01
Flow File=f01
Plan File=p01
BEGIN DESCRIPTION:
Lacy 053
END DESCRIPTION:

--- Lacy 053.p01 (plan) ---

Plan Title=Multiple Run
Short Identifier=Multiple
Geom File=g01
Flow File=f01
Subcritical Flow
K Sum by GR= 0
Std Step Tol= 0.01
Critical Tol= 0.01
Num of Std Step Trials= 20
Max Error Tol= 0.3
Flow Tol Ratio= 0.001
Split Flow NTrial= 30
Split Flow Tol= 0.02
Split Flow Ratio= 0.02
Log Output Level= 0
Friction Slope Method= 1
Unsteady Friction Slope Method= 2
Unsteady Bridges Friction Slope Method= 1
Parabolic Critical Depth
Global Vel Dist=  1 , 1 , 1
Global Log Level= 0
CheckData=True
Encroach Param= -1, 0, 0, 0
BEGIN DESCRIPTION:
Multiple Run
END DESCRIPTION:

--- Lacy 053.f01 (steady flow) ---

Flow Title=Multiple
Number of Profiles=7
Profile Names=10-year,25-year,50-year,1pct_min,100-year,1pct_plu,500-year
River Rch & RM= Lacy 053,Reach-1,6786
     352     456     539     317     632    1260     869
River Rch & RM= Lacy 053,Reach-1,4556
     466     615     734     436     870    1735    1222
River Rch & RM= Lacy 053,Reach-1,2670
     582     779     938     562    1121    2238    1604
Boundary for River Rch & Prof#=Lacy 053,Reach-1,1
Up Type=0
Dn Type=3
Dn Slope=0.005
Boundary for River Rch & Prof#=Lacy 053,Reach-1,2
Up Type=0
Dn Type=3
Dn Slope=0.005
Boundary for River Rch & Prof#=Lacy 053,Reach-1,3
Up Type=0
Dn Type=3
Dn Slope=0.005
Boundary for River Rch & Prof#=Lacy 053,Reach-1,4
Up Type=0
Dn Type=3
Dn Slope=0.005
Boundary for River Rch & Prof#=Lacy 053,Reach-1,5
Up Type=0
Dn Type=3
Dn Slope=0.005
Boundary for River Rch & Prof#=Lacy 053,Reach-1,6
Up Type=0
Dn Type=3
Dn Slope=0.005
Boundary for River Rch & Prof#=Lacy 053,Reach-1,7
Up Type=0
Dn Type=3
Dn Slope=0.005

--- Lacy 053.g01 (geometry) ---

Geom Title=Existing Conditions

River Reach=Lacy 053,Reach-1
Reach XY= 30
      2765776.00      6891461.00      2765675.94      6891418.57
      2765622.77      6891452.78      2765460.79      6891361.51
      2764981.67      6891359.02      2764874.75      6891214.45
      2764577.55      6891207.25      2764224.50      6890964.47
      2764027.63      6891007.88      2763829.34      6890818.51
      2763776.11      6890853.36      2763581.86      6890813.05
      2763386.05      6890999.89      2763282.05      6890962.68
      2763176.00      6891053.90      2762915.50      6890912.22
      2762627.63      6890957.87      2762324.51      6890714.60
      2762136.46      6890712.14      2762031.61      6890766.59
      2761834.14      6891004.94      2761706.27      6891281.51
      2761381.47      6891416.26      2761231.47      6891608.55
      2761186.18      6891800.68      2760801.00      6891861.41
      2760622.30      6891768.65      2760578.06      6891816.45
      2760570.60      6891963.48      2760476.00      6892061.00

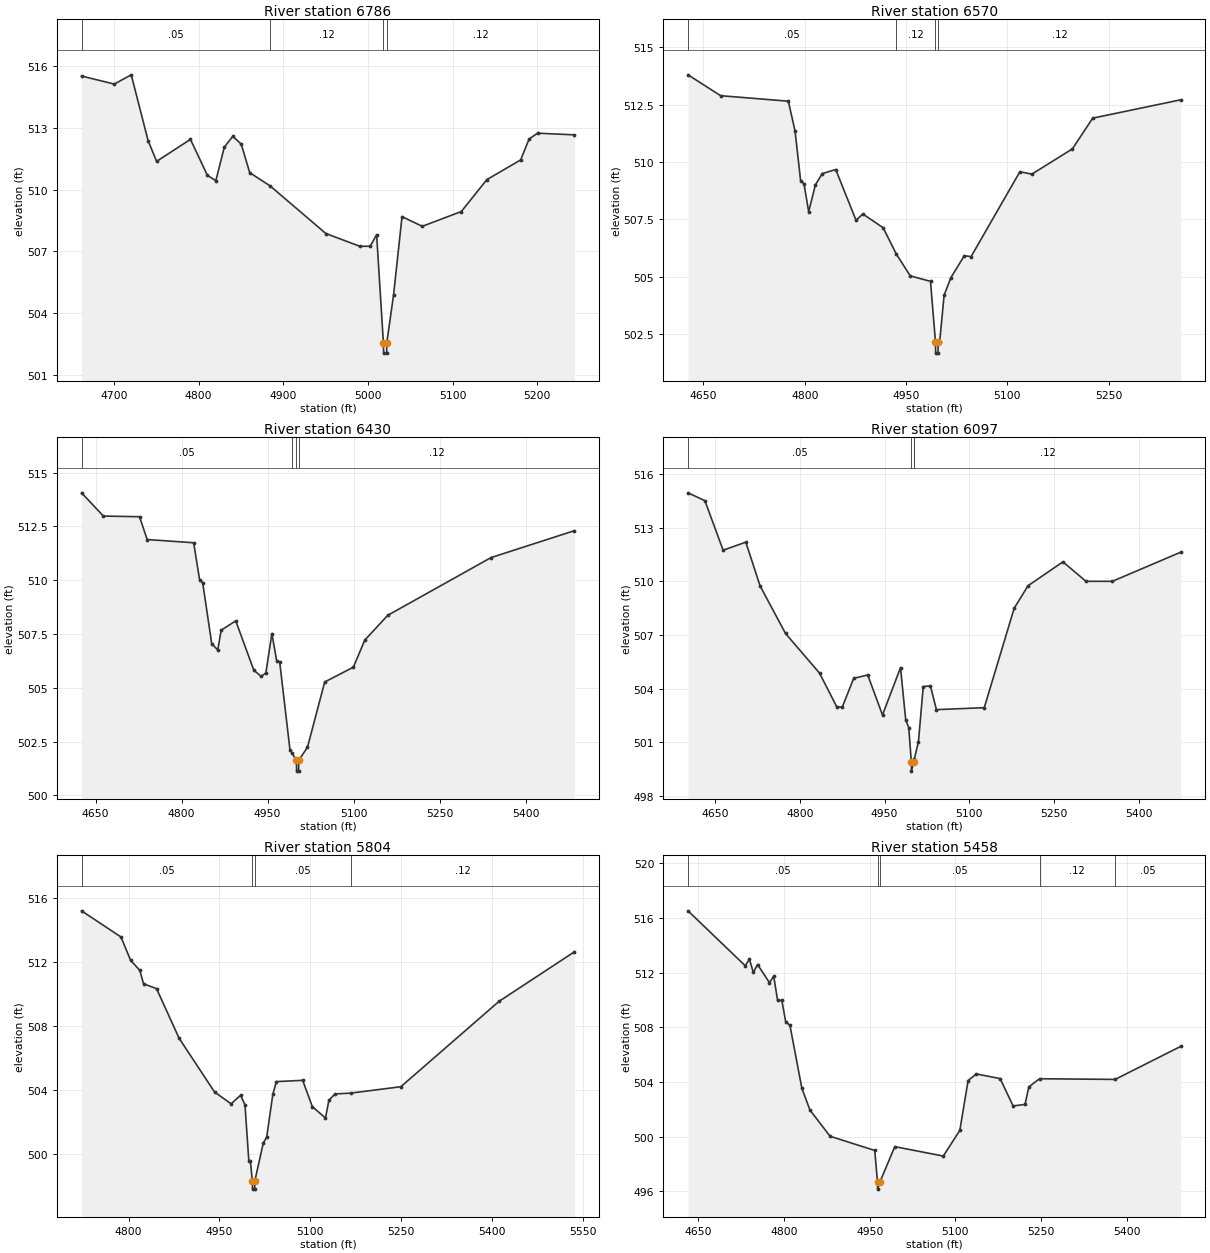
Type RM Length L Ch R = 1,6786,216,216,216
BEGIN DESCRIPTION:
Lacy 053 2634
END DESCRIPTION:
XS GIS Cut Line= 3
      2765742.76      6891122.30      2765744.12      6891460.70
      2765732.09      6891704.30
#Sta/Elev= 30
  4661.6  515.53  4700.3  515.14  4720.3  515.59  4740.3  512.38  4750.3  511.38
  4790.3  512.45  4810.3  510.70  4820.3  510.44  4830.3  512.07  4840.3  512.60
  4850.3  512.22  4860.3  510.83  4884.3  510.19  4950.3  507.87  4990.3  507.25
  5002.7  507.25  5010.3  507.81  5018.3  502.55  5018.6  502.05  5022.1  502.05
  5022.3  502.55  5030.3  504.88  5040.3  508.69  5064.3  508.22  5110.4  508.94
  5140.5  510.49  5180.5  511.45  5190.5  512.47  5200.5  512.75  5243.9  512.67
#Mann=4,-1,0
  4661.6    0.05       0  4884.3    0.12       0  5018.3    0.07       0
  5022.3    0.12       0
Bank Sta=5018.3,5022.3
Exp/Cntr=0.3,0.1

Type RM Length L Ch R = 1,6570,140,140,140
BEGIN DESCRIPTION:
Lacy 053 2633
END DESCRIPTION:
XS GIS Cut Line= 3
      2765594.36      6891042.87      2765565.04      6891414.47
      2765552.58      6891771.39
#Sta/Elev= 30
  4627.1  513.80  4675.4  512.89  4775.7  512.65  4785.7  511.34  4793.9  509.18
  4798.9  509.05  4805.8  507.83  4815.8  509.00  4825.9  509.49  4845.9  509.67
  4876.0  507.45  4886.0  507.73  4916.1  507.13  4935.5  505.99  4956.3  505.03
  4986.3  504.79  4993.6  502.16  4993.9  501.66  4997.4  501.66  4997.6  502.16
  4999.9  502.16  5006.4  504.18  5016.4  504.95  5036.4  505.91  5046.4  505.87
  5118.6  509.57  5136.5  509.47  5196.5  510.57  5226.5  511.91  5357.0  512.71
#Mann=4,-1,0
  4627.1    0.05       0  4935.5    0.12       0  4993.6    0.07       0
  4997.6    0.12       0
Bank Sta=4993.6,4997.6
Exp/Cntr=0.3,0.1

Type RM Length L Ch R = 1,6430,333,333,333
BEGIN DESCRIPTION:
Lacy 053 2632
END DESCRIPTION:
XS GIS Cut Line= 3
      2765554.91      6891004.66      2765440.80      6891364.06
      2765442.55      6891846.28
#Sta/Elev= 30
  4625.6  514.06  4663.7  512.98  4726.7  512.95  4740.0  511.89  4821.1  511.74
  4831.6  510.00  4836.8  509.89  4852.6  507.05  4863.1  506.76  4869.1  507.68
  4894.5  508.11  4926.0  505.82  4938.8  505.53  4947.0  505.69  4957.5  507.52
  4965.9  506.25  4971.1  506.21  4989.0  502.13  4992.2  501.99  5000.3  501.63
  5000.6  501.13  5004.1  501.13  5004.3  501.63  5019.6  502.24  5049.6  505.27
  5099.6  505.96  5119.6  507.22  5159.6  508.37  5339.6  511.05  5484.9  512.30
#Mann=4,-1,0
  4625.6    0.05       0  4992.2    0.12       0  5000.3    0.07       0
  5004.3    0.12       0
Bank Sta=5000.3,5004.3
Exp/Cntr=0.3,0.1

Type RM Length L Ch R = 1,6097,293,293,293
BEGIN DESCRIPTION:
Lacy 053 2631
END DESCRIPTION:
XS GIS Cut Line= 3
      2765097.56      6890969.17      2765131.91      6891294.32
      2764950.37      6891809.41
#Sta/Elev= 30
  4601.8  514.96  4631.7  514.52  4664.0  511.75  4704.2  512.20  4729.5  509.75
  4774.6  507.09  4834.9  504.87  4865.1  503.00  4875.1  502.97  4895.3  504.58
  4920.2  504.77  4946.4  502.53  4978.3  505.18  4987.6  502.24  4992.9  501.83
  4997.5  499.89  4997.7  499.39  5001.5  499.89  5003.0  500.09  5010.1  501.04
  5018.6  504.12  5031.3  504.16  5041.9  502.83  5126.7  502.94  5179.7  508.50
  5204.2  509.76  5266.1  511.10  5306.9  510.01  5353.7  510.01  5474.9  511.64
#Mann=4,-1,0
  4601.8    0.05       0  4997.5    0.05       0  5001.5    0.05       0
  5003.0    0.12       0
Bank Sta=4997.5,5001.5
Exp/Cntr=0.3,0.1

Type RM Length L Ch R = 1,5804,346,346,346
BEGIN DESCRIPTION:
Lacy 053 2630
END DESCRIPTION:
XS GIS Cut Line= 3
      2765032.82      6890987.87      2764893.08      6891226.91
      2764630.84      6891695.76
#Sta/Elev= 30
  4722.3  515.22  4787.5  513.58  4803.2  512.13  4818.6  511.49  4824.7  510.65
  4846.2  510.35  4883.4  507.25  4942.0  503.88  4969.3  503.14  4985.0  503.67
  4992.3  503.08  4998.7  499.54  5001.3  499.54  5004.5  498.30  5004.8  497.80
  5008.3  497.80  5008.5  498.30  5022.5  500.68  5028.2  501.06  5038.3  503.73
  5044.2  504.53  5087.6  504.61  5103.6  502.96  5125.3  502.25  5131.0  503.37
  5141.2  503.76  5166.9  503.81  5249.8  504.21  5411.9  509.55  5536.4  512.65
#Mann=4,-1,0
  4722.3    0.05       0  5004.5    0.05       0  5008.5    0.05       0
  5166.9    0.12       0
Bank Sta=5004.5,5008.5
Exp/Cntr=0.3,0.1

Type RM Length L Ch R = 1,5458,389,389,389
BEGIN DESCRIPTION:
Lacy 053 2629
END DESCRIPTION:
XS GIS Cut Line= 3
      2764828.59      6890941.73      2764552.82      6891194.72
      2764253.62      6891581.34
#Sta/Elev= 30
  4631.7  516.53  4731.9  512.51  4739.3  512.99  4746.1  512.02  4753.5  512.60
  4774.4  511.27  4781.8  511.75  4788.6  509.97  4796.0  509.98  4802.8  508.41
  4810.2  508.15  4831.1  503.54  4845.3  501.95  4880.5  500.03  4958.8  498.99
  4963.6  496.66  4963.8  496.16  4967.6  496.66  4993.9  499.27  5078.8  498.58
  5107.8  500.46  5122.3  504.11  5136.8  504.59  5178.4  504.25  5201.1  502.25
  5221.9  502.36  5228.8  503.65  5247.4  504.24  5379.7  504.19  5494.8  506.61
#Mann=5,-1,0
  4631.7    0.05       0  4963.6    0.04       0  4967.6    0.05       0
  5247.4    0.12       0  5379.7    0.05       0
Bank Sta=4963.6,4967.6
Exp/Cntr=0.3,0.1

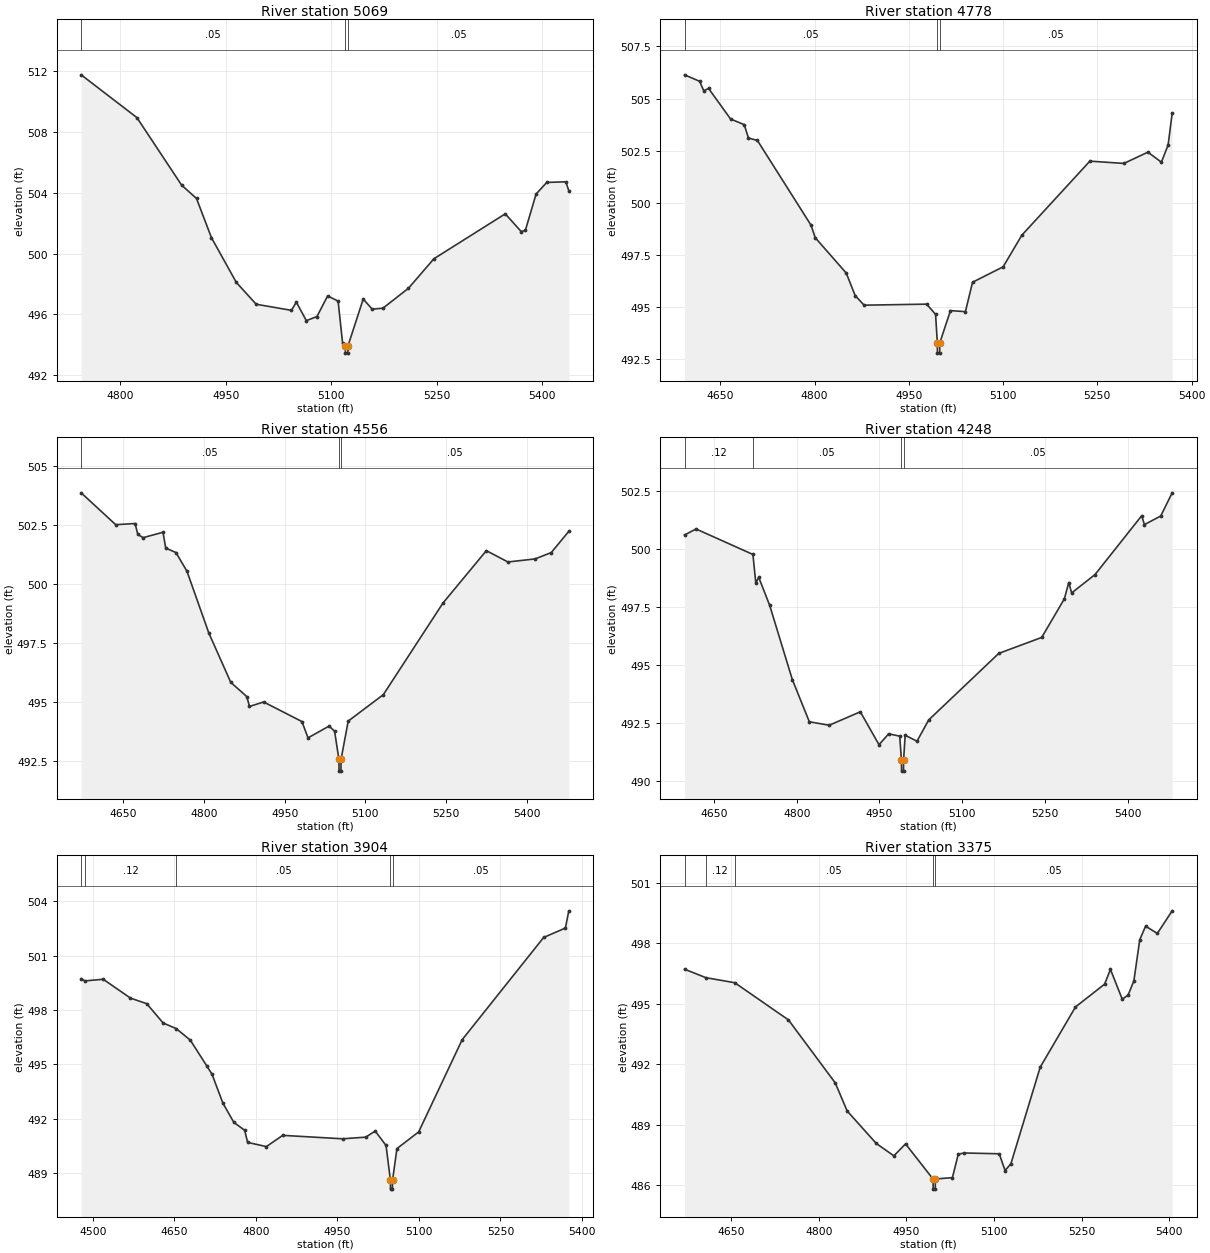
Type RM Length L Ch R = 1,5069,291,291,291
BEGIN DESCRIPTION:
Lacy 053 2628
END DESCRIPTION:
XS GIS Cut Line= 3
      2764426.88      6890799.77      2764240.81      6890983.56
      2764006.95      6891346.99
#Sta/Elev= 30
  4744.2  511.78  4823.5  508.96  4887.1  504.51  4908.3  503.63  4929.5  501.05
  4964.9  498.10  4993.2  496.66  5043.3  496.26  5050.3  496.80  5064.5  495.58
  5079.6  495.85  5094.8  497.21  5109.7  496.87  5116.0  494.14  5119.9  493.94
  5120.2  493.44  5123.7  493.44  5123.9  493.94  5145.4  497.00  5158.2  496.34
  5173.4  496.40  5209.7  497.71  5246.0  499.66  5347.5  502.62  5370.2  501.45
  5376.1  501.53  5391.3  503.92  5406.5  504.69  5433.6  504.73  5437.9  504.14
#Mann=3,-1,0
  4744.2    0.05       0  5119.9    0.04       0  5123.9    0.05       0
Bank Sta=5119.9,5123.9
Exp/Cntr=0.3,0.1

Type RM Length L Ch R = 1,4778,222,222,222
BEGIN DESCRIPTION:
Lacy 053 2611
END DESCRIPTION:
XS GIS Cut Line= 3
      2764258.38      6890669.71      2763988.33      6890973.10
      2763852.61      6891316.91
#Sta/Elev= 30
  4593.2  506.14  4617.2  505.83  4623.9  505.37  4631.4  505.49  4666.5  504.02
  4688.2  503.75  4694.9  503.11  4709.2  502.99  4794.4  498.93  4801.1  498.33
  4850.5  496.63  4864.7  495.55  4878.9  495.09  4978.4  495.14  4992.6  494.65
  4995.4  493.29  4995.6  492.79  4999.1  492.79  4999.4  493.29  5016.3  494.83
  5040.1  494.78  5051.4  496.19  5100.1  496.93  5129.9  498.45  5238.1  502.00
  5292.2  501.89  5330.4  502.43  5351.9  501.95  5362.6  502.78  5369.0  504.30
#Mann=3,-1,0
  4593.2    0.05       0  4995.4    0.04       0  4999.4    0.05       0
Bank Sta=4995.4,4999.4
Exp/Cntr=0.3,0.1

Type RM Length L Ch R = 1,4556,308,308,308
BEGIN DESCRIPTION:
Lacy 053 2609
END DESCRIPTION:
XS GIS Cut Line= 3
      2763910.04      6890397.97      2763829.35      6890816.79
      2763772.16      6891293.35
#Sta/Elev= 30
  4571.7  503.87  4635.9  502.52  4671.9  502.57  4677.0  502.11  4686.8  501.97
  4723.8  502.20  4728.9  501.53  4747.9  501.34  4768.3  500.55  4809.0  497.93
  4849.8  495.84  4879.5  495.24  4884.6  494.82  4910.9  495.01  4982.1  494.18
  4993.4  493.49  5032.7  493.99  5042.8  493.77  5050.8  492.58  5051.1  492.08
  5054.6  492.08  5054.8  492.58  5068.1  494.20  5133.4  495.32  5244.2  499.20
  5324.9  501.42  5365.0  500.94  5415.4  501.07  5445.6  501.34  5478.2  502.24
#Mann=3,-1,0
  4571.7    0.05       0  5050.8    0.04       0  5054.8    0.05       0
Bank Sta=5050.8,5054.8
Exp/Cntr=0.3,0.1

Type RM Length L Ch R = 1,4248,344,344,344
BEGIN DESCRIPTION:
Lacy 053 2610
END DESCRIPTION:
XS GIS Cut Line= 3
      2763461.61      6890440.65      2763553.14      6890834.25
      2763663.43      6891301.10
#Sta/Elev= 30
  4596.7  500.62  4617.6  500.88  4720.7  499.78  4725.9  498.54  4731.1  498.80
  4751.1  497.58  4792.1  494.38  4822.9  492.56  4858.9  492.41  4915.3  492.99
  4949.2  491.57  4966.7  492.04  4986.7  491.94  4989.8  490.93  4990.1  490.43
  4993.6  490.43  4993.8  490.93  4996.6  491.98  5018.0  491.72  5039.3  492.64
  5166.2  495.51  5244.1  496.20  5285.2  497.87  5293.1  498.57  5298.3  498.12
  5340.6  498.91  5425.2  501.45  5430.3  501.07  5459.8  501.44  5480.5  502.44
#Mann=4,-1,0
  4596.7    0.12       0  4720.7    0.05       0  4989.8    0.04       0
  4993.8    0.05       0
Bank Sta=4989.8,4993.8
Exp/Cntr=0.3,0.1

Type RM Length L Ch R = 1,3904,529,529,529
BEGIN DESCRIPTION:
Lacy 053 2608
END DESCRIPTION:
XS GIS Cut Line= 3
      2763311.98      6890440.38      2763293.32      6890961.22
      2763294.32      6891337.34
#Sta/Elev= 30
  4478.6  499.72  4485.4  499.60  4519.2  499.69  4569.3  498.65  4599.3  498.34
  4629.3  497.28  4653.7  496.96  4679.4  496.33  4709.4  494.92  4719.4  494.44
  4739.4  492.85  4759.4  491.79  4779.4  491.35  4784.9  490.68  4819.4  490.45
  4849.5  491.07  4959.5  490.88  5002.2  490.97  5019.6  491.31  5039.6  490.51
  5047.6  488.60  5047.8  488.10  5051.3  488.10  5051.6  488.60  5059.6  490.34
  5099.6  491.26  5179.6  496.35  5329.6  502.00  5369.6  502.52  5375.9  503.47
#Mann=5,-1,0
  4478.6    0.05       0  4485.4    0.12       0  4653.7    0.05       0
  5047.6    0.04       0  5051.6    0.05       0
Bank Sta=5047.6,5051.6
Exp/Cntr=0.3,0.1

Type RM Length L Ch R = 1,3375,373,373,373
BEGIN DESCRIPTION:
Lacy 053 2607
END DESCRIPTION:
XS GIS Cut Line= 3
      2762882.59      6890483.56      2762848.56      6890913.93
      2762818.16      6891316.37
#Sta/Elev= 30
  4570.0  496.71  4606.6  496.29  4656.1  496.04  4748.0  494.20  4828.2  491.08
  4848.6  489.69  4898.5  488.08  4928.6  487.47  4948.6  488.06  4995.7  486.32
  4996.0  485.82  4999.5  485.82  4999.7  486.32  5028.9  486.39  5038.9  487.55
  5048.9  487.61  5109.1  487.57  5119.1  486.74  5129.1  487.08  5179.3  491.86
  5239.7  494.84  5289.6  495.97  5299.6  496.70  5319.7  495.23  5329.7  495.42
  5339.7  496.13  5349.8  498.17  5359.8  498.84  5379.9  498.48  5405.3  499.60
#Mann=5,-1,0
  4570.0    0.05       0  4606.6    0.12       0  4656.1    0.05       0
  4995.7    0.05       0  4999.7    0.05       0
Bank Sta=4995.7,4999.7
Exp/Cntr=0.3,0.1

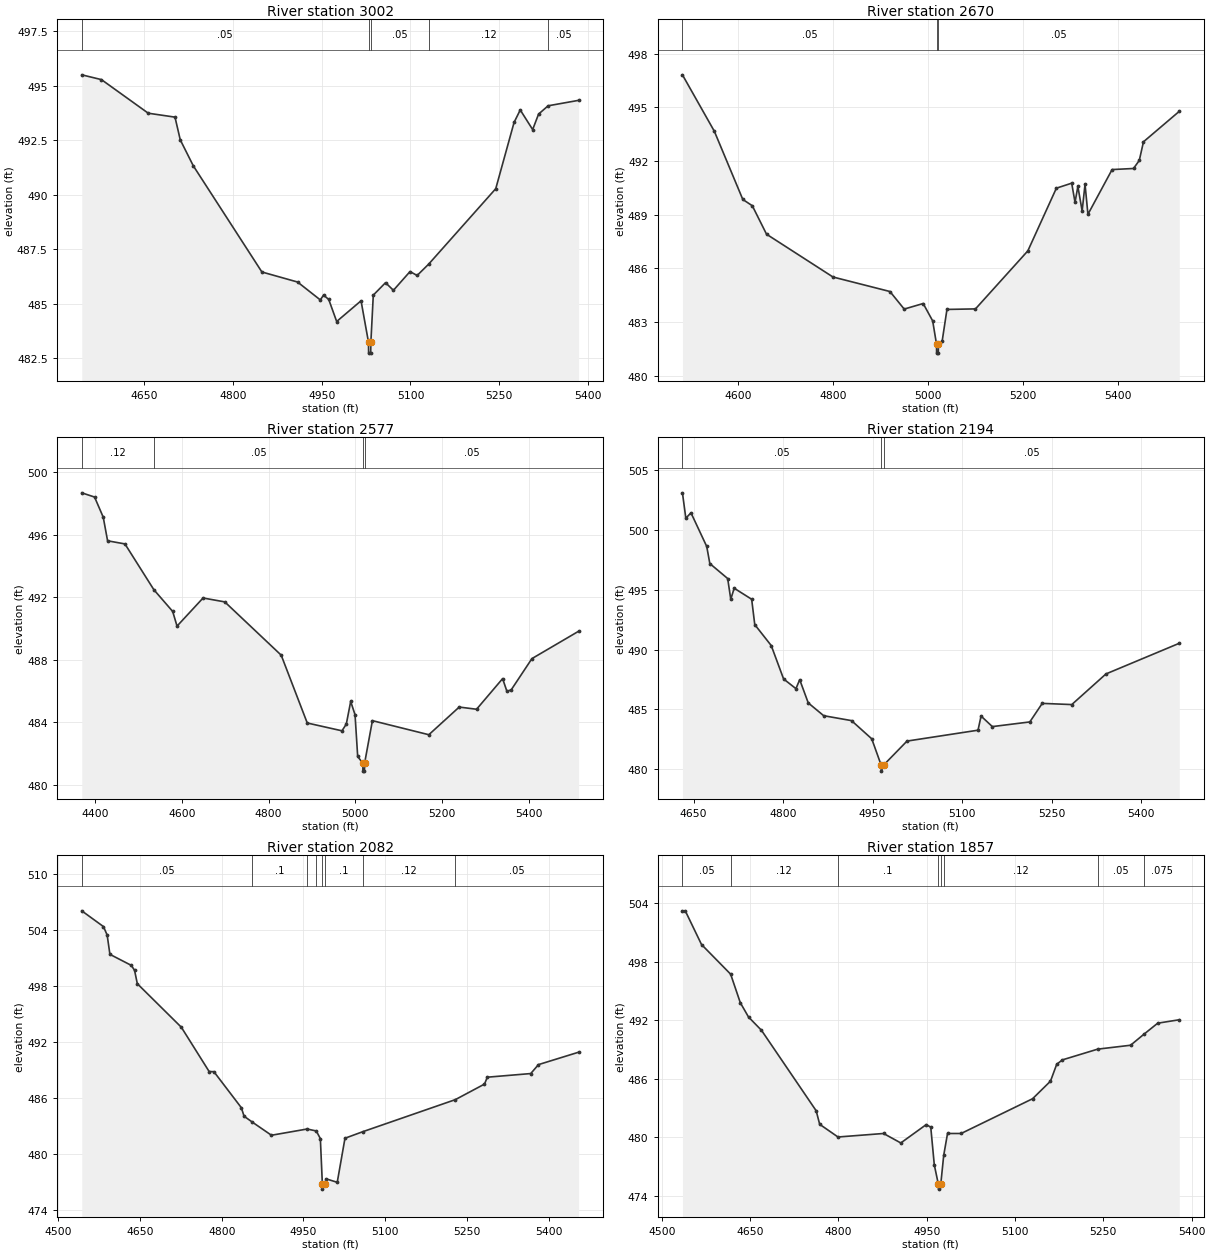
Type RM Length L Ch R = 1,3002,332,332,332
BEGIN DESCRIPTION:
Lacy 053 2590
END DESCRIPTION:
XS GIS Cut Line= 3
      2762740.06      6890461.54      2762529.97      6890860.56
      2762429.75      6891236.28
#Sta/Elev= 30
  4544.4  495.49  4577.7  495.27  4656.8  493.73  4702.0  493.55  4710.9  492.51
  4732.9  491.32  4848.9  486.45  4909.2  485.99  4947.6  485.17  4953.2  485.39
  4961.9  485.19  4975.3  484.18  5016.5  485.13  5029.1  483.23  5029.3  482.73
  5032.8  482.73  5033.1  483.23  5037.2  485.39  5057.9  485.96  5071.2  485.61
  5099.3  486.47  5111.3  486.29  5130.8  486.81  5244.2  490.27  5275.2  493.31
  5285.6  493.88  5306.6  492.98  5316.6  493.69  5332.7  494.07  5384.2  494.32
#Mann=5,-1,0
  4544.4    0.05       0  5029.1    0.05       0  5033.1    0.05       0
  5130.8    0.12       0  5332.7    0.05       0
Bank Sta=5029.1,5033.1
Exp/Cntr=0.3,0.1

Type RM Length L Ch R = 1,2670,93,93,93
BEGIN DESCRIPTION:
Lacy 053 2588
END DESCRIPTION:
XS GIS Cut Line= 4
      2762256.78      6890193.80      2762253.28      6890707.58
      2762273.21      6891009.06      2762401.21      6891201.08
#Sta/Elev= 30
  4482.6  496.81  4549.8  493.66  4609.8  489.85  4629.8  489.50  4659.8  487.91
  4799.8  485.52  4919.8  484.71  4949.8  483.73  4989.8  484.04  5009.8  483.07
  5017.9  481.77  5018.1  481.27  5021.6  481.27  5021.9  481.77  5029.9  481.96
  5039.9  483.71  5100.0  483.74  5210.3  486.98  5270.4  490.48  5302.7  490.76
  5309.7  489.69  5315.7  490.58  5324.7  489.21  5330.8  490.70  5336.9  489.02
  5387.8  491.52  5432.9  491.58  5445.1  492.03  5453.9  493.07  5529.3  494.77
#Mann=3,-1,0
  4482.6    0.05       0  5017.9    0.05       0  5021.9    0.05       0
Bank Sta=5017.9,5021.9
Exp/Cntr=0.3,0.1

Type RM Length L Ch R = 1,2577,383,383,383
BEGIN DESCRIPTION:
Lacy 053 2587
END DESCRIPTION:
XS GIS Cut Line= 4
      2762148.45      6890081.55      2762160.15      6890718.20
      2762165.70      6891085.97      2762257.37      6891191.83
#Sta/Elev= 30
  4369.5  498.69  4399.0  498.42  4419.0  497.13  4429.0  495.62  4469.0  495.42
  4535.6  492.49  4579.0  491.10  4589.0  490.16  4649.0  491.96  4699.0  491.71
  4829.0  488.30  4889.0  483.96  4969.0  483.46  4979.0  483.89  4989.1  485.34
  4999.1  484.49  5005.2  481.82  5017.1  481.38  5017.3  480.88  5020.8  480.88
  5021.1  481.38  5039.1  484.11  5169.1  483.21  5239.1  484.98  5279.1  484.84
  5339.1  486.80  5349.1  485.98  5359.1  486.09  5406.6  488.08  5514.1  489.83
#Mann=4,-1,0
  4369.5    0.12       0  4535.6    0.05       0  5017.1    0.04       0
  5021.1    0.05       0
Bank Sta=5017.1,5021.1
Exp/Cntr=0.3,0.1

Type RM Length L Ch R = 1,2194,112,112,112
BEGIN DESCRIPTION:
Lacy 053 2589
END DESCRIPTION:
XS GIS Cut Line= 5
      2761532.16      6890855.44      2761890.42      6890950.22
      2762068.19      6890987.32      2762159.98      6891096.58
      2762245.70      6891204.24
#Sta/Elev= 30
  4631.4  503.09  4637.1  500.97  4645.7  501.42  4672.1  498.61  4677.3  497.18
  4707.2  495.93  4712.4  494.20  4718.1  495.12  4747.4  494.20  4752.6  492.08
  4780.2  490.33  4800.9  487.54  4821.6  486.73  4827.9  487.48  4842.2  485.54
  4868.1  484.47  4914.7  484.06  4948.6  482.54  4964.4  480.34  4964.6  479.84
  4968.4  480.34  5007.7  482.35  5126.7  483.26  5131.8  484.44  5150.7  483.56
  5213.5  483.95  5234.3  485.50  5283.8  485.40  5341.1  487.96  5463.9  490.52
#Mann=3,-1,0
  4631.4    0.05       0  4964.4    0.05       0  4968.4    0.05       0
Bank Sta=4964.4,4968.4
Exp/Cntr=0.3,0.1

Type RM Length L Ch R = 1,2082,225,225,225
BEGIN DESCRIPTION:
Lacy 053 2586
END DESCRIPTION:
XS GIS Cut Line= 4
      2761376.99      6890946.24      2761826.33      6891038.95
      2762164.17      6891148.28      2762229.52      6891221.45
#Sta/Elev= 30
  4543.1  506.06  4582.9  504.37  4589.7  503.47  4594.8  501.39  4634.0  500.21
  4640.0  499.68  4645.1  498.24  4725.9  493.57  4776.9  488.82  4785.7  488.80
  4836.0  484.94  4841.1  484.02  4856.2  483.39  4891.3  481.98  4956.8  482.65
  4973.6  482.44  4981.1  481.62  4984.8  476.70  4985.0  476.20  4988.8  476.70
  4991.9  477.30  5012.1  476.93  5026.3  481.66  5058.9  482.36  5228.8  485.80
  5282.4  487.47  5287.6  488.21  5367.3  488.60  5381.5  489.56  5455.1  490.89
#Mann=8,-1,0
  4543.1    0.05       0  4856.2     0.1       0  4956.8    0.05       0
  4973.6     0.1       0  4984.8    0.07       0  4988.8     0.1       0
  5058.9    0.12       0  5228.8    0.05       0
Bank Sta=4984.8,4988.8
Exp/Cntr=0.3,0.1

Type RM Length L Ch R = 1,1857,446,446,446
BEGIN DESCRIPTION:
Lacy 053 3485
END DESCRIPTION:
XS GIS Cut Line= 3
      2761362.98      6890978.61      2761750.37      6891240.76
      2762122.20      6891298.84
#Sta/Elev= 30
  4534.9  503.20  4539.7  503.20  4567.3  499.75  4616.8  496.71  4633.2  493.79
  4647.2  492.32  4669.2  490.96  4762.1  482.72  4768.1  481.33  4799.2  480.03
  4876.6  480.39  4905.9  479.42  4949.1  481.30  4956.8  481.04  4962.8  477.18
  4969.7  475.19  4970.0  474.69  4973.8  475.19  4978.8  478.15  4985.3  480.39
  5008.4  480.39  5129.8  483.95  5160.2  485.75  5170.8  487.48  5180.4  487.93
  5240.4  489.03  5296.3  489.43  5318.8  490.55  5342.4  491.69  5379.0  492.04
#Mann=8,-1,0
  4534.9    0.05       0  4616.8    0.12       0  4799.2     0.1       0
  4969.7    0.07       0  4973.8     0.1       0  4978.8    0.12       0
  5240.4    0.05       0  5318.8   0.075       0
Bank Sta=4969.7,4973.8
Exp/Cntr=0.3,0.1

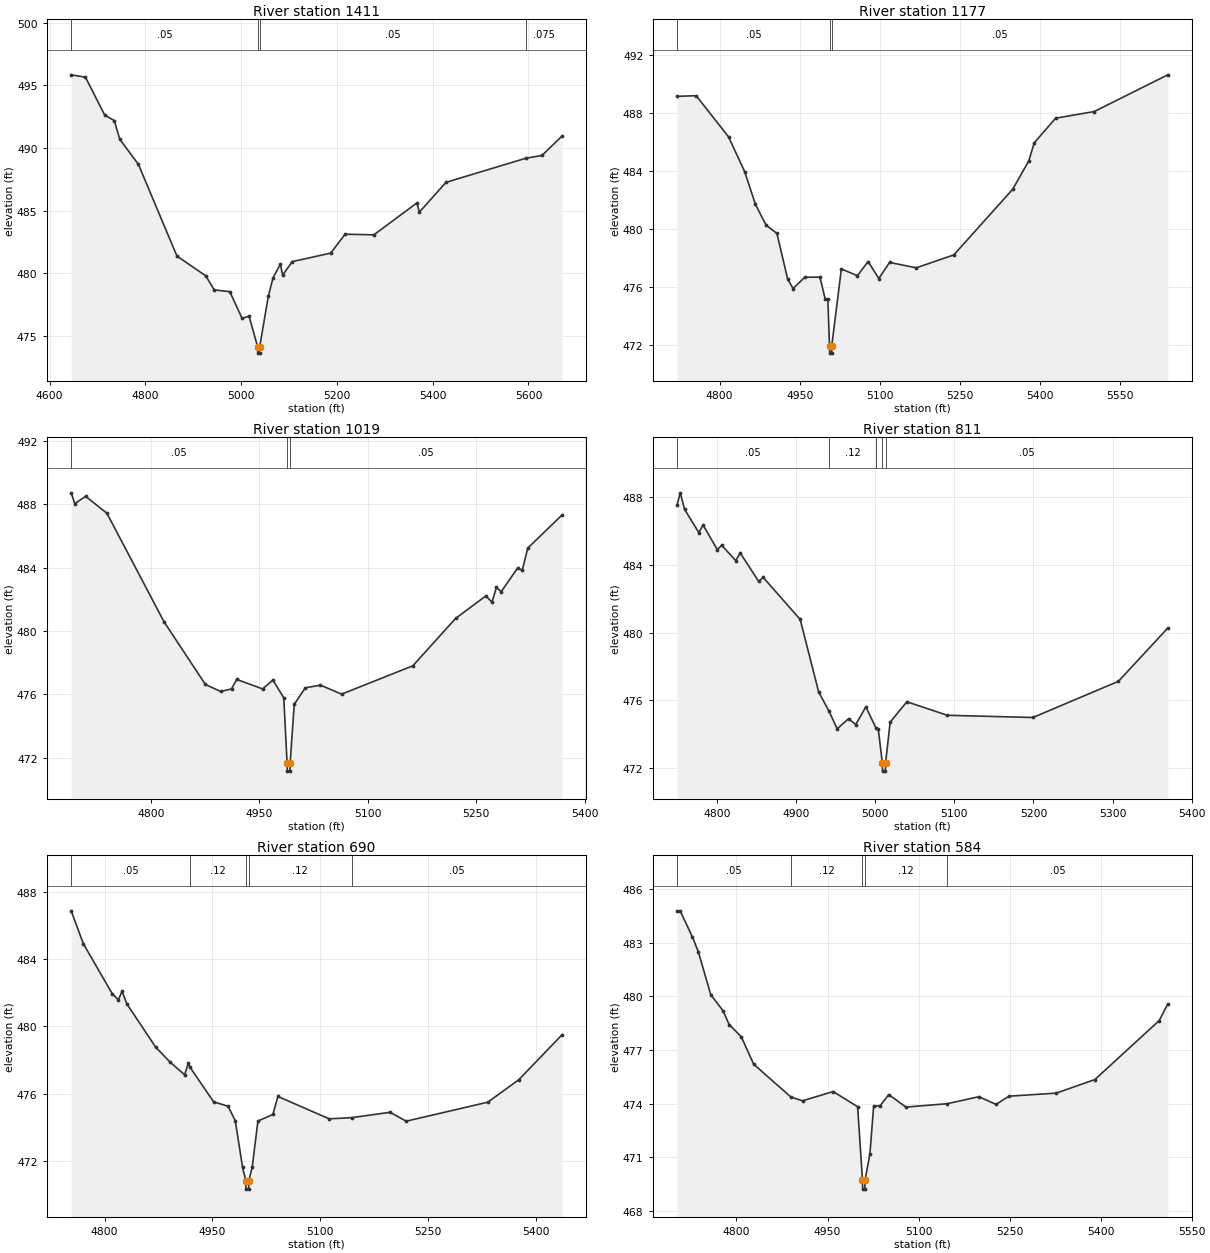
Type RM Length L Ch R = 1,1411,234,234,234
BEGIN DESCRIPTION:
Lacy 053 2580
END DESCRIPTION:
XS GIS Cut Line= 3
      2761026.39      6891386.42      2761381.74      6891421.49
      2762047.57      6891375.46
#Sta/Elev= 30
  4645.3  495.84  4675.1  495.65  4715.3  492.62  4735.3  492.19  4746.6  490.70
  4785.6  488.69  4866.0  481.37  4926.3  479.78  4943.9  478.66  4976.5  478.52
  5002.0  476.39  5016.7  476.56  5034.6  474.11  5035.0  473.61  5038.5  473.61
  5038.8  474.11  5056.8  478.14  5066.8  479.64  5081.9  480.71  5086.9  479.85
  5106.9  480.92  5187.1  481.60  5217.2  483.11  5277.3  483.06  5367.2  485.61
  5372.2  484.87  5427.7  487.25  5593.9  489.17  5628.1  489.40  5669.8  490.94
#Mann=4,-1,0
  4645.3    0.05       0  5034.6    0.05       0  5038.8    0.05       0
  5593.9   0.075       0
Bank Sta=5034.6,5038.8
Exp/Cntr=0.3,0.1

Type RM Length L Ch R = 1,1177,158,158,158
BEGIN DESCRIPTION:
Lacy 053 2579
END DESCRIPTION:
XS GIS Cut Line= 3
      2760960.18      6891571.84      2761240.78      6891600.78
      2761875.53      6891556.14
#Sta/Elev= 30
  4720.6  489.17  4756.4  489.21  4816.9  486.37  4847.1  483.97  4867.2  481.72
  4887.3  480.28  4907.4  479.72  4927.5  476.57  4937.6  475.92  4959.4  476.70
  4987.8  476.71  4997.8  475.20  5002.7  475.20  5005.8  471.97  5006.2  471.47
  5009.7  471.47  5010.0  471.97  5028.0  477.27  5058.0  476.81  5078.1  477.78
  5098.1  476.61  5118.2  477.72  5168.3  477.35  5238.5  478.24  5348.8  482.77
  5378.8  484.72  5388.9  485.96  5429.0  487.66  5501.3  488.12  5639.0  490.65
#Mann=3,-1,0
  4720.6    0.05       0  5005.8    0.04       0  5010.0    0.05       0
Bank Sta=5005.8,5010
Exp/Cntr=0.3,0.1

Type RM Length L Ch R = 1,1019,208,208,208
BEGIN DESCRIPTION:
Lacy 053 3496
END DESCRIPTION:
XS GIS Cut Line= 3
      2760964.72      6891584.73      2761224.02      6891755.35
      2761524.50      6891968.66
#Sta/Elev= 30
  4689.6  488.73  4694.5  488.05  4709.6  488.51  4739.0  487.44  4818.0  480.59
  4875.3  476.63  4896.3  476.19  4911.4  476.35  4918.6  476.95  4954.5  476.35
  4968.6  476.91  4983.7  475.79  4988.3  471.66  4988.6  471.16  4992.2  471.16
  4992.5  471.66  4998.2  475.38  5013.5  476.42  5034.4  476.59  5063.7  476.02
  5162.3  477.81  5221.4  480.80  5263.2  482.22  5271.8  481.83  5277.9  482.76
  5284.5  482.49  5307.5  484.00  5313.6  483.83  5321.3  485.24  5368.5  487.32
#Mann=3,-1,0
  4689.6    0.05       0  4988.3    0.04       0  4992.5    0.05       0
Bank Sta=4988.3,4992.5
Exp/Cntr=0.3,0.1

Type RM Length L Ch R = 1,811,121,121,121
BEGIN DESCRIPTION:
Lacy 053 3495
END DESCRIPTION:
XS GIS Cut Line= 3
      2760939.47      6891582.29      2761039.36      6891811.80
      2761244.36      6892119.70
#Sta/Elev= 30
  4749.7  487.55  4753.6  488.26  4759.2  487.28  4777.1  485.91  4782.5  486.36
  4800.5  484.90  4806.0  485.16  4823.9  484.25  4829.4  484.71  4852.8  483.02
  4858.3  483.27  4905.2  480.78  4928.6  476.49  4941.8  475.34  4952.0  474.31
  4966.4  474.91  4975.5  474.56  4988.2  475.61  5001.2  474.34  5004.0  474.29
  5009.0  472.31  5009.3  471.81  5012.9  471.81  5013.2  472.31  5019.0  474.71
  5040.1  475.91  5091.2  475.11  5199.4  474.98  5307.5  477.12  5369.9  480.27
#Mann=5,-1,0
  4749.7    0.05       0  4941.8    0.12       0  5001.2    0.05       0
  5009.0    0.07       0  5013.2    0.05       0
Bank Sta=5009,5013.2
Exp/Cntr=0.3,0.1

Type RM Length L Ch R = 1,690,106,106,106
BEGIN DESCRIPTION:
Lacy 053 3494
END DESCRIPTION:
XS GIS Cut Line= 3
      2760893.62      6891574.16      2760919.94      6891819.15
      2761194.69      6892157.43
#Sta/Elev= 30
  4753.6  486.87  4770.5  484.91  4810.8  481.93  4819.3  481.58  4824.3  482.09
  4830.9  481.34  4871.1  478.76  4891.2  477.87  4911.3  477.12  4916.3  477.80
  4918.6  477.58  4951.6  475.51  4971.7  475.25  4981.7  474.39  4991.8  471.63
  4996.3  470.82  4996.6  470.32  5000.2  470.32  5000.5  470.82  5005.3  471.64
  5013.2  474.37  5034.0  474.76  5041.0  475.83  5112.3  474.50  5143.4  474.57
  5197.0  474.89  5219.3  474.36  5332.8  475.49  5376.0  476.83  5435.8  479.49
#Mann=5,-1,0
  4753.6    0.05       0  4918.6    0.12       0  4996.3    0.07       0
  5000.5    0.12       0  5143.4    0.05       0
Bank Sta=4996.3,5000.5
Exp/Cntr=0.3,0.1

Type RM Length L Ch R = 1,584,277,277,277
BEGIN DESCRIPTION:
Lacy 053 3493
END DESCRIPTION:
XS GIS Cut Line= 3
      2760866.47      6891566.04      2760825.00      6891888.34
      2761160.68      6892236.39
#Sta/Elev= 30
  4702.2  484.79  4707.2  484.79  4727.4  483.33  4737.4  482.47  4757.6  480.10
  4777.8  479.20  4787.9  478.43  4808.0  477.74  4828.3  476.21  4889.4  474.38
  4908.8  474.16  4959.3  474.68  4999.6  473.83  5007.6  469.72  5007.9  469.22
  5011.5  469.22  5011.8  469.72  5019.8  471.17  5026.0  473.86  5036.8  473.89
  5050.9  474.51  5079.2  473.81  5147.4  474.00  5199.4  474.39  5227.7  473.96
  5249.0  474.42  5326.7  474.59  5390.5  475.35  5496.5  478.65  5510.7  479.58
#Mann=5,-1,0
  4702.2    0.05       0  4889.4    0.12       0  5007.6    0.07       0
  5011.8    0.12       0  5147.4    0.05       0
Bank Sta=5007.6,5011.8
Exp/Cntr=0.3,0.1

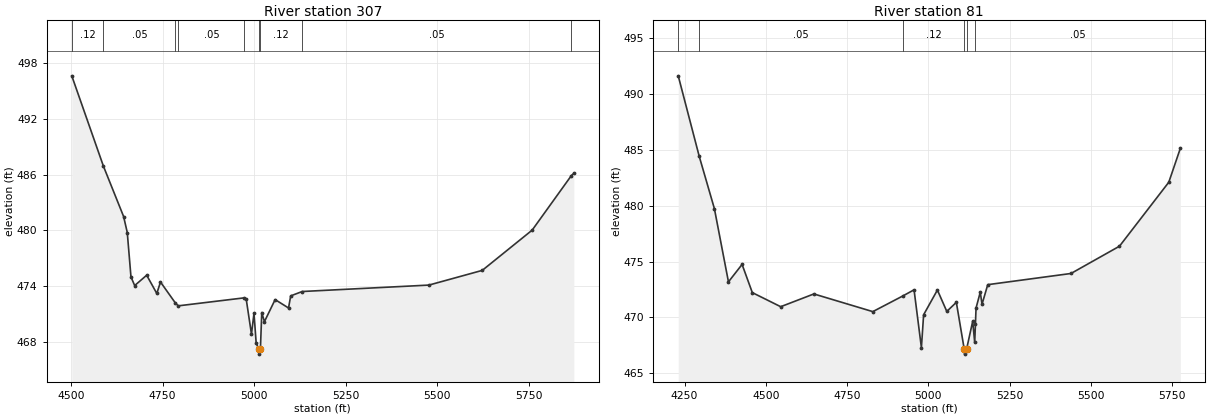
Type RM Length L Ch R = 1,307,226,226,226
BEGIN DESCRIPTION:
Lacy 053 3492
END DESCRIPTION:
XS GIS Cut Line= 4
      2760614.56      6891310.50      2760562.66      6891752.60
      2760684.07      6891946.08      2761272.22      6892320.00
#Sta/Elev= 30
  4502.1  496.62  4588.6  486.90  4643.6  481.50  4653.6  479.78  4663.7  475.01
  4673.8  474.08  4706.6  475.19  4734.2  473.23  4744.3  474.46  4785.2  472.19
  4792.9  471.90  4973.3  472.76  4978.3  472.62  4992.6  468.86  4999.5  471.10
  5005.4  467.93  5012.7  467.21  5013.0  466.71  5017.0  467.21  5020.7  471.18
  5028.0  470.20  5057.2  472.57  5093.8  471.67  5099.7  472.97  5131.2  473.44
  5476.9  474.13  5622.6  475.71  5758.9  480.04  5865.9  485.90  5872.6  486.14
#Mann=9,-1,0
  4502.1    0.12       0  4588.6    0.05       0  4785.2    0.12       0
  4792.9    0.05       0  4973.3    0.12       0  5012.7    0.07       0
  5017.0    0.12       0  5131.2    0.05       0  5865.9    0.12       0
Bank Sta=5012.7,5017
Exp/Cntr=0.3,0.1

Type RM Length L Ch R = 1,81,0,0,0
BEGIN DESCRIPTION:
Lacy 053 3491
END DESCRIPTION:
XS GIS Cut Line= 4
      2760575.86      6891333.79      2760394.67      6891904.36
      2760654.13      6892090.81      2761241.17      6892309.48
#Sta/Elev= 30
  4230.4  491.60  4294.9  484.41  4341.6  479.73  4384.9  473.18  4426.8  474.74
  4458.3  472.22  4545.6  470.96  4647.7  472.10  4829.0  470.52  4921.3  471.92
  4955.9  472.47  4978.5  467.30  4985.3  470.24  5027.7  472.45  5056.6  470.54
  5086.0  471.35  5109.9  467.22  5111.1  466.72  5117.9  467.22  5136.3  469.66
  5142.5  467.76  5144.7  469.41  5146.6  470.84  5159.6  472.26  5165.0  471.18
  5182.6  472.93  5438.7  473.93  5587.9  476.37  5739.6  482.09  5775.0  485.11
#Mann=6,-1,0
  4230.4    0.12       0  4294.9    0.05       0  4921.3    0.12       0
  5109.9    0.07       0  5117.9    0.12       0  5144.7    0.05       0
Bank Sta=5109.9,5117.9
Exp/Cntr=0.3,0.1

Chan Stop Cuts=-1