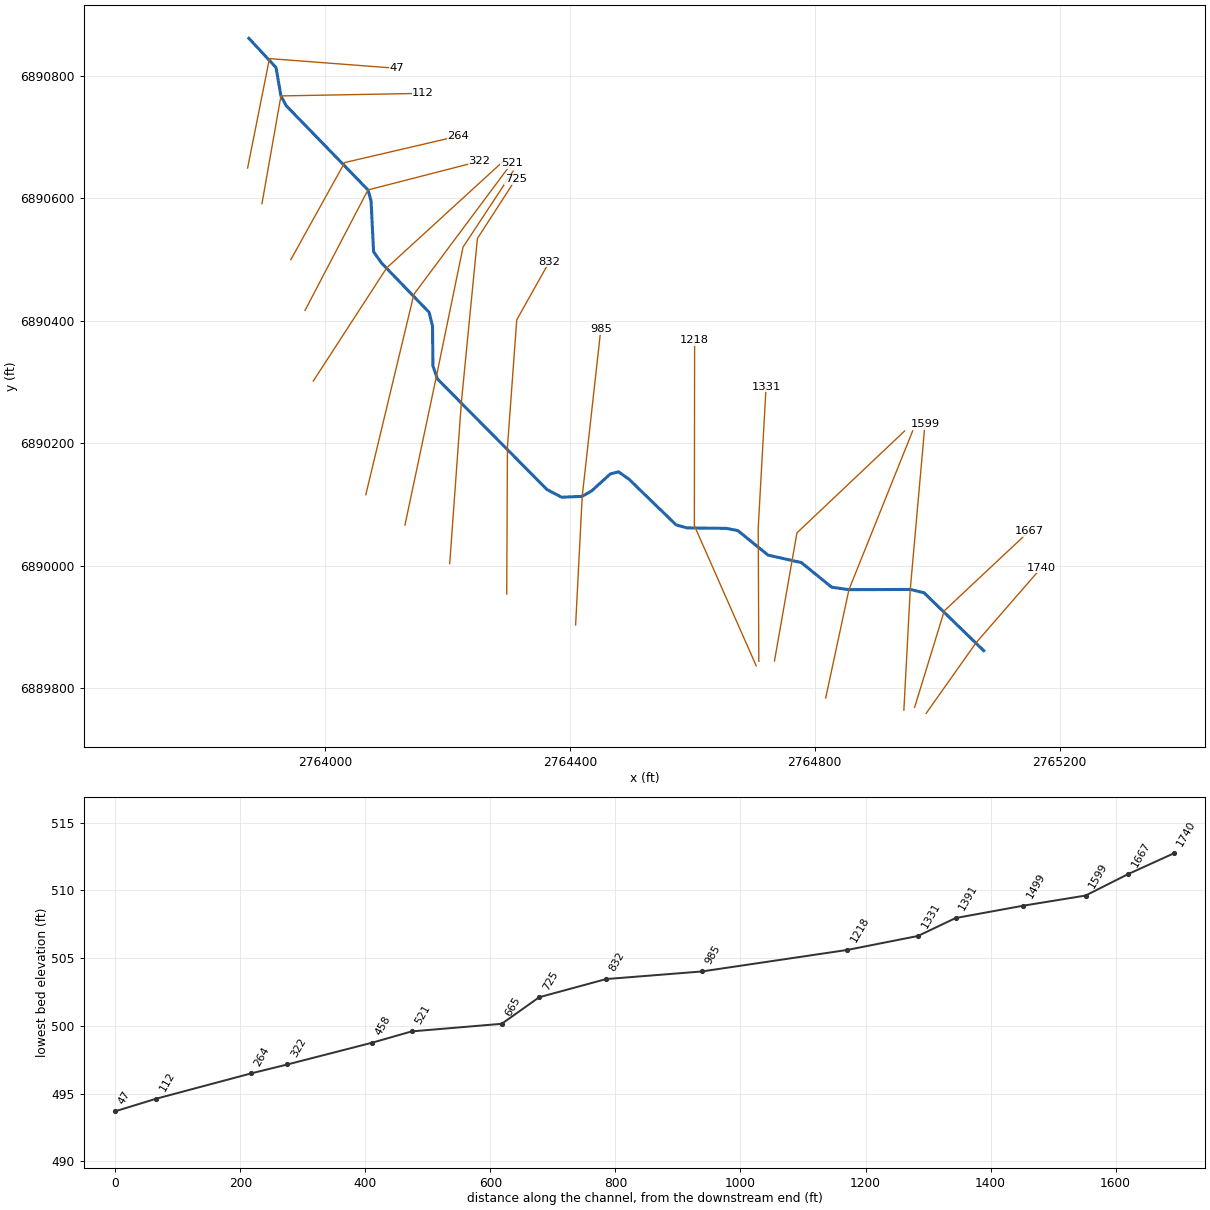
--- Lacy 054.prj (project) ---

Proj Title=Lacy 054 Base Level Engineering
Current Plan=p01
Default Exp/Contr=0.3,0.1
English Units
Geom File=g01
Flow File=f01
Plan File=p01
BEGIN DESCRIPTION:
Lacy 054
END DESCRIPTION:

--- Lacy 054.p01 (plan) ---

Plan Title=Multiple Run
Short Identifier=Multiple
Geom File=g01
Flow File=f01
Subcritical Flow
K Sum by GR= 0
Std Step Tol= 0.01
Critical Tol= 0.01
Num of Std Step Trials= 20
Max Error Tol= 0.3
Flow Tol Ratio= 0.001
Split Flow NTrial= 30
Split Flow Tol= 0.02
Split Flow Ratio= 0.02
Log Output Level= 0
Friction Slope Method= 1
Unsteady Friction Slope Method= 2
Unsteady Bridges Friction Slope Method= 1
Parabolic Critical Depth
Global Vel Dist=  1 , 1 , 1
Global Log Level= 0
CheckData=True
Encroach Param= -1, 0, 0, 0
BEGIN DESCRIPTION:
Multiple Run
END DESCRIPTION:

--- Lacy 054.f01 (steady flow) ---

Flow Title=Multiple
Number of Profiles=7
Profile Names=10-year,25-year,50-year,1pct_min,100-year,1pct_plu,500-year
River Rch & RM= Lacy 054,Reach-1,1740
     115     138     156      88     175     349     221
Boundary for River Rch & Prof#=Lacy 054,Reach-1,1
Up Type=0
Dn Type=3
Dn Slope=0.005
Boundary for River Rch & Prof#=Lacy 054,Reach-1,2
Up Type=0
Dn Type=3
Dn Slope=0.005
Boundary for River Rch & Prof#=Lacy 054,Reach-1,3
Up Type=0
Dn Type=3
Dn Slope=0.005
Boundary for River Rch & Prof#=Lacy 054,Reach-1,4
Up Type=0
Dn Type=3
Dn Slope=0.005
Boundary for River Rch & Prof#=Lacy 054,Reach-1,5
Up Type=0
Dn Type=3
Dn Slope=0.005
Boundary for River Rch & Prof#=Lacy 054,Reach-1,6
Up Type=0
Dn Type=3
Dn Slope=0.005
Boundary for River Rch & Prof#=Lacy 054,Reach-1,7
Up Type=0
Dn Type=3
Dn Slope=0.005

--- Lacy 054.g01 (geometry) ---

Geom Title=Existing Conditions

River Reach=Lacy 054,Reach-1
Reach XY= 30
      2765076.00      6889861.00      2764978.48      6889955.60
      2764956.01      6889961.03      2764855.86      6889960.67
      2764827.56      6889964.76      2764778.18      6890004.88
      2764723.82      6890017.11      2764674.41      6890057.17
      2764655.90      6890060.76      2764591.22      6890061.53
      2764573.57      6890066.55      2764496.01      6890141.66
      2764479.40      6890153.16      2764466.13      6890149.61
      2764435.68      6890121.93      2764419.95      6890112.99
      2764386.64      6890111.65      2764362.79      6890124.14
      2764183.86      6890304.83      2764176.53      6890326.22
      2764175.86      6890390.94      2764170.46      6890413.42
      2764092.49      6890494.26      2764079.63      6890512.50
      2764075.47      6890595.78      2764070.48      6890613.43
      2763936.70      6890751.29      2763928.34      6890766.97
      2763920.29      6890813.35      2763876.00      6890861.00

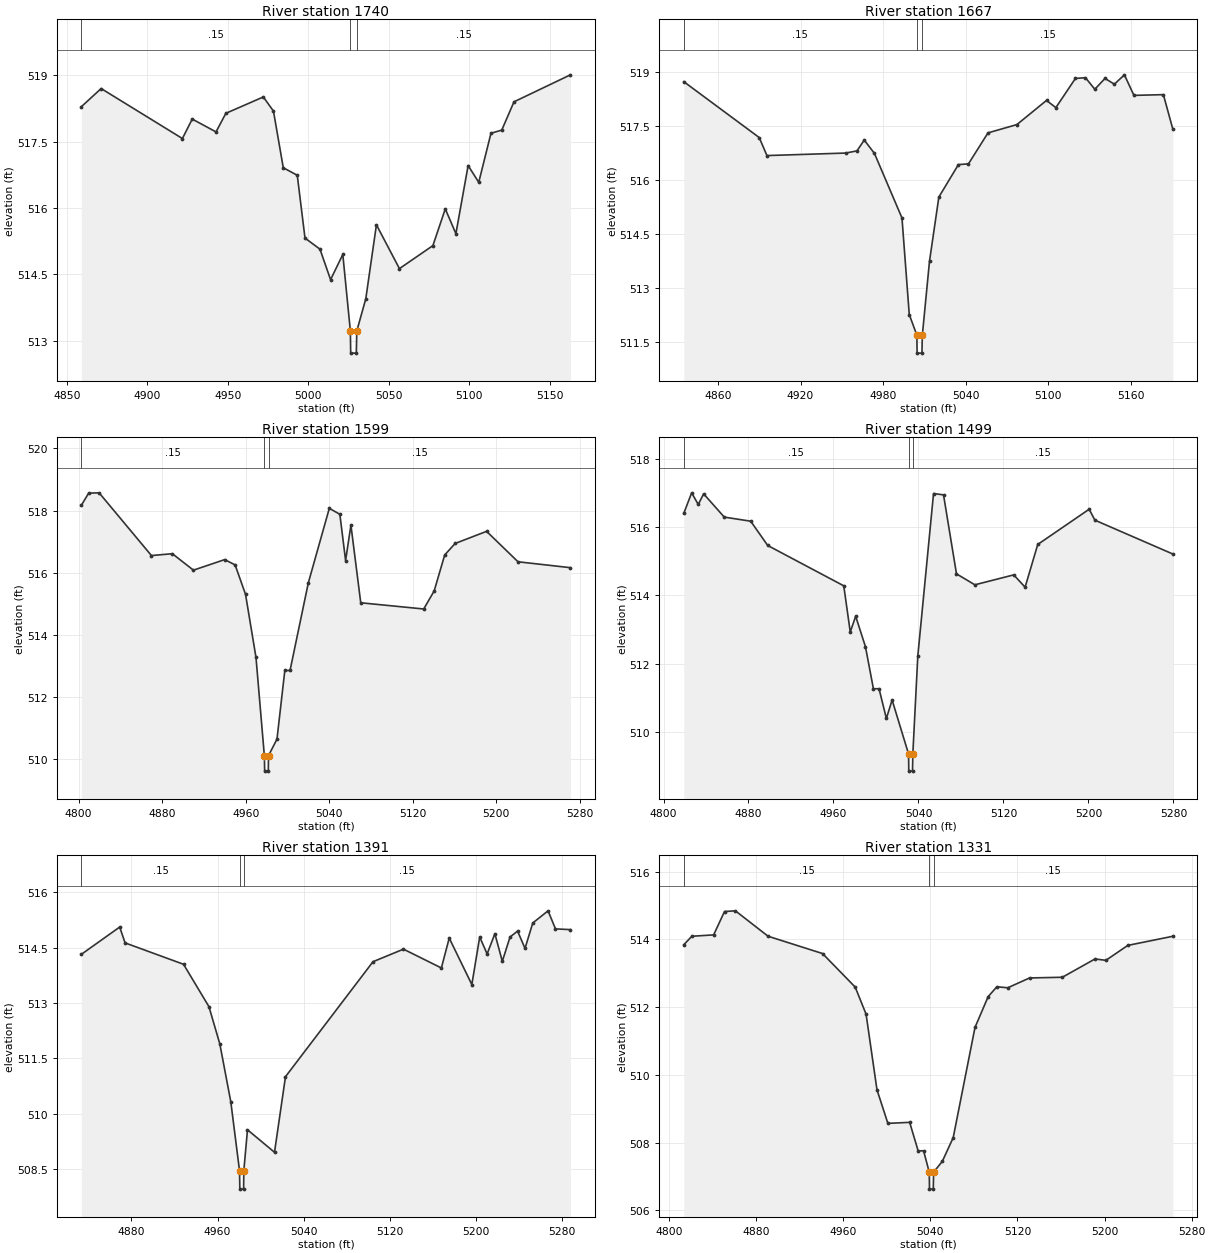
Type RM Length L Ch R = 1,1740,73,73,73
BEGIN DESCRIPTION:
Lacy 054 2627
END DESCRIPTION:
XS GIS Cut Line= 3
      2764981.94      6889758.67      2765063.33      6889873.81
      2765170.27      6889996.82
#Sta/Elev= 30
  4859.0  518.29  4871.3  518.70  4921.8  517.57  4927.9  518.01  4942.7  517.72
  4948.8  518.14  4972.1  518.51  4978.4  518.19  4984.5  516.91  4993.2  516.74
  4998.0  515.32  5007.3  515.07  5013.9  514.38  5021.5  514.95  5026.2  513.22
  5026.4  512.72  5029.9  512.72  5030.2  513.22  5035.8  513.95  5042.4  515.62
  5056.7  514.63  5077.5  515.15  5085.2  515.98  5091.8  515.42  5099.4  516.96
  5106.0  516.58  5113.6  517.69  5120.3  517.76  5127.9  518.40  5163.0  519.01
#Mann=3,-1,0
  4859.0    0.15       0  5026.2    0.05       0  5030.2    0.15       0
Bank Sta=5026.2,5030.2
Exp/Cntr=0.3,0.1

Type RM Length L Ch R = 1,1667,68,68,68
BEGIN DESCRIPTION:
Lacy 054 2626
END DESCRIPTION:
XS GIS Cut Line= 3
      2764963.13      6889768.61      2765011.57      6889926.13
      2765150.51      6890056.45
#Sta/Elev= 30
  4835.2  518.72  4890.0  517.17  4895.6  516.67  4952.8  516.74  4961.0  516.80
  4966.3  517.10  4973.7  516.73  4993.7  514.94  4999.0  512.26  5004.5  511.69
  5004.7  511.19  5008.2  511.19  5008.5  511.69  5013.7  513.74  5020.5  515.52
  5034.7  516.42  5042.0  516.44  5056.2  517.30  5077.2  517.53  5098.7  518.20
  5105.5  518.00  5119.7  518.81  5127.0  518.83  5133.8  518.51  5141.2  518.81
  5148.0  518.65  5155.3  518.91  5162.2  518.34  5183.6  518.36  5190.5  517.40
#Mann=3,-1,0
  4835.2    0.15       0  5004.5    0.05       0  5008.5    0.15       0
Bank Sta=5004.5,5008.5
Exp/Cntr=0.3,0.1

Type RM Length L Ch R = 1,1599,100,100,100
BEGIN DESCRIPTION:
Lacy 054 2625
END DESCRIPTION:
XS GIS Cut Line= 3
      2764945.58      6889764.01      2764956.01      6889961.03
      2764980.02      6890230.96
#Sta/Elev= 30
  4802.7  518.17  4809.7  518.56  4819.7  518.57  4869.8  516.55  4889.8  516.61
  4910.0  516.08  4939.9  516.42  4949.9  516.25  4959.9  515.30  4969.9  513.27
  4977.9  510.11  4978.2  509.61  4981.7  509.61  4981.9  510.11  4990.0  510.64
  4997.5  512.85  5002.5  512.85  5020.0  515.67  5040.1  518.07  5050.2  517.88
  5055.7  516.39  5060.8  517.53  5070.2  515.03  5130.5  514.83  5140.5  515.41
  5150.6  516.57  5160.6  516.94  5190.7  517.33  5220.8  516.35  5271.0  516.16
#Mann=3,-1,0
  4802.7    0.15       0  4977.9    0.05       0  4981.9    0.15       0
Bank Sta=4977.9,4981.9
Exp/Cntr=0.3,0.1

Type RM Length L Ch R = 1,1499,108,108,108
BEGIN DESCRIPTION:
Lacy 054 2624
END DESCRIPTION:
XS GIS Cut Line= 3
      2764817.91      6889783.80      2764855.86      6889960.67
      2764959.98      6890220.05
#Sta/Elev= 30
  4819.1  516.40  4826.5  517.00  4832.7  516.66  4837.8  516.97  4857.2  516.29
  4882.1  516.17  4898.1  515.46  4969.7  514.28  4975.8  512.93  4980.9  513.39
  4990.1  512.50  4997.6  511.27  5002.9  511.27  5009.8  510.40  5015.2  510.94
  5030.7  509.36  5030.9  508.86  5034.4  508.86  5034.7  509.36  5039.4  512.23
  5054.2  516.98  5063.6  516.94  5075.8  514.63  5093.1  514.31  5129.7  514.60
  5140.4  514.24  5152.3  515.49  5200.7  516.52  5206.1  516.20  5279.5  515.21
#Mann=3,-1,0
  4819.1    0.15       0  5030.7    0.05       0  5034.7    0.15       0
Bank Sta=5030.7,5034.7
Exp/Cntr=0.3,0.1

Type RM Length L Ch R = 1,1391,60,60,60
BEGIN DESCRIPTION:
Lacy 054 2623
END DESCRIPTION:
XS GIS Cut Line= 3
      2764734.27      6889844.29      2764770.98      6890053.46
      2764946.73      6890219.72
#Sta/Elev= 30
  4833.5  514.32  4869.1  515.06  4874.1  514.63  4928.4  514.05  4952.0  512.90
  4962.1  511.89  4972.3  510.32  4980.4  508.45  4980.7  507.95  4984.2  507.95
  4984.4  508.45  4987.8  509.56  5012.9  508.95  5023.1  511.00  5104.4  514.12
  5132.7  514.46  5167.9  513.95  5175.2  514.76  5196.2  513.50  5203.5  514.79
  5210.4  514.33  5217.6  514.88  5224.5  514.13  5231.7  514.79  5238.7  514.95
  5245.6  514.48  5252.8  515.17  5267.0  515.50  5273.9  515.01  5287.8  514.99
#Mann=3,-1,0
  4833.5    0.15       0  4980.4    0.05       0  4984.4    0.15       0
Bank Sta=4980.4,4984.4
Exp/Cntr=0.3,0.1

Type RM Length L Ch R = 1,1331,113,113,113
BEGIN DESCRIPTION:
Lacy 054 2622
END DESCRIPTION:
XS GIS Cut Line= 3
      2764708.68      6889843.65      2764707.73      6890061.60
      2764720.60      6890292.39
#Sta/Elev= 30
  4813.6  513.84  4821.0  514.09  4841.0  514.13  4851.0  514.82  4861.0  514.84
  4891.0  514.09  4941.0  513.58  4971.0  512.59  4981.0  511.79  4991.0  509.56
  5001.0  508.57  5021.0  508.60  5028.8  507.76  5033.8  507.76  5039.0  507.13
  5039.2  506.63  5042.7  506.63  5043.0  507.13  5051.0  507.45  5061.0  508.15
  5081.0  511.40  5093.1  512.31  5101.1  512.60  5111.1  512.57  5131.1  512.86
  5161.2  512.88  5191.2  513.42  5201.2  513.38  5221.3  513.82  5262.7  514.09
#Mann=3,-1,0
  4813.6    0.15       0  5039.0    0.05       0  5043.0    0.15       0
Bank Sta=5039,5043
Exp/Cntr=0.3,0.1

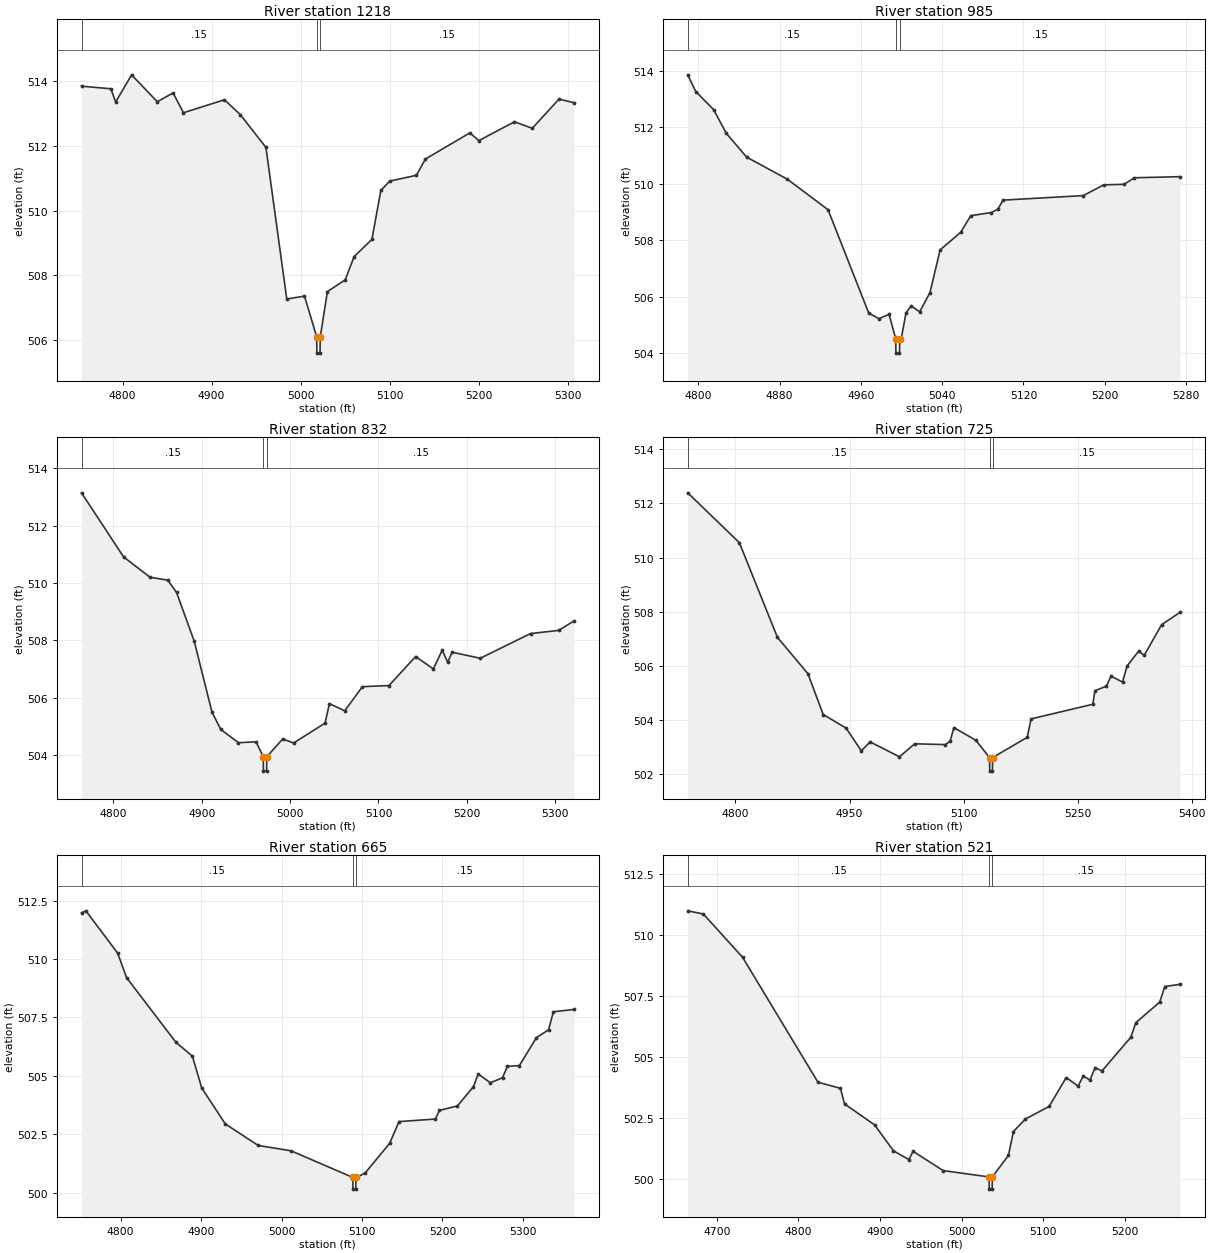
Type RM Length L Ch R = 1,1218,233,233,233
BEGIN DESCRIPTION:
Lacy 054 2621
END DESCRIPTION:
XS GIS Cut Line= 3
      2764704.44      6889836.29      2764603.42      6890065.29
      2764603.88      6890367.90
#Sta/Elev= 30
  4754.0  513.84  4786.9  513.76  4792.3  513.35  4810.2  514.19  4839.0  513.36
  4856.8  513.63  4868.4  513.02  4914.4  513.42  4932.3  512.96  4961.0  511.95
  4984.4  507.27  5004.3  507.36  5018.0  506.10  5018.2  505.60  5021.7  505.60
  5022.0  506.10  5030.0  507.50  5050.0  507.86  5060.0  508.58  5080.0  509.11
  5090.0  510.62  5100.0  510.91  5130.0  511.09  5140.0  511.59  5190.0  512.40
  5200.0  512.16  5240.0  512.74  5260.0  512.54  5290.0  513.44  5306.9  513.33
#Mann=3,-1,0
  4754.0    0.15       0  5018.0    0.05       0  5022.0    0.15       0
Bank Sta=5018,5022
Exp/Cntr=0.3,0.1

Type RM Length L Ch R = 1,985,153,153,153
BEGIN DESCRIPTION:
Lacy 054 2620
END DESCRIPTION:
XS GIS Cut Line= 3
      2764409.56      6889903.08      2764420.30      6890112.93
      2764450.68      6890385.82
#Sta/Elev= 30
  4789.6  513.85  4797.5  513.26  4815.1  512.62  4827.6  511.78  4847.6  510.94
  4887.6  510.16  4927.7  509.08  4967.8  505.42  4977.8  505.23  4987.8  505.38
  4994.3  504.51  4994.5  504.01  4998.0  504.01  4998.3  504.51  4999.7  504.51
  5004.4  505.43  5009.5  505.68  5017.9  505.47  5028.0  506.15  5038.0  507.66
  5058.2  508.28  5068.2  508.87  5088.3  508.98  5094.9  509.10  5099.9  509.42
  5178.9  509.58  5199.0  509.96  5219.1  509.98  5229.2  510.21  5274.3  510.25
#Mann=3,-1,0
  4789.6    0.15       0  4994.3    0.05       0  4998.3    0.15       0
Bank Sta=4994.3,4998.3
Exp/Cntr=0.3,0.1

Type RM Length L Ch R = 1,832,107,107,107
BEGIN DESCRIPTION:
Lacy 054 2614
END DESCRIPTION:
XS GIS Cut Line= 4
      2764297.03      6889953.49      2764298.20      6890193.35
      2764313.40      6890401.23      2764366.57      6890496.15
#Sta/Elev= 30
  4764.1  513.14  4811.6  510.91  4841.6  510.20  4861.6  510.10  4871.6  509.67
  4891.6  507.97  4911.6  505.51  4921.6  504.90  4941.6  504.44  4961.6  504.47
  4969.6  503.95  4969.9  503.45  4973.4  503.45  4973.6  503.95  4991.6  504.57
  5004.0  504.43  5039.5  505.12  5044.5  505.80  5061.8  505.55  5081.8  506.39
  5111.9  506.43  5142.0  507.44  5162.0  507.01  5172.1  507.66  5178.3  507.24
  5183.3  507.59  5215.1  507.38  5272.0  508.24  5303.8  508.35  5321.2  508.68
#Mann=3,-1,0
  4764.1    0.15       0  4969.6    0.05       0  4973.6    0.15       0
Bank Sta=4969.6,4973.6
Exp/Cntr=0.3,0.1

Type RM Length L Ch R = 1,725,60,60,60
BEGIN DESCRIPTION:
Lacy 054 2613
END DESCRIPTION:
XS GIS Cut Line= 4
      2764203.94      6890003.29      2764223.06      6890267.62
      2764249.19      6890534.16      2764311.56      6890630.73
#Sta/Elev= 30
  4737.2  512.39  4805.1  510.55  4855.2  507.05  4895.3  505.71  4915.4  504.20
  4945.5  503.70  4965.5  502.86  4977.1  503.19  5015.7  502.64  5035.8  503.12
  5076.0  503.09  5082.3  503.21  5087.3  503.72  5116.1  503.25  5134.2  502.61
  5134.5  502.11  5138.0  502.11  5138.2  502.61  5183.8  503.36  5188.8  504.04
  5270.0  504.58  5272.8  505.08  5288.0  505.25  5293.9  505.62  5309.1  505.40
  5315.0  505.99  5330.2  506.54  5337.7  506.39  5360.5  507.52  5385.0  507.98
#Mann=3,-1,0
  4737.2    0.15       0  5134.2    0.05       0  5138.2    0.15       0
Bank Sta=5134.2,5138.2
Exp/Cntr=0.3,0.1

Type RM Length L Ch R = 1,665,144,144,144
BEGIN DESCRIPTION:
Lacy 054 2619
END DESCRIPTION:
XS GIS Cut Line= 4
      2764130.86      6890066.17      2764182.29      6890309.37
      2764225.69      6890520.03      2764307.44      6890644.05
#Sta/Elev= 30
  4751.4  511.97  4756.8  512.06  4796.3  510.25  4807.4  509.20  4868.8  506.43
  4889.2  505.84  4900.8  504.48  4930.1  502.94  4971.0  502.02  5011.8  501.79
  5088.6  500.65  5088.8  500.15  5092.3  500.15  5092.6  500.65  5103.7  500.83
  5134.4  502.11  5146.0  503.04  5191.2  503.15  5196.3  503.52  5218.6  503.71
  5238.5  504.53  5244.5  505.08  5259.6  504.70  5274.7  504.92  5280.7  505.40
  5295.7  505.44  5316.8  506.63  5331.9  506.97  5337.9  507.74  5363.6  507.84
#Mann=3,-1,0
  4751.4    0.15       0  5088.6    0.05       0  5092.6    0.15       0
Bank Sta=5088.6,5092.6
Exp/Cntr=0.3,0.1

Type RM Length L Ch R = 1,521,63,63,63
BEGIN DESCRIPTION:
Lacy 054 2615
END DESCRIPTION:
XS GIS Cut Line= 3
      2764066.92      6890115.67      2764145.44      6890442.98
      2764305.20      6890657.29
#Sta/Elev= 30
  4664.3  510.99  4683.5  510.86  4731.5  509.09  4824.0  503.97  4851.5  503.72
  4856.6  503.08  4893.5  502.22  4916.6  501.16  4935.5  500.80  4940.6  501.14
  4977.5  500.35  5033.8  500.09  5034.1  499.59  5037.6  499.59  5037.8  500.09
  5057.5  500.97  5063.7  501.95  5078.3  502.46  5107.5  502.98  5128.4  504.16
  5143.0  503.81  5149.2  504.22  5157.6  504.06  5163.8  504.57  5172.2  504.43
  5207.6  505.81  5213.8  506.41  5243.0  507.25  5249.3  507.89  5268.2  507.98
#Mann=3,-1,0
  4664.3    0.15       0  5033.8    0.05       0  5037.8    0.15       0
Bank Sta=5033.8,5037.8
Exp/Cntr=0.3,0.1

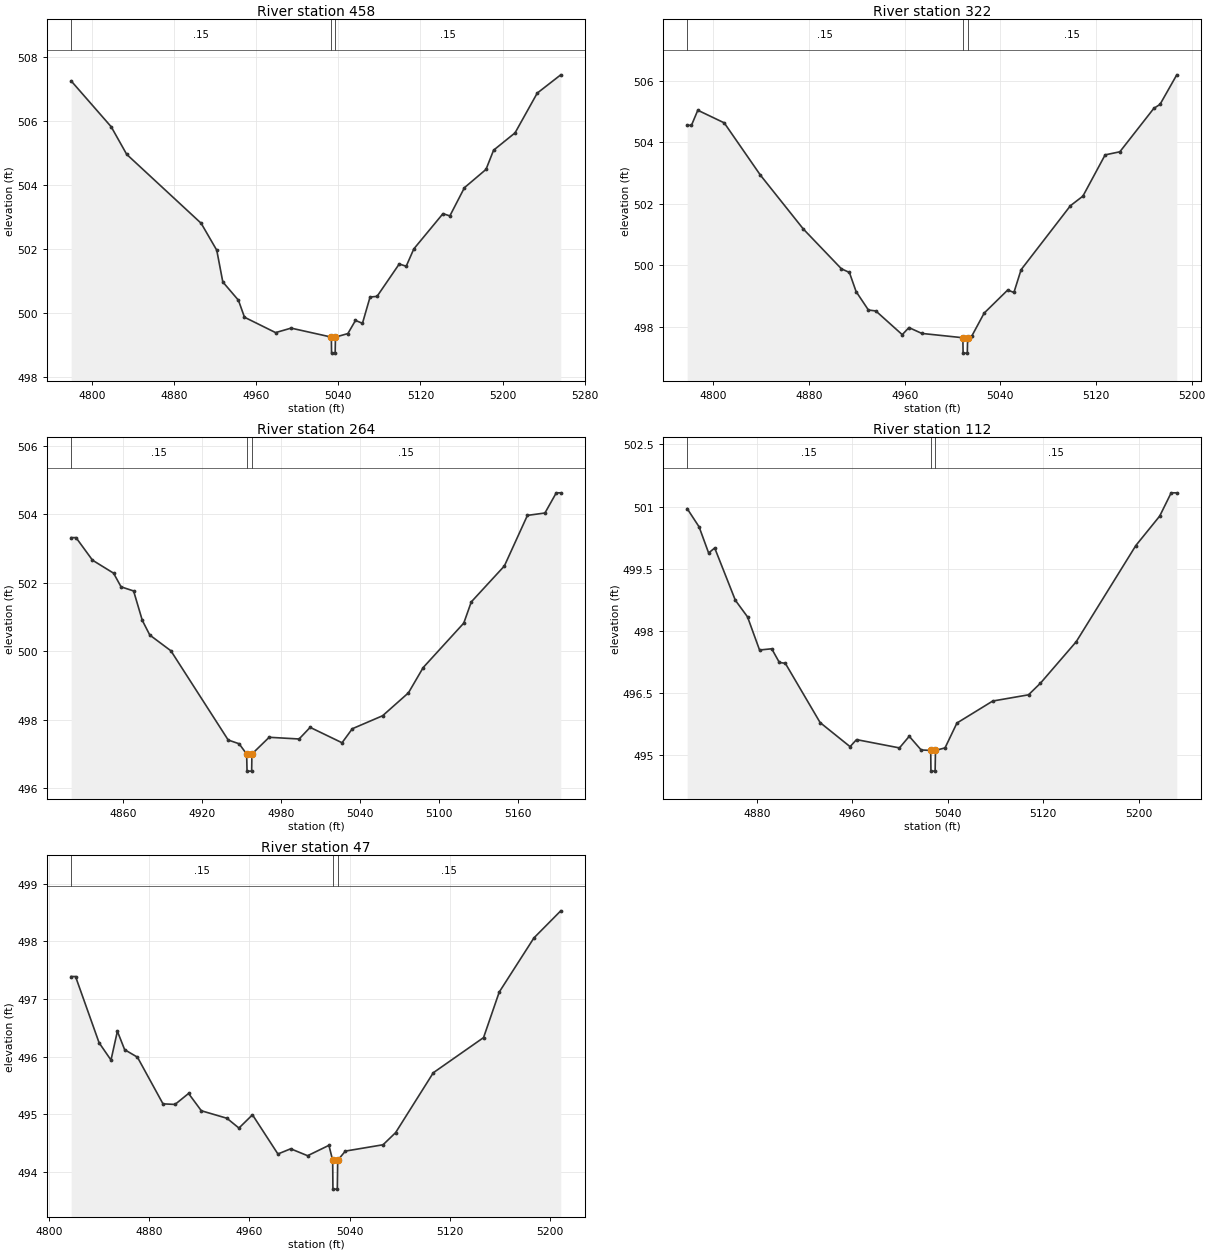
Type RM Length L Ch R = 1,458,136,136,136
BEGIN DESCRIPTION:
Lacy 054 2616
END DESCRIPTION:
XS GIS Cut Line= 3
      2763981.11      6890301.30      2764101.03      6890486.13
      2764290.26      6890659.25
#Sta/Elev= 30
  4779.9  507.25  4818.9  505.82  4834.0  504.96  4906.5  502.81  4921.7  501.97
  4927.6  500.98  4942.8  500.41  4948.7  499.88  4979.0  499.40  4994.1  499.54
  5033.3  499.26  5033.5  498.76  5037.0  498.76  5037.3  499.26  5049.4  499.37
  5056.8  499.78  5063.6  499.69  5071.0  500.51  5077.8  500.53  5099.4  501.54
  5106.2  501.47  5113.6  502.01  5142.0  503.11  5148.7  503.04  5162.9  503.92
  5183.9  504.49  5191.3  505.09  5212.2  505.63  5233.8  506.87  5256.7  507.44
#Mann=3,-1,0
  4779.9    0.15       0  5033.3    0.05       0  5037.3    0.15       0
Bank Sta=5033.3,5037.3
Exp/Cntr=0.3,0.1

Type RM Length L Ch R = 1,322,58,58,58
BEGIN DESCRIPTION:
Lacy 054 2618
END DESCRIPTION:
XS GIS Cut Line= 3
      2763967.65      6890416.67      2764070.48      6890613.43
      2764252.06      6890660.15
#Sta/Elev= 30
  4778.0  504.55  4781.6  504.55  4786.9  505.04  4809.0  504.63  4839.3  502.93
  4875.2  501.18  4907.0  499.89  4913.7  499.77  4919.3  499.15  4929.6  498.55
  4935.8  498.52  4957.9  497.75  4963.5  497.98  4974.3  497.79  5008.6  497.65
  5008.8  497.15  5012.3  497.15  5012.6  497.65  5016.0  497.70  5026.4  498.45
  5046.1  499.20  5051.3  499.12  5057.3  499.86  5098.6  501.94  5109.0  502.25
  5127.6  503.59  5139.9  503.69  5168.3  505.10  5173.5  505.23  5187.5  506.19
#Mann=3,-1,0
  4778.0    0.15       0  5008.6    0.05       0  5012.6    0.15       0
Bank Sta=5008.6,5012.6
Exp/Cntr=0.3,0.1

Type RM Length L Ch R = 1,264,152,152,152
BEGIN DESCRIPTION:
Lacy 054 2617
END DESCRIPTION:
XS GIS Cut Line= 3
      2763944.42      6890499.52      2764032.40      6890658.14
      2764217.67      6890701.27
#Sta/Elev= 30
  4820.7  503.32  4824.4  503.32  4836.9  502.66  4852.9  502.28  4858.6  501.88
  4868.1  501.76  4874.7  500.90  4880.4  500.47  4896.4  500.01  4939.9  497.40
  4948.2  497.29  4953.9  496.99  4954.2  496.49  4957.7  496.49  4957.9  496.99
  4971.0  497.48  4993.7  497.43  5002.1  497.77  5026.3  497.32  5034.1  497.73
  5057.1  498.11  5076.7  498.78  5087.9  499.52  5118.7  500.82  5124.4  501.44
  5149.5  502.49  5167.0  503.97  5180.3  504.04  5188.9  504.63  5192.3  504.63
#Mann=3,-1,0
  4820.7    0.15       0  4953.9    0.05       0  4957.9    0.15       0
Bank Sta=4953.9,4957.9
Exp/Cntr=0.3,0.1

Type RM Length L Ch R = 1,112,65,65,65
BEGIN DESCRIPTION:
Lacy 054 2612
END DESCRIPTION:
XS GIS Cut Line= 3
      2763897.38      6890591.17      2763928.34      6890766.97
      2764160.30      6890771.15
#Sta/Elev= 30
  4821.5  500.95  4831.5  500.51  4839.5  499.88  4844.6  500.00  4861.9  498.74
  4872.1  498.34  4882.2  497.54  4892.4  497.57  4898.8  497.24  4903.8  497.22
  4933.0  495.79  4958.1  495.21  4963.5  495.38  4999.5  495.18  5007.7  495.46
  5017.7  495.13  5025.7  495.12  5025.9  494.62  5029.4  494.62  5029.7  495.12
  5037.7  495.18  5047.7  495.78  5077.7  496.31  5107.7  496.46  5117.7  496.74
  5147.7  497.74  5197.7  500.06  5217.7  500.77  5227.3  501.33  5232.0  501.33
#Mann=3,-1,0
  4821.5    0.15       0  5025.7    0.05       0  5029.7    0.15       0
Bank Sta=5025.7,5029.7
Exp/Cntr=0.3,0.1

Type RM Length L Ch R = 1,47,0,0,0
BEGIN DESCRIPTION:
Lacy 054 3492
END DESCRIPTION:
XS GIS Cut Line= 3
      2763873.91      6890649.15      2763909.58      6890827.92
      2764117.37      6890812.07
#Sta/Elev= 30
  4817.7  497.39  4821.2  497.39  4840.0  496.24  4849.5  495.94  4854.6  496.44
  4860.4  496.12  4870.6  495.99  4891.0  495.18  4900.6  495.17  4911.4  495.36
  4921.6  495.06  4942.0  494.93  4951.6  494.76  4962.4  494.99  4982.7  494.31
  4992.9  494.40  5006.4  494.28  5023.4  494.46  5026.4  494.20  5026.6  493.70
  5030.1  493.70  5030.4  494.20  5036.5  494.36  5066.6  494.47  5076.6  494.68
  5106.7  495.72  5146.8  496.33  5159.3  497.12  5187.0  498.06  5208.4  498.53
#Mann=3,-1,0
  4817.7    0.15       0  5026.4    0.05       0  5030.4    0.15       0
Bank Sta=5026.4,5030.4
Exp/Cntr=0.3,0.1

Chan Stop Cuts=-1