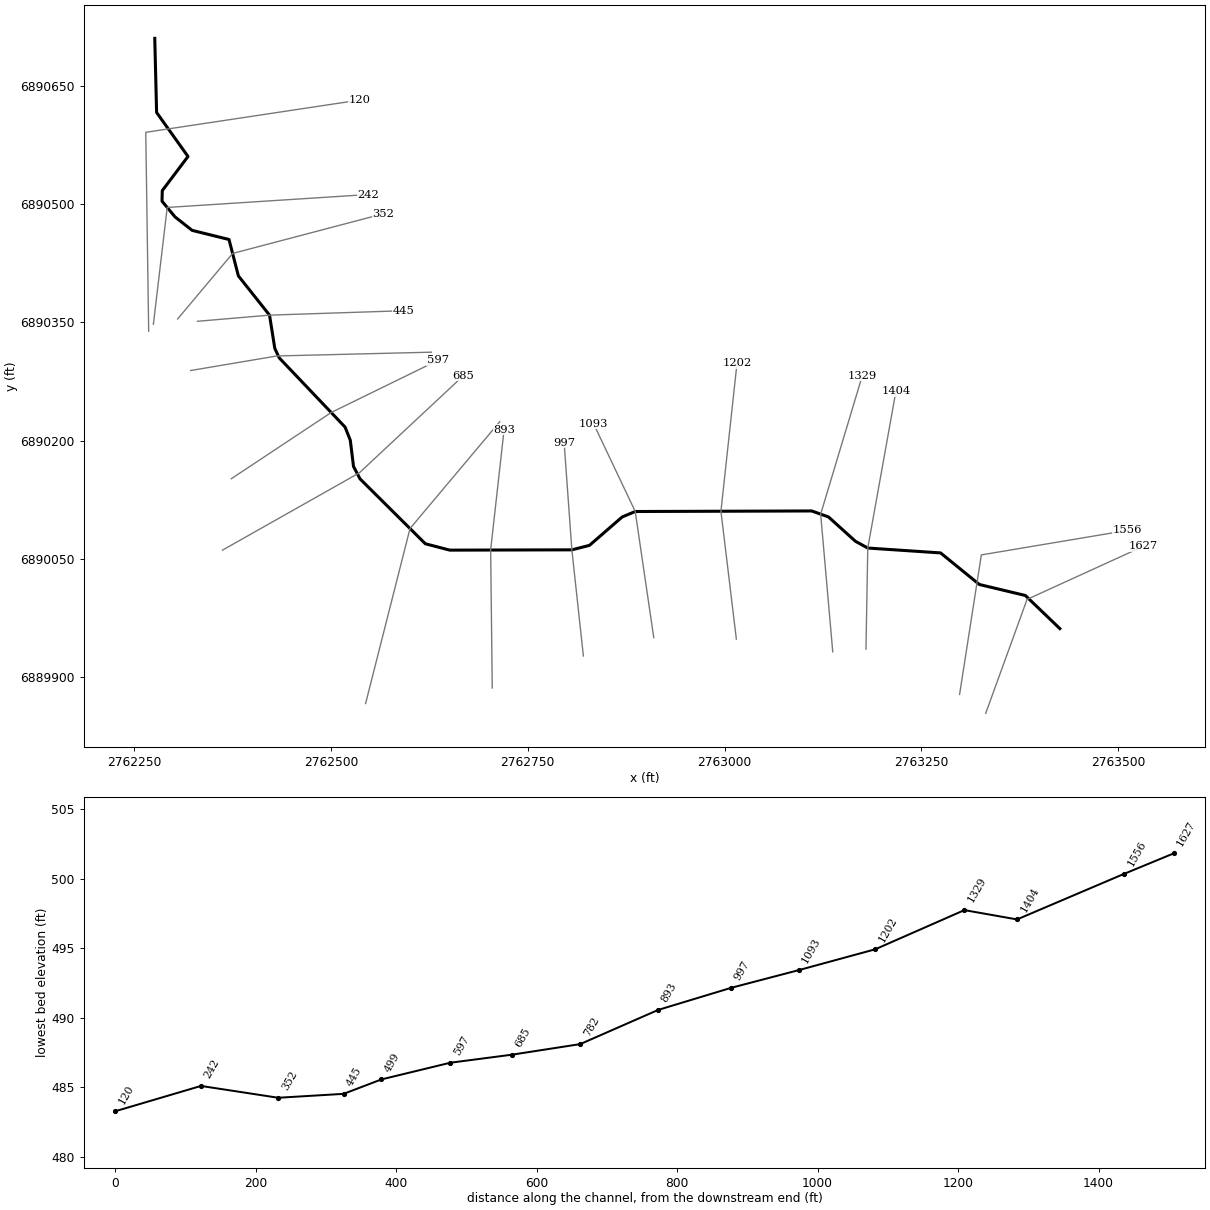
--- Lacy 055.prj (project) ---

Proj Title=Lacy 055 Base Level Engineering
Current Plan=p01
Default Exp/Contr=0.3,0.1
English Units
Geom File=g01
Flow File=f01
Plan File=p01
Y Axis Title=Elevation
X Axis Title(PF)=Main Channel Distance
X Axis Title(XS)=Station
BEGIN DESCRIPTION:
Lacy 055
END DESCRIPTION:
DSS Export Rating Curves= 0
DSS Export Rating Curve Sorted= 0
DSS Export Volume Flow Curves= 0
DXF OffsetX= 0
DXF OffsetY= 0
DXF ScaleX= 1
DXF ScaleY= 10

--- Lacy 055.p01 (plan) ---

Plan Title=Multiple Run
Short Identifier=Multiple
Geom File=g01
Flow File=f01
Subcritical Flow
K Sum by GR= 0
Std Step Tol= 0.01
Critical Tol= 0.01
Num of Std Step Trials= 20
Max Error Tol= 0.3
Flow Tol Ratio= 0.001
Split Flow NTrial= 30
Split Flow Tol= 0.02
Split Flow Ratio= 0.02
Log Output Level= 0
Friction Slope Method= 1
Unsteady Friction Slope Method= 2
Unsteady Bridges Friction Slope Method= 1
Parabolic Critical Depth
Global Vel Dist=  1 , 1 , 1
Global Log Level= 0
CheckData=True
Encroach Param= -1, 0, 0, 0
BEGIN DESCRIPTION:
Multiple Run
END DESCRIPTION:

--- Lacy 055.f01 (steady flow) ---

Flow Title=Multiple
Number of Profiles=7
Profile Names=10-year,25-year,50-year,1pct_min,100-year,1pct_plu,500-year
River Rch & RM= Lacy 055,Reach-1,1627
     129     156     177     101     201     400     256
Boundary for River Rch & Prof#=Lacy 055,Reach-1,1
Up Type=0
Dn Type=3
Dn Slope=0.005
Boundary for River Rch & Prof#=Lacy 055,Reach-1,2
Up Type=0
Dn Type=3
Dn Slope=0.005
Boundary for River Rch & Prof#=Lacy 055,Reach-1,3
Up Type=0
Dn Type=3
Dn Slope=0.005
Boundary for River Rch & Prof#=Lacy 055,Reach-1,4
Up Type=0
Dn Type=3
Dn Slope=0.005
Boundary for River Rch & Prof#=Lacy 055,Reach-1,5
Up Type=0
Dn Type=3
Dn Slope=0.005
Boundary for River Rch & Prof#=Lacy 055,Reach-1,6
Up Type=0
Dn Type=3
Dn Slope=0.005
Boundary for River Rch & Prof#=Lacy 055,Reach-1,7
Up Type=0
Dn Type=3
Dn Slope=0.005

--- Lacy 055.g01 (geometry) ---

Geom Title=Existing Conditions
Program Version=4.10

River Reach=Lacy 055        ,Reach-1
Reach XY= 30
        2763426.        6889961.      2763382.15      6890003.09
      2763323.78      6890017.03      2763274.42      6890057.18
      2763181.98      6890063.36      2763166.37      6890071.89
      2763132.06      6890102.86      2763110.78      6890110.48
       2762886.5      6890109.78      2762869.94      6890102.86
      2762828.33      6890066.75      2762805.97      6890061.07
      2762650.88       6890060.7      2762619.79       6890068.8
      2762536.77       6890151.3      2762528.53      6890167.04
      2762524.44      6890200.35      2762517.82      6890217.04
      2762434.16      6890304.95      2762428.51      6890317.04
      2762421.82      6890359.29      2762382.24      6890409.15
      2762370.34      6890455.39       2762323.5      6890466.99
      2762301.78      6890484.07      2762285.22      6890504.07
      2762285.55      6890517.51      2762318.23      6890560.89
      2762278.33      6890616.77        2762276.        6890711.

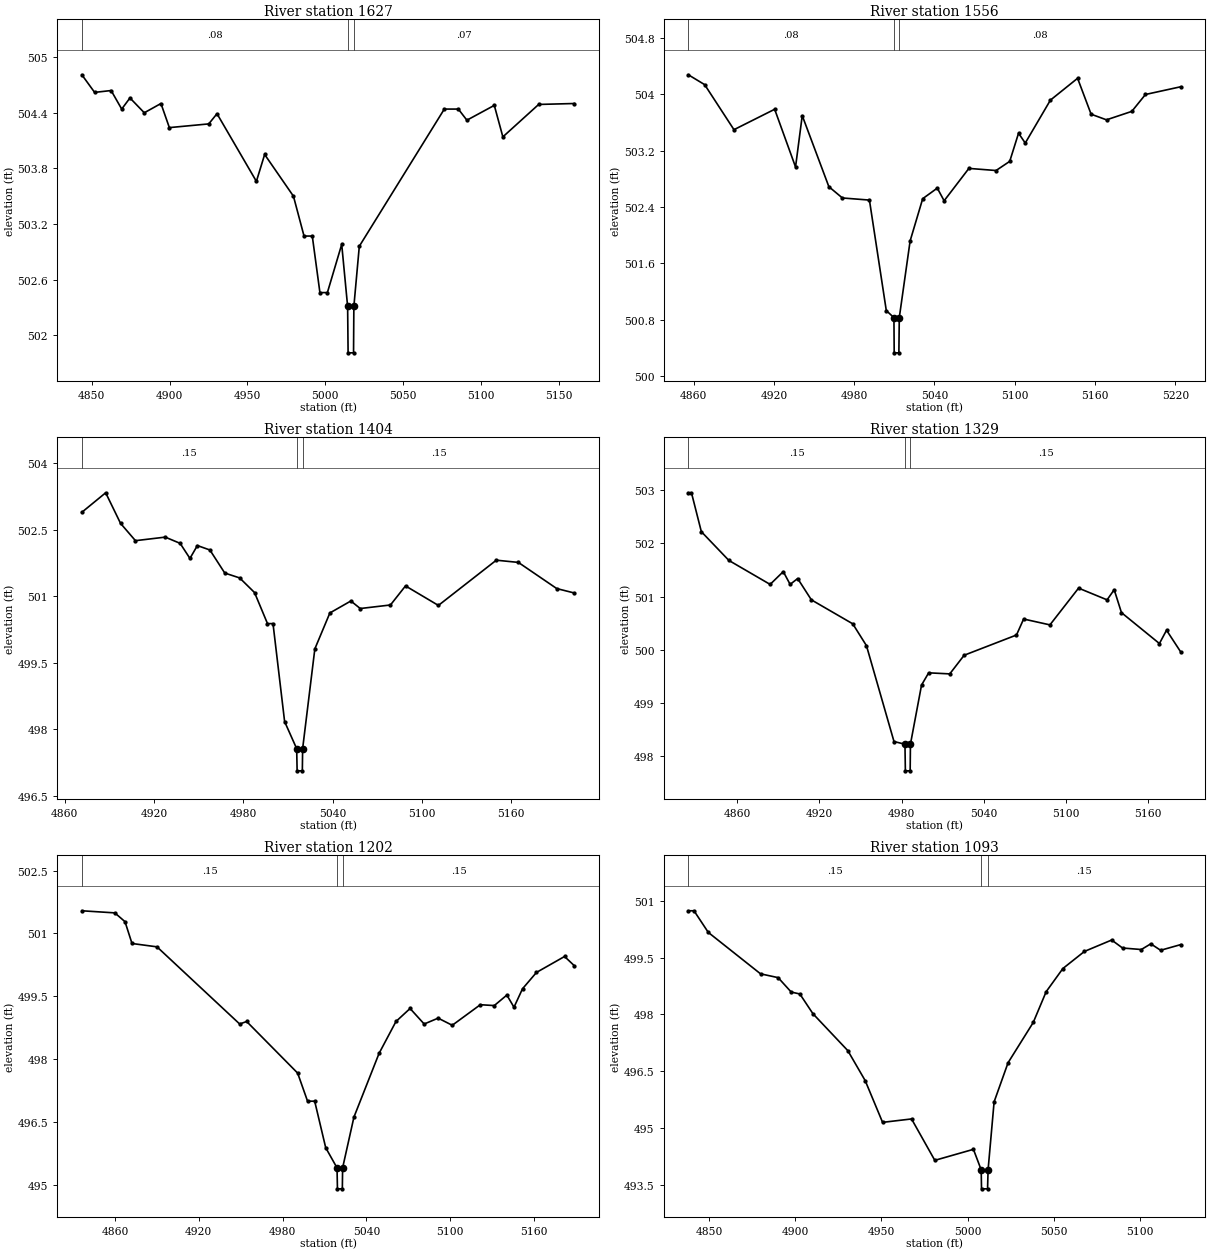
Type RM Length L Ch R = 1 ,1627    ,71,71,71
BEGIN DESCRIPTION:
Lacy 055 2605
END DESCRIPTION:
XS GIS Cut Line= 3
      2763331.79      6889853.28      2763384.33      6889998.09
      2763531.93      6890065.48
#Sta/Elev= 30
  4843.7  504.81  4851.9  504.62  4862.5  504.64  4869.3  504.44  4874.6  504.56
  4883.8   504.4  4894.5   504.5  4899.9  504.24  4925.2  504.28  4930.5  504.39
  4955.8  503.66  4961.1  503.95  4979.6   503.5  4986.4  503.07  4991.7  503.07
  4996.6  502.46  5001.4  502.46  5010.6  502.98  5014.4  502.31  5014.7  501.81
  5018.2  501.81  5018.4  502.31  5021.9  502.96  5076.5  504.44  5085.5  504.44
    5091  504.32  5108.6  504.48  5114.1  504.14  5137.1  504.49    5160   504.5
#Mann= 3 ,-1 , 0
  4843.7     .08       0  5014.4     .04       0  5018.4     .07       0
Bank Sta=5014.4,5018.4
XS Rating Curve= 0 ,0
Exp/Cntr=0.3,0.1

Type RM Length L Ch R = 1 ,1556    ,152,152,152
BEGIN DESCRIPTION:
Lacy 055 2604
END DESCRIPTION:
XS GIS Cut Line= 3
      2763298.61      6889877.29      2763326.25      6890054.63
      2763512.08      6890085.82
#Sta/Elev= 30
  4856.1  504.28  4868.3  504.14  4890.2   503.5  4920.6  503.79  4936.2  502.97
  4941.2   503.7  4961.1  502.69  4971.2  502.53  4991.4   502.5    5004  500.93
  5009.7  500.83  5009.9  500.33  5013.4  500.33  5013.7  500.83  5021.8  501.92
  5031.2  502.52  5042.1  502.67  5047.2  502.49  5065.7  502.95    5086  502.92
  5096.2  503.05  5102.8  503.45  5107.8  503.31  5126.6  503.92  5146.9  504.23
    5157  503.72  5168.5  503.64  5187.4  503.76  5197.6     504    5224  504.11
#Mann= 3 ,-1 , 0
  4856.1     .08       0  5009.7     .05       0  5013.7     .08       0
Bank Sta=5009.7,5013.7
XS Rating Curve= 0 ,0
Exp/Cntr=0.3,0.1

Type RM Length L Ch R = 1 ,1404    ,75,75,75
BEGIN DESCRIPTION:
Lacy 055 2602
END DESCRIPTION:
XS GIS Cut Line= 3
      2763179.67      6889934.98      2763181.98      6890063.36
      2763217.74      6890262.57
#Sta/Elev= 30
  4871.6  502.89  4887.6  503.33  4897.6  502.64  4907.6  502.25  4927.6  502.33
  4937.6  502.19  4944.2  501.85  4949.2  502.14  4957.6  502.04  4967.6  501.52
  4977.6  501.41  4987.6  501.08  4996.3  500.38    5000  500.38  5007.8  498.17
  5015.9  497.56  5016.2  497.06  5019.7  497.06  5019.9  497.56  5028.1  499.81
  5038.2  500.62  5052.3  500.89  5058.6  500.72  5078.9   500.8    5089  501.23
  5111.1  500.79    5150  501.81  5164.8  501.76  5190.6  501.17  5202.4  501.07
#Mann= 3 ,-1 , 0
  4871.6     .15       0  5015.9     .05       0  5019.9     .15       0
Bank Sta=5015.9,5019.9
XS Rating Curve= 0 ,0
Exp/Cntr=0.3,0.1

Type RM Length L Ch R = 1 ,1329    ,127,127,127
BEGIN DESCRIPTION:
Lacy 055 2600
END DESCRIPTION:
XS GIS Cut Line= 3
      2763137.46       6889931.5       2763122.1      6890106.43
      2763175.04      6890282.44
#Sta/Elev= 30
  4824.4  502.95  4826.7  502.95  4833.9  502.22    4854  501.68  4884.1  501.23
  4893.7  501.47  4898.7  501.23  4904.2  501.34  4914.2  500.94  4944.4  500.49
  4954.4  500.08  4974.5  498.28  4982.5  498.23  4982.8  497.73  4986.3  497.73
  4986.5  498.23  4994.6  499.34  4999.8  499.57  5015.2  499.55  5025.7   499.9
  5063.9  500.28  5069.1  500.58  5088.3  500.47  5109.2  501.16    5130  500.94
  5135.2  501.13  5140.5   500.7  5168.2  500.12  5173.4  500.37  5183.8  499.96
#Mann= 3 ,-1 , 0
  4824.4     .15       0  4982.5     .05       0  4986.5     .15       0
Bank Sta=4982.5,4986.5
XS Rating Curve= 0 ,0
Exp/Cntr=0.3,0.1

Type RM Length L Ch R = 1 ,1202    ,109,109,109
BEGIN DESCRIPTION:
Lacy 055 2601
END DESCRIPTION:
XS GIS Cut Line= 3
      2763014.98       6889947.6      2762995.38      6890110.12
      2763015.79      6890297.91
#Sta/Elev= 30
  4836.3  501.54  4859.9  501.49  4867.2  501.28  4872.2  500.76  4890.1  500.68
  4949.3  498.84  4954.3   498.9  4990.8  497.67  4997.9     497    5003     497
  5010.9  495.89    5019  495.41  5019.3  494.91  5022.8  494.91    5023  495.41
  5031.1  496.62  5049.1  498.14  5061.2   498.9  5071.3  499.21  5081.4  498.84
  5091.4  498.98  5101.5  498.81  5121.6   499.3  5131.6  499.28  5140.6  499.53
  5145.7  499.24  5151.8  499.68  5161.8  500.07  5181.9  500.45  5188.9  500.23
#Mann= 3 ,-1 , 0
  4836.3     .15       0    5019     .05       0    5023     .15       0
Bank Sta=5019,5023
XS Rating Curve= 0 ,0
Exp/Cntr=0.3,0.1

Type RM Length L Ch R = 1 ,1093    ,96,96,96
BEGIN DESCRIPTION:
Lacy 055 2606
END DESCRIPTION:
XS GIS Cut Line= 3
      2762910.04       6889949.5       2762886.5      6890109.78
      2762833.46      6890221.53
#Sta/Elev= 30
    4838  500.73  4841.3  500.73  4849.6  500.16  4879.9  499.07  4890.1  498.97
  4897.7  498.59  4902.7  498.54  4910.3  498.02  4930.5  497.05  4940.6  496.26
  4950.7  495.16  4967.5  495.25    4981  494.16  5003.4  494.45  5007.9  493.91
  5008.1  493.41  5011.6  493.41  5011.9  493.91  5015.4   495.7  5023.5  496.73
  5038.1  497.79  5045.6   498.6  5055.3  499.21  5067.8  499.66  5083.6  499.96
  5089.9  499.75  5100.8  499.71  5106.3  499.86    5112  499.69  5123.7  499.84
#Mann= 3 ,-1 , 0
    4838     .15       0  5007.9     .05       0  5011.9     .15       0
Bank Sta=5007.9,5011.9
XS Rating Curve= 0 ,0
Exp/Cntr=0.3,0.1

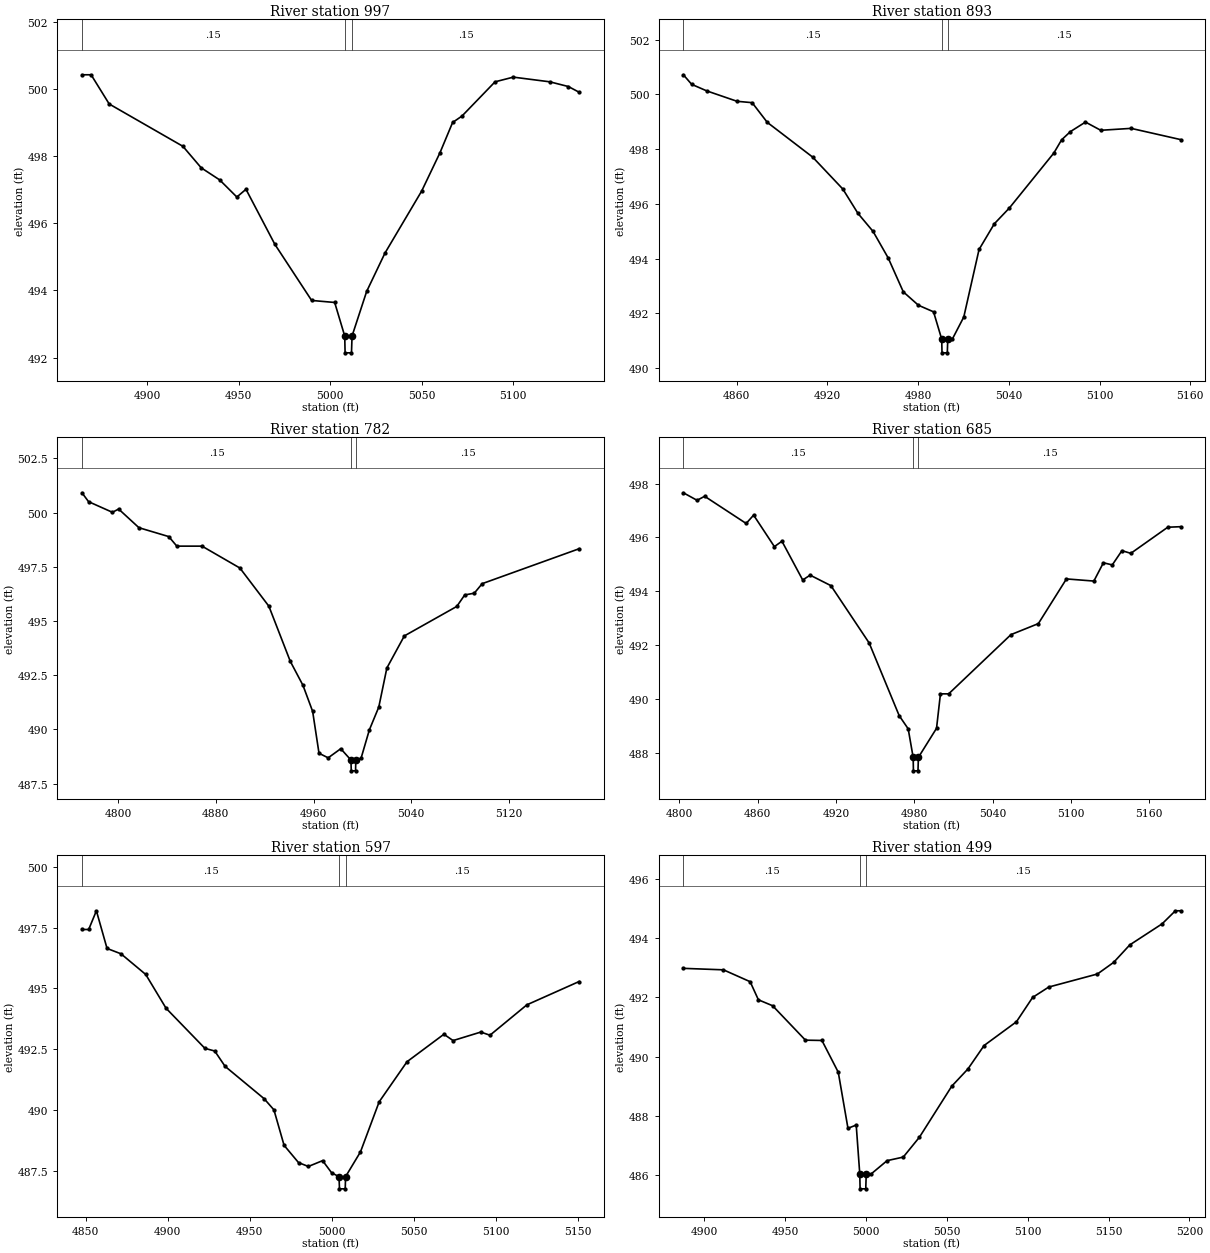
Type RM Length L Ch R = 1 ,997     ,104,104,104
BEGIN DESCRIPTION:
Lacy 055 2599
END DESCRIPTION:
XS GIS Cut Line= 3
      2762820.61      6889926.16      2762805.97      6890061.07
      2762796.16      6890196.92
#Sta/Elev= 26
  4864.3  500.42  4869.3  500.42  4879.2  499.55  4919.5  498.29  4929.5  497.65
  4939.6  497.29    4949  496.78    4954  497.01  4969.8  495.37  4989.9   493.7
  5002.5  493.64    5008  492.64  5008.2  492.14  5011.7  492.14    5012  492.64
    5020  493.97    5030  495.11  5050.1  496.96  5060.1   498.1    5067     499
  5072.1  499.19  5090.2  500.21  5100.2  500.35  5120.2  500.21  5130.3  500.07
  5136.2   499.9
#Mann= 3 ,-1 , 0
  4864.3     .15       0    5008     .05       0    5012     .15       0
Bank Sta=5008,5012
XS Rating Curve= 0 ,0
Exp/Cntr=0.3,0.1

Type RM Length L Ch R = 1 ,893     ,111,111,111
BEGIN DESCRIPTION:
Lacy 055 2598
END DESCRIPTION:
XS GIS Cut Line= 3
      2762704.83      6889885.54      2762702.77      6890060.82
      2762719.83      6890213.47
#Sta/Elev= 30
  4824.7  500.72  4830.2  500.37  4840.2  500.13  4860.2  499.75  4870.2   499.7
  4880.2  498.98  4910.2  497.71  4930.2  496.54  4940.2  495.65  4950.2  494.99
  4960.2  494.02  4970.2  492.78  4980.2  492.29  4990.2  492.05  4995.6  491.05
  4995.8  490.55  4999.3  490.55  4999.6  491.05  5002.6  491.05  5010.2  491.86
  5020.3  494.33  5030.4  495.27  5040.4  495.85  5069.8  497.86  5074.9  498.34
  5080.7  498.64  5090.7  498.99  5100.8  498.69  5120.9  498.76  5153.6  498.35
#Mann= 3 ,-1 , 0
  4824.7     .15       0  4995.6     .05       0  4999.6     .15       0
Bank Sta=4995.6,4999.6
XS Rating Curve= 0 ,0
Exp/Cntr=0.3,0.1

Type RM Length L Ch R = 1 ,782     ,97,97,97
BEGIN DESCRIPTION:
Lacy 055 2597
END DESCRIPTION:
XS GIS Cut Line= 3
      2762543.89       6889865.8      2762600.32      6890088.15
      2762714.37       6890223.9
#Sta/Elev= 30
  4770.6  500.91    4776   500.5  4795.5  500.01  4800.6  500.16  4817.2   499.3
  4841.6  498.89  4848.2  498.45  4868.8  498.45  4899.8  497.44  4923.5  495.68
    4941  493.14  4951.4  492.03  4959.3  490.83  4964.5   488.9    4972  488.69
  4982.3  489.11  4990.6  488.59  4990.9  488.09  4994.4  488.09  4994.6  488.59
  4998.9  488.67  5005.7  489.98  5013.4  491.03    5020  492.83  5034.3  494.31
  5077.2  495.67  5083.7   496.2  5091.5  496.28    5098  496.72  5177.3  498.33
#Mann= 3 ,-1 , 0
  4770.6     .15       0  4990.6     .05       0  4994.6     .15       0
Bank Sta=4990.6,4994.6
XS Rating Curve= 0 ,0
Exp/Cntr=0.3,0.1

Type RM Length L Ch R = 1 ,685     ,88,88,88
BEGIN DESCRIPTION:
Lacy 055 2596
END DESCRIPTION:
XS GIS Cut Line= 3
      2762362.07      6890060.69      2762535.96      6890158.93
      2762668.32       6890282.5
#Sta/Elev= 30
  4803.1  497.66  4813.6  497.38  4819.4  497.53  4851.2  496.52  4856.9  496.83
  4872.8  495.66  4878.6  495.86  4894.5  494.42  4900.2   494.6  4916.1  494.21
  4945.4  492.08  4968.4  489.38  4975.3  488.89  4979.1  487.83  4979.3  487.33
  4982.8  487.33  4983.1  487.83    4997  488.91    5000  490.19  5006.3  490.19
    5054  492.39    5075   492.8  5096.5  494.46  5117.5  494.38  5124.8  495.06
  5131.6  494.98    5139  495.51  5145.8  495.41  5174.1  496.38  5183.9   496.4
#Mann= 3 ,-1 , 0
  4803.1     .15       0  4979.1     .05       0  4983.1     .15       0
Bank Sta=4979.1,4983.1
XS Rating Curve= 0 ,0
Exp/Cntr=0.3,0.1

Type RM Length L Ch R = 1 ,597     ,98,98,98
BEGIN DESCRIPTION:
Lacy 055 2595
END DESCRIPTION:
XS GIS Cut Line= 3
      2762373.24      6890151.43      2762500.19      6890235.57
      2762635.85      6890301.89
#Sta/Elev= 30
  4847.7  497.42  4851.8  497.42  4856.5  498.19    4863  496.64  4871.5  496.42
  4886.6  495.57    4899  494.18  4922.7  492.53  4928.7  492.42    4935  491.79
  4958.8  490.46  4964.8     490    4971  488.54  4979.8  487.83  4985.8  487.67
  4994.5  487.91    5000  487.41  5004.5  487.25  5004.8  486.75  5008.3  486.75
  5008.5  487.25  5017.6  488.27    5029  490.33    5046  491.98  5068.5  493.11
  5074.1  492.85    5091   493.2  5096.6  493.07  5119.1  494.32    5151  495.28
#Mann= 3 ,-1 , 0
  4847.7     .15       0  5004.5     .05       0  5008.5     .15       0
Bank Sta=5004.5,5008.5
XS Rating Curve= 0 ,0
Exp/Cntr=0.3,0.1

Type RM Length L Ch R = 1 ,499     ,54,54,54
BEGIN DESCRIPTION:
Lacy 055 2594
END DESCRIPTION:
XS GIS Cut Line= 3
      2762321.54      6890288.91      2762431.16      6890307.41
      2762627.43      6890312.22
#Sta/Elev= 30
    4887  492.98  4911.8  492.93  4928.3  492.53  4933.4  491.92  4942.2  491.72
  4962.5  490.56  4972.7  490.55  4982.8  489.48  4988.8  487.59  4993.9   487.7
  4996.1  486.05  4996.3  485.55  4999.8  485.55  5000.1  486.05  5003.1  486.05
    5013   486.5    5023  486.62    5033  487.29    5053  489.01    5063  489.59
    5073  490.38    5093  491.18    5103     492    5113  492.35  5143.1  492.79
  5153.1  493.18  5163.1  493.77  5183.1  494.48  5191.3  494.92  5194.5  494.92
#Mann= 3 ,-1 , 0
    4887     .15       0  4996.1     .05       0  5000.1     .15       0
Bank Sta=4996.1,5000.1
XS Rating Curve= 0 ,0
Exp/Cntr=0.3,0.1

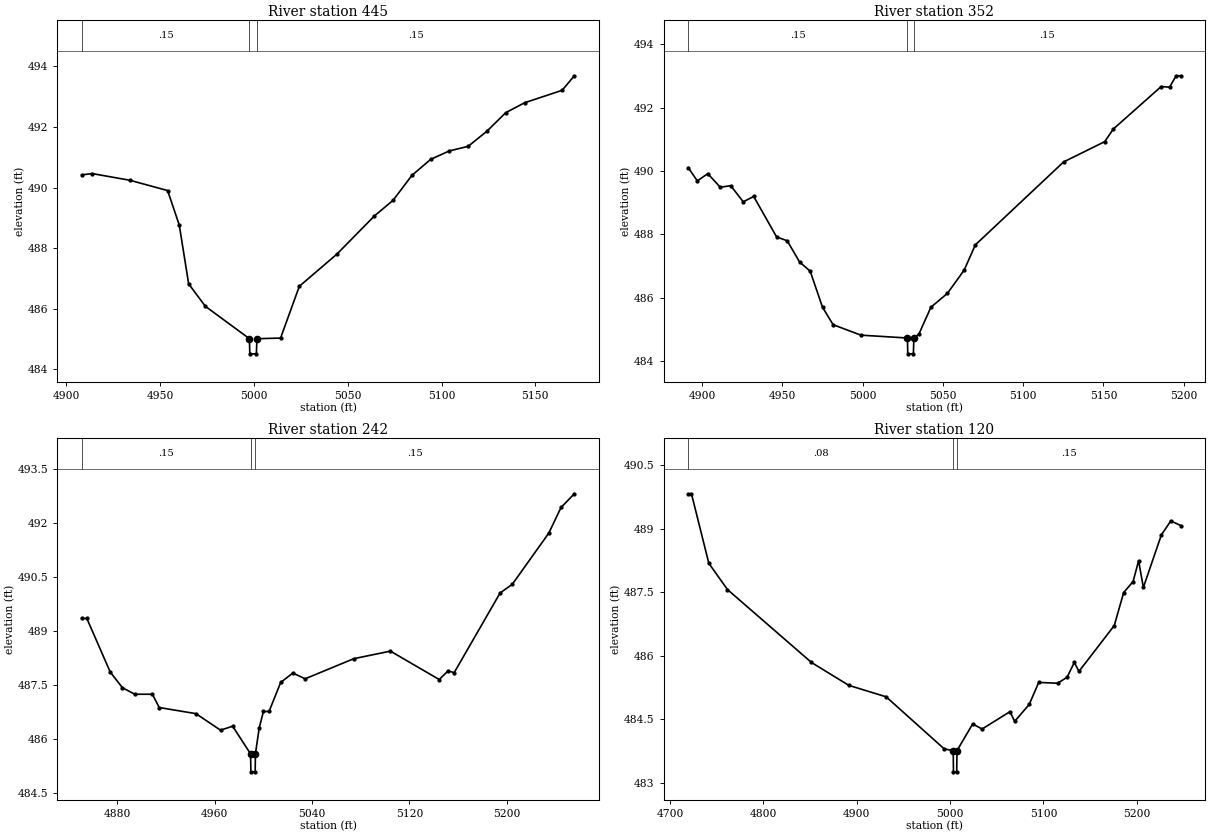
Type RM Length L Ch R = 1 ,445     ,93,93,93
BEGIN DESCRIPTION:
Lacy 055 2592
END DESCRIPTION:
XS GIS Cut Line= 3
      2762330.36      6890351.48      2762421.82      6890359.29
      2762592.53      6890364.92
#Sta/Elev= 25
  4908.2  490.42  4913.9  490.46  4933.9  490.24    4954   489.9  4960.2  488.76
  4965.2  486.82  4974.1  486.08  4997.6  485.01  4997.8  484.51  5001.3  484.51
  5001.6  485.01  5014.2  485.03  5024.2  486.74  5044.2   487.8  5064.2  489.06
  5074.2  489.58  5084.2   490.4  5094.2  490.93  5104.2  491.21  5114.2  491.36
  5124.2  491.86  5134.2  492.47  5144.3   492.8  5164.3  493.21  5170.8  493.69
#Mann= 3 ,-1 , 0
  4908.2     .15       0  4997.6     .05       0  5001.6     .15       0
Bank Sta=4997.6,5001.6
XS Rating Curve= 0 ,0
Exp/Cntr=0.3,0.1

Type RM Length L Ch R = 1 ,352     ,110,110,110
BEGIN DESCRIPTION:
Lacy 055 2593
END DESCRIPTION:
XS GIS Cut Line= 3
      2762305.05      6890354.38       2762374.9      6890437.67
      2762566.57      6890488.12
#Sta/Elev= 30
  4891.3  490.11    4897  489.69  4903.5  489.92  4911.3  489.49  4917.8  489.54
  4925.6  489.03  4932.1   489.2  4946.4  487.92    4953   487.8  4960.7  487.13
  4967.3  486.84    4975   485.7  4981.6  485.15  4998.9  484.82  5027.9  484.73
  5028.1  484.23  5031.6  484.23  5031.9  484.73    5035  484.85  5042.5   485.7
  5052.8  486.14  5063.2  486.87  5070.2  487.67  5125.2  490.29  5150.8  490.93
  5156.2  491.33    5186  492.67  5191.2  492.65  5195.3  493.01  5198.2  493.01
#Mann= 3 ,-1 , 0
  4891.3     .15       0  5027.9     .05       0  5031.9     .15       0
Bank Sta=5027.9,5031.9
XS Rating Curve= 0 ,0
Exp/Cntr=0.3,0.1

Type RM Length L Ch R = 1 ,242     ,122,122,122
BEGIN DESCRIPTION:
Lacy 055 2591
END DESCRIPTION:
XS GIS Cut Line= 3
      2762274.24      6890347.74      2762291.82       6890496.1
      2762546.89      6890512.52
#Sta/Elev= 30
  4850.6  489.35  4854.8  489.35    4874  487.86  4884.1  487.42  4894.2  487.24
  4908.7  487.24  4914.3  486.87  4944.5   486.7  4964.7  486.24  4974.7  486.35
  4989.4  485.58  4989.7  485.08  4993.2  485.08  4993.4  485.58  4996.5   486.3
    5000  486.76  5004.6  486.76  5014.2  487.57  5024.2  487.83  5034.3  487.67
  5074.3  488.23  5104.4  488.44  5144.5  487.65  5151.8  487.89  5156.8  487.84
  5194.6  490.06  5204.6   490.3  5234.7  491.73  5244.7  492.44  5255.6  492.82
#Mann= 3 ,-1 , 0
  4850.6     .15       0  4989.4     .05       0  4993.4     .15       0
Bank Sta=4989.4,4993.4
XS Rating Curve= 0 ,0
Exp/Cntr=0.3,0.1

Type RM Length L Ch R = 1 ,120     ,0,0,0
BEGIN DESCRIPTION:
Lacy 055 3490
END DESCRIPTION:
XS GIS Cut Line= 3
      2762268.27      6890338.89      2762264.55      6890591.59
      2762536.54      6890632.61
#Sta/Elev= 30
  4719.4  489.82  4722.9  489.82  4741.5  488.18  4761.5  487.56  4851.5  485.84
  4891.5   485.3  4931.5  485.03  4993.8   483.8  5003.4  483.76  5003.6  483.26
  5007.1  483.26  5007.4  483.76  5024.2  484.39  5034.3  484.27  5064.2  484.68
  5069.2  484.45  5084.8  484.85    5095  485.37  5115.2  485.35  5125.3  485.49
  5133.1  485.84  5138.1  485.63  5175.9  486.71    5186  487.49  5196.1  487.75
    5202  488.24  5207.1  487.61  5226.4  488.85  5236.5  489.18  5247.2  489.07
#Mann= 3 ,-1 , 0
  4719.4     .08       0  5003.4     .05       0  5007.4     .15       0
Bank Sta=5003.4,5007.4
XS Rating Curve= 0 ,0
Exp/Cntr=0.3,0.1

Chan Stop Cuts=-1
Use User Specified Reach Order=0
Composite Channel Slope=5