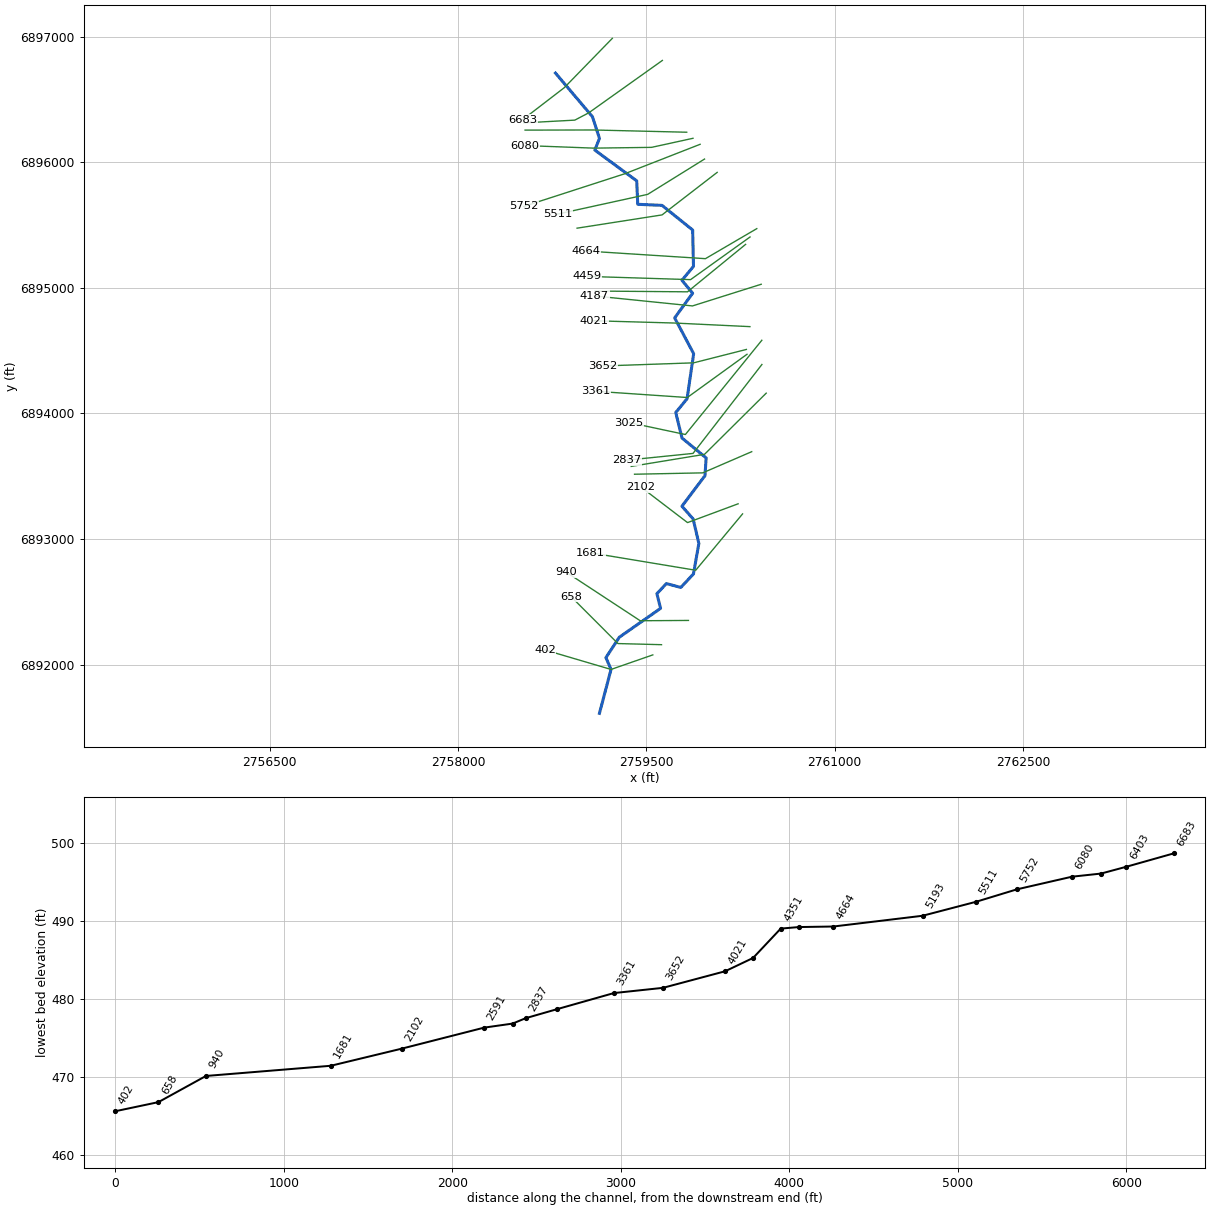
--- Lacy 056.prj (project) ---

Proj Title=Lacy 056 Base Level Engineering
Current Plan=p01
Default Exp/Contr=0.3,0.1
English Units
Geom File=g01
Flow File=f01
Plan File=p01
BEGIN DESCRIPTION:
Lacy 056
END DESCRIPTION:

--- Lacy 056.p01 (plan) ---

Plan Title=Multiple Run
Short Identifier=Multiple
Geom File=g01
Flow File=f01
Subcritical Flow
K Sum by GR= 0
Std Step Tol= 0.01
Critical Tol= 0.01
Num of Std Step Trials= 20
Max Error Tol= 0.3
Flow Tol Ratio= 0.001
Split Flow NTrial= 30
Split Flow Tol= 0.02
Split Flow Ratio= 0.02
Log Output Level= 0
Friction Slope Method= 1
Unsteady Friction Slope Method= 2
Unsteady Bridges Friction Slope Method= 1
Parabolic Critical Depth
Global Vel Dist=  1 , 1 , 1
Global Log Level= 0
CheckData=True
Encroach Param= -1, 0, 0, 0
BEGIN DESCRIPTION:
Multiple Run
END DESCRIPTION:

--- Lacy 056.f01 (steady flow) ---

Flow Title=Multiple
Number of Profiles=7
Profile Names=10-year,25-year,50-year,1pct_min,100-year,1pct_plu,500-year
River Rch & RM= Lacy 056,Reach-1,6683
     344     443     521     304     607    1211     826
Boundary for River Rch & Prof#=Lacy 056,Reach-1,1
Up Type=0
Dn Type=3
Dn Slope=0.005
Boundary for River Rch & Prof#=Lacy 056,Reach-1,2
Up Type=0
Dn Type=3
Dn Slope=0.005
Boundary for River Rch & Prof#=Lacy 056,Reach-1,3
Up Type=0
Dn Type=3
Dn Slope=0.005
Boundary for River Rch & Prof#=Lacy 056,Reach-1,4
Up Type=0
Dn Type=3
Dn Slope=0.005
Boundary for River Rch & Prof#=Lacy 056,Reach-1,5
Up Type=0
Dn Type=3
Dn Slope=0.005
Boundary for River Rch & Prof#=Lacy 056,Reach-1,6
Up Type=0
Dn Type=3
Dn Slope=0.005
Boundary for River Rch & Prof#=Lacy 056,Reach-1,7
Up Type=0
Dn Type=3
Dn Slope=0.005

--- Lacy 056.g01 (geometry) ---

Geom Title=Existing Conditions

River Reach=Lacy 056,Reach-1
Reach XY= 30
      2758776.00      6896711.00      2759070.48      6896363.43
      2759126.21      6896190.79      2759089.54      6896097.62
      2759422.93      6895852.70      2759431.00      6895666.00
      2759624.53      6895657.46      2759868.55      6895461.21
      2759875.05      6895171.48      2759783.11      6895060.99
      2759868.39      6894957.67      2759725.15      6894761.01
      2759876.53      6894476.19      2759823.92      6894116.85
      2759733.88      6894007.78      2759783.70      6893804.53
      2759975.99      6893645.64      2759966.69      6893504.34
      2759783.09      6893261.00      2759872.43      6893159.53
      2759917.92      6892964.30      2759874.95      6892721.43
      2759774.37      6892614.15      2759659.23      6892644.70
      2759583.82      6892564.44      2759613.01      6892447.44
      2759284.04      6892217.33      2759177.66      6892054.95
      2759218.41      6891961.01      2759126.00      6891611.00

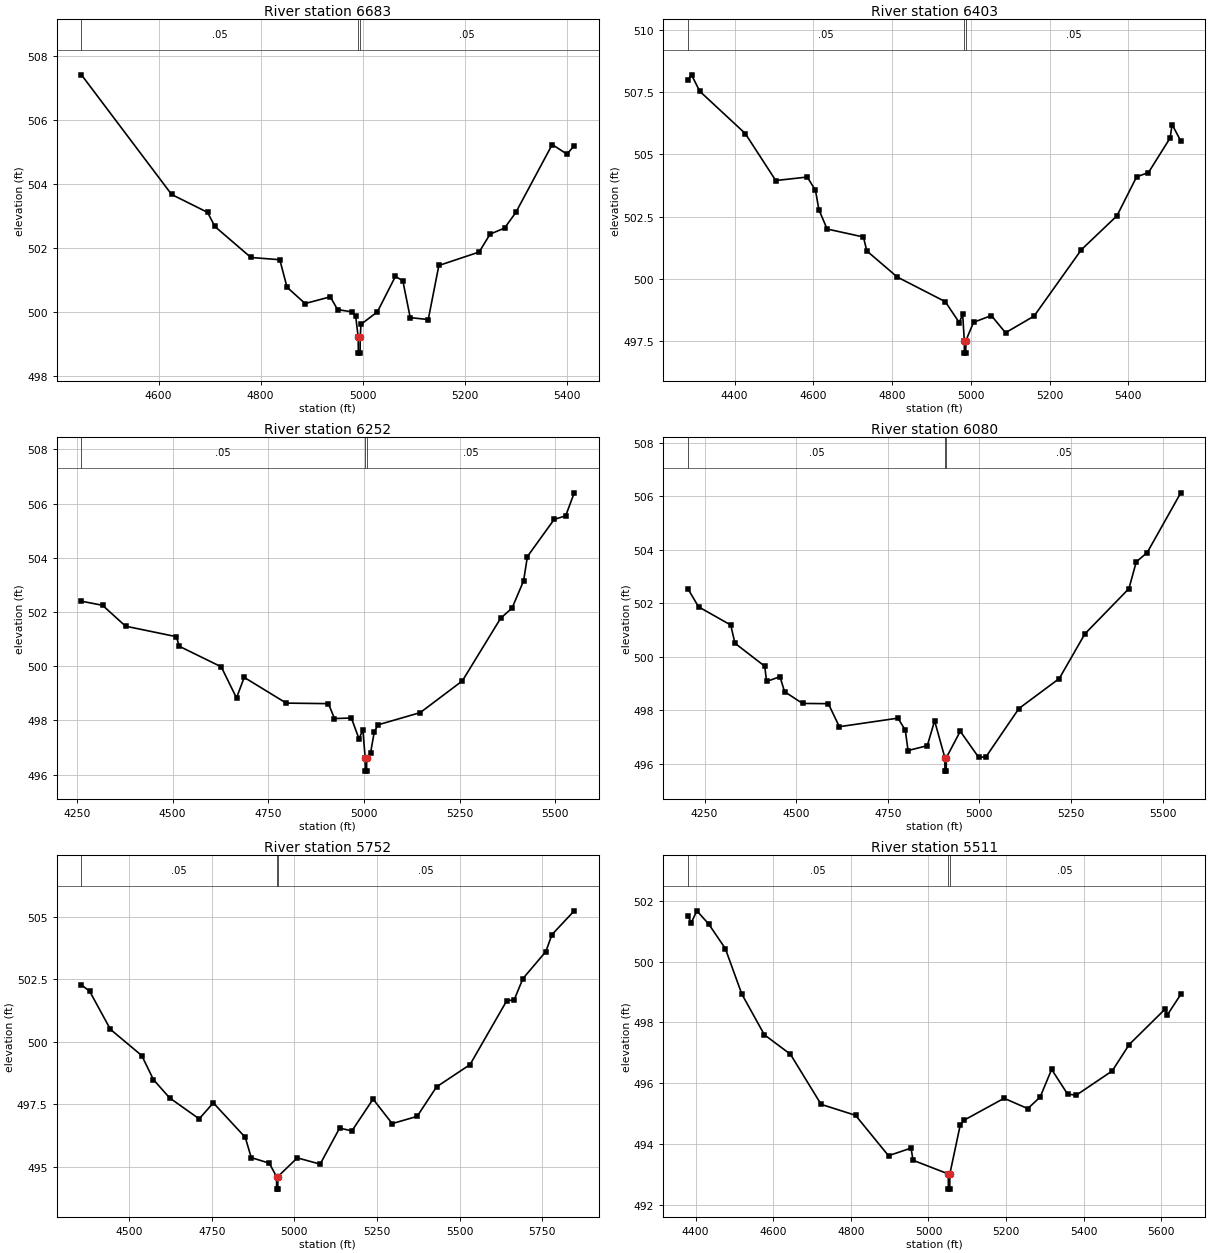
Type RM Length L Ch R = 1,6683,280,280,280
BEGIN DESCRIPTION:
Lacy 056 2575
END DESCRIPTION:
XS GIS Cut Line= 3
      2759228.80      6896987.96      2758846.12      6896595.00
      2758515.26      6896340.87
#Sta/Elev= 30
  4448.8  507.42  4625.5  503.68  4696.0  503.12  4710.2  502.68  4780.9  501.71
  4837.5  501.64  4851.7  500.78  4887.1  500.27  4936.5  500.48  4950.7  500.08
  4979.0  500.01  4986.1  499.89  4991.1  499.22  4991.4  498.72  4994.9  498.72
  4995.1  499.22  4996.6  499.62  5028.7  500.01  5064.1  501.12  5078.6  500.98
  5093.1  499.83  5128.4  499.77  5149.2  501.46  5228.1  501.88  5249.6  502.44
  5278.0  502.63  5300.1  503.12  5371.3  505.24  5400.4  504.94  5414.5  505.21
#Mann=3,-1,0
  4448.8    0.05       0  4991.1    0.04       0  4995.1    0.05       0
Bank Sta=4991.1,4995.1
Exp/Cntr=0.3,0.1

Type RM Length L Ch R = 1,6403,151,151,151
BEGIN DESCRIPTION:
Lacy 056 2574
END DESCRIPTION:
XS GIS Cut Line= 4
      2759627.40      6896811.93      2759041.01      6896394.71
      2758930.07      6896336.51      2758524.02      6896314.53
#Sta/Elev= 30
  4281.7  508.00  4290.7  508.20  4311.6  507.54  4427.2  505.84  4504.7  503.95
  4584.6  504.09  4605.5  503.56  4614.2  502.78  4635.1  502.00  4727.3  501.68
  4735.9  501.12  4813.3  500.07  4935.1  499.08  4970.7  498.24  4979.4  498.57
  4983.5  497.51  4983.8  497.01  4987.3  497.01  4987.5  497.51  5007.0  498.25
  5052.2  498.52  5088.2  497.83  5160.8  498.50  5280.9  501.17  5371.1  502.53
  5421.2  504.10  5451.2  504.27  5506.2  505.66  5511.3  506.20  5533.3  505.54
#Mann=3,-1,0
  4281.7    0.05       0  4983.5    0.05       0  4987.5    0.05       0
Bank Sta=4983.5,4987.5
Exp/Cntr=0.3,0.1

Type RM Length L Ch R = 1,6252,172,172,172
BEGIN DESCRIPTION:
Lacy 056 2573
END DESCRIPTION:
XS GIS Cut Line= 3
      2759821.18      6896240.08      2759075.00      6896258.03
      2758533.60      6896256.87
#Sta/Elev= 30
  4262.0  502.40  4317.2  502.25  4377.2  501.48  4510.3  501.09  4517.3  500.74
  4627.3  499.98  4667.3  498.83  4687.3  499.59  4797.3  498.64  4907.4  498.62
  4923.3  498.07  4967.4  498.09  4987.4  497.32  4997.4  497.66  5003.4  496.63
  5003.7  496.13  5007.2  496.13  5007.4  496.63  5017.4  496.79  5027.4  497.59
  5037.4  497.84  5147.4  498.29  5257.4  499.46  5357.4  501.77  5387.4  502.15
  5417.4  503.15  5427.4  504.05  5497.4  505.42  5527.4  505.55  5549.8  506.40
#Mann=3,-1,0
  4262.0    0.05       0  5003.4    0.05       0  5007.4    0.05       0
Bank Sta=5003.4,5007.4
Exp/Cntr=0.3,0.1

Type RM Length L Ch R = 1,6080,328,328,328
BEGIN DESCRIPTION:
Lacy 056 2572
END DESCRIPTION:
XS GIS Cut Line= 4
      2759871.25      6896191.75      2759541.04      6896119.51
      2759080.58      6896113.42      2758534.58      6896133.85
#Sta/Elev= 30
  4204.8  502.54  4233.7  501.87  4321.5  501.19  4333.0  500.51  4414.3  499.65
  4419.4  499.08  4455.9  499.26  4468.4  498.70  4517.4  498.26  4587.9  498.25
  4617.9  497.39  4777.9  497.71  4797.9  497.26  4805.4  496.50  4857.9  496.68
  4877.9  497.61  4905.9  496.23  4906.1  495.73  4909.6  495.73  4909.9  496.23
  4947.9  497.22  4997.9  496.25  5017.9  496.26  5108.0  498.07  5218.1  499.19
  5288.1  500.86  5408.2  502.55  5428.2  503.55  5458.2  503.90  5549.7  506.13
#Mann=3,-1,0
  4204.8    0.05       0  4905.9    0.04       0  4909.9    0.05       0
Bank Sta=4905.9,4909.9
Exp/Cntr=0.3,0.1

Type RM Length L Ch R = 1,5752,241,241,241
BEGIN DESCRIPTION:
Lacy 056 2576
END DESCRIPTION:
XS GIS Cut Line= 3
      2759927.71      6896143.78      2759328.68      6895909.59
      2758521.92      6895648.64
#Sta/Elev= 30
  4355.6  502.27  4380.6  502.01  4443.3  500.49  4538.2  499.44  4573.4  498.48
  4622.3  497.75  4711.8  496.91  4754.7  497.55  4851.3  496.17  4869.4  495.36
  4923.7  495.14  4946.0  494.60  4946.2  494.10  4949.7  494.10  4950.0  494.60
  5008.7  495.35  5077.9  495.10  5136.7  496.54  5174.0  496.43  5238.0  497.70
  5295.9  496.72  5371.3  497.01  5430.1  498.19  5531.4  499.08  5642.7  501.64
  5664.7  501.66  5691.4  502.52  5760.7  503.60  5779.3  504.28  5846.7  505.23
#Mann=3,-1,0
  4355.6    0.05       0  4946.0    0.04       0  4950.0    0.05       0
Bank Sta=4946,4950
Exp/Cntr=0.3,0.1

Type RM Length L Ch R = 1,5511,318,318,318
BEGIN DESCRIPTION:
Lacy 056 2578
END DESCRIPTION:
XS GIS Cut Line= 3
      2759963.24      6896026.43      2759510.44      6895745.17
      2758791.03      6895587.66
#Sta/Elev= 30
  4380.4  501.50  4388.9  501.28  4403.4  501.67  4434.1  501.23  4476.6  500.43
  4519.1  498.93  4577.3  497.59  4644.3  496.95  4723.4  495.30  4812.0  494.94
  4897.0  493.61  4955.1  493.86  4960.2  493.46  5051.0  493.01  5051.3  492.51
  5054.8  492.51  5055.0  493.01  5081.8  494.62  5091.7  494.78  5194.8  495.50
  5255.8  495.16  5287.6  495.54  5317.2  496.45  5358.2  495.64  5380.4  495.60
  5473.3  496.40  5517.1  497.27  5609.9  498.44  5615.1  498.24  5649.9  498.92
#Mann=3,-1,0
  4380.4    0.05       0  5051.0    0.04       0  5055.0    0.05       0
Bank Sta=5051,5055
Exp/Cntr=0.3,0.1

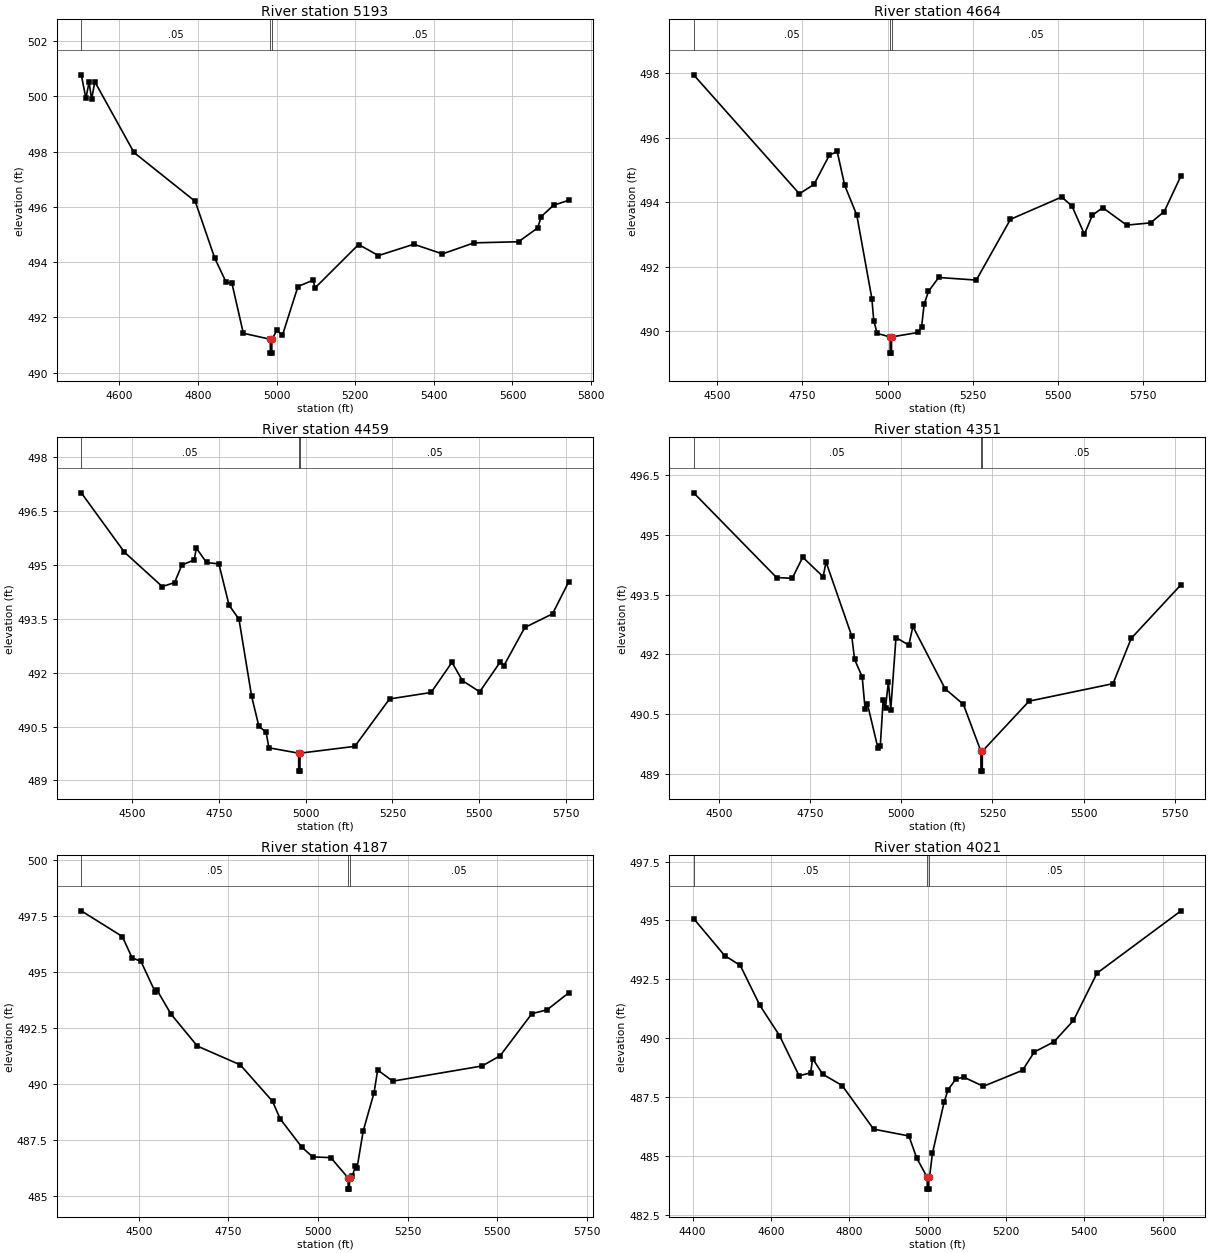
Type RM Length L Ch R = 1,5193,529,529,529
BEGIN DESCRIPTION:
Lacy 056 2577
END DESCRIPTION:
XS GIS Cut Line= 3
      2760063.89      6895920.32      2759624.77      6895581.50
      2758948.01      6895475.83
#Sta/Elev= 30
  4503.4  500.78  4515.1  499.93  4523.3  500.52  4529.6  499.89  4537.8  500.53
  4637.4  497.97  4793.2  496.20  4843.0  494.14  4872.0  493.27  4886.5  493.24
  4915.5  491.43  4984.1  491.21  4984.4  490.71  4987.9  490.71  4988.1  491.21
  5000.6  491.53  5015.1  491.36  5054.4  493.12  5093.0  493.35  5098.0  493.07
  5208.6  494.64  5259.2  494.24  5349.1  494.65  5422.0  494.30  5502.1  494.70
  5615.4  494.74  5664.1  495.24  5673.1  495.65  5704.5  496.06  5743.0  496.24
#Mann=3,-1,0
  4503.4    0.05       0  4984.1    0.04       0  4988.1    0.05       0
Bank Sta=4984.1,4988.1
Exp/Cntr=0.3,0.1

Type RM Length L Ch R = 1,4664,205,205,205
BEGIN DESCRIPTION:
Lacy 056 2571
END DESCRIPTION:
XS GIS Cut Line= 3
      2760379.31      6895472.10      2759970.40      6895232.91
      2759016.78      6895294.04
#Sta/Elev= 30
  4431.0  497.94  4741.0  494.26  4784.0  494.55  4828.7  495.45  4851.9  495.57
  4874.0  494.52  4909.4  493.60  4953.6  491.02  4959.2  490.33  4969.3  489.94
  5007.3  489.83  5007.6  489.33  5011.1  489.33  5011.3  489.83  5089.5  489.97
  5099.5  490.15  5106.9  490.84  5119.6  491.24  5149.6  491.67  5259.9  491.59
  5360.1  493.47  5510.4  494.16  5540.4  493.88  5576.9  493.01  5600.6  493.60
  5630.6  493.83  5700.8  493.29  5770.9  493.36  5811.0  493.71  5860.3  494.82
#Mann=3,-1,0
  4431.0    0.05       0  5007.3    0.04       0  5011.3    0.05       0
Bank Sta=5007.3,5011.3
Exp/Cntr=0.3,0.1

Type RM Length L Ch R = 1,4459,108,108,108
BEGIN DESCRIPTION:
Lacy 056 2570
END DESCRIPTION:
XS GIS Cut Line= 3
      2760325.75      6895405.64      2759851.90      6895065.97
      2759029.42      6895091.61
#Sta/Elev= 30
  4352.4  497.01  4476.6  495.36  4585.9  494.40  4621.5  494.51  4642.4  495.00
  4678.0  495.14  4684.3  495.47  4713.6  495.07  4749.3  495.03  4778.7  493.88
  4807.3  493.49  4843.8  491.34  4864.7  490.51  4885.6  490.34  4893.5  489.91
  4979.3  489.76  4979.6  489.26  4983.1  489.26  4983.3  489.76  5141.4  489.95
  5241.5  491.27  5361.5  491.45  5421.6  492.29  5451.6  491.78  5501.6  491.47
  5561.6  492.31  5571.6  492.20  5631.7  493.26  5711.7  493.64  5758.3  494.53
#Mann=3,-1,0
  4352.4    0.05       0  4979.3    0.04       0  4983.3    0.05       0
Bank Sta=4979.3,4983.3
Exp/Cntr=0.3,0.1

Type RM Length L Ch R = 1,4351,164,164,164
BEGIN DESCRIPTION:
Lacy 056 2568
END DESCRIPTION:
XS GIS Cut Line= 3
      2760290.39      6895346.86      2759827.71      6894968.88
      2759089.49      6894974.91
#Sta/Elev= 30
  4431.1  496.06  4658.2  493.93  4701.3  493.91  4730.0  494.44  4786.0  493.95
  4793.9  494.32  4864.3  492.46  4872.2  491.87  4893.0  491.43  4900.9  490.63
  4907.4  490.75  4936.1  489.64  4942.5  489.68  4950.4  490.84  4956.9  490.66
  4964.8  491.31  4971.3  490.61  4985.6  492.42  5020.8  492.23  5031.9  492.70
  5120.3  491.13  5170.3  490.74  5218.3  489.56  5218.5  489.06  5222.0  489.06
  5222.3  489.56  5350.3  490.82  5580.3  491.26  5630.3  492.40  5766.8  493.75
#Mann=3,-1,0
  4431.1    0.05       0  5218.3    0.04       0  5222.3    0.05       0
Bank Sta=5218.3,5222.3
Exp/Cntr=0.3,0.1

Type RM Length L Ch R = 1,4187,166,166,166
BEGIN DESCRIPTION:
Lacy 056 2569
END DESCRIPTION:
XS GIS Cut Line= 3
      2760414.62      6895029.06      2759867.24      6894856.46
      2759086.04      6894936.12
#Sta/Elev= 30
  4339.9  497.74  4454.4  496.59  4481.5  495.64  4506.2  495.48  4546.3  494.10
  4551.5  494.18  4590.1  493.12  4663.5  491.69  4783.2  490.85  4873.2  489.22
  4894.2  488.44  4955.3  487.16  4985.5  486.73  5035.7  486.70  5084.0  485.79
  5084.2  485.29  5087.7  485.29  5088.0  485.79  5096.0  485.86  5103.8  486.32
  5108.8  486.23  5126.2  487.90  5156.3  489.60  5166.4  490.62  5208.3  490.12
  5457.9  490.80  5508.1  491.26  5596.5  493.14  5638.8  493.31  5699.1  494.07
#Mann=3,-1,0
  4339.9    0.05       0  5084.0    0.04       0  5088.0    0.05       0
Bank Sta=5084,5088
Exp/Cntr=0.3,0.1

Type RM Length L Ch R = 1,4021,369,369,369
BEGIN DESCRIPTION:
Lacy 056 2565
END DESCRIPTION:
XS GIS Cut Line= 3
      2760324.87      6894691.54      2759723.46      6894720.26
      2759081.51      6894738.34
#Sta/Elev= 30
  4402.6  495.08  4481.6  493.51  4521.6  493.09  4571.7  491.39  4621.7  490.11
  4671.8  488.40  4701.3  488.52  4706.3  489.13  4731.8  488.47  4781.9  487.98
  4862.0  486.13  4952.1  485.84  4972.1  484.90  4998.9  484.08  4999.2  483.58
  5002.7  483.58  5002.9  484.08  5004.7  484.08  5012.2  485.10  5042.2  487.29
  5052.2  487.81  5072.2  488.26  5092.2  488.34  5142.2  487.95  5242.2  488.63
  5272.3  489.41  5322.3  489.84  5372.3  490.75  5432.3  492.76  5646.9  495.41
#Mann=3,-1,0
  4402.6    0.05       0  4998.9    0.04       0  5002.9    0.05       0
Bank Sta=4998.9,5002.9
Exp/Cntr=0.3,0.1

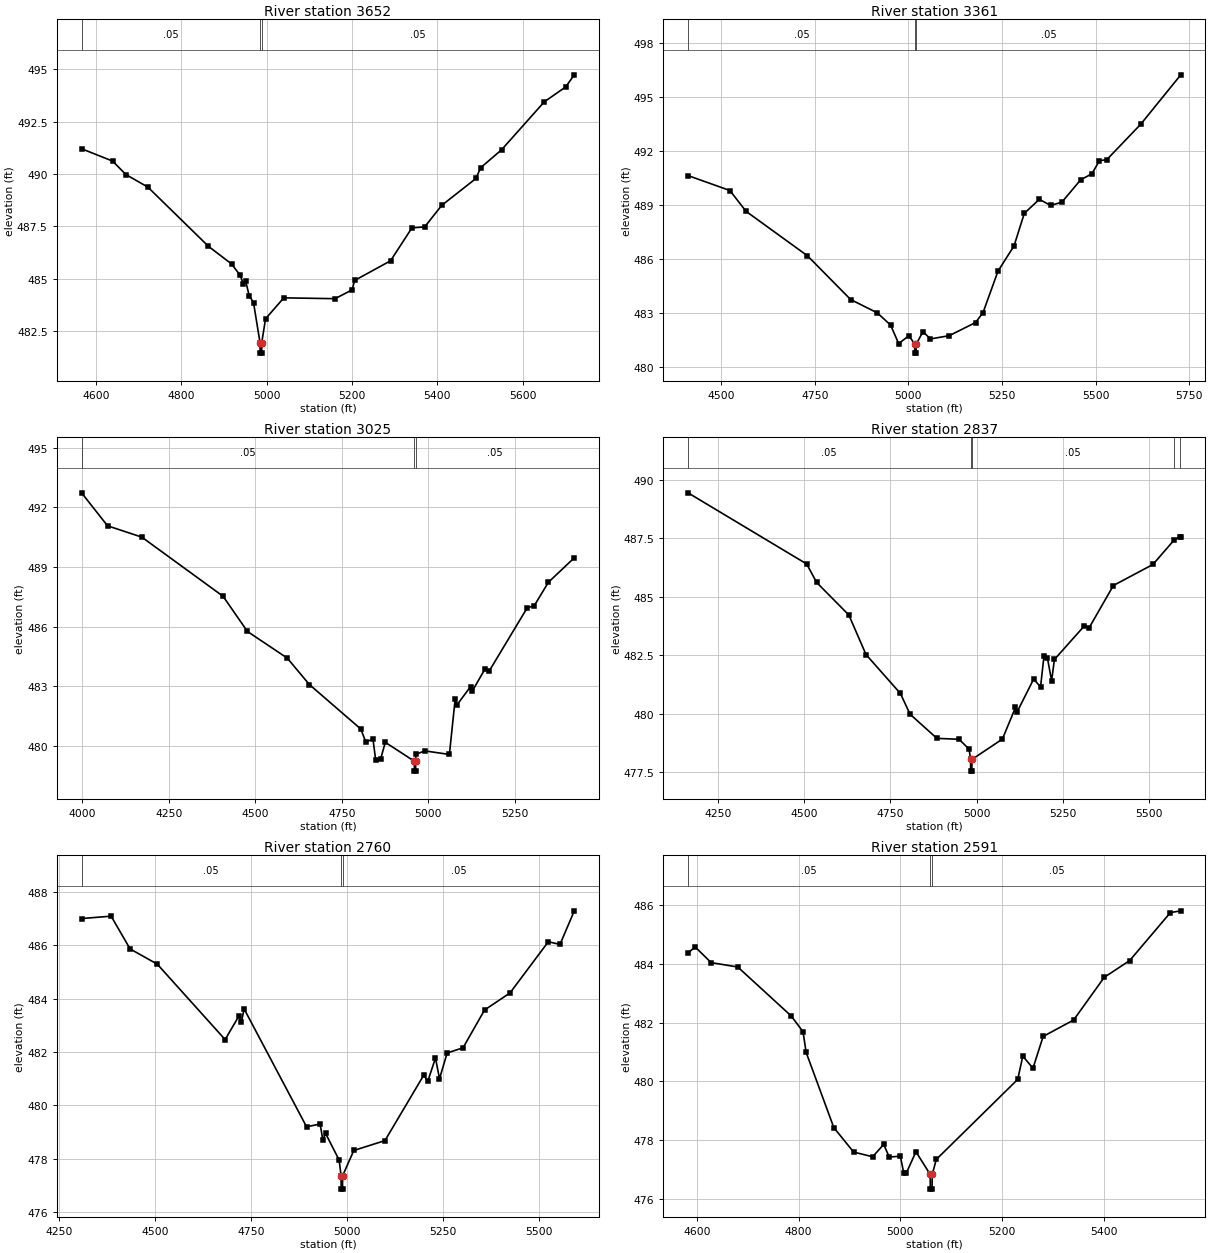
Type RM Length L Ch R = 1,3652,291,291,291
BEGIN DESCRIPTION:
Lacy 056 2566
END DESCRIPTION:
XS GIS Cut Line= 3
      2760296.56      6894509.91      2759876.28      6894403.14
      2759155.64      6894378.28
#Sta/Elev= 30
  4566.5  491.21  4639.3  490.62  4670.3  489.98  4721.8  489.38  4863.9  486.55
  4917.9  485.71  4938.5  485.16  4945.8  484.73  4950.9  484.91  4959.2  484.20
  4969.5  483.86  4984.7  481.95  4985.0  481.45  4988.5  481.45  4988.7  481.95
  4997.7  483.09  5040.4  484.09  5160.5  484.05  5200.5  484.47  5206.4  484.92
  5290.6  485.86  5340.6  487.43  5370.6  487.48  5410.7  488.51  5490.7  489.79
  5501.5  490.30  5550.7  491.16  5650.8  493.45  5700.8  494.16  5721.2  494.74
#Mann=3,-1,0
  4566.5    0.05       0  4984.7    0.04       0  4988.7    0.05       0
Bank Sta=4984.7,4988.7
Exp/Cntr=0.3,0.1

Type RM Length L Ch R = 1,3361,336,336,336
BEGIN DESCRIPTION:
Lacy 056 2567
END DESCRIPTION:
XS GIS Cut Line= 3
      2760301.62      6894471.43      2759825.83      6894126.88
      2759099.17      6894176.49
#Sta/Elev= 30
  4411.7  490.65  4523.4  489.82  4566.8  488.66  4730.7  486.19  4845.9  483.76
  4917.0  483.02  4952.6  482.34  4974.2  481.31  5001.6  481.75  5017.0  481.28
  5017.3  480.78  5020.8  480.78  5021.0  481.28  5039.1  481.97  5059.1  481.57
  5109.2  481.75  5179.4  482.48  5199.4  483.03  5239.5  485.34  5282.2  486.74
  5309.7  488.55  5349.8  489.33  5379.9  488.99  5409.9  489.17  5460.0  490.41
  5490.1  490.75  5510.2  491.47  5530.2  491.54  5620.4  493.50  5727.5  496.25
#Mann=3,-1,0
  4411.7    0.05       0  5017.0    0.04       0  5021.0    0.05       0
Bank Sta=5017,5021
Exp/Cntr=0.3,0.1

Type RM Length L Ch R = 1,3025,188,188,188
BEGIN DESCRIPTION:
Lacy 056 2564
END DESCRIPTION:
XS GIS Cut Line= 3
      2760419.47      6894582.92      2759810.56      6893832.19
      2759362.80      6893927.40
#Sta/Elev= 30
  3998.0  492.73  4073.1  491.07  4172.2  490.50  4407.2  487.52  4477.6  485.75
  4592.6  484.41  4656.5  483.08  4805.2  480.84  4819.6  480.19  4840.4  480.33
  4848.3  479.27  4862.7  479.34  4876.0  480.17  4959.8  479.22  4960.1  478.72
  4963.6  478.72  4963.8  479.22  4964.3  479.56  4989.7  479.74  5061.3  479.56
  5077.9  482.33  5083.0  482.05  5122.4  482.97  5127.5  482.75  5163.5  483.84
  5177.1  483.78  5286.2  486.94  5306.7  487.05  5347.6  488.23  5422.4  489.46
#Mann=3,-1,0
  3998.0    0.05       0  4959.8    0.04       0  4963.8    0.05       0
Bank Sta=4959.8,4963.8
Exp/Cntr=0.3,0.1

Type RM Length L Ch R = 1,2837,77,77,77
BEGIN DESCRIPTION:
Lacy 056 2563
END DESCRIPTION:
XS GIS Cut Line= 3
      2760420.10      6894389.92      2759871.45      6893681.69
      2759341.57      6893627.73
#Sta/Elev= 30
  4163.7  489.44  4507.7  486.40  4536.6  485.61  4629.9  484.22  4679.7  482.53
  4779.3  480.87  4807.5  479.98  4885.2  478.95  4949.5  478.91  4978.5  478.49
  4982.8  478.05  4983.0  477.55  4986.5  477.55  4986.8  478.05  5075.1  478.92
  5113.0  480.27  5118.1  480.09  5165.6  481.48  5185.7  481.15  5195.7  482.48
  5205.8  482.37  5217.7  481.41  5225.9  482.32  5312.3  483.75  5326.4  483.67
  5396.8  485.48  5511.5  486.38  5573.3  487.43  5589.2  487.56  5592.2  487.56
#Mann=5,-1,0
  4163.7    0.05       0  4982.8    0.03       0  4986.8    0.05       0
  5573.3    0.12       0  5589.2     0.1       0
Bank Sta=4982.8,4986.8
Exp/Cntr=0.3,0.1

Type RM Length L Ch R = 1,2760,169,169,169
BEGIN DESCRIPTION:
Lacy 056 2562
END DESCRIPTION:
XS GIS Cut Line= 3
      2760454.30      6894161.58      2759962.88      6893674.24
      2759379.22      6893578.23
#Sta/Elev= 30
  4307.9  487.01  4384.9  487.10  4434.4  485.87  4505.1  485.30  4681.9  482.47
  4717.2  483.34  4724.3  483.14  4731.4  483.62  4894.0  479.20  4929.4  479.30
  4936.5  478.70  4943.5  478.95  4978.9  477.95  4983.9  477.36  4984.2  476.86
  4987.7  476.86  4987.9  477.36  5017.1  478.31  5098.2  478.68  5199.5  481.14
  5209.7  480.90  5229.9  481.78  5240.3  481.00  5260.3  481.97  5301.6  482.16
  5357.7  483.58  5424.0  484.22  5523.8  486.14  5554.2  486.04  5591.5  487.30
#Mann=3,-1,0
  4307.9    0.05       0  4983.9    0.04       0  4987.9    0.05       0
Bank Sta=4983.9,4987.9
Exp/Cntr=0.3,0.1

Type RM Length L Ch R = 1,2591,489,489,489
BEGIN DESCRIPTION:
Lacy 056 2561
END DESCRIPTION:
XS GIS Cut Line= 3
      2760339.04      6893695.56      2759948.80      6893526.78
      2759405.59      6893515.91
#Sta/Elev= 30
  4582.6  484.37  4596.8  484.57  4628.0  484.04  4680.4  483.89  4785.2  482.23
  4808.7  481.69  4814.7  480.99  4869.2  478.43  4908.1  477.60  4945.5  477.44
  4967.2  477.86  4978.1  477.43  4999.9  477.46  5006.6  476.89  5011.7  476.89
  5030.6  477.61  5058.6  476.84  5058.8  476.34  5062.3  476.34  5062.6  476.84
  5070.6  477.35  5230.6  480.07  5240.6  480.86  5260.6  480.45  5280.6  481.53
  5340.6  482.09  5400.7  483.54  5450.7  484.11  5530.7  485.74  5551.1  485.80
#Mann=3,-1,0
  4582.6    0.05       0  5058.6    0.04       0  5062.6    0.05       0
Bank Sta=5058.6,5062.6
Exp/Cntr=0.3,0.1

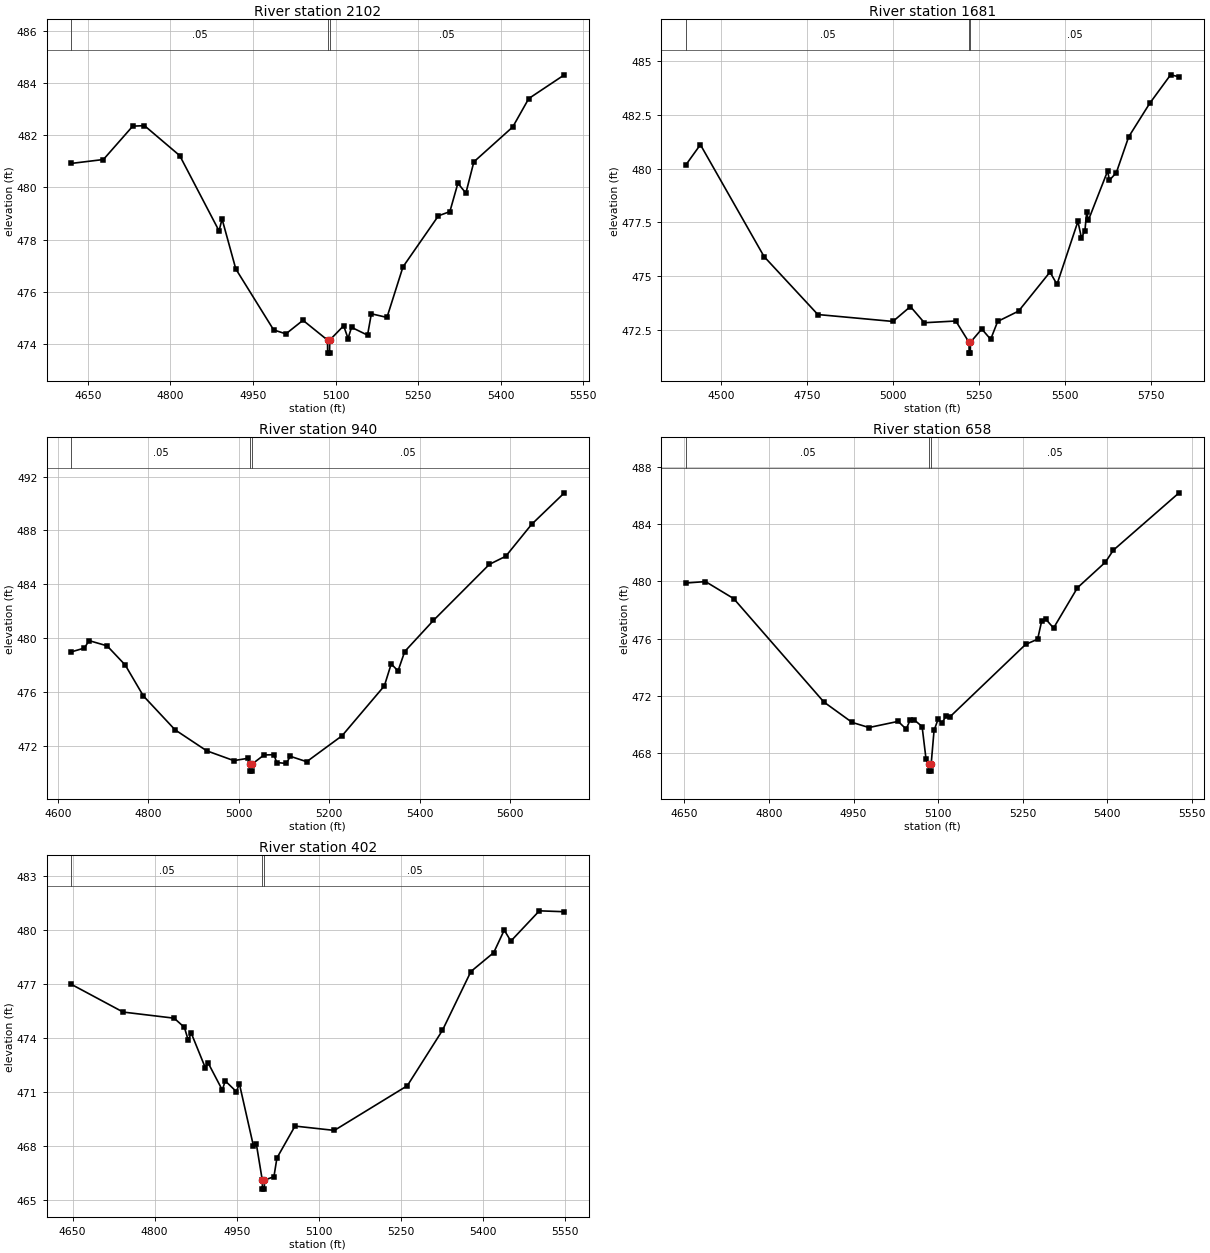
Type RM Length L Ch R = 1,2102,421,421,421
BEGIN DESCRIPTION:
Lacy 056 2560
END DESCRIPTION:
XS GIS Cut Line= 3
      2760230.62      6893280.35      2759827.72      6893130.59
      2759457.14      6893413.41
#Sta/Elev= 30
  4619.9  480.92  4678.2  481.07  4731.5  482.35  4752.8  482.37  4816.9  481.22
  4888.4  478.33  4893.8  478.79  4918.8  476.87  4987.6  474.53  5009.9  474.38
  5040.9  474.90  5085.5  474.14  5085.7  473.64  5089.2  473.64  5089.5  474.14
  5114.8  474.69  5122.8  474.20  5129.1  474.63  5158.2  474.33  5165.1  475.15
  5193.5  475.01  5222.6  476.95  5287.0  478.91  5307.8  479.07  5322.4  480.16
  5336.9  479.78  5351.4  480.98  5422.1  482.32  5451.2  483.41  5515.9  484.32
#Mann=3,-1,0
  4619.9    0.05       0  5085.5    0.04       0  5089.5    0.05       0
Bank Sta=5085.5,5089.5
Exp/Cntr=0.3,0.1

Type RM Length L Ch R = 1,1681,741,741,741
BEGIN DESCRIPTION:
Lacy 056 2559
END DESCRIPTION:
XS GIS Cut Line= 3
      2760266.14      6893200.06      2759892.84      6892751.06
      2759056.31      6892889.94
#Sta/Elev= 30
  4398.4  480.18  4440.2  481.11  4625.1  475.92  4781.3  473.23  4999.4  472.91
  5050.1  473.60  5090.6  472.85  5181.9  472.93  5220.4  471.94  5220.6  471.44
  5224.1  471.44  5224.4  471.94  5257.3  472.56  5283.2  472.08  5303.5  472.91
  5364.3  473.39  5455.5  475.20  5475.8  474.63  5536.6  477.55  5546.8  476.79
  5556.9  477.12  5562.0  477.98  5567.1  477.61  5622.9  479.89  5628.0  479.46
  5648.1  479.81  5683.9  481.47  5744.8  483.02  5805.7  484.35  5830.3  484.26
#Mann=3,-1,0
  4398.4    0.05       0  5220.4    0.04       0  5224.4    0.05       0
Bank Sta=5220.4,5224.4
Exp/Cntr=0.3,0.1

Type RM Length L Ch R = 1,940,282,282,282
BEGIN DESCRIPTION:
Lacy 056 2557
END DESCRIPTION:
XS GIS Cut Line= 3
      2759835.15      6892351.33      2759450.91      6892348.86
      2758860.93      6892736.00
#Sta/Elev= 30
  4629.6  478.98  4658.7  479.27  4668.7  479.82  4708.7  479.43  4748.7  478.01
  4788.7  475.72  4858.8  473.20  4928.8  471.64  4988.8  470.91  5019.8  471.08
  5024.3  470.63  5024.5  470.13  5028.0  470.13  5028.3  470.63  5055.6  471.33
  5077.5  471.35  5083.5  470.77  5104.6  470.70  5113.7  471.23  5149.9  470.83
  5228.2  472.76  5321.6  476.46  5336.7  478.09  5351.8  477.57  5366.6  479.01
  5430.1  481.32  5553.7  485.48  5589.9  486.08  5647.1  488.45  5719.5  490.79
#Mann=3,-1,0
  4629.6    0.05       0  5024.3    0.04       0  5028.3    0.05       0
Bank Sta=5024.3,5028.3
Exp/Cntr=0.3,0.1

Type RM Length L Ch R = 1,658,256,256,256
BEGIN DESCRIPTION:
Lacy 056 2556
END DESCRIPTION:
XS GIS Cut Line= 3
      2759620.62      6892158.13      2759273.44      6892167.09
      2758900.63      6892540.56
#Sta/Elev= 30
  4652.7  479.89  4687.3  479.99  4737.4  478.80  4897.4  471.59  4947.4  470.17
  4977.4  469.81  5029.2  470.24  5043.4  469.70  5050.4  470.33  5057.5  470.35
  5071.7  469.88  5078.7  467.60  5083.8  467.27  5084.1  466.77  5087.6  466.77
  5087.8  467.27  5092.9  469.61  5100.0  470.38  5107.0  470.13  5114.1  470.61
  5121.2  470.56  5255.5  475.61  5276.7  475.97  5283.8  477.22  5290.9  477.38
  5305.0  476.75  5347.4  479.56  5396.9  481.34  5411.1  482.18  5527.7  486.18
#Mann=3,-1,0
  4652.7    0.05       0  5083.8    0.04       0  5087.8    0.05       0
Bank Sta=5083.8,5087.8
Exp/Cntr=0.3,0.1

Type RM Length L Ch R = 1,402,0,0,0
BEGIN DESCRIPTION:
Lacy 056 2555
END DESCRIPTION:
XS GIS Cut Line= 3
      2759551.13      6892076.83      2759218.41      6891961.01
      2758692.18      6892116.07
#Sta/Elev= 30
  4647.7  476.97  4742.3  475.43  4835.6  475.09  4854.3  474.58  4861.4  473.86
  4866.7  474.27  4892.5  472.34  4897.8  472.60  4923.6  471.10  4928.9  471.61
  4949.4  471.01  4954.7  471.46  4980.5  467.99  4985.7  468.12  4996.6  466.10
  4996.9  465.60  5000.4  465.60  5000.6  466.10  5017.9  466.29  5023.4  467.33
  5056.4  469.10  5128.3  468.86  5261.6  471.34  5325.7  474.41  5377.8  477.68
  5419.5  478.73  5438.7  479.98  5450.8  479.37  5502.9  481.05  5548.6  481.00
#Mann=3,-1,0
  4647.7    0.05       0  4996.6    0.04       0  5000.6    0.05       0
Bank Sta=4996.6,5000.6
Exp/Cntr=0.3,0.1

Chan Stop Cuts=-1