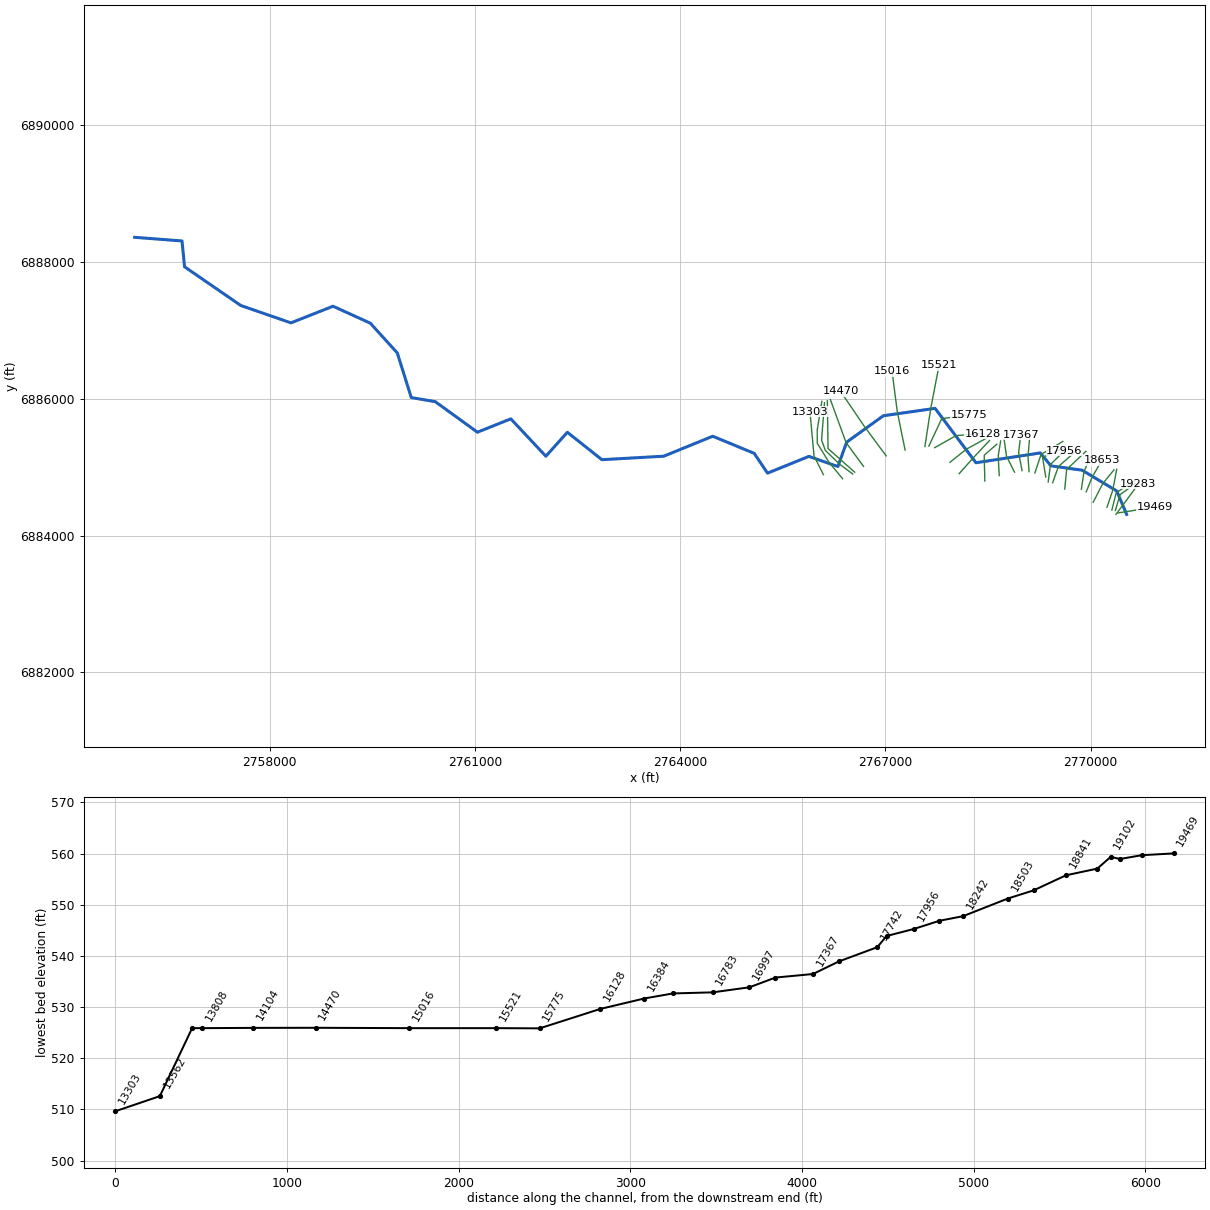
--- Lacy 057.prj (project) ---

Proj Title=Lacy 057 Base Level Engineering
Current Plan=p01
Default Exp/Contr=0.3,0.1
English Units
Geom File=g01
Flow File=f01
Plan File=p01
Y Axis Title=Elevation
X Axis Title(PF)=Main Channel Distance
X Axis Title(XS)=Station
BEGIN DESCRIPTION:
Lacy 057
END DESCRIPTION:
DSS Export Rating Curves= 0
DSS Export Rating Curve Sorted= 0
DSS Export Volume Flow Curves= 0
DXF OffsetX= 0
DXF OffsetY= 0
DXF ScaleX= 1
DXF ScaleY= 10

--- Lacy 057.p01 (plan) ---

Plan Title=Multiple Run
Short Identifier=Multiple
Geom File=g01
Flow File=f01
Subcritical Flow
K Sum by GR= 0
Std Step Tol= 0.01
Critical Tol= 0.01
Num of Std Step Trials= 20
Max Error Tol= 0.3
Flow Tol Ratio= 0.001
Split Flow NTrial= 30
Split Flow Tol= 0.02
Split Flow Ratio= 0.02
Log Output Level= 0
Friction Slope Method= 1
Unsteady Friction Slope Method= 2
Unsteady Bridges Friction Slope Method= 1
Parabolic Critical Depth
Global Vel Dist=  1 , 1 , 1
Global Log Level= 0
CheckData=True
Encroach Param= -1, 0, 0, 0
BEGIN DESCRIPTION:
Multiple Run
END DESCRIPTION:

--- Lacy 057.f01 (steady flow) ---

Flow Title=Multiple
Number of Profiles=7
Profile Names=10-year,25-year,50-year,1pct_min,100-year,1pct_plu,500-year
River Rch & RM= Lacy 057,Reach-1,19469
     156     192     218     124     248     495     319
River Rch & RM= Lacy 057,Reach-1,15521
     322     416     490     288     574    1145     786
River Rch & RM= Lacy 057,Reach-1,12806
     467     616     736     437     873    1741    1228
River Rch & RM= Lacy 057,Reach-1,8986
     733     994    1208     729    1455    2903    2115
River Rch & RM= Lacy 057,Reach-1,6122
     803    1092    1329     803    1603    3198    2337
River Rch & RM= Lacy 057,Reach-1,3748
     891    1214    1480     895    1785    3561    2604
Boundary for River Rch & Prof#=Lacy 057,Reach-1,1
Up Type=0
Dn Type=3
Dn Slope=0.005
Boundary for River Rch & Prof#=Lacy 057,Reach-1,2
Up Type=0
Dn Type=3
Dn Slope=0.005
Boundary for River Rch & Prof#=Lacy 057,Reach-1,3
Up Type=0
Dn Type=3
Dn Slope=0.005
Boundary for River Rch & Prof#=Lacy 057,Reach-1,4
Up Type=0
Dn Type=3
Dn Slope=0.005
Boundary for River Rch & Prof#=Lacy 057,Reach-1,5
Up Type=0
Dn Type=3
Dn Slope=0.005
Boundary for River Rch & Prof#=Lacy 057,Reach-1,6
Up Type=0
Dn Type=3
Dn Slope=0.005
Boundary for River Rch & Prof#=Lacy 057,Reach-1,7
Up Type=0
Dn Type=3
Dn Slope=0.005

--- Lacy 057.g01 (geometry) ---

Geom Title=Existing Conditions
Program Version=4.10

River Reach=Lacy 057        ,Reach-1
Reach XY= 30
        2770526.        6884311.      2770382.17      6884653.14
      2769874.53      6884957.45      2769419.33       6885020.3
      2769264.13      6885209.49      2768323.46      6885065.96
        2767726.        6885861.      2766969.95      6885752.84
      2766433.81      6885367.19      2766305.87      6885010.59
      2765881.85      6885158.94      2765277.39      6884914.02
      2765082.17      6885203.14      2764475.99      6885453.47
      2763759.86      6885161.53      2762855.79      6885110.64
        2762351.      6885511.42      2762036.52      6885161.46
      2761524.51      6885707.54       2761036.5      6885512.19
      2760420.21      6885959.09      2760069.43       6886018.7
      2759865.24      6886670.68       2759470.9      6887105.89
      2758926.04      6887353.69      2758310.82      6887110.56
      2757577.47      6887364.55      2756755.35      6887930.42
      2756718.09      6888308.09        2756026.        6888361.

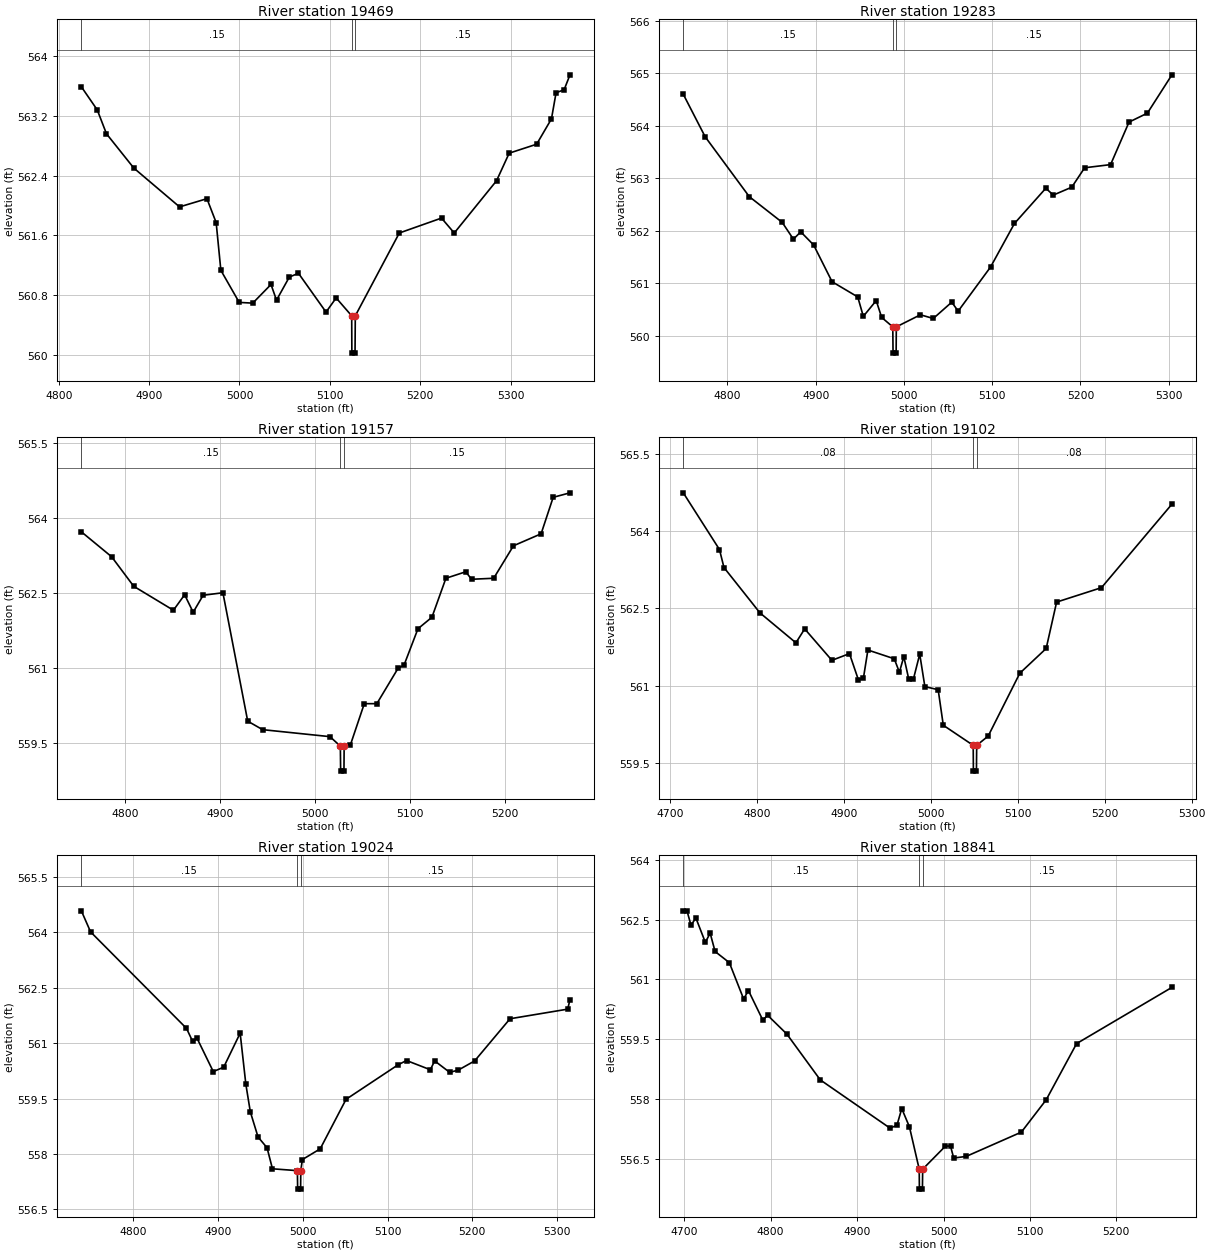
Type RM Length L Ch R = 1 ,19469   ,186,186,186
BEGIN DESCRIPTION:
Lacy 057 2547
END DESCRIPTION:
XS GIS Cut Line= 3
      2770398.57      6884332.53      2770571.54      6884359.09
      2770932.37      6884419.16
#Sta/Elev= 30
    4825  563.59  4842.6  563.28  4852.8  562.96  4883.1   562.5  4933.7  561.98
    4964  562.09  4974.2  561.77  4979.4  561.13  4999.7   560.7  5014.7  560.69
  5034.9  560.94    5041  560.73  5055.2  561.04  5065.3  561.09  5095.8  560.57
    5107  560.76  5124.2  560.52  5124.4  560.02  5127.9  560.02  5128.2  560.52
  5176.9  561.63  5223.6  561.83  5237.7  561.63  5284.5  562.33  5298.5   562.7
  5328.9  562.82  5345.3  563.16  5350.4  563.51  5359.3  563.55  5365.8  563.75
#Mann= 3 ,-1 , 0
    4825     .15       0  5124.2     .05       0  5128.2     .15       0
Bank Sta=5124.2,5128.2
XS Rating Curve= 0 ,0
Exp/Cntr=0.3,0.1

Type RM Length L Ch R = 1 ,19283   ,126,126,126
BEGIN DESCRIPTION:
Lacy 057 2546
END DESCRIPTION:
XS GIS Cut Line= 3
      2770369.83      6884311.25      2770521.76      6884514.14
      2770698.58      6884756.78
#Sta/Elev= 30
  4749.9   564.6  4774.7  563.79  4824.7  562.65    4862  562.16  4874.7  561.84
    4883  561.98  4897.6  561.73  4918.5  561.03  4947.6  560.74  4953.9  560.37
  4968.5  560.67  4974.7  560.35  4987.3  560.17  4987.6  559.67  4991.1  559.67
  4991.3  560.17  5018.6   560.4  5033.2  560.33  5054.1  560.64  5061.4  560.47
  5098.1  561.31  5125.2  562.14  5160.7  562.81  5169.2  562.68  5190.1  562.83
  5204.7   563.2  5234.1  563.26    5255  564.07  5275.8  564.24  5303.6  564.97
#Mann= 3 ,-1 , 0
  4749.9     .15       0  4987.3     .05       0  4991.3     .15       0
Bank Sta=4987.3,4991.3
XS Rating Curve= 0 ,0
Exp/Cntr=0.3,0.1

Type RM Length L Ch R = 1 ,19157   ,55,55,55
BEGIN DESCRIPTION:
Lacy 057 2545
END DESCRIPTION:
XS GIS Cut Line= 3
      2770361.07      6884368.17      2770430.13      6884600.19
      2770650.66      6884759.79
#Sta/Elev= 30
  4754.1  563.72    4786  563.22  4809.2  562.63    4851  562.15  4862.8  562.46
  4871.8  562.11  4882.3  562.45  4903.1   562.5  4929.2  559.93  4944.9  559.76
  5015.8  559.62  5026.7  559.43    5027  558.93  5030.5  558.93  5030.7  559.43
  5037.2  559.45  5051.9  560.28  5065.1  560.28  5087.5  560.99  5093.7  561.05
  5108.4  561.78  5123.1  562.01  5137.8  562.79  5158.7  562.92  5164.8  562.77
  5188.1  562.79  5208.9  563.44    5238  563.68  5250.7  564.41  5268.4   564.5
#Mann= 3 ,-1 , 0
  4754.1     .15       0  5026.7     .05       0  5030.7     .15       0
Bank Sta=5026.7,5030.7
XS Rating Curve= 0 ,0
Exp/Cntr=0.3,0.1

Type RM Length L Ch R = 1 ,19102   ,78,78,78
BEGIN DESCRIPTION:
Lacy 057 2544
END DESCRIPTION:
XS GIS Cut Line= 3
      2770310.98      6884375.54      2770373.69      6884628.24
       2770627.9      6884790.41
#Sta/Elev= 30
  4715.4  564.74    4757  563.64  4762.2  563.29  4803.6  562.41  4844.9  561.83
    4855   562.1  4886.3  561.49  4906.5  561.62  4916.8  561.11  4922.5  561.14
  4927.7  561.69    4958  561.52  4963.9  561.26    4969  561.56  4974.6  561.13
  4980.1  561.13  4987.3  561.61  4993.2  560.98  5008.5  560.92  5014.4  560.23
  5048.8  559.84    5049  559.34  5052.5  559.34  5052.8  559.84    5066  560.02
  5102.4  561.24  5132.7  561.72  5144.7  562.62  5196.3   562.9  5277.3  564.52
#Mann= 3 ,-1 , 0
  4715.4     .08       0  5048.8     .05       0  5052.8     .08       0
Bank Sta=5048.8,5052.8
XS Rating Curve= 0 ,0
Exp/Cntr=0.3,0.1

Type RM Length L Ch R = 1 ,19024   ,183,183,183
BEGIN DESCRIPTION:
Lacy 057 2543
END DESCRIPTION:
XS GIS Cut Line= 3
      2770238.17      6884413.63      2770322.93      6884663.35
      2770381.16      6884970.46
#Sta/Elev= 30
  4738.9  564.58  4749.8  564.01  4862.9   561.4  4870.1  561.05  4875.4  561.13
  4894.5  560.23  4906.8  560.35  4926.2  561.27  4932.9  559.89  4938.2  559.14
  4947.3  558.46  4957.9  558.17  4964.3   557.6  4993.7  557.55    4994  557.05
  4997.5  557.05  4997.7  557.55  4999.6  557.85  5020.6  558.14  5051.1  559.48
  5112.2  560.41  5122.4  560.53  5150.5  560.28  5155.6  560.52  5173.3  560.21
  5183.4  560.27  5202.8  560.52  5244.5  561.66  5312.5  561.92  5315.2  562.18
#Mann= 3 ,-1 , 0
  4738.9     .15       0  4993.7     .05       0  4997.7     .15       0
Bank Sta=4993.7,4997.7
XS Rating Curve= 0 ,0
Exp/Cntr=0.3,0.1

Type RM Length L Ch R = 1 ,18841   ,188,188,188
BEGIN DESCRIPTION:
Lacy 057 2542
END DESCRIPTION:
XS GIS Cut Line= 3
      2770036.79       6884488.3      2770176.75      6884760.17
      2770340.48      6884961.65
#Sta/Elev= 30
  4698.9  562.72  4703.2  562.72  4707.8  562.36  4713.5  562.54  4724.4  561.93
    4730  562.16  4735.7   561.7  4752.2  561.42  4768.7  560.51  4774.3  560.72
  4790.9  559.98  4796.5   560.1  4818.7  559.63  4857.4  558.48  4938.1  557.27
  4946.1  557.34  4951.7  557.76  4960.6   557.3  4971.9  556.24  4972.1  555.74
  4975.6  555.74  4975.9  556.24  5002.3  556.82  5008.1  556.82  5011.8  556.52
  5026.2  556.56  5090.1  557.17  5118.8  557.98    5154  559.39  5264.3   560.8
#Mann= 3 ,-1 , 0
  4698.9     .15       0  4971.9     .05       0  4975.9     .15       0
Bank Sta=4971.9,4975.9
XS Rating Curve= 0 ,0
Exp/Cntr=0.3,0.1

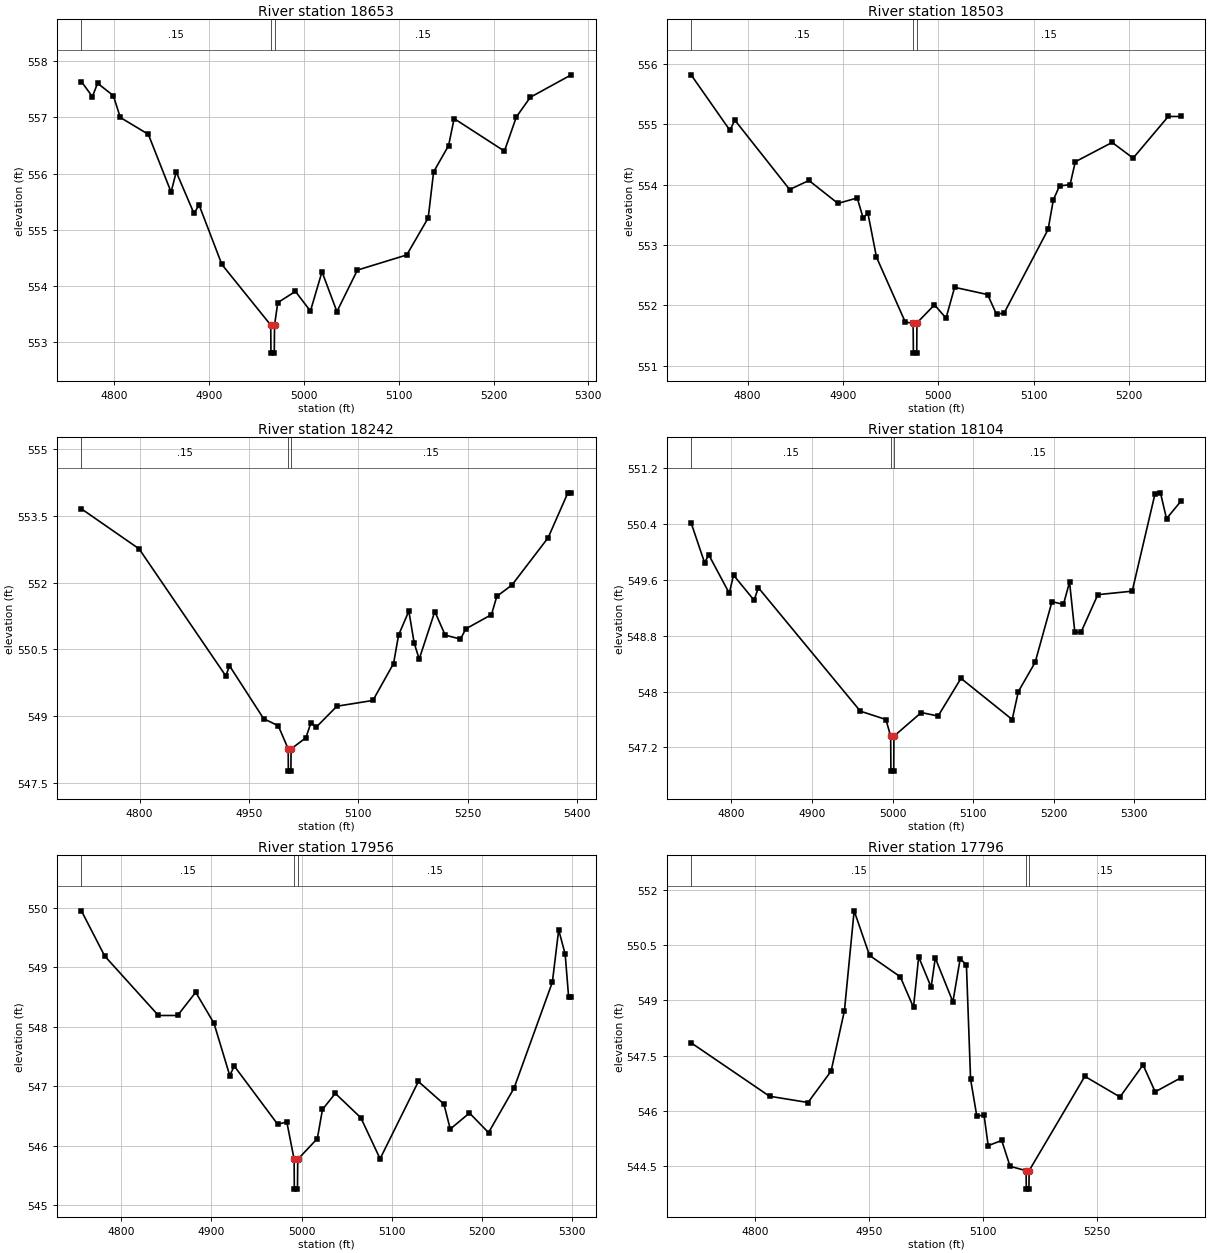
Type RM Length L Ch R = 1 ,18653   ,150,150,150
BEGIN DESCRIPTION:
Lacy 057 2541
END DESCRIPTION:
XS GIS Cut Line= 3
      2769934.73      6884639.91      2770024.62      6884860.31
      2770163.89      6885100.99
#Sta/Elev= 30
  4765.8  557.64  4777.4  557.37  4782.8  557.61  4799.4  557.39  4806.8     557
  4836.3   556.7  4860.3  555.67  4865.7  556.03  4884.4  555.29  4889.8  555.44
  4913.8  554.38  4965.3   553.3  4965.5   552.8    4969   552.8  4969.3   553.3
  4972.7   553.7  4991.3   553.9  5007.1  553.55  5019.3  554.25    5035  553.54
  5056.6  554.28  5108.6  554.55  5131.2  555.21  5136.9  556.03  5152.7   556.5
  5158.5  556.98  5211.5   556.4  5224.1  557.01  5238.8  557.36  5281.9  557.76
#Mann= 3 ,-1 , 0
  4765.8     .15       0  4965.3     .05       0  4969.3     .15       0
Bank Sta=4965.3,4969.3
XS Rating Curve= 0 ,0
Exp/Cntr=0.3,0.1

Type RM Length L Ch R = 1 ,18503   ,261,261,261
BEGIN DESCRIPTION:
Lacy 057 3488
END DESCRIPTION:
XS GIS Cut Line= 3
      2769864.63      6884678.77      2769902.97      6884939.71
      2770007.24      6885166.55
#Sta/Elev= 30
  4740.8  555.82  4781.5   554.9  4786.6  555.07  4844.1  553.92  4864.3  554.07
  4894.7  553.69  4914.9  553.78  4921.1  553.45  4926.1  553.53  4935.1   552.8
  4965.4  551.72  4973.5  551.71  4973.8  551.21  4977.3  551.21  4977.5  551.71
  4995.9  552.01    5008  551.79    5017   552.3  5051.6  552.18    5061  551.85
  5069.1  551.88    5115  553.26  5120.5  553.75    5127  553.98    5138     554
  5143.5  554.38  5182.1   554.7  5204.1  554.44  5240.9  555.13  5254.2  555.13
#Mann= 3 ,-1 , 0
  4740.8     .15       0  4973.5     .05       0  4977.5     .15       0
Bank Sta=4973.5,4977.5
XS Rating Curve= 0 ,0
Exp/Cntr=0.3,0.1

Type RM Length L Ch R = 1 ,18242   ,138,138,138
BEGIN DESCRIPTION:
Lacy 057 2539
END DESCRIPTION:
XS GIS Cut Line= 3
      2769621.16      6884682.32      2769649.33      6884967.05
       2769929.3      6885232.31
#Sta/Elev= 30
  4720.3  553.66  4799.4  552.76  4918.4   549.9  4923.4  550.13  4970.2  548.94
  4990.3  548.78  5003.9  548.26  5004.1  547.76  5007.6  547.76  5007.9  548.26
  5028.2  548.51  5035.1  548.85  5042.4  548.75  5070.7  549.22  5120.1  549.35
  5148.4  550.18  5155.3  550.82  5169.4  551.36  5176.7  550.64  5183.6  550.28
    5205  551.35  5219.2  550.82  5240.2  550.73  5247.5  550.96  5282.7  551.28
    5290  551.69    5311  551.95  5360.4  553.01  5387.5  554.02  5392.1  554.02
#Mann= 3 ,-1 , 0
  4720.3     .15       0  5003.9     .05       0  5007.9     .15       0
Bank Sta=5003.9,5007.9
XS Rating Curve= 0 ,0
Exp/Cntr=0.3,0.1

Type RM Length L Ch R = 1 ,18104   ,148,148,148
BEGIN DESCRIPTION:
Lacy 057 2538
END DESCRIPTION:
XS GIS Cut Line= 3
      2769444.33      6884773.24       2769529.4      6885010.85
      2769796.43      6885246.02
#Sta/Elev= 30
  4749.9  550.42  4766.6  549.85  4771.9  549.96  4797.3  549.41  4802.6  549.67
  4828.1  549.31  4833.4  549.49    4960  547.72  4991.8   547.6  4997.7  547.36
    4998  546.86  5001.5  546.86  5001.7  547.36  5035.7   547.7  5056.6  547.65
    5085  548.19  5148.6   547.6  5156.2     548  5177.1  548.42    5198  549.29
  5212.2  549.25  5219.8  549.57  5226.4  548.85    5234  548.85  5254.9  549.39
  5297.6  549.44    5326  550.84  5332.7  550.85  5340.2  550.48  5358.1  550.73
#Mann= 3 ,-1 , 0
  4749.9     .15       0  4997.7     .05       0  5001.7     .15       0
Bank Sta=4997.7,5001.7
XS Rating Curve= 0 ,0
Exp/Cntr=0.3,0.1

Type RM Length L Ch R = 1 ,17956   ,160,160,160
BEGIN DESCRIPTION:
Lacy 057 2537
END DESCRIPTION:
XS GIS Cut Line= 3
      2769379.46      6884785.43      2769412.76      6885040.86
      2769616.47      6885240.04
#Sta/Elev= 30
  4756.2  549.95    4782  549.19  4841.5  548.19  4862.7  548.19  4882.8  548.58
    4903  548.06  4920.5  547.18  4925.5  547.34  4973.6  546.36  4983.7   546.4
  4991.8  545.77    4992  545.27  4995.5  545.27  4995.8  545.77  5017.5  546.12
  5023.2  546.61  5037.4  546.88  5065.7  546.47    5087  545.78  5129.4  547.08
  5157.7   546.7  5164.7  546.28    5186  546.55  5207.1  546.22  5235.4  546.97
  5277.8  548.75  5284.8  549.63    5292  549.22  5295.8   548.5  5298.7   548.5
#Mann= 3 ,-1 , 0
  4756.2     .15       0  4991.8     .05       0  4995.8     .15       0
Bank Sta=4991.8,4995.8
XS Rating Curve= 0 ,0
Exp/Cntr=0.3,0.1

Type RM Length L Ch R = 1 ,17796   ,54,54,54
BEGIN DESCRIPTION:
Lacy 057 2536
END DESCRIPTION:
XS GIS Cut Line= 3
       2769343.9      6884859.01       2769297.2      6885145.38
      2769621.59      6885289.94
#Sta/Elev= 30
  4715.8  547.85  4819.1   546.4  4869.8  546.23  4900.2  547.08  4917.8  548.72
  4930.6  551.43  4950.9  550.22  4991.4  549.64  5008.8  548.81  5015.6  550.18
    5032  549.36  5037.5  550.15  5060.7  548.96  5070.3  550.13  5078.5  549.96
    5084  546.86  5092.2  545.86  5101.7  545.89  5107.2  545.06    5125   545.2
    5136   544.5  5157.1  544.38  5157.4  543.88  5160.9  543.88  5161.1  544.38
  5234.5  546.94  5280.8  546.38  5311.2  547.25  5327.2  546.52  5361.1   546.9
#Mann= 3 ,-1 , 0
  4715.8     .15       0  5157.1     .05       0  5161.1     .15       0
Bank Sta=5157.1,5161.1
XS Rating Curve= 0 ,0
Exp/Cntr=0.3,0.1

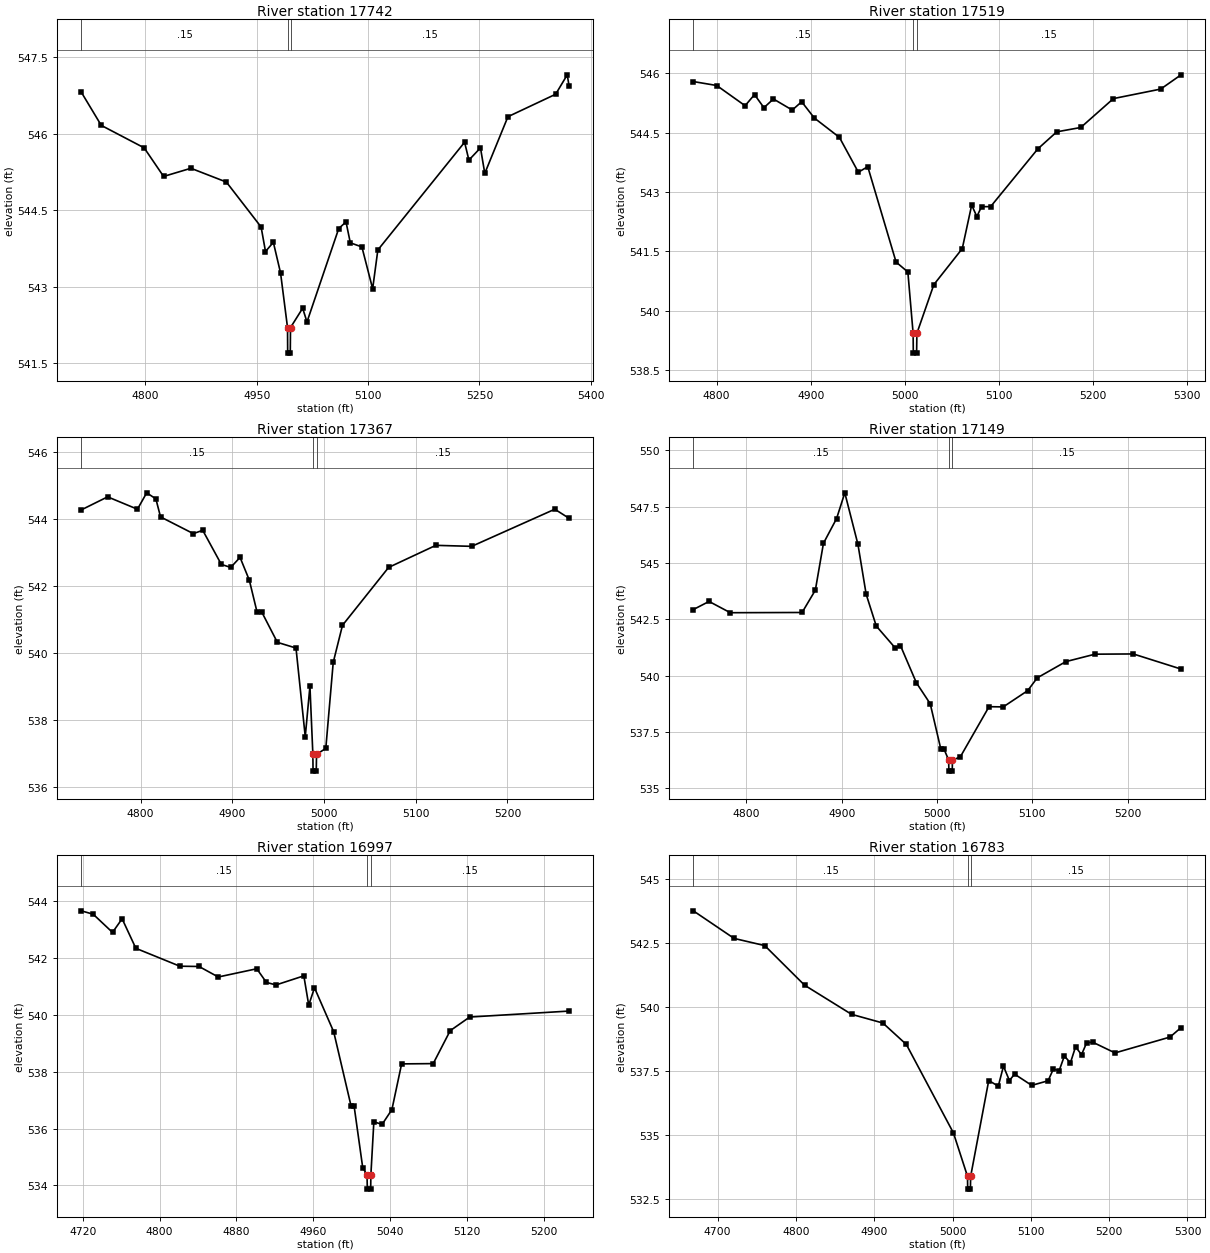
Type RM Length L Ch R = 1 ,17742   ,223,223,223
BEGIN DESCRIPTION:
Lacy 057 2535
END DESCRIPTION:
XS GIS Cut Line= 3
      2769184.04      6884915.69       2769275.6      6885188.14
      2769593.55      6885376.94
#Sta/Elev= 30
  4713.5  546.81  4740.4  546.16  4798.2  545.72  4824.4  545.16  4861.2  545.32
    4909  545.05  4955.8  544.17  4961.7  543.69  4972.3  543.87    4982  543.27
  4991.4   542.2  4991.6   541.7  4995.1   541.7  4995.4   542.2  5011.8  542.58
  5017.6  542.31  5060.4  544.14  5070.2  544.27    5076  543.86  5091.6  543.78
  5106.1  542.96  5113.1  543.72    5230  545.83  5235.8  545.48  5251.4  545.72
  5257.2  545.22  5288.4  546.33  5352.7  546.77  5368.3  547.15  5370.7  546.94
#Mann= 3 ,-1 , 0
  4713.5     .15       0  4991.4     .05       0  4995.4     .15       0
Bank Sta=4991.4,4995.4
XS Rating Curve= 0 ,0
Exp/Cntr=0.3,0.1

Type RM Length L Ch R = 1 ,17519   ,152,152,152
BEGIN DESCRIPTION:
Lacy 057 2534
END DESCRIPTION:
XS GIS Cut Line= 3
      2769099.91      6884936.14      2769084.08      6885160.89
      2769110.61      6885452.48
#Sta/Elev= 30
  4775.2  545.79  4800.1  545.69  4830.2  545.18  4840.2  545.46  4850.2  545.13
  4860.3  545.35  4880.3  545.07  4890.3  545.28  4903.7  544.87  4930.4  544.38
  4950.5   543.5  4960.5  543.64  4990.6  541.23  5003.1  540.98  5008.7  539.43
  5008.9  538.93  5012.4  538.93  5012.7  539.43  5030.7  540.66  5060.9  541.57
  5070.9  542.67  5076.4  542.38  5081.4  542.63    5091  542.63  5141.2  544.09
  5161.3  544.52  5186.8  544.63  5221.5  545.36  5271.7   545.6  5293.3  545.96
#Mann= 3 ,-1 , 0
  4775.2     .15       0  5008.7     .05       0  5012.7     .15       0
Bank Sta=5008.7,5012.7
XS Rating Curve= 0 ,0
Exp/Cntr=0.3,0.1

Type RM Length L Ch R = 1 ,17367   ,218,218,218
BEGIN DESCRIPTION:
Lacy 057 2533
END DESCRIPTION:
XS GIS Cut Line= 3
      2768996.85      6884950.89      2768947.82      6885212.94
      2768977.91      6885476.42
#Sta/Elev= 30
  4735.3  544.27    4764  544.66  4796.5  544.29  4806.6  544.78  4816.6   544.6
  4821.7  544.06  4857.5  543.56  4867.7  543.66    4888  542.64  4898.2  542.55
  4908.4  542.85  4918.5  542.17  4926.9  541.22    4932  541.22  4949.1  540.31
  4969.4  540.14  4979.5  537.49  4984.6     539  4987.8  536.96    4988  536.46
  4991.5  536.46  4991.8  536.96  5001.9  537.14    5010  539.71  5020.1  540.82
  5070.4  542.55  5121.9  543.21    5161  543.18  5251.6  544.29  5267.1  544.02
#Mann= 3 ,-1 , 0
  4735.3     .15       0  4987.8     .05       0  4991.8     .15       0
Bank Sta=4987.8,4991.8
XS Rating Curve= 0 ,0
Exp/Cntr=0.3,0.1

Type RM Length L Ch R = 1 ,17149   ,152,152,152
BEGIN DESCRIPTION:
Lacy 057 2532
END DESCRIPTION:
XS GIS Cut Line= 3
      2768887.36      6884929.13      2768770.09      6885161.78
       2768734.6      6885410.33
#Sta/Elev= 30
  4744.4  542.94  4760.9   543.3  4783.2   542.8  4858.5  542.81  4872.4   543.8
  4880.9  545.88  4894.7  546.98  4903.3  548.12  4917.1  545.83  4925.7  543.62
  4936.3  542.21  4956.1  541.24  4961.7  541.34  4978.4  539.69  4992.9  538.76
  5003.9  536.77  5007.1  536.77  5012.2  536.27  5012.5  535.77    5016  535.77
  5016.2  536.27  5024.3  536.39  5054.6  538.63  5069.5  538.62  5095.1  539.34
  5105.2  539.91  5135.2  540.63  5165.8  540.96  5205.9  540.97    5256   540.3
#Mann= 3 ,-1 , 0
  4744.4     .15       0  5012.2     .05       0  5016.2     .15       0
Bank Sta=5012.2,5016.2
XS Rating Curve= 0 ,0
Exp/Cntr=0.3,0.1

Type RM Length L Ch R = 1 ,16997   ,214,214,214
BEGIN DESCRIPTION:
Lacy 057 2531
END DESCRIPTION:
XS GIS Cut Line= 3
      2768664.12      6884878.58      2768648.31      6885162.24
      2768683.93      6885383.08
#Sta/Elev= 30
  4718.5  543.67  4730.9  543.55    4751  542.91    4761  543.39  4775.3  542.35
  4821.1  541.72  4841.1  541.71  4861.1  541.34  4901.2  541.63  4911.2  541.15
  4921.2  541.06  4950.2  541.38  4955.3  540.35  4961.3  540.96  4981.3  539.41
  4999.5  536.78  5002.6  536.78  5011.5  534.63    5016  534.37  5016.3  533.87
  5019.8  533.87    5020  534.37  5023.1  536.24  5031.7  536.15  5041.9  536.67
    5052  538.28  5084.9  538.29  5102.6  539.45  5122.9  539.93  5226.3  540.14
#Mann= 3 ,-1 , 0
  4718.5     .15       0    5016     .05       0    5020     .15       0
Bank Sta=5016,5020
XS Rating Curve= 0 ,0
Exp/Cntr=0.3,0.1

Type RM Length L Ch R = 1 ,16783   ,231,231,231
BEGIN DESCRIPTION:
Lacy 057 2530
END DESCRIPTION:
XS GIS Cut Line= 3
      2768453.35      6884798.95      2768444.03      6885176.24
      2768629.36      6885337.24
#Sta/Elev= 30
  4668.9  543.77    4721  542.69  4760.1  542.41    4811  540.86    4871  539.72
    4911  539.38    4941  538.54  5001.1  535.08  5019.1  533.38  5019.3  532.88
  5022.8  532.88  5023.1  533.38  5046.2  537.13  5058.4  536.91    5065  537.69
  5072.6  537.13  5079.2  537.38  5101.1  536.94    5122  537.12  5128.6  537.57
  5136.2  537.52  5142.8  538.09  5150.5  537.82  5157.1  538.45  5164.7  538.14
  5171.3  538.61    5179  538.63  5207.5  538.21  5277.7  538.83  5291.8   539.2
#Mann= 3 ,-1 , 0
  4668.9     .15       0  5019.1     .05       0  5023.1     .15       0
Bank Sta=5019.1,5023.1
XS Rating Curve= 0 ,0
Exp/Cntr=0.3,0.1

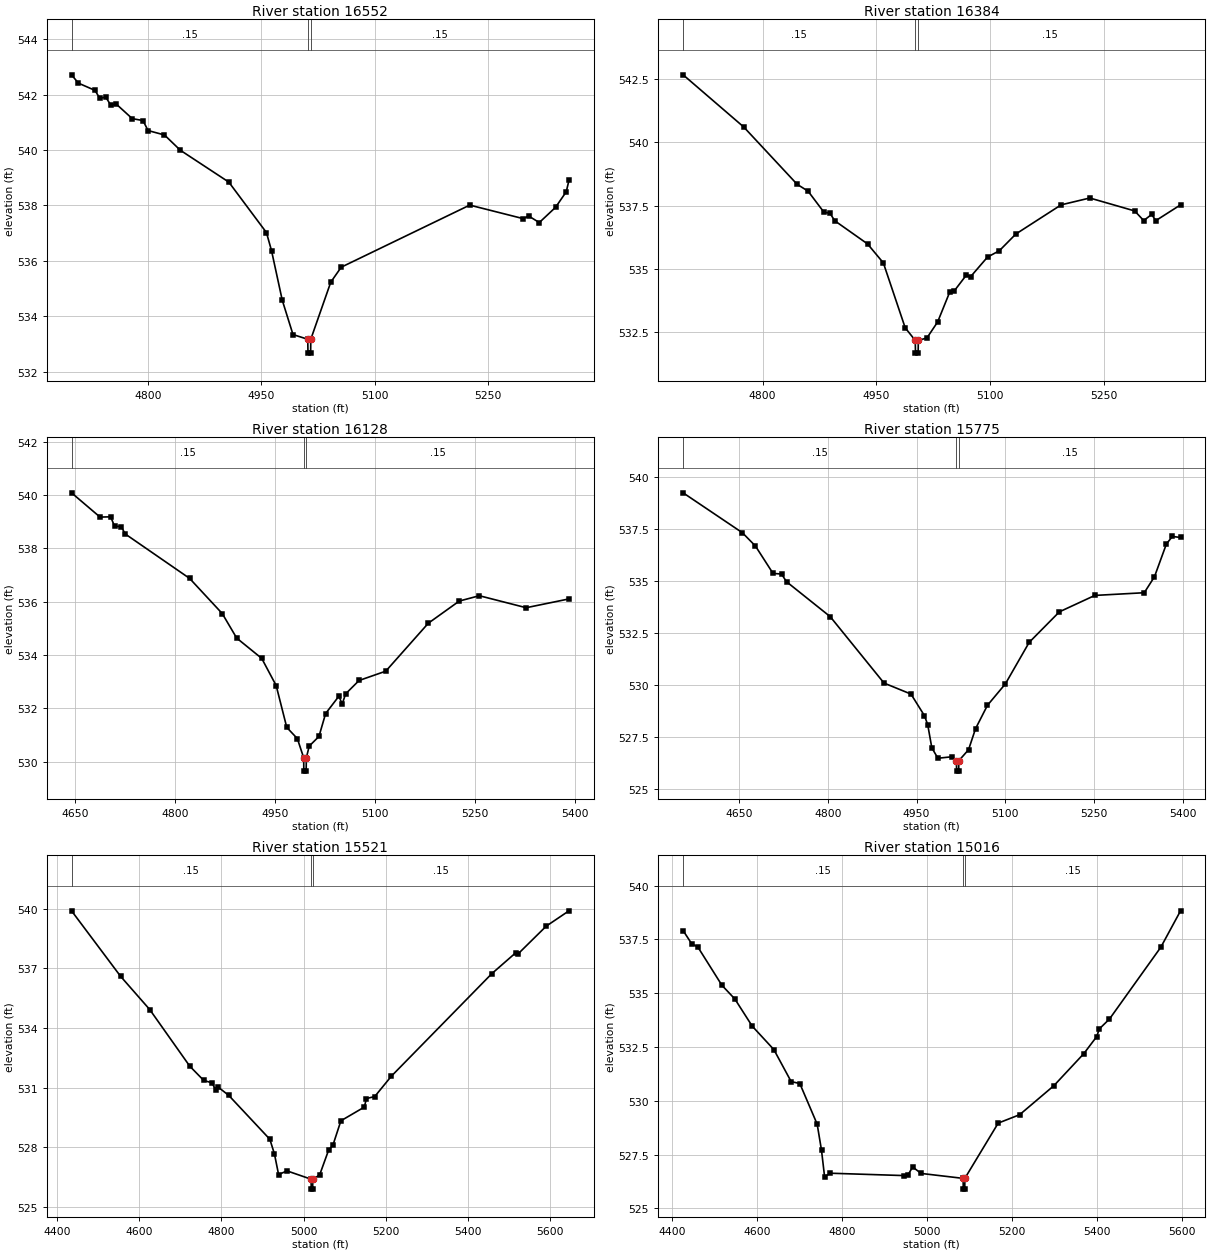
Type RM Length L Ch R = 1 ,16552   ,168,168,168
BEGIN DESCRIPTION:
Lacy 057 2528
END DESCRIPTION:
XS GIS Cut Line= 3
      2768078.06      6884905.69       2768277.9      6885130.57
      2768521.69      6885390.49
#Sta/Elev= 30
  4699.3  542.71  4708.4  542.41  4730.2  542.15  4736.8  541.86  4744.4  541.91
  4751.1  541.62  4758.6  541.65  4779.5  541.13  4793.7  541.06  4800.4   540.7
  4822.1  540.54    4843  539.99  4907.1  538.84  4956.8  537.02  4963.5  536.37
  4977.7  534.58  4991.9  533.34  5011.4  533.17  5011.7  532.67  5015.2  532.67
  5015.4  533.17  5041.8  535.23  5055.6  535.77  5225.4  538.01  5296.3  537.52
  5303.1  537.62  5317.3  537.38  5338.8  537.93  5352.9  538.49  5356.5   538.9
#Mann= 3 ,-1 , 0
  4699.3     .15       0  5011.4     .05       0  5015.4     .15       0
Bank Sta=5011.4,5015.4
XS Rating Curve= 0 ,0
Exp/Cntr=0.3,0.1

Type RM Length L Ch R = 1 ,16384   ,256,256,256
BEGIN DESCRIPTION:
Lacy 057 2529
END DESCRIPTION:
XS GIS Cut Line= 3
      2767943.37      6885072.07      2768179.31      6885261.48
      2768489.05      6885431.92
#Sta/Elev= 30
  4695.3  542.66  4775.3   540.6  4845.7  538.34  4860.1  538.07    4881  537.24
  4888.9   537.2  4895.4   536.9  4938.5  535.99  4959.4  535.24  4988.2  532.68
  5001.5  532.18  5001.8  531.68  5005.3  531.68  5005.5  532.18  5016.9  532.28
    5031  532.91  5047.1   534.1  5052.8  534.13  5068.9  534.76  5074.6   534.7
  5096.8  535.47  5112.4  535.72  5134.2  536.38  5193.9  537.53  5231.7   537.8
  5290.9  537.29  5302.8  536.91  5313.2  537.15  5318.9  536.91  5351.4  537.53
#Mann= 3 ,-1 , 0
  4695.3     .15       0  5001.5     .05       0  5005.5     .15       0
Bank Sta=5001.5,5005.5
XS Rating Curve= 0 ,0
Exp/Cntr=0.3,0.1

Type RM Length L Ch R = 1 ,16128   ,353,353,353
BEGIN DESCRIPTION:
Lacy 057 2527
END DESCRIPTION:
XS GIS Cut Line= 3
      2767720.92      6885286.51      2768032.04       6885462.2
      2768420.05      6885492.57
#Sta/Elev= 30
  4644.1  540.08  4686.9  539.17  4702.8  539.18  4708.6  538.83  4718.8  538.81
  4724.5  538.54  4821.3  536.87  4870.3  535.55    4892  534.63  4929.5  533.87
  4951.2  532.85  4967.1  531.28    4983  530.86  4992.5  530.14  4992.7  529.64
  4996.2  529.64  4996.5  530.14  5000.8  530.58  5015.4  530.94  5025.4   531.8
  5045.3  532.45  5050.3  532.16  5055.5  532.54  5075.6  533.04  5115.7  533.39
  5179.6  535.19    5226  536.02  5256.1  536.22  5326.4  535.77  5390.6   536.1
#Mann= 3 ,-1 , 0
  4644.1     .15       0  4992.5     .05       0  4996.5     .15       0
Bank Sta=4992.5,4996.5
XS Rating Curve= 0 ,0
Exp/Cntr=0.3,0.1

Type RM Length L Ch R = 1 ,15775   ,254,254,254
BEGIN DESCRIPTION:
Lacy 057 2526
END DESCRIPTION:
XS GIS Cut Line= 3
      2767635.25      6885310.36      2767823.46      6885709.89
      2768219.64       6885764.7
#Sta/Elev= 30
    4555  539.25  4655.2  537.33  4677.3  536.69  4707.1  535.37  4721.5  535.34
  4729.9  534.97  4803.8  533.29  4894.9  530.09  4940.5  529.56  4963.3  528.52
  4968.8  528.09  4975.8  526.97  4986.1  526.47  5009.3  526.54  5017.4  526.35
  5017.7  525.85  5021.2  525.85  5021.4  526.35  5037.9  526.88  5049.7  527.89
  5069.9  529.02  5100.2  530.05  5140.5  532.05  5191.6  533.52  5251.6  534.31
  5335.2  534.44  5352.5  535.21  5372.7  536.79  5382.8  537.15  5396.6   537.1
#Mann= 3 ,-1 , 0
    4555     .15       0  5017.4     .05       0  5021.4     .15       0
Bank Sta=5017.4,5021.4
XS Rating Curve= 0 ,0
Exp/Cntr=0.3,0.1

Type RM Length L Ch R = 1 ,15521   ,505,505,505
BEGIN DESCRIPTION:
Lacy 057 2525
END DESCRIPTION:
XS GIS Cut Line= 3
      2767577.13      6885302.92      2767662.44      6885858.32
      2767785.35      6886495.16
#Sta/Elev= 30
  4435.3   539.9  4554.8   536.6  4625.6  534.93    4723  532.08  4757.1  531.36
  4777.3  531.24  4786.3  530.87  4791.3  531.04  4817.8  530.61  4917.9   528.4
  4929.1  527.66  4939.2  526.62  4959.5  526.81  5018.3  526.39  5018.6  525.89
  5022.1  525.89  5022.3  526.39    5039   526.6    5061  527.86  5071.2  528.09
  5090.8  529.33  5147.8  530.02  5152.9  530.45  5173.1  530.55  5213.8  531.58
  5458.2  536.74  5515.8  537.78  5520.9  537.71  5590.6  539.13  5645.8   539.9
#Mann= 3 ,-1 , 0
  4435.3     .15       0  5018.3     .05       0  5022.3     .15       0
Bank Sta=5018.3,5022.3
XS Rating Curve= 0 ,0
Exp/Cntr=0.3,0.1

Type RM Length L Ch R = 1 ,15016   ,546,546,546
BEGIN DESCRIPTION:
Lacy 057 2524
END DESCRIPTION:
XS GIS Cut Line= 3
      2767287.91      6885251.57       2767172.7      6885817.65
      2767096.65      6886406.98
#Sta/Elev= 30
  4425.1  537.91  4444.9  537.31    4460  537.14  4516.4  535.37    4547  534.73
  4587.8  533.47  4638.8  532.38  4679.6  530.89    4700   530.8  4740.9  528.91
  4751.1   527.7  4758.4  526.46  4771.5  526.63    4945  526.52  4955.2  526.56
  4965.8  526.92  4985.8  526.62  5084.8  526.39  5085.1  525.89  5088.6  525.89
  5088.8  526.39  5167.4  528.96  5217.9  529.35  5298.6   530.7  5369.1  532.19
  5399.4  532.98  5405.6  533.34  5429.6   533.8  5550.6  537.14    5597  538.83
#Mann= 3 ,-1 , 0
  4425.1     .15       0  5084.8     .05       0  5088.8     .15       0
Bank Sta=5084.8,5088.8
XS Rating Curve= 0 ,0
Exp/Cntr=0.3,0.1

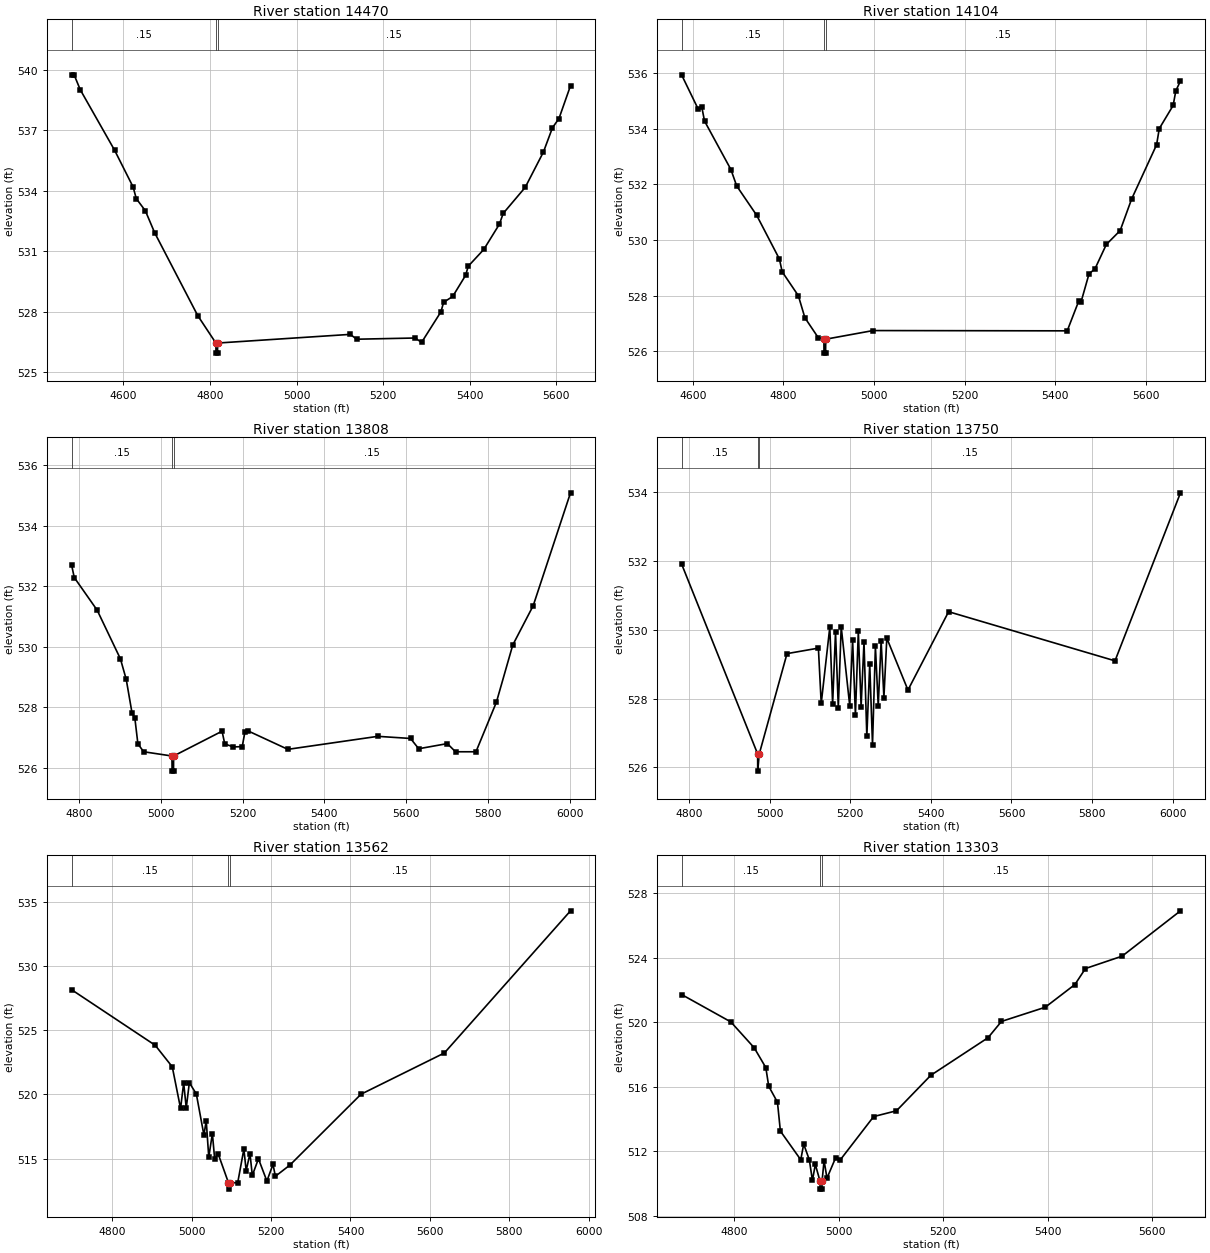
Type RM Length L Ch R = 1 ,14470   ,366,366,366
BEGIN DESCRIPTION:
Lacy 057 2523
END DESCRIPTION:
XS GIS Cut Line= 3
      2767010.53      6885166.78      2766691.77      6885597.97
      2766345.66      6886107.51
#Sta/Elev= 30
  4480.5  539.76  4486.3  539.76  4500.5  539.02  4579.8  536.02  4622.5   534.2
  4629.9  533.62  4650.8  533.02  4672.3  531.93  4771.8  527.82  4813.7  526.46
    4814  525.96  4817.5  525.96  4817.7  526.46    5124  526.89    5139  526.65
  5274.2  526.71  5288.7  526.49  5333.5  528.01  5339.6  528.48  5360.6  528.77
  5390.5  529.82  5396.5  530.27  5432.4   531.1  5468.4  532.35  5477.3  532.89
  5528.1  534.18  5570.1  535.93  5591.1  537.14    5606  537.59  5632.7  539.22
#Mann= 3 ,-1 , 0
  4480.5     .15       0  4813.7     .05       0  4817.7     .15       0
Bank Sta=4813.7,4817.7
XS Rating Curve= 0 ,0
Exp/Cntr=0.3,0.1

Type RM Length L Ch R = 1 ,14104   ,296,296,296
BEGIN DESCRIPTION:
Lacy 057 2511
END DESCRIPTION:
XS GIS Cut Line= 3
       2766679.6      6885013.18      2766425.31      6885359.77
       2766195.2      6885990.54
#Sta/Elev= 30
  4575.2  535.93  4611.3  534.72  4619.7  534.78  4625.9  534.27  4684.1  532.53
  4696.9  531.94  4740.9  530.89  4791.1  529.32  4797.3  528.86    4833     528
  4847.4  527.21  4876.7   526.5  4889.4  526.44  4889.6  525.94  4893.1  525.94
  4893.4  526.44  4997.9  526.75  5426.5  526.74  5451.7   527.8  5457.1  527.78
  5474.7  528.79  5487.6  528.96  5512.8  529.84  5543.4  530.34  5568.6  531.47
  5623.8  533.42  5629.7     534  5660.3  534.83  5666.3  535.36  5676.5  535.71
#Mann= 3 ,-1 , 0
  4575.2     .15       0  4889.4     .05       0  4893.4     .15       0
Bank Sta=4889.4,4893.4
XS Rating Curve= 0 ,0
Exp/Cntr=0.3,0.1

Type RM Length L Ch R = 1 ,13808   ,58,58,58
BEGIN DESCRIPTION:
Lacy 057 2507
END DESCRIPTION:
XS GIS Cut Line= 3
      2766551.48      6884927.78      2766161.53      6885273.17
      2766151.64      6885972.18
#Sta/Elev= 30
  4781.8   532.7  4788.3  532.29  4844.3  531.21  4901.2   529.6  4915.4  528.92
  4929.7   527.8  4936.3  527.66  4943.9  526.79  4958.1  526.53  5027.2  526.39
  5027.5  525.89    5031  525.89  5031.2  526.39  5149.7  527.21  5156.3  526.79
  5177.2  526.69    5199   526.7  5205.7  527.19  5213.2  527.22  5310.6  526.61
  5530.6  527.04  5610.6  526.97  5630.6  526.63  5700.6   526.8  5720.6  526.53
  5770.6  526.53  5820.6  528.17  5860.6  530.06  5910.6  531.36  6001.8  535.09
#Mann= 3 ,-1 , 0
  4781.8     .15       0  5027.2     .05       0  5031.2     .15       0
Bank Sta=5027.2,5031.2
XS Rating Curve= 0 ,0
Exp/Cntr=0.3,0.1

Type RM Length L Ch R = 1 ,13750   ,188,188,188
BEGIN DESCRIPTION:
Lacy 057 2506
END DESCRIPTION:
XS GIS Cut Line= 5
      2766522.84      6884901.06      2766332.24      6885043.58
      2766121.85      6885246.22      2766066.75      6885398.56
      2766110.18      6885943.02
#Sta/Elev= 30
  4781.2  531.92    4970  526.39  4970.2  525.89    4974  526.39  5042.9  529.31
  5120.8  529.47  5127.8  527.86  5149.1  530.08  5156.1  527.84  5163.3  529.94
  5170.2  527.74  5177.4  530.09  5198.5   527.8  5205.7  529.71  5212.7  527.52
  5219.9  529.96  5226.8  527.77    5234  529.65    5241   526.9  5248.2  529.01
  5255.1  526.66  5262.3  529.52  5269.3  527.79  5276.5  529.68  5283.4  528.03
  5290.6  529.76  5343.1  528.25    5444  530.53    5857   529.1  6019.5  533.99
#Mann= 3 ,-1 , 0
  4781.2     .15       0    4970     .05       0    4974     .15       0
Bank Sta=4970,4974
XS Rating Curve= 0 ,0
Exp/Cntr=0.3,0.1

Type RM Length L Ch R = 1 ,13562   ,259,259,259
BEGIN DESCRIPTION:
Lacy 057 2508
END DESCRIPTION:
XS GIS Cut Line= 5
      2766374.15      6884832.44      2766173.77      6885074.31
      2766003.72      6885351.55      2766002.75      6885539.86
      2766071.07      6885963.14
#Sta/Elev= 30
  4697.8  528.18  4908.4  523.84  4951.3  522.16  4972.2  518.91    4980   520.9
  4986.5  518.95  4994.3  520.92  5011.9  520.04    5031  516.83  5036.8  517.96
  5043.2   515.1  5052.3  516.95  5058.1  514.95  5066.7  515.38  5092.8  513.11
  5093.1  512.61  5096.8  513.11  5116.1  513.11  5131.6  515.73  5137.4  514.06
    5147  515.38  5152.9  513.68  5168.3  514.98  5189.6  513.24    5205  514.55
  5210.9  513.61  5247.6  514.49  5426.6  520.02  5636.5  523.24  5954.2  534.34
#Mann= 3 ,-1 , 0
  4697.8     .15       0  5092.8     .05       0  5096.8     .15       0
Bank Sta=5092.8,5096.8
XS Rating Curve= 0 ,0
Exp/Cntr=0.3,0.1

Type RM Length L Ch R = 1 ,13303   ,197,197,197
BEGIN DESCRIPTION:
Lacy 057 2510
END DESCRIPTION:
XS GIS Cut Line= 3
      2766093.87       6884892.7      2765956.98      6885164.22
      2765897.01      6885812.17
#Sta/Elev= 30
    4699  521.73  4793.3  520.03  4837.9  518.43  4860.2   517.2  4865.8  516.04
  4882.5  515.05  4888.1  513.26  4927.1  511.48  4932.7  512.45  4943.5  511.48
  4949.4   510.2    4955  511.19  4963.9  510.16  4964.1  509.66  4967.6  509.66
  4967.9  510.16  4971.7  511.43  4977.3  510.34    4994  511.62  5003.1  511.49
  5066.6  514.16  5110.3  514.52    5176  516.72  5285.5  519.05  5311.2  520.06
    5395  520.94  5451.8  522.35  5471.9  523.34  5542.2  524.11  5653.8  526.92
#Mann= 3 ,-1 , 0
    4699     .15       0  4963.9     .05       0  4967.9     .15       0
Bank Sta=4963.9,4967.9
XS Rating Curve= 0 ,0
Exp/Cntr=0.3,0.1