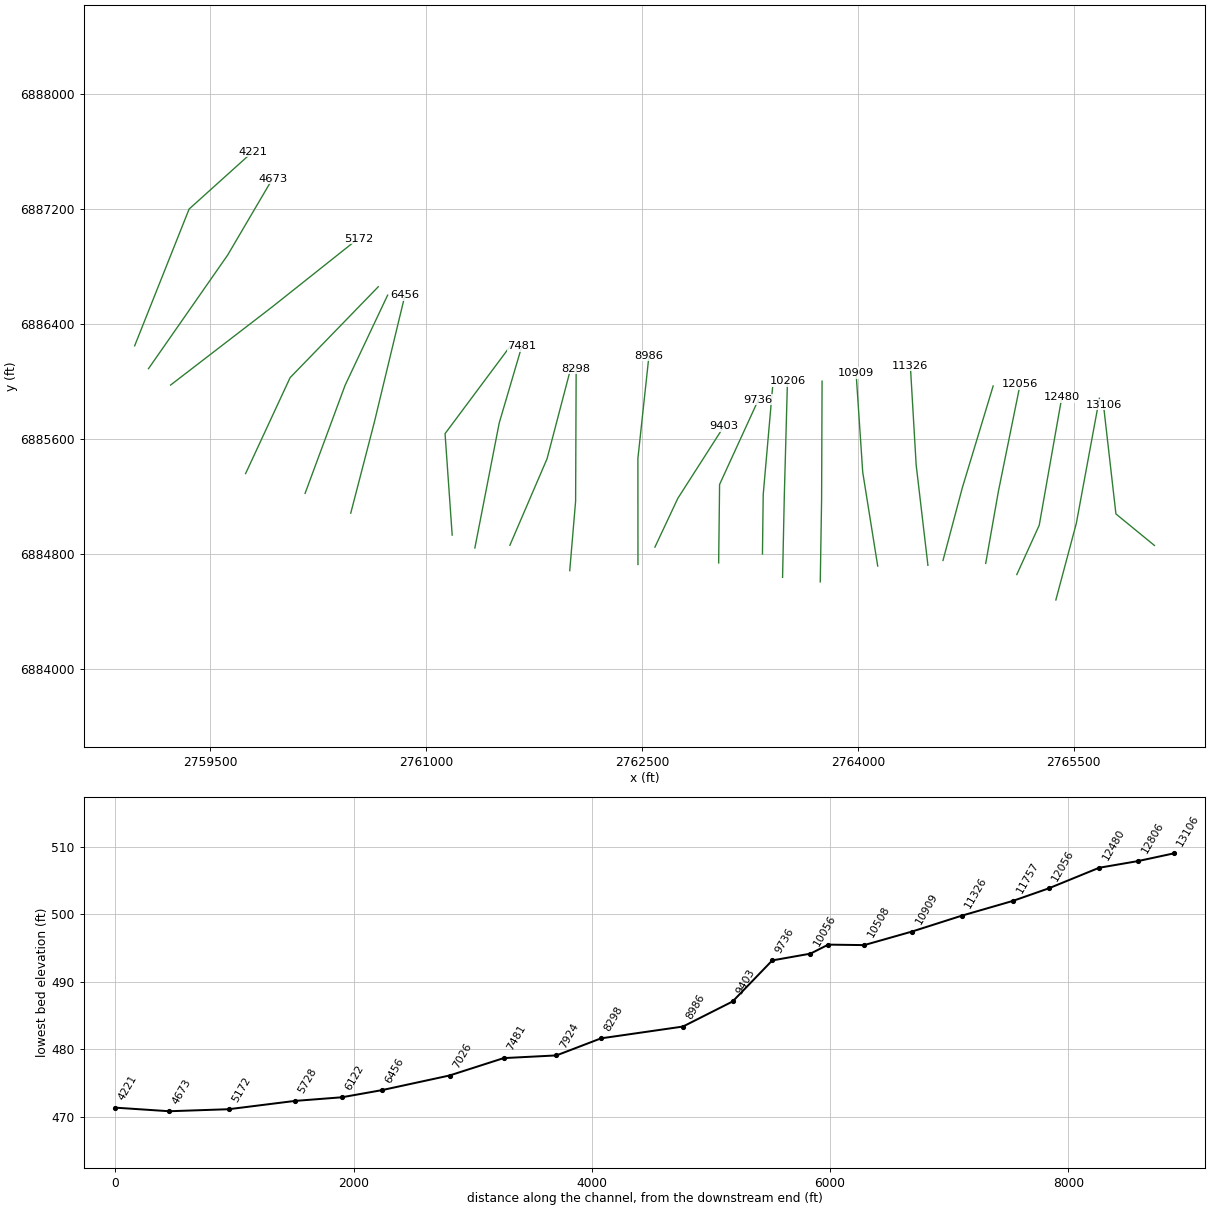
HEC-RAS study Lacy 057.prj: Lacy 057 Base Level Engineering

--- Lacy 057.g01 (geometry) --- (continued)

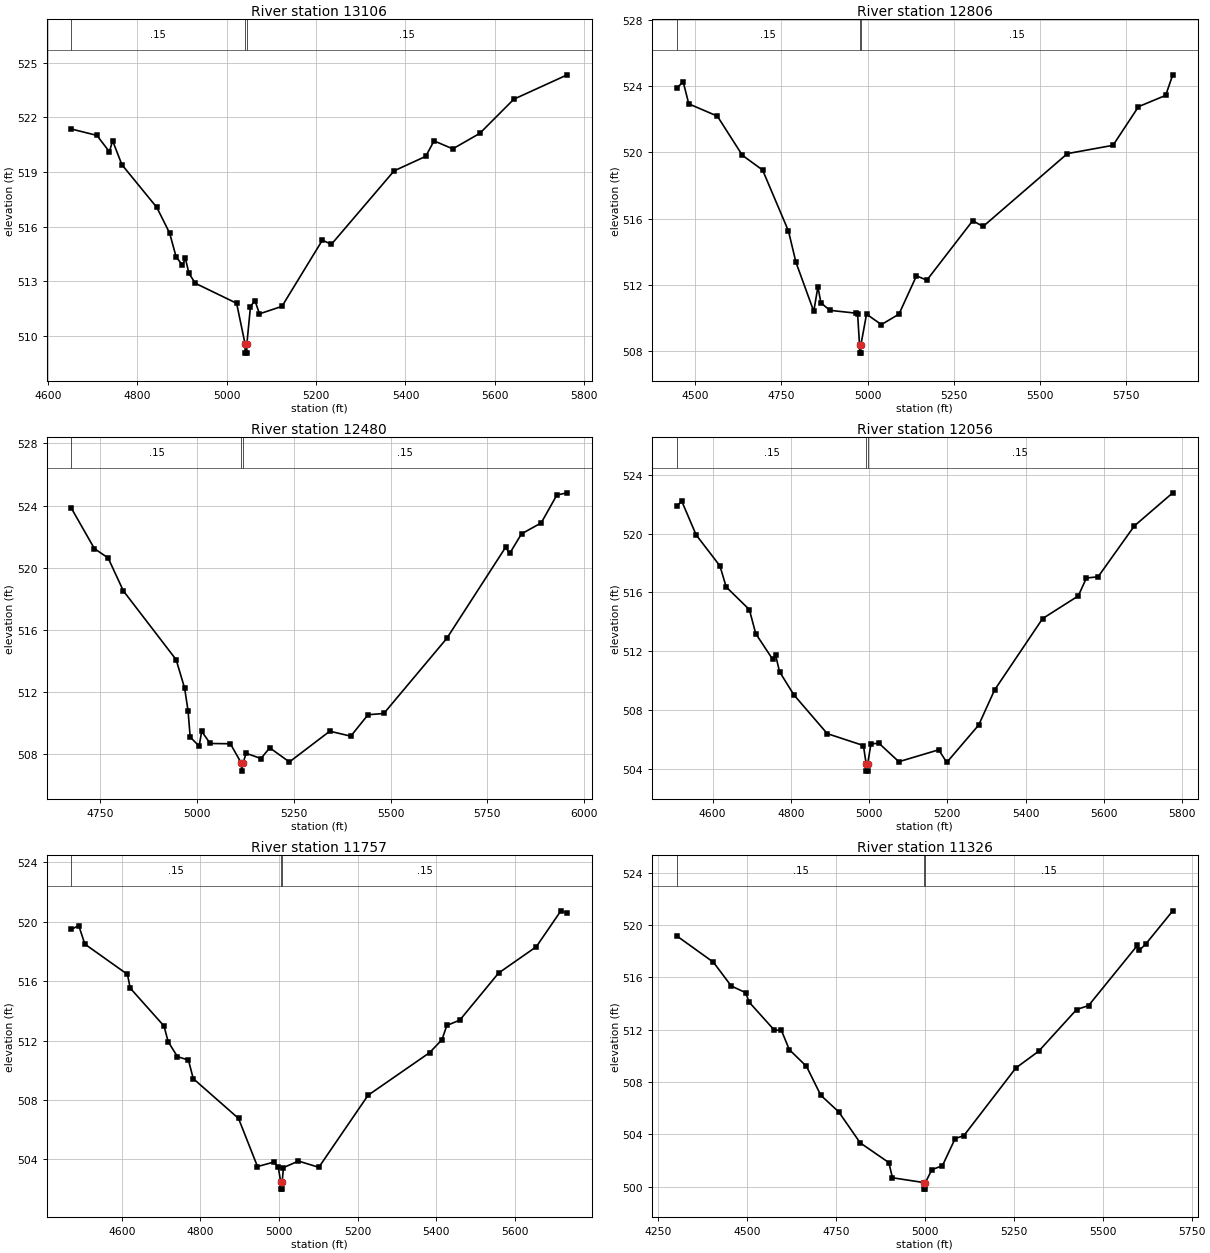
Type RM Length L Ch R = 1 ,13106   ,300,300,300
BEGIN DESCRIPTION:
Lacy 057 2509
END DESCRIPTION:
XS GIS Cut Line= 3
      2766061.76      6884857.23      2765794.19      6885076.59
      2765707.54      6885835.66
#Sta/Elev= 30
  4652.2  521.36  4709.1  521.01  4737.2  520.11  4744.3  520.72  4765.1   519.4
  4843.3  517.05    4872  515.64  4886.4  514.34  4900.8  513.87  4907.2  514.26
  4915.1  513.43  4929.5  512.88    5022  511.78  5040.9  509.54  5041.2  509.04
  5044.7  509.04  5044.9  509.54    5053   511.6    5063  511.93  5073.1   511.2
  5123.4  511.61    5214  515.25  5234.1  515.02  5374.5  519.06  5445.5  519.86
  5463.9  520.71  5505.9  520.27  5566.3  521.12  5642.6     523  5762.2  524.34
#Mann= 3 ,-1 , 0
  4652.2     .15       0  5040.9     .05       0  5044.9     .15       0
Bank Sta=5040.9,5044.9
XS Rating Curve= 0 ,0
Exp/Cntr=0.3,0.1

Type RM Length L Ch R = 1 ,12806   ,326,326,326
BEGIN DESCRIPTION:
Lacy 057 2503
END DESCRIPTION:
XS GIS Cut Line= 3
      2765376.58        6884478.      2765518.96      6885011.42
      2765679.45      6885881.24
#Sta/Elev= 30
  4447.8  523.88  4465.7  524.27    4482  522.93  4564.8  522.19  4637.2  519.83
  4695.9  518.94  4770.9  515.26  4792.5  513.38  4844.2  510.42  4856.2   511.9
  4864.9  510.93  4891.1  510.48  4966.1  510.31  4971.3  510.23  4976.8   508.4
    4977   507.9  4980.5   507.9  4980.8   508.4  4997.1  510.25  5040.1  509.62
    5091  510.25  5141.8  512.56  5171.9   512.3  5304.5  515.88    5335  515.54
  5579.1  519.93  5711.3  520.43  5785.1  522.76  5863.8  523.44  5884.4  524.68
#Mann= 3 ,-1 , 0
  4447.8     .15       0  4976.8     .05       0  4980.8     .15       0
Bank Sta=4976.8,4980.8
XS Rating Curve= 0 ,0
Exp/Cntr=0.3,0.1

Type RM Length L Ch R = 1 ,12480   ,424,424,424
BEGIN DESCRIPTION:
Lacy 057 2505
END DESCRIPTION:
XS GIS Cut Line= 3
      2765105.21       6884654.9      2765261.07      6884998.15
      2765417.89      6885887.35
#Sta/Elev= 30
  4676.3  523.82  4735.5  521.23  4770.9  520.63  4810.3  518.51  4946.6  514.08
  4968.5  512.24  4977.3  510.79  4982.8   509.1  5005.9  508.52  5012.5  509.47
  5034.4  508.69  5086.6  508.67  5115.1  507.41  5115.3  506.91  5119.1  507.41
  5127.2  508.06  5165.4  507.72  5188.2  508.41  5238.9   507.5  5343.2  509.48
  5397.3  509.16    5442  510.54  5482.7  510.62  5645.1  515.45  5796.9  521.31
  5807.6  520.92  5838.1  522.18  5888.8  522.88  5929.4  524.68  5956.2  524.82
#Mann= 3 ,-1 , 0
  4676.3     .15       0  5115.1     .05       0  5119.1     .15       0
Bank Sta=5115.1,5119.1
XS Rating Curve= 0 ,0
Exp/Cntr=0.3,0.1

Type RM Length L Ch R = 1 ,12056   ,299,299,299
BEGIN DESCRIPTION:
Lacy 057 2504
END DESCRIPTION:
XS GIS Cut Line= 3
      2764889.09      6884732.72       2764976.6      6885230.14
      2765128.11      6885977.28
#Sta/Elev= 30
  4508.9  521.88  4521.2   522.2  4557.9  519.91  4618.8   517.8  4634.7  516.37
    4694  514.83  4710.2   513.2  4753.3  511.46    4761  511.74  4771.1  510.61
  4807.6  509.04    4893   506.4  4985.5  505.59  4992.5  504.35  4992.8  503.85
  4996.3  503.85  4996.5  504.35  5004.7   505.7    5025  505.75  5076.1  504.49
  5178.1   505.3  5198.5  504.44  5280.1  506.98  5320.9  509.37  5443.6  514.22
  5534.7  515.76  5555.6  516.98  5585.4  517.06  5678.1  520.52  5776.3  522.77
#Mann= 3 ,-1 , 0
  4508.9     .15       0  4992.5     .05       0  4996.5     .15       0
Bank Sta=4992.5,4996.5
XS Rating Curve= 0 ,0
Exp/Cntr=0.3,0.1

Type RM Length L Ch R = 1 ,11757   ,431,431,431
BEGIN DESCRIPTION:
Lacy 057 2501
END DESCRIPTION:
XS GIS Cut Line= 3
      2764592.21      6884753.08      2764726.49      6885258.62
      2764940.72      6885966.55
#Sta/Elev= 30
  4471.4  519.49  4489.9  519.75  4505.5   518.5  4614.1  516.46  4620.9  515.54
  4707.2  512.98  4717.6  511.93  4741.4  510.92  4769.3  510.69  4781.6  509.44
  4896.9  506.76  4945.2  503.52  4986.6  503.82  4998.3  503.47  5004.1   502.5
  5004.4     502  5007.9     502  5008.1   502.5  5011.3  503.45  5049.5  503.89
  5101.4  503.47  5226.8  508.32  5383.5  511.19  5414.9  512.06  5427.4  513.02
  5460.4  513.38  5559.2  516.55  5655.2  518.32  5717.9  520.74  5734.1  520.58
#Mann= 3 ,-1 , 0
  4471.4     .15       0  5004.1     .05       0  5008.1     .15       0
Bank Sta=5004.1,5008.1
XS Rating Curve= 0 ,0
Exp/Cntr=0.3,0.1

Type RM Length L Ch R = 1 ,11326   ,417,417,417
BEGIN DESCRIPTION:
Lacy 057 2502
END DESCRIPTION:
XS GIS Cut Line= 3
      2764487.41      6884719.32       2764405.7      6885416.99
      2764365.29      6886107.37
#Sta/Elev= 30
  4302.9  519.16  4405.3  517.16  4455.6  515.34  4495.9  514.83    4506   514.1
  4576.4  511.97  4596.6  511.94  4618.8  510.47  4667.1  509.19  4707.3  506.98
  4757.7  505.71  4818.1  503.34  4898.6  501.83  4908.7  500.67  4997.3   500.3
  4997.6   499.8  5001.1   499.8  5001.3   500.3  5019.4  501.28  5049.4   501.6
  5085.1  503.67  5109.5  503.89  5255.8  509.07  5319.9  510.35  5426.6  513.54
  5460.1  513.84  5597.3  518.44  5602.3  518.06  5620.4  518.53  5696.9  521.09
#Mann= 3 ,-1 , 0
  4302.9     .15       0  4997.3     .05       0  5001.3     .15       0
Bank Sta=4997.3,5001.3
XS Rating Curve= 0 ,0
Exp/Cntr=0.3,0.1

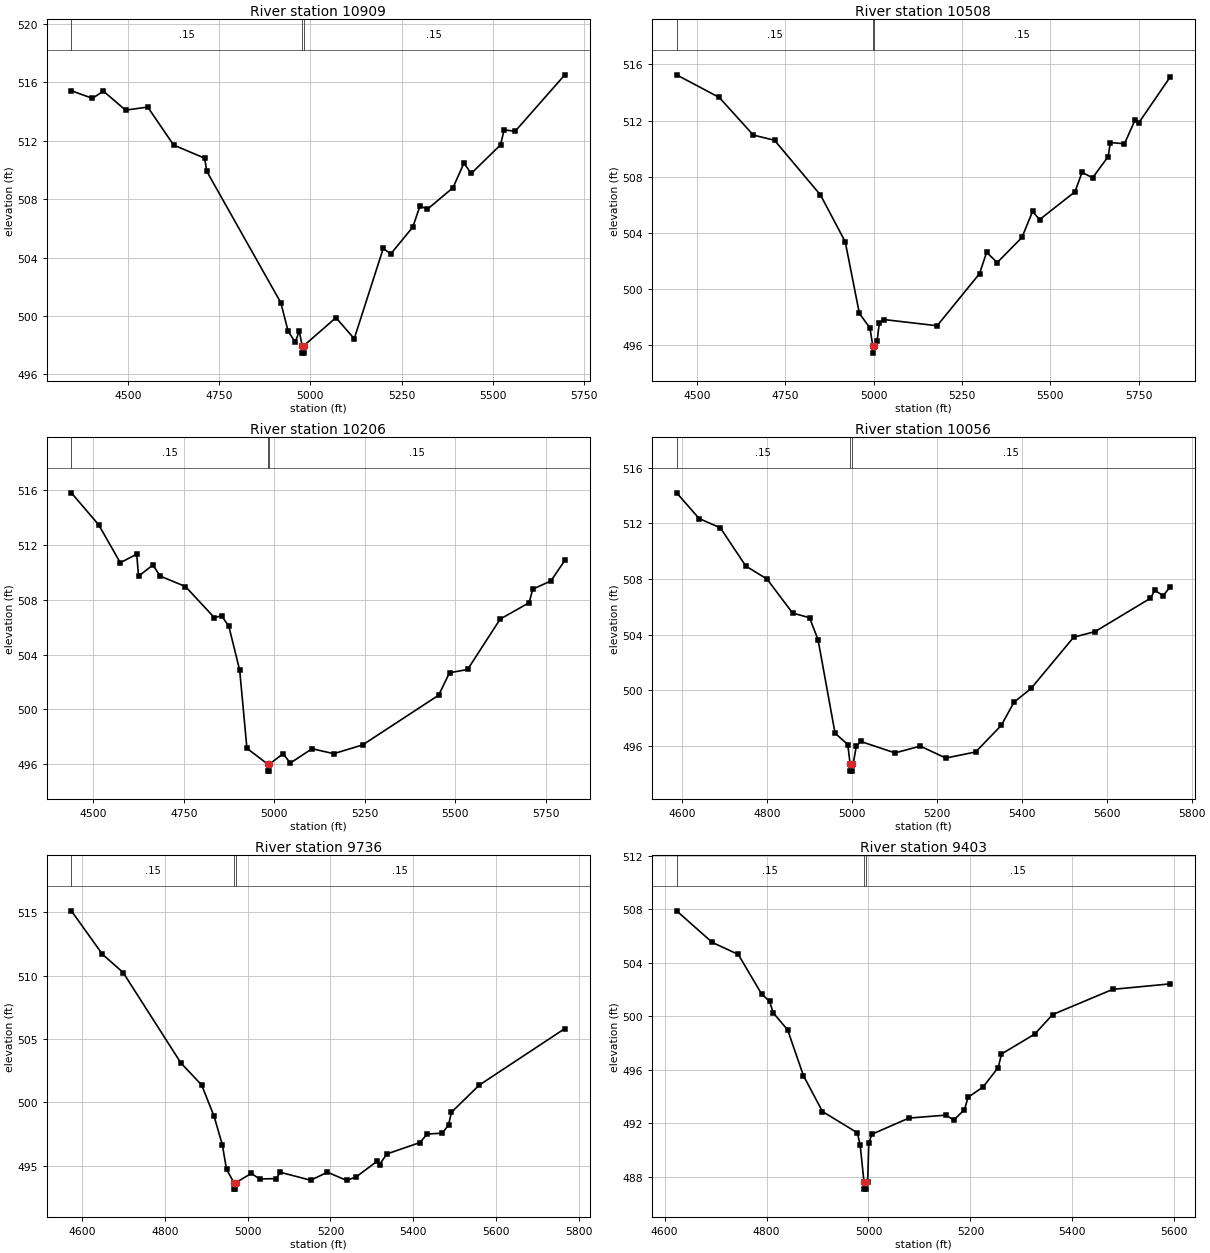
Type RM Length L Ch R = 1 ,10909   ,401,401,401
BEGIN DESCRIPTION:
Lacy 057 2500
END DESCRIPTION:
XS GIS Cut Line= 3
      2764138.35      6884714.22       2764034.3      6885366.29
      2763988.02      6886056.92
#Sta/Elev= 30
    4345  515.43  4402.5  514.91  4432.9   515.4  4493.6   514.1  4554.4  514.31
  4625.3  511.71  4710.2  510.81  4716.4   509.9    4919  500.91  4939.2  498.95
  4958.6   498.2  4969.6  498.96  4977.7  497.95    4978  497.45  4981.5  497.45
  4981.7  497.95  5070.2  499.88  5120.3  498.44  5199.8  504.62  5220.5  504.25
  5280.6  506.08  5300.7  507.54  5320.7  507.31  5390.9  508.78    5421  510.47
    5441  509.76  5521.2  511.72  5531.2  512.75  5561.3  512.65  5697.5  516.52
#Mann= 3 ,-1 , 0
    4345     .15       0  4977.7     .05       0  4981.7     .15       0
Bank Sta=4977.7,4981.7
XS Rating Curve= 0 ,0
Exp/Cntr=0.3,0.1

Type RM Length L Ch R = 1 ,10508   ,302,302,302
BEGIN DESCRIPTION:
Lacy 057 2499
END DESCRIPTION:
XS GIS Cut Line= 3
      2763739.06      6884603.99      2763748.41      6885179.16
      2763751.71      6886000.11
#Sta/Elev= 30
  4442.7  515.26  4563.3  513.65  4659.7  510.97  4719.7   510.6  4849.8   506.7
  4919.8  503.37  4959.8  498.27  4989.8  497.23  4997.8  495.94    4998  495.44
  5001.8  495.94  5009.8   496.3  5016.4   497.6  5029.8  497.83  5179.8  497.39
  5299.8   501.1  5319.8  502.62  5349.8  501.89  5419.8  503.68  5449.8  505.53
  5469.8  504.95  5569.8  506.93  5589.8  508.31  5619.8  507.93  5663.8  509.44
  5669.8  510.44  5709.8  510.35  5739.8  512.04  5749.8  511.82  5838.9   515.1
#Mann= 3 ,-1 , 0
  4442.7     .15       0  4997.8     .05       0  5001.8     .15       0
Bank Sta=4997.8,5001.8
XS Rating Curve= 0 ,0
Exp/Cntr=0.3,0.1

Type RM Length L Ch R = 1 ,10206   ,150,150,150
BEGIN DESCRIPTION:
Lacy 057 2498
END DESCRIPTION:
XS GIS Cut Line= 3
      2763477.13       6884635.6      2763489.41      6885210.89
      2763511.04      6885999.67
#Sta/Elev= 30
  4438.8  515.77  4514.2  513.45  4574.2  510.68  4619.6  511.31  4624.6   509.7
  4664.3  510.52  4684.3  509.71  4754.3  508.95  4834.3  506.68  4854.3  506.82
  4874.3  506.05  4904.3  502.85  4924.3  497.17  4982.3  496.01  4982.6  495.51
  4986.1  495.51  4986.3  496.01  5024.3  496.78  5044.3   496.1  5104.4  497.14
  5164.4  496.78  5244.4  497.42  5454.5  501.04  5484.5  502.67  5534.5  502.91
  5624.6  506.58  5704.6  507.77  5714.6  508.76  5764.6  509.35  5803.3  510.85
#Mann= 3 ,-1 , 0
  4438.8     .15       0  4982.3     .05       0  4986.3     .15       0
Bank Sta=4982.3,4986.3
XS Rating Curve= 0 ,0
Exp/Cntr=0.3,0.1

Type RM Length L Ch R = 1 ,10056   ,320,320,320
BEGIN DESCRIPTION:
Lacy 057 2462
END DESCRIPTION:
XS GIS Cut Line= 3
       2763337.3      6884797.98      2763342.55      6885211.15
      2763407.73       6885957.1
#Sta/Elev= 30
  4587.2   514.2  4640.2  512.35  4690.2  511.68  4750.2  508.93  4800.2  507.99
  4860.2  505.55  4900.2  505.21  4920.2  503.64  4960.3   496.9  4990.3  496.08
  4995.8  494.67  4996.1  494.17  4999.6  494.17  4999.8  494.67  5002.8  494.67
  5010.3  495.95  5020.3  496.31  5101.6  495.48  5160.9  495.97  5221.1  495.11
  5291.4  495.55  5351.6  497.46  5381.7  499.13  5421.9  500.12  5522.2  503.81
  5572.4  504.21  5702.9  506.61    5713  507.18    5733   506.8  5749.2  507.42
#Mann= 3 ,-1 , 0
  4587.2     .15       0  4995.8     .05       0  4999.8     .15       0
Bank Sta=4995.8,4999.8
XS Rating Curve= 0 ,0
Exp/Cntr=0.3,0.1

Type RM Length L Ch R = 1 ,9736    ,333,333,333
BEGIN DESCRIPTION:
Lacy 057 2463
END DESCRIPTION:
XS GIS Cut Line= 3
      2763032.92      6884735.95      2763039.33      6885281.64
      2763308.78      6885870.17
#Sta/Elev= 30
  4573.5   515.1  4648.6  511.68  4698.6  510.24  4838.6   503.1  4888.6  501.37
  4918.6  498.91  4938.6  496.65  4948.6  494.74  4966.6  493.67  4966.8  493.17
  4970.3  493.17  4970.6  493.67  5008.6  494.41  5028.6  493.97  5068.6     494
  5078.6   494.5  5152.1  493.87  5192.7   494.5  5238.7  493.86  5261.5  494.12
  5313.2  495.38  5318.7  495.11  5336.2  495.94  5416.2  496.84  5433.7  497.51
  5470.5  497.58  5485.3  498.23  5492.5  499.23  5559.8  501.37  5766.5  505.82
#Mann= 3 ,-1 , 0
  4573.5     .15       0  4966.6     .05       0  4970.6     .15       0
Bank Sta=4966.6,4970.6
XS Rating Curve= 0 ,0
Exp/Cntr=0.3,0.1

Type RM Length L Ch R = 1 ,9403    ,417,417,417
BEGIN DESCRIPTION:
Lacy 057 2461
END DESCRIPTION:
XS GIS Cut Line= 3
      2762589.86       6884845.8      2762749.18      6885185.15
      2763069.02      6885684.99
#Sta/Elev= 30
  4623.5  507.88  4693.4  505.52  4744.5  504.62  4790.2  501.67    4806  501.11
    4813  500.26  4841.3  498.99  4872.3  495.57  4909.7  492.88  4978.2  491.29
  4983.7  490.36  4991.3  487.58  4991.6  487.08  4995.1  487.08  4995.3  487.58
  4998.4  487.58  5000.6   490.5  5006.5  491.18  5079.2  492.39    5152  492.61
  5167.2  492.25  5188.3  493.01  5195.3  493.94  5224.7  494.71  5254.6  496.17
    5261  497.18  5325.9  498.66  5361.5  500.13  5479.2  502.01  5591.8  502.42
#Mann= 3 ,-1 , 0
  4623.5     .15       0  4991.3     .05       0  4995.3     .15       0
Bank Sta=4991.3,4995.3
XS Rating Curve= 0 ,0
Exp/Cntr=0.3,0.1

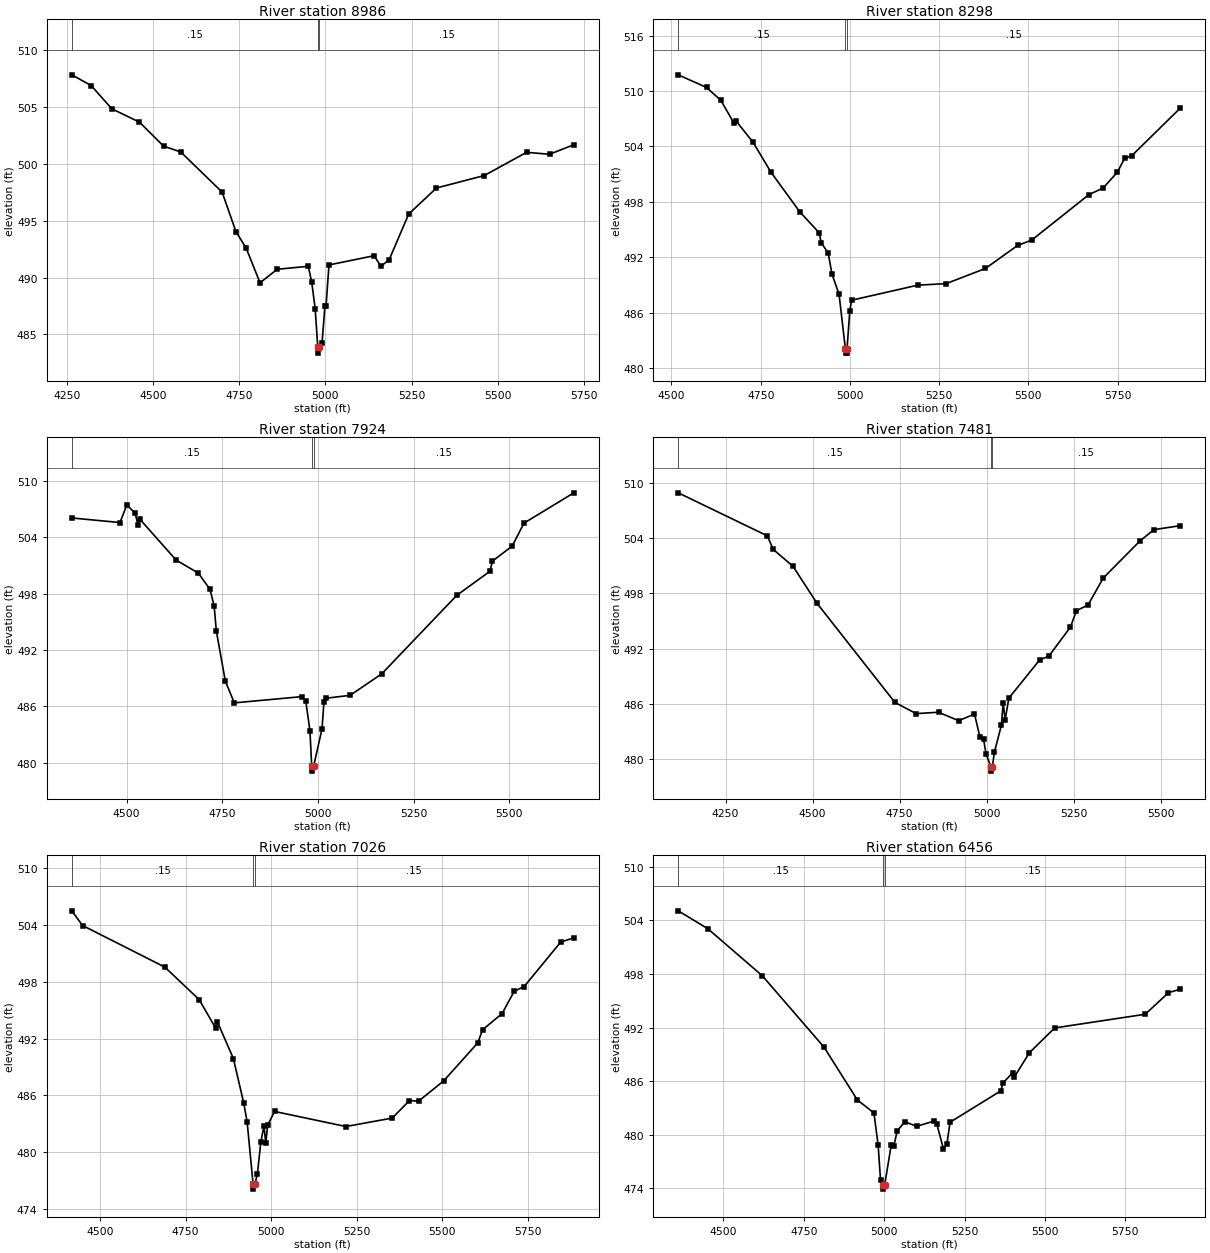
Type RM Length L Ch R = 1 ,8986    ,688,688,688
BEGIN DESCRIPTION:
Lacy 057 2458
END DESCRIPTION:
XS GIS Cut Line= 3
      2762472.01      6884724.82      2762471.52      6885462.54
      2762548.42      6886177.39
#Sta/Elev= 30
  4264.3  507.85  4320.5  506.91  4380.5  504.86  4460.5  503.69  4530.5  501.58
  4580.5  501.06  4700.5  497.53  4740.5  494.06  4770.5  492.58  4810.5  489.55
  4860.5  490.74  4950.5     491  4960.5  489.59  4970.5  487.28  4978.1  483.86
  4978.6  483.36  4982.8  483.86  4990.5  484.29  4998.8  487.47    5002  487.47
  5010.5  491.12  5141.3  491.93  5161.4     491  5185.3  491.59  5241.9   495.6
  5322.3  497.89  5461.4  498.99  5583.8  501.03  5650.4  500.86    5721   501.7
#Mann= 3 ,-1 , 0
  4264.3     .15       0  4978.1     .05       0  4982.8     .15       0
Bank Sta=4978.1,4982.8
XS Rating Curve= 0 ,0
Exp/Cntr=0.3,0.1

Type RM Length L Ch R = 1 ,8298    ,374,374,374
BEGIN DESCRIPTION:
Lacy 057 2459
END DESCRIPTION:
XS GIS Cut Line= 3
       2761997.7      6884681.98      2762038.65      6885166.17
      2762042.44      6886087.24
#Sta/Elev= 30
  4518.9  511.76  4598.2  510.39  4638.3     509  4675.1  506.52  4680.1   506.8
  4728.7  504.45  4778.8  501.21  4859.1  496.94  4914.2  494.63  4919.3  493.59
  4939.4  492.43  4949.5  490.19  4969.5  488.01  4987.2  482.11  4987.7  481.61
  4991.4  481.61    4992  482.11  4999.6  486.16  5004.7  487.34  5189.6  488.97
  5269.7  489.14  5379.7  490.78  5469.7  493.27  5509.7  493.86  5669.7  498.78
  5709.7   499.5  5749.7  501.22  5769.7  502.71  5789.7  502.99  5925.9  508.16
#Mann= 3 ,-1 , 0
  4518.9     .15       0  4987.2     .05       0    4992     .15       0
Bank Sta=4987.2,4992
XS Rating Curve= 0 ,0
Exp/Cntr=0.3,0.1

Type RM Length L Ch R = 1 ,7924    ,443,443,443
BEGIN DESCRIPTION:
Lacy 057 2460
END DESCRIPTION:
XS GIS Cut Line= 3
      2761581.85      6884858.86      2761839.99      6885460.04
      2762006.75      6886097.01
#Sta/Elev= 30
  4356.5  506.08  4482.5  505.59  4500.3  507.45  4522.1  506.61  4529.6  505.33
  4535.1  505.92  4629.3  501.59  4687.3   500.2    4718  498.46  4728.8  496.68
  4734.4  494.04    4758  488.67  4781.5  486.36  4957.3  487.02  4968.3  486.57
  4979.2  483.38  4983.9  479.58  4984.4  479.08  4988.7  479.58  5010.8  483.59
  5015.8  486.42  5022.1  486.86  5084.1  487.16  5166.8  489.45  5363.2  497.83
  5450.1   500.4  5456.2  501.48  5507.9  503.07  5538.9  505.53  5669.2  508.76
#Mann= 3 ,-1 , 0
  4356.5     .15       0  4983.9     .05       0  4988.7     .15       0
Bank Sta=4983.9,4988.7
XS Rating Curve= 0 ,0
Exp/Cntr=0.3,0.1

Type RM Length L Ch R = 1 ,7481    ,455,455,455
BEGIN DESCRIPTION:
Lacy 057 2443
END DESCRIPTION:
XS GIS Cut Line= 3
       2761338.4       6884839.9       2761507.8      6885709.94
       2761664.9      6886243.72
#Sta/Elev= 30
  4113.9  508.93  4369.7  504.26  4387.1  502.77  4443.8  500.94  4512.3  496.94
  4736.5  486.15  4797.6  484.93  4861.9  485.08  4919.9  484.16  4965.2  484.89
    4981  482.38  4991.2  482.18  4998.3  480.58  5011.9  479.18  5012.5  478.68
  5016.8  479.18  5022.2  480.71  5042.4  483.65  5047.7  486.06  5053.5  484.27
  5063.9  486.61  5152.9  490.79  5178.6  491.16  5241.1  494.34  5258.2  496.12
  5291.5  496.74  5335.3  499.67  5440.5  503.69  5480.9  504.93  5556.7  505.36
#Mann= 3 ,-1 , 0
  4113.9     .15       0  5011.9     .05       0  5016.8     .15       0
Bank Sta=5011.9,5016.8
XS Rating Curve= 0 ,0
Exp/Cntr=0.3,0.1

Type RM Length L Ch R = 1 ,7026    ,570,570,570
BEGIN DESCRIPTION:
Lacy 057 2444
END DESCRIPTION:
XS GIS Cut Line= 3
      2761180.68      6884929.52      2761131.13      6885634.91
      2761585.64      6886245.24
#Sta/Elev= 30
  4417.4  505.48    4449  503.93  4689.5  499.54  4789.8  496.11  4837.9  493.11
  4842.9  493.79    4890  489.88  4920.1  485.21  4930.1  483.22  4947.7   476.6
  4948.3   476.1  4952.6   476.6  4960.2  477.71  4970.2  481.08  4979.5   482.8
  4984.5  480.95  4990.3  482.86  5010.3   484.3    5219  482.71  5354.5   483.6
  5404.6  485.44  5431.6  485.39  5504.7  487.52  5604.8  491.55  5618.4  492.92
  5675.7  494.63  5711.1  496.99  5740.3  497.49  5846.6  502.16  5885.5  502.64
#Mann= 3 ,-1 , 0
  4417.4     .15       0  4947.7     .05       0  4952.6     .15       0
Bank Sta=4947.7,4952.6
XS Rating Curve= 0 ,0
Exp/Cntr=0.3,0.1

Type RM Length L Ch R = 1 ,6456    ,334,334,334
BEGIN DESCRIPTION:
Lacy 057 2442
END DESCRIPTION:
XS GIS Cut Line= 3
      2760475.66        6885082.      2760639.21      6885712.92
      2760852.06      6886596.99
#Sta/Elev= 30
  4359.8  505.08  4451.7  503.08  4621.2  497.81  4813.3  489.81  4916.6  483.91
  4968.3  482.45  4981.3  478.87  4988.9   474.9  4996.8  474.42  4997.4  473.92
  5001.8  474.42  5022.1  478.87  5030.2  478.74  5040.5  480.42  5064.1  481.47
  5100.8  480.95  5153.6  481.52  5163.9   481.2  5184.5  478.41    5195  478.93
    5205  481.41  5362.7  484.92  5369.6  485.82  5399.5  486.93  5404.7  486.47
  5451.9   489.2  5530.4  491.97  5811.9   493.5  5883.9  495.91  5920.9  496.31
#Mann= 3 ,-1 , 0
  4359.8     .15       0  4996.8     .05       0  5001.8     .15       0
Bank Sta=4996.8,5001.8
XS Rating Curve= 0 ,0
Exp/Cntr=0.3,0.1

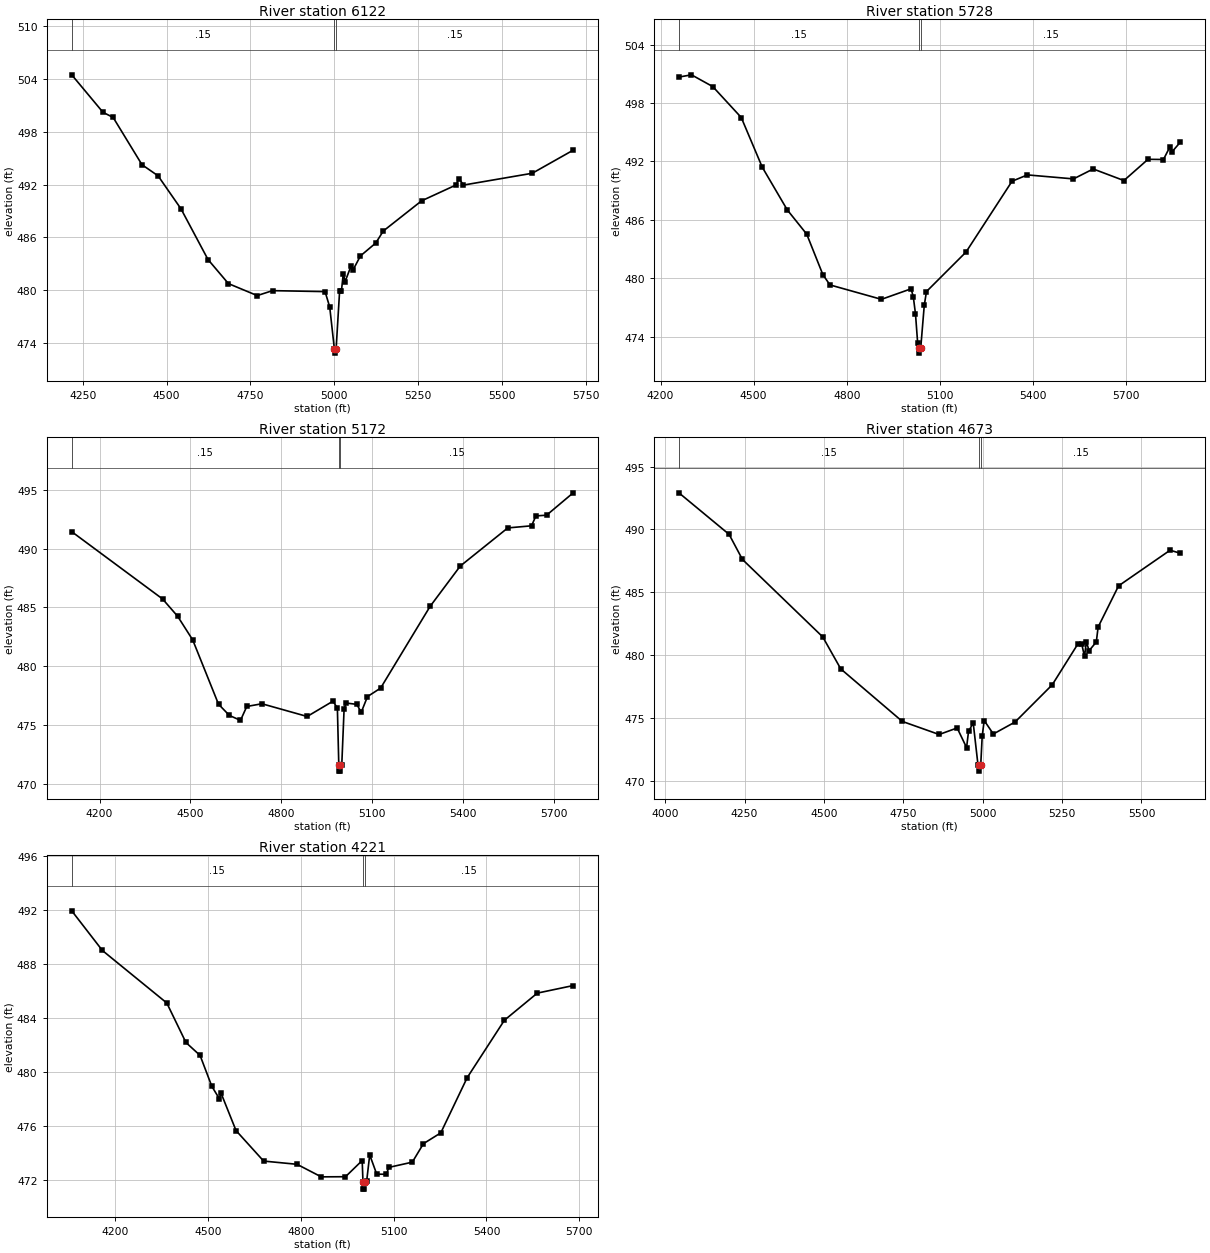
Type RM Length L Ch R = 1 ,6122    ,394,394,394
BEGIN DESCRIPTION:
Lacy 057 2441
END DESCRIPTION:
XS GIS Cut Line= 3
      2760158.33      6885219.72       2760436.3      6885971.19
      2760731.99      6886598.46
#Sta/Elev= 30
  4217.5  504.45  4310.6   500.2    4341  499.61  4426.9  494.25  4474.8  492.99
  4543.2  489.24  4623.7  483.49  4684.5  480.76  4770.4   479.4    4816  479.96
  4972.6  479.85  4986.5   478.1  5000.3  473.37  5001.1  472.87  5005.6  473.37
    5016  479.93  5021.4  479.93  5026.9  481.88  5032.4  480.99  5049.7  482.72
  5055.2  482.25    5078   483.9  5123.6  485.36  5146.3  486.73  5260.3  490.15
  5362.4  491.94  5372.3  492.66  5385.2  491.94  5590.2  493.28  5712.2   495.9
#Mann= 3 ,-1 , 0
  4217.5     .15       0  5000.3     .05       0  5005.6     .15       0
Bank Sta=5000.3,5005.6
XS Rating Curve= 0 ,0
Exp/Cntr=0.3,0.1

Type RM Length L Ch R = 1 ,5728    ,556,556,556
BEGIN DESCRIPTION:
Lacy 057 2424
END DESCRIPTION:
XS GIS Cut Line= 3
      2759744.83      6885357.23      2760054.19      6886024.59
       2760667.2      6886656.97
#Sta/Elev= 30
    4259  500.66  4299.6  500.89  4368.3  499.68    4460  496.51  4527.7  491.41
  4608.5  487.02    4671  484.54    4723  480.39  4745.9  479.33  4911.8  477.85
  5007.4  478.93  5014.6   478.1  5021.6  476.35  5028.7  473.32    5033  472.83
  5033.8  472.33  5038.4  472.83  5049.9  477.24    5057  478.65  5184.4   482.7
  5332.8  489.97  5382.2  490.62  5530.9  490.21  5594.4  491.23  5693.4  490.04
  5771.1  492.22  5820.8   492.2  5841.9  493.51  5849.1  493.01  5875.3  493.98
#Mann= 3 ,-1 , 0
    4259     .15       0    5033     .05       0  5038.4     .15       0
Bank Sta=5033,5038.4
XS Rating Curve= 0 ,0
Exp/Cntr=0.3,0.1

Type RM Length L Ch R = 1 ,5172    ,499,499,499
BEGIN DESCRIPTION:
Lacy 057 2423
END DESCRIPTION:
XS GIS Cut Line= 3
      2759223.65      6885973.14      2759927.77      6886515.07
      2760527.83      6886992.12
#Sta/Elev= 30
  4108.1  491.43  4407.8  485.72  4457.6  484.25  4507.4  482.24  4592.6  476.78
  4628.4  475.83  4665.1  475.41  4685.9  476.59  4735.8  476.82  4885.2  475.74
  4970.4  477.04  4984.9  476.45  4989.6   471.6  4990.4   471.1  4994.3   471.1
    4995   471.6  4999.4  471.63  5007.1   476.4  5013.9  476.88  5049.1  476.77
  5063.5  476.09  5084.3  477.43  5127.6  478.15    5291  485.09  5390.4  488.51
  5547.3  491.75  5625.8  491.93  5640.2  492.77  5675.4  492.83  5763.2  494.73
#Mann= 3 ,-1 , 0
  4108.1     .15       0  4989.6     .05       0    4995     .15       0
Bank Sta=4989.6,4995
XS Rating Curve= 0 ,0
Exp/Cntr=0.3,0.1

Type RM Length L Ch R = 1 ,4673    ,452,452,452
BEGIN DESCRIPTION:
Lacy 057 2422
END DESCRIPTION:
XS GIS Cut Line= 3
      2759069.98       6886087.2      2759619.65      6886876.41
      2759932.33      6887408.82
#Sta/Elev= 30
  4043.3  492.91  4201.4  489.61  4243.3  487.62  4496.4  481.46  4553.1  478.92
  4746.8  474.75  4862.9  473.71  4919.6  474.23  4949.3  472.67  4955.4  473.95
  4970.2  474.63  4985.1  471.32  4988.4   471.3  4989.2   470.8  4993.9   471.3
  4998.5  473.59  5004.8  474.82  5033.6  473.75  5101.9   474.7  5219.1  477.66
  5299.2  480.88  5311.9   480.9  5320.7  479.91  5326.5  481.07  5335.1  480.37
  5357.8  481.06  5363.6  482.25    5428  485.52  5590.2  488.35  5622.5  488.11
#Mann= 3 ,-1 , 0
  4043.3     .15       0  4988.4     .05       0  4993.9     .15       0
Bank Sta=4988.4,4993.9
XS Rating Curve= 0 ,0
Exp/Cntr=0.3,0.1

Type RM Length L Ch R = 1 ,4221    ,473,473,473
BEGIN DESCRIPTION:
Lacy 057 2421
END DESCRIPTION:
XS GIS Cut Line= 3
      2758973.66      6886245.88      2759352.15      6887197.18
      2759794.49      6887595.98
#Sta/Elev= 30
  4060.6  491.96  4159.6  489.02  4367.5  485.13  4429.4   482.2  4475.1  481.24
    4513  478.95  4537.3  478.03  4542.7  478.45  4591.2  475.67  4680.3  473.41
  4788.2  473.17  4866.4  472.24  4944.7  472.25  4998.6  473.45  5001.2  471.83
    5002  471.33  5005.9  471.33  5006.7  471.83  5013.2  471.95  5022.9  473.87
  5045.5  472.44  5076.9  472.43  5084.4  472.94  5160.5  473.33  5196.4   474.7
  5252.4   475.5  5337.6  479.59  5457.9  483.85  5564.1  485.86    5680  486.42
#Mann= 3 ,-1 , 0
  4060.6     .15       0  5001.2     .05       0  5006.7     .15       0
Bank Sta=5001.2,5006.7
XS Rating Curve= 0 ,0
Exp/Cntr=0.3,0.1