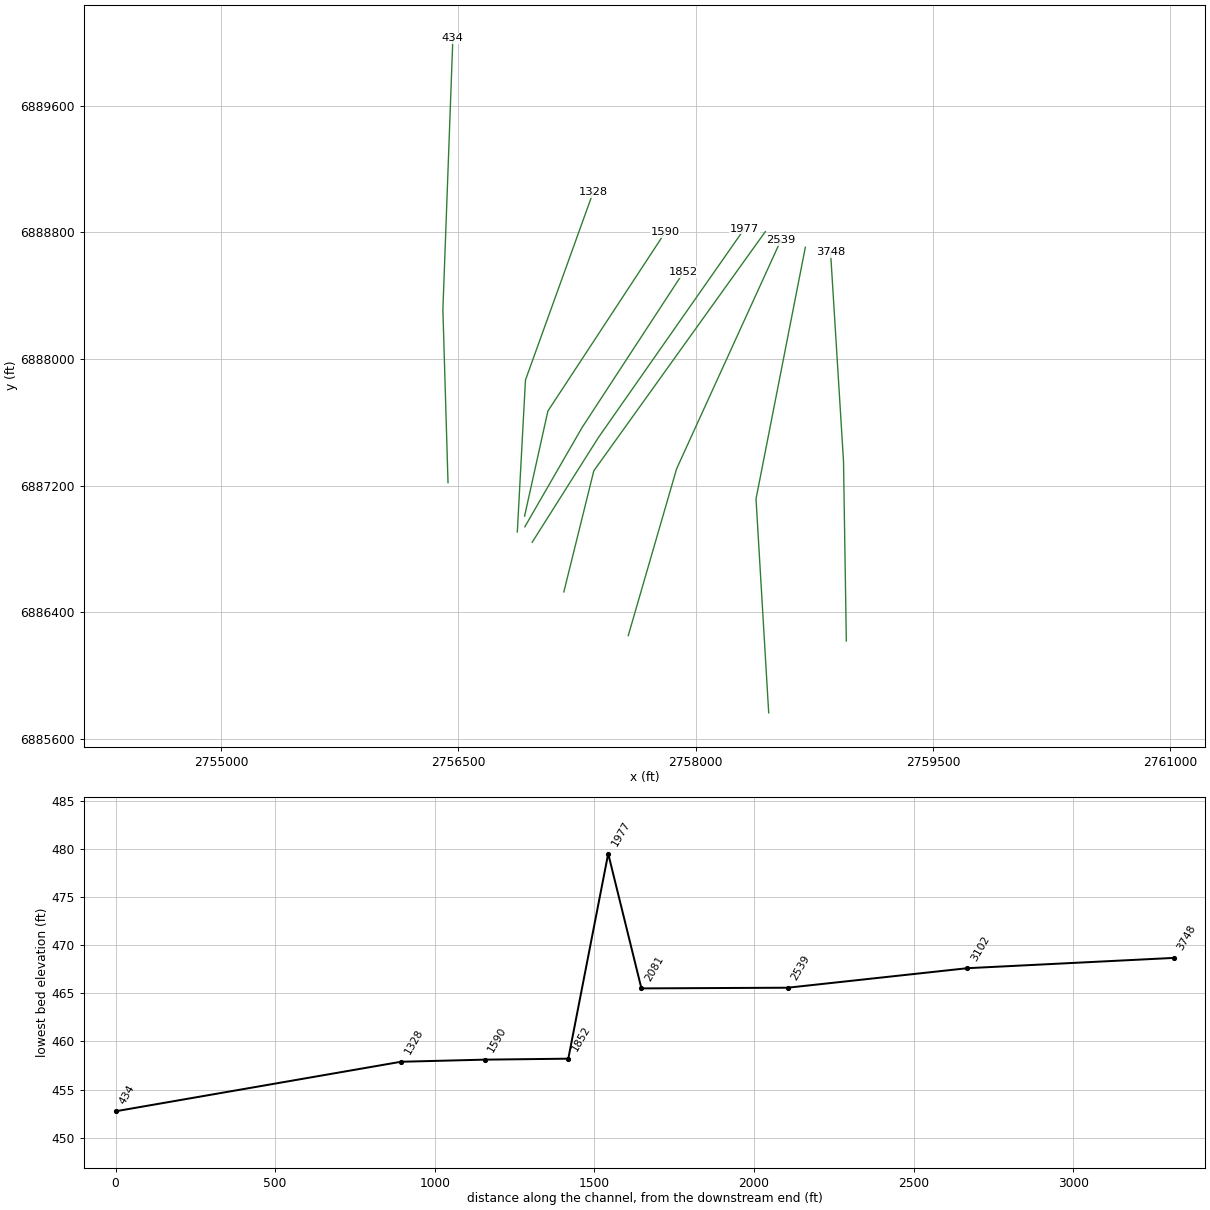
HEC-RAS study Lacy 057.prj: Lacy 057 Base Level Engineering

--- Lacy 057.g01 (geometry) --- (continued)

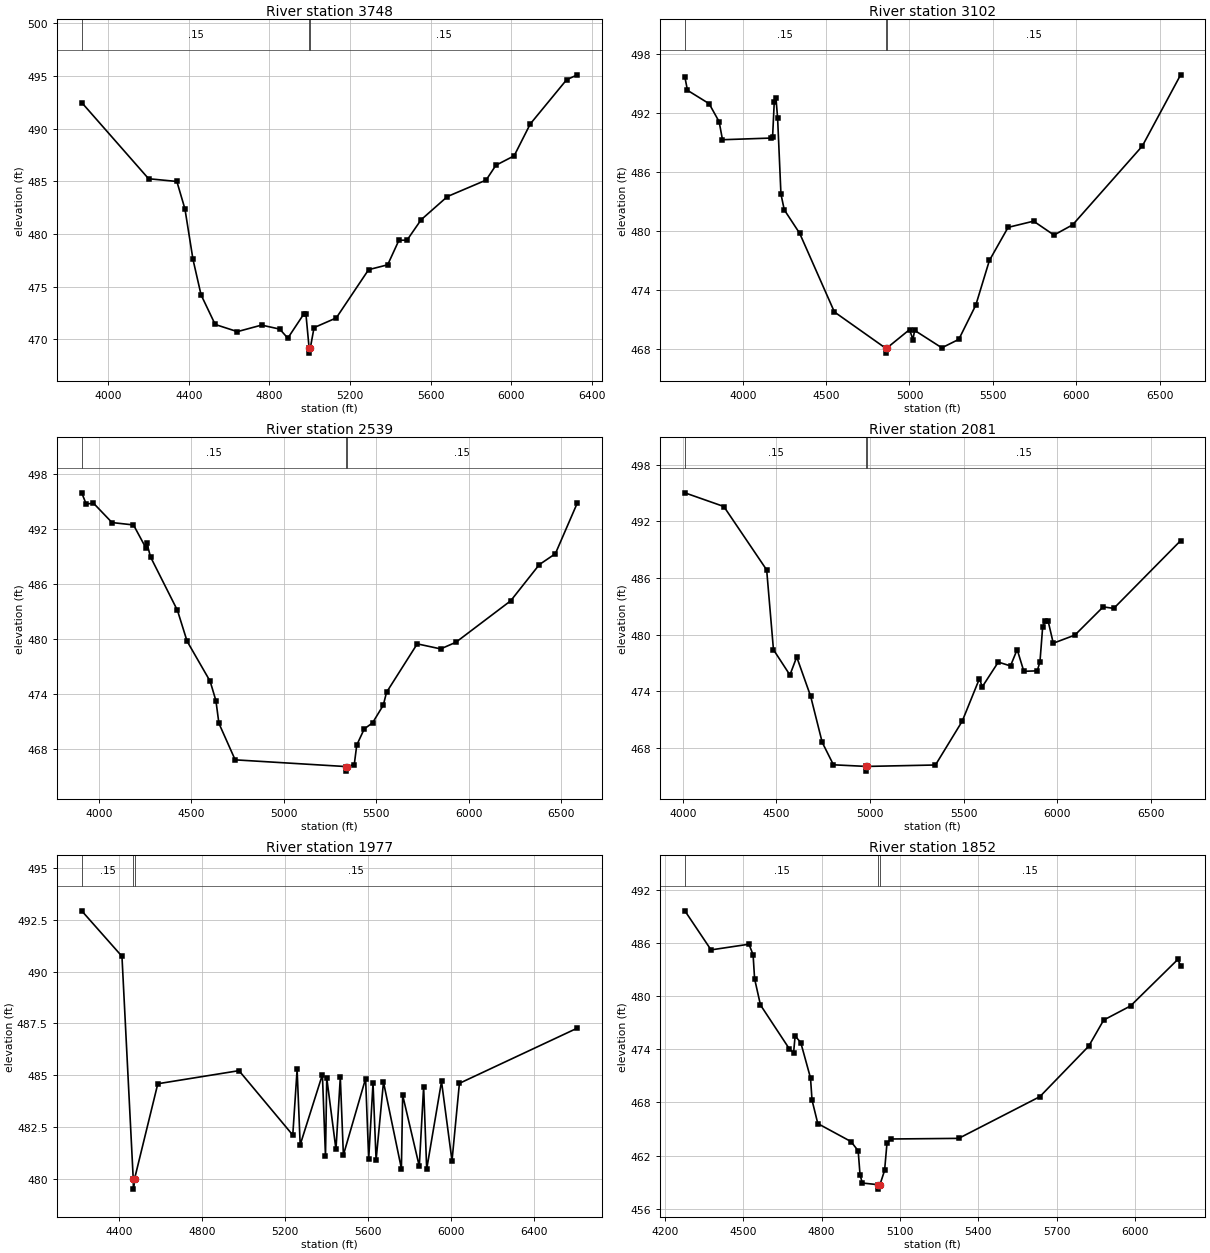
Type RM Length L Ch R = 1 ,3748    ,646,646,646
BEGIN DESCRIPTION:
Lacy 057 2419
END DESCRIPTION:
XS GIS Cut Line= 3
      2758952.31      6886219.39      2758934.64      6887353.24
      2758852.74      6888674.42
#Sta/Elev= 30
  3869.6  492.47  4201.2  485.24  4341.3  484.98  4381.3  482.38  4421.3  477.58
  4461.3  474.22  4531.3  471.41  4641.3  470.73  4761.3  471.35  4851.3  470.97
  4891.3  470.11  4971.3  472.42  4981.3  472.37  4996.9  469.19  4997.9  468.69
  5003.1  469.19  5021.4  471.11  5131.6  472.03  5291.9  476.61  5386.4  477.07
  5442.2   479.4  5482.3  479.41  5552.4  481.35  5682.6  483.55  5874.3  485.11
  5923.1  486.52  6013.3  487.41  6093.4  490.44  6273.8  494.64  6327.3   495.1
#Mann= 3 ,-1 , 0
  3869.6     .15       0  4996.9     .05       0  5003.1     .15       0
Bank Sta=4996.9,5003.1
XS Rating Curve= 0 ,0
Exp/Cntr=0.3,0.1

Type RM Length L Ch R = 1 ,3102    ,563,563,563
BEGIN DESCRIPTION:
Lacy 057 2420
END DESCRIPTION:
XS GIS Cut Line= 3
      2758461.64      6885765.81      2758381.49      6887116.33
      2758693.43      6888706.43
#Sta/Elev= 30
  3652.9  495.66  3668.4  494.31  3798.3  492.95  3858.4  491.12  3878.5  489.29
    4172  489.46    4179  489.57    4189  493.12    4199  493.57  4209.1  491.49
  4229.1  483.77  4249.1  482.17  4341.6  479.78  4549.7   471.8  4857.1  468.12
  4858.2  467.62  4863.3  468.12  5000.5  470.01  5020.7     469  5030.9  469.93
    5194  468.16  5295.9  469.02  5397.8   472.5  5479.3  477.03  5591.4  480.39
  5744.3  481.02  5866.6  479.61  5978.7  480.65  6396.5  488.65  6626.2  495.88
#Mann= 3 ,-1 , 0
  3652.9     .15       0  4857.1     .05       0  4863.3     .15       0
Bank Sta=4857.1,4863.3
XS Rating Curve= 0 ,0
Exp/Cntr=0.3,0.1

Type RM Length L Ch R = 1 ,2539    ,458,458,458
BEGIN DESCRIPTION:
Lacy 057 2418
END DESCRIPTION:
XS GIS Cut Line= 3
      2757573.91      6886253.32      2757879.52      6887306.71
      2758538.45      6888749.87
#Sta/Elev= 30
  3906.1  495.92  3930.6  494.69  3969.4   494.8  4070.1  492.68  4186.4  492.42
  4253.5  489.91  4258.7  490.44  4278.5  488.94  4424.3  483.11  4476.4  479.75
  4601.3  475.38  4632.6  473.26  4648.7   470.8  4736.7  466.82  5334.2  466.09
  5335.2  465.59  5340.7  466.09  5381.4  466.31  5394.8  468.43  5435.4  470.19
  5480.3  470.85  5538.5  472.78    5556  474.18  5722.2  479.46  5848.9  478.91
  5931.1  479.63  6227.9  484.15  6383.1   488.1  6469.7  489.28  6589.4  494.85
#Mann= 3 ,-1 , 0
  3906.1     .15       0  5334.2     .05       0  5340.7     .15       0
Bank Sta=5334.2,5340.7
XS Rating Curve= 0 ,0
Exp/Cntr=0.3,0.1

Type RM Length L Ch R = 1 ,2081    ,104,104,104
BEGIN DESCRIPTION:
Lacy 057 2440
END DESCRIPTION:
XS GIS Cut Line= 3
      2757166.68      6886529.13      2757356.11      6887293.95
       2758440.3      6888804.63
#Sta/Elev= 30
  4011.4  495.02  4219.4  493.57  4448.2  486.85  4484.5  478.39  4572.4  475.71
  4608.7  477.62    4683  473.46  4744.8  468.57  4804.8  466.19  4979.6  466.02
  4980.7  465.52  4986.2  466.02  5349.6  466.17  5492.4  470.81  5584.6  475.33
  5599.3  474.45  5685.2  477.08  5750.3  476.67  5785.9  478.41  5821.5   476.1
  5892.8  476.15  5907.5  477.08  5922.2  480.83    5937  481.46  5951.7  481.39
  5978.7  479.08  6094.1  479.94  6245.2  482.93  6301.7  482.77  6658.8  489.95
#Mann= 3 ,-1 , 0
  4011.4     .15       0  4979.6     .05       0  4986.2     .15       0
Bank Sta=4979.6,4986.2
XS Rating Curve= 0 ,0
Exp/Cntr=0.3,0.1

Type RM Length L Ch R = 1 ,1977    ,125,125,125
BEGIN DESCRIPTION:
Lacy 057 2437
END DESCRIPTION:
XS GIS Cut Line= 3
       2756966.6      6886842.83      2757384.67      6887503.34
      2758307.82      6888822.14
#Sta/Elev= 30
  4218.3  492.92  4412.5  490.73  4466.8  480.03  4467.8  479.53  4473.4  480.03
  4585.4   484.6    4977  485.23  5236.5  482.13  5257.4  485.29  5272.2  481.66
  5379.4  485.04  5394.3   481.1  5400.4  484.88  5444.8  481.44  5465.8  484.91
  5480.6  481.17  5587.8  484.85  5602.7  480.98  5623.6  484.63  5638.4  480.93
  5674.1  484.68  5760.5  480.52  5766.6  484.05  5846.8  480.63  5867.7  484.46
  5882.5  480.49    5954  484.71  6004.6  480.89  6040.3  484.62  6609.8  487.28
#Mann= 3 ,-1 , 0
  4218.3     .15       0  4466.8     .05       0  4473.4     .15       0
Bank Sta=4466.8,4473.4
XS Rating Curve= 0 ,0
Exp/Cntr=0.3,0.1

Type RM Length L Ch R = 1 ,1852    ,262,262,262
BEGIN DESCRIPTION:
Lacy 057 2438
END DESCRIPTION:
XS GIS Cut Line= 3
      2756920.21      6886940.42      2757281.77      6887566.99
      2757924.02      6888549.49
#Sta/Elev= 30
  4276.6  489.63  4376.8  485.22  4521.9  485.86  4537.7  484.67  4543.4  481.96
  4565.9     479    4677  474.02  4692.7  473.62  4698.5   475.5  4720.1  474.76
  4757.4  470.76  4763.2  468.26  4785.3  465.61  4912.3  463.58  4939.8  462.54
  4946.9  459.84  4955.6   458.9  5016.5  458.71  5017.5  458.21  5023.1  458.71
  5040.9  460.32    5050  463.38  5064.5  463.87  5324.5  463.94  5635.1  468.65
  5822.1  474.35  5879.4   477.3    5982  478.89    6163  484.14  6173.8  483.43
#Mann= 3 ,-1 , 0
  4276.6     .15       0  5016.5     .05       0  5023.1     .15       0
Bank Sta=5016.5,5023.1
XS Rating Curve= 0 ,0
Exp/Cntr=0.3,0.1

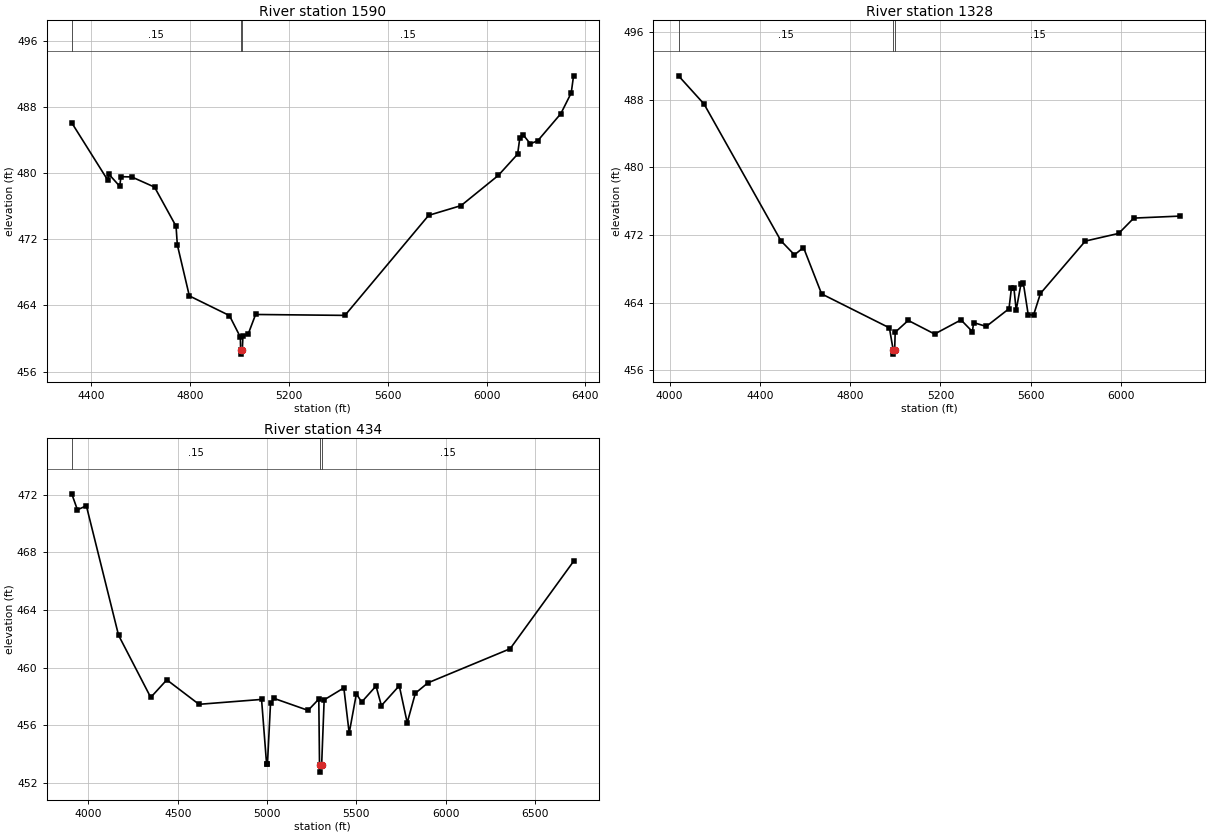
Type RM Length L Ch R = 1 ,1590    ,262,262,262
BEGIN DESCRIPTION:
Lacy 057 2439
END DESCRIPTION:
XS GIS Cut Line= 3
      2756918.57      6887007.94      2757065.89      6887671.38
      2757807.86      6888801.24
#Sta/Elev= 30
  4320.4  486.11  4465.9  479.18    4471  479.88  4514.6  478.43  4519.7  479.59
  4563.2  479.56  4655.5  478.33  4742.6  473.59  4747.7  471.35  4796.4  465.16
  4958.6  462.78  5002.8  460.18  5004.1  458.61  5005.2  458.11  5010.7  458.61
  5013.4   460.3  5035.4   460.6  5064.6  462.91  5426.3   462.8  5765.2  474.91
  5896.4  476.09    6047  479.74  6125.3  482.32  6134.4  484.33    6148  484.66
  6176.6  483.57  6206.8  483.94  6300.2  487.22  6342.3  489.73  6351.7   491.8
#Mann= 3 ,-1 , 0
  4320.4     .15       0  5004.1     .05       0  5010.7     .15       0
Bank Sta=5004.1,5010.7
XS Rating Curve= 0 ,0
Exp/Cntr=0.3,0.1

Type RM Length L Ch R = 1 ,1328    ,894,894,894
BEGIN DESCRIPTION:
Lacy 057 2436
END DESCRIPTION:
XS GIS Cut Line= 3
      2756872.59      6886908.06      2756924.16      6887867.28
      2757352.79      6889055.11
#Sta/Elev= 30
  4039.4  490.83  4152.5  487.49    4493  471.31  4553.1  469.64  4593.1  470.51
  4673.3  465.02  4973.7     461  4990.4  458.39  4991.5  457.89    4997  458.39
  4999.4  460.48  5057.1  461.88  5174.1  460.27    5291  461.94  5341.5  460.55
  5346.8  461.62  5402.9  461.17  5503.6  463.26  5514.3  465.68  5525.6  465.67
  5535.5   463.1  5556.8  466.22  5567.4  466.26  5588.7  462.58  5612.3   462.5
    5643  465.07  5841.8  471.27  5989.9  472.18  6056.5  473.99  6262.8  474.23
#Mann= 3 ,-1 , 0
  4039.4     .15       0  4990.4     .05       0    4997     .15       0
Bank Sta=4990.4,4997
XS Rating Curve= 0 ,0
Exp/Cntr=0.3,0.1

Type RM Length L Ch R = 1 ,434     ,0,0,0
BEGIN DESCRIPTION:
Lacy 057 2435
END DESCRIPTION:
XS GIS Cut Line= 3
      2756434.53      6887219.32      2756402.19      6888311.84
      2756465.23      6890025.58
#Sta/Elev= 30
    3907  472.07  3938.7  470.96  3988.7  471.24  4168.8  462.25  4348.9  457.93
  4438.9  459.15    4619  457.45  4969.1  457.79  4997.1  453.32  5002.1  453.32
  5019.2  457.51  5039.2  457.86  5229.3  457.03  5289.4  457.81  5293.4  453.24
  5295.1  452.74  5305.3  453.24  5319.4  457.76  5429.5  458.59  5459.5  455.45
  5499.5  458.17  5529.5  457.61  5609.6  458.72  5639.6  457.36  5739.7  458.74
  5784.2  456.17  5829.7  458.22  5899.8  458.94  6360.1  461.31  6714.9  467.38
#Mann= 3 ,-1 , 0
    3907     .15       0  5293.4     .05       0  5305.3     .15       0
Bank Sta=5293.4,5305.3
XS Rating Curve= 0 ,0
Exp/Cntr=0.3,0.1

Chan Stop Cuts=-1
Use User Specified Reach Order=0
Composite Channel Slope=5