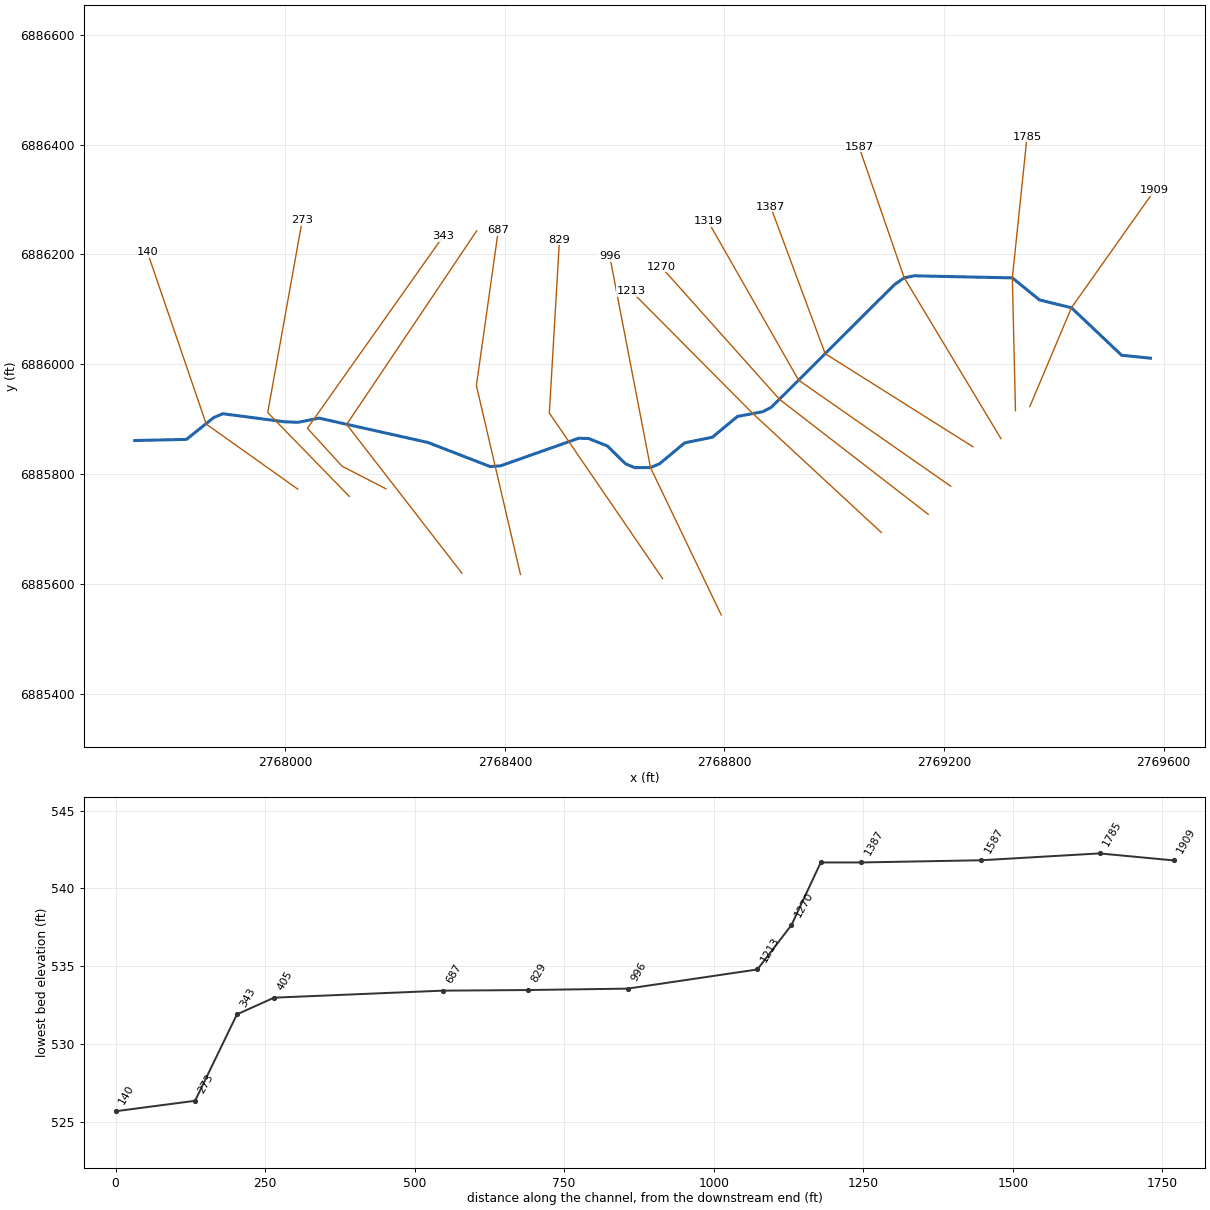
--- Lacy 058.prj (project) ---

Proj Title=Lacy 058 Base Level Engineering
Current Plan=p01
Default Exp/Contr=0.3,0.1
English Units
Geom File=g01
Flow File=f01
Plan File=p01
BEGIN DESCRIPTION:
Lacy 058
END DESCRIPTION:

--- Lacy 058.p01 (plan) ---

Plan Title=Multiple Run
Short Identifier=Multiple
Geom File=g01
Flow File=f01
Subcritical Flow
K Sum by GR= 0
Std Step Tol= 0.01
Critical Tol= 0.01
Num of Std Step Trials= 20
Max Error Tol= 0.3
Flow Tol Ratio= 0.001
Split Flow NTrial= 30
Split Flow Tol= 0.02
Split Flow Ratio= 0.02
Log Output Level= 0
Friction Slope Method= 1
Unsteady Friction Slope Method= 2
Unsteady Bridges Friction Slope Method= 1
Parabolic Critical Depth
Global Vel Dist=  1 , 1 , 1
Global Log Level= 0
CheckData=True
Encroach Param= -1, 0, 0, 0
BEGIN DESCRIPTION:
Multiple Run
END DESCRIPTION:

--- Lacy 058.f01 (steady flow) ---

Flow Title=Multiple
Number of Profiles=7
Profile Names=10-year,25-year,50-year,1pct_min,100-year,1pct_plu,500-year
River Rch & RM= Lacy 058,Reach-1,1909
     128     154     173      97     194     388     244
Boundary for River Rch & Prof#=Lacy 058,Reach-1,1
Up Type=0
Dn Type=3
Dn Slope=0.005
Boundary for River Rch & Prof#=Lacy 058,Reach-1,2
Up Type=0
Dn Type=3
Dn Slope=0.005
Boundary for River Rch & Prof#=Lacy 058,Reach-1,3
Up Type=0
Dn Type=3
Dn Slope=0.005
Boundary for River Rch & Prof#=Lacy 058,Reach-1,4
Up Type=0
Dn Type=3
Dn Slope=0.005
Boundary for River Rch & Prof#=Lacy 058,Reach-1,5
Up Type=0
Dn Type=3
Dn Slope=0.005
Boundary for River Rch & Prof#=Lacy 058,Reach-1,6
Up Type=0
Dn Type=3
Dn Slope=0.005
Boundary for River Rch & Prof#=Lacy 058,Reach-1,7
Up Type=0
Dn Type=3
Dn Slope=0.005

--- Lacy 058.g01 (geometry) ---

Geom Title=Existing Conditions

River Reach=Lacy 058,Reach-1
Reach XY= 30
      2769576.00      6886011.00      2769523.49      6886016.33
      2769432.06      6886102.86      2769373.83      6886117.14
      2769324.45      6886157.25      2769145.98      6886161.04
      2769127.46      6886157.47      2769109.24      6886144.57
      2768885.68      6885921.76      2768869.97      6885913.50
      2768823.81      6885904.90      2768778.20      6885867.08
      2768727.72      6885856.78      2768681.93      6885818.75
      2768665.30      6885811.70      2768636.63      6885811.60
      2768619.95      6885818.50      2768587.07      6885850.87
      2768552.71      6885864.73      2768534.34      6885865.11
      2768392.25      6885814.93      2768373.22      6885813.62
      2768259.87      6885857.50      2768061.78      6885901.78
      2768023.13      6885894.15      2767998.40      6885895.21
      2767886.50      6885909.79      2767869.93      6885902.90
      2767820.13      6885863.10      2767726.00      6885861.00

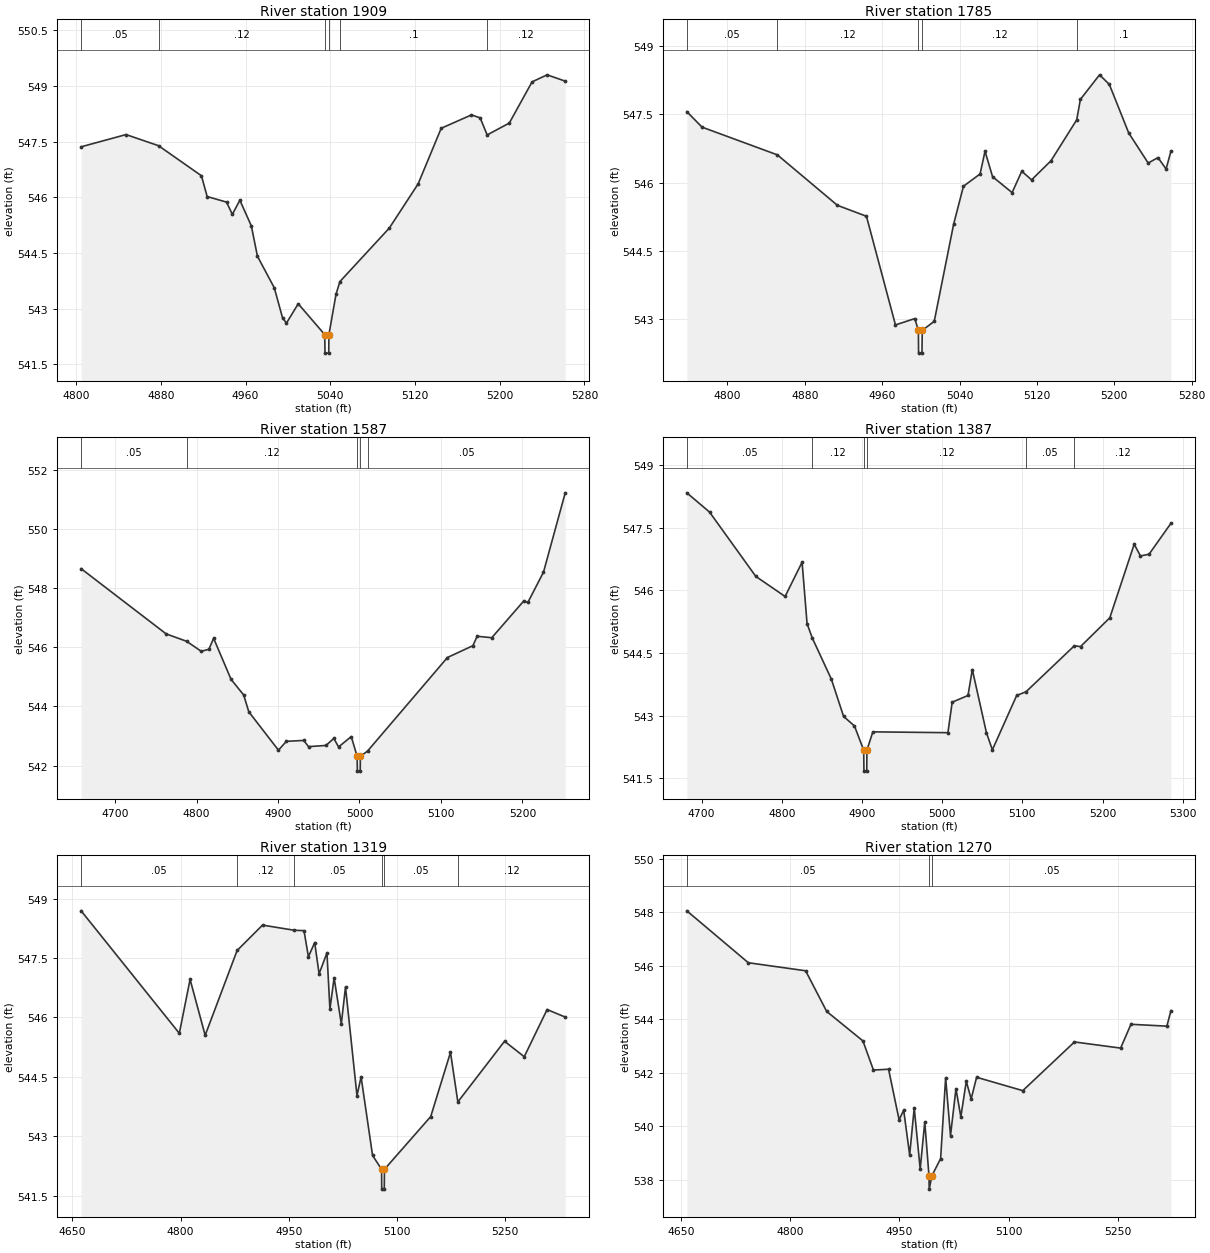
Type RM Length L Ch R = 1,1909,124,124,124
BEGIN DESCRIPTION:
Lacy 058 3544
END DESCRIPTION:
XS GIS Cut Line= 3
      2769356.26      6885922.86      2769432.06      6886102.86
      2769583.24      6886316.59
#Sta/Elev= 30
  4804.7  547.36  4847.1  547.69  4877.8  547.39  4918.3  546.58  4923.7  546.02
  4942.0  545.87  4947.5  545.54  4954.6  545.92  4965.4  545.23  4971.2  544.41
  4987.1  543.56  4994.9  542.75  4998.6  542.61  5009.7  543.13  5034.7  542.30
  5035.0  541.80  5038.5  541.80  5038.7  542.30  5045.4  543.39  5049.1  543.73
  5095.7  545.17  5122.9  546.36  5144.7  547.86  5173.3  548.22  5181.5  548.14
  5188.1  547.68  5209.0  548.00  5230.5  549.11  5244.7  549.30  5261.8  549.13
#Mann=6,-1,0
  4804.7    0.05       0  4877.8    0.12       0  5034.7    0.07       0
  5038.7    0.12       0  5049.1     0.1       0  5188.1    0.12       0
Bank Sta=5034.7,5038.7
Exp/Cntr=0.3,0.1

Type RM Length L Ch R = 1,1785,198,198,198
BEGIN DESCRIPTION:
Lacy 058 3543
END DESCRIPTION:
XS GIS Cut Line= 3
      2769330.13      6885915.32      2769324.45      6886157.25
      2769351.17      6886414.37
#Sta/Elev= 30
  4758.0  547.56  4773.7  547.22  4851.6  546.61  4913.7  545.50  4943.7  545.26
  4973.7  542.87  4993.7  543.01  4997.4  542.75  4997.6  542.25  5001.1  542.25
  5001.4  542.75  5013.8  542.95  5033.9  545.09  5044.0  545.92  5061.2  546.19
  5066.3  546.69  5074.1  546.13  5094.3  545.78  5104.3  546.25  5114.4  546.06
  5134.5  546.48  5161.1  547.38  5164.9  547.83  5184.7  548.37  5194.8  548.16
  5214.9  547.09  5235.0  546.43  5245.1  546.55  5253.5  546.30  5258.5  546.69
#Mann=5,-1,0
  4758.0    0.05       0  4851.6    0.12       0  4997.4    0.07       0
  5001.4    0.12       0  5161.1     0.1       0
Bank Sta=4997.4,5001.4
Exp/Cntr=0.3,0.1

Type RM Length L Ch R = 1,1587,200,200,200
BEGIN DESCRIPTION:
Lacy 058 3542
END DESCRIPTION:
XS GIS Cut Line= 3
      2769303.64      6885864.57      2769127.46      6886157.47
      2769045.02      6886396.23
#Sta/Elev= 30
  4658.2  548.67  4762.6  546.46  4787.7  546.21  4805.7  545.87  4815.1  545.94
  4820.9  546.31  4842.3  544.92  4857.8  544.39  4864.1  543.82  4900.5  542.52
  4910.2  542.82  4931.6  542.85  4937.4  542.64  4958.8  542.68  4968.5  542.92
  4974.3  542.63  4989.9  542.98  4997.1  542.31  4997.4  541.81  5000.9  541.81
  5001.1  542.31  5009.9  542.49  5108.0  545.66  5139.2  546.06  5144.5  546.38
  5162.4  546.33  5201.5  547.57  5206.8  547.53  5225.9  548.55  5252.6  551.24
#Mann=5,-1,0
  4658.2    0.05       0  4787.7    0.12       0  4997.1    0.07       0
  5001.1    0.12       0  5009.9    0.05       0
Bank Sta=4997.1,5001.1
Exp/Cntr=0.3,0.1

Type RM Length L Ch R = 1,1387,68,68,68
BEGIN DESCRIPTION:
Lacy 058 3541
END DESCRIPTION:
XS GIS Cut Line= 3
      2769252.80      6885849.57      2768983.52      6886019.27
      2768884.19      6886286.62
#Sta/Elev= 30
  4681.7  548.33  4710.0  547.87  4767.7  546.33  4804.2  545.85  4825.4  546.67
  4831.6  545.20  4838.0  544.86  4861.9  543.87  4877.1  542.98  4890.7  542.75
  4902.2  542.17  4902.5  541.67  4906.0  541.67  4906.2  542.17  4913.6  542.61
  5007.2  542.59  5012.5  543.32  5032.2  543.48  5037.6  544.10  5055.2  542.59
  5062.6  542.18  5092.9  543.48  5104.6  543.57  5164.8  544.67  5172.5  544.65
  5209.0  545.34  5239.4  547.10  5247.2  546.82  5257.9  546.86  5285.2  547.60
#Mann=6,-1,0
  4681.7    0.05       0  4838.0    0.12       0  4902.2    0.07       0
  4906.2    0.12       0  5104.6    0.05       0  5164.8    0.12       0
Bank Sta=4902.2,4906.2
Exp/Cntr=0.3,0.1

Type RM Length L Ch R = 1,1319,49,49,49
BEGIN DESCRIPTION:
Lacy 058 3540
END DESCRIPTION:
XS GIS Cut Line= 3
      2769212.20      6885777.83      2768935.08      6885971.00
      2768770.06      6886260.35
#Sta/Elev= 30
  4662.2  548.69  4798.3  545.60  4813.2  546.96  4834.1  545.55  4878.4  547.69
  4913.6  548.33  4957.5  548.20  4971.1  548.19  4977.2  547.53  4985.9  547.89
  4992.0  547.10  5002.9  547.63  5007.0  546.21  5012.8  547.00  5022.8  545.84
  5028.6  546.77  5044.5  544.03  5050.2  544.50  5066.1  542.52  5078.6  542.17
  5078.8  541.67  5082.3  541.67  5082.6  542.17  5146.7  543.50  5174.1  545.12
  5184.3  543.87  5249.0  545.40  5276.3  545.01  5308.0  546.20  5333.1  546.01
#Mann=6,-1,0
  4662.2    0.05       0  4878.4    0.12       0  4957.5    0.05       0
  5078.6    0.04       0  5082.6    0.05       0  5184.3    0.12       0
Bank Sta=5078.6,5082.6
Exp/Cntr=0.3,0.1

Type RM Length L Ch R = 1,1270,57,57,57
BEGIN DESCRIPTION:
Lacy 058 3539
END DESCRIPTION:
XS GIS Cut Line= 3
      2769171.15      6885726.74      2768900.18      6885936.21
      2768684.73      6886177.40
#Sta/Elev= 30
  4657.5  548.05  4742.1  546.11  4820.9  545.81  4849.9  544.29  4899.7  543.19
  4914.2  542.10  4935.0  542.13  4949.5  540.24  4955.8  540.60  4964.0  538.93
  4970.3  540.68  4978.5  538.40  4984.8  540.16  4990.6  538.15  4990.9  537.65
  4994.6  538.15  5006.6  538.79  5013.5  541.81  5020.2  539.65  5027.7  541.40
  5034.4  540.35  5041.9  541.68  5048.6  541.02  5056.1  541.83  5119.6  541.33
  5190.7  543.15  5254.2  542.92  5268.4  543.81  5317.8  543.74  5323.4  544.32
#Mann=3,-1,0
  4657.5    0.05       0  4990.6    0.04       0  4994.6    0.05       0
Bank Sta=4990.6,4994.6
Exp/Cntr=0.3,0.1

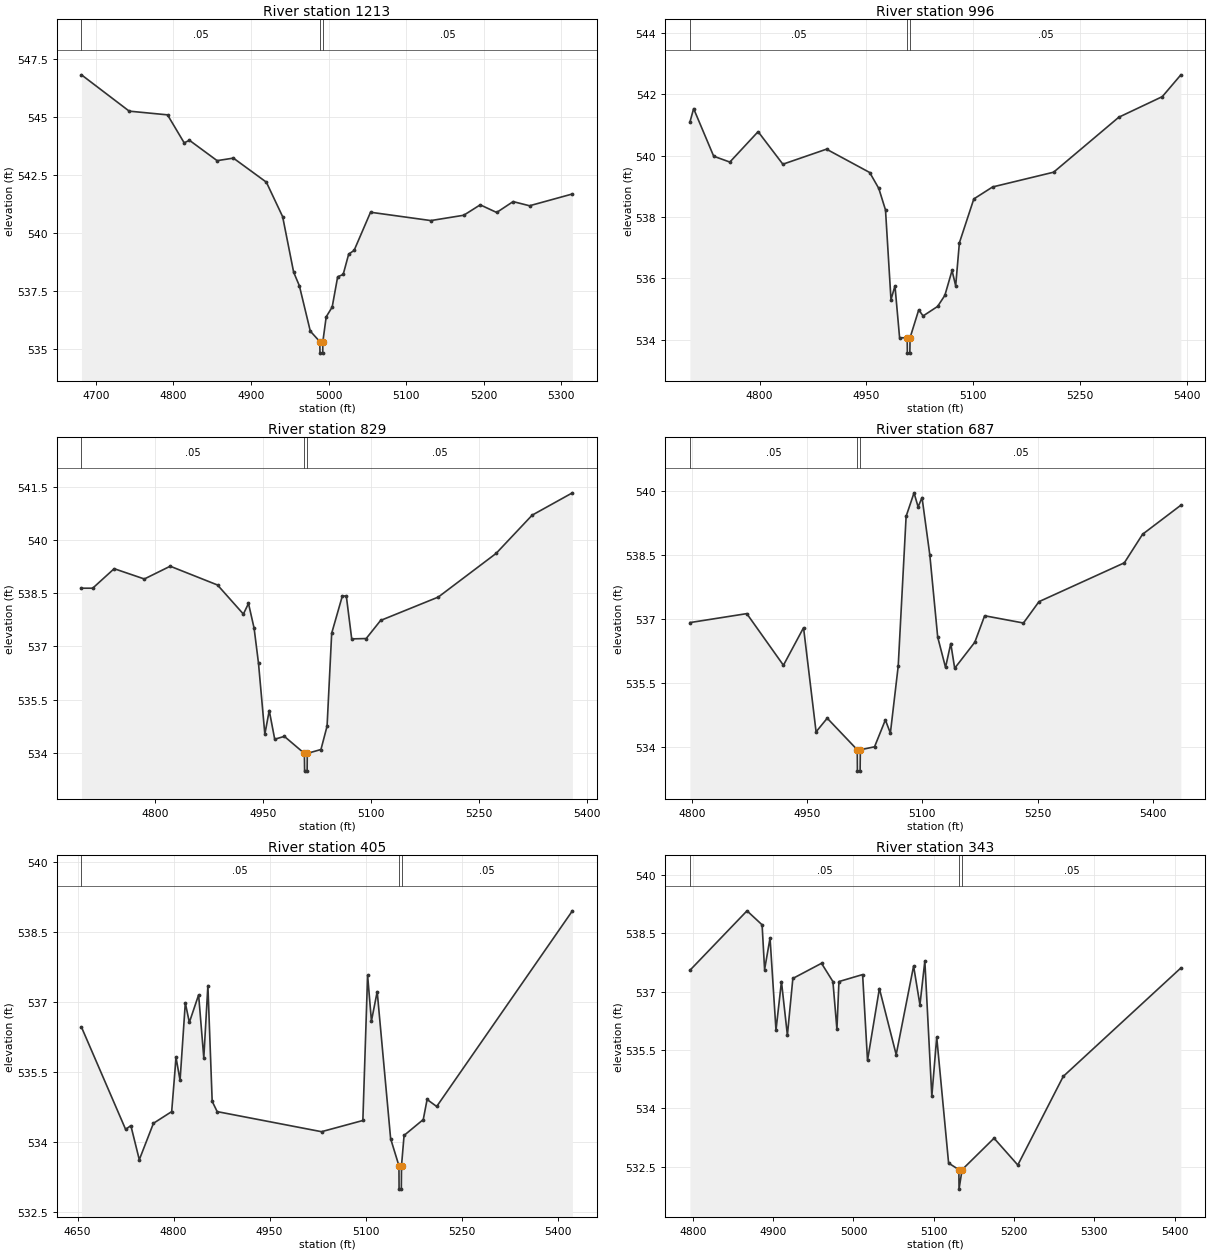
Type RM Length L Ch R = 1,1213,217,217,217
BEGIN DESCRIPTION:
Lacy 058 3538
END DESCRIPTION:
XS GIS Cut Line= 3
      2769085.69      6885693.62      2768851.81      6885910.11
      2768630.07      6886133.29
#Sta/Elev= 30
  4681.3  546.83  4742.9  545.26  4792.3  545.10  4813.8  543.89  4820.6  544.00
  4856.3  543.12  4877.3  543.23  4919.8  542.19  4940.8  540.70  4955.0  538.30
  4962.4  537.71  4976.5  535.75  4988.7  535.30  4989.0  534.80  4992.5  534.80
  4992.7  535.30  4997.0  536.37  5004.7  536.79  5011.8  538.10  5018.9  538.20
  5026.0  539.08  5033.0  539.24  5054.2  540.89  5132.0  540.53  5174.4  540.76
  5195.7  541.21  5216.9  540.88  5238.1  541.35  5259.3  541.17  5314.6  541.68
#Mann=3,-1,0
  4681.3    0.05       0  4988.7    0.04       0  4992.7    0.05       0
Bank Sta=4988.7,4992.7
Exp/Cntr=0.3,0.1

Type RM Length L Ch R = 1,996,167,167,167
BEGIN DESCRIPTION:
Lacy 058 3537
END DESCRIPTION:
XS GIS Cut Line= 3
      2768794.20      6885543.25      2768665.30      6885811.70
      2768591.10      6886196.62
#Sta/Elev= 30
  4702.2  541.09  4707.4  541.53  4735.6  539.98  4758.3  539.79  4798.0  540.78
  4832.8  539.72  4894.1  540.21  4954.8  539.45  4967.6  538.93  4977.0  538.23
  4984.7  535.31  4990.3  535.76  4996.8  534.07  5007.5  534.07  5007.7  533.57
  5011.2  533.57  5011.5  534.07  5023.7  534.98  5029.8  534.78  5050.2  535.09
  5060.4  535.45  5070.5  536.26  5075.6  535.76  5080.8  537.16  5101.1  538.59
  5127.5  538.98  5213.2  539.46  5304.8  541.25  5365.9  541.92  5392.0  542.63
#Mann=3,-1,0
  4702.2    0.05       0  5007.5    0.04       0  5011.5    0.05       0
Bank Sta=5007.5,5011.5
Exp/Cntr=0.3,0.1

Type RM Length L Ch R = 1,829,142,142,142
BEGIN DESCRIPTION:
Lacy 058 3536
END DESCRIPTION:
XS GIS Cut Line= 3
      2768687.35      6885609.58      2768481.10      6885911.02
      2768499.58      6886226.83
#Sta/Elev= 30
  4697.9  538.64  4713.5  538.64  4743.3  539.19  4785.2  538.90  4821.1  539.26
  4886.8  538.73  4922.7  537.91  4929.8  538.21  4937.6  537.51  4943.7  536.52
  4952.5  534.52  4958.6  535.19  4966.2  534.38  4979.6  534.46  5007.4  533.98
  5007.7  533.48  5011.2  533.48  5011.4  533.98  5030.4  534.09  5038.9  534.75
  5045.3  537.37  5060.1  538.42  5065.6  538.42  5073.1  537.21  5093.2  537.22
  5113.2  537.73  5193.3  538.39  5273.5  539.62  5323.6  540.70  5379.5  541.33
#Mann=3,-1,0
  4697.9    0.05       0  5007.4    0.04       0  5011.4    0.05       0
Bank Sta=5007.4,5011.4
Exp/Cntr=0.3,0.1

Type RM Length L Ch R = 1,687,282,282,282
BEGIN DESCRIPTION:
Lacy 058 3535
END DESCRIPTION:
XS GIS Cut Line= 3
      2768428.51      6885616.96      2768348.23      6885961.00
      2768388.16      6886243.91
#Sta/Elev= 30
  4797.4  536.92  4871.4  537.13  4919.1  535.92  4945.3  536.80  4961.6  534.36
  4976.1  534.68  5015.2  533.94  5015.4  533.44  5018.9  533.44  5019.2  533.94
  5037.7  534.01  5051.8  534.64  5058.3  534.33  5068.5  535.90  5078.8  539.41
  5089.1  539.96  5094.4  539.63  5099.5  539.85  5109.6  538.51  5119.9  536.58
  5130.1  535.87  5136.9  536.43  5142.0  535.85  5168.2  536.46  5181.0  537.08
  5231.5  536.91  5251.7  537.41  5362.8  538.32  5386.6  538.99  5436.4  539.67
#Mann=3,-1,0
  4797.4    0.05       0  5015.2    0.04       0  5019.2    0.05       0
Bank Sta=5015.2,5019.2
Exp/Cntr=0.3,0.1

Type RM Length L Ch R = 1,405,62,62,62
BEGIN DESCRIPTION:
Lacy 058 3534
END DESCRIPTION:
XS GIS Cut Line= 3
      2768321.76      6885619.51      2768111.93      6885890.34
      2768348.71      6886242.90
#Sta/Elev= 30
  4656.0  536.46  4725.0  534.27  4733.2  534.35  4746.4  533.62  4768.5  534.40
  4797.0  534.65  4803.8  535.81  4810.1  535.32  4818.3  536.98  4824.6  536.56
  4839.1  537.15  4847.2  535.80  4853.6  537.35  4860.3  534.87  4868.1  534.65
  5031.2  534.22  5095.8  534.46  5103.2  537.57  5109.2  536.59  5118.2  537.22
  5139.2  534.07  5152.2  533.49  5152.4  532.99  5155.9  532.99  5156.2  533.49
  5160.2  534.14  5190.2  534.48  5196.2  534.91  5211.2  534.76  5423.3  538.95
#Mann=3,-1,0
  4656.0    0.05       0  5152.2    0.04       0  5156.2    0.05       0
Bank Sta=5152.2,5156.2
Exp/Cntr=0.3,0.1

Type RM Length L Ch R = 1,343,70,70,70
BEGIN DESCRIPTION:
Lacy 058 3533
END DESCRIPTION:
XS GIS Cut Line= 4
      2768183.51      6885773.08      2768103.58      6885814.23
      2768040.49      6885883.40      2768287.61      6886232.82
#Sta/Elev= 30
  4796.3  537.55  4867.4  539.08  4886.2  538.72  4889.3  537.57  4896.1  538.38
  4903.5  536.01  4910.3  537.26  4917.7  535.88  4924.5  537.34  4960.2  537.73
  4974.4  537.26  4979.4  536.03  4981.9  537.26  5011.4  537.44  5017.5  535.23
  5032.3  537.08  5053.2  535.38  5074.9  537.66  5082.8  536.66  5088.9  537.79
  5097.6  534.31  5103.7  535.83  5118.5  532.59  5131.3  532.42  5131.5  531.92
  5135.3  532.42  5175.1  533.23  5204.7  532.54  5261.3  534.82  5407.8  537.61
#Mann=3,-1,0
  4796.3    0.05       0  5131.3    0.04       0  5135.3    0.05       0
Bank Sta=5131.3,5135.3
Exp/Cntr=0.3,0.1

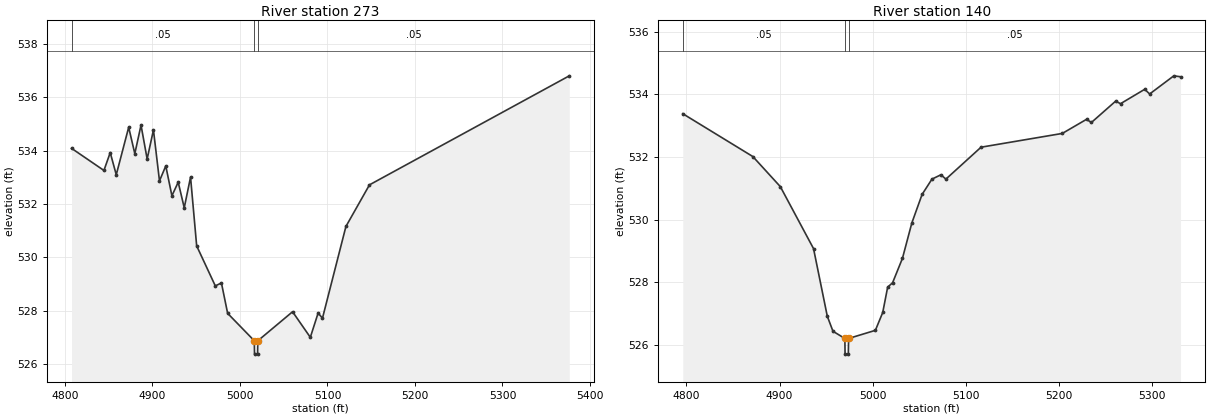
Type RM Length L Ch R = 1,273,133,133,133
BEGIN DESCRIPTION:
Lacy 058 3532
END DESCRIPTION:
XS GIS Cut Line= 3
      2768116.64      6885759.34      2767968.17      6885911.90
      2768031.05      6886262.32
#Sta/Elev= 30
  4807.5  534.09  4844.5  533.26  4851.7  533.93  4858.6  533.10  4872.8  534.88
  4879.8  533.89  4886.9  534.96  4893.9  533.69  4901.1  534.78  4908.0  532.87
  4915.2  533.43  4922.2  532.31  4929.4  532.82  4936.3  531.86  4943.5  533.01
  4950.5  530.43  4971.8  528.93  4978.8  529.04  4985.9  527.90  5016.4  526.87
  5016.6  526.37  5020.1  526.37  5020.4  526.87  5060.1  527.96  5080.4  527.00
  5089.3  527.91  5094.3  527.72  5121.1  531.16  5148.0  532.72  5376.4  536.81
#Mann=3,-1,0
  4807.5    0.05       0  5016.4    0.04       0  5020.4    0.05       0
Bank Sta=5016.4,5020.4
Exp/Cntr=0.3,0.1

Type RM Length L Ch R = 1,140,0,0,0
BEGIN DESCRIPTION:
Lacy 058 3531
END DESCRIPTION:
XS GIS Cut Line= 3
      2768022.77      6885772.56      2767856.17      6885890.93
      2767749.07      6886203.94
#Sta/Elev= 30
  4796.0  533.38  4871.4  532.01  4900.9  531.05  4936.6  529.07  4951.4  526.91
  4957.5  526.43  4970.3  526.20  4970.5  525.70  4974.0  525.70  4974.3  526.20
  5003.1  526.46  5011.0  527.03  5016.3  527.84  5021.6  527.98  5032.2  528.76
  5042.3  529.89  5053.3  530.80  5063.9  531.29  5073.6  531.43  5078.9  531.29
  5116.7  532.31  5204.1  532.75  5230.1  533.20  5235.4  533.10  5261.4  533.78
  5266.7  533.70  5292.7  534.16  5298.0  534.01  5324.0  534.59  5331.2  534.56
#Mann=3,-1,0
  4796.0    0.05       0  4970.3    0.04       0  4974.3    0.05       0
Bank Sta=4970.3,4974.3
Exp/Cntr=0.3,0.1

Chan Stop Cuts=-1