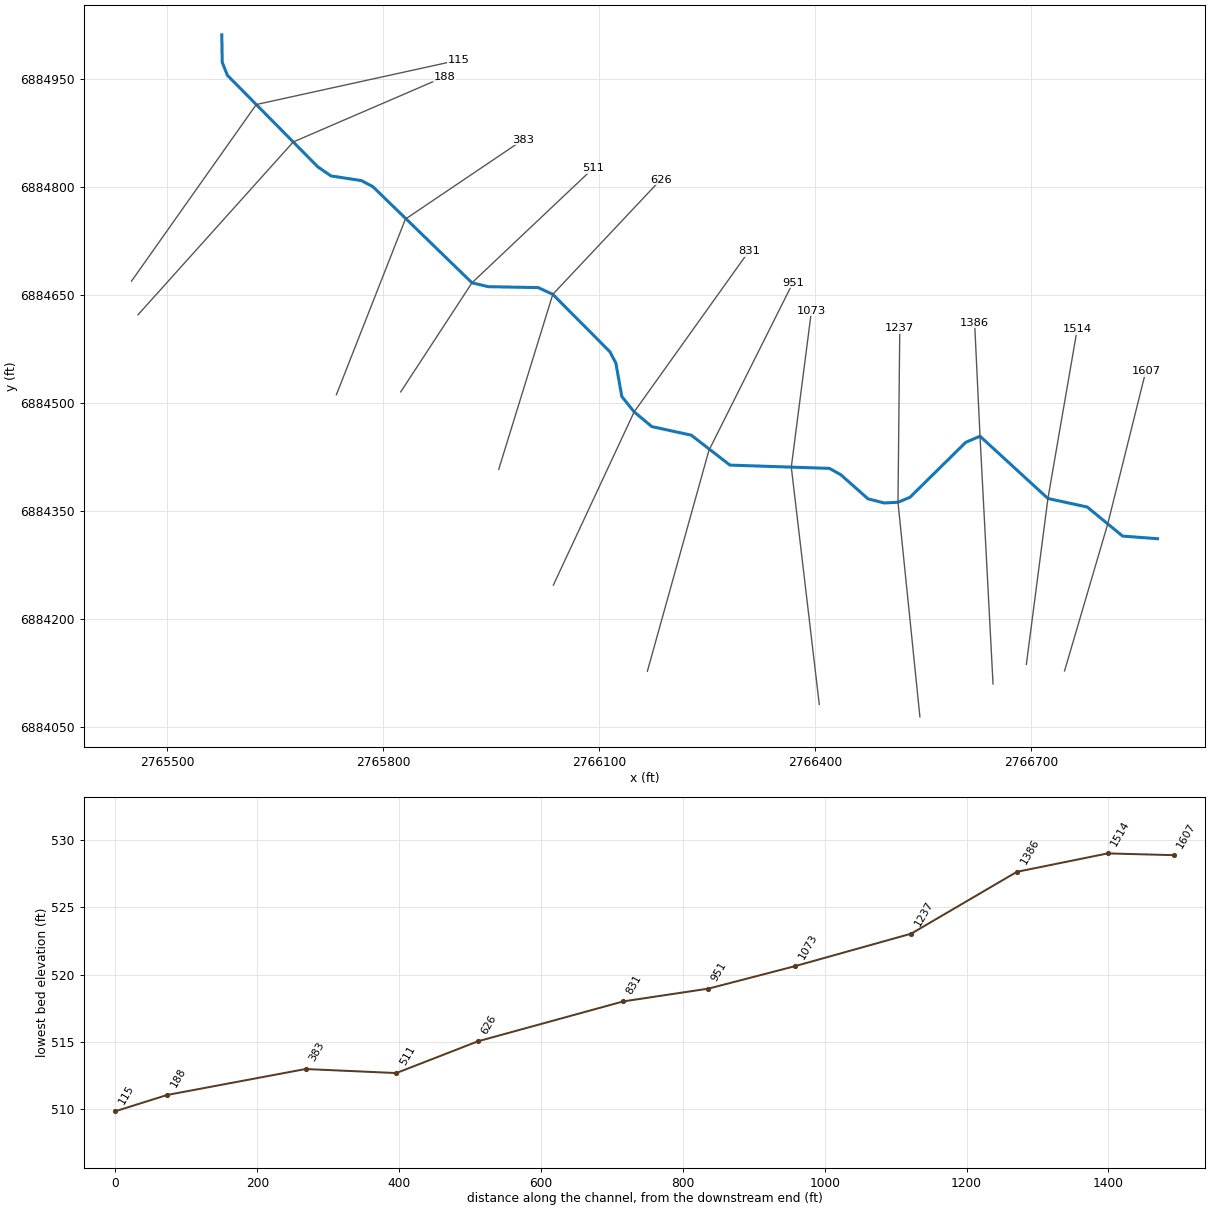
--- Lacy 059.prj (project) ---

Proj Title=Lacy 059 Base Level Engineering
Current Plan=p01
Default Exp/Contr=0.3,0.1
English Units
Geom File=g01
Flow File=f01
Plan File=p01
BEGIN DESCRIPTION:
Lacy 059
END DESCRIPTION:

--- Lacy 059.p01 (plan) ---

Plan Title=Multiple Run
Short Identifier=Multiple
Geom File=g01
Flow File=f01
Subcritical Flow
K Sum by GR= 0
Std Step Tol= 0.01
Critical Tol= 0.01
Num of Std Step Trials= 20
Max Error Tol= 0.3
Flow Tol Ratio= 0.001
Split Flow NTrial= 30
Split Flow Tol= 0.02
Split Flow Ratio= 0.02
Log Output Level= 0
Friction Slope Method= 1
Unsteady Friction Slope Method= 2
Unsteady Bridges Friction Slope Method= 1
Parabolic Critical Depth
Global Vel Dist=  1 , 1 , 1
Global Log Level= 0
CheckData=True
Encroach Param= -1, 0, 0, 0
BEGIN DESCRIPTION:
Multiple Run
END DESCRIPTION:

--- Lacy 059.f01 (steady flow) ---

Flow Title=Multiple
Number of Profiles=7
Profile Names=10-year,25-year,50-year,1pct_min,100-year,1pct_plu,500-year
River Rch & RM= Lacy 059,Reach-1,1607
     108     129     145      81     163     324     203
Boundary for River Rch & Prof#=Lacy 059,Reach-1,1
Up Type=0
Dn Type=3
Dn Slope=0.005
Boundary for River Rch & Prof#=Lacy 059,Reach-1,2
Up Type=0
Dn Type=3
Dn Slope=0.005
Boundary for River Rch & Prof#=Lacy 059,Reach-1,3
Up Type=0
Dn Type=3
Dn Slope=0.005
Boundary for River Rch & Prof#=Lacy 059,Reach-1,4
Up Type=0
Dn Type=3
Dn Slope=0.005
Boundary for River Rch & Prof#=Lacy 059,Reach-1,5
Up Type=0
Dn Type=3
Dn Slope=0.005
Boundary for River Rch & Prof#=Lacy 059,Reach-1,6
Up Type=0
Dn Type=3
Dn Slope=0.005
Boundary for River Rch & Prof#=Lacy 059,Reach-1,7
Up Type=0
Dn Type=3
Dn Slope=0.005

--- Lacy 059.g01 (geometry) ---

Geom Title=Existing Conditions

River Reach=Lacy 059,Reach-1
Reach XY= 30
      2766876.00      6884311.00      2766827.49      6884314.60
      2766778.24      6884355.03      2766723.69      6884366.85
      2766629.33      6884453.39      2766609.35      6884444.77
      2766532.06      6884368.52      2766515.38      6884361.61
      2766496.21      6884360.65      2766473.83      6884366.35
      2766435.67      6884400.08      2766420.07      6884408.70
      2766281.93      6884413.25      2766228.15      6884454.85
      2766173.45      6884466.73      2766148.86      6884487.16
      2766131.75      6884508.46      2766123.45      6884554.92
      2766115.22      6884570.69      2766035.81      6884650.49
      2766015.52      6884659.84      2765946.06      6884661.13
      2765923.57      6884666.52      2765785.68      6884800.22
      2765769.95      6884808.46      2765727.65      6884814.98
      2765709.33      6884827.65      2765583.76      6884954.79
      2765576.59      6884972.84      2765576.00      6885011.00

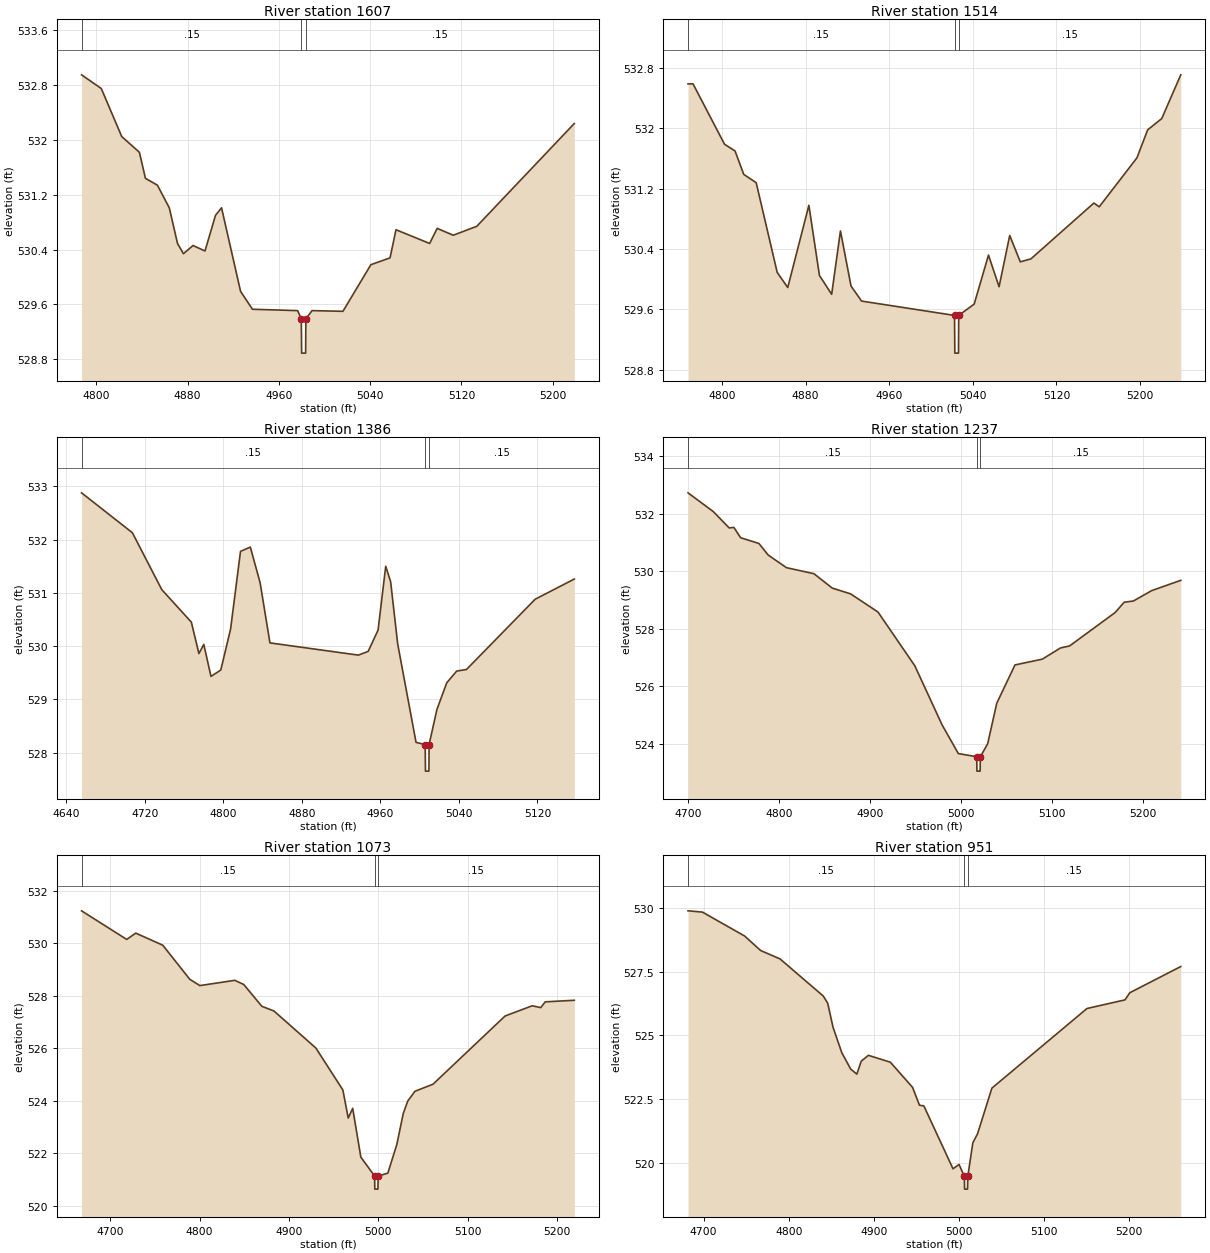
Type RM Length L Ch R = 1,1607,93,93,93
BEGIN DESCRIPTION:
Lacy 059 2522
END DESCRIPTION:
XS GIS Cut Line= 3
      2766746.74      6884127.23      2766806.79      6884331.59
      2766859.72      6884544.00
#Sta/Elev= 30
  4787.0  532.95  4804.3  532.75  4822.2  532.05  4837.7  531.82  4843.0  531.44
  4853.5  531.34  4863.9  531.01  4871.1  530.49  4876.3  530.34  4884.7  530.46
  4895.2  530.38  4904.4  530.90  4909.7  531.01  4926.4  529.79  4936.8  529.53
  4976.4  529.51  4979.6  529.39  4979.9  528.89  4983.4  528.89  4983.6  529.39
  4989.0  529.51  5016.1  529.50  5040.6  530.18  5057.4  530.28  5062.6  530.69
  5092.1  530.49  5098.7  530.71  5112.8  530.61  5133.4  530.74  5218.9  532.24
#Mann=3,-1,0
  4787.0    0.15       0  4979.6    0.05       0  4983.6    0.15       0
Bank Sta=4979.6,4983.6
Exp/Cntr=0.3,0.1

Type RM Length L Ch R = 1,1514,128,128,128
BEGIN DESCRIPTION:
Lacy 059 2521
END DESCRIPTION:
XS GIS Cut Line= 3
      2766693.71      6884136.39      2766723.69      6884366.85
      2766764.38      6884602.26
#Sta/Elev= 30
  4767.6  532.59  4772.4  532.59  4802.5  531.79  4812.6  531.70  4820.9  531.39
  4832.8  531.28  4852.9  530.09  4863.0  529.89  4883.2  530.98  4893.3  530.05
  4905.0  529.80  4913.4  530.64  4923.5  529.91  4933.6  529.71  5022.5  529.52
  5022.8  529.02  5026.3  529.02  5026.5  529.52  5041.3  529.67  5055.0  530.32
  5065.1  529.90  5075.3  530.58  5085.4  530.23  5095.6  530.27  5155.8  531.01
  5160.9  530.96  5197.0  531.61  5207.2  531.98  5220.7  532.13  5238.9  532.71
#Mann=3,-1,0
  4767.6    0.15       0  5022.5    0.05       0  5026.5    0.15       0
Bank Sta=5022.5,5026.5
Exp/Cntr=0.3,0.1

Type RM Length L Ch R = 1,1386,149,149,149
BEGIN DESCRIPTION:
Lacy 059 2520
END DESCRIPTION:
XS GIS Cut Line= 3
      2766647.42      6884109.26      2766629.33      6884453.39
      2766621.85      6884610.81
#Sta/Elev= 30
  4655.4  532.88  4707.2  532.13  4737.2  531.06  4767.3  530.45  4775.0  529.86
  4780.0  530.03  4787.3  529.43  4797.3  529.55  4807.3  530.32  4817.4  531.78
  4827.4  531.86  4837.4  531.19  4847.4  530.06  4937.5  529.83  4947.5  529.90
  4957.6  530.30  4965.4  531.50  4970.4  531.21  4977.6  530.04  4996.3  528.19
  5005.6  528.15  5005.9  527.65  5009.4  527.65  5009.6  528.15  5017.6  528.81
  5027.6  529.31  5037.7  529.53  5047.7  529.56  5117.7  530.88  5157.6  531.26
#Mann=3,-1,0
  4655.4    0.15       0  5005.6    0.05       0  5009.6    0.15       0
Bank Sta=5005.6,5009.6
Exp/Cntr=0.3,0.1

Type RM Length L Ch R = 1,1237,164,164,164
BEGIN DESCRIPTION:
Lacy 059 2519
END DESCRIPTION:
XS GIS Cut Line= 3
      2766545.85      6884063.47      2766515.38      6884361.61
      2766517.88      6884603.10
#Sta/Elev= 30
  4700.3  532.72  4728.0  532.07  4745.5  531.50  4750.6  531.52  4758.1  531.16
  4778.2  530.96  4788.3  530.56  4808.4  530.12  4838.6  529.91  4858.7  529.41
  4878.8  529.21  4908.9  528.58  4949.4  526.71  4979.3  524.66  4997.2  523.66
  5017.4  523.55  5017.6  523.05  5021.1  523.05  5021.4  523.55  5029.4  524.00
  5039.4  525.41  5059.4  526.74  5089.4  526.94  5109.4  527.33  5119.4  527.40
  5169.4  528.56  5179.4  528.92  5189.4  528.96  5209.4  529.32  5241.5  529.68
#Mann=3,-1,0
  4700.3    0.15       0  5017.4    0.05       0  5021.4    0.15       0
Bank Sta=5017.4,5021.4
Exp/Cntr=0.3,0.1

Type RM Length L Ch R = 1,1073,122,122,122
BEGIN DESCRIPTION:
Lacy 059 2518
END DESCRIPTION:
XS GIS Cut Line= 3
      2766406.04      6884080.83      2766367.17      6884410.44
      2766395.22      6884627.74
#Sta/Elev= 30
  4668.1  531.24  4718.6  530.15  4728.7  530.39  4758.9  529.93  4789.1  528.63
  4800.4  528.39  4839.5  528.59  4849.5  528.43  4869.7  527.60  4883.3  527.42
  4930.1  526.01  4960.3  524.41  4966.3  523.34  4971.3  523.71  4980.4  521.85
  4995.8  521.13  4996.0  520.63  4999.5  520.63  4999.8  521.13  5010.6  521.24
  5020.7  522.34  5027.8  523.51  5032.9  523.99  5040.9  524.36  5061.1  524.63
  5141.7  527.23  5172.0  527.62  5181.6  527.55  5186.6  527.77  5219.1  527.83
#Mann=3,-1,0
  4668.1    0.15       0  4995.8    0.05       0  4999.8    0.15       0
Bank Sta=4995.8,4999.8
Exp/Cntr=0.3,0.1

Type RM Length L Ch R = 1,951,120,120,120
BEGIN DESCRIPTION:
Lacy 059 2517
END DESCRIPTION:
XS GIS Cut Line= 3
      2766167.24      6884126.89      2766252.68      6884433.61
      2766369.36      6884666.52
#Sta/Elev= 30
  4681.6  529.90  4698.5  529.85  4748.1  528.91  4766.9  528.34  4789.7  528.01
  4840.5  526.55  4845.7  526.27  4852.0  525.32  4862.3  524.32  4872.7  523.68
  4879.9  523.48  4885.1  523.99  4893.5  524.22  4919.3  523.95  4945.4  522.96
  4953.5  522.26  4958.7  522.23  4992.9  519.76  5000.0  519.93  5006.3  519.46
  5006.5  518.96  5010.0  518.96  5010.3  519.46  5016.2  520.78  5021.8  521.14
  5038.6  522.93  5150.3  526.06  5195.0  526.40  5200.6  526.68  5260.5  527.71
#Mann=3,-1,0
  4681.6    0.15       0  5006.3    0.05       0  5010.3    0.15       0
Bank Sta=5006.3,5010.3
Exp/Cntr=0.3,0.1

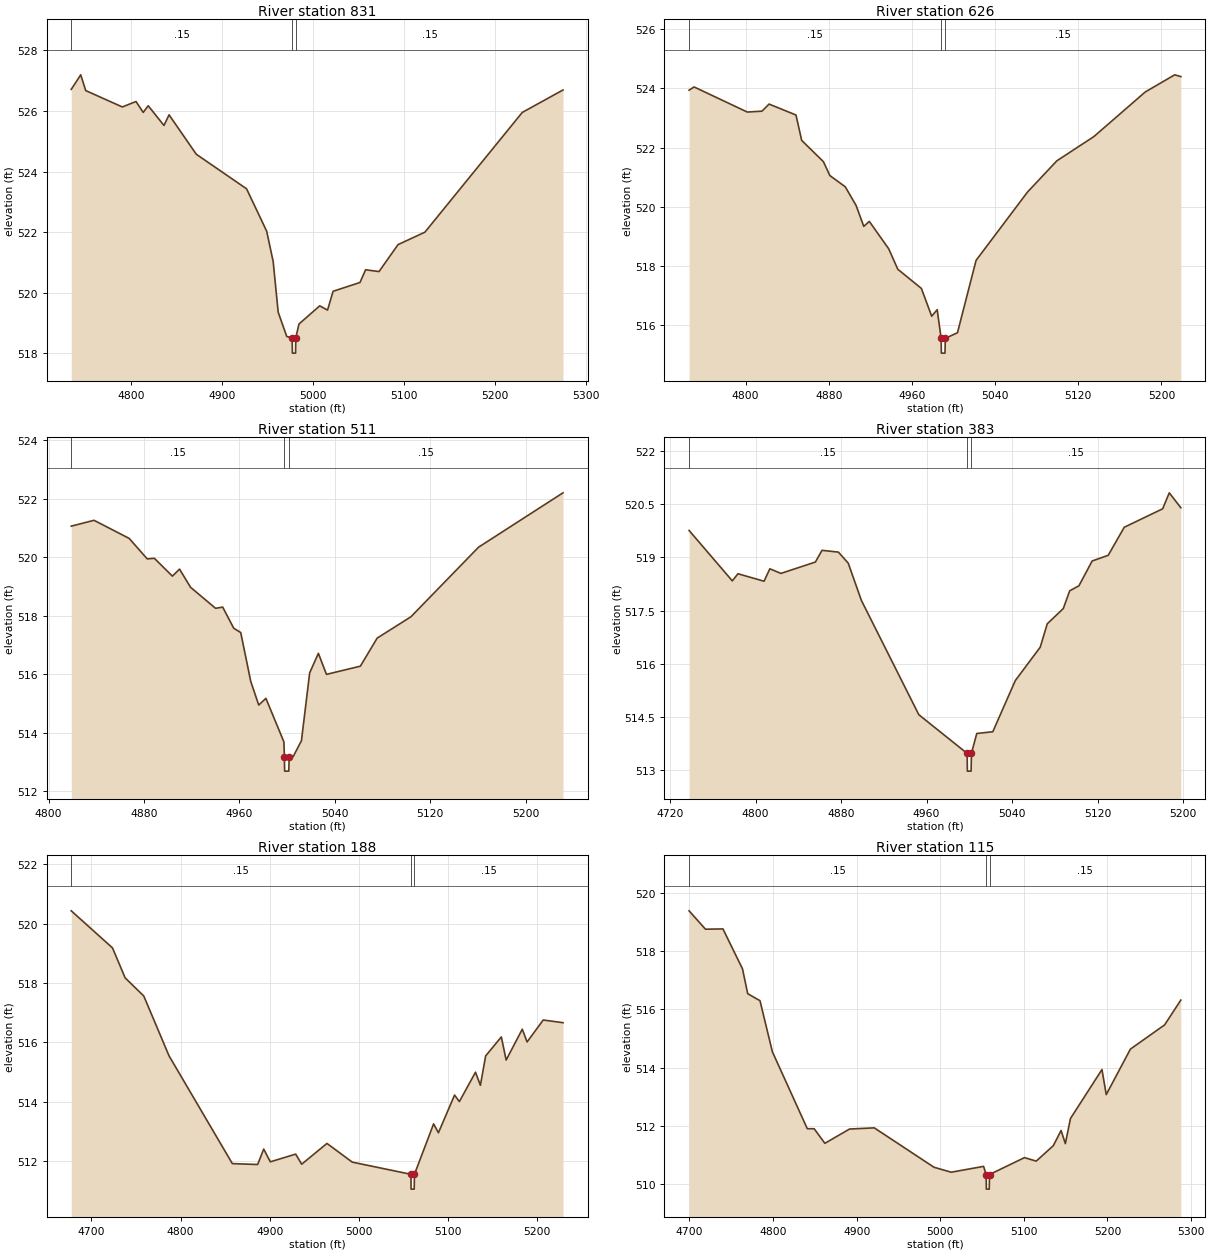
Type RM Length L Ch R = 1,831,205,205,205
BEGIN DESCRIPTION:
Lacy 059 2516
END DESCRIPTION:
XS GIS Cut Line= 3
      2766036.61      6884246.55      2766148.86      6884487.16
      2766308.34      6884710.46
#Sta/Elev= 30
  4734.5  526.71  4744.9  527.19  4750.4  526.67  4790.6  526.13  4805.6  526.31
  4813.5  525.95  4819.0  526.17  4836.3  525.52  4841.9  525.87  4871.8  524.57
  4927.0  523.43  4949.1  522.03  4956.2  521.03  4961.7  519.36  4971.1  518.56
  4977.0  518.51  4977.3  518.01  4980.8  518.01  4981.0  518.51  4984.5  518.97
  5007.3  519.57  5015.9  519.43  5022.0  520.05  5051.5  520.34  5057.7  520.76
  5072.4  520.70  5093.3  521.59  5122.8  522.00  5229.7  525.95  5274.4  526.69
#Mann=3,-1,0
  4734.5    0.15       0  4977.0    0.05       0  4981.0    0.15       0
Bank Sta=4977,4981
Exp/Cntr=0.3,0.1

Type RM Length L Ch R = 1,626,115,115,115
BEGIN DESCRIPTION:
Lacy 059 2515
END DESCRIPTION:
XS GIS Cut Line= 3
      2765960.77      6884407.51      2766035.81      6884650.49
      2766185.64      6884809.67
#Sta/Elev= 30
  4745.7  523.94  4750.5  524.05  4801.7  523.20  4815.8  523.23  4822.6  523.47
  4848.5  523.10  4854.0  522.24  4874.9  521.52  4881.1  521.05  4895.9  520.67
  4906.3  520.04  4913.7  519.33  4919.0  519.50  4937.7  518.57  4946.4  517.88
  4969.1  517.23  4979.0  516.29  4984.3  516.51  4988.1  515.54  4988.3  515.04
  4991.8  515.04  4992.1  515.54  5003.8  515.73  5021.7  518.18  5071.1  520.49
  5099.4  521.55  5135.0  522.37  5184.4  523.88  5212.7  524.46  5218.6  524.40
#Mann=3,-1,0
  4745.7    0.15       0  4988.1    0.05       0  4992.1    0.15       0
Bank Sta=4988.1,4992.1
Exp/Cntr=0.3,0.1

Type RM Length L Ch R = 1,511,128,128,128
BEGIN DESCRIPTION:
Lacy 059 2514
END DESCRIPTION:
XS GIS Cut Line= 3
      2765824.61      6884514.98      2765923.57      6884666.52
      2766091.69      6884825.38
#Sta/Elev= 30
  4819.0  521.06  4838.1  521.26  4867.6  520.64  4882.7  519.94  4888.7  519.96
  4903.8  519.35  4909.8  519.59  4919.0  518.97  4940.0  518.25  4946.0  518.29
  4955.2  517.57  4961.1  517.42  4969.5  515.75  4976.2  514.94  4982.2  515.17
  4997.3  513.68  4997.7  513.18  4997.9  512.68  5001.4  512.68  5001.7  513.18
  5005.1  513.18  5012.0  513.72  5018.9  516.04  5026.2  516.71  5033.0  515.99
  5061.4  516.27  5075.5  517.23  5103.8  517.96  5160.5  520.34  5231.3  522.20
#Mann=3,-1,0
  4819.0    0.15       0  4997.7    0.05       0  5001.7    0.15       0
Bank Sta=4997.7,5001.7
Exp/Cntr=0.3,0.1

Type RM Length L Ch R = 1,383,195,195,195
BEGIN DESCRIPTION:
Lacy 059 2513
END DESCRIPTION:
XS GIS Cut Line= 3
      2765735.21      6884511.06      2765831.08      6884755.00
      2765994.97      6884865.56
#Sta/Elev= 30
  4737.9  519.76  4778.3  518.34  4783.6  518.54  4808.0  518.33  4813.4  518.68
  4823.8  518.55  4856.0  518.87  4862.2  519.20  4877.5  519.15  4886.7  518.84
  4899.0  517.79  4952.7  514.57  4997.9  513.48  4998.1  512.98  5001.6  512.98
  5001.9  513.48  5006.9  514.04  5021.9  514.09  5042.9  515.53  5066.2  516.47
  5072.8  517.13  5087.8  517.56  5093.8  518.06  5102.4  518.20  5114.8  518.90
  5129.8  519.06  5144.8  519.85  5180.7  520.37  5186.9  520.82  5197.7  520.40
#Mann=3,-1,0
  4737.9    0.15       0  4997.9    0.05       0  5001.9    0.15       0
Bank Sta=4997.9,5001.9
Exp/Cntr=0.3,0.1

Type RM Length L Ch R = 1,188,73,73,73
BEGIN DESCRIPTION:
Lacy 059 2512
END DESCRIPTION:
XS GIS Cut Line= 3
      2765459.62      6884622.07      2765675.26      6884862.15
      2765885.72      6884952.92
#Sta/Elev= 30
  4677.3  520.43  4723.6  519.18  4737.8  518.17  4758.7  517.56  4787.1  515.54
  4858.1  511.91  4886.5  511.88  4893.3  512.40  4900.7  511.97  4929.2  512.23
  4935.9  511.89  4964.3  512.59  4992.7  511.96  5058.5  511.55  5058.7  511.05
  5062.2  511.05  5062.5  511.55  5084.0  513.25  5089.4  512.95  5107.5  514.22
  5112.9  514.00  5131.0  514.99  5136.5  514.55  5142.4  515.54  5160.0  516.18
  5165.4  515.40  5183.5  516.44  5188.9  516.01  5207.0  516.75  5229.2  516.66
#Mann=3,-1,0
  4677.3    0.15       0  5058.5    0.05       0  5062.5    0.15       0
Bank Sta=5058.5,5062.5
Exp/Cntr=0.3,0.1

Type RM Length L Ch R = 1,115,0,0,0
BEGIN DESCRIPTION:
Lacy 059 3489
END DESCRIPTION:
XS GIS Cut Line= 3
      2765450.58      6884668.79      2765623.90      6884914.15
      2765904.91      6884975.83
#Sta/Elev= 30
  4699.6  519.38  4719.2  518.75  4740.1  518.76  4763.5  517.39  4769.7  516.54
  4784.4  516.30  4799.2  514.55  4841.0  511.91  4849.2  511.91  4862.0  511.41
  4891.5  511.90  4921.1  511.94  4992.5  510.59  5013.1  510.42  5051.8  510.62
  5054.9  510.34  5055.1  509.84  5058.6  509.84  5058.9  510.34  5100.7  510.92
  5114.8  510.80  5135.2  511.33  5144.5  511.85  5149.6  511.40  5155.7  512.26
  5193.4  513.94  5198.5  513.08  5227.4  514.64  5268.3  515.47  5287.7  516.32
#Mann=3,-1,0
  4699.6    0.15       0  5054.9    0.05       0  5058.9    0.15       0
Bank Sta=5054.9,5058.9
Exp/Cntr=0.3,0.1

Chan Stop Cuts=-1