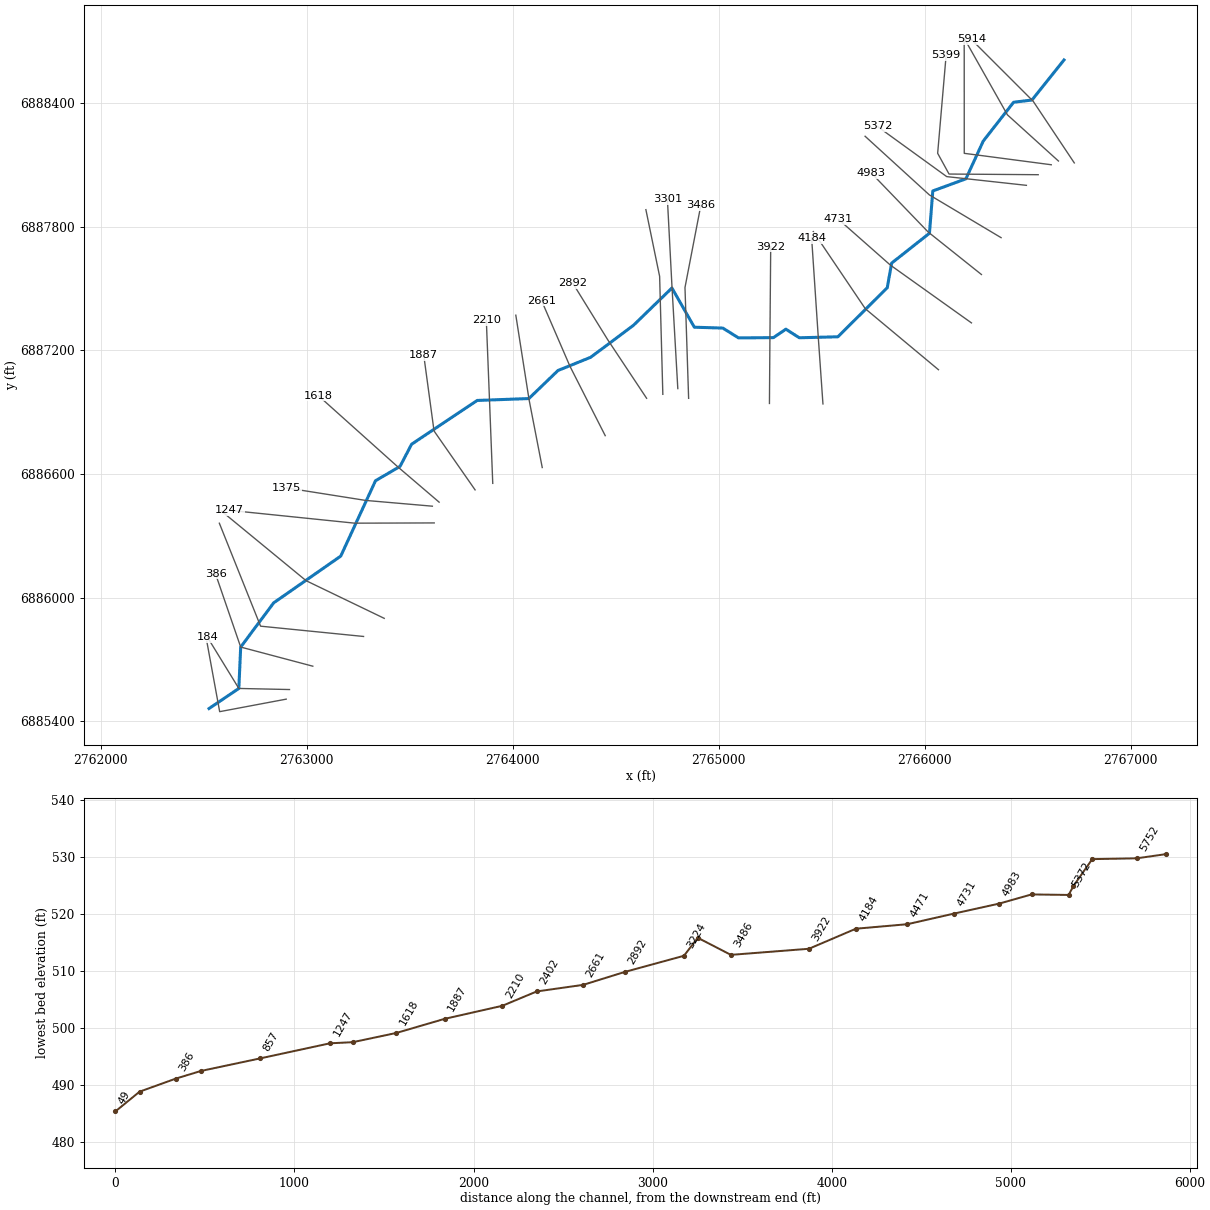
--- Lacy 060.prj (project) ---

Proj Title=Lacy 060 Base Level Engineering
Current Plan=p01
Default Exp/Contr=0.3,0.1
English Units
Geom File=g01
Flow File=f01
Plan File=p01
BEGIN DESCRIPTION:
Lacy 060
END DESCRIPTION:

--- Lacy 060.p01 (plan) ---

Plan Title=Multiple Run
Short Identifier=Multiple
Geom File=g01
Flow File=f01
Subcritical Flow
K Sum by GR= 0
Std Step Tol= 0.01
Critical Tol= 0.01
Num of Std Step Trials= 20
Max Error Tol= 0.3
Flow Tol Ratio= 0.001
Split Flow NTrial= 30
Split Flow Tol= 0.02
Split Flow Ratio= 0.02
Log Output Level= 0
Friction Slope Method= 1
Unsteady Friction Slope Method= 2
Unsteady Bridges Friction Slope Method= 1
Parabolic Critical Depth
Global Vel Dist=  1 , 1 , 1
Global Log Level= 0
CheckData=True
Encroach Param= -1, 0, 0, 0
BEGIN DESCRIPTION:
Multiple Run
END DESCRIPTION:

--- Lacy 060.f01 (steady flow) ---

Flow Title=Multiple
Number of Profiles=7
Profile Names=10-year,25-year,50-year,1pct_min,100-year,1pct_plu,500-year
River Rch & RM= Lacy 060,Reach-1,5914
     277     354     414     241     482     961     652
River Rch & RM= Lacy 060,Reach-1,1618
     323     418     492     288     575    1148     788
Boundary for River Rch & Prof#=Lacy 060,Reach-1,1
Up Type=0
Dn Type=3
Dn Slope=0.005
Boundary for River Rch & Prof#=Lacy 060,Reach-1,2
Up Type=0
Dn Type=3
Dn Slope=0.005
Boundary for River Rch & Prof#=Lacy 060,Reach-1,3
Up Type=0
Dn Type=3
Dn Slope=0.005
Boundary for River Rch & Prof#=Lacy 060,Reach-1,4
Up Type=0
Dn Type=3
Dn Slope=0.005
Boundary for River Rch & Prof#=Lacy 060,Reach-1,5
Up Type=0
Dn Type=3
Dn Slope=0.005
Boundary for River Rch & Prof#=Lacy 060,Reach-1,6
Up Type=0
Dn Type=3
Dn Slope=0.005
Boundary for River Rch & Prof#=Lacy 060,Reach-1,7
Up Type=0
Dn Type=3
Dn Slope=0.005

--- Lacy 060.g01 (geometry) ---

Geom Title=Existing Conditions

River Reach=Lacy 060,Reach-1
Reach XY= 30
      2766676.00      6888611.00      2766520.46      6888416.29
      2766431.54      6888405.71      2766284.14      6888217.06
      2766199.90      6888033.72      2766039.20      6887974.73
      2766022.93      6887769.30      2765839.40      6887624.30
      2765818.14      6887504.83      2765578.45      6887266.46
      2765391.16      6887261.66      2765326.00      6887303.44
      2765265.56      6887262.38      2765096.03      6887261.07
      2765020.06      6887308.73      2764881.65      6887312.98
      2764772.87      6887503.50      2764585.68      6887321.78
      2764378.30      6887166.83      2764219.94      6887102.86
      2764078.45      6886966.46      2763827.55      6886957.25
      2763509.08      6886744.58      2763453.17      6886637.02
      2763334.02      6886567.34      2763165.24      6886201.30
      2762839.62      6885974.24      2762679.54      6885759.54
      2762670.56      6885558.53      2762526.00      6885461.00

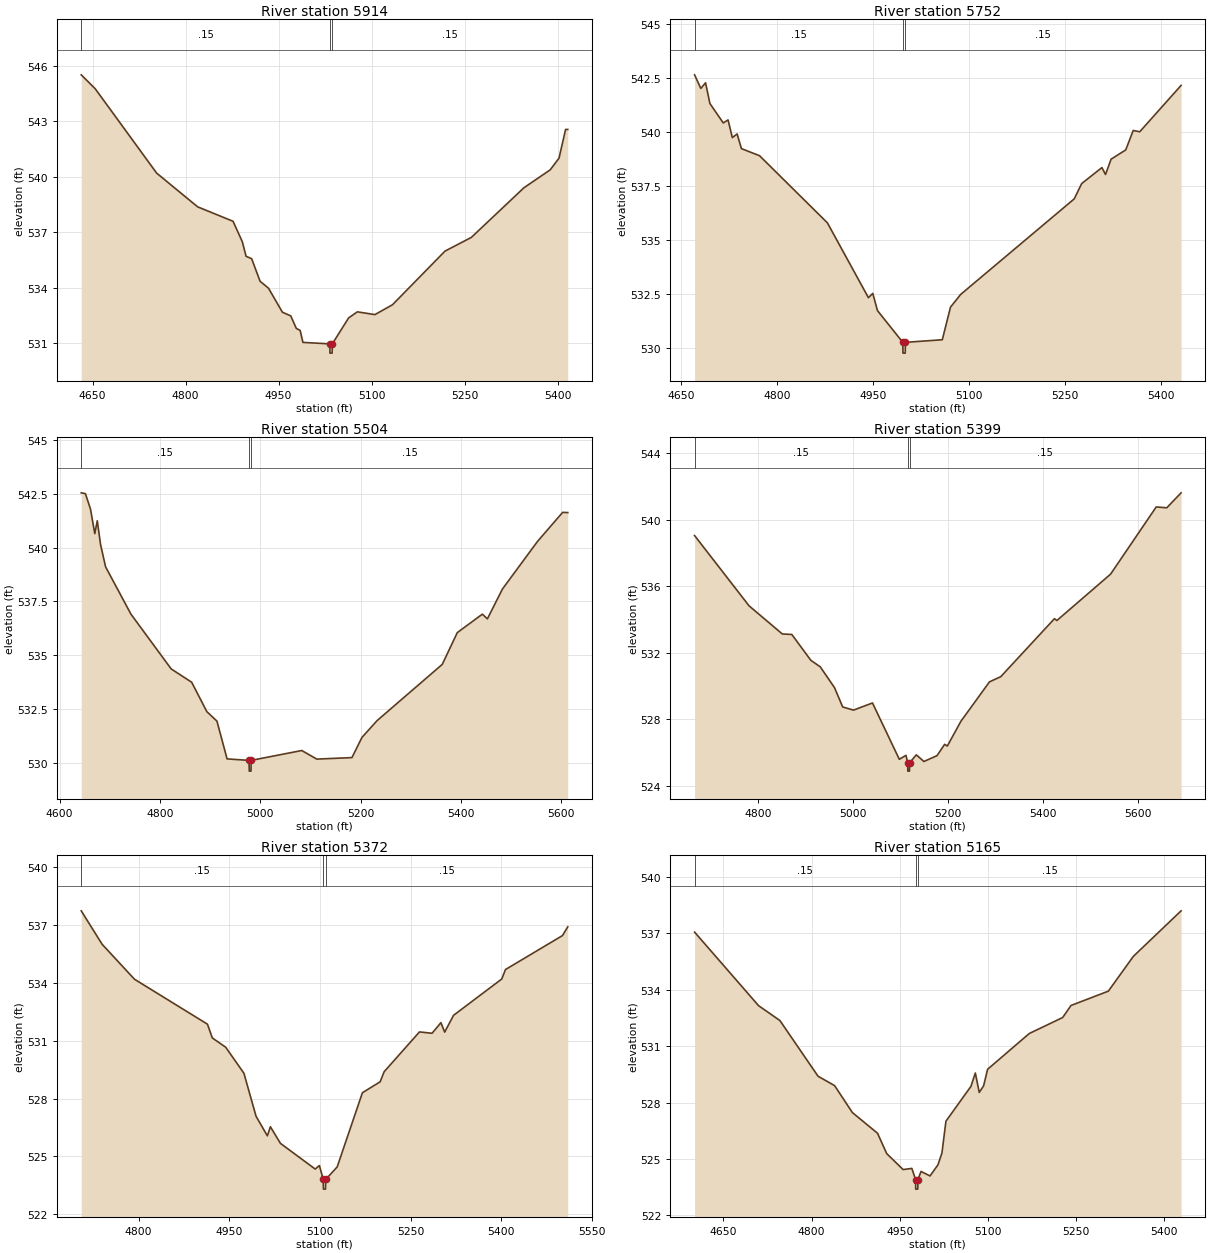
Type RM Length L Ch R = 1,5914,162,162,162
BEGIN DESCRIPTION:
Lacy 060 63
END DESCRIPTION:
XS GIS Cut Line= 3
      2766726.01      6888110.99      2766526.00      6888411.00
      2766226.02      6888710.98
#Sta/Elev= 30
  4631.7  545.50  4654.2  544.75  4753.4  540.19  4819.5  538.37  4876.6  537.59
  4891.6  536.48  4897.6  535.70  4906.6  535.57  4920.2  534.35  4933.7  533.98
  4956.2  532.68  4969.7  532.48  4978.7  531.80  4984.8  531.70  4989.3  531.05
  5032.7  530.97  5032.9  530.47  5036.4  530.47  5036.7  530.97  5063.0  532.37
  5077.1  532.70  5105.4  532.55  5133.7  533.08  5218.5  535.98  5261.0  536.72
  5345.8  539.40  5388.2  540.37  5402.4  541.00  5413.0  542.55  5416.5  542.55
#Mann=3,-1,0
  4631.7    0.15       0  5032.7    0.05       0  5036.7    0.15       0
Bank Sta=5032.7,5036.7
Exp/Cntr=0.3,0.1

Type RM Length L Ch R = 1,5752,248,248,248
BEGIN DESCRIPTION:
Lacy 060 2497
END DESCRIPTION:
XS GIS Cut Line= 3
      2766649.04      6888120.16      2766401.43      6888344.41
      2766191.49      6888716.39
#Sta/Elev= 30
  4670.7  542.64  4680.5  542.01  4687.9  542.27  4694.7  541.31  4715.6  540.41
  4723.1  540.55  4729.8  539.73  4737.3  539.90  4744.0  539.22  4772.4  538.89
  4878.5  535.78  4942.7  532.31  4949.5  532.51  4956.9  531.71  4996.5  530.24
  4996.8  529.74  5000.3  529.74  5000.5  530.24  5058.3  530.36  5071.1  531.87
  5087.0  532.46  5264.7  536.89  5276.4  537.60  5308.0  538.34  5313.7  538.02
  5322.4  538.73  5345.3  539.16  5357.0  540.06  5367.2  540.00  5431.9  542.15
#Mann=3,-1,0
  4670.7    0.15       0  4996.5    0.05       0  5000.5    0.15       0
Bank Sta=4996.5,5000.5
Exp/Cntr=0.3,0.1

Type RM Length L Ch R = 1,5504,105,105,105
BEGIN DESCRIPTION:
Lacy 060 2496
END DESCRIPTION:
XS GIS Cut Line= 4
      2766614.21      6888102.01      2766259.56      6888148.68
      2766191.86      6888157.41      2766191.66      6888701.23
#Sta/Elev= 30
  4643.2  542.56  4651.5  542.52  4661.6  541.81  4670.2  540.66  4675.2  541.26
  4681.7  540.15  4691.8  539.11  4742.3  536.91  4822.5  534.36  4863.3  533.74
  4893.6  532.37  4913.7  531.93  4933.9  530.17  4977.8  530.10  4978.1  529.60
  4981.6  529.60  4981.8  530.10  5082.8  530.56  5112.8  530.16  5182.8  530.23
  5202.8  531.17  5232.8  531.95  5362.8  534.57  5392.8  536.05  5442.8  536.91
  5452.8  536.69  5482.8  538.08  5552.8  540.30  5602.8  541.65  5613.0  541.64
#Mann=3,-1,0
  4643.2    0.15       0  4977.8    0.05       0  4981.8    0.15       0
Bank Sta=4977.8,4981.8
Exp/Cntr=0.3,0.1

Type RM Length L Ch R = 1,5399,27,27,27
BEGIN DESCRIPTION:
Lacy 060 2495
END DESCRIPTION:
XS GIS Cut Line= 4
      2766550.89      6888053.69      2766118.05      6888056.87
      2766062.76      6888157.69      2766103.85      6888633.18
#Sta/Elev= 30
  4666.4  539.05  4781.3  534.82  4851.3  533.13  4871.3  533.10  4911.3  531.55
  4931.3  531.15  4961.3  529.90  4978.5  528.74  5001.3  528.55  5041.3  528.98
  5097.8  525.59  5111.8  525.83  5115.5  525.38  5115.7  524.88  5119.2  524.88
  5119.5  525.38  5133.6  525.86  5149.6  525.46  5177.2  525.81  5193.3  526.49
  5199.0  526.39  5227.6  527.88  5287.8  530.25  5311.5  530.56  5424.7  534.05
  5429.8  533.94  5543.0  536.73  5639.1  540.77  5661.3  540.72  5691.5  541.62
#Mann=3,-1,0
  4666.4    0.15       0  5115.5    0.05       0  5119.5    0.15       0
Bank Sta=5115.5,5119.5
Exp/Cntr=0.3,0.1

Type RM Length L Ch R = 1,5372,207,207,207
BEGIN DESCRIPTION:
Lacy 060 2493
END DESCRIPTION:
XS GIS Cut Line= 3
      2766493.51      6888002.05      2766106.62      6888044.47
      2765770.06      6888288.27
#Sta/Elev= 30
  4705.0  537.72  4739.5  535.99  4793.0  534.18  4913.8  531.85  4921.8  531.14
  4943.9  530.66  4974.1  529.31  4994.2  527.08  5012.9  526.07  5017.9  526.54
  5034.5  525.68  5092.0  524.35  5099.0  524.53  5105.3  523.81  5105.6  523.31
  5109.1  523.31  5109.3  523.81  5128.4  524.46  5170.1  528.30  5199.5  528.87
  5206.1  529.39  5264.5  531.45  5285.3  531.38  5300.0  531.93  5306.2  531.44
  5320.9  532.31  5400.6  534.19  5406.8  534.68  5501.1  536.44  5509.8  536.89
#Mann=3,-1,0
  4705.0    0.15       0  5105.3    0.05       0  5109.3    0.15       0
Bank Sta=5105.3,5109.3
Exp/Cntr=0.3,0.1

Type RM Length L Ch R = 1,5165,182,182,182
BEGIN DESCRIPTION:
Lacy 060 2492
END DESCRIPTION:
XS GIS Cut Line= 3
      2766370.67      6887747.90      2766022.25      6887955.80
      2765710.55      6888240.37
#Sta/Elev= 30
  4601.0  537.06  4709.9  533.15  4746.2  532.36  4811.1  529.40  4839.3  528.90
  4869.5  527.47  4912.3  526.37  4927.9  525.29  4955.8  524.44  4970.7  524.50
  4977.1  523.90  4977.3  523.40  4980.8  523.40  4981.1  523.90  4986.3  524.34
  5001.6  524.10  5015.1  524.69  5021.9  525.32  5028.7  527.01  5071.2  528.86
  5078.7  529.57  5085.4  528.54  5092.8  528.89  5099.6  529.77  5170.5  531.67
  5227.3  532.52  5241.5  533.16  5305.0  533.92  5347.6  535.77  5428.8  538.19
#Mann=3,-1,0
  4601.0    0.15       0  4977.1    0.05       0  4981.1    0.15       0
Bank Sta=4977.1,4981.1
Exp/Cntr=0.3,0.1

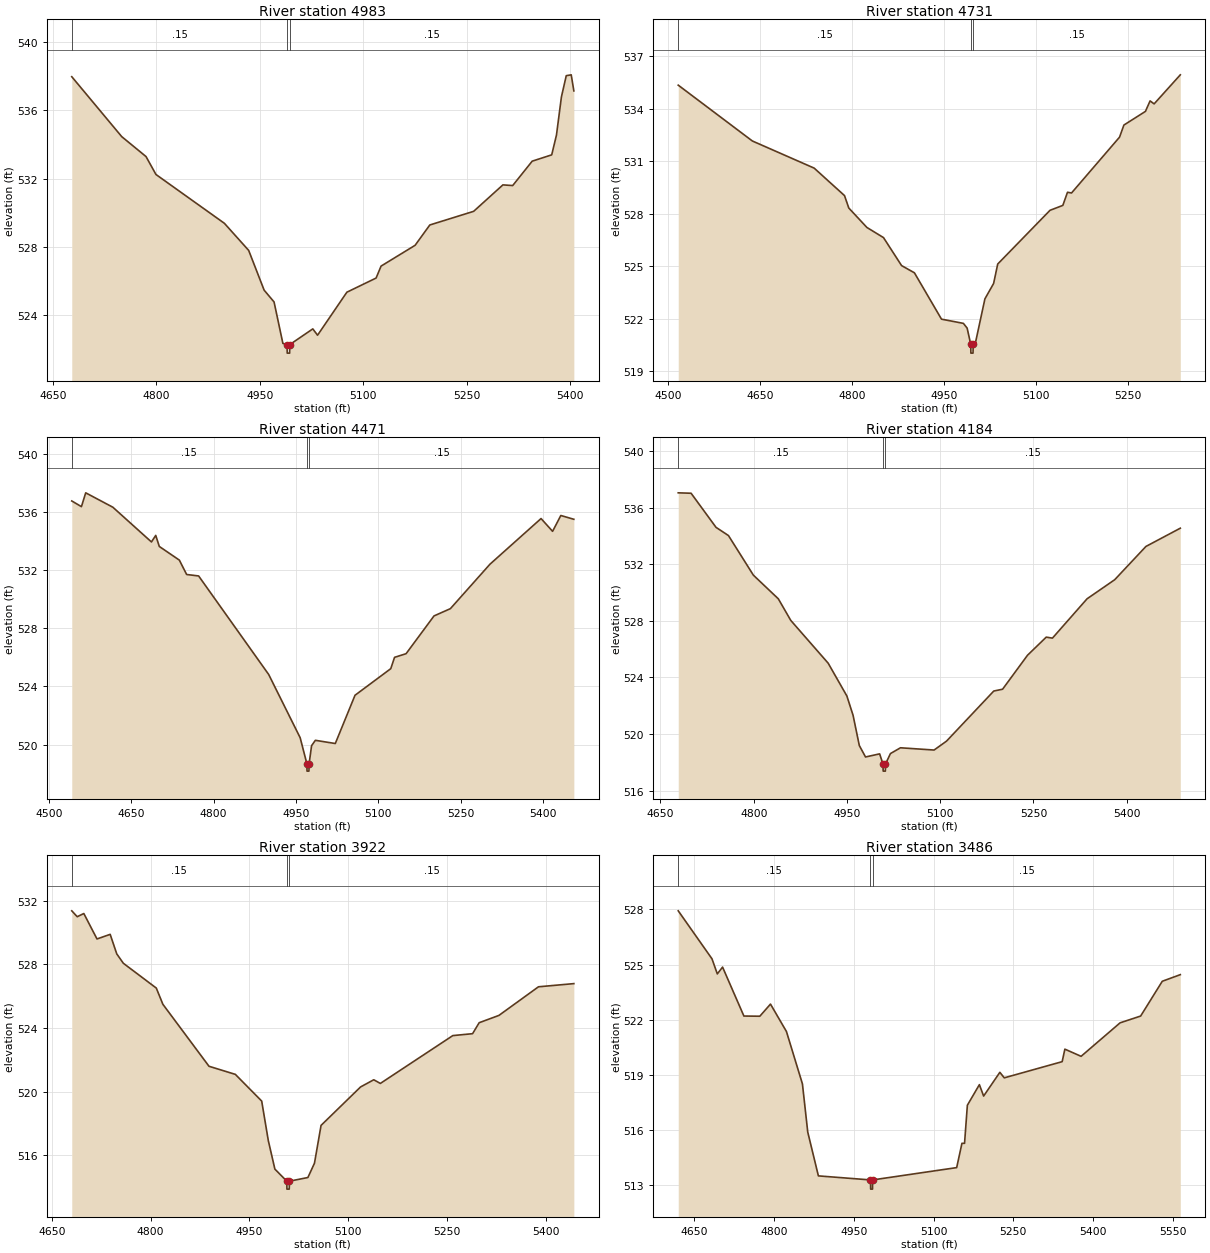
Type RM Length L Ch R = 1,4983,252,252,252
BEGIN DESCRIPTION:
Lacy 060 2491
END DESCRIPTION:
XS GIS Cut Line= 3
      2766275.27      6887568.94      2766016.43      6887775.54
      2765740.94      6888061.42
#Sta/Elev= 30
  4677.3  537.98  4749.7  534.47  4785.0  533.30  4799.4  532.25  4898.6  529.39
  4933.9  527.80  4956.3  525.47  4970.7  524.78  4983.5  522.35  4989.5  522.28
  4989.8  521.78  4993.3  521.78  4993.5  522.28  5026.9  523.20  5033.8  522.83
  5076.3  525.35  5118.7  526.18  5125.9  526.88  5175.3  528.10  5196.6  529.29
  5260.2  530.09  5302.6  531.64  5316.8  531.60  5345.1  533.03  5373.4  533.40
  5380.3  534.56  5387.5  536.80  5394.5  538.04  5401.7  538.09  5405.5  537.15
#Mann=3,-1,0
  4677.3    0.15       0  4989.5    0.05       0  4993.5    0.15       0
Bank Sta=4989.5,4993.5
Exp/Cntr=0.3,0.1

Type RM Length L Ch R = 1,4731,260,260,260
BEGIN DESCRIPTION:
Lacy 060 2490
END DESCRIPTION:
XS GIS Cut Line= 3
      2766226.81      6887333.93      2765832.60      6887615.15
      2765581.71      6887836.62
#Sta/Elev= 30
  4515.9  535.34  4636.8  532.15  4737.6  530.60  4787.1  529.03  4794.1  528.32
  4823.6  527.21  4850.7  526.63  4880.2  525.03  4901.1  524.62  4945.3  521.97
  4981.0  521.73  4987.1  521.46  4993.0  520.53  4993.2  520.03  4996.7  520.03
  4997.0  520.53  5000.1  520.53  5016.1  523.13  5030.3  524.01  5037.0  525.12
  5122.3  528.19  5143.2  528.47  5150.8  529.22  5157.4  529.18  5235.7  532.37
  5242.8  533.06  5277.9  533.84  5285.5  534.44  5292.1  534.27  5334.8  535.93
#Mann=3,-1,0
  4515.9    0.15       0  4993.0    0.05       0  4997.0    0.15       0
Bank Sta=4993,4997
Exp/Cntr=0.3,0.1

Type RM Length L Ch R = 1,4471,287,287,287
BEGIN DESCRIPTION:
Lacy 060 2488
END DESCRIPTION:
XS GIS Cut Line= 3
      2766066.66      6887106.56      2765711.67      6887402.62
      2765458.91      6887777.41
#Sta/Elev= 30
  4541.6  536.76  4559.2  536.37  4567.0  537.32  4616.4  536.33  4686.7  533.94
  4694.5  534.39  4701.0  533.63  4737.5  532.69  4750.8  531.70  4772.6  531.60
  4900.2  524.82  4957.5  520.47  4969.8  518.67  4970.0  518.17  4973.5  518.17
  4973.8  518.67  4978.3  519.92  4985.2  520.29  5021.5  520.07  5057.4  523.39
  5122.5  525.22  5129.4  526.00  5150.4  526.25  5201.3  528.85  5231.1  529.35
  5303.2  532.41  5396.2  535.55  5417.2  534.67  5432.2  535.76  5455.9  535.50
#Mann=3,-1,0
  4541.6    0.15       0  4969.8    0.05       0  4973.8    0.15       0
Bank Sta=4969.8,4973.8
Exp/Cntr=0.3,0.1

Type RM Length L Ch R = 1,4184,262,262,262
BEGIN DESCRIPTION:
Lacy 060 2489
END DESCRIPTION:
XS GIS Cut Line= 3
      2765505.93      6886940.39      2765483.30      6887263.65
      2765451.02      6887746.22
#Sta/Elev= 30
  4678.6  537.05  4699.3  537.02  4739.4  534.61  4759.4  534.03  4799.5  531.23
  4839.6  529.56  4859.7  528.03  4919.8  525.01  4949.9  522.69  4959.9  521.32
  4969.9  519.19  4979.9  518.38  5002.6  518.60  5008.0  517.88  5008.3  517.38
  5011.8  517.38  5012.0  517.88  5020.0  518.62  5036.1  519.03  5090.2  518.87
  5110.2  519.50  5186.2  523.04  5200.4  523.17  5240.5  525.57  5270.6  526.85
  5280.6  526.78  5336.3  529.56  5380.8  530.91  5431.0  533.26  5486.3  534.55
#Mann=3,-1,0
  4678.6    0.15       0  5008.0    0.05       0  5012.0    0.15       0
Bank Sta=5008,5012
Exp/Cntr=0.3,0.1

Type RM Length L Ch R = 1,3922,436,436,436
BEGIN DESCRIPTION:
Lacy 060 2487
END DESCRIPTION:
XS GIS Cut Line= 3
      2765246.21      6886942.66      2765248.59      6887263.06
      2765252.39      6887704.73
#Sta/Elev= 30
  4680.4  531.37  4688.7  531.00  4698.7  531.20  4718.7  529.60  4738.7  529.89
  4748.7  528.66  4758.7  528.07  4808.7  526.51  4818.7  525.49  4888.7  521.59
  4928.7  521.08  4968.7  519.40  4978.7  516.92  4988.7  515.12  5006.8  514.36
  5007.0  513.86  5010.5  513.86  5010.8  514.36  5038.8  514.59  5048.8  515.49
  5058.8  517.87  5118.8  520.29  5138.8  520.74  5148.8  520.51  5258.8  523.52
  5288.8  523.64  5298.8  524.33  5328.8  524.79  5388.8  526.59  5442.5  526.79
#Mann=3,-1,0
  4680.4    0.15       0  5006.8    0.05       0  5010.8    0.15       0
Bank Sta=5006.8,5010.8
Exp/Cntr=0.3,0.1

Type RM Length L Ch R = 1,3486,185,185,185
BEGIN DESCRIPTION:
Lacy 060 2485
END DESCRIPTION:
XS GIS Cut Line= 3
      2764853.90      6886967.56      2764836.25      6887505.76
      2764913.00      6887904.25
#Sta/Elev= 30
  4619.8  527.92  4683.3  525.31  4693.3  524.49  4703.2  524.86  4743.3  522.20
  4773.3  522.19  4793.3  522.85  4823.3  521.36  4853.4  518.51  4863.4  515.89
  4883.4  513.51  4981.4  513.29  4981.7  512.79  4985.2  512.79  4985.4  513.29
  5143.5  513.96  5153.4  515.28  5158.3  515.28  5163.6  517.35  5186.2  518.47
  5194.2  517.85  5224.7  519.14  5233.0  518.84  5341.9  519.72  5347.0  520.40
  5377.5  520.01  5450.8  521.83  5489.5  522.20  5530.2  524.09  5564.1  524.45
#Mann=3,-1,0
  4619.8    0.15       0  4981.4    0.05       0  4985.4    0.15       0
Bank Sta=4981.4,4985.4
Exp/Cntr=0.3,0.1

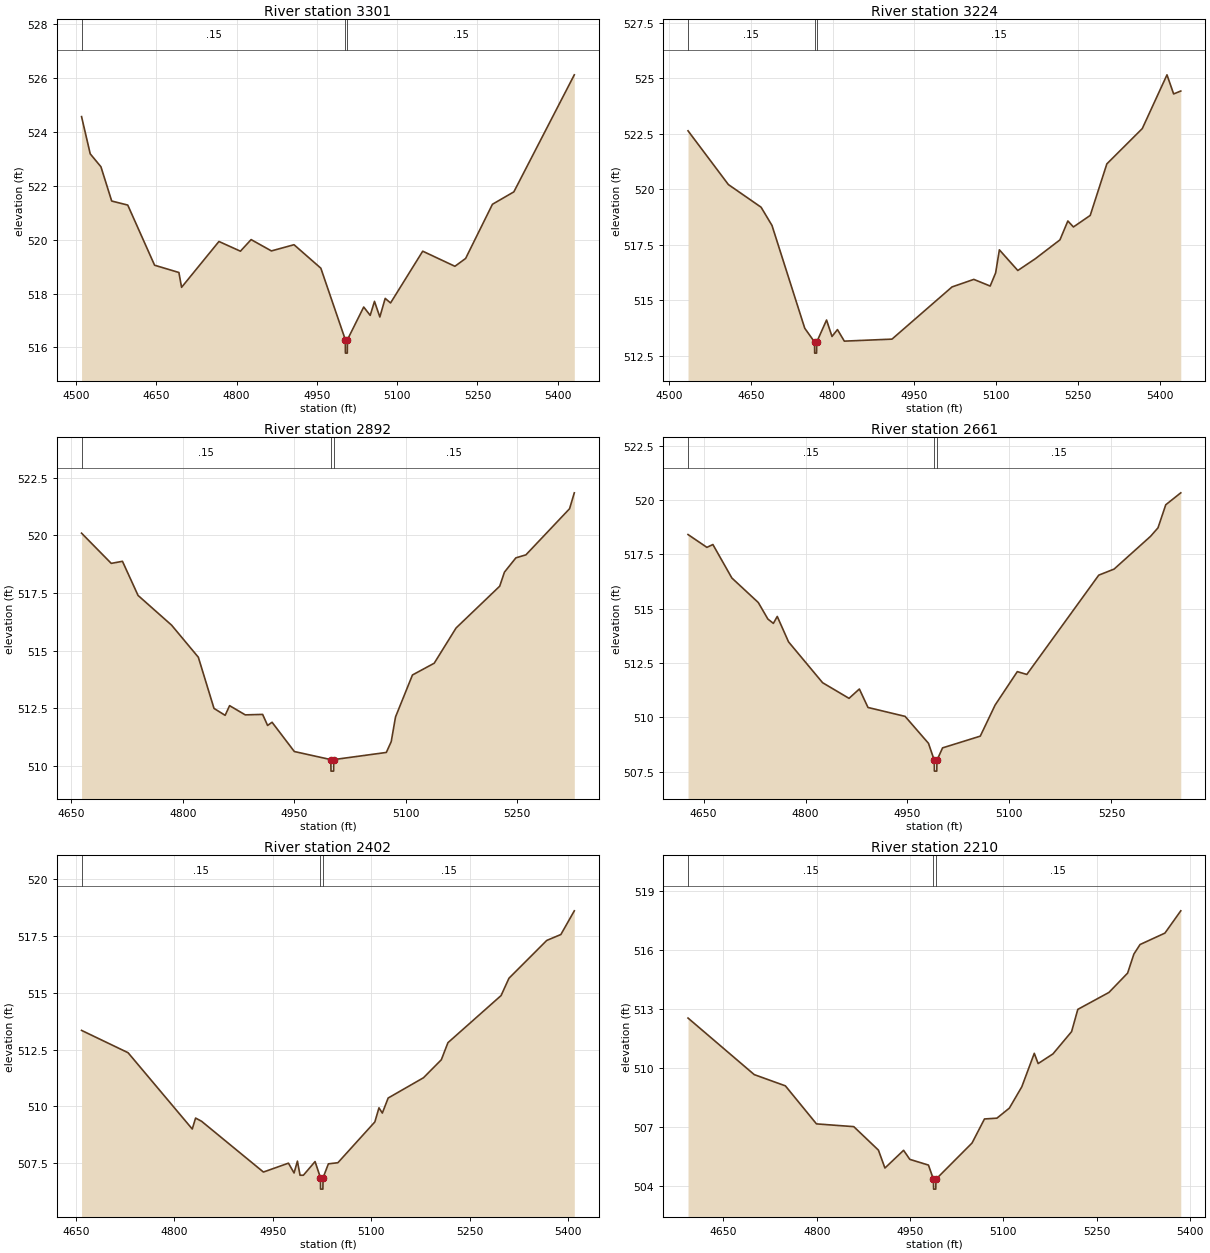
Type RM Length L Ch R = 1,3301,77,77,77
BEGIN DESCRIPTION:
Lacy 060 2484
END DESCRIPTION:
XS GIS Cut Line= 3
      2764801.39      6887014.82      2764773.04      6887511.13
      2764750.94      6887933.73
#Sta/Elev= 30
  4510.6  524.56  4526.8  523.18  4546.8  522.70  4566.9  521.43  4596.9  521.28
  4647.0  519.05  4692.4  518.78  4697.4  518.23  4767.2  519.93  4807.3  519.57
  4827.3  520.00  4865.2  519.58  4907.4  519.81  4957.5  518.94  5003.2  516.29
  5003.4  515.79  5006.9  515.79  5007.2  516.29  5037.6  517.50  5049.7  517.19
  5057.7  517.71  5067.7  517.13  5077.7  517.82  5087.7  517.65  5147.8  519.57
  5207.9  519.01  5227.9  519.30  5278.0  521.31  5318.0  521.77  5430.9  526.11
#Mann=3,-1,0
  4510.6    0.15       0  5003.2    0.05       0  5007.2    0.15       0
Bank Sta=5003.2,5007.2
Exp/Cntr=0.3,0.1

Type RM Length L Ch R = 1,3224,332,332,332
BEGIN DESCRIPTION:
Lacy 060 2486
END DESCRIPTION:
XS GIS Cut Line= 3
      2764728.72      6886987.01      2764713.16      6887559.88
      2764646.51      6887883.82
#Sta/Elev= 30
  4534.8  522.64  4608.8  520.22  4668.8  519.20  4688.8  518.38  4748.9  513.75
  4766.9  513.13  4767.1  512.63  4770.6  512.63  4770.9  513.13  4788.9  514.12
  4798.9  513.38  4808.9  513.69  4821.5  513.17  4908.9  513.26  5019.0  515.61
  5059.0  515.95  5089.0  515.65  5099.0  516.24  5105.9  517.28  5139.7  516.35
  5171.8  516.88  5217.0  517.73  5231.5  518.58  5241.7  518.31  5272.5  518.83
  5303.0  521.15  5368.0  522.74  5413.3  525.16  5425.5  524.30  5438.6  524.43
#Mann=3,-1,0
  4534.8    0.15       0  4766.9    0.05       0  4770.9    0.15       0
Bank Sta=4766.9,4770.9
Exp/Cntr=0.3,0.1

Type RM Length L Ch R = 1,2892,231,231,231
BEGIN DESCRIPTION:
Lacy 060 2483
END DESCRIPTION:
XS GIS Cut Line= 3
      2764649.95      6886967.81      2764461.06      6887252.35
      2764291.79      6887526.47
#Sta/Elev= 30
  4663.6  520.10  4703.6  518.79  4718.7  518.88  4739.7  517.40  4784.9  516.11
  4820.9  514.72  4842.0  512.50  4857.0  512.20  4863.0  512.62  4884.1  512.22
  4907.5  512.24  4914.2  511.76  4920.2  511.90  4950.2  510.63  4999.3  510.28
  4999.6  509.78  5003.1  509.78  5003.3  510.28  5074.1  510.59  5080.7  511.06
  5086.5  512.13  5109.3  513.95  5138.6  514.46  5168.1  515.99  5226.8  517.80
  5233.2  518.41  5248.6  519.03  5262.1  519.16  5320.9  521.16  5327.3  521.85
#Mann=3,-1,0
  4663.6    0.15       0  4999.3    0.05       0  5003.3    0.15       0
Bank Sta=4999.3,5003.3
Exp/Cntr=0.3,0.1

Type RM Length L Ch R = 1,2661,259,259,259
BEGIN DESCRIPTION:
Lacy 060 2482
END DESCRIPTION:
XS GIS Cut Line= 3
      2764449.03      6886786.22      2764277.92      6887123.15
      2764140.26      6887441.80
#Sta/Elev= 30
  4627.1  518.41  4654.9  517.82  4663.7  517.95  4691.6  516.41  4730.5  515.28
  4744.6  514.52  4752.7  514.32  4758.4  514.64  4775.0  513.47  4825.1  511.59
  4864.0  510.87  4879.2  511.30  4891.9  510.45  4946.5  510.04  4980.9  508.80
  4989.4  508.02  4989.6  507.52  4993.1  507.52  4993.4  508.02  5001.6  508.59
  5057.1  509.13  5078.9  510.56  5111.6  512.10  5125.6  511.97  5231.4  516.54
  5254.0  516.82  5307.7  518.33  5318.6  518.72  5330.0  519.78  5352.1  520.33
#Mann=3,-1,0
  4627.1    0.15       0  4989.4    0.05       0  4993.4    0.15       0
Bank Sta=4989.4,4993.4
Exp/Cntr=0.3,0.1

Type RM Length L Ch R = 1,2402,192,192,192
BEGIN DESCRIPTION:
Lacy 060 2481
END DESCRIPTION:
XS GIS Cut Line= 3
      2764143.31      6886631.44      2764079.46      6886960.68
      2764015.09      6887371.29
#Sta/Elev= 30
  4658.7  513.34  4729.6  512.36  4827.4  509.01  4832.5  509.49  4841.6  509.35
  4935.9  507.12  4974.0  507.51  4982.6  507.08  4987.7  507.60  4991.7  506.98
  4996.8  506.98  5014.6  507.58  5022.8  506.87  5023.0  506.37  5026.5  506.37
  5026.8  506.87  5034.9  507.48  5049.4  507.53  5105.7  509.32  5112.0  509.94
  5117.1  509.71  5126.0  510.37  5179.8  511.26  5207.0  512.05  5217.1  512.80
  5298.1  514.87  5310.1  515.63  5367.7  517.29  5389.2  517.55  5409.7  518.59
#Mann=3,-1,0
  4658.7    0.15       0  5022.8    0.05       0  5026.8    0.15       0
Bank Sta=5022.8,5026.8
Exp/Cntr=0.3,0.1

Type RM Length L Ch R = 1,2210,323,323,323
BEGIN DESCRIPTION:
Lacy 060 2471
END DESCRIPTION:
XS GIS Cut Line= 3
      2763903.13      6886554.57      2763887.31      6886959.42
      2763871.94      6887346.45
#Sta/Elev= 30
  4593.0  512.53  4699.5  509.66  4749.6  509.09  4799.6  507.16  4859.6  507.02
  4899.2  505.83  4909.7  504.92  4939.7  505.82  4949.7  505.36  4979.7  505.07
  4987.7  504.35  4988.0  503.85  4991.5  503.85  4991.7  504.35  5049.8  506.19
  5069.8  507.41  5089.8  507.45  5109.8  507.96  5129.8  509.04  5149.9  510.74
  5156.1  510.22  5179.9  510.71  5209.9  511.84  5219.9  512.97  5270.0  513.83
  5300.0  514.81  5310.0  515.77  5320.0  516.26  5360.0  516.84  5385.5  517.97
#Mann=3,-1,0
  4593.0    0.15       0  4987.7    0.05       0  4991.7    0.15       0
Bank Sta=4987.7,4991.7
Exp/Cntr=0.3,0.1

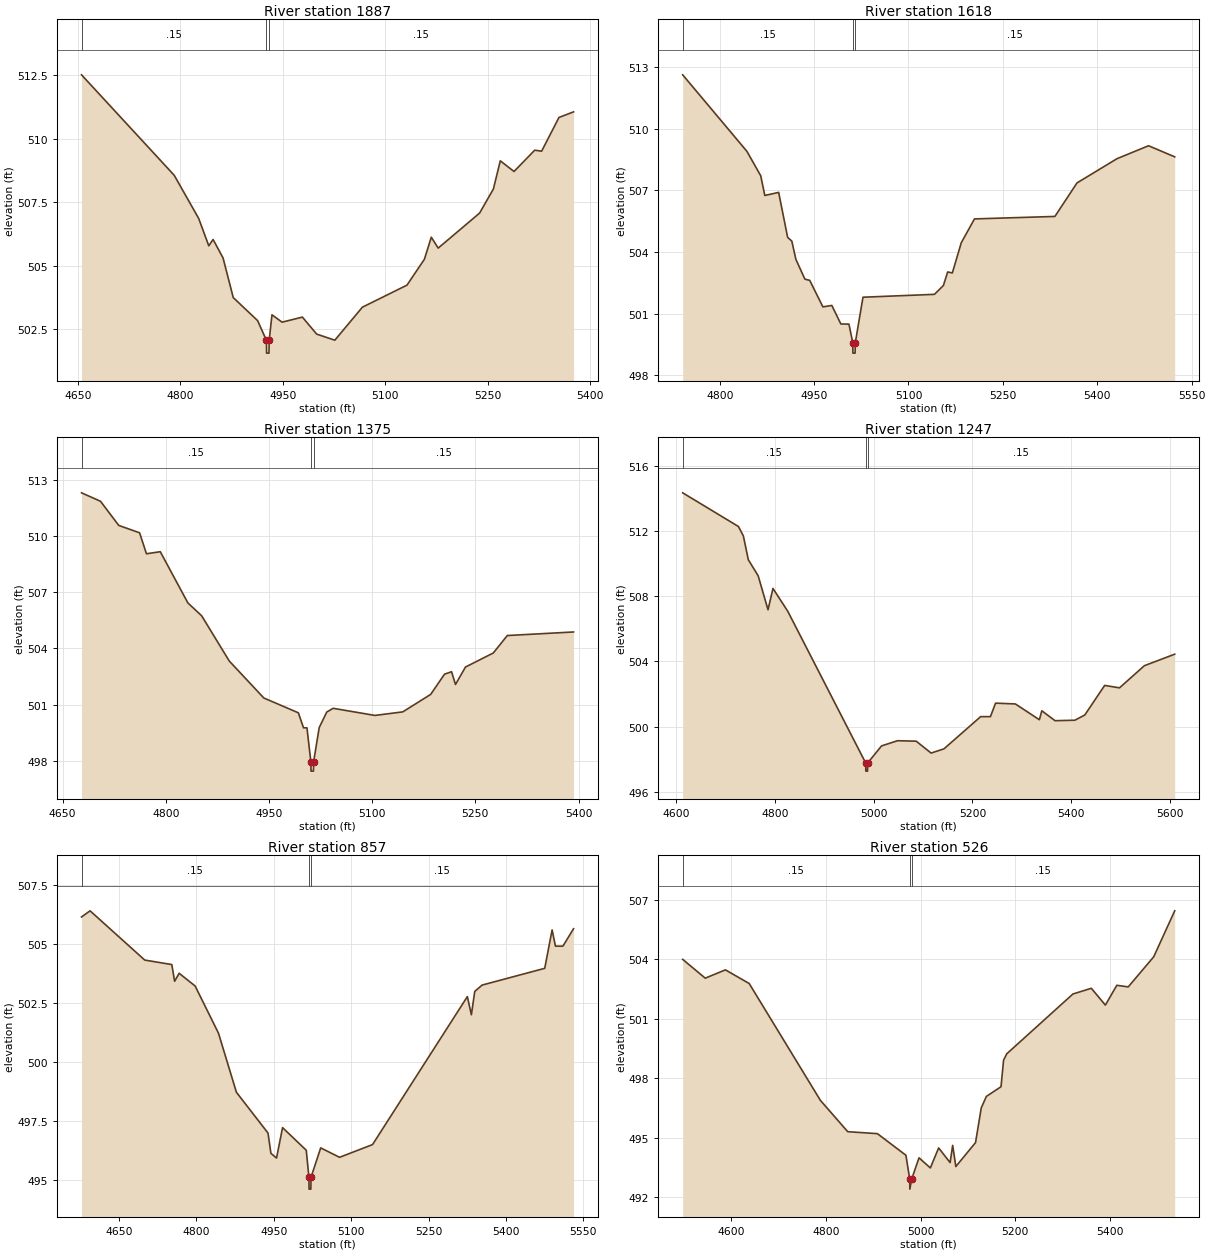
Type RM Length L Ch R = 1,1887,269,269,269
BEGIN DESCRIPTION:
Lacy 060 2470
END DESCRIPTION:
XS GIS Cut Line= 3
      2763817.37      6886522.98      2763618.14      6886809.06
      2763568.14      6887177.27
#Sta/Elev= 30
  4655.5  512.52  4791.2  508.56  4827.0  506.86  4841.8  505.78  4848.1  506.03
  4862.7  505.30  4877.6  503.74  4913.3  502.83  4926.2  502.05  4926.4  501.55
  4929.9  501.55  4930.2  502.05  4934.3  503.06  4949.1  502.77  4978.8  502.97
  4999.7  502.30  5026.3  502.06  5066.6  503.36  5131.9  504.23  5157.4  505.25
  5167.5  506.12  5177.6  505.69  5238.2  507.07  5258.4  508.02  5268.5  509.13
  5288.6  508.71  5318.9  509.55  5329.0  509.51  5354.4  510.84  5375.7  511.06
#Mann=3,-1,0
  4655.5    0.15       0  4926.2    0.05       0  4930.2    0.15       0
Bank Sta=4926.2,4930.2
Exp/Cntr=0.3,0.1

Type RM Length L Ch R = 1,1618,243,243,243
BEGIN DESCRIPTION:
Lacy 060 2469
END DESCRIPTION:
XS GIS Cut Line= 3
      2763642.74      6886463.32      2763441.96      6886635.02
      2763056.45      6886980.57
#Sta/Elev= 30
  4741.2  512.62  4843.2  508.90  4865.2  507.71  4871.7  506.75  4893.7  506.90
  4908.0  504.71  4914.6  504.53  4921.1  503.64  4935.4  502.68  4943.1  502.62
  4964.0  501.33  4978.2  501.40  4992.5  500.50  5005.4  500.49  5011.5  499.58
  5011.7  499.08  5015.2  499.08  5015.5  499.58  5027.7  501.80  5141.3  501.94
  5155.5  502.37  5162.3  503.03  5169.7  502.98  5183.9  504.45  5204.9  505.61
  5332.7  505.73  5367.8  507.36  5431.4  508.54  5481.5  509.17  5523.1  508.63
#Mann=3,-1,0
  4741.2    0.15       0  5011.5    0.05       0  5015.5    0.15       0
Bank Sta=5011.5,5015.5
Exp/Cntr=0.3,0.1

Type RM Length L Ch R = 1,1375,128,128,128
BEGIN DESCRIPTION:
Lacy 060 2467
END DESCRIPTION:
XS GIS Cut Line= 3
      2763610.05      6886443.75      2763286.19      6886471.74
      2762900.85      6886532.73
#Sta/Elev= 30
  4677.5  512.30  4705.1  511.85  4731.7  510.56  4761.9  510.17  4771.9  509.05
  4792.0  509.16  4832.1  506.43  4852.2  505.74  4892.3  503.33  4942.5  501.36
  4992.7  500.57  5000.2  499.77  5005.2  499.77  5010.9  497.96  5011.1  497.46
  5014.6  497.46  5014.9  497.96  5023.0  499.78  5034.0  500.61  5043.3  500.81
  5104.0  500.43  5144.5  500.62  5185.0  501.55  5205.2  502.63  5215.4  502.76
  5221.1  502.08  5235.6  503.01  5276.1  503.76  5296.4  504.69  5392.7  504.88
#Mann=3,-1,0
  4677.5    0.15       0  5010.9    0.05       0  5014.9    0.15       0
Bank Sta=5010.9,5014.9
Exp/Cntr=0.3,0.1

Type RM Length L Ch R = 1,1247,390,390,390
BEGIN DESCRIPTION:
Lacy 060 2466
END DESCRIPTION:
XS GIS Cut Line= 3
      2763619.00      6886362.43      2763232.70      6886361.24
      2762624.70      6886423.71
#Sta/Elev= 30
  4612.7  514.37  4725.7  512.30  4735.7  511.72  4745.7  510.26  4765.7  509.27
  4785.7  507.18  4795.7  508.49  4825.7  507.09  4983.7  497.76  4984.0  497.26
  4987.5  497.26  4987.7  497.76  5015.8  498.81  5048.3  499.13  5086.2  499.10
  5116.3  498.37  5142.4  498.63  5216.8  500.61  5236.6  500.61  5247.0  501.44
  5287.2  501.39  5335.8  500.42  5340.8  500.97  5367.6  500.36  5407.8  500.39
  5427.9  500.71  5468.2  502.53  5498.3  502.38  5548.6  503.74  5610.2  504.45
#Mann=3,-1,0
  4612.7    0.15       0  4983.7    0.05       0  4987.7    0.15       0
Bank Sta=4983.7,4987.7
Exp/Cntr=0.3,0.1

Type RM Length L Ch R = 1,857,331,331,331
BEGIN DESCRIPTION:
Lacy 060 2468
END DESCRIPTION:
XS GIS Cut Line= 3
      2763376.33      6885899.01      2762997.20      6886081.80
      2762586.14      6886420.01
#Sta/Elev= 30
  4577.7  506.16  4594.3  506.42  4700.2  504.33  4752.6  504.14  4758.1  503.43
  4766.8  503.77  4797.8  503.23  4843.0  501.23  4877.8  498.72  4939.0  496.99
  4944.6  496.13  4955.5  495.93  4967.2  497.22  5013.1  496.26  5018.3  495.11
  5018.5  494.61  5022.0  494.61  5022.3  495.11  5041.1  496.36  5077.6  495.96
  5141.5  496.50  5325.2  502.78  5333.0  502.01  5339.5  503.00  5353.9  503.27
  5475.1  503.98  5489.4  505.61  5495.9  504.92  5510.3  504.92  5530.9  505.66
#Mann=3,-1,0
  4577.7    0.15       0  5018.3    0.05       0  5022.3    0.15       0
Bank Sta=5018.3,5022.3
Exp/Cntr=0.3,0.1

Type RM Length L Ch R = 1,526,140,140,140
BEGIN DESCRIPTION:
Lacy 060 62
END DESCRIPTION:
XS GIS Cut Line= 3
      2763276.00      6885811.00      2762776.00      6885861.00
      2762576.00      6886360.99
#Sta/Elev= 30
  4496.8  504.00  4544.5  503.05  4587.2  503.47  4637.5  502.78  4788.2  496.88
  4846.0  495.30  4908.8  495.20  4969.1  494.11  4977.2  492.90  4977.4  492.40
  4981.2  492.90  4996.8  493.98  5020.8  493.47  5038.3  494.48  5062.6  493.74
  5068.0  494.61  5074.7  493.54  5116.4  494.75  5128.5  496.50  5139.3  497.08
  5170.3  497.57  5175.7  498.91  5182.4  499.23  5322.4  502.25  5361.4  502.54
  5391.1  501.69  5415.3  502.69  5439.5  502.61  5493.4  504.13  5537.8  506.45
#Mann=3,-1,0
  4496.8    0.15       0  4977.2    0.05       0  4981.2    0.15       0
Bank Sta=4977.2,4981.2
Exp/Cntr=0.3,0.1

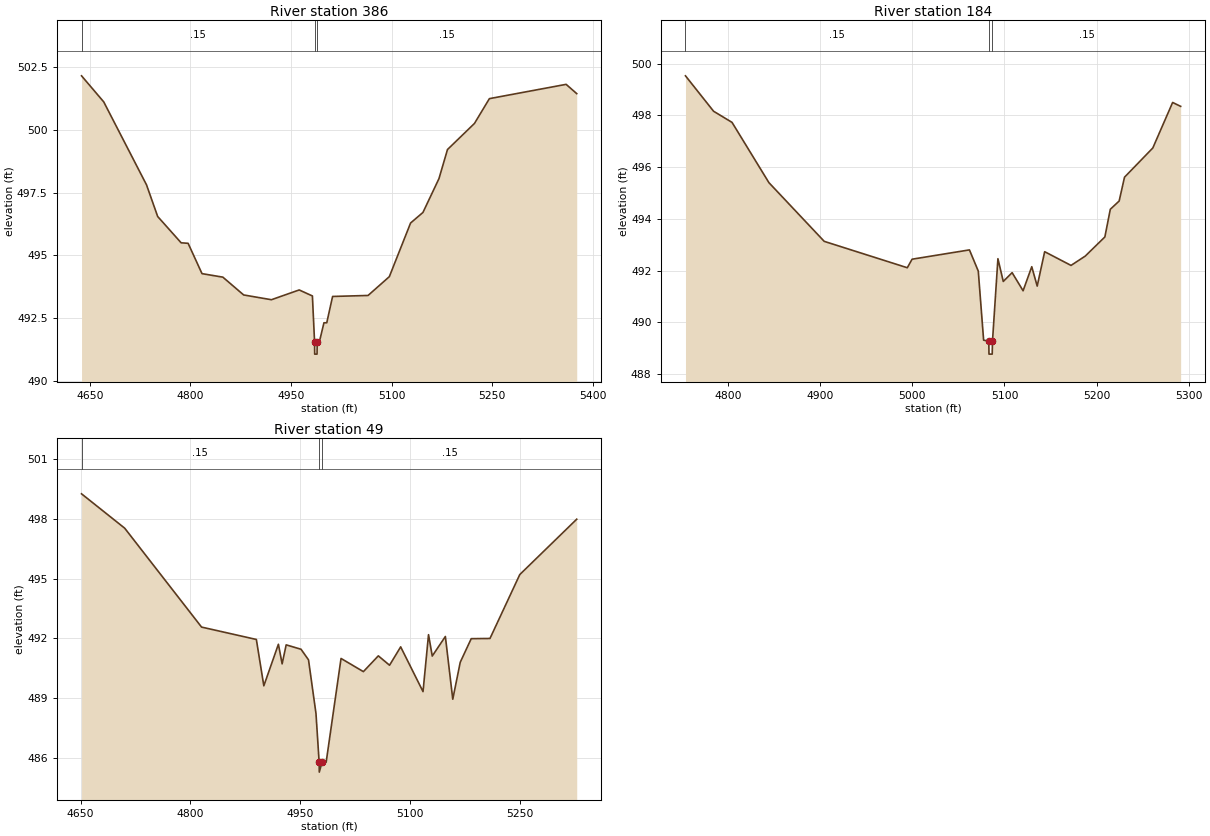
Type RM Length L Ch R = 1,386,202,202,202
BEGIN DESCRIPTION:
Lacy 060 2465
END DESCRIPTION:
XS GIS Cut Line= 3
      2763029.61      6885666.60      2762679.54      6885759.54
      2762557.33      6886115.23
#Sta/Elev= 30
  4637.8  502.16  4670.9  501.12  4734.7  497.81  4751.3  496.55  4786.3  495.50
  4796.7  495.48  4817.4  494.27  4848.5  494.13  4879.5  493.42  4920.9  493.23
  4962.3  493.62  4982.0  493.38  4985.2  491.56  4985.4  491.06  4988.9  491.06
  4989.2  491.56  4993.3  491.65  4999.2  492.31  5003.4  492.31  5012.1  493.36
  5065.0  493.40  5096.7  494.15  5128.4  496.29  5146.8  496.71  5170.7  498.06
  5183.4  499.22  5223.6  500.26  5245.9  501.25  5360.3  501.82  5376.1  501.45
#Mann=3,-1,0
  4637.8    0.15       0  4985.2    0.05       0  4989.2    0.15       0
Bank Sta=4985.2,4989.2
Exp/Cntr=0.3,0.1

Type RM Length L Ch R = 1,184,135,135,135
BEGIN DESCRIPTION:
Lacy 060 2464
END DESCRIPTION:
XS GIS Cut Line= 3
      2762916.50      6885553.25      2762670.56      6885558.53
      2762518.48      6885806.75
#Sta/Elev= 30
  4754.0  499.53  4784.5  498.16  4804.5  497.73  4844.5  495.40  4904.5  493.13
  4994.6  492.11  4999.8  492.44  5062.0  492.80  5071.6  491.98  5077.4  489.31
  5083.0  489.27  5083.2  488.77  5086.7  488.77  5087.0  489.27  5092.9  492.46
  5098.7  491.58  5108.3  491.92  5120.2  491.22  5129.6  492.15  5135.5  491.40
  5143.6  492.73  5172.2  492.20  5187.6  492.56  5208.9  493.30  5214.8  494.37
  5224.4  494.69  5230.2  495.61  5260.9  496.74  5282.4  498.50  5291.1  498.35
#Mann=3,-1,0
  4754.0    0.15       0  5083.0    0.05       0  5087.0    0.15       0
Bank Sta=5083,5087
Exp/Cntr=0.3,0.1

Type RM Length L Ch R = 1,49,0,0,0
BEGIN DESCRIPTION:
Lacy 060 3491
END DESCRIPTION:
XS GIS Cut Line= 3
      2762900.47      6885506.59      2762577.53      6885445.79
      2762515.07      6885787.42
#Sta/Elev= 30
  4651.4  499.24  4710.3  497.52  4815.2  492.57  4890.0  491.95  4900.2  489.63
  4920.1  491.71  4925.2  490.73  4930.7  491.68  4951.0  491.46  4961.2  490.93
  4971.4  488.24  4975.7  485.81  4975.9  485.31  4979.7  485.81  4985.3  485.81
  5005.6  491.00  5036.1  490.34  5056.5  491.13  5071.8  490.66  5087.0  491.58
  5117.5  489.34  5125.0  492.19  5130.1  491.12  5148.0  492.10  5158.1  488.96
  5168.3  490.81  5183.3  491.99  5208.9  492.00  5249.6  495.20  5327.3  497.97
#Mann=3,-1,0
  4651.4    0.15       0  4975.7    0.05       0  4979.7    0.15       0
Bank Sta=4975.7,4979.7
Exp/Cntr=0.3,0.1

Chan Stop Cuts=-1