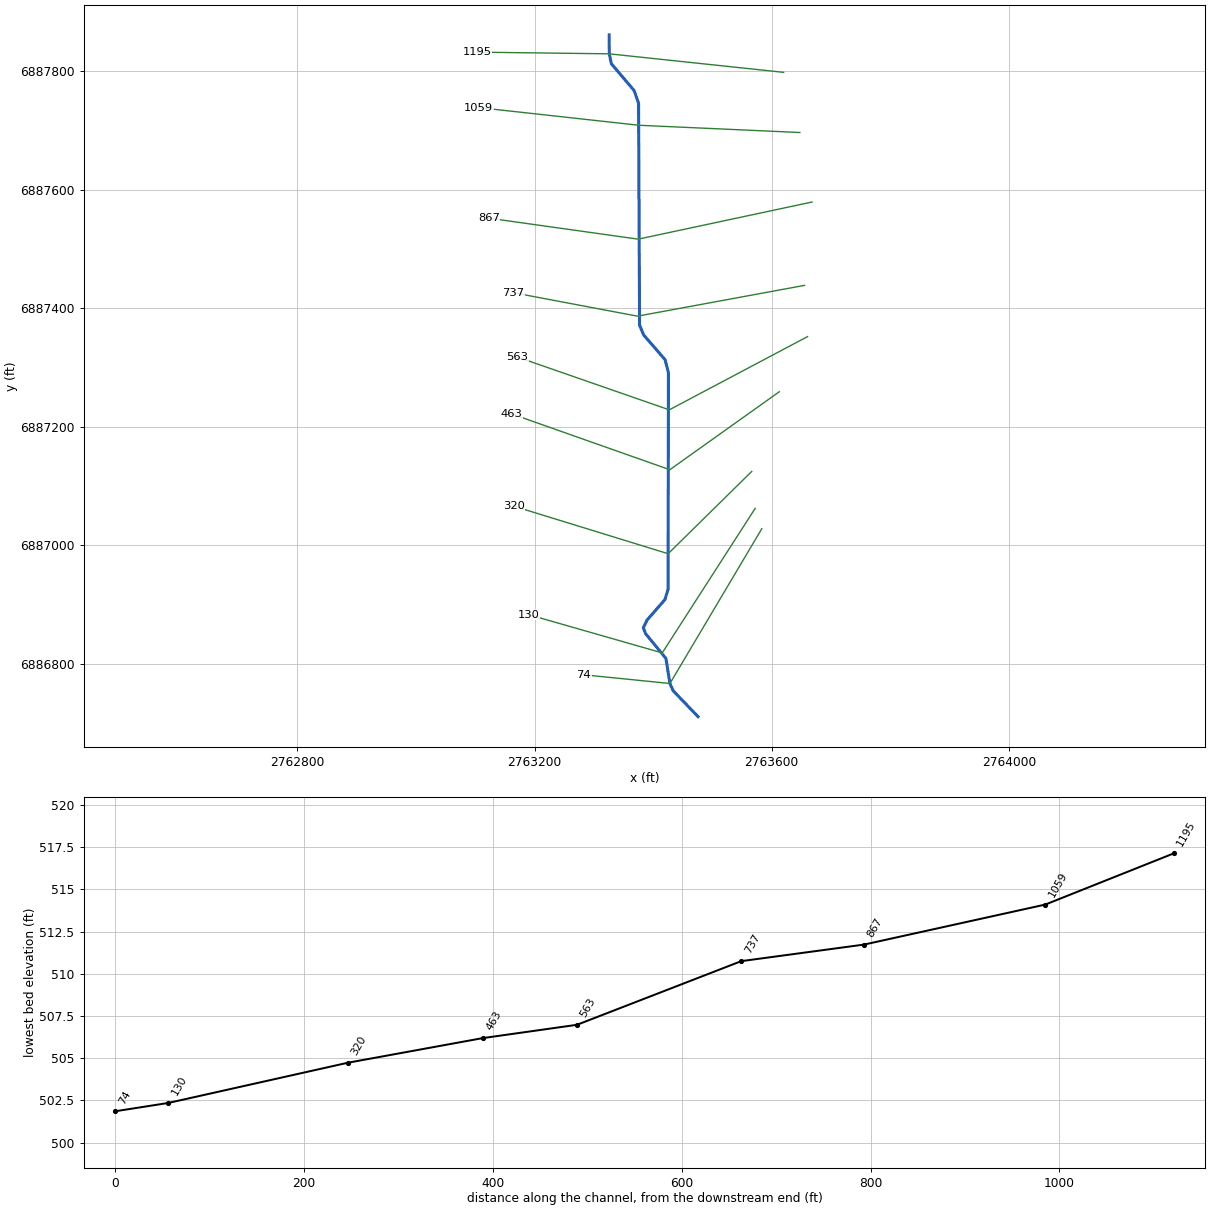
--- Lacy 061.prj (project) ---

Proj Title=Lacy 061 Base Level Engineering
Current Plan=p01
Default Exp/Contr=0.3,0.1
English Units
Geom File=g01
Flow File=f01
Plan File=p01
Y Axis Title=Elevation
X Axis Title(PF)=Main Channel Distance
X Axis Title(XS)=Station
BEGIN DESCRIPTION:
Lacy 061
END DESCRIPTION:
DSS Export Rating Curves= 0
DSS Export Rating Curve Sorted= 0
DSS Export Volume Flow Curves= 0
DXF OffsetX= 0
DXF OffsetY= 0
DXF ScaleX= 1
DXF ScaleY= 10

--- Lacy 061.p01 (plan) ---

Plan Title=Multiple Run
Short Identifier=Multiple
Geom File=g01
Flow File=f01
Subcritical Flow
K Sum by GR= 0
Std Step Tol= 0.01
Critical Tol= 0.01
Num of Std Step Trials= 20
Max Error Tol= 0.3
Flow Tol Ratio= 0.001
Split Flow NTrial= 30
Split Flow Tol= 0.02
Split Flow Ratio= 0.02
Log Output Level= 0
Friction Slope Method= 1
Unsteady Friction Slope Method= 2
Unsteady Bridges Friction Slope Method= 1
Parabolic Critical Depth
Global Vel Dist=  1 , 1 , 1
Global Log Level= 0
CheckData=True
Encroach Param= -1, 0, 0, 0
BEGIN DESCRIPTION:
Multiple Run
END DESCRIPTION:

--- Lacy 061.f01 (steady flow) ---

Flow Title=Multiple
Number of Profiles=7
Profile Names=10-year,25-year,50-year,1pct_min,100-year,1pct_plu,500-year
River Rch & RM= Lacy 061,Reach-1,1195
      53      59      64      34      69     137      79
Boundary for River Rch & Prof#=Lacy 061,Reach-1,1
Up Type=0
Dn Type=3
Dn Slope=0.005
Boundary for River Rch & Prof#=Lacy 061,Reach-1,2
Up Type=0
Dn Type=3
Dn Slope=0.005
Boundary for River Rch & Prof#=Lacy 061,Reach-1,3
Up Type=0
Dn Type=3
Dn Slope=0.005
Boundary for River Rch & Prof#=Lacy 061,Reach-1,4
Up Type=0
Dn Type=3
Dn Slope=0.005
Boundary for River Rch & Prof#=Lacy 061,Reach-1,5
Up Type=0
Dn Type=3
Dn Slope=0.005
Boundary for River Rch & Prof#=Lacy 061,Reach-1,6
Up Type=0
Dn Type=3
Dn Slope=0.005
Boundary for River Rch & Prof#=Lacy 061,Reach-1,7
Up Type=0
Dn Type=3
Dn Slope=0.005

--- Lacy 061.g01 (geometry) ---

Geom Title=Existing Conditions
Program Version=4.10

River Reach=Lacy 061        ,Reach-1
Reach XY= 18
        2763326.        6887861.      2763326.12       6887829.2
      2763329.65      6887812.51      2763368.11      6887767.16
      2763375.55      6887745.81      2763377.22       6887371.5
      2763384.14      6887354.94      2763420.25      6887313.33
      2763425.93      6887290.97      2763425.34      6886926.16
      2763419.98      6886908.55      2763389.94       6886874.2
      2763383.51      6886860.99      2763387.39      6886851.07
      2763421.67      6886809.42      2763428.46      6886767.06
      2763433.88      6886754.86        2763476.        6886711.

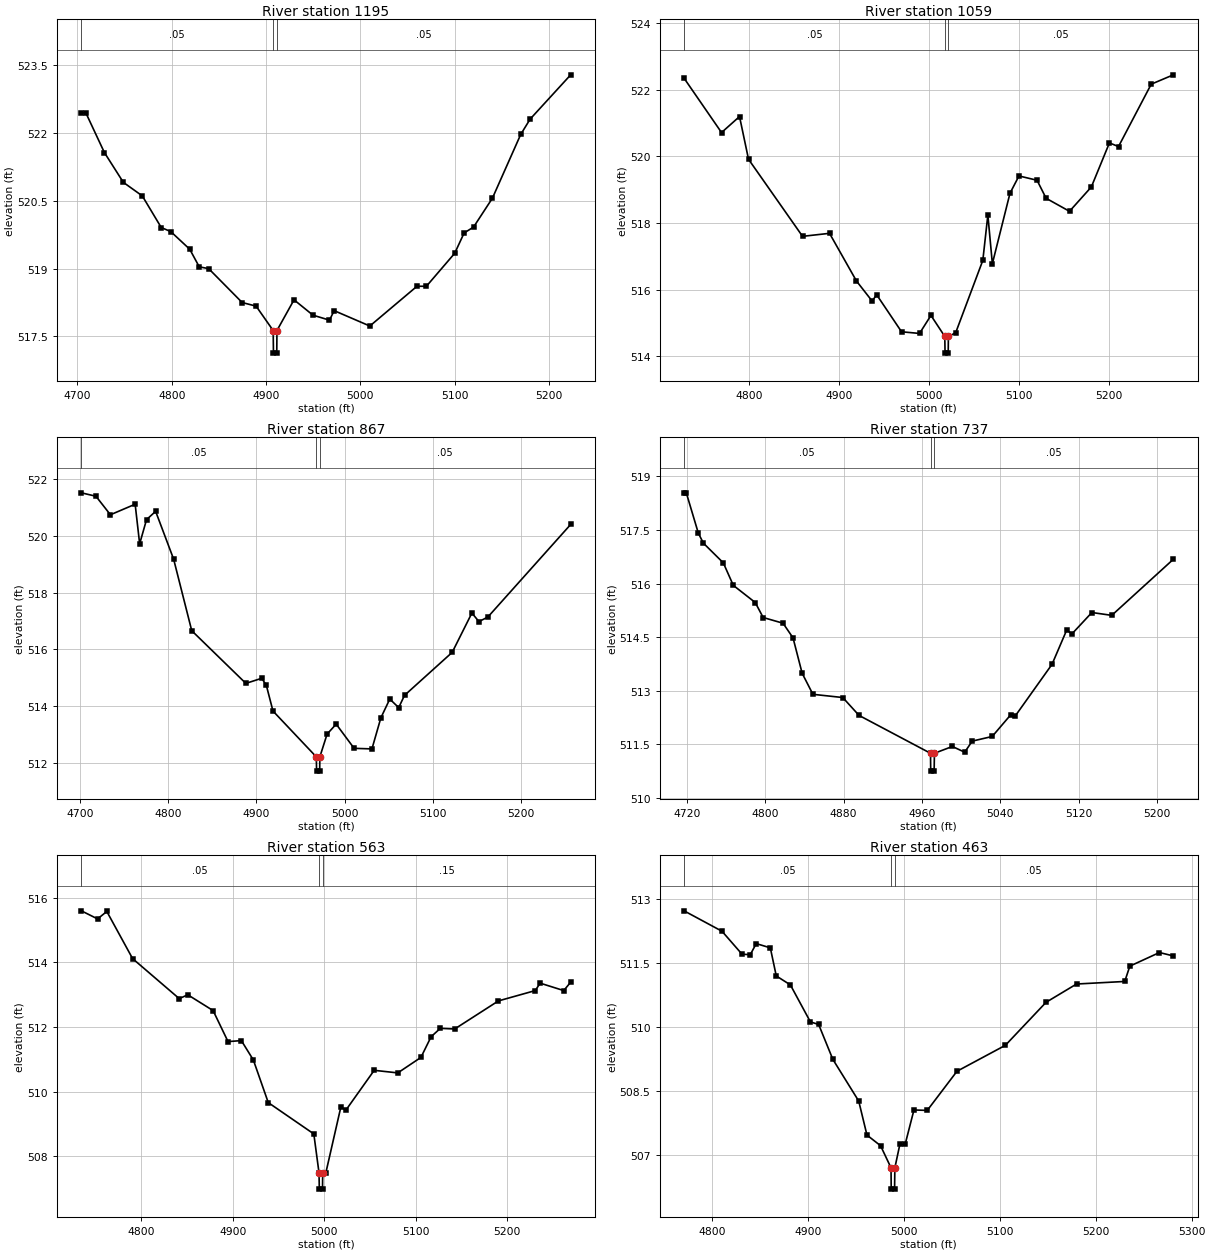
Type RM Length L Ch R = 1 ,1195    ,136,136,136
BEGIN DESCRIPTION:
Lacy 061 2480
END DESCRIPTION:
XS GIS Cut Line= 3
      2763620.27      6887797.98      2763326.12       6887829.2
      2763103.04      6887832.04
#Sta/Elev= 30
  4704.2  522.45  4708.9  522.45  4728.6  521.57  4748.7  520.91  4768.8  520.61
  4788.9  519.91    4799  519.82  4819.1  519.43  4829.2  519.04  4839.2     519
  4874.7  518.25  4889.5  518.17  4907.6  517.63  4907.9  517.13  4911.4  517.13
  4911.6  517.63  4929.7  518.31  4949.8  517.97  4967.3  517.86  4972.3  518.07
  5010.1  517.73  5060.1  518.61  5070.1  518.61  5100.1  519.34  5110.1  519.79
  5120.1  519.92  5140.1  520.56  5170.1  521.97  5180.1  522.31  5223.1  523.29
#Mann= 3 ,-1 , 0
  4704.2     .05       0  4907.6     .05       0  4911.6     .05       0
Bank Sta=4907.6,4911.6
XS Rating Curve= 0 ,0
Exp/Cntr=0.3,0.1

Type RM Length L Ch R = 1 ,1059    ,192,192,192
BEGIN DESCRIPTION:
Lacy 061 2479
END DESCRIPTION:
XS GIS Cut Line= 3
      2763647.64      6887696.48      2763375.72      6887708.73
      2763105.36      6887738.57
#Sta/Elev= 30
  4727.8  522.34  4769.5  520.71  4789.5  521.19  4799.5  519.91  4859.6   517.6
  4889.6  517.69  4919.6  516.26    4937  515.66    4942  515.85  4969.7  514.74
  4989.7  514.69  5002.4  515.23  5017.8   514.6  5018.1   514.1  5021.6   514.1
  5021.8   514.6  5029.9  514.71  5060.1  516.88  5065.7  518.24  5070.7  516.78
  5090.3  518.89  5100.3  519.41  5120.4  519.28  5130.5  518.74  5156.5  518.35
  5180.8  519.08  5200.9   520.4    5211  520.29  5247.4  522.16    5272  522.44
#Mann= 3 ,-1 , 0
  4727.8     .05       0  5017.8     .04       0  5021.8     .05       0
Bank Sta=5017.8,5021.8
XS Rating Curve= 0 ,0
Exp/Cntr=0.3,0.1

Type RM Length L Ch R = 1 ,867     ,130,130,130
BEGIN DESCRIPTION:
Lacy 061 2474
END DESCRIPTION:
XS GIS Cut Line= 3
       2763668.2      6887579.23      2763374.83       6887516.6
      2763123.08      6887551.98
#Sta/Elev= 30
  4701.8   521.5  4718.3  521.38  4734.7  520.73  4762.7   521.1  4767.8  519.71
  4775.6  520.56  4785.9  520.85  4806.3  519.17  4826.8  516.66  4888.1  514.81
  4906.1  514.99  4911.3  514.74  4918.8  513.84  4967.9  512.23  4968.2  511.73
  4971.7  511.73  4971.9  512.23  4980.1  513.03  4990.4  513.38  5010.7  512.53
  5030.9  512.51    5041   513.6  5051.1  514.26  5061.2  513.96  5067.8  514.39
  5121.8   515.9  5144.1  517.28  5152.1  516.98  5162.2  517.14    5256  520.39
#Mann= 3 ,-1 , 0
  4701.8     .05       0  4967.9     .04       0  4971.9     .05       0
Bank Sta=4967.9,4971.9
XS Rating Curve= 0 ,0
Exp/Cntr=0.3,0.1

Type RM Length L Ch R = 1 ,737     ,174,174,174
BEGIN DESCRIPTION:
Lacy 061 2473
END DESCRIPTION:
XS GIS Cut Line= 3
      2763655.46      6887438.63      2763373.62      6887386.68
      2763164.22      6887426.27
#Sta/Elev= 30
    4717  518.54  4719.3  518.54  4731.6  517.41  4736.8  517.13  4757.1  516.58
  4767.3  515.95  4789.7  515.47  4797.8  515.05  4818.1  514.89  4828.3  514.48
  4837.6  513.49  4848.6   512.9  4879.1  512.81  4895.7  512.31  4968.7  511.25
  4968.9  510.75  4972.4  510.75  4972.7  511.25    4991  511.44  5003.6  511.28
  5011.3  511.59  5031.7  511.72  5050.4  512.32  5055.4   512.3  5092.8  513.74
  5107.8   514.7  5113.1  514.59  5133.5  515.19  5153.8  515.11  5216.7  516.68
#Mann= 3 ,-1 , 0
    4717     .05       0  4968.7     .04       0  4972.7     .05       0
Bank Sta=4968.7,4972.7
XS Rating Curve= 0 ,0
Exp/Cntr=0.3,0.1

Type RM Length L Ch R = 1 ,563     ,100,100,100
BEGIN DESCRIPTION:
Lacy 061 2472
END DESCRIPTION:
XS GIS Cut Line= 3
      2763660.55      6887352.17      2763427.38      6887228.67
      2763171.36      6887317.65
#Sta/Elev= 30
  4734.5   515.6  4752.2  515.35  4762.3  515.58  4790.5  514.12  4841.5  512.88
  4850.8     513  4878.5  512.51  4894.8  511.55  4909.4  511.58  4922.5  510.98
  4938.8  509.66  4988.6  508.69  4994.3  507.48  4994.6  506.98  4998.1  506.98
  4998.3  507.48  5001.7  507.48  5018.2  509.53  5023.5  509.42  5054.6  510.66
  5080.4  510.58  5105.7  511.06  5116.8   511.7  5126.9  511.96  5142.6  511.94
  5190.4  512.81  5230.7  513.13    5236  513.36  5261.8  513.13  5269.4  513.39
#Mann= 3 ,-1 , 0
  4734.5     .05       0  4994.3     .05       0  4998.3     .15       0
Bank Sta=4994.3,4998.3
XS Rating Curve= 0 ,0
Exp/Cntr=0.3,0.1

Type RM Length L Ch R = 1 ,463     ,143,143,143
BEGIN DESCRIPTION:
Lacy 061 2478
END DESCRIPTION:
XS GIS Cut Line= 3
      2763612.95      6887259.21      2763428.27      6887127.67
      2763160.77      6887222.04
#Sta/Elev= 30
  4770.5  512.73  4810.1  512.25    4831  511.71  4839.6   511.7  4845.8  511.96
  4860.5  511.86  4866.7   511.2  4881.4  510.99  4902.3  510.12  4910.9  510.06
  4925.7  509.24  4952.7  508.26  4961.3  507.46  4975.5  507.21  4986.4  506.69
  4986.6  506.19  4990.1  506.19  4990.4  506.69  4995.6  507.24  5001.1  507.24
  5010.3  508.05  5024.2  508.04  5055.2  508.96  5105.7  509.57  5148.1  510.58
  5179.9  511.01  5230.2  511.07  5235.5  511.43  5266.4  511.75  5280.9  511.67
#Mann= 3 ,-1 , 0
  4770.5     .05       0  4986.4     .04       0  4990.4     .05       0
Bank Sta=4986.4,4990.4
XS Rating Curve= 0 ,0
Exp/Cntr=0.3,0.1

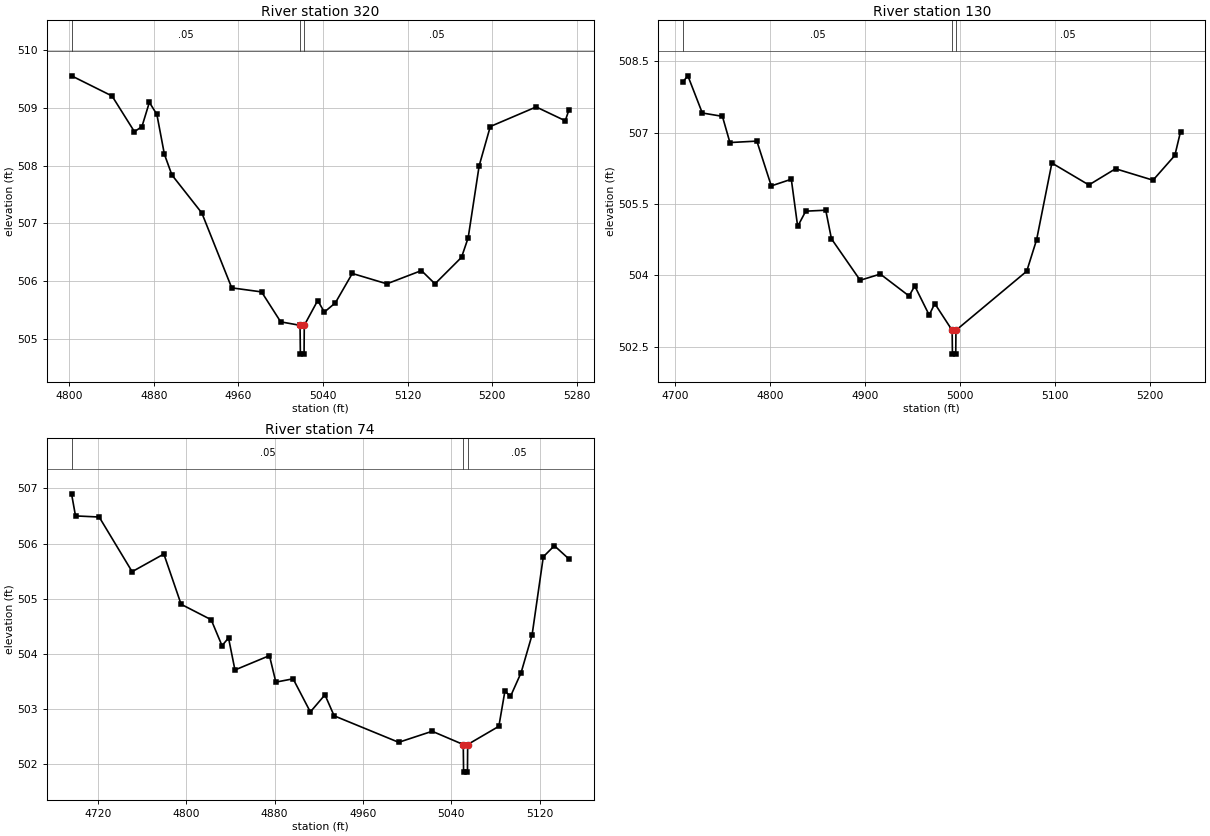
Type RM Length L Ch R = 1 ,320     ,190,190,190
BEGIN DESCRIPTION:
Lacy 061 2477
END DESCRIPTION:
XS GIS Cut Line= 3
       2763566.4      6887124.74      2763425.44      6886985.98
      2763164.91      6887066.19
#Sta/Elev= 30
  4802.2  509.56  4840.5  509.21  4861.7  508.59  4868.8  508.68  4875.8   509.1
  4882.9  508.89    4890   508.2  4897.1  507.84  4925.4  507.18  4953.7  505.88
  4981.9  505.81    5000  505.29  5018.3  505.23  5018.6  504.73  5022.1  504.73
  5022.3  505.23    5035  505.66  5041.3  505.46  5051.7  505.62  5067.7  506.13
  5100.4  505.95  5133.1  506.18  5145.9  505.95    5171  506.41  5177.3  506.75
  5187.7     508  5198.2  508.68  5241.6  509.02  5269.1  508.78  5272.6  508.97
#Mann= 3 ,-1 , 0
  4802.2     .05       0  5018.3     .04       0  5022.3     .05       0
Bank Sta=5018.3,5022.3
XS Rating Curve= 0 ,0
Exp/Cntr=0.3,0.1

Type RM Length L Ch R = 1 ,130     ,56,56,56
BEGIN DESCRIPTION:
Lacy 061 2476
END DESCRIPTION:
XS GIS Cut Line= 3
      2763572.28      6887062.48      2763415.45      6886818.68
      2763190.19      6886883.17
#Sta/Elev= 30
  4708.2  508.07  4713.2  508.19  4728.4  507.41  4749.6  507.34  4757.5  506.79
  4785.9  506.82  4801.1  505.88  4822.2  506.02  4828.9  505.03  4837.4  505.35
  4858.5  505.37  4864.5  504.77  4894.8   503.9    4916  504.03  4946.3  503.57
  4952.3  503.78  4967.5  503.17  4973.4  503.41  4991.7  502.85    4992  502.35
  4995.5  502.35  4995.7  502.85  5070.3  504.09  5080.7  504.75  5096.8  506.36
  5135.8   505.9  5163.9  506.24  5203.4     506  5226.4  506.52  5232.4  507.02
#Mann= 3 ,-1 , 0
  4708.2     .05       0  4991.7     .04       0  4995.7     .05       0
Bank Sta=4991.7,4995.7
XS Rating Curve= 0 ,0
Exp/Cntr=0.3,0.1

Type RM Length L Ch R = 1 ,74      ,0,0,0
BEGIN DESCRIPTION:
Lacy 061 2475
END DESCRIPTION:
XS GIS Cut Line= 3
      2763583.41      6887028.14      2763428.46      6886767.06
       2763282.9      6886781.77
#Sta/Elev= 30
  4696.4   506.9    4700   506.5  4721.4  506.48  4751.2  505.49  4779.9  505.81
  4795.5   504.9  4822.7  504.62  4832.5  504.15  4838.4  504.29  4844.2  503.71
  4875.4  503.97  4881.2  503.49  4896.8  503.55  4912.4  502.95  4925.6  503.26
  4933.9  502.88  4992.3   502.4  5022.6   502.6  5050.7  502.36    5051  501.86
  5054.5  501.86  5054.7  502.36  5082.9  502.69  5088.4  503.33  5093.4  503.23
    5103  503.66    5113  504.35  5123.1  505.76  5133.1  505.96  5146.3  505.72
#Mann= 3 ,-1 , 0
  4696.4     .05       0  5050.7     .04       0  5054.7     .05       0
Bank Sta=5050.7,5054.7
XS Rating Curve= 0 ,0
Exp/Cntr=0.3,0.1

Chan Stop Cuts=-1
Use User Specified Reach Order=0
Composite Channel Slope=5