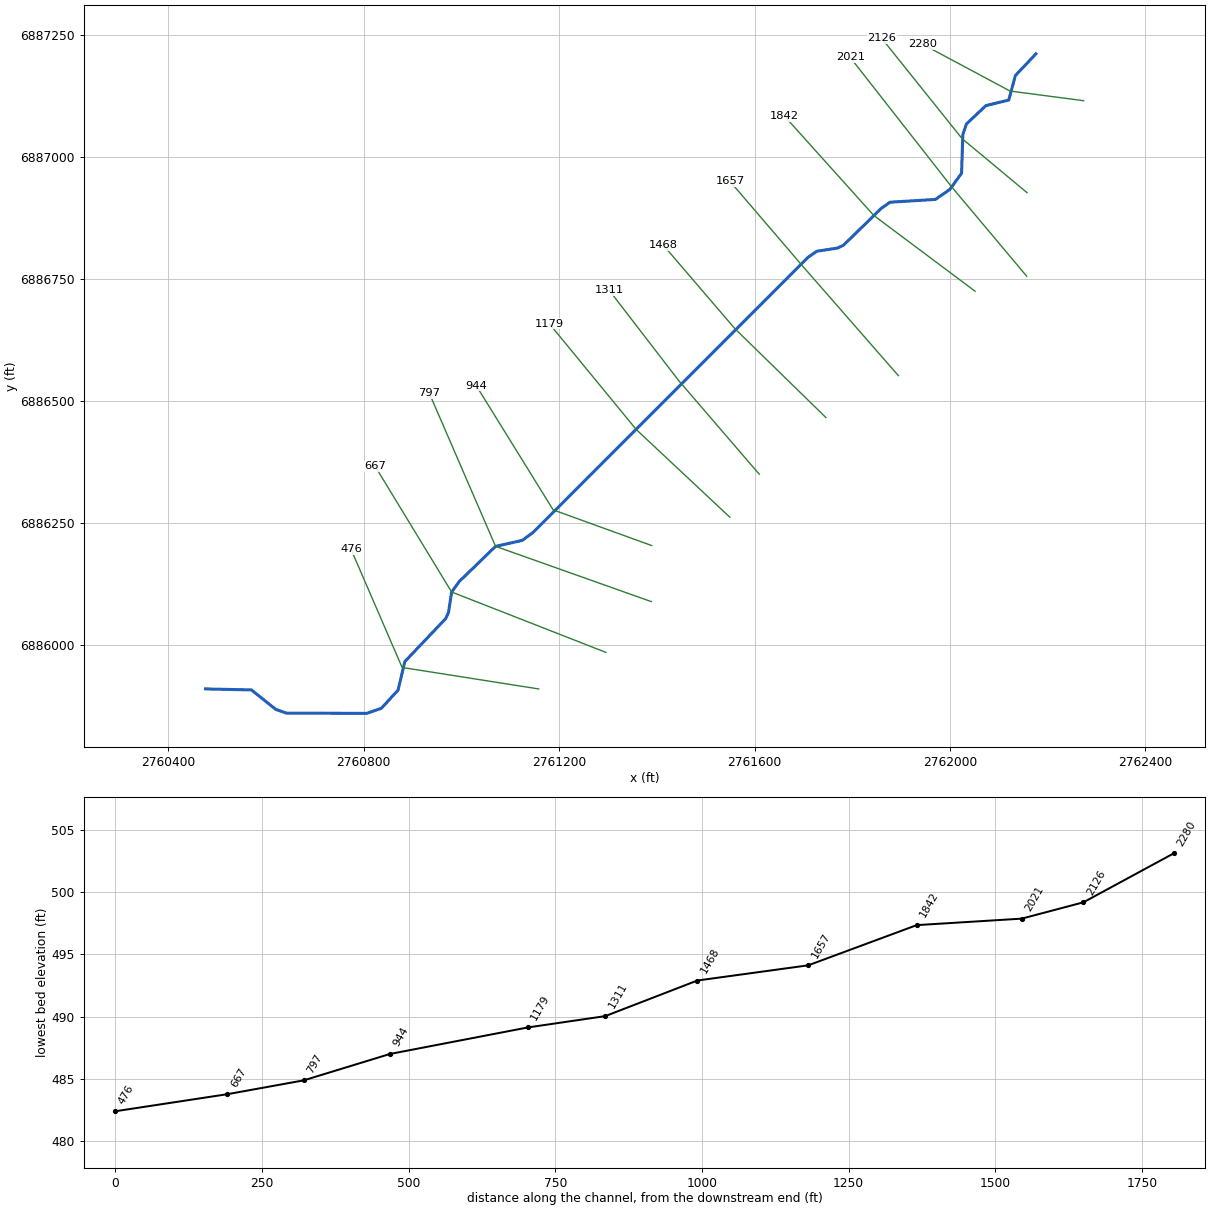
--- Lacy 062.prj (project) ---

Proj Title=Lacy 062 Base Level Engineering
Current Plan=p01
Default Exp/Contr=0.3,0.1
English Units
Geom File=g01
Flow File=f01
Plan File=p01
BEGIN DESCRIPTION:
Lacy 062
END DESCRIPTION:

--- Lacy 062.p01 (plan) ---

Plan Title=Multiple Run
Short Identifier=Multiple
Geom File=g01
Flow File=f01
Subcritical Flow
K Sum by GR= 0
Std Step Tol= 0.01
Critical Tol= 0.01
Num of Std Step Trials= 20
Max Error Tol= 0.3
Flow Tol Ratio= 0.001
Split Flow NTrial= 30
Split Flow Tol= 0.02
Split Flow Ratio= 0.02
Log Output Level= 0
Friction Slope Method= 1
Unsteady Friction Slope Method= 2
Unsteady Bridges Friction Slope Method= 1
Parabolic Critical Depth
Global Vel Dist=  1 , 1 , 1
Global Log Level= 0
CheckData=True
Encroach Param= -1, 0, 0, 0
BEGIN DESCRIPTION:
Multiple Run
END DESCRIPTION:

--- Lacy 062.f01 (steady flow) ---

Flow Title=Multiple
Number of Profiles=7
Profile Names=10-year,25-year,50-year,1pct_min,100-year,1pct_plu,500-year
River Rch & RM= Lacy 062,Reach-1,2280
     121     146     164      93     185     370     234
Boundary for River Rch & Prof#=Lacy 062,Reach-1,1
Up Type=0
Dn Type=3
Dn Slope=0.005
Boundary for River Rch & Prof#=Lacy 062,Reach-1,2
Up Type=0
Dn Type=3
Dn Slope=0.005
Boundary for River Rch & Prof#=Lacy 062,Reach-1,3
Up Type=0
Dn Type=3
Dn Slope=0.005
Boundary for River Rch & Prof#=Lacy 062,Reach-1,4
Up Type=0
Dn Type=3
Dn Slope=0.005
Boundary for River Rch & Prof#=Lacy 062,Reach-1,5
Up Type=0
Dn Type=3
Dn Slope=0.005
Boundary for River Rch & Prof#=Lacy 062,Reach-1,6
Up Type=0
Dn Type=3
Dn Slope=0.005
Boundary for River Rch & Prof#=Lacy 062,Reach-1,7
Up Type=0
Dn Type=3
Dn Slope=0.005

--- Lacy 062.g01 (geometry) ---

Geom Title=Existing Conditions

River Reach=Lacy 062,Reach-1
Reach XY= 30
      2762176.00      6887211.00      2762134.12      6887166.70
      2762120.53      6887116.52      2762073.75      6887105.15
      2762033.79      6887067.44      2762026.49      6887045.90
      2762023.93      6886966.69      2762000.01      6886933.68
      2761970.31      6886913.07      2761877.50      6886907.37
      2761859.26      6886894.51      2761782.04      6886819.18
      2761769.95      6886813.54      2761727.65      6886807.03
      2761709.33      6886794.35      2761146.09      6886230.79
      2761124.35      6886214.98      2761069.93      6886202.85
      2760995.77      6886131.13      2760979.97      6886109.36
      2760973.46      6886067.05      2760967.82      6886054.96
      2760884.19      6885967.02      2760870.26      6885908.42
      2760836.12      6885871.34      2760806.12      6885860.91
      2760641.21      6885861.51      2760619.93      6885869.10
      2760570.13      6885908.90      2760476.00      6885911.00

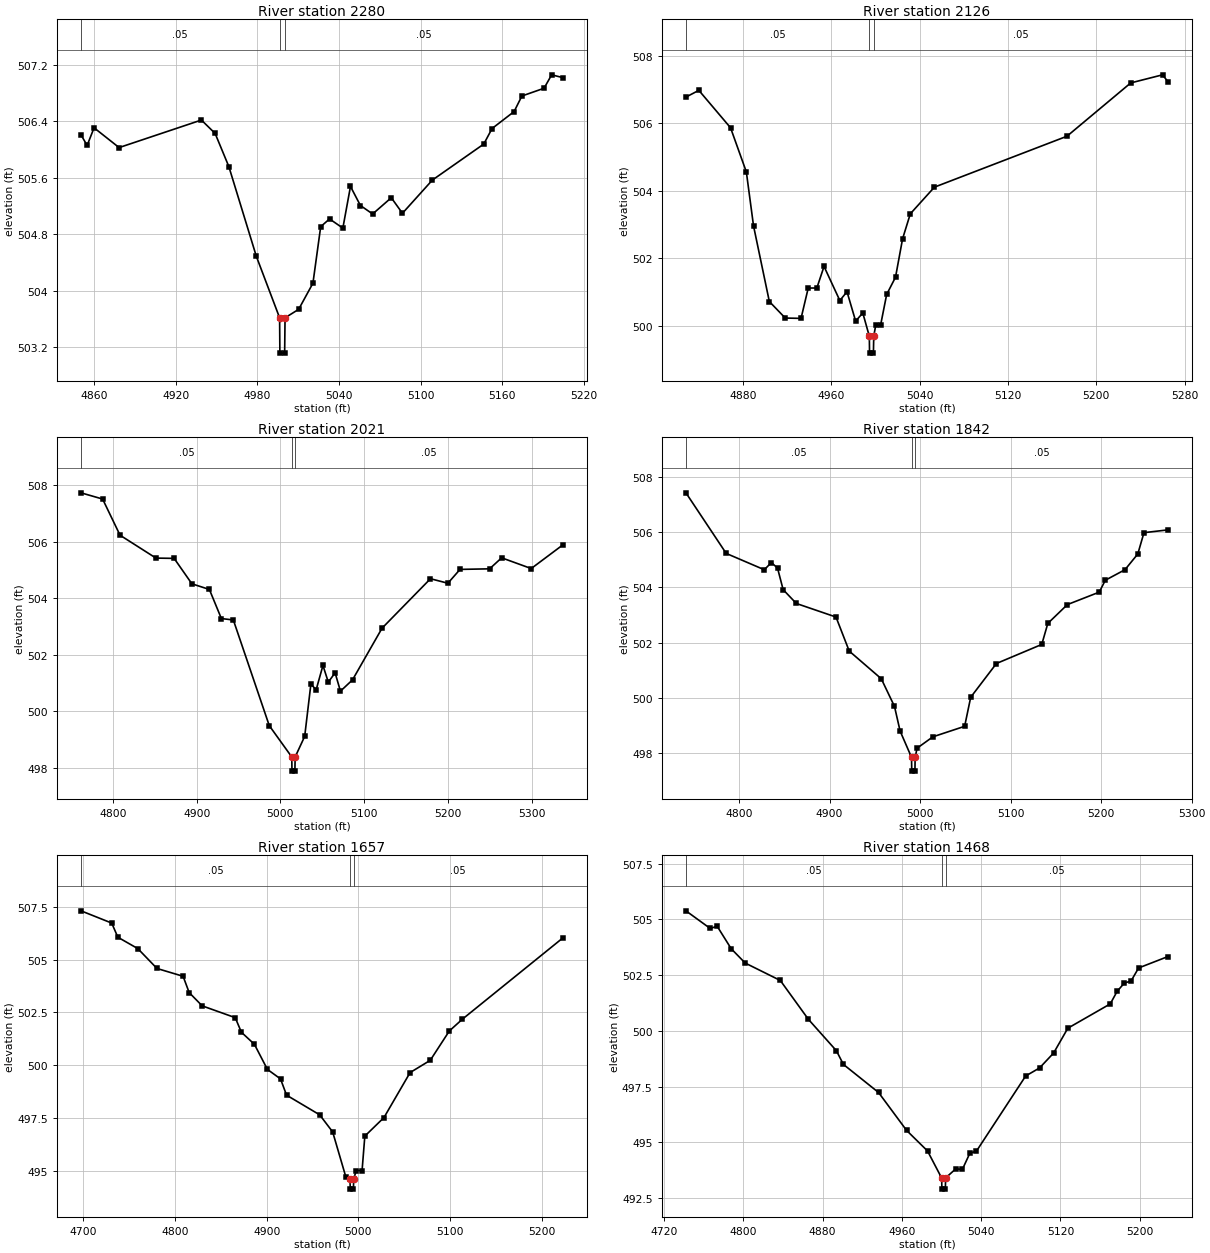
Type RM Length L Ch R = 1,2280,154,154,154
BEGIN DESCRIPTION:
Lacy 062 3483
END DESCRIPTION:
XS GIS Cut Line= 3
      2762273.77      6887115.19      2762123.09      6887134.98
      2761944.69      6887230.42
#Sta/Elev= 30
  4850.4  506.21  4854.9  506.06  4860.0  506.31  4878.4  506.03  4938.9  506.42
  4949.0  506.23  4959.1  505.76  4979.3  504.49  4996.4  503.62  4996.6  503.12
  5000.1  503.12  5000.4  503.62  5010.4  503.74  5020.9  504.11  5026.6  504.91
  5033.1  505.02  5042.9  504.89  5048.5  505.48  5055.8  505.21  5064.8  505.09
  5078.5  505.32  5086.7  505.10  5108.7  505.57  5146.5  506.08  5152.6  506.30
  5168.8  506.54  5174.5  506.76  5190.8  506.87  5196.4  507.06  5204.7  507.02
#Mann=3,-1,0
  4850.4    0.05       0  4996.4    0.04       0  5000.4    0.05       0
Bank Sta=4996.4,5000.4
Exp/Cntr=0.3,0.1

Type RM Length L Ch R = 1,2126,105,105,105
BEGIN DESCRIPTION:
Lacy 062 3482
END DESCRIPTION:
XS GIS Cut Line= 3
      2762158.04      6886926.85      2762025.04      6887037.47
      2761860.44      6887242.86
#Sta/Elev= 30
  4828.5  506.78  4840.2  506.98  4868.9  505.87  4883.2  504.56  4889.7  502.96
  4904.0  500.72  4918.4  500.23  4932.7  500.22  4939.2  501.12  4947.0  501.12
  4953.5  501.76  4967.8  500.75  4974.3  501.01  4982.1  500.14  4988.6  500.38
  4994.5  499.69  4994.7  499.19  4998.2  499.19  4998.5  499.69  5000.3  500.02
  5004.7  500.02  5010.2  500.93  5018.2  501.44  5024.6  502.58  5031.6  503.32
  5053.4  504.11  5173.4  505.62  5231.1  507.20  5259.9  507.44  5264.7  507.24
#Mann=3,-1,0
  4828.5    0.05       0  4994.5    0.04       0  4998.5    0.05       0
Bank Sta=4994.5,4998.5
Exp/Cntr=0.3,0.1

Type RM Length L Ch R = 1,2021,179,179,179
BEGIN DESCRIPTION:
Lacy 062 2451
END DESCRIPTION:
XS GIS Cut Line= 3
      2762157.22      6886755.84      2762002.31      6886940.39
      2761795.98      6887203.75
#Sta/Elev= 30
  4761.9  507.73  4787.7  507.51  4808.5  506.23  4851.4  505.42  4873.1  505.41
  4894.3  504.51  4915.2  504.31  4929.5  503.28  4943.8  503.23  4986.7  499.49
  5013.6  498.38  5013.8  497.88  5017.3  497.88  5017.6  498.38  5029.0  499.11
  5036.4  500.96  5042.7  500.76  5050.8  501.62  5057.2  501.03  5065.3  501.36
  5071.7  500.71  5086.1  501.11  5121.4  502.94  5179.2  504.69  5200.0  504.53
  5214.5  505.02  5249.8  505.04  5264.2  505.43  5299.5  505.05  5337.4  505.89
#Mann=3,-1,0
  4761.9    0.05       0  5013.6    0.04       0  5017.6    0.05       0
Bank Sta=5013.6,5017.6
Exp/Cntr=0.3,0.1

Type RM Length L Ch R = 1,1842,185,185,185
BEGIN DESCRIPTION:
Lacy 062 2452
END DESCRIPTION:
XS GIS Cut Line= 3
      2762051.61      6886725.11      2761844.24      6886880.23
      2761661.41      6887083.54
#Sta/Elev= 30
  4741.3  507.42  4785.8  505.23  4827.9  504.64  4835.7  504.90  4842.5  504.70
  4848.7  503.92  4863.3  503.42  4907.1  502.93  4921.7  501.70  4957.1  500.70
  4971.7  499.70  4977.9  498.81  4990.5  497.86  4990.8  497.36  4994.3  497.36
  4994.5  497.86  4996.7  498.19  5014.1  498.60  5049.2  498.98  5055.9  500.03
  5084.3  501.25  5134.4  501.94  5141.1  502.70  5162.7  503.38  5197.9  503.83
  5204.6  504.26  5226.3  504.64  5240.5  505.21  5247.3  505.98  5273.7  506.08
#Mann=3,-1,0
  4741.3    0.05       0  4990.5    0.04       0  4994.5    0.05       0
Bank Sta=4990.5,4994.5
Exp/Cntr=0.3,0.1

Type RM Length L Ch R = 1,1657,189,189,189
BEGIN DESCRIPTION:
Lacy 062 2449
END DESCRIPTION:
XS GIS Cut Line= 3
      2761894.48      6886552.38      2761694.46      6886781.31
      2761550.07      6886949.80
#Sta/Elev= 30
  4697.3  507.31  4730.8  506.73  4737.5  506.06  4759.3  505.52  4780.2  504.58
  4808.7  504.21  4815.3  503.44  4829.5  502.81  4865.6  502.25  4872.3  501.56
  4886.5  500.99  4900.7  499.80  4915.0  499.35  4921.6  498.58  4957.7  497.65
  4971.9  496.84  4986.2  494.72  4990.8  494.63  4991.1  494.13  4994.6  494.13
  4994.8  494.63  4997.8  495.01  5004.0  495.01  5007.0  496.64  5027.9  497.52
  5056.4  499.65  5078.4  500.23  5099.2  501.62  5113.5  502.18  5223.2  506.03
#Mann=3,-1,0
  4697.3    0.05       0  4990.8    0.04       0  4994.8    0.05       0
Bank Sta=4990.8,4994.8
Exp/Cntr=0.3,0.1

Type RM Length L Ch R = 1,1468,157,157,157
BEGIN DESCRIPTION:
Lacy 062 2448
END DESCRIPTION:
XS GIS Cut Line= 3
      2761746.16      6886466.55      2761560.19      6886648.14
      2761412.97      6886819.84
#Sta/Elev= 30
  4742.2  505.38  4766.7  504.59  4773.7  504.69  4787.9  503.68  4802.0  503.04
  4837.4  502.26  4865.7  500.52  4894.0  499.11  4901.0  498.50  4936.5  497.24
  4964.8  495.54  4985.9  494.62  5000.1  493.41  5000.4  492.91  5003.9  492.91
  5004.1  493.41  5014.4  493.82  5021.0  493.79  5028.6  494.52  5035.2  494.61
  5084.9  497.98  5098.9  498.34  5113.1  499.01  5127.4  500.12  5170.2  501.21
  5177.1  501.77  5184.5  502.15  5191.1  502.23  5198.8  502.82  5228.3  503.33
#Mann=3,-1,0
  4742.2    0.05       0  5000.1    0.04       0  5004.1    0.05       0
Bank Sta=5000.1,5004.1
Exp/Cntr=0.3,0.1

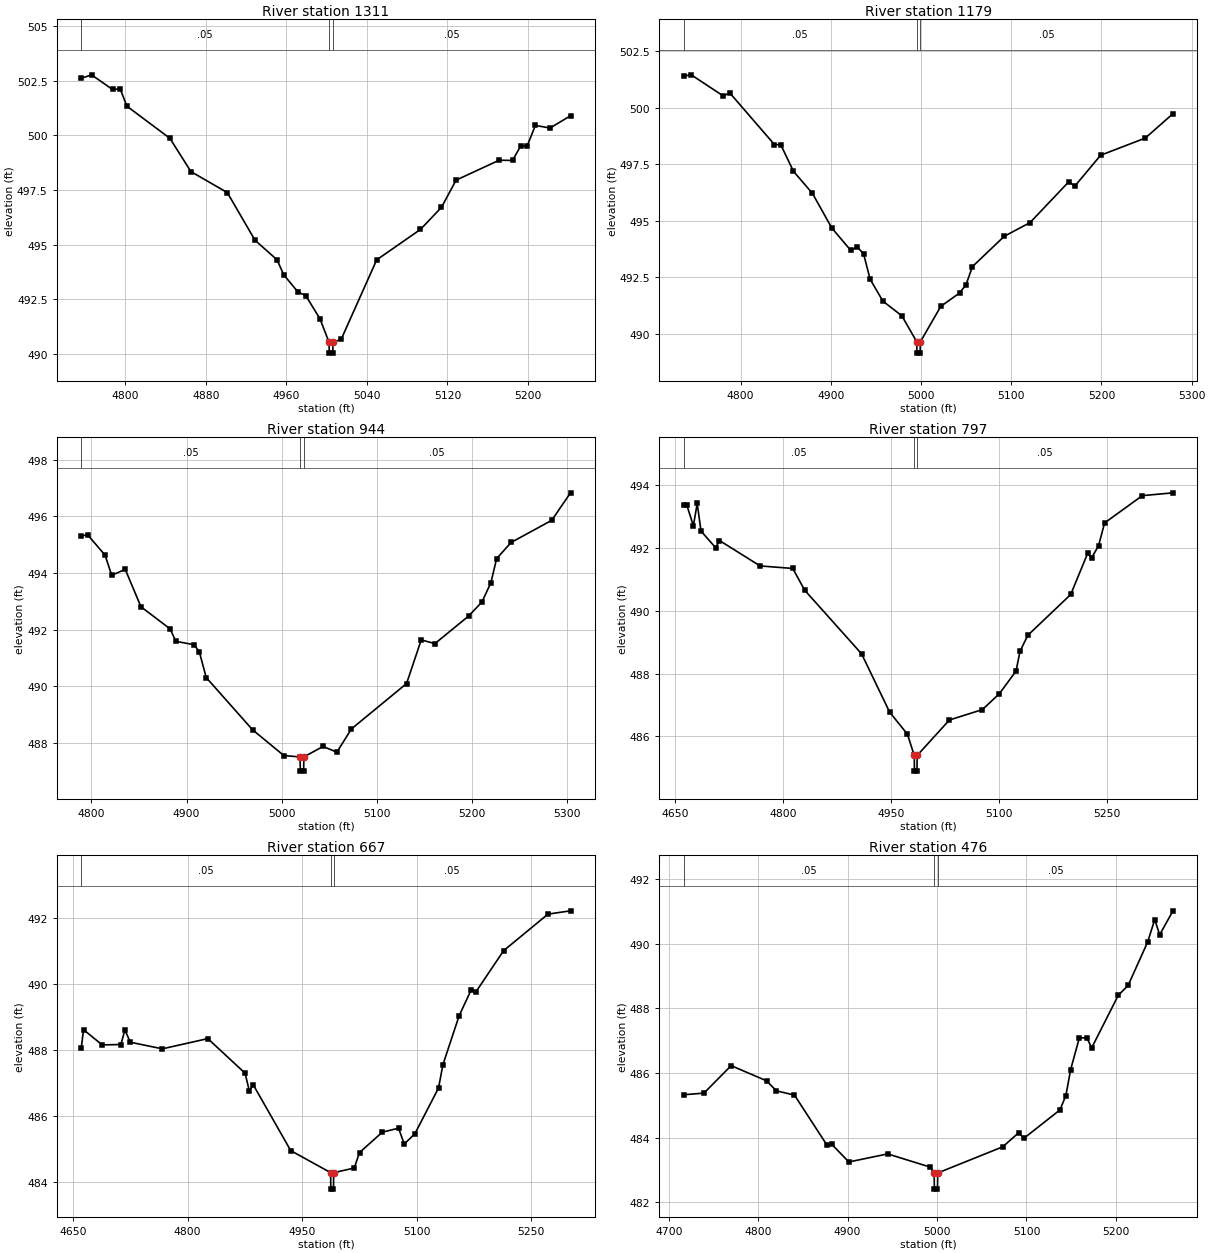
Type RM Length L Ch R = 1,1311,132,132,132
BEGIN DESCRIPTION:
Lacy 062 2447
END DESCRIPTION:
XS GIS Cut Line= 3
      2761609.67      6886350.59      2761445.44      6886541.42
      2761302.43      6886727.17
#Sta/Elev= 30
  4756.1  502.60  4766.3  502.76  4787.2  502.09  4794.8  502.12  4801.4  501.33
  4844.2  499.86  4865.1  498.34  4901.3  497.38  4928.7  495.21  4950.7  494.31
  4957.3  493.63  4971.5  492.84  4979.2  492.68  4993.4  491.61  5002.3  490.55
  5002.6  490.05  5006.1  490.05  5006.3  490.55  5014.4  490.68  5049.7  494.31
  5093.2  495.70  5114.1  496.71  5128.6  497.95  5171.4  498.86  5184.7  498.85
  5192.9  499.52  5199.2  499.51  5207.4  500.45  5221.9  500.33  5242.3  500.89
#Mann=3,-1,0
  4756.1    0.05       0  5002.3    0.04       0  5006.3    0.05       0
Bank Sta=5002.3,5006.3
Exp/Cntr=0.3,0.1

Type RM Length L Ch R = 1,1179,235,235,235
BEGIN DESCRIPTION:
Lacy 062 2446
END DESCRIPTION:
XS GIS Cut Line= 3
      2761549.46      6886262.55      2761358.02      6886441.86
      2761180.36      6886658.28
#Sta/Elev= 30
  4737.0  501.41  4745.3  501.46  4781.0  500.52  4787.8  500.67  4837.6  498.37
  4844.5  498.37  4858.6  497.19  4879.7  496.21  4901.1  494.68  4922.1  493.69
  4929.5  493.83  4936.3  493.54  4943.6  492.41  4957.8  491.44  4978.8  490.79
  4995.3  489.64  4995.5  489.14  4999.0  489.14  4999.3  489.64  5021.9  491.21
  5042.7  491.80  5049.9  492.17  5057.0  492.97  5092.2  494.31  5120.9  494.92
  5163.9  496.73  5170.4  496.53  5199.1  497.90  5248.6  498.66  5279.3  499.74
#Mann=3,-1,0
  4737.0    0.05       0  4995.3    0.04       0  4999.3    0.05       0
Bank Sta=4995.3,4999.3
Exp/Cntr=0.3,0.1

Type RM Length L Ch R = 1,944,147,147,147
BEGIN DESCRIPTION:
Lacy 062 2445
END DESCRIPTION:
XS GIS Cut Line= 3
      2761389.48      6886204.51      2761187.83      6886277.50
      2761030.17      6886532.08
#Sta/Elev= 30
  4789.4  495.31  4796.1  495.35  4814.4  494.63  4821.4  493.92  4835.6  494.13
  4852.1  492.81  4882.7  492.03  4888.8  491.59  4908.0  491.47  4913.4  491.22
  4920.7  490.31  4969.3  488.47  5002.2  487.56  5019.2  487.51  5019.5  487.01
  5023.0  487.01  5023.2  487.51  5043.3  487.88  5057.9  487.68  5073.2  488.50
  5131.1  490.10  5146.5  491.64  5160.9  491.51  5196.2  492.48  5210.3  492.98
  5219.7  493.66  5225.7  494.51  5241.0  495.08  5283.6  495.86  5303.3  496.83
#Mann=3,-1,0
  4789.4    0.05       0  5019.2    0.04       0  5023.2    0.05       0
Bank Sta=5019.2,5023.2
Exp/Cntr=0.3,0.1

Type RM Length L Ch R = 1,797,130,130,130
BEGIN DESCRIPTION:
Lacy 062 2457
END DESCRIPTION:
XS GIS Cut Line= 3
      2761388.66      6886089.75      2761069.93      6886202.85
      2760934.44      6886515.88
#Sta/Elev= 30
  4661.8  493.38  4665.9  493.38  4675.2  492.71  4680.5  493.42  4685.8  492.54
  4706.1  492.01  4711.4  492.24  4767.8  491.43  4813.2  491.35  4829.6  490.66
  4908.7  488.63  4947.7  486.77  4972.3  486.07  4981.9  485.39  4982.1  484.89
  4985.6  484.89  4985.9  485.39  5030.7  486.52  5076.3  486.85  5099.8  487.35
  5123.2  488.08  5128.7  488.71  5139.6  489.22  5199.1  490.52  5222.6  491.83
  5228.1  491.69  5237.7  492.07  5246.1  492.80  5298.5  493.67  5341.1  493.76
#Mann=3,-1,0
  4661.8    0.05       0  4981.9    0.04       0  4985.9    0.05       0
Bank Sta=4981.9,4985.9
Exp/Cntr=0.3,0.1

Type RM Length L Ch R = 1,667,191,191,191
BEGIN DESCRIPTION:
Lacy 062 2456
END DESCRIPTION:
XS GIS Cut Line= 3
      2761295.84      6885985.74      2760979.97      6886109.36
      2760823.14      6886367.10
#Sta/Elev= 30
  4660.8  488.07  4663.8  488.62  4688.2  488.16  4712.7  488.17  4718.0  488.61
  4725.1  488.24  4767.0  488.04  4826.6  488.35  4875.4  487.30  4880.9  486.77
  4886.3  486.94  4935.2  484.95  4987.5  484.28  4987.7  483.78  4991.2  483.78
  4991.5  484.28  5018.4  484.42  5025.3  484.89  5055.2  485.51  5076.5  485.63
  5083.9  485.15  5097.8  485.46  5128.8  486.85  5134.6  487.56  5155.9  489.05
  5171.4  489.82  5177.5  489.76  5214.1  491.02  5272.2  492.13  5301.7  492.23
#Mann=3,-1,0
  4660.8    0.05       0  4987.5    0.04       0  4991.5    0.05       0
Bank Sta=4987.5,4991.5
Exp/Cntr=0.3,0.1

Type RM Length L Ch R = 1,476,0,0,0
BEGIN DESCRIPTION:
Lacy 062 2455
END DESCRIPTION:
XS GIS Cut Line= 3
      2761158.32      6885910.92      2760878.56      6885954.91
      2760773.93      6886197.07
#Sta/Elev= 30
  4716.8  485.33  4739.4  485.38  4769.8  486.23  4809.5  485.76  4820.4  485.45
  4840.6  485.32  4877.2  483.76  4882.2  483.80  4901.4  483.25  4944.8  483.50
  4992.5  483.09  4996.8  482.91  4997.0  482.41  5000.5  482.41  5000.8  482.91
  5073.5  483.72  5091.5  484.16  5097.0  483.98  5137.4  484.86  5144.0  485.30
  5149.4  486.11  5159.1  487.09  5167.5  487.09  5172.9  486.78  5202.7  488.41
  5213.6  488.71  5235.4  490.05  5243.4  490.75  5248.9  490.28  5263.8  491.02
#Mann=3,-1,0
  4716.8    0.05       0  4996.8    0.04       0  5000.8    0.05       0
Bank Sta=4996.8,5000.8
Exp/Cntr=0.3,0.1

Chan Stop Cuts=-1