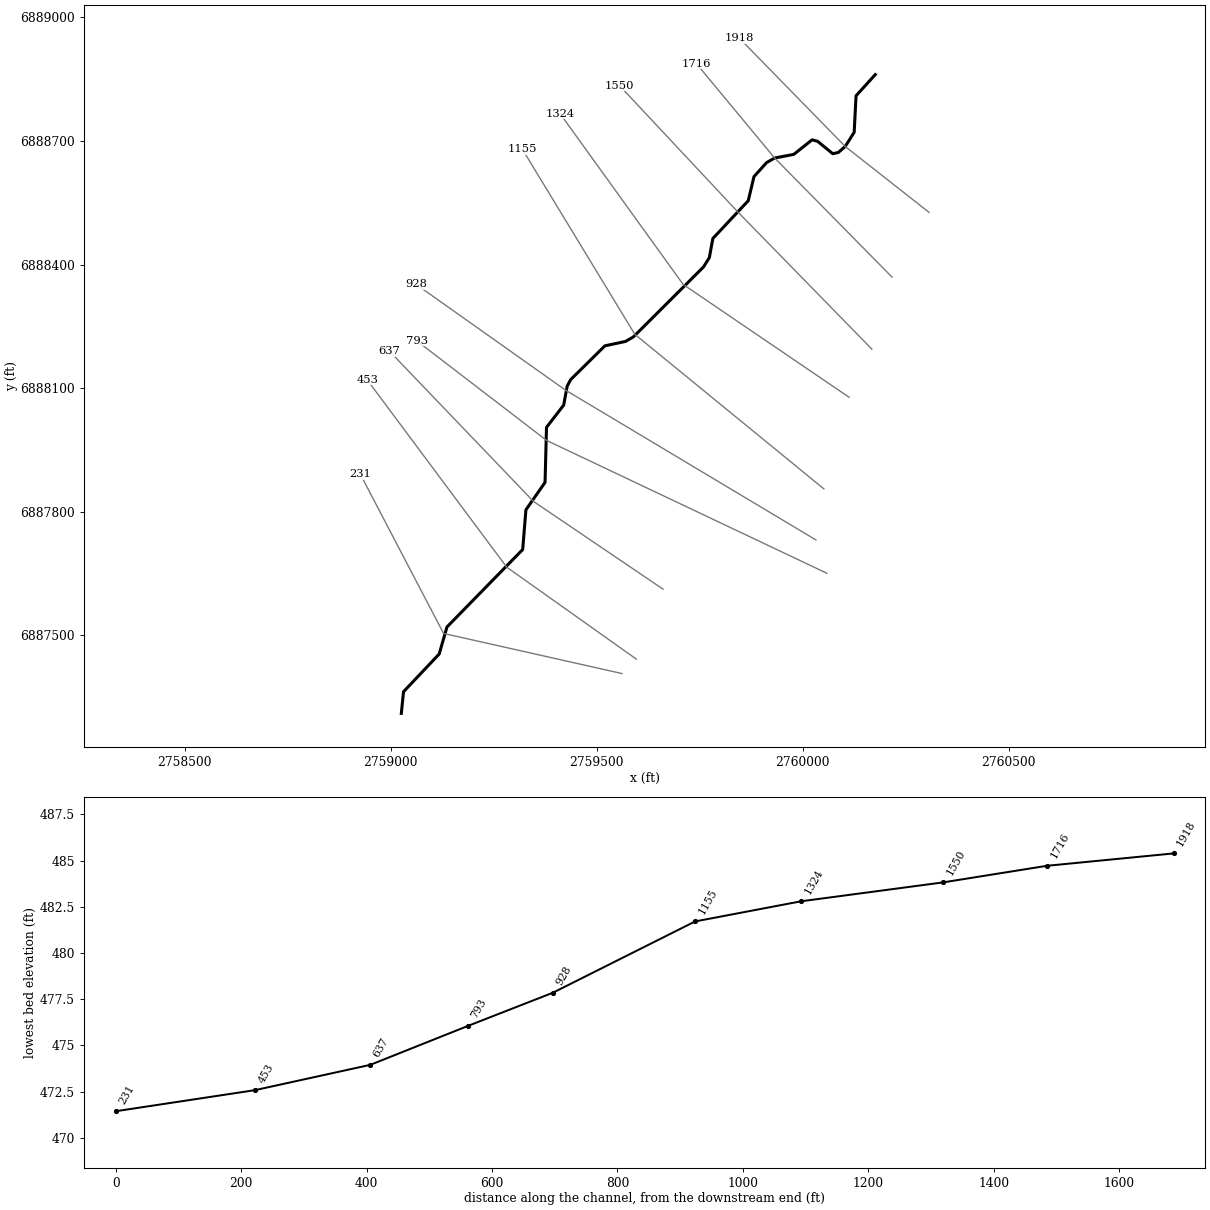
--- Lacy 063.prj (project) ---

Proj Title=Lacy 063 Base Level Engineering
Current Plan=p01
Default Exp/Contr=0.3,0.1
English Units
Geom File=g01
Flow File=f01
Plan File=p01
BEGIN DESCRIPTION:
Lacy 063
END DESCRIPTION:

--- Lacy 063.p01 (plan) ---

Plan Title=Multiple Run
Short Identifier=Multiple
Geom File=g01
Flow File=f01
Subcritical Flow
K Sum by GR= 0
Std Step Tol= 0.01
Critical Tol= 0.01
Num of Std Step Trials= 20
Max Error Tol= 0.3
Flow Tol Ratio= 0.001
Split Flow NTrial= 30
Split Flow Tol= 0.02
Split Flow Ratio= 0.02
Log Output Level= 0
Friction Slope Method= 1
Unsteady Friction Slope Method= 2
Unsteady Bridges Friction Slope Method= 1
Parabolic Critical Depth
Global Vel Dist=  1 , 1 , 1
Global Log Level= 0
CheckData=True
Encroach Param= -1, 0, 0, 0
BEGIN DESCRIPTION:
Multiple Run
END DESCRIPTION:

--- Lacy 063.f01 (steady flow) ---

Flow Title=Multiple
Number of Profiles=7
Profile Names=10-year,25-year,50-year,1pct_min,100-year,1pct_plu,500-year
River Rch & RM= Lacy 063,Reach-1,1918
     184     229     263     151     301     600     393
Boundary for River Rch & Prof#=Lacy 063,Reach-1,1
Up Type=0
Dn Type=3
Dn Slope=0.005
Boundary for River Rch & Prof#=Lacy 063,Reach-1,2
Up Type=0
Dn Type=3
Dn Slope=0.005
Boundary for River Rch & Prof#=Lacy 063,Reach-1,3
Up Type=0
Dn Type=3
Dn Slope=0.005
Boundary for River Rch & Prof#=Lacy 063,Reach-1,4
Up Type=0
Dn Type=3
Dn Slope=0.005
Boundary for River Rch & Prof#=Lacy 063,Reach-1,5
Up Type=0
Dn Type=3
Dn Slope=0.005
Boundary for River Rch & Prof#=Lacy 063,Reach-1,6
Up Type=0
Dn Type=3
Dn Slope=0.005
Boundary for River Rch & Prof#=Lacy 063,Reach-1,7
Up Type=0
Dn Type=3
Dn Slope=0.005

--- Lacy 063.g01 (geometry) ---

Geom Title=Existing Conditions

River Reach=Lacy 063,Reach-1
Reach XY= 30
      2760176.00      6888861.00      2760129.39      6888809.59
      2760124.88      6888721.13      2760103.13      6888686.58
      2760086.37      6888672.08      2760072.88      6888669.06
      2760036.08      6888699.15      2760022.78      6888702.75
      2759978.27      6888667.41      2759931.87      6888658.62
      2759912.44      6888647.54      2759881.75      6888613.54
      2759867.82      6888554.98      2759781.87      6888463.28
      2759773.47      6888417.05      2759759.35      6888394.33
      2759589.21      6888224.63      2759569.95      6888213.54
      2759519.93      6888202.85      2759436.75      6888120.71
      2759428.49      6888104.98      2759419.86      6888058.83
      2759378.25      6888005.07      2759374.77      6887871.51
      2759328.36      6887805.02      2759320.48      6887708.57
      2759136.78      6887520.68      2759117.84      6887454.95
      2759031.33      6887363.51      2759026.00      6887311.00

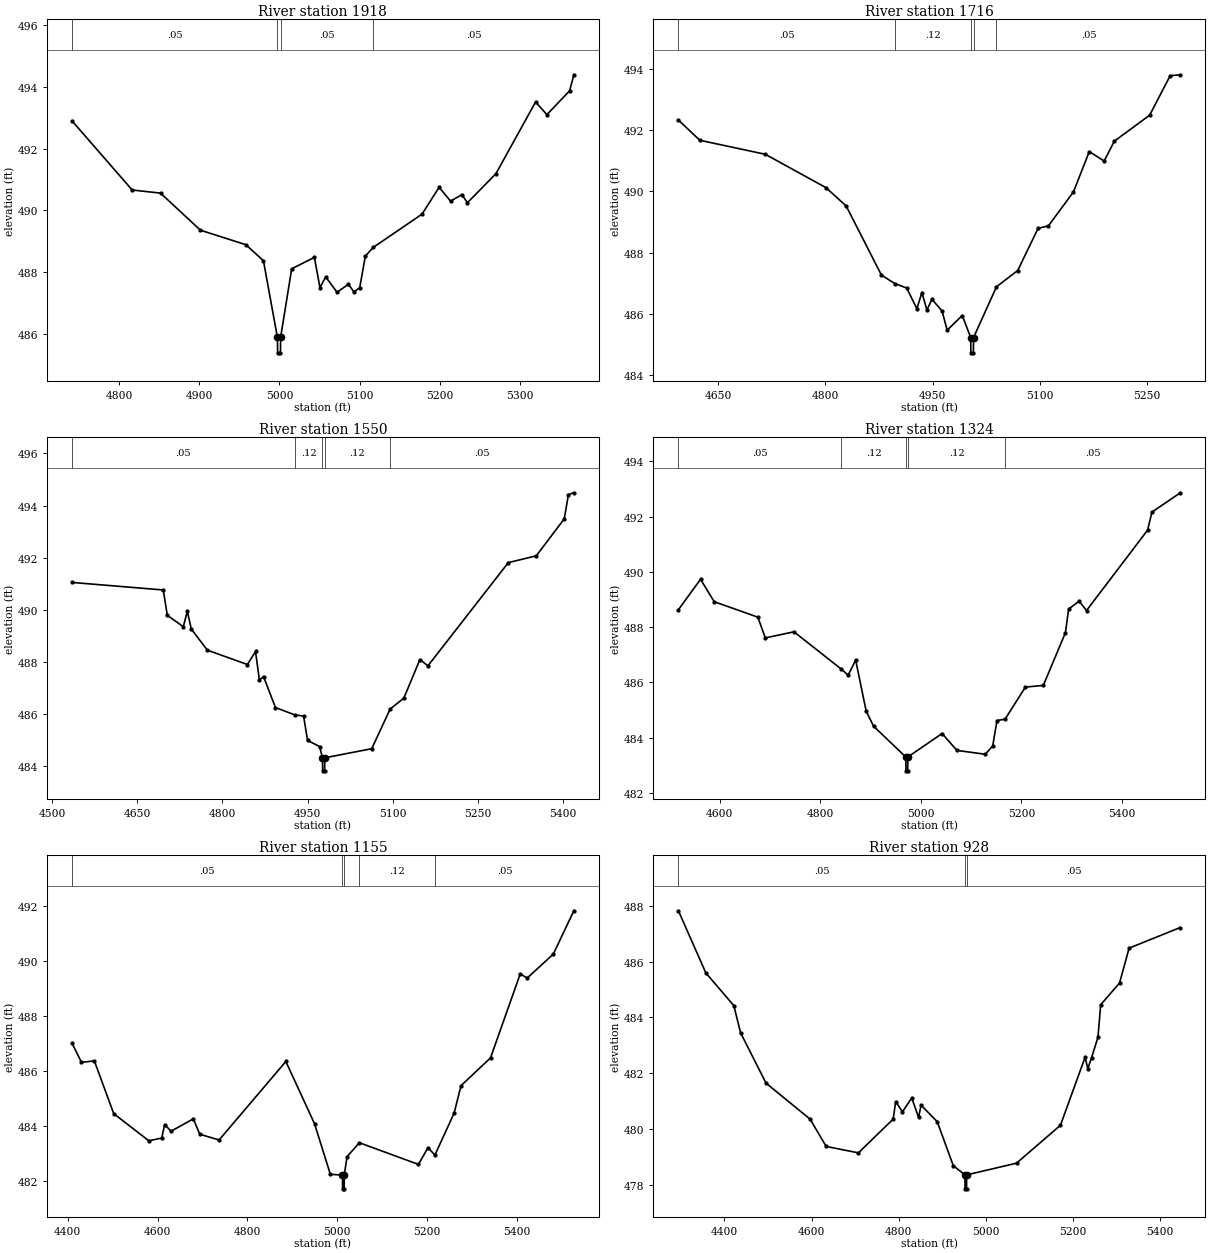
Type RM Length L Ch R = 1,1918,202,202,202
BEGIN DESCRIPTION:
Lacy 063 2434
END DESCRIPTION:
XS GIS Cut Line= 3
      2760306.44      6888526.77      2760103.13      6888686.58
      2759846.58      6888949.01
#Sta/Elev= 30
  4741.4  492.90  4816.5  490.66  4851.8  490.56  4901.5  489.36  4958.2  488.89
  4980.1  488.37  4997.5  485.89  4997.8  485.39  5001.3  485.39  5001.5  485.89
  5015.3  488.11  5043.6  488.48  5050.5  487.50  5057.7  487.85  5071.8  487.35
  5086.0  487.61  5093.0  487.36  5100.1  487.50  5107.1  488.52  5116.8  488.80
  5177.8  489.88  5199.1  490.75  5213.3  490.30  5227.4  490.51  5234.4  490.25
  5269.9  491.19  5319.3  493.51  5333.4  493.10  5361.7  493.87  5367.0  494.39
#Mann=4,-1,0
  4741.4    0.05       0  4997.5    0.07       0  5001.5    0.05       0
  5116.8    0.05       0
Bank Sta=4997.5,5001.5
Exp/Cntr=0.3,0.1

Type RM Length L Ch R = 1,1716,166,166,166
BEGIN DESCRIPTION:
Lacy 063 2433
END DESCRIPTION:
XS GIS Cut Line= 3
      2760216.82      6888369.55      2759931.87      6888658.62
      2759742.27      6888887.36
#Sta/Elev= 30
  4594.1  492.33  4624.0  491.67  4715.9  491.21  4800.8  490.12  4829.1  489.52
  4878.5  487.26  4897.6  486.98  4913.9  486.84  4928.1  486.16  4935.1  486.69
  4942.2  486.12  4949.2  486.47  4963.4  486.09  4970.5  485.46  4991.7  485.94
  5003.5  485.22  5003.7  484.72  5007.2  484.72  5007.5  485.22  5039.6  486.88
  5069.3  487.41  5097.9  488.79  5112.3  488.87  5147.4  489.98  5169.6  491.30
  5190.4  490.99  5204.7  491.64  5254.2  492.49  5282.9  493.78  5297.1  493.81
#Mann=5,-1,0
  4594.1    0.05       0  4897.6    0.12       0  5003.5    0.07       0
  5007.5    0.12       0  5039.6    0.05       0
Bank Sta=5003.5,5007.5
Exp/Cntr=0.3,0.1

Type RM Length L Ch R = 1,1550,226,226,226
BEGIN DESCRIPTION:
Lacy 063 2432
END DESCRIPTION:
XS GIS Cut Line= 3
      2760167.64      6888194.97      2759842.39      6888527.85
      2759555.54      6888834.23
#Sta/Elev= 30
  4534.6  491.05  4695.7  490.76  4702.7  489.79  4730.9  489.35  4738.1  489.94
  4745.1  489.26  4773.4  488.45  4844.1  487.90  4858.3  488.40  4865.2  487.30
  4872.4  487.44  4893.5  486.25  4927.1  485.97  4943.1  485.92  4950.1  484.99
  4971.4  484.75  4976.4  484.32  4976.7  483.82  4980.2  483.82  4980.4  484.32
  5063.3  484.67  5095.7  486.19  5119.9  486.61  5148.2  488.09  5162.4  487.85
  5304.1  491.81  5353.4  492.07  5402.8  493.49  5410.1  494.42  5419.7  494.49
#Mann=5,-1,0
  4534.6    0.05       0  4927.1    0.12       0  4976.4    0.07       0
  4980.4    0.12       0  5095.7    0.05       0
Bank Sta=4976.4,4980.4
Exp/Cntr=0.3,0.1

Type RM Length L Ch R = 1,1324,169,169,169
BEGIN DESCRIPTION:
Lacy 063 2429
END DESCRIPTION:
XS GIS Cut Line= 3
      2760112.64      6888078.00      2759709.80      6888351.90
      2759411.24      6888766.31
#Sta/Elev= 30
  4517.9  488.63  4561.9  489.73  4589.0  488.92  4675.8  488.36  4690.7  487.61
  4747.6  487.83  4841.8  486.48  4855.4  486.26  4870.3  486.81  4891.3  484.95
  4906.2  484.41  4970.0  483.30  4970.3  482.80  4973.8  482.80  4974.0  483.30
  5042.1  484.15  5071.6  483.54  5128.0  483.40  5142.8  483.70  5151.3  484.62
  5167.4  484.67  5207.8  485.83  5243.4  485.89  5287.4  487.80  5293.7  488.65
  5314.6  488.94  5329.3  488.60  5450.8  491.51  5459.3  492.16  5515.8  492.86
#Mann=5,-1,0
  4517.9    0.05       0  4841.8    0.12       0  4970.0    0.07       0
  4974.0    0.12       0  5167.4    0.05       0
Bank Sta=4970,4974
Exp/Cntr=0.3,0.1

Type RM Length L Ch R = 1,1155,227,227,227
BEGIN DESCRIPTION:
Lacy 063 2428
END DESCRIPTION:
XS GIS Cut Line= 3
      2760051.30      6887855.80      2759592.58      6888230.80
      2759319.97      6888679.59
#Sta/Elev= 30
  4409.5  487.02  4430.7  486.32  4459.4  486.37  4502.5  484.45  4580.7  483.46
  4609.4  483.56  4615.9  484.05  4630.2  483.81  4679.8  484.26  4694.1  483.70
  4737.2  483.49  4885.8  486.35  4949.7  484.08  4984.9  482.24  5011.9  482.21
  5012.2  481.71  5015.7  481.71  5015.9  482.21  5022.0  482.88  5049.5  483.39
  5181.0  482.60  5202.3  483.21  5217.7  482.94  5260.5  484.47  5275.9  485.47
  5341.5  486.48  5407.7  489.54  5423.2  489.39  5481.3  490.26  5527.1  491.84
#Mann=5,-1,0
  4409.5    0.05       0  5011.9    0.04       0  5015.9    0.05       0
  5049.5    0.12       0  5217.7    0.05       0
Bank Sta=5011.9,5015.9
Exp/Cntr=0.3,0.1

Type RM Length L Ch R = 1,928,135,135,135
BEGIN DESCRIPTION:
Lacy 063 2426
END DESCRIPTION:
XS GIS Cut Line= 3
      2760032.06      6887731.84      2759424.51      6888095.32
      2759062.10      6888351.86
#Sta/Elev= 30
  4294.3  487.82  4357.3  485.59  4421.5  484.42  4437.1  483.44  4495.4  481.64
  4596.5  480.35  4633.5  479.37  4707.4  479.14  4787.2  480.35  4793.0  480.98
  4808.5  480.61  4829.9  481.11  4845.5  480.41  4851.3  480.85  4888.3  480.26
  4925.2  478.68  4951.9  478.35  4952.2  477.85  4955.7  477.85  4955.9  478.35
  5070.3  478.77  5171.2  480.13  5227.8  482.57  5233.9  482.16  5242.6  482.55
  5257.3  483.29  5263.5  484.45  5306.8  485.23  5328.7  486.48  5446.3  487.22
#Mann=3,-1,0
  4294.3    0.05       0  4951.9    0.04       0  4955.9    0.05       0
Bank Sta=4951.9,4955.9
Exp/Cntr=0.3,0.1

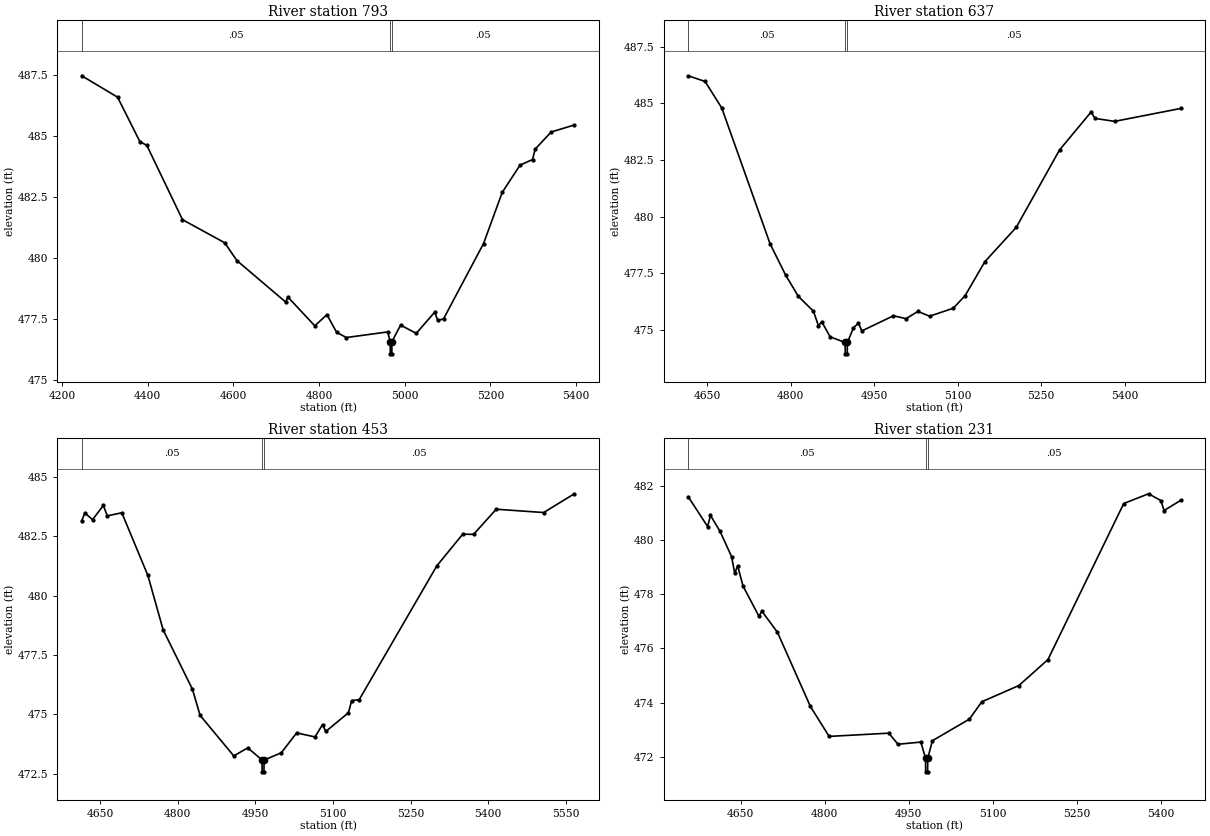
Type RM Length L Ch R = 1,793,156,156,156
BEGIN DESCRIPTION:
Lacy 063 2427
END DESCRIPTION:
XS GIS Cut Line= 3
      2760058.54      6887651.02      2759378.53      6887973.33
      2759063.27      6888215.22
#Sta/Elev= 30
  4246.1  487.48  4329.8  486.60  4381.7  484.78  4398.1  484.62  4481.3  481.57
  4580.0  480.62  4608.3  479.89  4722.0  478.19  4727.5  478.39  4790.2  477.21
  4818.5  477.67  4841.2  476.94  4863.9  476.73  4960.4  476.96  4966.2  476.56
  4966.5  476.06  4970.0  476.06  4970.2  476.56  4990.4  477.24  5027.0  476.90
  5069.9  477.77  5077.4  477.43  5090.8  477.50  5184.1  480.59  5227.7  482.69
  5269.3  483.81  5298.4  484.04  5304.7  484.47  5341.9  485.17  5396.0  485.46
#Mann=3,-1,0
  4246.1    0.05       0  4966.2    0.04       0  4970.2    0.05       0
Bank Sta=4966.2,4970.2
Exp/Cntr=0.3,0.1

Type RM Length L Ch R = 1,637,184,184,184
BEGIN DESCRIPTION:
Lacy 063 2425
END DESCRIPTION:
XS GIS Cut Line= 3
      2759661.13      6887612.38      2759346.53      6887825.41
      2758997.11      6888189.96
#Sta/Elev= 30
  4616.1  486.21  4646.4  485.96  4676.4  484.79  4763.2  478.80  4791.4  477.41
  4814.1  476.48  4841.1  475.83  4850.1  475.19  4856.1  475.36  4871.1  474.70
  4898.1  474.45  4898.3  473.95  4901.8  473.95  4902.1  474.45  4913.0  475.10
  4922.0  475.30  4928.0  474.96  4984.9  475.63  5007.4  475.50  5028.7  475.82
  5049.8  475.61  5092.3  475.96  5113.7  476.52  5148.9  478.01  5205.5  479.53
  5283.2  482.94  5339.8  484.61  5347.0  484.33  5382.2  484.20  5501.0  484.77
#Mann=3,-1,0
  4616.1    0.05       0  4898.1    0.04       0  4902.1    0.05       0
Bank Sta=4898.1,4902.1
Exp/Cntr=0.3,0.1

Type RM Length L Ch R = 1,453,222,222,222
BEGIN DESCRIPTION:
Lacy 063 2431
END DESCRIPTION:
XS GIS Cut Line= 3
      2759596.26      6887442.66      2759281.62      6887665.91
      2758943.17      6888120.32
#Sta/Elev= 30
  4614.2  483.16  4620.3  483.48  4635.1  483.20  4656.0  483.80  4663.6  483.36
  4691.7  483.49  4742.1  480.85  4771.6  478.56  4828.2  476.06  4843.0  474.96
  4908.2  473.25  4935.2  473.59  4962.8  473.08  4963.0  472.58  4966.5  472.58
  4966.8  473.08  5000.0  473.38  5029.8  474.22  5065.2  474.05  5079.8  474.57
  5086.1  474.28  5129.9  475.07  5136.1  475.58  5150.7  475.62  5300.9  481.26
  5350.9  482.59  5371.8  482.58  5415.6  483.64  5507.3  483.50  5566.6  484.29
#Mann=3,-1,0
  4614.2    0.05       0  4962.8    0.04       0  4966.8    0.05       0
Bank Sta=4962.8,4966.8
Exp/Cntr=0.3,0.1

Type RM Length L Ch R = 1,231,0,0,0
BEGIN DESCRIPTION:
Lacy 063 2430
END DESCRIPTION:
XS GIS Cut Line= 3
      2759561.53      6887407.64      2759128.53      6887504.95
      2758926.51      6887891.32
#Sta/Elev= 30
  4556.2  481.61  4590.9  480.51  4596.0  480.92  4613.1  480.33  4633.6  479.40
  4639.3  478.78  4644.5  479.06  4654.1  478.31  4682.6  477.19  4687.8  477.38
  4715.6  476.60  4774.4  473.86  4807.9  472.75  4914.5  472.87  4930.8  472.46
  4971.8  472.54  4980.1  471.94  4980.3  471.44  4983.8  471.44  4984.1  471.94
  4992.3  472.59  5058.5  473.39  5080.6  474.03  5146.8  474.63  5198.7  475.59
  5334.1  481.36  5378.4  481.72  5400.4  481.47  5406.1  481.10  5436.0  481.48
#Mann=3,-1,0
  4556.2    0.05       0  4980.1    0.04       0  4984.1    0.05       0
Bank Sta=4980.1,4984.1
Exp/Cntr=0.3,0.1

Chan Stop Cuts=-1