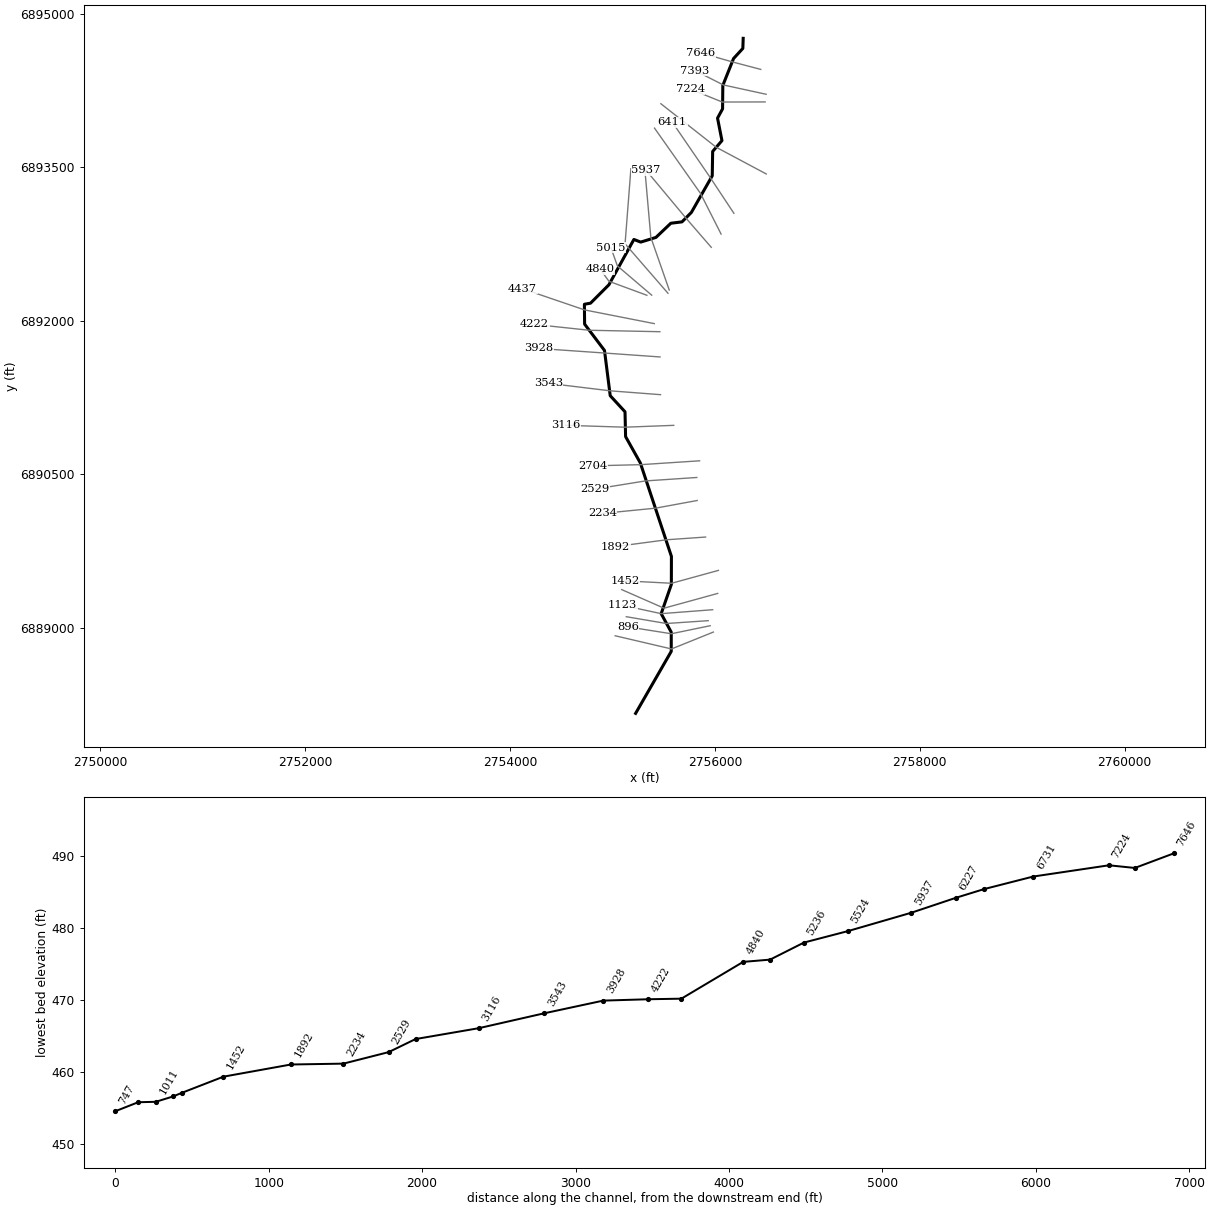
--- Lacy 064.prj (project) ---

Proj Title=Lacy 064 Base Level Engineering
Current Plan=p01
Default Exp/Contr=0.3,0.1
English Units
Geom File=g01
Flow File=f01
Plan File=p01
BEGIN DESCRIPTION:
Lacy 064
END DESCRIPTION:

--- Lacy 064.p01 (plan) ---

Plan Title=Multiple Run
Short Identifier=Multiple
Geom File=g01
Flow File=f01
Subcritical Flow
K Sum by GR= 0
Std Step Tol= 0.01
Critical Tol= 0.01
Num of Std Step Trials= 20
Max Error Tol= 0.3
Flow Tol Ratio= 0.001
Split Flow NTrial= 30
Split Flow Tol= 0.02
Split Flow Ratio= 0.02
Log Output Level= 0
Friction Slope Method= 1
Unsteady Friction Slope Method= 2
Unsteady Bridges Friction Slope Method= 1
Parabolic Critical Depth
Global Vel Dist=  1 , 1 , 1
Global Log Level= 0
CheckData=True
Encroach Param= -1, 0, 0, 0
BEGIN DESCRIPTION:
Multiple Run
END DESCRIPTION:

--- Lacy 064.f01 (steady flow) ---

Flow Title=Multiple
Number of Profiles=7
Profile Names=10-year,25-year,50-year,1pct_min,100-year,1pct_plu,500-year
River Rch & RM= Lacy 064,Reach-1,7646
     226     285     330     191     380     759     505
River Rch & RM= Lacy 064,Reach-1,4437
     476     629     751     446     890    1776    1253
Boundary for River Rch & Prof#=Lacy 064,Reach-1,1
Up Type=0
Dn Type=3
Dn Slope=0.005
Boundary for River Rch & Prof#=Lacy 064,Reach-1,2
Up Type=0
Dn Type=3
Dn Slope=0.005
Boundary for River Rch & Prof#=Lacy 064,Reach-1,3
Up Type=0
Dn Type=3
Dn Slope=0.005
Boundary for River Rch & Prof#=Lacy 064,Reach-1,4
Up Type=0
Dn Type=3
Dn Slope=0.005
Boundary for River Rch & Prof#=Lacy 064,Reach-1,5
Up Type=0
Dn Type=3
Dn Slope=0.005
Boundary for River Rch & Prof#=Lacy 064,Reach-1,6
Up Type=0
Dn Type=3
Dn Slope=0.005
Boundary for River Rch & Prof#=Lacy 064,Reach-1,7
Up Type=0
Dn Type=3
Dn Slope=0.005

--- Lacy 064.g01 (geometry) ---

Geom Title=Existing Conditions

River Reach=Lacy 064,Reach-1
Reach XY= 30
      2756276.00      6894761.00      2756272.61      6894662.41
      2756181.84      6894563.29      2756077.22      6894300.50
      2756074.78      6894071.50      2756025.64      6893981.15
      2756068.67      6893760.90      2755978.08      6893655.15
      2755973.94      6893416.86      2755770.17      6893058.69
      2755678.44      6892966.52      2755569.83      6892953.14
      2755424.50      6892814.61      2755275.90      6892768.80
      2755209.30      6892794.63      2754965.24      6892351.32
      2754785.79      6892171.51      2754726.00      6892161.00
      2754728.22      6891966.90      2754922.25      6891709.45
      2754978.23      6891266.90      2755122.52      6891109.74
      2755128.24      6890866.93      2755272.17      6890609.42
      2755575.48      6889695.78      2755574.78      6889421.50
      2755475.59      6889136.00      2755573.76      6888955.07
      2755573.76      6888766.93      2755226.00      6888161.00

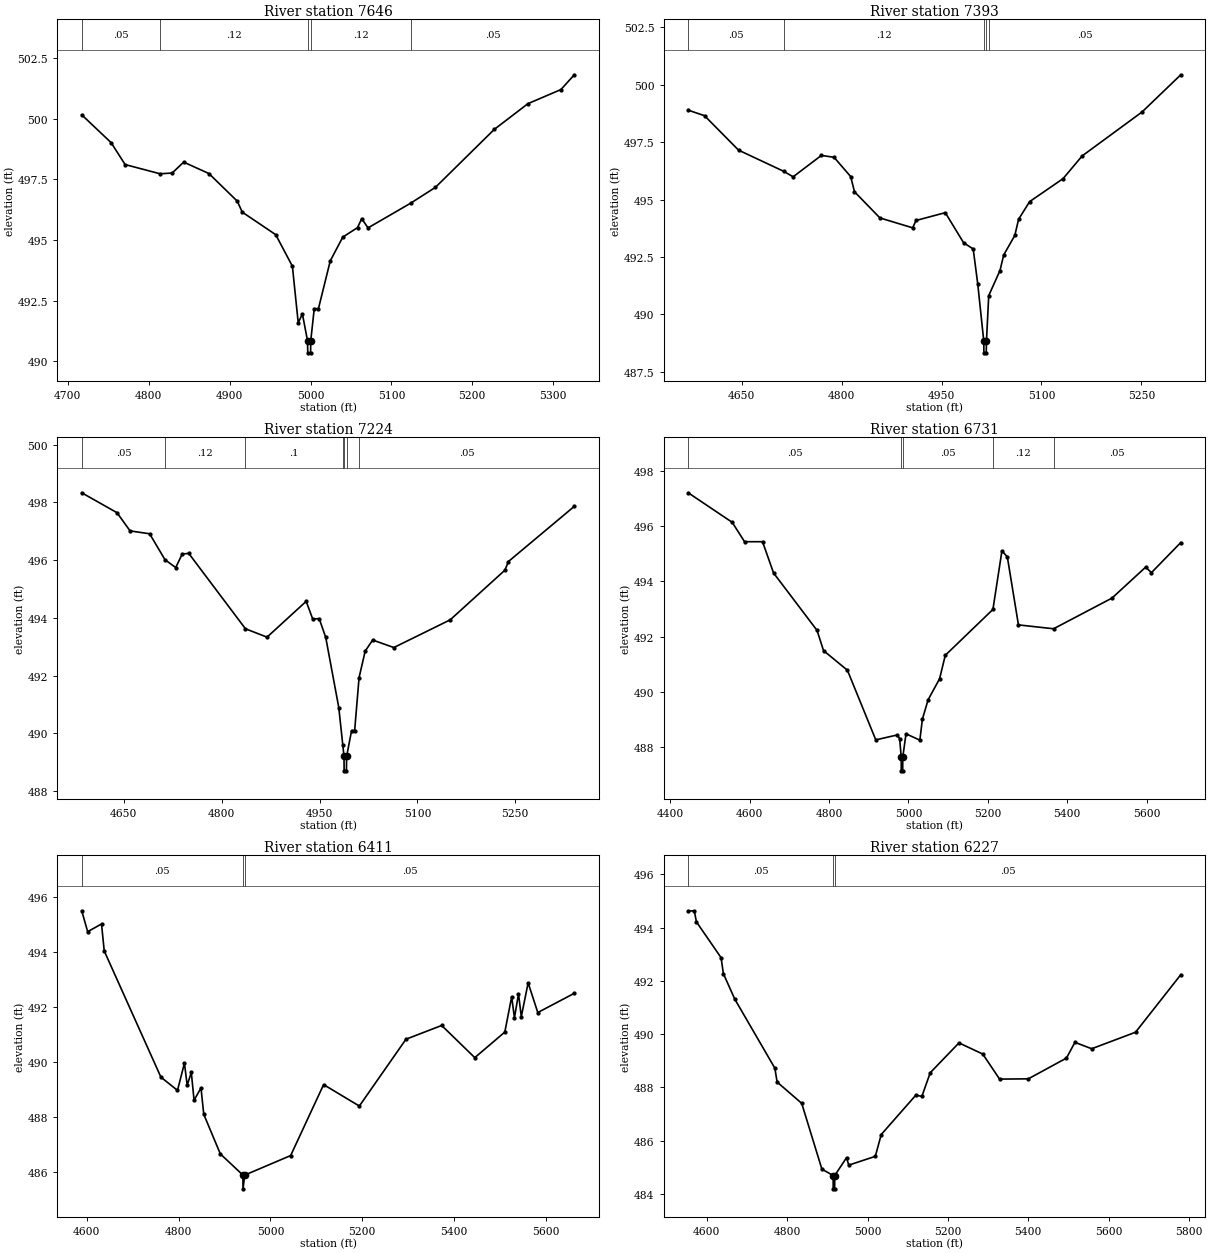
Type RM Length L Ch R = 1,7646,253,253,253
BEGIN DESCRIPTION:
Lacy 064 2416
END DESCRIPTION:
XS GIS Cut Line= 3
      2756447.79      6894457.11      2756168.81      6894530.84
      2755860.96      6894619.43
#Sta/Elev= 30
  4717.2  500.16  4753.6  499.01  4770.8  498.11  4814.0  497.73  4829.0  497.76
  4843.2  498.21  4874.4  497.74  4909.5  496.60  4915.6  496.15  4957.0  495.22
  4977.6  493.92  4984.8  491.59  4990.0  491.95  4996.3  490.85  4996.6  490.35
  5000.1  490.35  5000.3  490.85  5004.6  492.17  5009.8  492.17  5024.4  494.14
  5039.9  495.12  5058.1  495.51  5063.3  495.88  5071.1  495.50  5123.9  496.52
  5154.4  497.17  5227.2  499.56  5268.8  500.62  5309.5  501.20  5326.1  501.81
#Mann=5,-1,0
  4717.2    0.05       0  4814.0    0.12       0  4996.3    0.07       0
  5000.3    0.12       0  5123.9    0.05       0
Bank Sta=4996.3,5000.3
Exp/Cntr=0.3,0.1

Type RM Length L Ch R = 1,7393,169,169,169
BEGIN DESCRIPTION:
Lacy 064 2415
END DESCRIPTION:
XS GIS Cut Line= 3
      2756499.91      6894214.19      2756081.89      6894305.32
      2755804.06      6894446.31
#Sta/Elev= 30
  4569.7  498.89  4594.2  498.65  4645.3  497.15  4713.0  496.23  4727.2  495.99
  4769.6  496.92  4788.6  496.84  4813.6  496.00  4819.3  495.34  4857.5  494.20
  4906.6  493.77  4911.7  494.09  4955.6  494.43  4983.1  493.12  4997.5  492.85
  5004.4  491.31  5013.4  488.83  5013.6  488.33  5017.1  488.33  5017.4  488.83
  5020.8  490.82  5037.7  491.91  5043.3  492.59  5060.0  493.44  5065.6  494.14
  5082.2  494.91  5132.4  495.91  5161.1  496.90  5250.9  498.81  5309.1  500.43
#Mann=5,-1,0
  4569.7    0.05       0  4713.0    0.12       0  5013.4    0.07       0
  5017.4    0.12       0  5020.8    0.05       0
Bank Sta=5013.4,5017.4
Exp/Cntr=0.3,0.1

Type RM Length L Ch R = 1,7224,493,493,493
BEGIN DESCRIPTION:
Lacy 064 3484
END DESCRIPTION:
XS GIS Cut Line= 3
      2756490.09      6894139.26      2756071.69      6894138.19
      2755759.64      6894264.90
#Sta/Elev= 30
  4585.4  498.33  4639.5  497.64  4659.5  497.01  4689.5  496.91  4713.1  496.01
  4729.5  495.74  4739.5  496.21  4749.5  496.23  4836.4  493.62  4869.5  493.33
  4929.5  494.57  4939.5  493.96  4949.5  493.97  4959.5  493.32  4979.5  490.89
  4985.7  489.58  4987.5  489.20  4987.7  488.70  4991.2  488.70  4991.5  489.20
  4999.1  490.09  5003.8  490.09  5010.6  491.93  5020.0  492.85  5031.5  493.23
  5063.9  492.97  5150.3  493.93  5234.2  495.65  5239.6  495.95  5340.6  497.86
#Mann=7,-1,0
  4585.4    0.05       0  4713.1    0.12       0  4836.4     0.1       0
  4985.7    0.12       0  4987.5    0.07       0  4991.5    0.12       0
  5010.6    0.05       0
Bank Sta=4987.5,4991.5
Exp/Cntr=0.3,0.1

Type RM Length L Ch R = 1,6731,320,320,320
BEGIN DESCRIPTION:
Lacy 064 2414
END DESCRIPTION:
XS GIS Cut Line= 3
      2756501.27      6893434.92      2756013.13      6893695.78
      2755472.58      6894121.62
#Sta/Elev= 30
  4444.8  497.20  4555.8  496.13  4586.8  495.43  4632.2  495.43  4659.9  494.30
  4769.6  492.22  4785.9  491.49  4846.1  490.78  4917.6  488.26  4972.1  488.44
  4977.8  488.30  4981.7  487.64  4981.9  487.14  4985.4  487.14  4985.7  487.64
  4993.8  488.48  5028.7  488.25  5035.1  489.01  5049.5  489.71  5078.4  490.47
  5092.8  491.32  5212.9  492.98  5235.6  495.10  5249.2  494.88  5277.2  492.42
  5365.8  492.28  5513.0  493.39  5597.9  494.51  5612.4  494.31  5686.4  495.40
#Mann=5,-1,0
  4444.8    0.05       0  4981.7    0.04       0  4985.7    0.05       0
  5212.9    0.12       0  5365.8    0.05       0
Bank Sta=4981.7,4985.7
Exp/Cntr=0.3,0.1

Type RM Length L Ch R = 1,6411,184,184,184
BEGIN DESCRIPTION:
Lacy 064 2399
END DESCRIPTION:
XS GIS Cut Line= 3
      2756185.04      6893050.54      2755952.04      6893403.35
      2755584.79      6893939.90
#Sta/Elev= 30
  4588.9  495.51  4601.8  494.75  4632.0  495.03  4637.9  494.05  4761.4  489.46
  4797.5  488.98  4812.6  489.97  4818.6  489.17  4827.6  489.63  4833.6  488.62
  4848.7  489.07  4854.7  488.11  4890.8  486.67  4940.0  485.90  4940.2  485.40
  4944.0  485.90  5044.0  486.61  5115.8  489.19  5193.6  488.41  5295.2  490.84
  5373.0  491.34  5445.1  490.17  5510.5  491.10  5525.4  492.38  5531.5  491.62
  5540.3  492.49  5546.4  491.66  5561.3  492.89  5582.3  491.81  5661.9  492.51
#Mann=3,-1,0
  4588.9    0.05       0  4940.0    0.04       0  4944.0    0.05       0
Bank Sta=4940,4944
Exp/Cntr=0.3,0.1

Type RM Length L Ch R = 1,6227,290,290,290
BEGIN DESCRIPTION:
Lacy 064 2400
END DESCRIPTION:
XS GIS Cut Line= 3
      2756060.19      6892847.43      2755859.08      6893245.22
      2755410.58      6893883.09
#Sta/Elev= 30
  4553.9  494.62  4568.9  494.63  4574.5  494.21  4635.7  492.87  4641.4  492.27
  4669.9  491.31  4769.5  488.72  4775.1  488.20  4836.3  487.40  4886.5  484.93
  4914.5  484.69  4914.7  484.19  4918.2  484.19  4918.5  484.69  4947.8  485.36
  4953.4  485.08  5019.4  485.41  5034.2  486.23  5120.4  487.71  5135.2  487.66
  5156.1  488.55  5227.6  489.67  5286.8  489.25  5328.6  488.31  5400.1  488.32
  5495.0  489.10  5516.0  489.69  5557.8  489.45  5666.8  490.07  5779.4  492.23
#Mann=3,-1,0
  4553.9    0.05       0  4914.5    0.04       0  4918.5    0.05       0
Bank Sta=4914.5,4918.5
Exp/Cntr=0.3,0.1

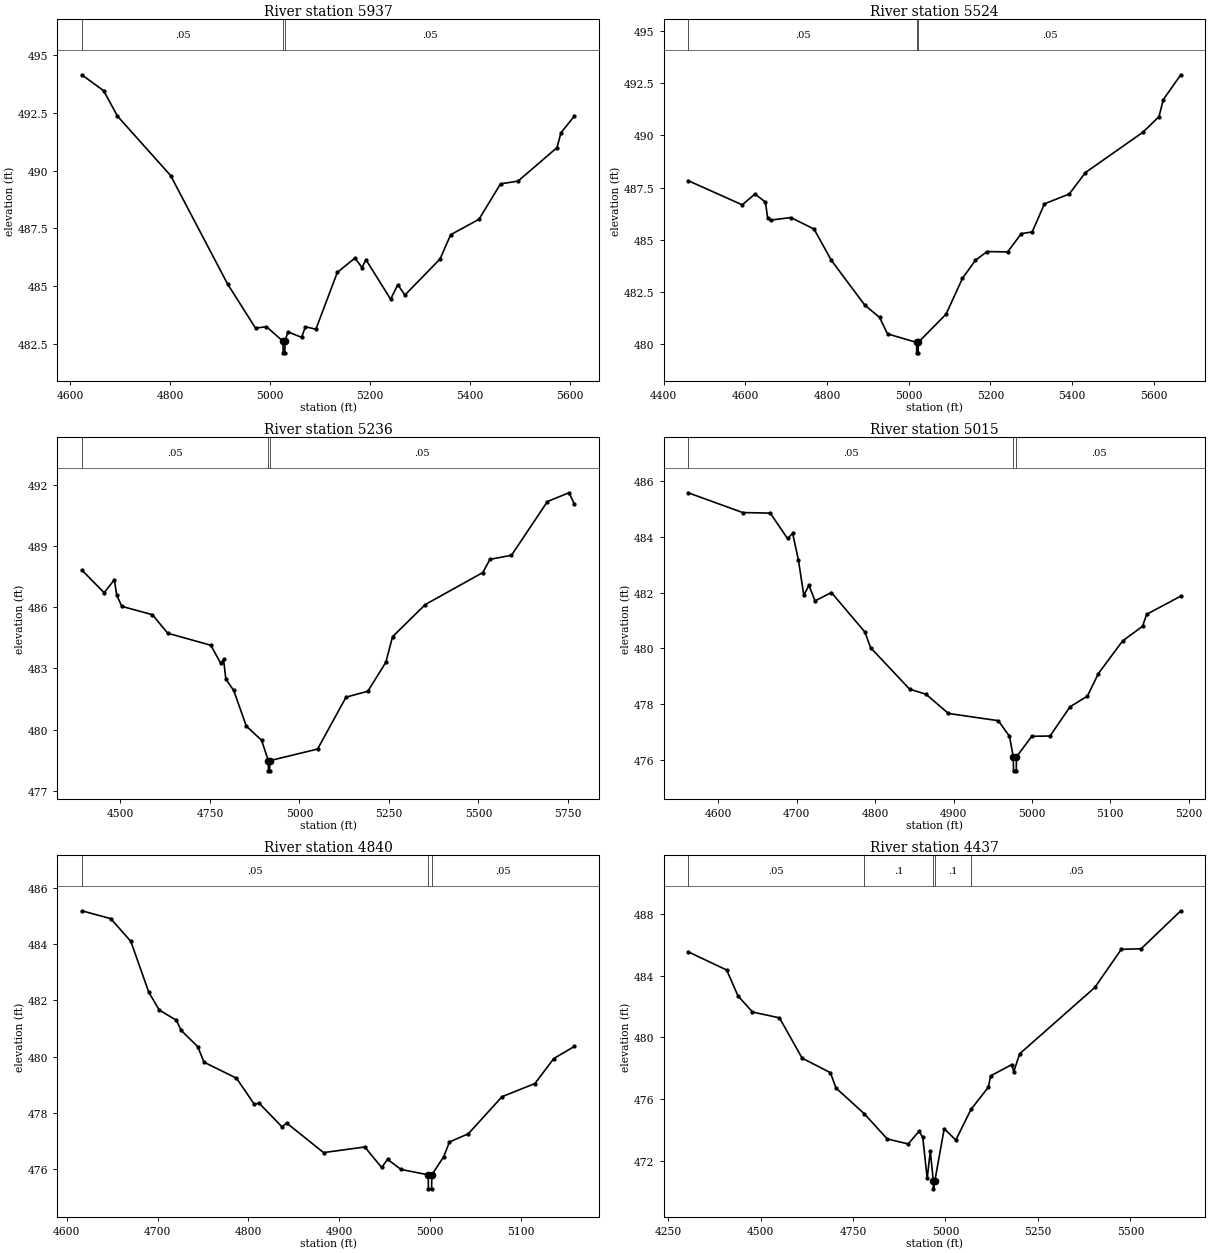
Type RM Length L Ch R = 1,5937,413,413,413
BEGIN DESCRIPTION:
Lacy 064 2401
END DESCRIPTION:
XS GIS Cut Line= 3
      2755964.35      6892717.82      2755724.36      6892995.16
      2755327.78      6893471.27
#Sta/Elev= 30
  4622.5  494.15  4666.4  493.46  4694.1  492.36  4800.5  489.79  4914.5  485.10
  4970.5  483.19  4992.4  483.25  5025.6  482.62  5025.8  482.12  5029.3  482.12
  5029.6  482.62  5035.4  483.03  5062.7  482.79  5070.5  483.25  5091.4  483.14
  5134.3  485.60  5169.5  486.22  5183.8  485.81  5191.6  486.15  5241.1  484.44
  5255.4  485.07  5269.7  484.62  5340.0  486.18  5361.3  487.23  5418.1  487.90
  5461.1  489.43  5496.2  489.55  5574.3  491.00  5582.1  491.64  5608.9  492.36
#Mann=3,-1,0
  4622.5    0.05       0  5025.6    0.04       0  5029.6    0.05       0
Bank Sta=5025.6,5029.6
Exp/Cntr=0.3,0.1

Type RM Length L Ch R = 1,5524,288,288,288
BEGIN DESCRIPTION:
Lacy 064 2402
END DESCRIPTION:
XS GIS Cut Line= 3
      2755554.27      6892300.00      2755374.51      6892815.21
      2755316.70      6893473.61
#Sta/Elev= 30
  4459.8  487.83  4592.2  486.67  4623.3  487.19  4649.0  486.80  4654.3  486.06
  4662.1  485.94  4711.2  486.06  4768.0  485.51  4810.4  484.01  4892.3  481.86
  4928.6  481.27  4948.0  480.48  5019.3  480.07  5019.6  479.57  5023.1  479.57
  5023.3  480.07  5091.6  481.43  5131.7  483.15  5163.4  484.01  5192.0  484.43
  5242.2  484.41  5275.8  485.29  5302.4  485.37  5332.5  486.72  5393.2  487.19
  5432.9  488.22  5573.4  490.15  5612.9  490.90  5623.6  491.72  5666.4  492.91
#Mann=3,-1,0
  4459.8    0.05       0  5019.3    0.04       0  5023.3    0.05       0
Bank Sta=5019.3,5023.3
Exp/Cntr=0.3,0.1

Type RM Length L Ch R = 1,5236,221,221,221
BEGIN DESCRIPTION:
Lacy 064 2403
END DESCRIPTION:
XS GIS Cut Line= 3
      2755541.85      6892268.52      2755123.04      6892751.94
      2755180.00      6893485.92
#Sta/Elev= 30
  4392.0  487.84  4454.6  486.72  4483.1  487.36  4489.7  486.60  4504.0  486.05
  4589.5  485.64  4632.2  484.73  4752.5  484.14  4780.3  483.25  4788.0  483.45
  4794.6  482.47  4816.5  481.92  4851.6  480.17  4894.4  479.47  4913.2  478.47
  4913.5  477.97  4917.0  477.97  4917.2  478.47  5050.7  479.04  5130.2  481.59
  5191.1  481.88  5241.3  483.30  5260.1  484.56  5351.6  486.14  5512.1  487.71
  5532.2  488.36  5592.3  488.56  5692.7  491.20  5752.8  491.63  5767.8  491.09
#Mann=3,-1,0
  4392.0    0.05       0  4913.2    0.04       0  4917.2    0.05       0
Bank Sta=4913.2,4917.2
Exp/Cntr=0.3,0.1

Type RM Length L Ch R = 1,5015,175,175,175
BEGIN DESCRIPTION:
Lacy 064 3450
END DESCRIPTION:
XS GIS Cut Line= 3
      2755382.93      6892249.95      2755048.19      6892535.88
      2754985.14      6892713.27
#Sta/Elev= 30
  4561.4  485.58  4631.0  484.87  4666.1  484.85  4688.1  483.94  4694.7  484.12
  4702.0  483.17  4708.9  481.90  4715.5  482.26  4723.2  481.70  4744.1  482.00
  4786.9  480.58  4794.1  480.02  4844.0  478.53  4864.8  478.35  4893.4  477.66
  4957.1  477.40  4971.3  476.84  4976.2  476.10  4976.5  475.60  4980.0  475.60
  4980.2  476.10  4999.8  476.84  5023.1  476.85  5048.6  477.90  5070.7  478.28
  5084.7  479.09  5115.6  480.26  5141.1  480.79  5146.4  481.22  5189.9  481.87
#Mann=3,-1,0
  4561.4    0.05       0  4976.2    0.04       0  4980.2    0.05       0
Bank Sta=4976.2,4980.2
Exp/Cntr=0.3,0.1

Type RM Length L Ch R = 1,4840,403,403,403
BEGIN DESCRIPTION:
Lacy 064 3451
END DESCRIPTION:
XS GIS Cut Line= 3
      2755335.97      6892248.81      2754966.08      6892385.47
      2754878.58      6892505.42
#Sta/Elev= 30
  4616.5  485.19  4648.5  484.91  4670.6  484.10  4690.4  482.29  4701.8  481.66
  4720.8  481.29  4726.1  480.93  4744.4  480.35  4751.2  479.80  4787.0  479.23
  4806.7  478.30  4812.0  478.34  4837.1  477.50  4842.4  477.63  4883.0  476.58
  4928.4  476.78  4947.0  476.05  4953.5  476.34  4968.3  475.98  4998.3  475.79
  4998.5  475.29  5002.0  475.29  5002.3  475.79  5015.5  476.44  5021.7  476.96
  5042.5  477.25  5079.6  478.57  5115.9  479.04  5136.7  479.93  5159.3  480.36
#Mann=3,-1,0
  4616.5    0.05       0  4998.3    0.04       0  5002.3    0.05       0
Bank Sta=4998.3,5002.3
Exp/Cntr=0.3,0.1

Type RM Length L Ch R = 1,4437,215,215,215
BEGIN DESCRIPTION:
Lacy 064 2398
END DESCRIPTION:
XS GIS Cut Line= 3
      2755408.19      6891971.78      2754727.31      6892105.89
      2754123.81      6892312.05
#Sta/Elev= 30
  4304.5  485.54  4408.6  484.36  4439.2  482.68  4478.2  481.64  4551.3  481.26
  4612.5  478.65  4688.8  477.71  4704.2  476.71  4780.4  475.05  4842.8  473.41
  4899.3  473.09  4928.4  473.91  4938.6  473.52  4950.6  470.86  4959.0  472.62
  4967.2  470.68  4967.5  470.18  4971.2  470.68  4996.6  474.08  5028.0  473.34
  5069.1  475.33  5116.1  476.77  5122.0  477.50  5179.3  478.23  5184.6  477.77
  5200.6  478.93  5403.8  483.23  5475.4  485.70  5529.1  485.74  5636.2  488.20
#Mann=5,-1,0
  4304.5    0.05       0  4780.4     0.1       0  4967.2    0.07       0
  4971.2     0.1       0  5069.1    0.05       0
Bank Sta=4967.2,4971.2
Exp/Cntr=0.3,0.1

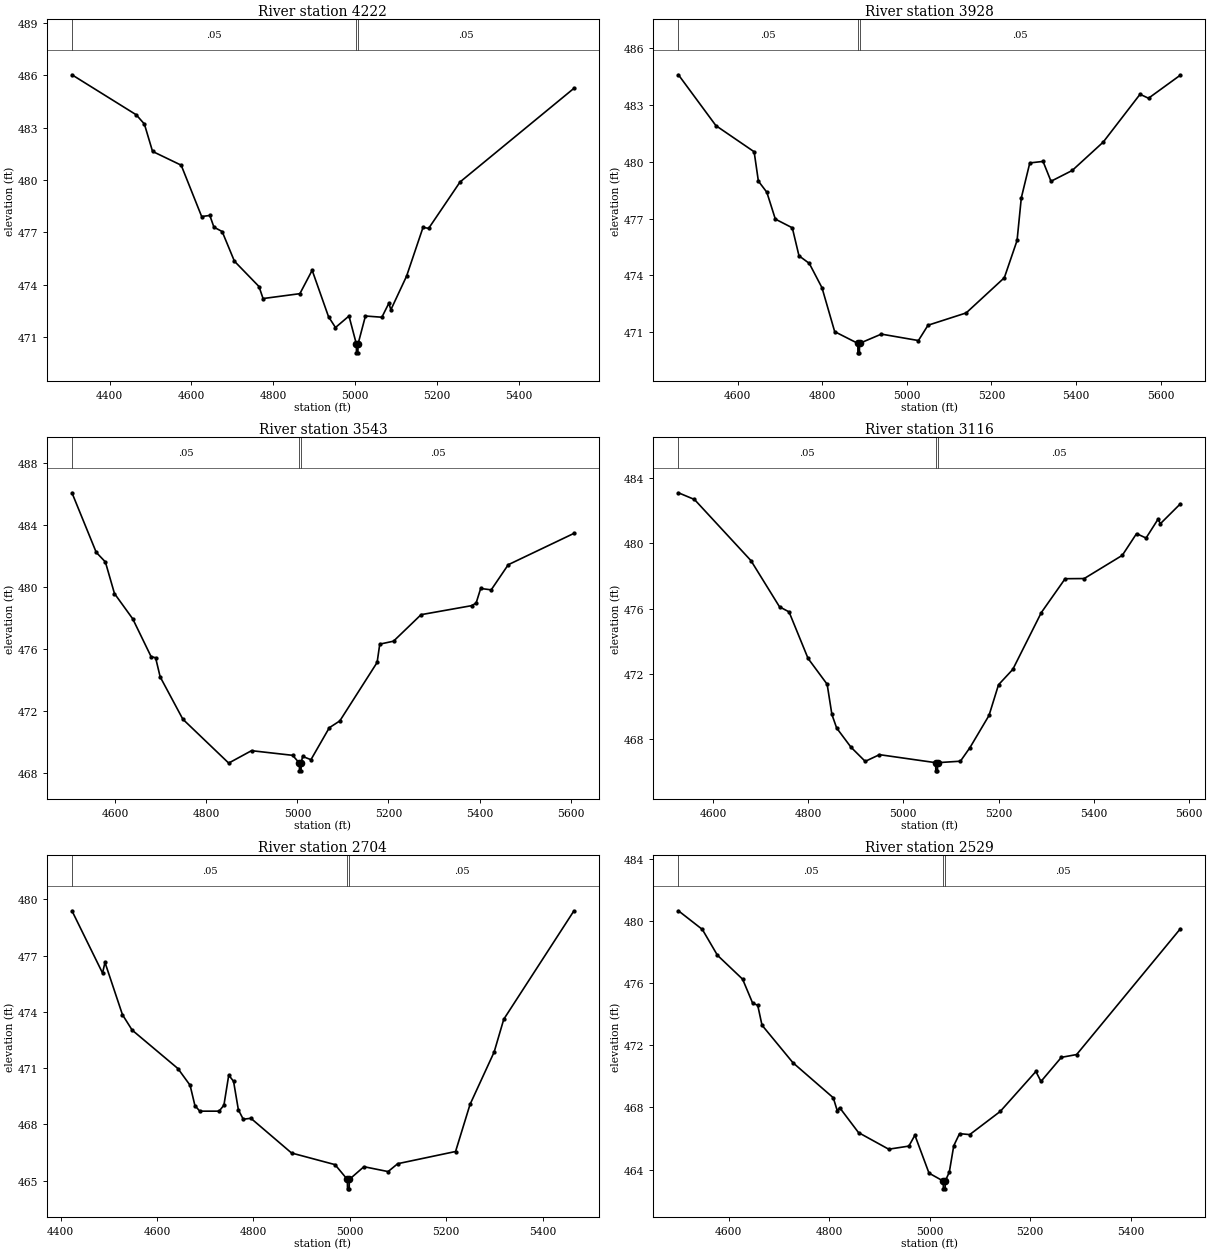
Type RM Length L Ch R = 1,4222,294,294,294
BEGIN DESCRIPTION:
Lacy 064 2397
END DESCRIPTION:
XS GIS Cut Line= 3
      2755462.97      6891892.57      2754771.74      6891906.94
      2754239.47      6891963.95
#Sta/Elev= 30
  4308.1  486.03  4465.1  483.74  4485.1  483.21  4505.1  481.64  4575.1  480.85
  4625.1  477.91  4645.1  477.97  4655.1  477.30  4675.2  477.05  4705.2  475.35
  4765.2  473.90  4775.2  473.21  4865.2  473.49  4895.2  474.83  4935.2  472.17
  4952.2  471.55  4985.2  472.21  5003.3  470.60  5003.5  470.10  5007.0  470.10
  5007.3  470.60  5025.4  472.21  5065.6  472.14  5082.6  472.94  5087.6  472.57
  5125.9  474.49  5166.2  477.29  5179.9  477.23  5256.7  479.89  5534.8  485.25
#Mann=3,-1,0
  4308.1    0.05       0  5003.3    0.05       0  5007.3    0.05       0
Bank Sta=5003.3,5007.3
Exp/Cntr=0.3,0.1

Type RM Length L Ch R = 1,3928,385,385,385
BEGIN DESCRIPTION:
Lacy 064 2395
END DESCRIPTION:
XS GIS Cut Line= 3
      2755464.51      6891645.83      2754917.96      6891684.49
      2754281.01      6891728.77
#Sta/Elev= 30
  4460.1  484.61  4548.8  481.92  4639.1  480.54  4649.1  478.99  4669.1  478.40
  4689.2  476.98  4729.3  476.52  4745.1  475.04  4769.4  474.64  4799.5  473.35
  4829.5  471.03  4884.2  470.41  4884.4  469.91  4887.9  469.91  4888.2  470.41
  4939.8  470.90  5027.4  470.56  5050.1  471.37  5140.3  472.02  5230.5  473.88
  5260.6  475.85  5270.6  478.10  5290.7  479.95  5322.0  480.03  5340.8  478.98
  5390.9  479.55  5464.2  481.05  5551.3  483.58  5571.3  483.37  5646.5  484.59
#Mann=3,-1,0
  4460.1    0.05       0  4884.2    0.04       0  4888.2    0.05       0
Bank Sta=4884.2,4888.2
Exp/Cntr=0.3,0.1

Type RM Length L Ch R = 1,3543,427,427,427
BEGIN DESCRIPTION:
Lacy 064 2396
END DESCRIPTION:
XS GIS Cut Line= 3
      2755469.15      6891277.06      2754979.76      6891314.52
      2754372.93      6891388.10
#Sta/Elev= 30
  4505.0  486.08  4558.3  482.24  4578.4  481.62  4598.4  479.58  4638.5  477.95
  4678.7  475.52  4688.7  475.44  4698.7  474.21  4748.5  471.48  4849.2  468.65
  4899.3  469.45  4989.6  469.15  5004.4  468.65  5004.6  468.15  5008.1  468.15
  5008.4  468.65  5011.4  469.08  5029.8  468.87  5070.1  470.93  5093.2  471.37
  5175.1  475.14  5180.9  476.32  5211.1  476.51  5271.6  478.22  5382.4  478.80
  5392.5  478.97  5402.5  479.91  5425.6  479.82  5463.0  481.44  5607.1  483.46
#Mann=3,-1,0
  4505.0    0.05       0  5004.4    0.04       0  5008.4    0.05       0
Bank Sta=5004.4,5008.4
Exp/Cntr=0.3,0.1

Type RM Length L Ch R = 1,3116,412,412,412
BEGIN DESCRIPTION:
Lacy 064 2394
END DESCRIPTION:
XS GIS Cut Line= 3
      2755598.33      6890977.14      2755122.06      6890959.06
      2754544.06      6890977.49
#Sta/Elev= 30
  4527.2  483.10  4560.9  482.69  4679.6  478.95  4739.7  476.12  4759.7  475.81
  4799.7  472.96  4839.8  471.38  4849.8  469.53  4859.8  468.70  4889.8  467.53
  4919.8  466.66  4949.8  467.07  5067.9  466.58  5068.2  466.08  5071.7  466.08
  5071.9  466.58  5119.9  466.67  5139.9  467.50  5180.0  469.47  5200.0  471.35
  5230.0  472.29  5290.0  475.77  5340.0  477.84  5380.1  477.85  5460.1  479.27
  5490.1  480.60  5510.1  480.33  5535.2  481.48  5540.3  481.21  5582.1  482.42
#Mann=3,-1,0
  4527.2    0.05       0  5067.9    0.04       0  5071.9    0.05       0
Bank Sta=5067.9,5071.9
Exp/Cntr=0.3,0.1

Type RM Length L Ch R = 1,2704,175,175,175
BEGIN DESCRIPTION:
Lacy 064 2393
END DESCRIPTION:
XS GIS Cut Line= 3
      2755850.60      6890630.42      2755275.82      6890592.63
      2754810.68      6890581.32
#Sta/Elev= 30
  4423.6  479.39  4487.1  476.07  4492.1  476.64  4528.4  473.85  4548.5  473.03
  4643.5  470.98  4668.7  470.09  4678.7  469.01  4688.8  468.71  4728.9  468.71
  4738.9  469.03  4748.9  470.63  4758.9  470.30  4768.9  468.78  4779.0  468.28
  4794.9  468.33  4879.2  466.48  4969.4  465.86  4995.0  465.07  4995.3  464.57
  4998.8  464.57  4999.0  465.07  5029.4  465.75  5079.5  465.49  5099.5  465.91
  5219.5  466.56  5249.5  469.07  5299.5  471.86  5319.5  473.61  5464.9  479.38
#Mann=3,-1,0
  4423.6    0.05       0  4995.0    0.04       0  4999.0    0.05       0
Bank Sta=4995,4999
Exp/Cntr=0.3,0.1

Type RM Length L Ch R = 1,2529,295,295,295
BEGIN DESCRIPTION:
Lacy 064 2391
END DESCRIPTION:
XS GIS Cut Line= 3
      2755823.45      6890467.40      2755320.03      6890433.51
      2754832.34      6890354.54
#Sta/Elev= 30
  4500.2  480.65  4547.8  479.45  4577.8  477.79  4627.9  476.25  4648.0  474.70
  4658.0  474.57  4666.5  473.29  4728.2  470.87  4808.3  468.62  4816.1  467.80
  4821.1  467.98  4858.5  466.38  4918.6  465.31  4958.7  465.51  4970.7  466.21
  4998.8  463.77  5027.1  463.26  5027.4  462.76  5030.9  462.76  5031.1  463.26
  5039.2  463.84  5048.0  465.53  5059.5  466.31  5079.8  466.25  5140.5  467.74
  5211.4  470.31  5221.6  469.67  5262.1  471.22  5292.5  471.40  5498.8  479.49
#Mann=3,-1,0
  4500.2    0.05       0  5027.1    0.04       0  5031.1    0.05       0
Bank Sta=5027.1,5031.1
Exp/Cntr=0.3,0.1

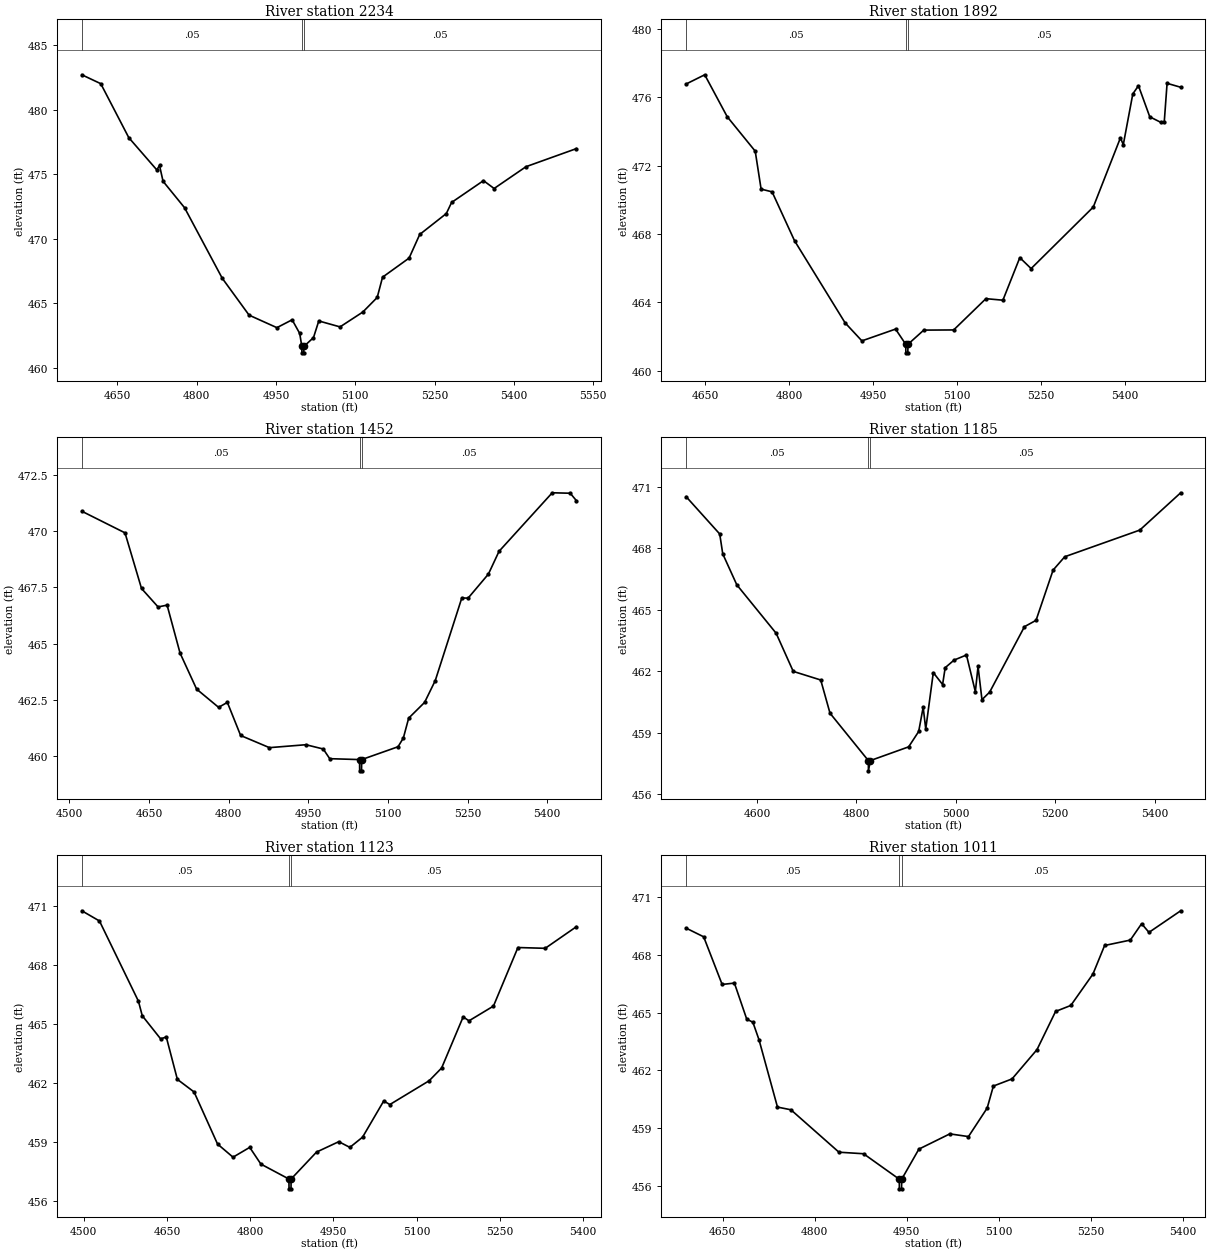
Type RM Length L Ch R = 1,2234,342,342,342
BEGIN DESCRIPTION:
Lacy 064 2392
END DESCRIPTION:
XS GIS Cut Line= 3
      2755827.08      6890242.35      2755421.84      6890167.55
      2754901.17      6890115.98
#Sta/Elev= 30
  4582.8  482.70  4618.6  482.01  4671.6  477.83  4724.6  475.33  4729.7  475.68
  4736.4  474.45  4777.1  472.40  4848.3  466.94  4899.1  464.08  4951.7  463.11
  4980.5  463.72  4994.9  462.66  4998.8  461.66  4999.0  461.16  5002.5  461.16
  5002.8  461.66  5020.9  462.34  5030.9  463.63  5071.1  463.17  5114.2  464.32
  5141.4  465.45  5151.5  467.02  5201.7  468.50  5221.8  470.33  5272.1  471.95
  5282.1  472.81  5342.4  474.50  5362.5  473.89  5422.8  475.58  5518.1  476.98
#Mann=3,-1,0
  4582.8    0.05       0  4998.8    0.04       0  5002.8    0.05       0
Bank Sta=4998.8,5002.8
Exp/Cntr=0.3,0.1

Type RM Length L Ch R = 1,1892,440,440,440
BEGIN DESCRIPTION:
Lacy 064 2390
END DESCRIPTION:
XS GIS Cut Line= 3
      2755909.13      6889885.00      2755528.38      6889858.42
      2755031.25      6889792.22
#Sta/Elev= 30
  4615.8  476.77  4649.0  477.31  4689.1  474.86  4739.2  472.84  4749.7  470.62
  4769.3  470.46  4809.4  467.60  4899.6  462.80  4929.7  461.74  4989.8  462.43
  5008.0  461.54  5008.2  461.04  5011.7  461.04  5012.0  461.54  5040.2  462.37
  5093.6  462.38  5151.2  464.21  5181.5  464.12  5211.7  466.61  5231.9  465.97
  5342.9  469.57  5391.4  473.62  5396.5  473.22  5413.5  476.19  5423.6  476.67
  5443.8  474.85  5463.9  474.52  5469.7  474.57  5474.7  476.81  5499.0  476.58
#Mann=3,-1,0
  4615.8    0.05       0  5008.0    0.04       0  5012.0    0.05       0
Bank Sta=5008,5012
Exp/Cntr=0.3,0.1

Type RM Length L Ch R = 1,1452,267,267,267
BEGIN DESCRIPTION:
Lacy 064 2389
END DESCRIPTION:
XS GIS Cut Line= 3
      2756034.40      6889559.00      2755577.22      6889433.15
      2755120.51      6889456.65
#Sta/Elev= 30
  4523.4  470.88  4604.7  469.92  4635.8  467.45  4667.0  466.63  4684.0  466.71
  4708.4  464.58  4739.6  462.98  4781.0  462.17  4797.5  462.39  4822.5  460.92
  4876.7  460.38  4945.5  460.51  4978.1  460.32  4990.3  459.89  5046.5  459.85
  5046.7  459.35  5050.2  459.35  5050.5  459.85  5119.0  460.42  5129.0  460.81
  5139.0  461.69  5169.0  462.39  5189.1  463.36  5239.1  467.03  5250.9  467.02
  5289.2  468.09  5309.2  469.10  5409.4  471.70  5443.3  471.68  5454.9  471.35
#Mann=3,-1,0
  4523.4    0.05       0  5046.5    0.04       0  5050.5    0.05       0
Bank Sta=5046.5,5050.5
Exp/Cntr=0.3,0.1

Type RM Length L Ch R = 1,1185,62,62,62
BEGIN DESCRIPTION:
Lacy 064 2387
END DESCRIPTION:
XS GIS Cut Line= 4
      2756027.08      6889333.70      2755544.37      6889200.72
      2755504.32      6889188.92      2755090.05      6889371.09
#Sta/Elev= 30
  4457.4  470.51  4525.0  468.69  4531.1  467.72  4559.4  466.21  4638.5  463.85
  4672.9  461.99  4728.2  461.57  4746.9  459.95  4824.0  457.64  4824.2  457.14
  4828.0  457.64  4905.1  458.31  4925.3  459.06  4934.3  460.24  4939.5  459.18
  4954.7  461.93  4973.4  461.35  4978.6  462.17  4996.4  462.54  5021.4  462.79
  5039.3  461.00  5044.7  462.23  5052.6  460.61  5068.1  460.98  5138.1  464.17
  5161.4  464.48  5195.7  466.93  5219.1  467.58  5370.1  468.88  5452.4  470.70
#Mann=3,-1,0
  4457.4    0.05       0  4824.0    0.04       0  4828.0    0.05       0
Bank Sta=4824,4828
Exp/Cntr=0.3,0.1

Type RM Length L Ch R = 1,1123,112,112,112
BEGIN DESCRIPTION:
Lacy 064 2386
END DESCRIPTION:
XS GIS Cut Line= 3
      2755977.72      6889174.46      2755475.59      6889136.00
      2755096.55      6889217.97
#Sta/Elev= 30
  4496.4  470.75  4528.2  470.23  4598.4  466.15  4605.3  465.41  4638.5  464.23
  4648.6  464.33  4668.6  462.17  4698.7  461.53  4741.0  458.88  4768.9  458.21
  4799.0  458.71  4819.1  457.86  4869.6  457.10  4869.9  456.60  4873.4  456.60
  4873.6  457.10  4919.4  458.47  4959.5  459.00  4979.5  458.71  5002.4  459.23
  5040.5  461.07  5051.6  460.89  5122.4  462.10  5144.9  462.75  5183.7  465.35
  5194.2  465.15  5238.3  465.90  5282.4  468.88  5331.6  468.84  5387.8  469.94
#Mann=3,-1,0
  4496.4    0.05       0  4869.6    0.04       0  4873.6    0.05       0
Bank Sta=4869.6,4873.6
Exp/Cntr=0.3,0.1

Type RM Length L Ch R = 1,1011,115,115,115
BEGIN DESCRIPTION:
Lacy 064 2385
END DESCRIPTION:
XS GIS Cut Line= 3
      2755934.57      6889067.34      2755525.80      6889039.63
      2755135.03      6889106.16
#Sta/Elev= 30
  4590.3  469.38  4618.9  468.93  4649.0  466.46  4669.0  466.53  4689.1  464.66
  4699.1  464.50  4709.1  463.59  4739.2  460.10  4761.1  459.96  4839.4  457.76
  4879.5  457.68  4937.7  456.36  4937.9  455.86  4941.4  455.86  4941.7  456.36
  4969.7  457.92  5020.1  458.71  5050.5  458.57  5081.0  460.05  5091.1  461.19
  5121.5  461.56  5162.2  463.08  5192.5  465.06  5217.3  465.37  5253.4  467.00
  5272.4  468.48  5314.3  468.76  5332.7  469.61  5344.7  469.16  5396.4  470.28
#Mann=3,-1,0
  4590.3    0.05       0  4937.7    0.04       0  4941.7    0.05       0
Bank Sta=4937.7,4941.7
Exp/Cntr=0.3,0.1

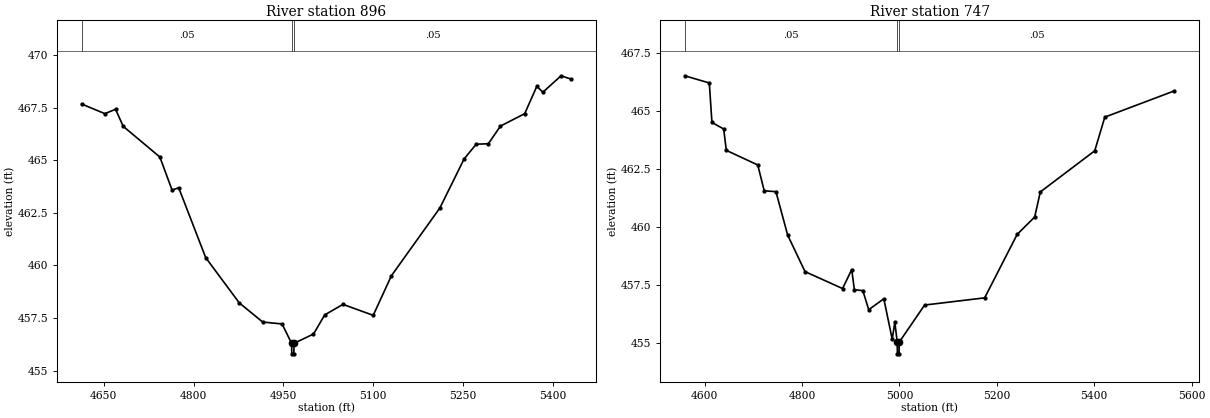
Type RM Length L Ch R = 1,896,149,149,149
BEGIN DESCRIPTION:
Lacy 064 2384
END DESCRIPTION:
XS GIS Cut Line= 3
      2755954.07      6889018.03      2755574.56      6888939.52
      2755149.29      6889006.79
#Sta/Elev= 30
  4612.9  467.67  4651.8  467.21  4669.7  467.42  4682.4  466.61  4743.7  465.15
  4764.1  463.58  4775.2  463.69  4820.3  460.37  4876.4  458.22  4915.6  457.31
  4947.9  457.22  4963.8  456.30  4964.1  455.80  4967.6  455.80  4967.8  456.30
  5000.4  456.74  5019.2  457.65  5049.6  458.15  5100.2  457.63  5130.6  459.51
  5211.6  462.73  5252.1  465.06  5272.3  465.76  5292.6  465.78  5312.8  466.62
  5353.3  467.21  5373.6  468.51  5383.7  468.23  5414.1  469.01  5431.0  468.85
#Mann=3,-1,0
  4612.9    0.05       0  4963.8    0.04       0  4967.8    0.05       0
Bank Sta=4963.8,4967.8
Exp/Cntr=0.3,0.1

Type RM Length L Ch R = 1,747,0,0,0
BEGIN DESCRIPTION:
Lacy 064 2383
END DESCRIPTION:
XS GIS Cut Line= 3
      2755984.95      6888956.01      2755576.37      6888790.85
      2755026.77      6888919.71
#Sta/Elev= 30
  4559.3  466.52  4609.7  466.21  4615.1  464.51  4639.2  464.23  4644.6  463.31
  4709.2  462.68  4722.4  461.57  4746.5  461.53  4770.6  459.66  4806.2  458.09
  4883.3  457.36  4902.1  458.18  4907.5  457.31  4924.9  457.27  4937.0  456.45
  4968.0  456.92  4985.2  455.18  4990.6  455.91  4995.5  455.05  4995.8  454.55
  4999.3  454.55  4999.5  455.05  5051.7  456.65  5175.0  456.96  5241.7  459.69
  5277.7  460.44  5289.3  461.52  5401.0  463.29  5421.7  464.74  5564.5  465.87
#Mann=3,-1,0
  4559.3    0.05       0  4995.5    0.04       0  4999.5    0.05       0
Bank Sta=4995.5,4999.5
Exp/Cntr=0.3,0.1

Chan Stop Cuts=-1