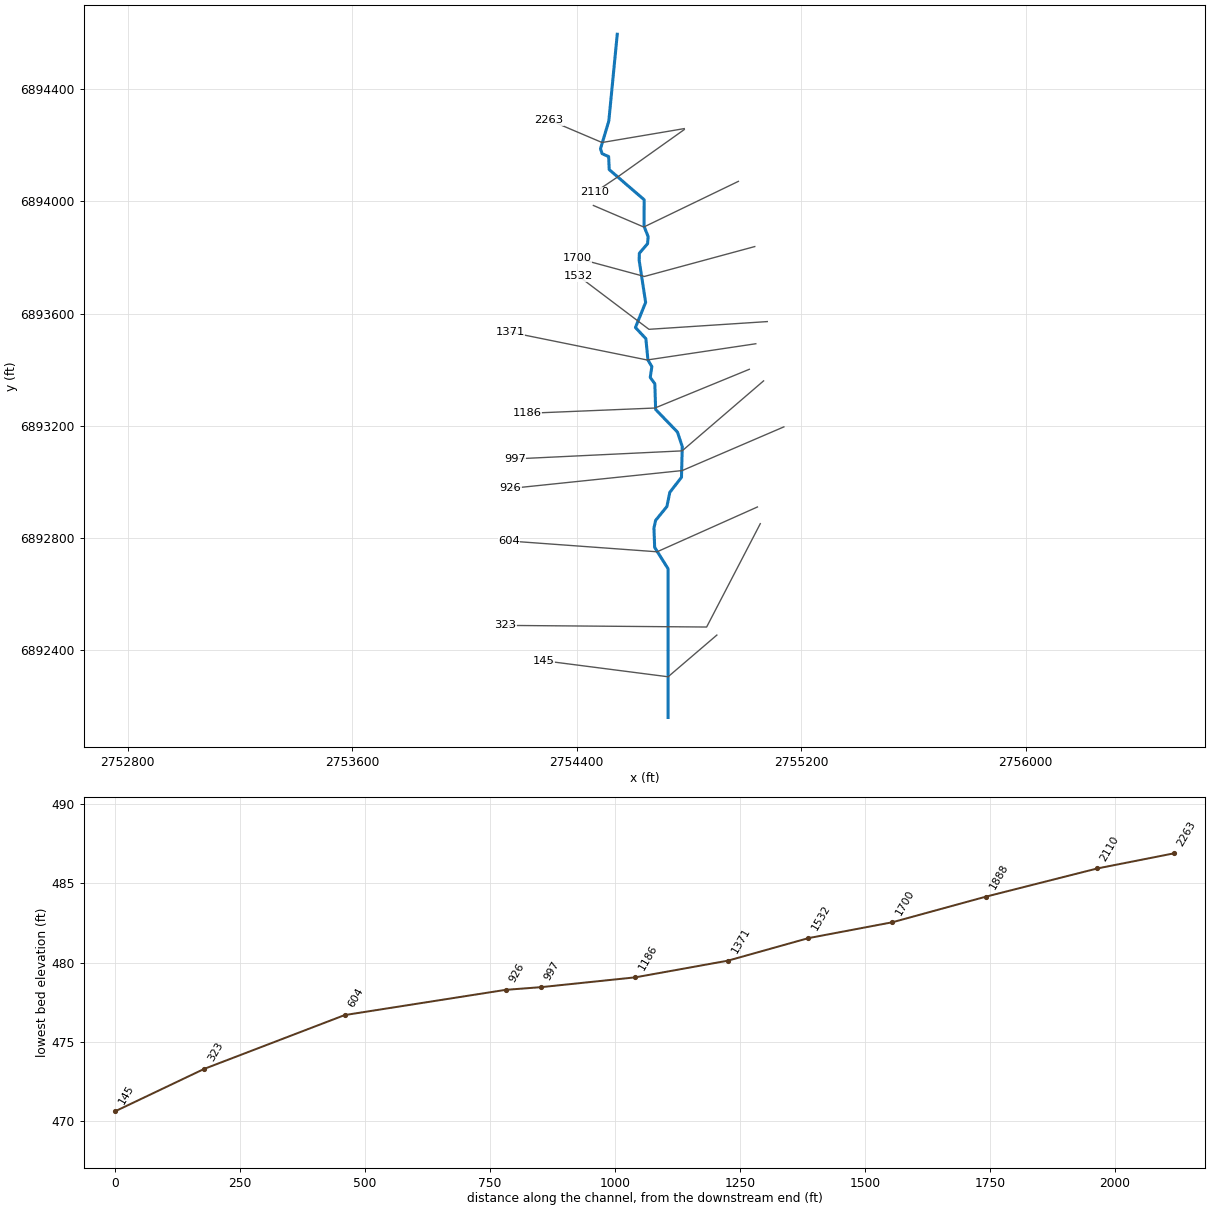
--- Lacy 065.prj (project) ---

Proj Title=Lacy 065 Base Level Engineering
Current Plan=p01
Default Exp/Contr=0.3,0.1
English Units
Geom File=g01
Flow File=f01
Plan File=p01
BEGIN DESCRIPTION:
Lacy 065
END DESCRIPTION:

--- Lacy 065.p01 (plan) ---

Plan Title=Multiple Run
Short Identifier=Multiple
Geom File=g01
Flow File=f01
Subcritical Flow
K Sum by GR= 0
Std Step Tol= 0.01
Critical Tol= 0.01
Num of Std Step Trials= 20
Max Error Tol= 0.3
Flow Tol Ratio= 0.001
Split Flow NTrial= 30
Split Flow Tol= 0.02
Split Flow Ratio= 0.02
Log Output Level= 0
Friction Slope Method= 1
Unsteady Friction Slope Method= 2
Unsteady Bridges Friction Slope Method= 1
Parabolic Critical Depth
Global Vel Dist=  1 , 1 , 1
Global Log Level= 0
CheckData=True
Encroach Param= -1, 0, 0, 0
BEGIN DESCRIPTION:
Multiple Run
END DESCRIPTION:

--- Lacy 065.f01 (steady flow) ---

Flow Title=Multiple
Number of Profiles=7
Profile Names=10-year,25-year,50-year,1pct_min,100-year,1pct_plu,500-year
River Rch & RM= Lacy 065,Reach-1,2263
     248     316     369     215     430     857     581
Boundary for River Rch & Prof#=Lacy 065,Reach-1,1
Up Type=0
Dn Type=3
Dn Slope=0.005
Boundary for River Rch & Prof#=Lacy 065,Reach-1,2
Up Type=0
Dn Type=3
Dn Slope=0.005
Boundary for River Rch & Prof#=Lacy 065,Reach-1,3
Up Type=0
Dn Type=3
Dn Slope=0.005
Boundary for River Rch & Prof#=Lacy 065,Reach-1,4
Up Type=0
Dn Type=3
Dn Slope=0.005
Boundary for River Rch & Prof#=Lacy 065,Reach-1,5
Up Type=0
Dn Type=3
Dn Slope=0.005
Boundary for River Rch & Prof#=Lacy 065,Reach-1,6
Up Type=0
Dn Type=3
Dn Slope=0.005
Boundary for River Rch & Prof#=Lacy 065,Reach-1,7
Up Type=0
Dn Type=3
Dn Slope=0.005

--- Lacy 065.g01 (geometry) ---

Geom Title=Existing Conditions

River Reach=Lacy 065,Reach-1
Reach XY= 30
      2754544.84      6894595.67      2754514.77      6894286.46
      2754485.09      6894187.25      2754491.01      6894170.07
      2754514.18      6894159.81      2754516.22      6894113.32
      2754640.75      6894005.94      2754640.29      6893911.76
      2754654.95      6893874.24      2754652.81      6893849.29
      2754623.39      6893815.02      2754623.10      6893789.04
      2754645.97      6893640.22      2754609.65      6893550.59
      2754646.79      6893510.89      2754654.26      6893434.48
      2754668.11      6893411.29      2754662.41      6893372.56
      2754678.79      6893350.04      2754681.56      6893258.65
      2754759.54      6893177.75      2754776.53      6893126.19
      2754773.77      6893016.93      2754732.12      6892963.18
      2754721.81      6892912.73      2754681.65      6892863.32
      2754675.59      6892836.00      2754678.17      6892766.98
      2754725.93      6892690.97      2754726.00      6892161.00

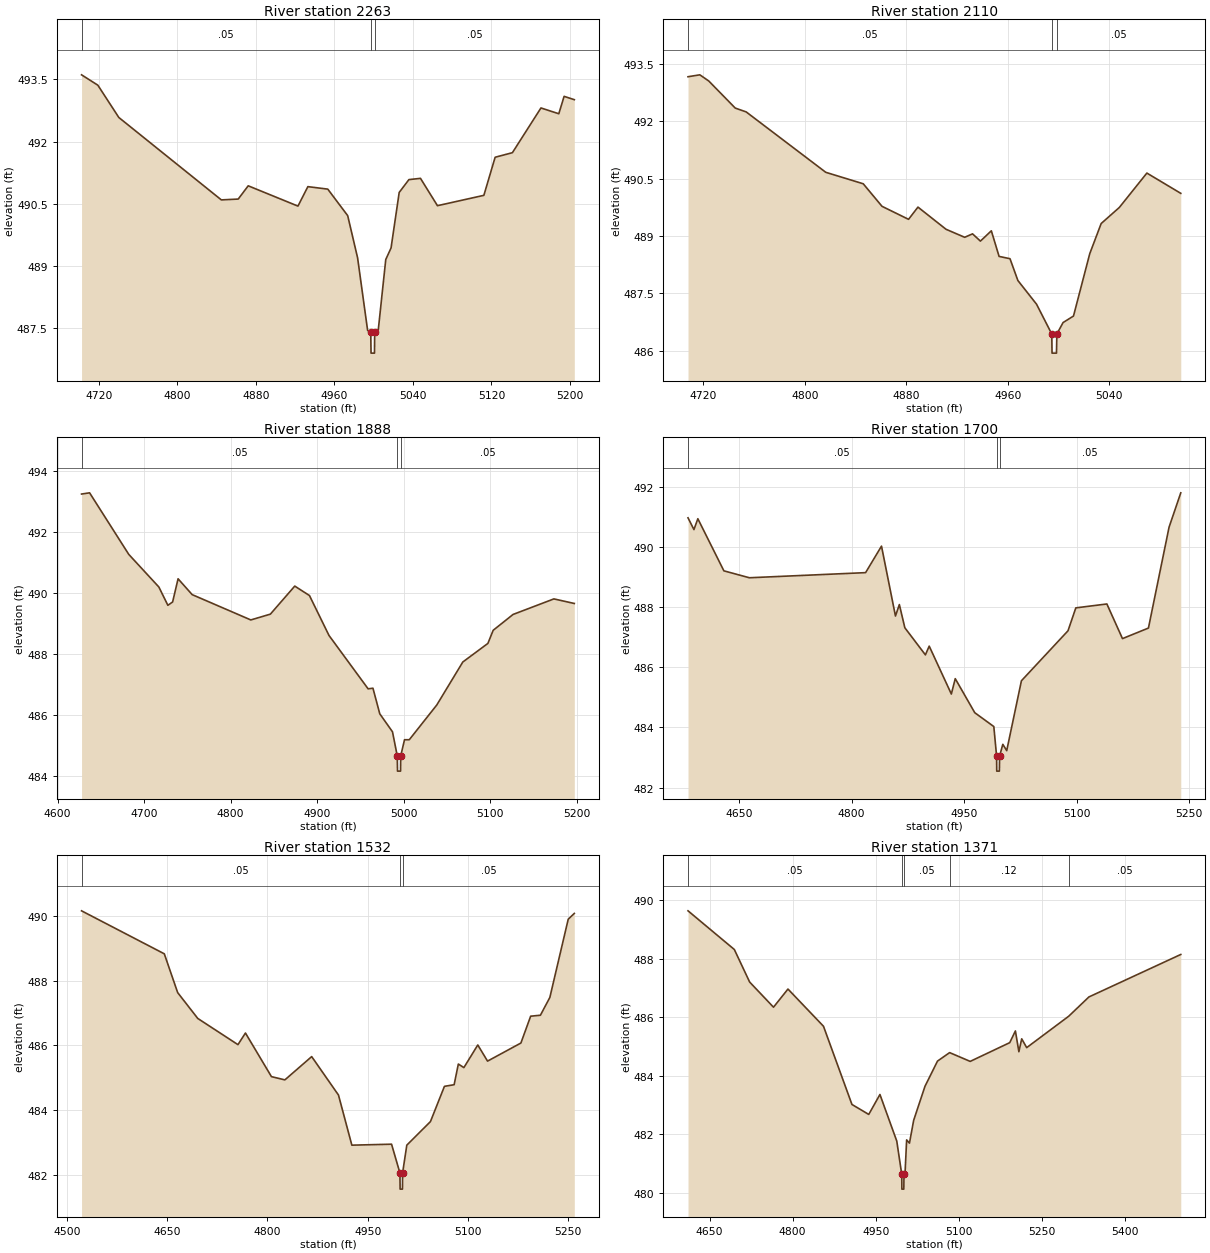
Type RM Length L Ch R = 1,2263,153,153,153
BEGIN DESCRIPTION:
Lacy 065 3457
END DESCRIPTION:
XS GIS Cut Line= 3
      2754783.48      6894259.42      2754490.64      6894209.88
      2754301.69      6894290.15
#Sta/Elev= 30
  4702.2  493.61  4718.8  493.36  4740.2  492.58  4844.7  490.59  4861.9  490.61
  4872.1  490.93  4922.8  490.44  4932.9  490.91  4953.2  490.85  4973.5  490.21
  4983.6  489.19  4993.8  487.44  4997.0  487.39  4997.3  486.89  5000.8  486.89
  5001.0  487.39  5004.4  487.39  5012.3  489.15  5017.7  489.43  5026.0  490.77
  5035.9  491.08  5047.7  491.11  5065.0  490.45  5112.3  490.70  5123.8  491.62
  5141.4  491.73  5170.5  492.81  5188.7  492.67  5194.1  493.09  5204.5  493.01
#Mann=3,-1,0
  4702.2    0.05       0  4997.0    0.04       0  5001.0    0.05       0
Bank Sta=4997,5001
Exp/Cntr=0.3,0.1

Type RM Length L Ch R = 1,2110,222,222,222
BEGIN DESCRIPTION:
Lacy 065 3456
END DESCRIPTION:
XS GIS Cut Line= 3
      2754783.57      6894255.94      2754546.01      6894086.98
      2754465.88      6894033.06
#Sta/Elev= 30
  4708.1  493.17  4717.4  493.22  4724.4  493.06  4745.3  492.35  4753.9  492.25
  4816.6  490.67  4846.1  490.37  4860.9  489.78  4881.8  489.44  4889.2  489.76
  4911.3  489.18  4926.0  488.97  4932.2  489.06  4938.4  488.87  4947.0  489.14
  4953.1  488.47  4961.7  488.41  4967.9  487.84  4982.6  487.22  4994.6  486.44
  4994.8  485.94  4998.3  485.94  4998.6  486.44  5003.5  486.74  5011.7  486.91
  5024.5  488.54  5033.5  489.33  5047.8  489.75  5069.5  490.65  5096.2  490.12
#Mann=3,-1,0
  4708.1    0.05       0  4994.6    0.04       0  4998.6    0.05       0
Bank Sta=4994.6,4998.6
Exp/Cntr=0.3,0.1

Type RM Length L Ch R = 1,1888,188,188,188
BEGIN DESCRIPTION:
Lacy 065 3455
END DESCRIPTION:
XS GIS Cut Line= 3
      2754976.51      6894071.47      2754639.45      6893908.71
      2754459.77      6893985.50
#Sta/Elev= 30
  4627.6  493.26  4636.9  493.30  4682.2  491.28  4717.0  490.21  4727.4  489.61
  4732.9  489.72  4739.2  490.48  4755.5  489.96  4823.3  489.13  4845.9  489.32
  4874.1  490.24  4891.1  489.93  4913.7  488.62  4958.9  486.87  4964.5  486.89
  4972.4  486.05  4987.1  485.46  4992.6  484.67  4992.9  484.17  4996.4  484.17
  4996.6  484.67  5001.0  485.20  5006.5  485.20  5038.3  486.34  5068.4  487.75
  5097.4  488.36  5103.5  488.79  5126.5  489.31  5173.7  489.82  5197.3  489.67
#Mann=3,-1,0
  4627.6    0.05       0  4992.6    0.04       0  4996.6    0.05       0
Bank Sta=4992.6,4996.6
Exp/Cntr=0.3,0.1

Type RM Length L Ch R = 1,1700,168,168,168
BEGIN DESCRIPTION:
Lacy 065 3454
END DESCRIPTION:
XS GIS Cut Line= 3
      2755034.92      6893839.09      2754641.53      6893732.55
      2754400.96      6893797.69
#Sta/Elev= 30
  4581.9  490.96  4589.8  490.57  4595.0  490.93  4629.7  489.20  4663.7  488.97
  4818.6  489.14  4839.8  490.02  4858.4  487.70  4863.6  488.08  4870.9  487.31
  4898.3  486.41  4903.4  486.70  4932.9  485.11  4938.1  485.62  4964.1  484.49
  4989.5  484.03  4993.2  483.05  4993.4  482.55  4996.9  482.55  4997.2  483.05
  5001.5  483.44  5006.7  483.23  5026.3  485.55  5088.4  487.21  5098.8  487.97
  5140.2  488.10  5161.0  486.95  5195.6  487.30  5223.1  490.65  5238.7  491.79
#Mann=3,-1,0
  4581.9    0.05       0  4993.2    0.04       0  4997.2    0.05       0
Bank Sta=4993.2,4997.2
Exp/Cntr=0.3,0.1

Type RM Length L Ch R = 1,1532,161,161,161
BEGIN DESCRIPTION:
Lacy 065 3453
END DESCRIPTION:
XS GIS Cut Line= 3
      2755079.54      6893571.74      2754657.84      6893544.18
      2754406.80      6893733.79
#Sta/Elev= 30
  4521.9  490.16  4645.7  488.83  4665.7  487.63  4695.8  486.83  4755.9  486.02
  4767.1  486.38  4806.0  485.03  4826.1  484.93  4866.2  485.65  4906.3  484.46
  4926.3  482.91  4985.7  482.94  4998.2  482.05  4998.5  481.55  5002.0  481.55
  5002.2  482.05  5008.5  482.91  5043.9  483.64  5064.8  484.73  5079.3  484.78
  5085.6  485.42  5093.9  485.31  5114.7  486.01  5129.3  485.51  5179.2  486.07
  5193.8  486.90  5208.4  486.93  5222.5  487.48  5250.0  489.90  5259.1  490.08
#Mann=3,-1,0
  4521.9    0.05       0  4998.2    0.04       0  5002.2    0.05       0
Bank Sta=4998.2,5002.2
Exp/Cntr=0.3,0.1

Type RM Length L Ch R = 1,1371,185,185,185
BEGIN DESCRIPTION:
Lacy 065 2409
END DESCRIPTION:
XS GIS Cut Line= 3
      2755038.64      6893492.79      2754651.38      6893434.89
      2754163.48      6893533.87
#Sta/Elev= 30
  4611.2  489.63  4694.8  488.31  4722.4  487.20  4765.5  486.34  4791.6  486.96
  4855.7  485.69  4907.1  483.02  4937.4  482.68  4957.6  483.36  4988.0  481.77
  4997.0  480.63  4997.2  480.13  5000.7  480.13  5001.0  480.63  5002.8  480.63
  5005.8  481.81  5010.9  481.70  5018.5  482.48  5038.9  483.64  5061.5  484.50
  5083.4  484.79  5120.5  484.49  5191.9  485.13  5202.1  485.53  5208.4  484.82
  5213.5  485.26  5222.5  484.96  5298.2  486.03  5334.8  486.69  5500.6  488.14
#Mann=5,-1,0
  4611.2    0.05       0  4997.0    0.04       0  5001.0    0.05       0
  5083.4    0.12       0  5298.2    0.05       0
Bank Sta=4997,5001
Exp/Cntr=0.3,0.1

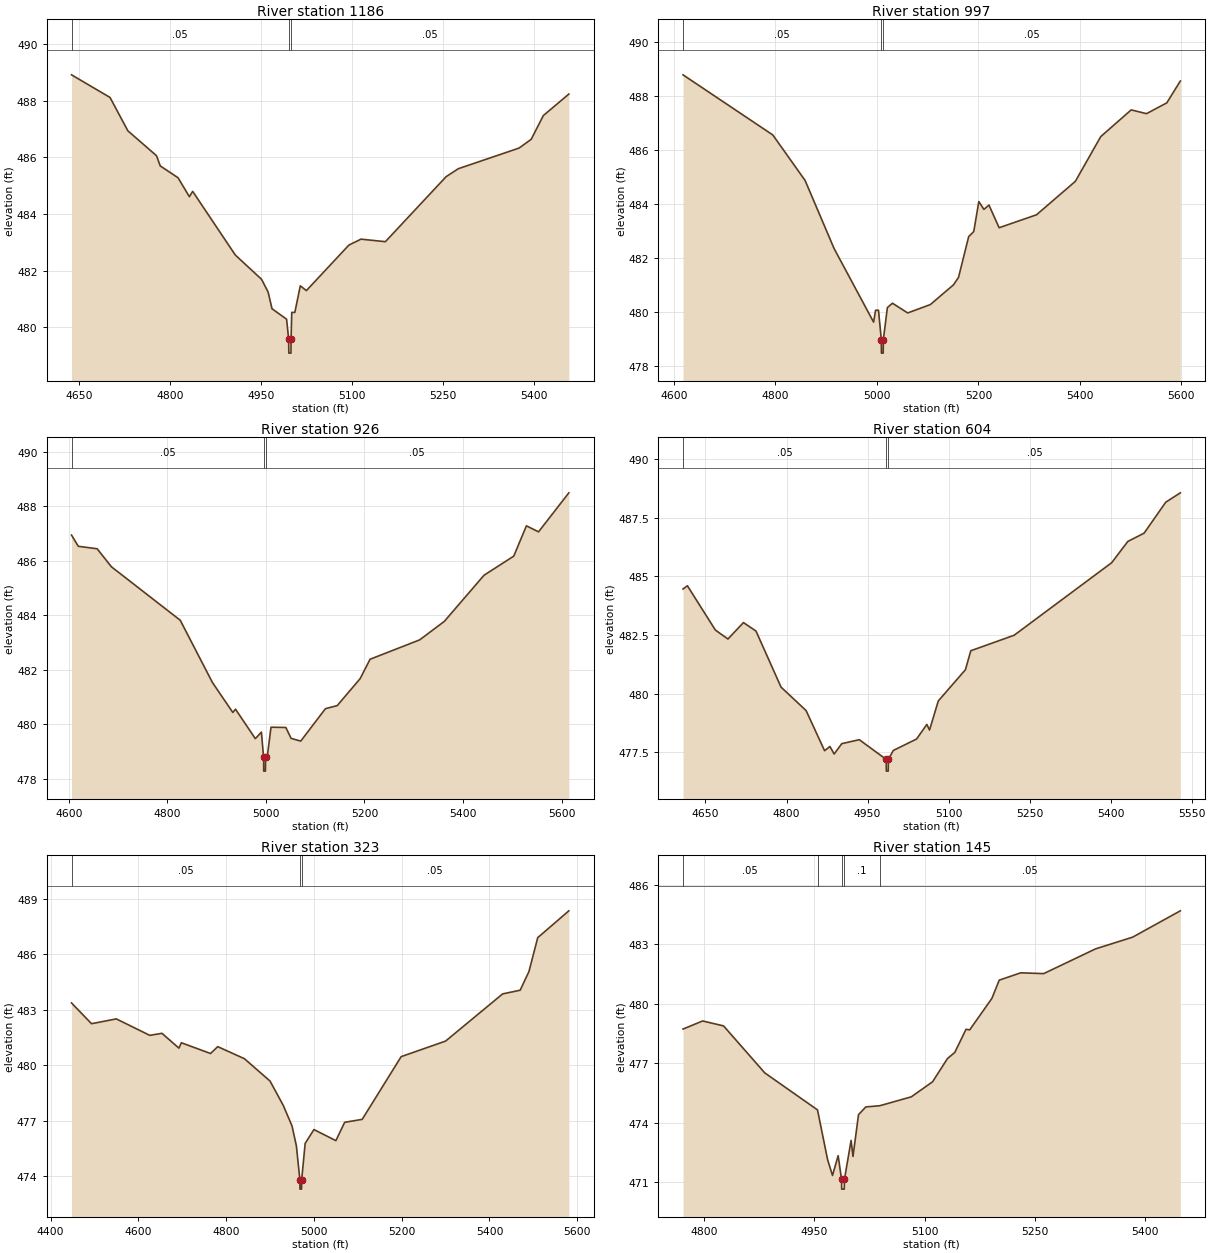
Type RM Length L Ch R = 1,1186,189,189,189
BEGIN DESCRIPTION:
Lacy 065 3459
END DESCRIPTION:
XS GIS Cut Line= 3
      2755015.54      6893401.73      2754679.01      6893263.68
      2754224.04      6893244.83
#Sta/Elev= 30
  4637.6  488.92  4701.0  488.12  4730.4  486.94  4777.6  486.06  4783.7  485.70
  4813.1  485.28  4831.7  484.61  4837.1  484.80  4907.3  482.55  4950.6  481.69
  4961.4  481.24  4967.8  480.65  4991.8  480.28  4995.2  479.58  4995.5  479.08
  4999.0  479.08  4999.2  479.58  5000.3  480.52  5005.4  480.52  5014.4  481.46
  5024.4  481.29  5094.4  482.90  5114.4  483.11  5154.5  483.02  5254.6  485.32
  5274.6  485.60  5374.7  486.33  5394.7  486.64  5414.7  487.48  5456.7  488.24
#Mann=3,-1,0
  4637.6    0.05       0  4995.2    0.04       0  4999.2    0.05       0
Bank Sta=4995.2,4999.2
Exp/Cntr=0.3,0.1

Type RM Length L Ch R = 1,997,71,71,71
BEGIN DESCRIPTION:
Lacy 065 67
END DESCRIPTION:
XS GIS Cut Line= 3
      2755066.31      6893360.46      2754776.00      6893111.00
      2754179.36      6893082.33
#Sta/Elev= 30
  4617.9  488.78  4794.9  486.55  4858.6  484.86  4915.6  482.34  4993.5  479.61
  4997.4  480.05  5003.2  480.05  5008.7  478.96  5008.9  478.46  5012.4  478.46
  5012.7  478.96  5020.7  480.15  5030.7  480.31  5060.7  479.95  5105.3  480.26
  5150.8  480.99  5160.9  481.27  5180.9  482.78  5190.9  482.97  5200.9  484.08
  5210.9  483.79  5220.9  483.95  5240.9  483.11  5314.6  483.59  5391.1  484.83
  5441.2  486.49  5501.2  487.48  5531.3  487.34  5571.3  487.74  5598.0  488.55
#Mann=3,-1,0
  4617.9    0.05       0  5008.7    0.04       0  5012.7    0.05       0
Bank Sta=5008.7,5012.7
Exp/Cntr=0.3,0.1

Type RM Length L Ch R = 1,926,322,322,322
BEGIN DESCRIPTION:
Lacy 065 2407
END DESCRIPTION:
XS GIS Cut Line= 3
      2755138.66      6893196.54      2754776.40      6893040.86
      2754164.81      6892977.15
#Sta/Elev= 30
  4605.7  486.94  4619.5  486.53  4657.7  486.44  4686.6  485.78  4826.3  483.82
  4891.6  481.54  4933.0  480.44  4938.5  480.56  4978.7  479.48  4991.0  479.72
  4995.5  478.79  4995.7  478.29  4999.2  478.29  4999.5  478.79  5002.7  478.79
  5010.5  479.90  5040.6  479.89  5051.3  479.49  5070.8  479.39  5121.0  480.58
  5144.8  480.69  5191.4  481.68  5211.5  482.39  5312.1  483.10  5362.3  483.78
  5442.8  485.47  5503.1  486.17  5528.8  487.28  5553.4  487.06  5614.9  488.49
#Mann=3,-1,0
  4605.7    0.05       0  4995.5    0.04       0  4999.5    0.05       0
Bank Sta=4995.5,4999.5
Exp/Cntr=0.3,0.1

Type RM Length L Ch R = 1,604,281,281,281
BEGIN DESCRIPTION:
Lacy 065 2405
END DESCRIPTION:
XS GIS Cut Line= 3
      2755044.36      6892911.09      2754686.81      6892751.37
      2754159.12      6892789.88
#Sta/Elev= 30
  4608.4  484.46  4616.5  484.60  4668.4  482.71  4691.6  482.33  4720.3  483.03
  4743.5  482.67  4789.9  480.28  4836.3  479.28  4870.5  477.57  4880.4  477.75
  4888.2  477.43  4902.3  477.87  4934.7  478.04  4984.6  477.20  4984.8  476.70
  4988.3  476.70  4988.6  477.20  4997.7  477.58  5040.9  478.07  5059.8  478.69
  5064.8  478.45  5081.0  479.69  5131.2  481.02  5141.2  481.83  5221.4  482.49
  5401.9  485.58  5432.0  486.49  5462.0  486.84  5502.1  488.16  5529.1  488.56
#Mann=3,-1,0
  4608.4    0.05       0  4984.6    0.04       0  4988.6    0.05       0
Bank Sta=4984.6,4988.6
Exp/Cntr=0.3,0.1

Type RM Length L Ch R = 1,323,178,178,178
BEGIN DESCRIPTION:
Lacy 065 2406
END DESCRIPTION:
XS GIS Cut Line= 3
      2755054.60      6892851.57      2754863.35      6892483.26
      2754145.07      6892489.05
#Sta/Elev= 30
  4447.6  483.37  4493.2  482.25  4549.7  482.51  4625.9  481.62  4653.7  481.73
  4692.3  480.93  4697.9  481.22  4764.3  480.64  4780.8  481.01  4841.5  480.36
  4900.0  479.15  4930.0  477.84  4950.0  476.73  4960.0  475.65  4968.0  473.81
  4968.2  473.31  4971.7  473.31  4972.0  473.81  4980.0  475.78  5000.0  476.53
  5050.0  475.93  5070.0  476.92  5110.0  477.08  5198.8  480.47  5300.0  481.31
  5430.0  483.86  5470.0  484.06  5490.0  485.07  5510.0  486.90  5580.9  488.35
#Mann=3,-1,0
  4447.6    0.05       0  4968.0    0.04       0  4972.0    0.05       0
Bank Sta=4968,4972
Exp/Cntr=0.3,0.1

Type RM Length L Ch R = 1,145,0,0,0
BEGIN DESCRIPTION:
Lacy 065 3452
END DESCRIPTION:
XS GIS Cut Line= 3
      2754899.79      6892454.60      2754725.98      6892305.96
      2754281.66      6892363.30
#Sta/Elev= 30
  4771.3  478.72  4798.0  479.13  4826.5  478.88  4882.5  476.51  4954.3  474.64
  4968.1  472.12  4974.7  471.33  4982.4  472.33  4987.0  471.14  4987.2  470.64
  4990.7  470.64  4991.0  471.14  5000.0  473.10  5002.6  472.29  5010.1  474.40
  5020.1  474.79  5039.0  474.85  5082.0  475.30  5110.9  476.06  5131.1  477.23
  5141.1  477.54  5156.4  478.71  5161.4  478.68  5191.6  480.27  5201.6  481.19
  5230.8  481.56  5262.1  481.52  5332.7  482.77  5383.1  483.36  5448.0  484.69
#Mann=5,-1,0
  4771.3    0.05       0  4954.3     0.1       0  4987.0    0.07       0
  4991.0     0.1       0  5039.0    0.05       0
Bank Sta=4987,4991
Exp/Cntr=0.3,0.1

Chan Stop Cuts=-1