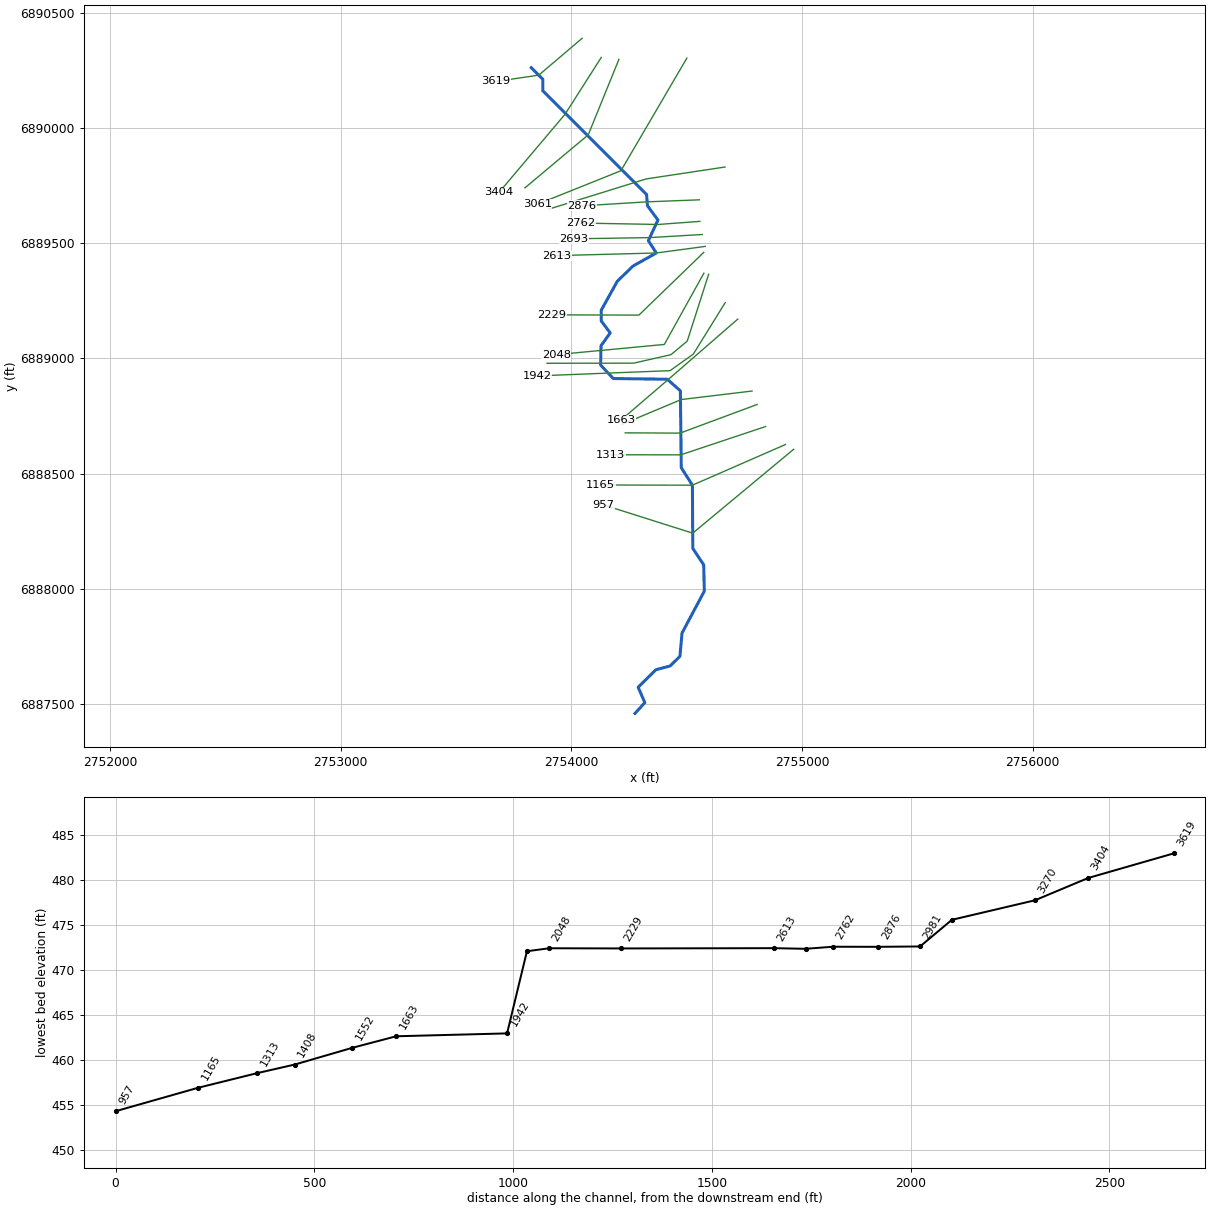
--- Lacy 066.prj (project) ---

Proj Title=Lacy 066 Base Level Engineering
Current Plan=p01
Default Exp/Contr=0.3,0.1
English Units
Geom File=g01
Flow File=f01
Plan File=p01
BEGIN DESCRIPTION:
Lacy 066
END DESCRIPTION:

--- Lacy 066.p01 (plan) ---

Plan Title=Multiple Run
Short Identifier=Multiple
Geom File=g01
Flow File=f01
Subcritical Flow
K Sum by GR= 0
Std Step Tol= 0.01
Critical Tol= 0.01
Num of Std Step Trials= 20
Max Error Tol= 0.3
Flow Tol Ratio= 0.001
Split Flow NTrial= 30
Split Flow Tol= 0.02
Split Flow Ratio= 0.02
Log Output Level= 0
Friction Slope Method= 1
Unsteady Friction Slope Method= 2
Unsteady Bridges Friction Slope Method= 1
Parabolic Critical Depth
Global Vel Dist=  1 , 1 , 1
Global Log Level= 0
CheckData=True
Encroach Param= -1, 0, 0, 0
BEGIN DESCRIPTION:
Multiple Run
END DESCRIPTION:

--- Lacy 066.f01 (steady flow) ---

Flow Title=Multiple
Number of Profiles=7
Profile Names=10-year,25-year,50-year,1pct_min,100-year,1pct_plu,500-year
River Rch & RM= Lacy 066,Reach-1,3619
     115     139     155      87     174     347     218
Boundary for River Rch & Prof#=Lacy 066,Reach-1,1
Up Type=0
Dn Type=3
Dn Slope=0.005
Boundary for River Rch & Prof#=Lacy 066,Reach-1,2
Up Type=0
Dn Type=3
Dn Slope=0.005
Boundary for River Rch & Prof#=Lacy 066,Reach-1,3
Up Type=0
Dn Type=3
Dn Slope=0.005
Boundary for River Rch & Prof#=Lacy 066,Reach-1,4
Up Type=0
Dn Type=3
Dn Slope=0.005
Boundary for River Rch & Prof#=Lacy 066,Reach-1,5
Up Type=0
Dn Type=3
Dn Slope=0.005
Boundary for River Rch & Prof#=Lacy 066,Reach-1,6
Up Type=0
Dn Type=3
Dn Slope=0.005
Boundary for River Rch & Prof#=Lacy 066,Reach-1,7
Up Type=0
Dn Type=3
Dn Slope=0.005

--- Lacy 066.g01 (geometry) ---

Geom Title=Existing Conditions

River Reach=Lacy 066,Reach-1
Reach XY= 30
      2753826.00      6890261.00      2753876.00      6890211.00
      2753876.00      6890161.00      2754326.00      6889711.00
      2754329.69      6889662.49      2754375.33      6889600.31
      2754333.84      6889510.90      2754368.11      6889457.42
      2754266.33      6889400.23      2754198.99      6889334.52
      2754129.37      6889209.27      2754129.60      6889162.64
      2754168.40      6889111.01      2754128.36      6889055.10
      2754126.87      6888971.31      2754181.64      6888912.97
      2754415.74      6888910.02      2754472.57      6888859.78
      2754476.52      6888526.22      2754524.78      6888450.50
      2754526.52      6888176.22      2754573.75      6888105.06
      2754576.40      6887990.86      2754479.83      6887809.41
      2754470.58      6887708.33      2754428.57      6887666.74
      2754366.29      6887650.21      2754289.58      6887574.36
      2754318.48      6887507.67      2754276.00      6887461.00

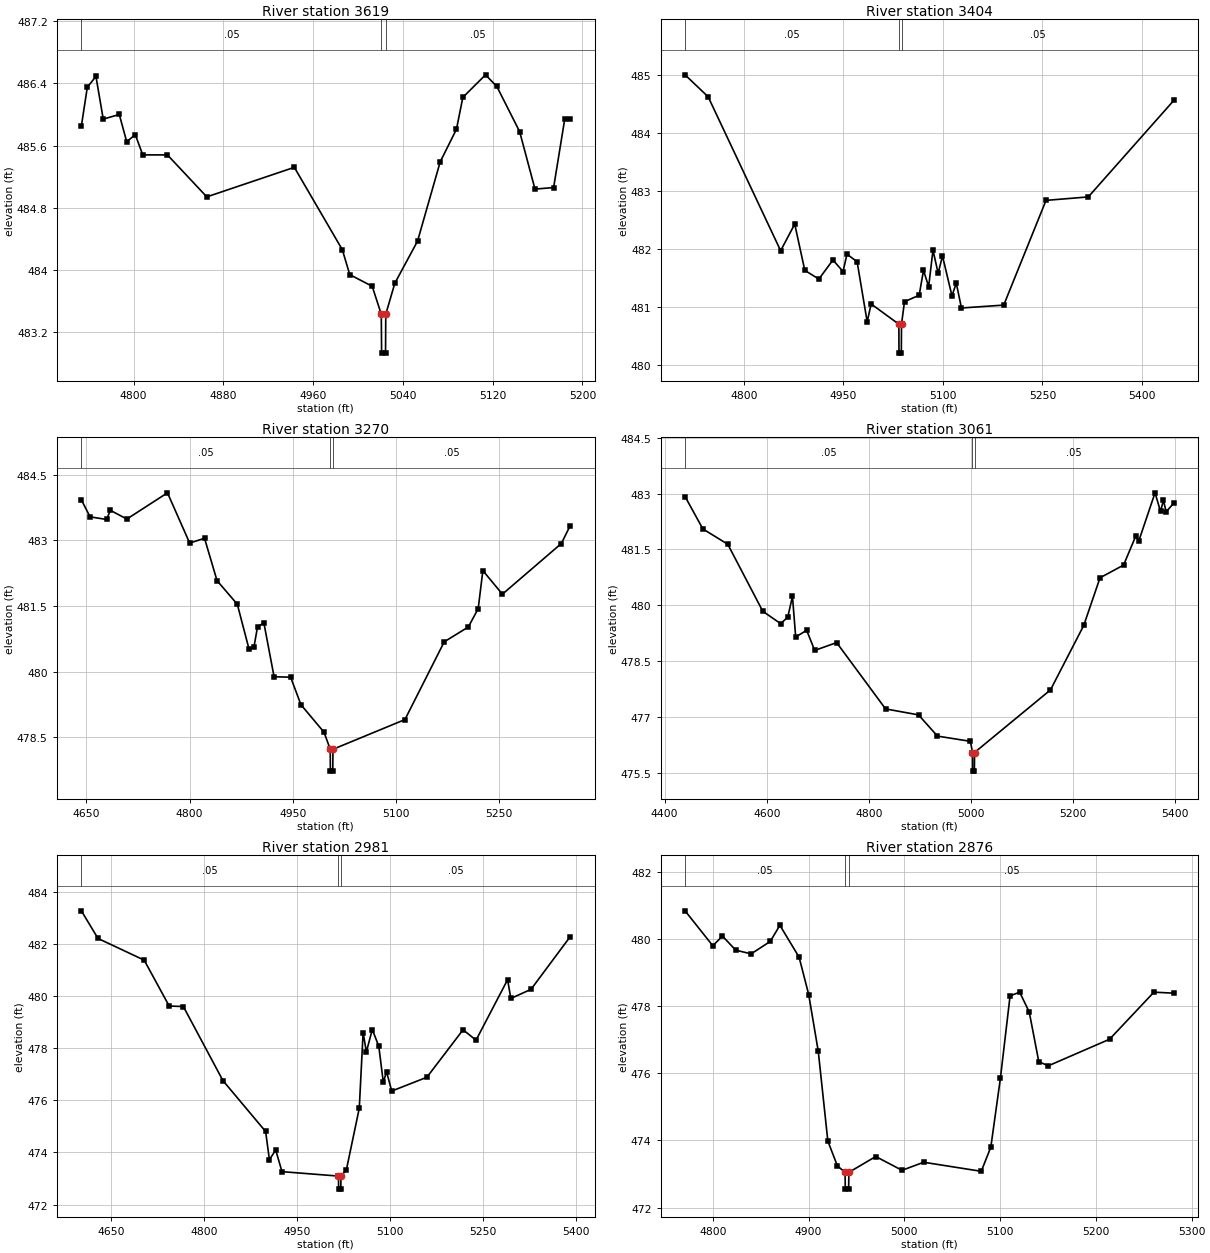
Type RM Length L Ch R = 1,3619,215,215,215
BEGIN DESCRIPTION:
Lacy 066 3450
END DESCRIPTION:
XS GIS Cut Line= 3
      2754046.32      6890388.28      2753858.45      6890228.55
      2753671.33      6890201.25
#Sta/Elev= 30
  4753.4  485.85  4758.7  486.35  4766.4  486.49  4772.9  485.94  4787.2  486.00
  4793.8  485.65  4801.5  485.74  4808.1  485.48  4830.1  485.48  4865.2  484.94
  4943.2  485.32  4986.0  484.26  4992.6  483.94  5012.6  483.79  5020.7  483.43
  5021.0  482.93  5024.5  482.93  5024.7  483.43  5032.8  483.83  5053.0  484.37
  5073.2  485.39  5087.7  485.81  5093.4  486.22  5113.6  486.51  5123.7  486.36
  5144.0  485.78  5157.7  485.04  5174.3  485.06  5184.2  485.94  5189.1  485.94
#Mann=3,-1,0
  4753.4    0.05       0  5020.7    0.04       0  5024.7    0.05       0
Bank Sta=5020.7,5024.7
Exp/Cntr=0.3,0.1

Type RM Length L Ch R = 1,3404,134,134,134
BEGIN DESCRIPTION:
Lacy 066 3433
END DESCRIPTION:
XS GIS Cut Line= 4
      2754129.58      6890305.60      2753972.72      6890059.30
      2753688.96      6889723.37      2753684.58      6889721.52
#Sta/Elev= 30
  4711.6  485.01  4746.4  484.63  4855.6  481.97  4876.8  482.43  4892.0  481.63
  4913.2  481.48  4934.4  481.81  4949.6  481.61  4955.5  481.91  4970.8  481.78
  4986.0  480.74  4991.9  481.05  5033.7  480.70  5033.9  480.20  5037.4  480.20
  5037.7  480.70  5042.2  481.09  5064.3  481.20  5070.8  481.63  5078.6  481.35
  5085.1  481.98  5092.9  481.58  5099.4  481.88  5113.7  481.19  5120.2  481.41
  5128.0  480.98  5191.7  481.03  5255.4  482.84  5319.1  482.90  5448.1  484.57
#Mann=3,-1,0
  4711.6    0.05       0  5033.7    0.04       0  5037.7    0.05       0
Bank Sta=5033.7,5037.7
Exp/Cntr=0.3,0.1

Type RM Length L Ch R = 1,3270,209,209,209
BEGIN DESCRIPTION:
Lacy 066 3430
END DESCRIPTION:
XS GIS Cut Line= 3
      2754206.05      6890297.05      2754073.17      6889969.95
      2753798.57      6889739.88
#Sta/Elev= 30
  4642.6  483.93  4655.3  483.54  4679.4  483.48  4684.7  483.69  4708.8  483.49
  4767.9  484.09  4800.2  482.94  4821.8  483.05  4840.0  482.08  4869.5  481.54
  4886.6  480.51  4893.6  480.55  4899.0  481.03  4908.2  481.11  4923.0  479.88
  4947.1  479.87  4962.1  479.24  4995.7  478.61  5004.7  478.22  5004.9  477.72
  5008.4  477.72  5008.7  478.22  5113.4  478.90  5170.6  480.68  5205.7  481.02
  5220.0  481.44  5226.8  482.31  5255.2  481.77  5341.0  482.93  5353.9  483.34
#Mann=3,-1,0
  4642.6    0.05       0  5004.7    0.04       0  5008.7    0.05       0
Bank Sta=5004.7,5008.7
Exp/Cntr=0.3,0.1

Type RM Length L Ch R = 1,3061,80,80,80
BEGIN DESCRIPTION:
Lacy 066 3431
END DESCRIPTION:
XS GIS Cut Line= 3
      2754500.75      6890302.45      2754214.84      6889814.07
      2753851.66      6889668.44
#Sta/Elev= 30
  4440.0  482.92  4474.9  482.05  4523.6  481.64  4592.2  479.84  4627.1  479.51
  4641.0  479.68  4650.3  480.24  4656.6  479.15  4678.1  479.33  4693.8  478.79
  4736.8  479.00  4832.6  477.22  4897.1  477.06  4934.2  476.49  4998.7  476.35
  5002.8  476.05  5003.0  475.55  5006.5  475.55  5006.8  476.05  5155.5  477.73
  5220.6  479.46  5252.5  480.74  5298.6  481.08  5322.8  481.87  5328.2  481.72
  5360.2  483.02  5371.0  482.52  5376.6  482.82  5382.0  482.51  5397.2  482.75
#Mann=3,-1,0
  4440.0    0.05       0  5002.8    0.04       0  5006.8    0.05       0
Bank Sta=5002.8,5006.8
Exp/Cntr=0.3,0.1

Type RM Length L Ch R = 1,2981,105,105,105
BEGIN DESCRIPTION:
Lacy 066 3432
END DESCRIPTION:
XS GIS Cut Line= 3
      2754666.24      6889830.22      2754324.25      6889778.62
      2753900.75      6889647.17
#Sta/Elev= 30
  4601.5  483.26  4628.4  482.20  4702.9  481.37  4743.3  479.61  4766.2  479.59
  4830.1  476.75  4899.0  474.80  4905.1  473.72  4915.3  474.09  4925.4  473.26
  5016.6  473.09  5016.9  472.59  5020.4  472.59  5020.6  473.09  5029.3  473.32
  5050.2  475.69  5056.4  478.59  5061.7  477.85  5071.2  478.71  5081.7  478.07
  5089.0  476.69  5094.3  477.09  5102.6  476.35  5159.4  476.88  5217.8  478.70
  5238.7  478.30  5289.7  480.62  5294.9  479.90  5327.5  480.25  5390.8  482.27
#Mann=3,-1,0
  4601.5    0.05       0  5016.6    0.04       0  5020.6    0.05       0
Bank Sta=5016.6,5020.6
Exp/Cntr=0.3,0.1

Type RM Length L Ch R = 1,2876,114,114,114
BEGIN DESCRIPTION:
Lacy 066 2382
END DESCRIPTION:
XS GIS Cut Line= 3
      2754554.97      6889687.99      2754326.14      6889679.19
      2754045.18      6889661.76
#Sta/Elev= 30
  4771.0  480.83  4800.0  479.79  4810.0  480.08  4823.9  479.66  4840.0  479.55
  4860.0  479.92  4870.0  480.40  4890.1  479.45  4900.1  478.34  4910.1  476.65
  4920.1  473.98  4930.1  473.24  4938.1  473.05  4938.3  472.55  4941.8  472.55
  4942.1  473.05  4970.1  473.52  4997.6  473.11  5020.2  473.35  5080.3  473.08
  5090.3  473.80  5100.3  475.85  5110.4  478.30  5120.4  478.41  5130.4  477.82
  5140.4  476.34  5150.4  476.22  5214.3  477.01  5260.6  478.41  5281.5  478.38
#Mann=3,-1,0
  4771.0    0.05       0  4938.1    0.04       0  4942.1    0.05       0
Bank Sta=4938.1,4942.1
Exp/Cntr=0.3,0.1

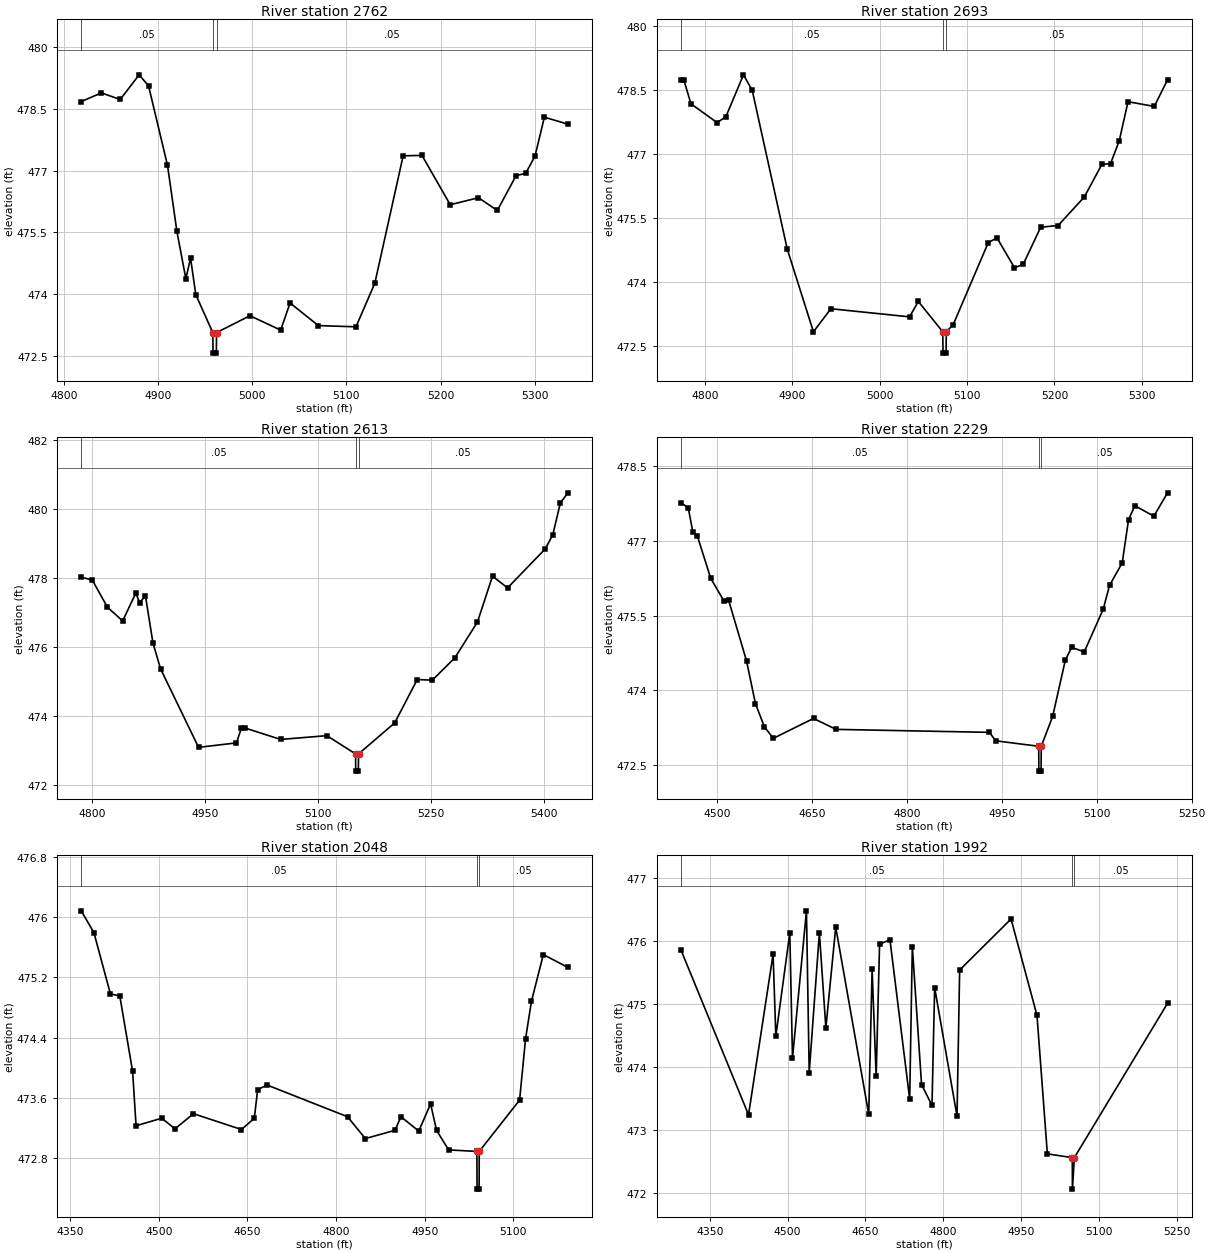
Type RM Length L Ch R = 1,2762,69,69,69
BEGIN DESCRIPTION:
Lacy 066 2381
END DESCRIPTION:
XS GIS Cut Line= 3
      2754557.33      6889594.53      2754376.23      6889581.12
      2754041.08      6889587.19
#Sta/Elev= 30
  4818.4  478.68  4839.8  478.89  4859.8  478.73  4879.9  479.33  4889.9  479.06
  4910.0  477.13  4920.0  475.52  4929.5  474.37  4934.5  474.87  4940.1  473.98
  4958.1  473.06  4958.4  472.56  4961.9  472.56  4962.1  473.06  4997.6  473.47
  5030.2  473.12  5040.2  473.78  5070.2  473.23  5110.2  473.20  5130.2  474.26
  5160.3  477.36  5180.3  477.37  5210.3  476.17  5240.3  476.34  5260.3  476.03
  5280.3  476.88  5290.3  476.93  5300.3  477.35  5310.3  478.30  5335.2  478.13
#Mann=3,-1,0
  4818.4    0.05       0  4958.1    0.04       0  4962.1    0.05       0
Bank Sta=4958.1,4962.1
Exp/Cntr=0.3,0.1

Type RM Length L Ch R = 1,2693,80,80,80
BEGIN DESCRIPTION:
Lacy 066 2380
END DESCRIPTION:
XS GIS Cut Line= 3
      2754567.44      6889537.63      2754340.14      6889524.18
      2754010.78      6889518.91
#Sta/Elev= 30
  4772.3  478.74  4775.5  478.74  4783.8  478.17  4813.8  477.73  4823.8  477.87
  4843.9  478.85  4853.9  478.49  4894.0  474.77  4924.0  472.83  4944.0  473.37
  5034.1  473.18  5044.1  473.54  5072.1  472.83  5072.4  472.33  5075.9  472.33
  5076.1  472.83  5084.1  473.00  5124.2  474.92  5134.2  475.03  5154.2  474.33
  5164.2  474.41  5184.2  475.28  5204.2  475.32  5234.2  475.99  5254.2  476.75
  5264.2  476.77  5274.2  477.31  5284.2  478.22  5314.2  478.11  5329.4  478.73
#Mann=3,-1,0
  4772.3    0.05       0  5072.1    0.04       0  5076.1    0.05       0
Bank Sta=5072.1,5076.1
Exp/Cntr=0.3,0.1

Type RM Length L Ch R = 1,2613,384,384,384
BEGIN DESCRIPTION:
Lacy 066 2379
END DESCRIPTION:
XS GIS Cut Line= 3
      2754580.50      6889485.99      2754368.11      6889457.42
      2753935.96      6889446.10
#Sta/Elev= 30
  4785.7  478.03  4800.3  477.95  4820.5  477.16  4840.7  476.76  4858.2  477.57
  4863.3  477.29  4871.0  477.49  4881.0  476.12  4891.1  475.37  4941.6  473.09
  4992.0  473.22  4998.5  473.65  5003.6  473.65  5050.6  473.32  5112.1  473.43
  5150.2  472.90  5150.4  472.40  5153.9  472.40  5154.2  472.90  5202.2  473.80
  5232.2  475.06  5252.2  475.04  5282.2  475.69  5312.2  476.73  5332.2  478.06
  5352.2  477.72  5402.2  478.85  5412.3  479.26  5422.3  480.18  5432.3  480.48
#Mann=3,-1,0
  4785.7    0.05       0  5150.2    0.04       0  5154.2    0.05       0
Bank Sta=5150.2,5154.2
Exp/Cntr=0.3,0.1

Type RM Length L Ch R = 1,2229,181,181,181
BEGIN DESCRIPTION:
Lacy 066 2378
END DESCRIPTION:
XS GIS Cut Line= 3
      2754573.74      6889459.83      2754292.84      6889188.06
      2753914.39      6889189.26
#Sta/Elev= 30
  4442.4  477.77  4454.0  477.67  4461.2  477.18  4468.2  477.11  4489.5  476.25
  4510.6  475.79  4517.8  475.81  4546.1  474.59  4560.2  473.73  4574.4  473.26
  4588.5  473.03  4652.1  473.43  4687.6  473.21  4930.1  473.15  4940.1  472.98
  5008.1  472.87  5008.3  472.37  5011.8  472.37  5012.1  472.87  5030.1  473.47
  5050.1  474.60  5060.1  474.86  5080.1  474.77  5110.1  475.63  5120.1  476.11
  5140.1  476.56  5150.1  477.43  5160.1  477.71  5190.1  477.50  5211.7  477.97
#Mann=3,-1,0
  4442.4    0.05       0  5008.1    0.04       0  5012.1    0.05       0
Bank Sta=5008.1,5012.1
Exp/Cntr=0.3,0.1

Type RM Length L Ch R = 1,2048,56,56,56
BEGIN DESCRIPTION:
Lacy 066 2377
END DESCRIPTION:
XS GIS Cut Line= 3
      2754574.49      6889369.83      2754403.02      6889060.85
      2753934.68      6889016.58
#Sta/Elev= 30
  4368.6  476.08  4390.1  475.79  4417.9  474.98  4433.9  474.95  4455.6  473.95
  4461.4  473.23  4504.8  473.33  4527.4  473.19  4558.6  473.39  4639.9  473.18
  4661.6  473.33  4667.3  473.71  4683.3  473.77  4819.4  473.35  4849.6  473.06
  4899.8  473.17  4909.8  473.35  4940.0  473.16  4960.1  473.52  4970.1  473.17
  4990.6  472.91  5038.4  472.89  5038.7  472.39  5042.2  472.39  5042.4  472.89
  5110.7  473.57  5120.8  474.38  5130.8  474.88  5150.9  475.50  5192.4  475.33
#Mann=3,-1,0
  4368.6    0.05       0  5038.4    0.04       0  5042.4    0.05       0
Bank Sta=5038.4,5042.4
Exp/Cntr=0.3,0.1

Type RM Length L Ch R = 1,1992,50,50,50
BEGIN DESCRIPTION:
Lacy 066 2375
END DESCRIPTION:
XS GIS Cut Line= 5
      2754595.14      6889365.14      2754502.41      6889075.39
      2754431.96      6889016.53      2754270.03      6888979.69
      2753894.54      6888979.23
#Sta/Elev= 30
  4294.5  475.86  4424.8  473.24  4472.1  475.79  4477.4  474.49  4504.3  476.13
  4509.5  474.14  4536.4  476.48  4541.7  473.91  4561.3  476.13  4573.8  474.62
  4592.8  476.22  4656.4  473.25  4662.9  475.55  4670.7  473.85  4677.3  475.95
  4697.3  476.02  4735.3  473.49  4740.4  475.91  4758.2  473.72  4778.3  473.39
  4783.4  475.26  4826.5  473.22  4831.6  475.54  4930.6  476.35  4980.6  474.82
  5000.6  472.62  5048.6  472.56  5048.9  472.06  5052.6  472.56  5232.1  475.01
#Mann=3,-1,0
  4294.5    0.05       0  5048.6    0.04       0  5052.6    0.05       0
Bank Sta=5048.6,5052.6
Exp/Cntr=0.3,0.1

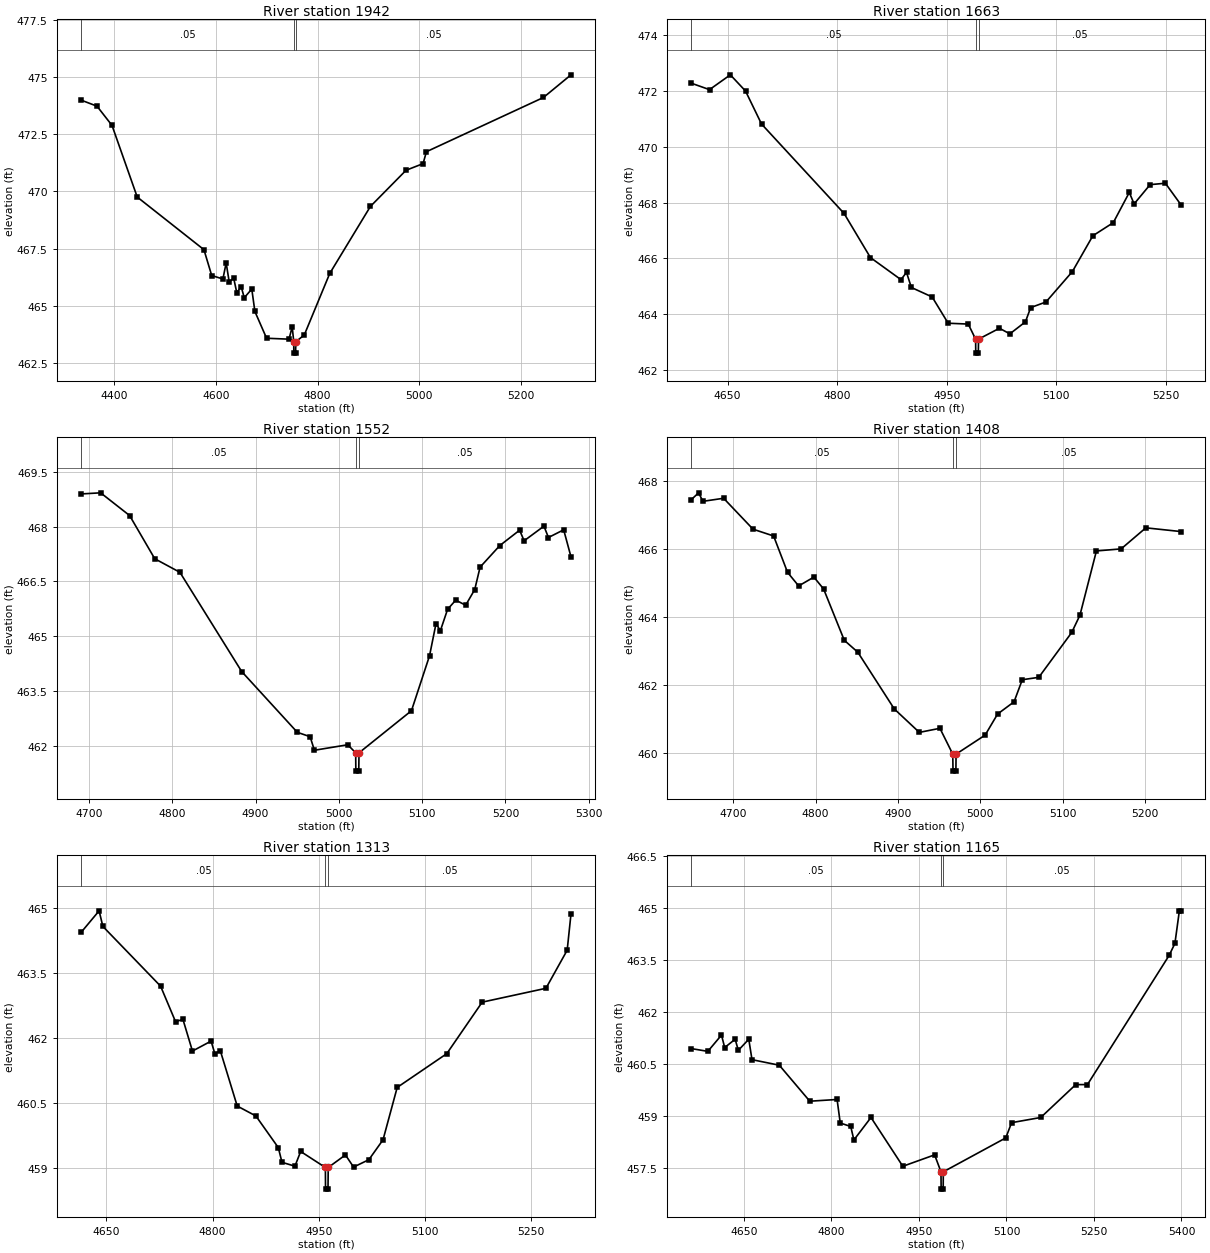
Type RM Length L Ch R = 1,1942,279,279,279
BEGIN DESCRIPTION:
Lacy 066 2376
END DESCRIPTION:
XS GIS Cut Line= 4
      2754667.06      6889242.18      2754528.72      6889018.88
      2754427.78      6888947.15      2753851.84      6888924.51
#Sta/Elev= 30
  4335.3  473.98  4366.0  473.72  4395.5  472.88  4445.1  469.75  4576.3  467.45
  4591.6  466.32  4613.6  466.17  4620.0  466.87  4626.1  466.03  4634.7  466.22
  4640.9  465.57  4649.5  465.84  4655.6  465.35  4670.4  465.73  4676.5  464.75
  4699.5  463.58  4743.6  463.54  4749.9  464.08  4752.9  463.43  4753.1  462.93
  4756.6  462.93  4756.9  463.43  4773.6  463.72  4823.7  466.41  4903.7  469.34
  4973.8  470.92  5007.3  471.21  5013.8  471.73  5244.0  474.10  5298.2  475.09
#Mann=3,-1,0
  4335.3    0.05       0  4752.9    0.04       0  4756.9    0.05       0
Bank Sta=4752.9,4756.9
Exp/Cntr=0.3,0.1

Type RM Length L Ch R = 1,1663,111,111,111
BEGIN DESCRIPTION:
Lacy 066 2374
END DESCRIPTION:
XS GIS Cut Line= 3
      2754721.59      6889170.75      2754424.22      6888912.43
      2754214.45      6888732.45
#Sta/Elev= 30
  4600.3  472.27  4625.2  472.04  4653.7  472.57  4674.5  471.99  4696.4  470.81
  4809.4  467.61  4845.5  466.03  4887.3  465.24  4894.9  465.50  4901.5  464.96
  4930.0  464.62  4951.9  463.68  4979.4  463.65  4989.5  463.11  4989.7  462.61
  4993.2  462.61  4993.5  463.11  5022.1  463.50  5036.4  463.30  5057.7  463.73
  5064.9  464.24  5085.8  464.44  5122.0  465.53  5150.0  466.81  5178.0  467.28
  5199.9  468.36  5206.5  467.95  5228.4  468.64  5249.3  468.69  5270.6  467.92
#Mann=3,-1,0
  4600.3    0.05       0  4989.5    0.04       0  4993.5    0.05       0
Bank Sta=4989.5,4993.5
Exp/Cntr=0.3,0.1

Type RM Length L Ch R = 1,1552,144,144,144
BEGIN DESCRIPTION:
Lacy 066 2373
END DESCRIPTION:
XS GIS Cut Line= 3
      2754783.46      6888858.81      2754476.30      6888821.91
      2754219.37      6888714.11
#Sta/Elev= 30
  4690.8  468.89  4713.9  468.92  4748.7  468.30  4778.9  467.12  4809.1  466.75
  4883.3  464.04  4950.1  462.38  4965.5  462.26  4970.6  461.89  5010.7  462.04
  5020.2  461.82  5020.4  461.32  5023.9  461.32  5024.2  461.82  5087.2  462.97
  5108.9  464.47  5116.6  465.34  5122.0  465.16  5130.6  465.74  5140.4  465.99
  5152.3  465.85  5163.2  466.28  5169.6  466.89  5193.3  467.48  5217.1  467.90
  5222.5  467.61  5246.3  468.01  5251.7  467.70  5270.0  467.91  5278.8  467.17
#Mann=3,-1,0
  4690.8    0.05       0  5020.2    0.04       0  5024.2    0.05       0
Bank Sta=5020.2,5024.2
Exp/Cntr=0.3,0.1

Type RM Length L Ch R = 1,1408,95,95,95
BEGIN DESCRIPTION:
Lacy 066 2372
END DESCRIPTION:
XS GIS Cut Line= 3
      2754805.45      6888800.48      2754471.03      6888676.31
      2754233.36      6888677.46
#Sta/Elev= 30
  4649.1  467.46  4657.9  467.66  4663.2  467.41  4688.3  467.50  4724.0  466.59
  4749.0  466.39  4765.9  465.32  4779.4  464.92  4797.9  465.18  4809.7  464.83
  4834.8  463.32  4851.2  462.97  4895.5  461.30  4925.9  460.61  4950.9  460.73
  4966.5  459.97  4966.8  459.47  4970.3  459.47  4970.5  459.97  5005.8  460.53
  5020.9  461.15  5040.9  461.51  5050.9  462.16  5070.9  462.23  5110.9  463.55
  5120.9  464.06  5140.9  465.95  5170.9  466.01  5200.9  466.63  5243.5  466.52
#Mann=3,-1,0
  4649.1    0.05       0  4966.5    0.04       0  4970.5    0.05       0
Bank Sta=4966.5,4970.5
Exp/Cntr=0.3,0.1

Type RM Length L Ch R = 1,1313,148,148,148
BEGIN DESCRIPTION:
Lacy 066 2371
END DESCRIPTION:
XS GIS Cut Line= 3
      2754842.03      6888704.80      2754473.97      6888582.10
      2754170.65      6888582.41
#Sta/Elev= 30
  4614.7  464.45  4639.7  464.94  4645.0  464.58  4726.5  463.20  4747.6  462.38
  4758.1  462.43  4771.5  461.70  4797.8  461.93  4803.1  461.64  4810.8  461.71
  4834.7  460.43  4861.1  460.20  4892.7  459.47  4897.9  459.13  4916.2  459.04
  4924.3  459.38  4959.2  459.01  4959.4  458.51  4962.9  458.51  4963.2  459.01
  4987.5  459.30  4999.0  459.02  5020.6  459.19  5040.6  459.65  5060.6  460.86
  5130.6  461.64  5180.6  462.83  5270.6  463.15  5300.6  464.03  5306.0  464.87
#Mann=3,-1,0
  4614.7    0.05       0  4959.2    0.04       0  4963.2    0.05       0
Bank Sta=4959.2,4963.2
Exp/Cntr=0.3,0.1

Type RM Length L Ch R = 1,1165,208,208,208
BEGIN DESCRIPTION:
Lacy 066 2370
END DESCRIPTION:
XS GIS Cut Line= 3
      2754928.25      6888626.79      2754524.78      6888450.50
      2754125.68      6888451.45
#Sta/Elev= 30
  4559.7  460.95  4588.0  460.87  4611.4  461.34  4616.9  460.98  4634.8  461.22
  4640.3  460.90  4658.2  461.22  4663.7  460.63  4710.5  460.47  4762.8  459.43
  4809.6  459.48  4815.0  458.80  4833.0  458.70  4838.4  458.31  4867.7  458.96
  4922.3  457.55  4976.8  457.88  4987.7  457.39  4988.0  456.89  4991.5  456.89
  4991.7  457.39  5098.8  458.37  5108.8  458.81  5158.8  458.96  5218.8  459.91
  5238.8  459.91  5378.8  463.64  5388.8  463.99  5396.4  464.93  5399.1  464.93
#Mann=3,-1,0
  4559.7    0.05       0  4987.7    0.04       0  4991.7    0.05       0
Bank Sta=4987.7,4991.7
Exp/Cntr=0.3,0.1

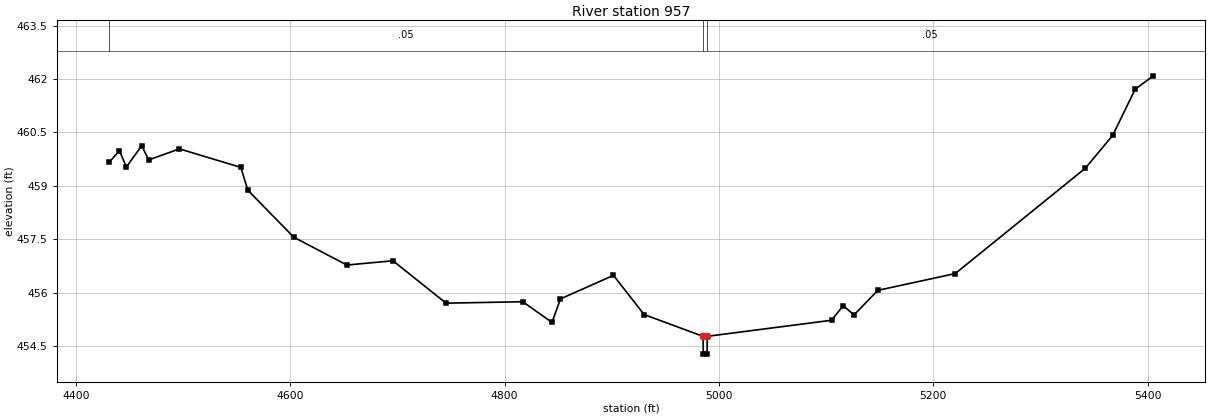
Type RM Length L Ch R = 1,957,0,0,0
BEGIN DESCRIPTION:
Lacy 066 2369
END DESCRIPTION:
XS GIS Cut Line= 3
      2754963.65      6888606.04      2754526.10      6888242.46
      2754139.92      6888364.82
#Sta/Elev= 30
  4431.1  459.66  4440.7  459.99  4447.2  459.53  4461.5  460.13  4468.0  459.73
  4496.7  460.04  4554.0  459.52  4560.5  458.88  4603.4  457.56  4652.9  456.78
  4695.9  456.90  4745.4  455.71  4817.0  455.75  4844.3  455.17  4852.1  455.83
  4901.6  456.49  4930.2  455.39  4985.1  454.78  4985.4  454.28  4988.9  454.28
  4989.1  454.78  5105.0  455.23  5115.9  455.64  5126.0  455.38  5148.2  456.07
  5220.4  456.54  5341.9  459.50  5367.3  460.42  5388.2  461.71  5405.1  462.09
#Mann=3,-1,0
  4431.1    0.05       0  4985.1    0.04       0  4989.1    0.05       0
Bank Sta=4985.1,4989.1
Exp/Cntr=0.3,0.1

Chan Stop Cuts=-1