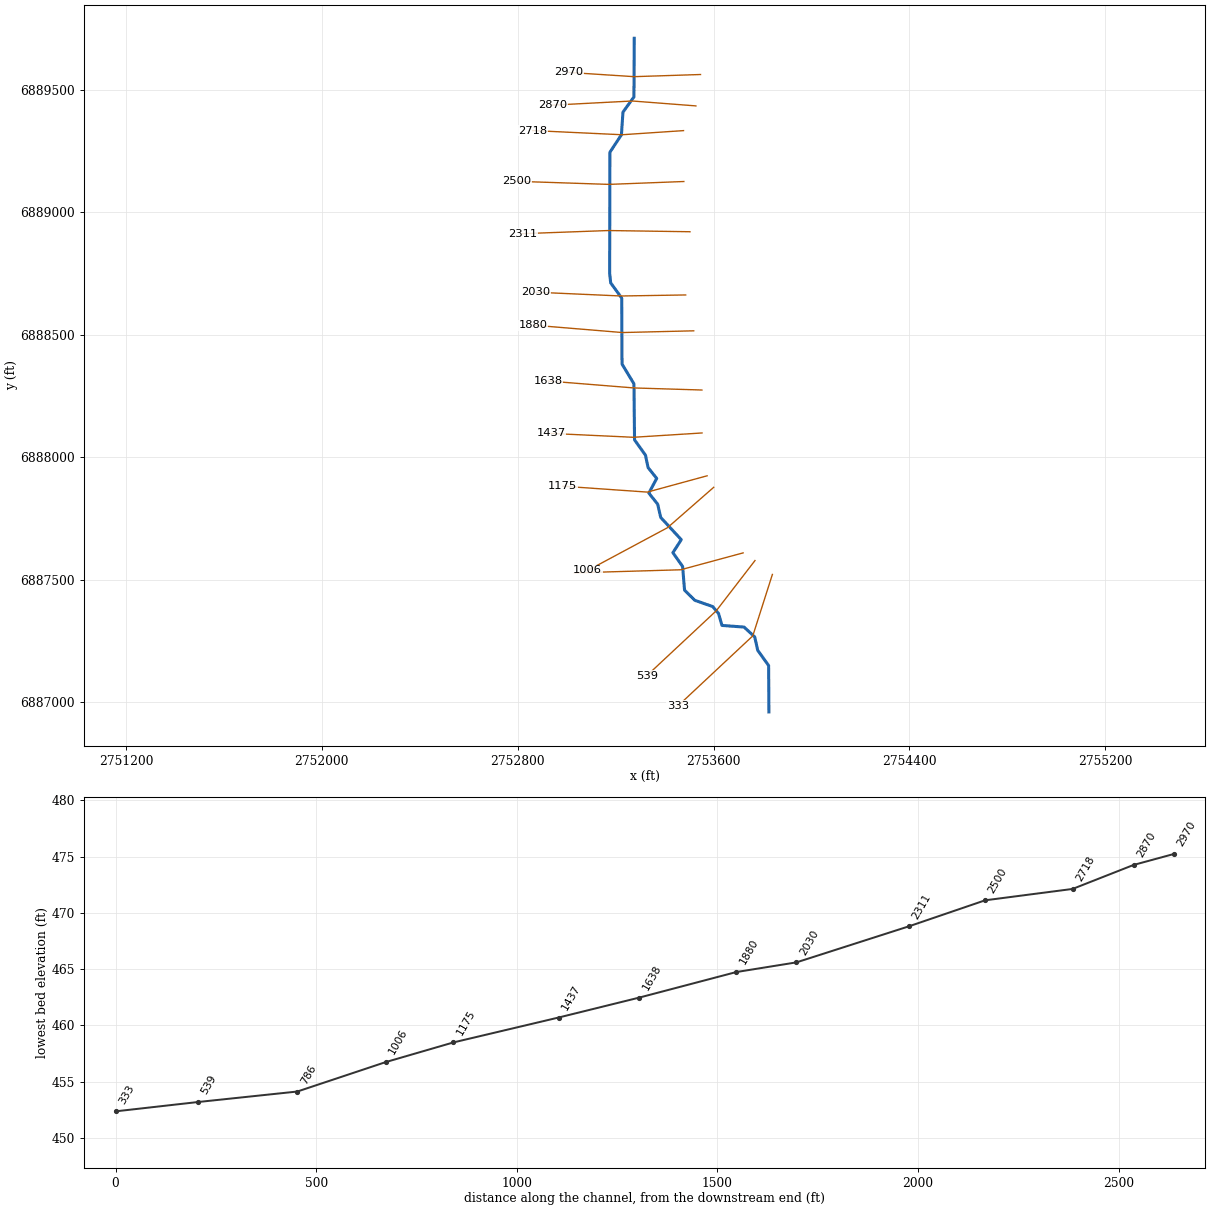
--- Lacy 067.prj (project) ---

Proj Title=Lacy 067 Base Level Engineering
Current Plan=p01
Default Exp/Contr=0.3,0.1
English Units
Geom File=g01
Flow File=f01
Plan File=p01
BEGIN DESCRIPTION:
Lacy 067
END DESCRIPTION:

--- Lacy 067.p01 (plan) ---

Plan Title=Multiple Run
Short Identifier=Multiple
Geom File=g01
Flow File=f01
Subcritical Flow
K Sum by GR= 0
Std Step Tol= 0.01
Critical Tol= 0.01
Num of Std Step Trials= 20
Max Error Tol= 0.3
Flow Tol Ratio= 0.001
Split Flow NTrial= 30
Split Flow Tol= 0.02
Split Flow Ratio= 0.02
Log Output Level= 0
Friction Slope Method= 1
Unsteady Friction Slope Method= 2
Unsteady Bridges Friction Slope Method= 1
Parabolic Critical Depth
Global Vel Dist=  1 , 1 , 1
Global Log Level= 0
CheckData=True
Encroach Param= -1, 0, 0, 0
BEGIN DESCRIPTION:
Multiple Run
END DESCRIPTION:

--- Lacy 067.f01 (steady flow) ---

Flow Title=Multiple
Number of Profiles=7
Profile Names=10-year,25-year,50-year,1pct_min,100-year,1pct_plu,500-year
River Rch & RM= Lacy 067,Reach-1,2970
     209     263     303     175     349     697     462
Boundary for River Rch & Prof#=Lacy 067,Reach-1,1
Up Type=0
Dn Type=3
Dn Slope=0.005
Boundary for River Rch & Prof#=Lacy 067,Reach-1,2
Up Type=0
Dn Type=3
Dn Slope=0.005
Boundary for River Rch & Prof#=Lacy 067,Reach-1,3
Up Type=0
Dn Type=3
Dn Slope=0.005
Boundary for River Rch & Prof#=Lacy 067,Reach-1,4
Up Type=0
Dn Type=3
Dn Slope=0.005
Boundary for River Rch & Prof#=Lacy 067,Reach-1,5
Up Type=0
Dn Type=3
Dn Slope=0.005
Boundary for River Rch & Prof#=Lacy 067,Reach-1,6
Up Type=0
Dn Type=3
Dn Slope=0.005
Boundary for River Rch & Prof#=Lacy 067,Reach-1,7
Up Type=0
Dn Type=3
Dn Slope=0.005

--- Lacy 067.g01 (geometry) ---

Geom Title=Existing Conditions

River Reach=Lacy 067,Reach-1
Reach XY= 30
      2753276.00      6889711.00      2753274.78      6889471.50
      2753229.86      6889409.40      2753223.64      6889316.98
      2753176.52      6889245.78      2753175.55      6888750.81
      2753179.78      6888712.57      2753224.78      6888650.50
      2753226.07      6888381.03      2753274.78      6888300.50
      2753277.20      6888071.50      2753321.84      6888009.25
      2753332.37      6887958.70      2753367.76      6887914.23
      2753335.58      6887854.45      2753371.56      6887809.35
      2753384.16      6887754.95      2753467.99      6887664.33
      2753433.80      6887611.10      2753473.45      6887555.10
      2753481.42      6887458.33      2753523.45      6887416.75
      2753596.42      6887391.26      2753620.08      6887363.15
      2753634.35      6887314.19      2753724.65      6887307.45
      2753767.99      6887267.38      2753780.23      6887212.78
      2753824.81      6887150.51      2753826.00      6886961.00

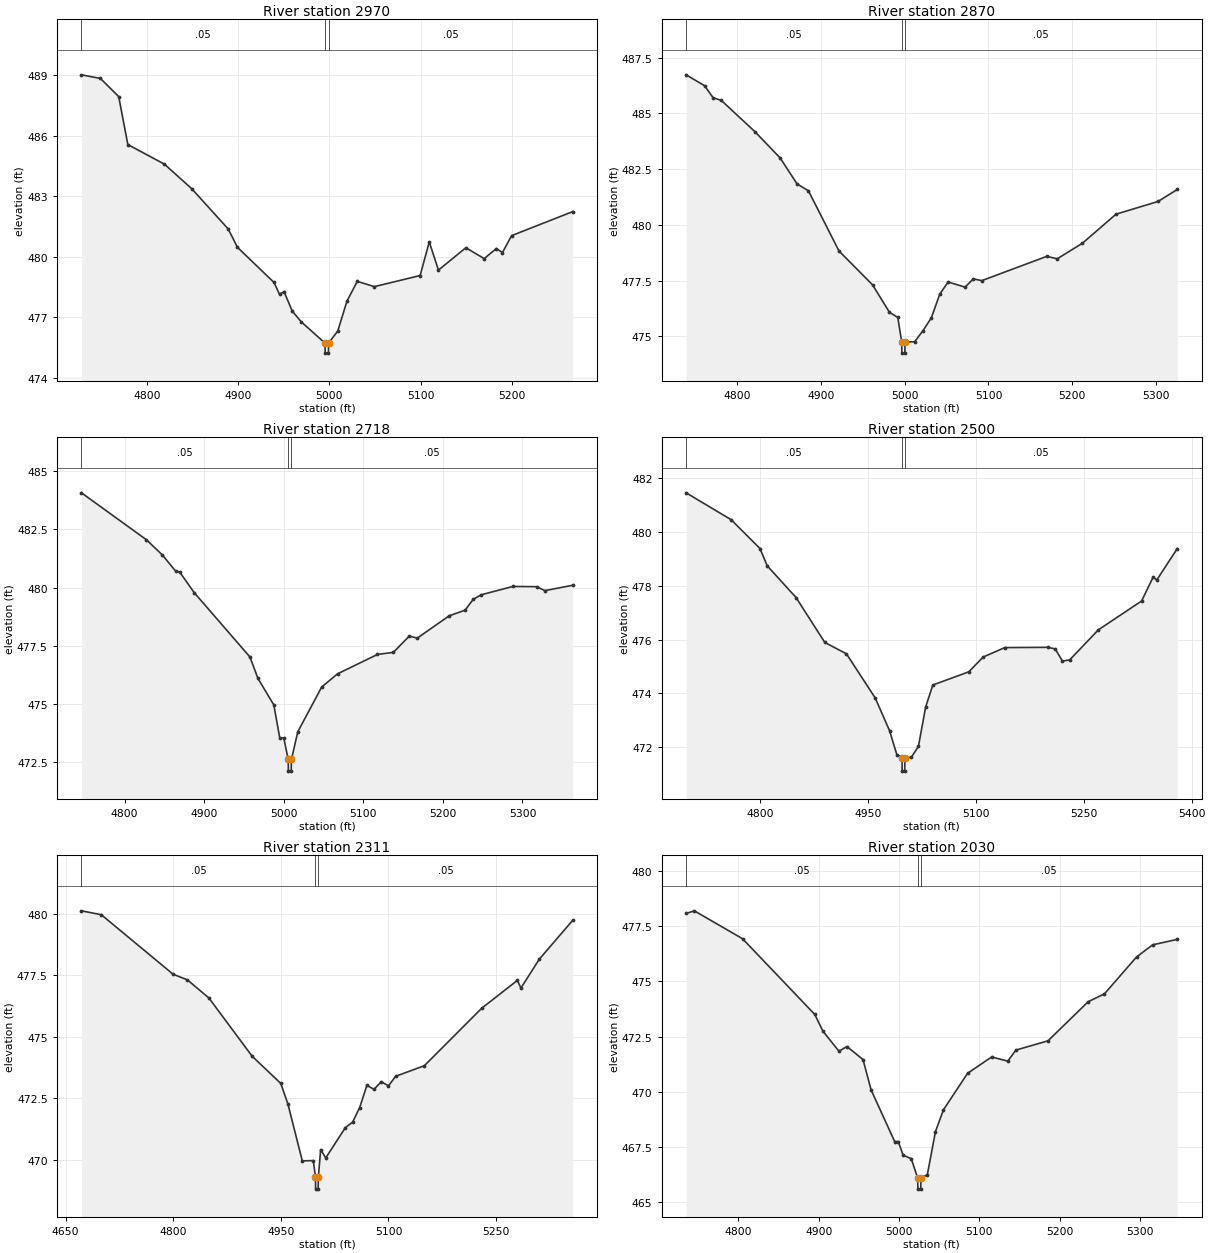
Type RM Length L Ch R = 1,2970,100,100,100
BEGIN DESCRIPTION:
Lacy 067 2368
END DESCRIPTION:
XS GIS Cut Line= 3
      2753546.76      6889563.07      2753275.20      6889554.27
      2753009.26      6889571.53
#Sta/Elev= 30
  4728.3  489.03  4749.1  488.85  4769.1  487.95  4779.1  485.57  4819.1  484.60
  4849.1  483.38  4889.1  481.38  4899.2  480.47  4939.2  478.73  4945.3  478.14
  4950.3  478.27  4959.2  477.31  4969.2  476.77  4995.1  475.72  4995.4  475.22
  4998.9  475.22  4999.1  475.72  5009.2  476.32  5019.2  477.80  5030.5  478.78
  5049.3  478.52  5099.4  479.07  5109.4  480.74  5119.5  479.34  5149.5  480.45
  5169.6  479.91  5182.9  480.41  5189.6  480.21  5199.6  481.05  5266.5  482.24
#Mann=3,-1,0
  4728.3    0.05       0  4995.1    0.04       0  4999.1    0.05       0
Bank Sta=4995.1,4999.1
Exp/Cntr=0.3,0.1

Type RM Length L Ch R = 1,2870,152,152,152
BEGIN DESCRIPTION:
Lacy 067 2367
END DESCRIPTION:
XS GIS Cut Line= 3
      2753527.89      6889434.90      2753267.86      6889454.94
      2752942.90      6889438.03
#Sta/Elev= 30
  4739.2  486.73  4761.2  486.24  4771.2  485.71  4781.2  485.58  4821.3  484.18
  4851.4  483.00  4871.5  481.84  4885.1  481.53  4921.6  478.83  4961.7  477.31
  4981.8  476.08  4991.8  475.85  4996.4  474.75  4996.7  474.25  5000.2  474.25
  5000.4  474.75  5011.9  474.76  5021.9  475.26  5031.9  475.84  5041.9  476.90
  5051.9  477.44  5072.0  477.21  5082.0  477.58  5092.0  477.50  5169.6  478.59
  5182.1  478.48  5212.2  479.18  5252.2  480.48  5302.3  481.05  5325.4  481.59
#Mann=3,-1,0
  4739.2    0.05       0  4996.4    0.04       0  5000.4    0.05       0
Bank Sta=4996.4,5000.4
Exp/Cntr=0.3,0.1

Type RM Length L Ch R = 1,2718,218,218,218
BEGIN DESCRIPTION:
Lacy 067 2365
END DESCRIPTION:
XS GIS Cut Line= 3
      2753477.18      6889334.09      2753226.38      6889317.18
      2752861.05      6889334.30
#Sta/Elev= 30
  4745.9  484.07  4827.3  482.06  4847.3  481.41  4864.2  480.71  4869.3  480.67
  4887.4  479.79  4957.6  477.02  4967.6  476.10  4987.6  474.96  4995.0  473.55
  5000.0  473.55  5005.7  472.62  5005.9  472.12  5009.4  472.12  5009.7  472.62
  5017.7  473.81  5047.7  475.73  5067.7  476.30  5117.8  477.13  5137.8  477.22
  5157.8  477.92  5167.8  477.83  5207.9  478.79  5227.9  479.03  5237.9  479.49
  5247.9  479.69  5288.0  480.05  5318.0  480.04  5328.0  479.87  5363.0  480.10
#Mann=3,-1,0
  4745.9    0.05       0  5005.7    0.04       0  5009.7    0.05       0
Bank Sta=5005.7,5009.7
Exp/Cntr=0.3,0.1

Type RM Length L Ch R = 1,2500,189,189,189
BEGIN DESCRIPTION:
Lacy 067 2364
END DESCRIPTION:
XS GIS Cut Line= 3
      2753478.54      6889126.30      2753172.61      6889114.55
      2752796.37      6889127.08
#Sta/Elev= 30
  4697.5  481.45  4760.1  480.45  4800.1  479.38  4810.1  478.74  4850.2  477.56
  4890.2  475.89  4920.2  475.47  4960.2  473.83  4980.2  472.61  4990.3  471.72
  4997.5  471.61  4997.7  471.11  5001.2  471.11  5001.5  471.61  5010.3  471.62
  5020.3  472.03  5030.3  473.49  5040.3  474.31  5090.3  474.80  5110.3  475.35
  5140.3  475.70  5200.4  475.71  5210.4  475.65  5220.4  475.20  5230.4  475.24
  5270.4  476.36  5330.4  477.43  5346.5  478.32  5351.5  478.21  5380.1  479.38
#Mann=3,-1,0
  4697.5    0.05       0  4997.5    0.04       0  5001.5    0.05       0
Bank Sta=4997.5,5001.5
Exp/Cntr=0.3,0.1

Type RM Length L Ch R = 1,2311,281,281,281
BEGIN DESCRIPTION:
Lacy 067 2362
END DESCRIPTION:
XS GIS Cut Line= 3
      2753503.66      6888921.26      2753169.85      6888926.15
      2752819.53      6888913.35
#Sta/Elev= 30
  4672.2  480.13  4699.9  479.97  4799.9  477.55  4819.9  477.32  4849.9  476.58
  4909.9  474.22  4949.9  473.11  4959.9  472.27  4979.9  469.96  4995.2  469.97
  4998.3  469.31  4998.5  468.81  5002.0  468.81  5002.3  469.31  5005.5  470.42
  5012.6  470.08  5039.9  471.31  5049.9  471.53  5059.9  472.13  5069.9  473.03
  5079.9  472.87  5090.0  473.18  5100.0  473.01  5110.0  473.40  5150.0  473.83
  5230.0  476.17  5279.6  477.30  5284.6  476.99  5310.1  478.16  5356.6  479.74
#Mann=3,-1,0
  4672.2    0.05       0  4998.3    0.04       0  5002.3    0.05       0
Bank Sta=4998.3,5002.3
Exp/Cntr=0.3,0.1

Type RM Length L Ch R = 1,2030,150,150,150
BEGIN DESCRIPTION:
Lacy 067 2363
END DESCRIPTION:
XS GIS Cut Line= 3
      2753486.08      6888663.23      2753222.17      6888658.99
      2752875.25      6888674.39
#Sta/Elev= 30
  4735.1  478.07  4745.2  478.19  4805.2  476.93  4895.2  473.50  4905.2  472.75
  4925.2  471.84  4935.2  472.05  4955.2  471.46  4965.2  470.09  4994.6  467.75
  4999.0  467.75  5005.2  467.13  5015.2  466.98  5023.2  466.10  5023.5  465.60
  5027.0  465.60  5027.2  466.10  5035.2  466.25  5045.3  468.20  5055.3  469.19
  5085.3  470.84  5115.3  471.58  5135.3  471.39  5145.4  471.89  5185.4  472.31
  5235.4  474.08  5255.5  474.43  5295.5  476.10  5315.5  476.65  5346.3  476.90
#Mann=3,-1,0
  4735.1    0.05       0  5023.2    0.04       0  5027.2    0.05       0
Bank Sta=5023.2,5027.2
Exp/Cntr=0.3,0.1

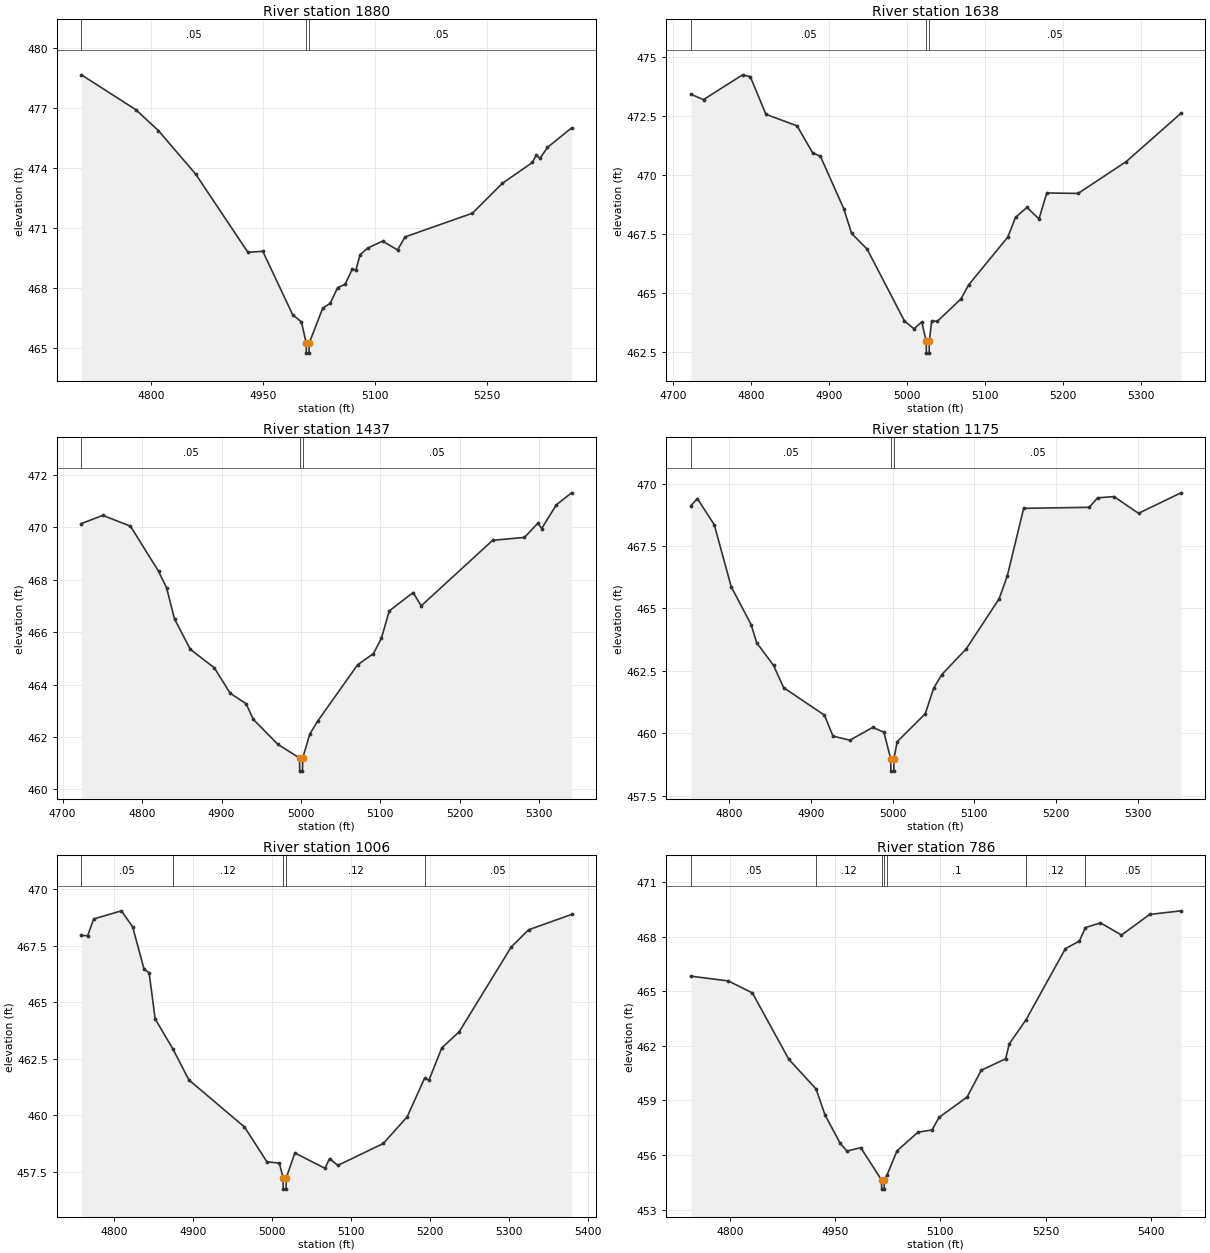
Type RM Length L Ch R = 1,1880,242,242,242
BEGIN DESCRIPTION:
Lacy 067 2361
END DESCRIPTION:
XS GIS Cut Line= 3
      2753518.96      6888516.82      2753227.62      6888509.76
      2752863.79      6888539.90
#Sta/Elev= 30
  4706.4  478.68  4779.4  476.93  4809.4  475.89  4859.4  473.71  4929.4  469.79
  4949.4  469.84  4989.4  466.66  5001.2  466.30  5007.5  465.24  5007.7  464.74
  5011.2  464.74  5011.5  465.24  5029.6  466.99  5039.6  467.23  5049.6  468.02
  5059.7  468.19  5069.1  468.94  5074.1  468.91  5079.7  469.67  5089.8  470.00
  5109.8  470.35  5129.9  469.91  5139.9  470.56  5230.2  471.75  5270.4  473.25
  5310.5  474.29  5315.6  474.66  5320.6  474.49  5330.6  475.04  5362.9  476.02
#Mann=3,-1,0
  4706.4    0.05       0  5007.5    0.04       0  5011.5    0.05       0
Bank Sta=5007.5,5011.5
Exp/Cntr=0.3,0.1

Type RM Length L Ch R = 1,1638,201,201,201
BEGIN DESCRIPTION:
Lacy 067 2360
END DESCRIPTION:
XS GIS Cut Line= 3
      2753552.33      6888275.18      2753275.28      6888283.61
      2752924.40      6888311.90
#Sta/Elev= 30
  4722.5  473.43  4738.8  473.20  4788.9  474.25  4798.9  474.17  4818.9  472.58
  4858.9  472.09  4878.9  470.95  4888.9  470.80  4918.9  468.58  4928.9  467.54
  4948.9  466.87  4996.8  463.83  5009.0  463.50  5019.0  463.79  5024.7  462.97
  5025.0  462.47  5028.5  462.47  5028.7  462.97  5031.7  463.83  5039.1  463.82
  5069.2  464.76  5079.2  465.36  5129.4  467.38  5139.4  468.22  5154.1  468.64
  5169.5  468.15  5179.5  469.25  5219.7  469.23  5281.6  470.58  5351.7  472.62
#Mann=3,-1,0
  4722.5    0.05       0  5024.7    0.04       0  5028.7    0.05       0
Bank Sta=5024.7,5028.7
Exp/Cntr=0.3,0.1

Type RM Length L Ch R = 1,1437,262,262,262
BEGIN DESCRIPTION:
Lacy 067 2359
END DESCRIPTION:
XS GIS Cut Line= 3
      2753552.94      6888099.85      2753272.82      6888082.23
      2752936.86      6888097.90
#Sta/Elev= 30
  4723.6  470.14  4750.6  470.45  4785.3  470.04  4820.7  468.32  4830.8  467.69
  4840.8  466.50  4860.8  465.34  4890.9  464.64  4910.9  463.67  4930.9  463.27
  4940.1  462.67  4971.0  461.72  4998.2  461.20  4998.4  460.70  5001.9  460.70
  5002.2  461.20  5011.1  462.11  5021.1  462.61  5071.2  464.75  5091.2  465.18
  5101.2  465.76  5111.2  466.81  5141.2  467.51  5151.3  467.00  5241.3  469.50
  5281.4  469.61  5298.1  470.15  5303.1  469.95  5321.4  470.85  5340.6  471.31
#Mann=3,-1,0
  4723.6    0.05       0  4998.2    0.04       0  5002.2    0.05       0
Bank Sta=4998.2,5002.2
Exp/Cntr=0.3,0.1

Type RM Length L Ch R = 1,1175,169,169,169
BEGIN DESCRIPTION:
Lacy 067 2358
END DESCRIPTION:
XS GIS Cut Line= 3
      2753573.67      6887925.00      2753329.59      6887858.47
      2752984.31      6887882.57
#Sta/Elev= 30
  4753.3  469.11  4761.3  469.40  4782.0  468.35  4802.7  465.87  4827.1  464.35
  4833.8  463.63  4854.5  462.72  4866.8  461.83  4916.7  460.73  4927.1  459.89
  4947.8  459.73  4975.7  460.24  4989.3  460.05  4997.6  458.99  4997.9  458.49
  5001.4  458.49  5001.6  458.99  5005.6  459.67  5040.0  460.79  5050.0  461.80
  5060.0  462.35  5090.1  463.39  5130.2  465.39  5140.2  466.31  5160.2  469.01
  5240.4  469.05  5250.5  469.43  5270.5  469.48  5300.6  468.81  5352.4  469.63
#Mann=3,-1,0
  4753.3    0.05       0  4997.6    0.04       0  5001.6    0.05       0
Bank Sta=4997.6,5001.6
Exp/Cntr=0.3,0.1

Type RM Length L Ch R = 1,1006,220,220,220
BEGIN DESCRIPTION:
Lacy 067 2357
END DESCRIPTION:
XS GIS Cut Line= 3
      2753600.53      6887878.04      2753411.97      6887713.27
      2753086.11      6887538.67
#Sta/Elev= 30
  4758.9  467.96  4766.8  467.95  4774.4  468.69  4809.5  469.05  4823.7  468.34
  4838.0  466.49  4844.6  466.30  4852.2  464.27  4874.8  462.93  4894.9  461.57
  4965.2  459.49  4993.6  457.95  5009.3  457.89  5014.1  457.24  5014.3  456.74
  5017.8  456.74  5018.1  457.24  5028.9  458.34  5067.1  457.66  5072.8  458.09
  5083.3  457.79  5140.9  458.76  5171.1  459.94  5193.0  461.64  5198.7  461.57
  5214.9  462.99  5236.9  463.70  5302.7  467.45  5324.6  468.21  5379.0  468.89
#Mann=5,-1,0
  4758.9    0.05       0  4874.8    0.12       0  5014.1    0.07       0
  5018.1    0.12       0  5193.0    0.05       0
Bank Sta=5014.1,5018.1
Exp/Cntr=0.3,0.1

Type RM Length L Ch R = 1,786,247,247,247
BEGIN DESCRIPTION:
Lacy 067 2356
END DESCRIPTION:
XS GIS Cut Line= 3
      2753720.73      6887610.36      2753465.65      6887541.39
      2753031.37      6887528.69
#Sta/Elev= 30
  4744.3  465.83  4797.6  465.57  4832.1  464.91  4883.9  461.27  4922.7  459.64
  4935.7  458.20  4957.1  456.66  4966.7  456.22  4986.6  456.41  5016.2  454.63
  5016.4  454.13  5019.9  454.13  5020.2  454.63  5024.1  454.91  5038.2  456.23
  5068.2  457.26  5088.2  457.38  5098.2  458.07  5138.2  459.19  5158.3  460.66
  5193.1  461.29  5198.3  462.11  5222.1  463.43  5278.3  467.34  5298.3  467.76
  5306.9  468.50  5328.3  468.76  5358.3  468.09  5398.4  469.22  5443.0  469.42
#Mann=7,-1,0
  4744.3    0.05       0  4922.7    0.12       0  5016.2    0.07       0
  5020.2    0.12       0  5024.1     0.1       0  5222.1    0.12       0
  5306.9    0.05       0
Bank Sta=5016.2,5020.2
Exp/Cntr=0.3,0.1

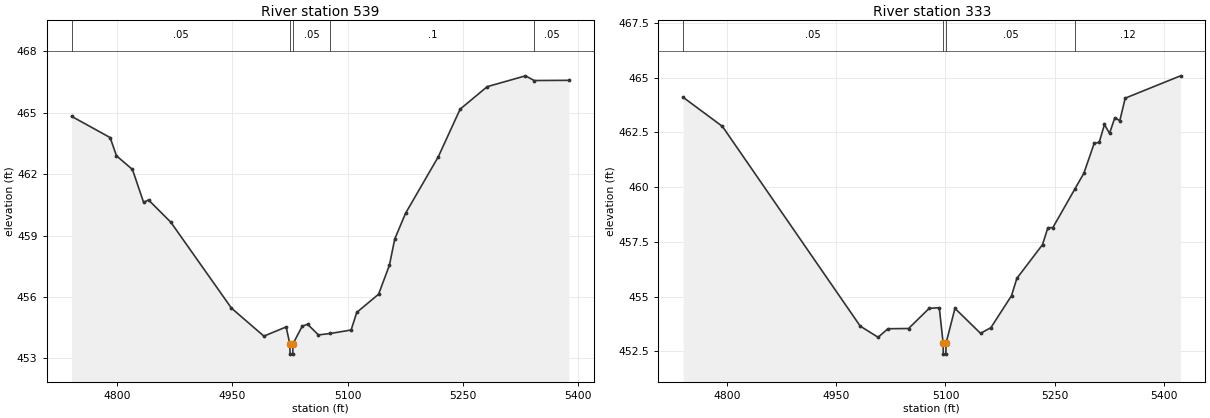
Type RM Length L Ch R = 1,539,206,206,206
BEGIN DESCRIPTION:
Lacy 067 2355
END DESCRIPTION:
XS GIS Cut Line= 3
      2753769.14      6887579.07      2753610.91      6887373.89
      2753327.57      6887109.40
#Sta/Elev= 30
  4741.0  464.83  4791.2  463.79  4799.4  462.90  4820.2  462.23  4834.7  460.62
  4841.1  460.74  4870.1  459.65  4948.9  455.45  4991.1  454.08  5020.0  454.53
  5024.8  453.70  5025.1  453.20  5028.6  453.20  5028.8  453.70  5041.0  454.57
  5047.9  454.66  5062.0  454.14  5077.5  454.21  5104.5  454.38  5111.8  455.24
  5140.2  456.13  5154.3  457.55  5161.2  458.83  5175.3  460.09  5217.8  462.85
  5246.2  465.18  5281.4  466.28  5331.2  466.81  5342.5  466.58  5387.7  466.59
#Mann=5,-1,0
  4741.0    0.05       0  5024.8    0.04       0  5028.8    0.05       0
  5077.5     0.1       0  5342.5    0.05       0
Bank Sta=5024.8,5028.8
Exp/Cntr=0.3,0.1

Type RM Length L Ch R = 1,333,0,0,0
BEGIN DESCRIPTION:
Lacy 067 2366
END DESCRIPTION:
XS GIS Cut Line= 3
      2753840.20      6887522.35      2753760.09      6887271.44
      2753454.17      6886985.40
#Sta/Elev= 30
  4740.2  464.10  4794.1  462.77  4983.1  453.65  5007.6  453.14  5021.1  453.53
  5049.4  453.54  5077.6  454.46  5091.5  454.49  5096.8  452.87  5097.0  452.37
  5100.5  452.37  5100.8  452.87  5113.0  454.46  5148.1  453.32  5162.3  453.58
  5190.6  455.04  5197.9  455.83  5233.1  457.37  5240.4  458.14  5247.3  458.15
  5277.6  459.92  5289.8  460.63  5304.0  462.00  5310.8  462.04  5318.1  462.86
  5325.0  462.45  5332.3  463.17  5339.1  463.03  5346.5  464.06  5422.4  465.08
#Mann=4,-1,0
  4740.2    0.05       0  5096.8    0.04       0  5100.8    0.05       0
  5277.6    0.12       0
Bank Sta=5096.8,5100.8
Exp/Cntr=0.3,0.1

Chan Stop Cuts=-1