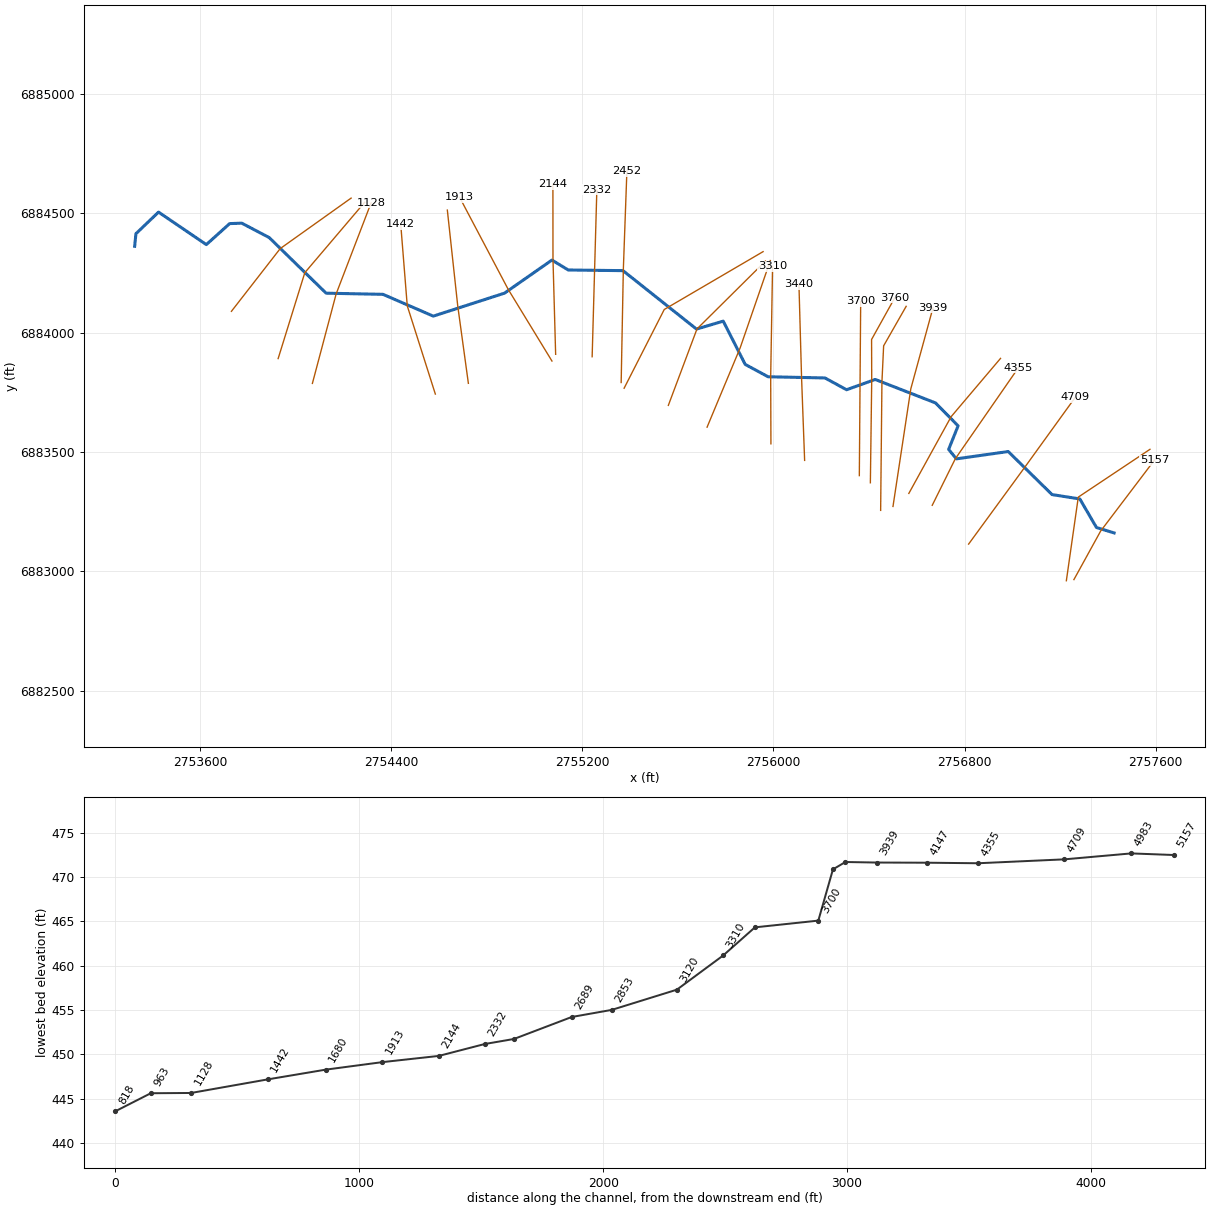
--- Lacy 068.prj (project) ---

Proj Title=Lacy 068 Base Level Engineering
Current Plan=p01
Default Exp/Contr=0.3,0.1
English Units
Geom File=g01
Flow File=f01
Plan File=p01
BEGIN DESCRIPTION:
Lacy 068
END DESCRIPTION:

--- Lacy 068.p01 (plan) ---

Plan Title=Multiple Run
Short Identifier=Multiple
Geom File=g01
Flow File=f01
Subcritical Flow
K Sum by GR= 0
Std Step Tol= 0.01
Critical Tol= 0.01
Num of Std Step Trials= 20
Max Error Tol= 0.3
Flow Tol Ratio= 0.001
Split Flow NTrial= 30
Split Flow Tol= 0.02
Split Flow Ratio= 0.02
Log Output Level= 0
Friction Slope Method= 1
Unsteady Friction Slope Method= 2
Unsteady Bridges Friction Slope Method= 1
Parabolic Critical Depth
Global Vel Dist=  1 , 1 , 1
Global Log Level= 0
CheckData=True
Encroach Param= -1, 0, 0, 0
BEGIN DESCRIPTION:
Multiple Run
END DESCRIPTION:

--- Lacy 068.f01 (steady flow) ---

Flow Title=Multiple
Number of Profiles=7
Profile Names=10-year,25-year,50-year,1pct_min,100-year,1pct_plu,500-year
River Rch & RM= Lacy 068,Reach-1,5157
     317     409     481     282     562    1121     767
Boundary for River Rch & Prof#=Lacy 068,Reach-1,1
Up Type=0
Dn Type=3
Dn Slope=0.005
Boundary for River Rch & Prof#=Lacy 068,Reach-1,2
Up Type=0
Dn Type=3
Dn Slope=0.005
Boundary for River Rch & Prof#=Lacy 068,Reach-1,3
Up Type=0
Dn Type=3
Dn Slope=0.005
Boundary for River Rch & Prof#=Lacy 068,Reach-1,4
Up Type=0
Dn Type=3
Dn Slope=0.005
Boundary for River Rch & Prof#=Lacy 068,Reach-1,5
Up Type=0
Dn Type=3
Dn Slope=0.005
Boundary for River Rch & Prof#=Lacy 068,Reach-1,6
Up Type=0
Dn Type=3
Dn Slope=0.005
Boundary for River Rch & Prof#=Lacy 068,Reach-1,7
Up Type=0
Dn Type=3
Dn Slope=0.005

--- Lacy 068.g01 (geometry) ---

Geom Title=Existing Conditions

River Reach=Lacy 068,Reach-1
Reach XY= 30
      2757426.00      6883161.00      2757352.02      6883183.83
      2757282.45      6883303.25      2757166.22      6883321.52
      2756982.67      6883501.71      2756765.59      6883471.19
      2756733.26      6883510.64      2756772.85      6883609.36
      2756678.32      6883705.18      2756426.00      6883803.44
      2756305.96      6883760.42      2756215.50      6883809.78
      2755977.52      6883814.74      2755881.58      6883866.58
      2755789.73      6884047.60      2755677.74      6884014.37
      2755370.15      6884258.94      2755141.16      6884261.66
      2755072.59      6884303.19      2754874.42      6884164.83
      2754576.00      6884068.56      2754365.50      6884159.78
      2754127.46      6884164.54      2753889.21      6884397.38
      2753774.26      6884457.69      2753723.70      6884455.88
      2753626.00      6884367.98      2753425.92      6884503.98
      2753331.31      6884413.56      2753326.00      6884361.00

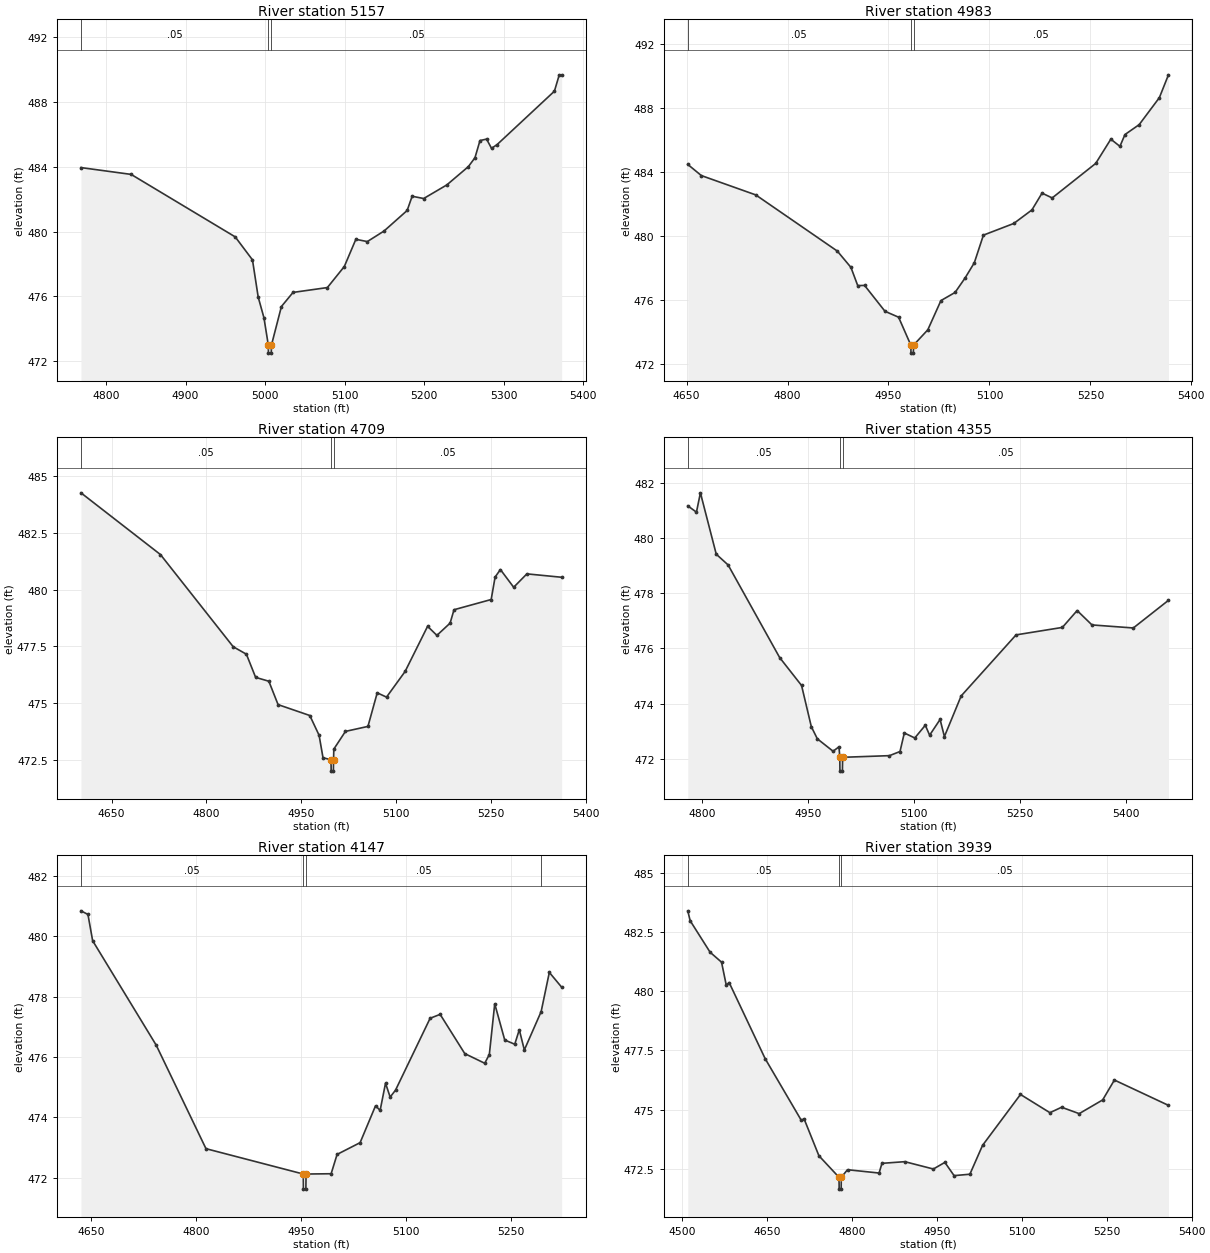
Type RM Length L Ch R = 1,5157,174,174,174
BEGIN DESCRIPTION:
Lacy 068 2324
END DESCRIPTION:
XS GIS Cut Line= 3
      2757257.66      6882965.71      2757369.37      6883168.59
      2757594.66      6883465.74
#Sta/Elev= 30
  4768.4  483.95  4831.5  483.53  4962.4  479.67  4984.1  478.25  4991.3  475.95
  4998.5  474.68  5004.0  472.99  5004.2  472.49  5007.7  472.49  5008.0  472.99
  5020.5  475.37  5035.1  476.24  5078.3  476.54  5099.6  477.84  5114.1  479.52
  5128.5  479.38  5149.5  480.03  5178.6  481.30  5184.9  482.18  5199.4  482.04
  5228.5  482.88  5255.6  484.01  5263.9  484.56  5270.2  485.62  5278.5  485.71
  5284.7  485.14  5291.7  485.37  5363.8  488.67  5369.9  489.68  5372.9  489.68
#Mann=3,-1,0
  4768.4    0.05       0  5004.0    0.04       0  5008.0    0.05       0
Bank Sta=5004,5008
Exp/Cntr=0.3,0.1

Type RM Length L Ch R = 1,4983,274,274,274
BEGIN DESCRIPTION:
Lacy 068 52
END DESCRIPTION:
XS GIS Cut Line= 3
      2757226.00      6882960.99      2757276.00      6883311.00
      2757575.98      6883510.99
#Sta/Elev= 30
  4651.8  484.49  4672.0  483.79  4752.8  482.58  4874.0  479.06  4894.2  478.04
  4904.3  476.90  4914.5  476.91  4944.8  475.29  4965.0  474.92  4983.2  473.17
  4983.4  472.67  4986.9  472.67  4987.2  473.17  5008.4  474.13  5027.9  475.96
  5048.9  476.47  5064.0  477.39  5077.5  478.33  5091.0  480.06  5136.1  480.79
  5163.1  481.64  5178.1  482.69  5193.2  482.39  5257.8  484.55  5280.3  486.07
  5293.8  485.62  5301.3  486.36  5322.4  486.98  5352.4  488.67  5365.9  490.10
#Mann=3,-1,0
  4651.8    0.05       0  4983.2    0.04       0  4987.2    0.05       0
Bank Sta=4983.2,4987.2
Exp/Cntr=0.3,0.1

Type RM Length L Ch R = 1,4709,354,354,354
BEGIN DESCRIPTION:
Lacy 068 2322
END DESCRIPTION:
XS GIS Cut Line= 3
      2756816.82      6883114.29      2757053.92      6883438.70
      2757263.98      6883729.57
#Sta/Elev= 30
  4601.6  484.26  4727.4  481.54  4842.5  477.48  4863.4  477.15  4878.0  476.13
  4898.9  475.96  4913.5  474.93  4963.7  474.45  4978.4  473.58  4984.6  472.59
  4997.3  472.50  4997.5  472.00  5001.0  472.00  5001.3  472.50  5001.7  472.97
  5020.1  473.75  5055.7  473.97  5070.4  475.45  5085.1  475.26  5114.5  476.39
  5150.1  478.38  5164.8  477.98  5185.7  478.52  5191.9  479.11  5250.7  479.56
  5256.9  480.55  5265.3  480.88  5286.3  480.10  5307.2  480.69  5362.2  480.54
#Mann=3,-1,0
  4601.6    0.05       0  4997.3    0.04       0  5001.3    0.05       0
Bank Sta=4997.3,5001.3
Exp/Cntr=0.3,0.1

Type RM Length L Ch R = 1,4355,208,208,208
BEGIN DESCRIPTION:
Lacy 068 2320
END DESCRIPTION:
XS GIS Cut Line= 3
      2756664.64      6883276.79      2756761.16      6883471.41
      2757024.76      6883851.87
#Sta/Elev= 30
  4779.8  481.16  4792.1  480.93  4797.7  481.63  4820.1  479.41  4836.9  479.02
  4909.8  475.67  4940.8  474.66  4954.6  473.17  4963.1  472.73  4985.4  472.28
  4993.8  472.44  4994.9  472.06  4995.1  471.56  4998.6  471.56  4998.9  472.06
  5065.2  472.12  5080.1  472.27  5086.2  472.94  5101.0  472.76  5115.9  473.22
  5122.0  472.86  5136.8  473.43  5142.9  472.81  5166.6  474.28  5244.3  476.49
  5309.8  476.76  5330.7  477.37  5351.7  476.85  5410.2  476.74  5459.9  477.74
#Mann=3,-1,0
  4779.8    0.05       0  4994.9    0.04       0  4998.9    0.05       0
Bank Sta=4994.9,4998.9
Exp/Cntr=0.3,0.1

Type RM Length L Ch R = 1,4147,208,208,208
BEGIN DESCRIPTION:
Lacy 068 2321
END DESCRIPTION:
XS GIS Cut Line= 3
      2756566.61      6883326.37      2756743.66      6883647.62
      2756950.47      6883891.67
#Sta/Elev= 30
  4635.8  480.84  4645.8  480.72  4652.5  479.85  4743.3  476.39  4814.4  472.96
  4953.4  472.12  4953.6  471.62  4957.1  471.62  4957.4  472.12  4993.2  472.13
  5001.7  472.77  5034.6  473.16  5056.6  474.38  5063.2  474.23  5070.9  475.13
  5077.5  474.67  5085.2  474.90  5134.6  477.28  5148.9  477.41  5184.1  476.11
  5212.6  475.79  5219.2  476.08  5226.9  477.76  5241.2  476.56  5255.5  476.42
  5262.0  476.90  5269.2  476.23  5293.2  477.50  5304.9  478.80  5322.5  478.31
#Mann=4,-1,0
  4635.8    0.05       0  4953.4    0.05       0  4957.4    0.05       0
  5293.2    0.12       0
Bank Sta=4953.4,4957.4
Exp/Cntr=0.3,0.1

Type RM Length L Ch R = 1,3939,128,128,128
BEGIN DESCRIPTION:
Lacy 068 2319
END DESCRIPTION:
XS GIS Cut Line= 3
      2756500.32      6883271.96      2756575.02      6883764.74
      2756667.63      6884103.09
#Sta/Elev= 30
  4509.8  483.40  4514.1  482.98  4549.3  481.65  4569.5  481.23  4577.8  480.26
  4582.9  480.37  4646.6  477.15  4710.3  474.55  4715.3  474.61  4741.5  473.05
  4777.0  472.14  4777.3  471.64  4780.8  471.64  4781.0  472.14  4792.0  472.46
  4847.8  472.32  4852.9  472.73  4893.2  472.80  4943.7  472.49  4964.0  472.77
  4980.3  472.21  5008.2  472.27  5030.6  473.49  5097.6  475.64  5149.6  474.87
  5170.2  475.10  5201.3  474.83  5242.8  475.41  5263.5  476.25  5359.0  475.18
#Mann=3,-1,0
  4509.8    0.05       0  4777.0    0.04       0  4781.0    0.05       0
Bank Sta=4777,4781
Exp/Cntr=0.3,0.1

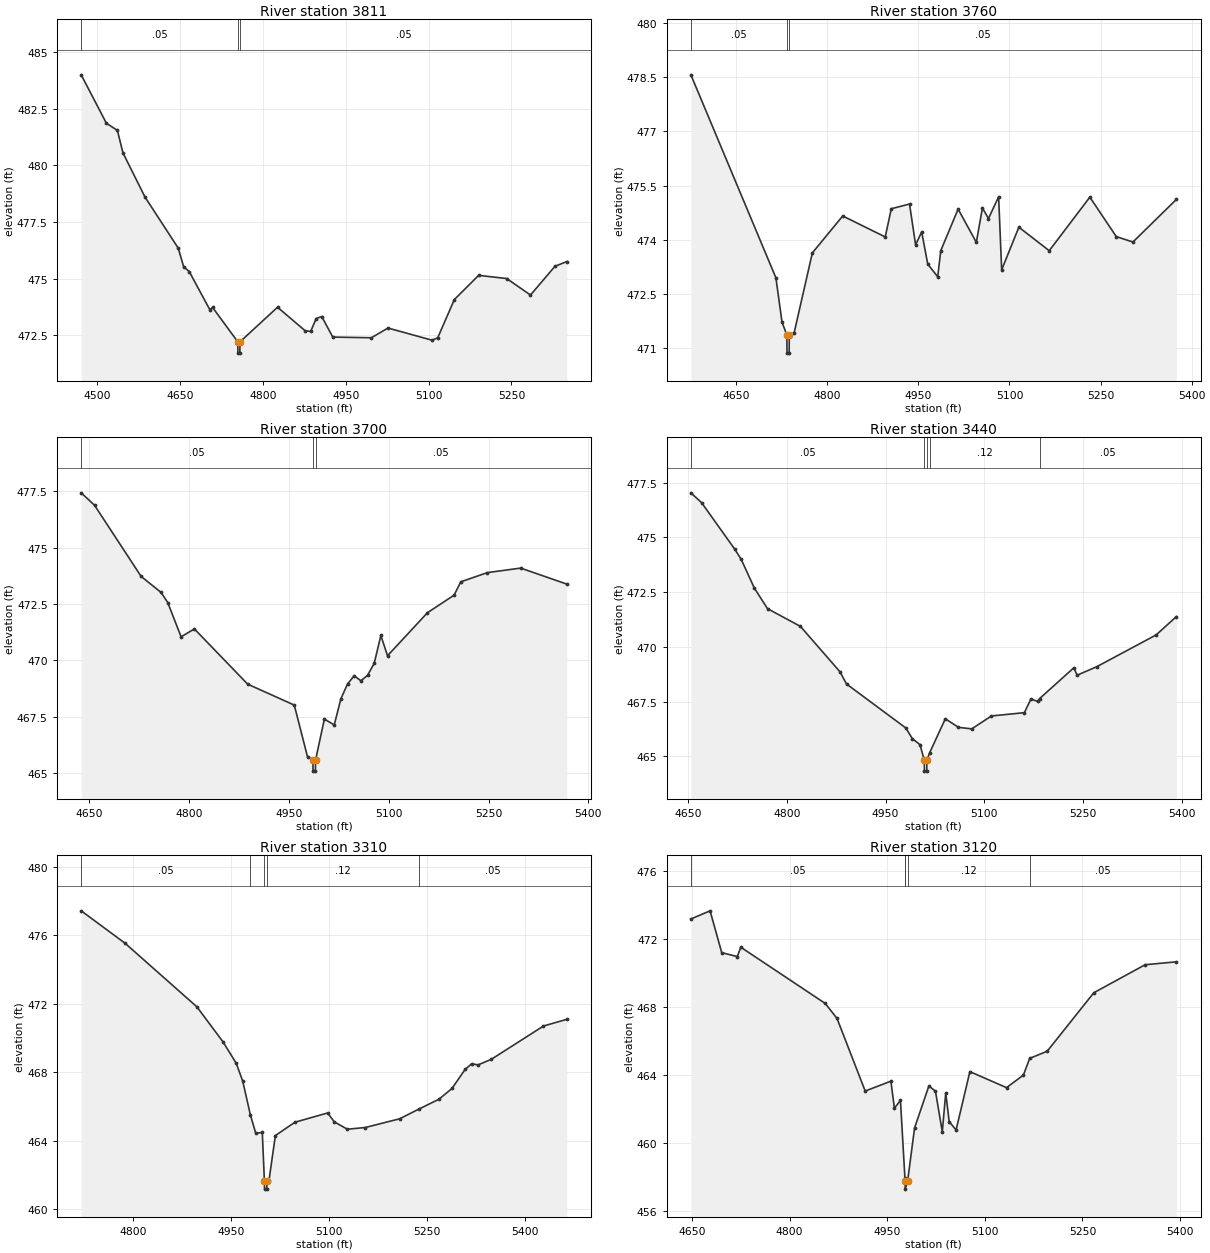
Type RM Length L Ch R = 1,3811,51,51,51
BEGIN DESCRIPTION:
Lacy 068 2318
END DESCRIPTION:
XS GIS Cut Line= 4
      2756448.64      6883255.42      2756454.02      6883792.97
      2756461.15      6883944.28      2756555.49      6884109.61
#Sta/Elev= 30
  4470.8  484.01  4516.4  481.87  4536.4  481.55  4546.4  480.56  4586.4  478.60
  4646.4  476.35  4656.4  475.52  4666.4  475.31  4703.8  473.62  4708.8  473.72
  4754.4  472.20  4754.6  471.70  4758.1  471.70  4758.4  472.20  4826.4  473.73
  4876.4  472.69  4886.4  472.66  4896.4  473.23  4906.4  473.32  4926.4  472.41
  4996.4  472.38  5026.4  472.81  5106.5  472.27  5116.5  472.38  5146.6  474.07
  5190.6  475.14  5241.3  475.00  5284.5  474.27  5328.8  475.54  5350.2  475.75
#Mann=3,-1,0
  4470.8    0.05       0  4754.4    0.04       0  4758.4    0.05       0
Bank Sta=4754.4,4758.4
Exp/Cntr=0.3,0.1

Type RM Length L Ch R = 1,3760,60,60,60
BEGIN DESCRIPTION:
Lacy 068 2316
END DESCRIPTION:
XS GIS Cut Line= 4
      2756405.61      6883371.01      2756411.29      6883800.59
      2756410.66      6883970.78      2756507.71      6884145.30
#Sta/Elev= 30
  4575.5  478.56  4715.5  472.95  4725.5  471.73  4733.5  471.37  4733.8  470.87
  4737.3  470.87  4737.5  471.37  4745.5  471.43  4775.5  473.64  4825.5  474.66
  4895.5  474.08  4905.5  474.86  4935.5  474.99  4945.5  473.86  4955.5  474.22
  4965.5  473.33  4981.9  472.98  4986.9  473.70  5015.5  474.85  5045.5  473.93
  5055.5  474.88  5065.5  474.59  5082.2  475.19  5087.2  473.17  5115.5  474.35
  5165.5  473.70  5232.4  475.18  5275.9  474.09  5303.3  473.94  5375.0  475.12
#Mann=3,-1,0
  4575.5    0.05       0  4733.5    0.04       0  4737.5    0.05       0
Bank Sta=4733.5,4737.5
Exp/Cntr=0.3,0.1

Type RM Length L Ch R = 1,3700,260,260,260
BEGIN DESCRIPTION:
Lacy 068 2317
END DESCRIPTION:
XS GIS Cut Line= 3
      2756359.39      6883401.02      2756362.24      6883766.49
      2756365.12      6884130.20
#Sta/Elev= 30
  4638.3  477.44  4658.3  476.89  4728.3  473.73  4758.3  473.02  4768.3  472.57
  4788.3  471.05  4808.3  471.40  4888.3  468.95  4958.3  468.02  4978.3  465.71
  4986.3  465.59  4986.5  465.09  4990.0  465.09  4990.3  465.59  5003.5  467.40
  5018.3  467.14  5028.3  468.30  5038.3  468.96  5048.3  469.32  5058.3  469.10
  5068.3  469.34  5078.3  469.87  5088.3  471.11  5098.3  470.21  5158.3  472.12
  5198.3  472.90  5208.3  473.49  5248.3  473.90  5298.3  474.10  5367.5  473.39
#Mann=3,-1,0
  4638.3    0.05       0  4986.3    0.04       0  4990.3    0.05       0
Bank Sta=4986.3,4990.3
Exp/Cntr=0.3,0.1

Type RM Length L Ch R = 1,3440,130,130,130
BEGIN DESCRIPTION:
Lacy 068 2311
END DESCRIPTION:
XS GIS Cut Line= 3
      2756130.43      6883464.71      2756117.57      6883812.49
      2756106.62      6884201.92
#Sta/Elev= 30
  4654.3  477.04  4670.6  476.59  4720.6  474.48  4730.6  474.01  4750.7  472.69
  4770.7  471.75  4820.7  470.94  4880.7  468.87  4890.7  468.31  4980.8  466.30
  4990.8  465.81  5002.3  465.54  5008.8  464.83  5009.1  464.33  5012.6  464.33
  5012.8  464.83  5017.0  465.17  5040.8  466.72  5060.8  466.33  5080.9  466.26
  5110.9  466.85  5160.9  467.00  5170.9  467.63  5180.9  467.51  5183.9  467.64
  5236.0  469.05  5241.0  468.71  5270.9  469.10  5361.0  470.55  5391.9  471.39
#Mann=5,-1,0
  4654.3    0.05       0  5008.8    0.04       0  5012.8    0.05       0
  5017.0    0.12       0  5183.9    0.05       0
Bank Sta=5008.8,5012.8
Exp/Cntr=0.3,0.1

Type RM Length L Ch R = 1,3310,190,190,190
BEGIN DESCRIPTION:
Lacy 068 2312
END DESCRIPTION:
XS GIS Cut Line= 3
      2755989.36      6883533.97      2755988.36      6883816.28
      2755996.22      6884276.60
#Sta/Elev= 30
  4720.8  477.42  4787.8  475.53  4897.8  471.81  4937.8  469.76  4957.8  468.52
  4967.8  467.48  4979.5  465.51  4987.8  464.42  4997.8  464.47  5001.0  461.66
  5001.2  461.16  5004.7  461.16  5005.0  461.66  5008.0  461.66  5017.8  464.29
  5047.8  465.07  5097.8  465.61  5107.9  465.09  5127.9  464.66  5155.3  464.76
  5207.9  465.27  5237.5  465.84  5267.9  466.41  5287.9  467.04  5307.9  468.15
  5317.9  468.48  5327.9  468.42  5347.9  468.74  5427.9  470.69  5463.5  471.08
#Mann=5,-1,0
  4720.8    0.05       0  4979.5    0.12       0  5001.0    0.07       0
  5005.0    0.12       0  5237.5    0.05       0
Bank Sta=5001,5005
Exp/Cntr=0.3,0.1

Type RM Length L Ch R = 1,3120,267,267,267
BEGIN DESCRIPTION:
Lacy 068 2313
END DESCRIPTION:
XS GIS Cut Line= 3
      2755722.11      6883603.73      2755860.74      6883936.13
      2755986.83      6884301.11
#Sta/Elev= 30
  4648.3  473.19  4677.8  473.67  4695.7  471.21  4719.6  470.98  4725.0  471.53
  4854.9  468.22  4872.9  467.34  4916.2  463.07  4955.7  463.65  4961.1  462.06
  4970.4  462.52  4977.3  457.93  4977.5  457.80  4977.7  457.30  4981.5  457.80
  4992.1  460.90  5014.1  463.37  5024.2  463.06  5034.7  460.67  5040.0  462.96
  5045.3  461.27  5055.9  460.78  5077.1  464.21  5133.5  463.27  5159.4  464.01
  5169.0  464.99  5195.9  465.41  5267.5  468.85  5346.5  470.50  5394.6  470.67
#Mann=5,-1,0
  4648.3    0.05       0  4977.3    0.12       0  4977.5    0.07       0
  4981.5    0.12       0  5169.0    0.05       0
Bank Sta=4977.5,4981.5
Exp/Cntr=0.3,0.1

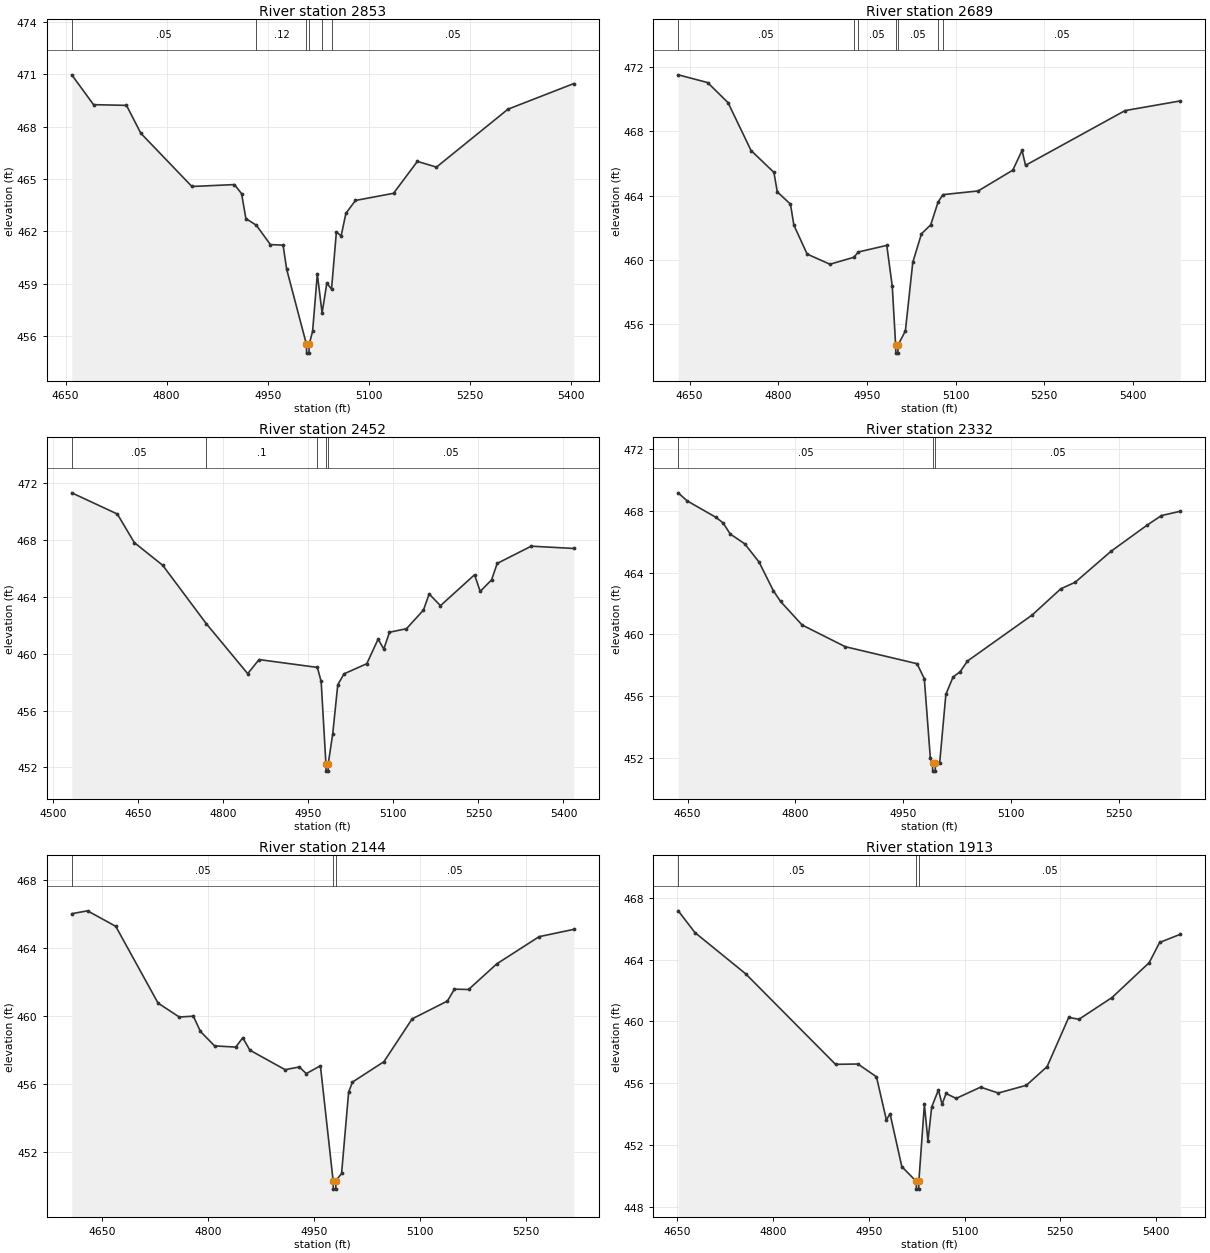
Type RM Length L Ch R = 1,2853,164,164,164
BEGIN DESCRIPTION:
Lacy 068 2314
END DESCRIPTION:
XS GIS Cut Line= 3
      2755559.95      6883695.00      2755679.83      6884014.86
      2755966.39      6884298.95
#Sta/Elev= 30
  4659.3  470.97  4691.6  469.26  4740.5  469.22  4761.8  467.62  4837.6  464.57
  4900.7  464.68  4911.3  464.16  4917.7  462.73  4933.2  462.35  4954.1  461.24
  4972.9  461.21  4978.2  459.83  5007.6  455.52  5007.8  455.02  5011.3  455.02
  5011.6  455.52  5016.7  456.27  5023.7  459.55  5030.8  457.32  5037.8  459.03
  5044.8  458.69  5052.0  461.96  5059.1  461.74  5066.1  463.03  5080.3  463.77
  5136.8  464.18  5172.2  466.01  5200.5  465.68  5306.6  469.00  5404.4  470.47
#Mann=6,-1,0
  4659.3    0.05       0  4933.2    0.12       0  5007.6    0.07       0
  5011.6    0.12       0  5030.8     0.1       0  5044.8    0.05       0
Bank Sta=5007.6,5011.6
Exp/Cntr=0.3,0.1

Type RM Length L Ch R = 1,2689,237,237,237
BEGIN DESCRIPTION:
Lacy 068 2315
END DESCRIPTION:
XS GIS Cut Line= 3
      2755374.82      6883766.72      2755542.87      6884096.38
      2755956.60      6884338.52
#Sta/Elev= 30
  4630.9  471.50  4680.6  471.02  4715.2  469.77  4754.1  466.80  4792.8  465.44
  4798.5  464.23  4820.8  463.47  4826.5  462.17  4849.0  460.37  4887.5  459.74
  4927.9  460.17  4935.6  460.50  4983.7  460.91  4993.0  458.37  4998.7  454.72
  4999.0  454.22  5002.5  454.22  5002.7  454.72  5015.2  455.60  5027.7  459.86
  5042.4  461.63  5058.1  462.19  5070.4  463.59  5078.6  464.06  5138.3  464.29
  5196.9  465.58  5212.6  466.81  5218.4  465.88  5386.9  469.28  5480.3  469.88
#Mann=7,-1,0
  4630.9    0.05       0  4927.9     0.1       0  4935.6    0.05       0
  4998.7    0.04       0  5002.7    0.05       0  5070.4     0.1       0
  5078.6    0.05       0
Bank Sta=4998.7,5002.7
Exp/Cntr=0.3,0.1

Type RM Length L Ch R = 1,2452,120,120,120
BEGIN DESCRIPTION:
Lacy 068 2310
END DESCRIPTION:
XS GIS Cut Line= 3
      2755362.50      6883790.66      2755371.55      6884263.67
      2755386.46      6884676.10
#Sta/Elev= 30
  4532.5  471.30  4612.9  469.81  4642.9  467.80  4692.9  466.21  4769.9  462.10
  4842.9  458.59  4862.9  459.58  4965.8  459.03  4972.5  458.04  4980.9  452.24
  4981.2  451.74  4984.7  451.74  4984.9  452.24  4992.9  454.36  5001.8  457.81
  5012.9  458.58  5053.0  459.29  5073.0  461.02  5083.0  460.32  5093.0  461.50
  5123.0  461.75  5153.0  463.06  5163.0  464.19  5183.0  463.37  5243.1  465.54
  5253.1  464.37  5273.1  465.18  5283.1  466.34  5343.1  467.55  5418.3  467.39
#Mann=5,-1,0
  4532.5    0.05       0  4769.9     0.1       0  4965.8    0.05       0
  4980.9    0.04       0  4984.9    0.05       0
Bank Sta=4980.9,4984.9
Exp/Cntr=0.3,0.1

Type RM Length L Ch R = 1,2332,188,188,188
BEGIN DESCRIPTION:
Lacy 068 2306
END DESCRIPTION:
XS GIS Cut Line= 3
      2755241.04      6883898.58      2755251.27      6884262.48
      2755260.66      6884597.31
#Sta/Elev= 30
  4636.9  469.15  4649.3  468.63  4689.3  467.57  4699.3  467.21  4709.3  466.49
  4729.4  465.86  4749.4  464.68  4769.4  462.82  4779.4  462.13  4809.4  460.61
  4869.4  459.21  4969.4  458.11  4979.5  457.14  4987.9  452.00  4990.9  451.67
  4991.2  451.17  4994.7  451.17  4994.9  451.67  5000.9  451.71  5009.5  456.13
  5019.5  457.25  5029.5  457.60  5039.5  458.28  5129.5  461.25  5169.5  462.95
  5189.5  463.37  5239.6  465.38  5289.6  467.06  5309.6  467.68  5335.9  467.96
#Mann=3,-1,0
  4636.9    0.05       0  4990.9    0.05       0  4994.9    0.05       0
Bank Sta=4990.9,4994.9
Exp/Cntr=0.3,0.1

Type RM Length L Ch R = 1,2144,231,231,231
BEGIN DESCRIPTION:
Lacy 068 2307
END DESCRIPTION:
XS GIS Cut Line= 3
      2755088.21      6883908.72      2755077.07      6884306.73
      2755076.79      6884620.16
#Sta/Elev= 30
  4606.6  466.04  4628.9  466.21  4668.9  465.30  4728.9  460.78  4758.9  459.96
  4778.9  460.01  4789.0  459.11  4809.0  458.26  4839.0  458.19  4849.0  458.74
  4859.0  458.01  4909.0  456.86  4929.0  457.02  4939.0  456.63  4959.0  457.09
  4977.0  450.33  4977.3  449.83  4980.8  449.83  4981.0  450.33  4989.0  450.75
  4999.0  455.54  5004.4  456.13  5049.0  457.33  5089.0  459.85  5139.0  460.90
  5149.0  461.60  5169.0  461.58  5209.0  463.09  5269.0  464.69  5318.2  465.12
#Mann=3,-1,0
  4606.6    0.05       0  4977.0    0.04       0  4981.0    0.05       0
Bank Sta=4977,4981
Exp/Cntr=0.3,0.1

Type RM Length L Ch R = 1,1913,233,233,233
BEGIN DESCRIPTION:
Lacy 068 2308
END DESCRIPTION:
XS GIS Cut Line= 3
      2755072.77      6883880.58      2754889.40      6884180.95
      2754686.40      6884565.65
#Sta/Elev= 30
  4651.2  467.17  4677.4  465.76  4757.1  463.08  4897.7  457.22  4932.9  457.24
  4961.9  456.41  4977.4  453.62  4983.2  454.01  5001.6  450.59  5024.3  449.63
  5024.5  449.13  5028.0  449.13  5028.3  449.63  5037.0  454.62  5042.6  452.25
  5048.4  454.45  5059.0  455.56  5064.7  454.63  5071.0  455.33  5086.7  455.01
  5125.1  455.74  5152.8  455.36  5196.8  455.86  5229.3  457.07  5263.2  460.26
  5279.2  460.14  5331.1  461.55  5389.3  463.81  5405.7  465.12  5438.1  465.65
#Mann=3,-1,0
  4651.2    0.05       0  5024.3    0.04       0  5028.3    0.05       0
Bank Sta=5024.3,5028.3
Exp/Cntr=0.3,0.1

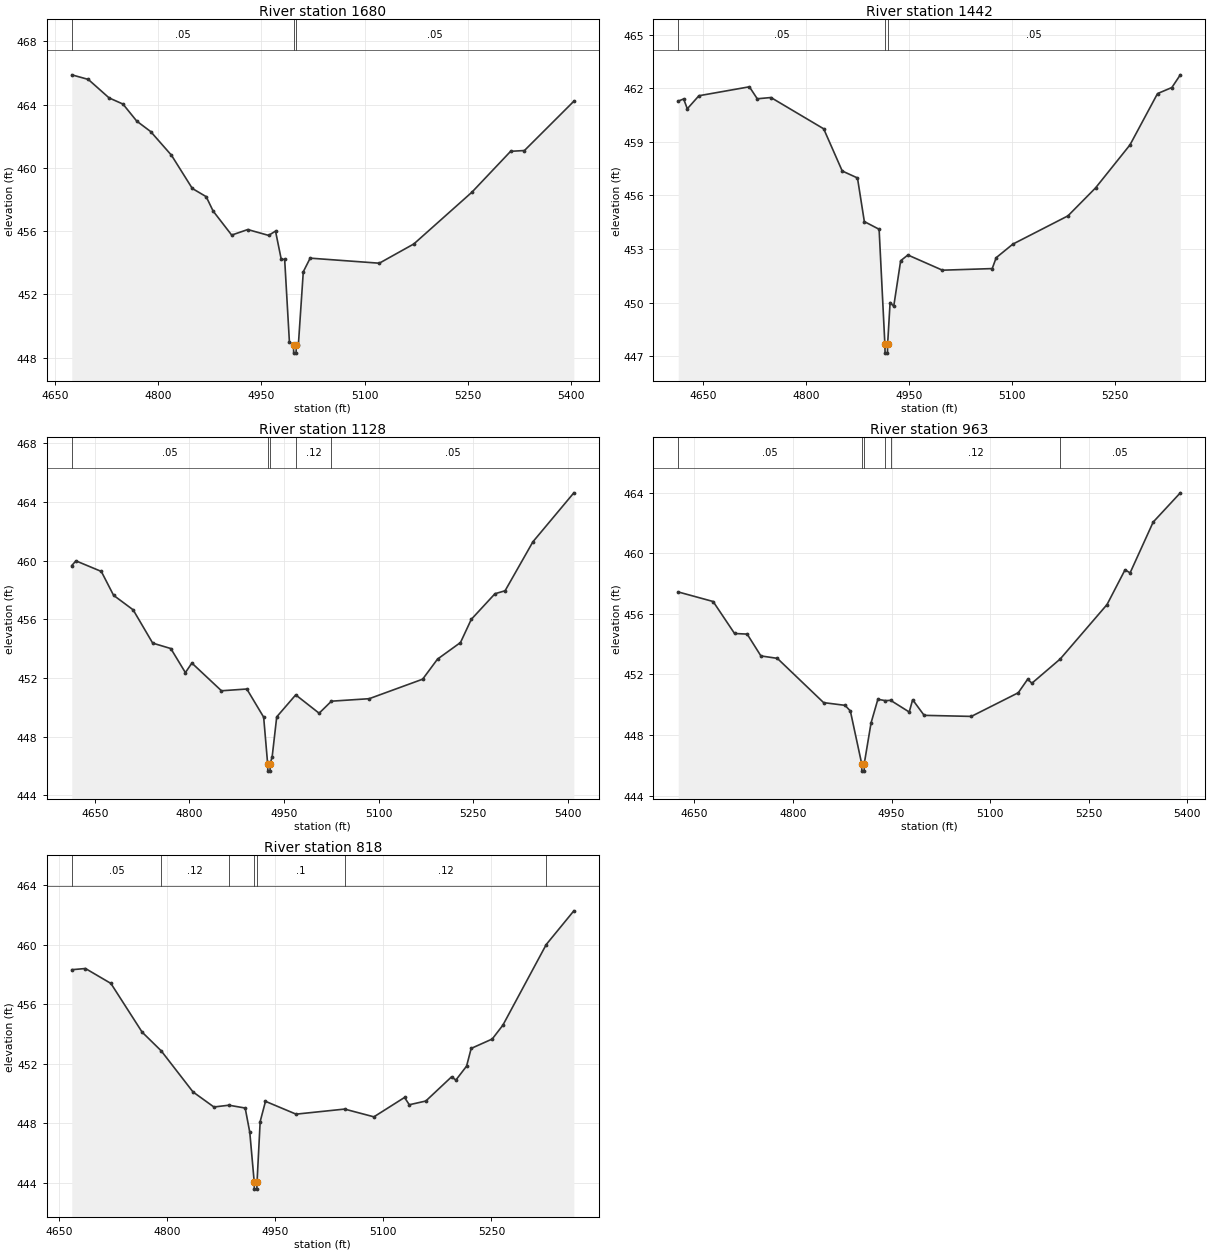
Type RM Length L Ch R = 1,1680,238,238,238
BEGIN DESCRIPTION:
Lacy 068 2309
END DESCRIPTION:
XS GIS Cut Line= 3
      2754722.90      6883787.23      2754678.34      6884111.74
      2754634.87      6884512.44
#Sta/Elev= 30
  4674.0  465.89  4698.0  465.60  4728.3  464.43  4748.5  464.04  4768.6  462.96
  4788.8  462.30  4819.1  460.80  4849.4  458.70  4869.6  458.18  4879.7  457.27
  4906.7  455.75  4930.1  456.10  4960.4  455.73  4970.5  456.00  4978.8  454.22
  4983.8  454.21  4990.7  448.99  4996.7  448.78  4996.9  448.28  5000.4  448.28
  5000.7  448.78  5003.7  448.78  5010.9  453.43  5020.9  454.29  5121.5  453.97
  5171.8  455.19  5256.2  458.46  5312.6  461.05  5332.7  461.10  5404.6  464.22
#Mann=3,-1,0
  4674.0    0.05       0  4996.7    0.04       0  5000.7    0.05       0
Bank Sta=4996.7,5000.7
Exp/Cntr=0.3,0.1

Type RM Length L Ch R = 1,1442,314,314,314
BEGIN DESCRIPTION:
Lacy 068 2305
END DESCRIPTION:
XS GIS Cut Line= 3
      2754584.62      6883742.31      2754467.07      6884111.81
      2754439.68      6884454.07
#Sta/Elev= 30
  4613.7  461.28  4621.6  461.40  4626.9  460.85  4643.8  461.58  4717.3  462.08
  4728.8  461.41  4748.7  461.48  4825.5  459.73  4852.5  457.37  4874.7  456.98
  4884.7  454.54  4906.2  454.11  4914.6  447.68  4914.9  447.18  4918.4  447.18
  4918.6  447.68  4922.2  450.01  4927.5  449.80  4937.6  452.35  4948.1  452.67
  4998.4  451.82  5070.9  451.91  5076.7  452.52  5101.0  453.28  5181.2  454.86
  5221.3  456.42  5271.5  458.83  5311.6  461.70  5332.5  462.04  5344.8  462.75
#Mann=3,-1,0
  4613.7    0.05       0  4914.6    0.04       0  4918.6    0.05       0
Bank Sta=4914.6,4918.6
Exp/Cntr=0.3,0.1

Type RM Length L Ch R = 1,1128,165,165,165
BEGIN DESCRIPTION:
Lacy 068 2304
END DESCRIPTION:
XS GIS Cut Line= 3
      2754070.01      6883786.95      2754169.49      6884161.73
      2754315.74      6884542.77
#Sta/Elev= 30
  4613.5  459.67  4620.1  459.99  4660.3  459.27  4679.8  457.64  4710.8  456.65
  4741.8  454.38  4770.5  454.01  4793.6  452.37  4803.9  453.02  4850.8  451.13
  4891.0  451.25  4917.7  449.33  4924.0  446.15  4924.3  445.65  4927.8  445.65
  4928.0  446.15  4931.2  446.64  4938.4  449.35  4968.5  450.85  5005.6  449.60
  5025.1  450.42  5085.0  450.59  5169.7  451.92  5193.3  453.29  5229.7  454.42
  5246.8  456.00  5284.4  457.75  5300.4  457.95  5344.5  461.29  5409.4  464.63
#Mann=5,-1,0
  4613.5    0.05       0  4924.0    0.07       0  4928.0    0.05       0
  4968.5    0.12       0  5025.1    0.05       0
Bank Sta=4924,4928
Exp/Cntr=0.3,0.1

Type RM Length L Ch R = 1,963,145,145,145
BEGIN DESCRIPTION:
Lacy 068 2303
END DESCRIPTION:
XS GIS Cut Line= 3
      2753926.64      6883890.83      2754038.23      6884250.33
      2754289.27      6884545.62
#Sta/Elev= 30
  4625.3  457.44  4678.4  456.81  4711.0  454.70  4730.2  454.66  4751.1  453.22
  4776.1  453.06  4846.5  450.14  4879.1  449.96  4887.2  449.59  4904.4  446.12
  4904.7  445.62  4908.2  445.62  4908.4  446.12  4918.7  448.80  4929.1  450.36
  4940.4  450.27  4948.5  450.29  4976.8  449.52  4982.0  450.33  4999.5  449.30
  5071.3  449.23  5142.7  450.79  5157.0  451.68  5163.5  451.42  5206.6  453.02
  5277.8  456.61  5305.2  458.90  5312.9  458.70  5348.0  462.05  5389.3  463.98
#Mann=6,-1,0
  4625.3    0.05       0  4904.4    0.07       0  4908.4    0.05       0
  4940.4     0.1       0  4948.5    0.12       0  5206.6    0.05       0
Bank Sta=4904.4,4908.4
Exp/Cntr=0.3,0.1

Type RM Length L Ch R = 1,818,0,0,0
BEGIN DESCRIPTION:
Lacy 068 2323
END DESCRIPTION:
XS GIS Cut Line= 3
      2753731.09      6884088.71      2753935.30      6884351.24
      2754232.04      6884562.57
#Sta/Elev= 30
  4667.4  458.31  4686.4  458.39  4721.7  457.39  4765.1  454.12  4791.5  452.87
  4835.7  450.11  4864.7  449.10  4885.5  449.22  4908.1  449.03  4914.5  447.40
  4920.6  444.09  4920.8  443.59  4924.3  443.59  4924.6  444.09  4928.9  448.12
  4936.3  449.48  4978.7  448.62  5046.1  448.96  5086.8  448.44  5129.3  449.74
  5135.9  449.25  5158.8  449.50  5194.5  451.12  5200.6  450.91  5215.4  451.84
  5221.8  453.03  5251.0  453.66  5265.8  454.59  5326.0  460.00  5364.3  462.26
#Mann=7,-1,0
  4667.4    0.05       0  4791.5    0.12       0  4885.5     0.1       0
  4920.6    0.07       0  4924.6     0.1       0  5046.1    0.12       0
  5326.0    0.05       0
Bank Sta=4920.6,4924.6
Exp/Cntr=0.3,0.1

Chan Stop Cuts=-1