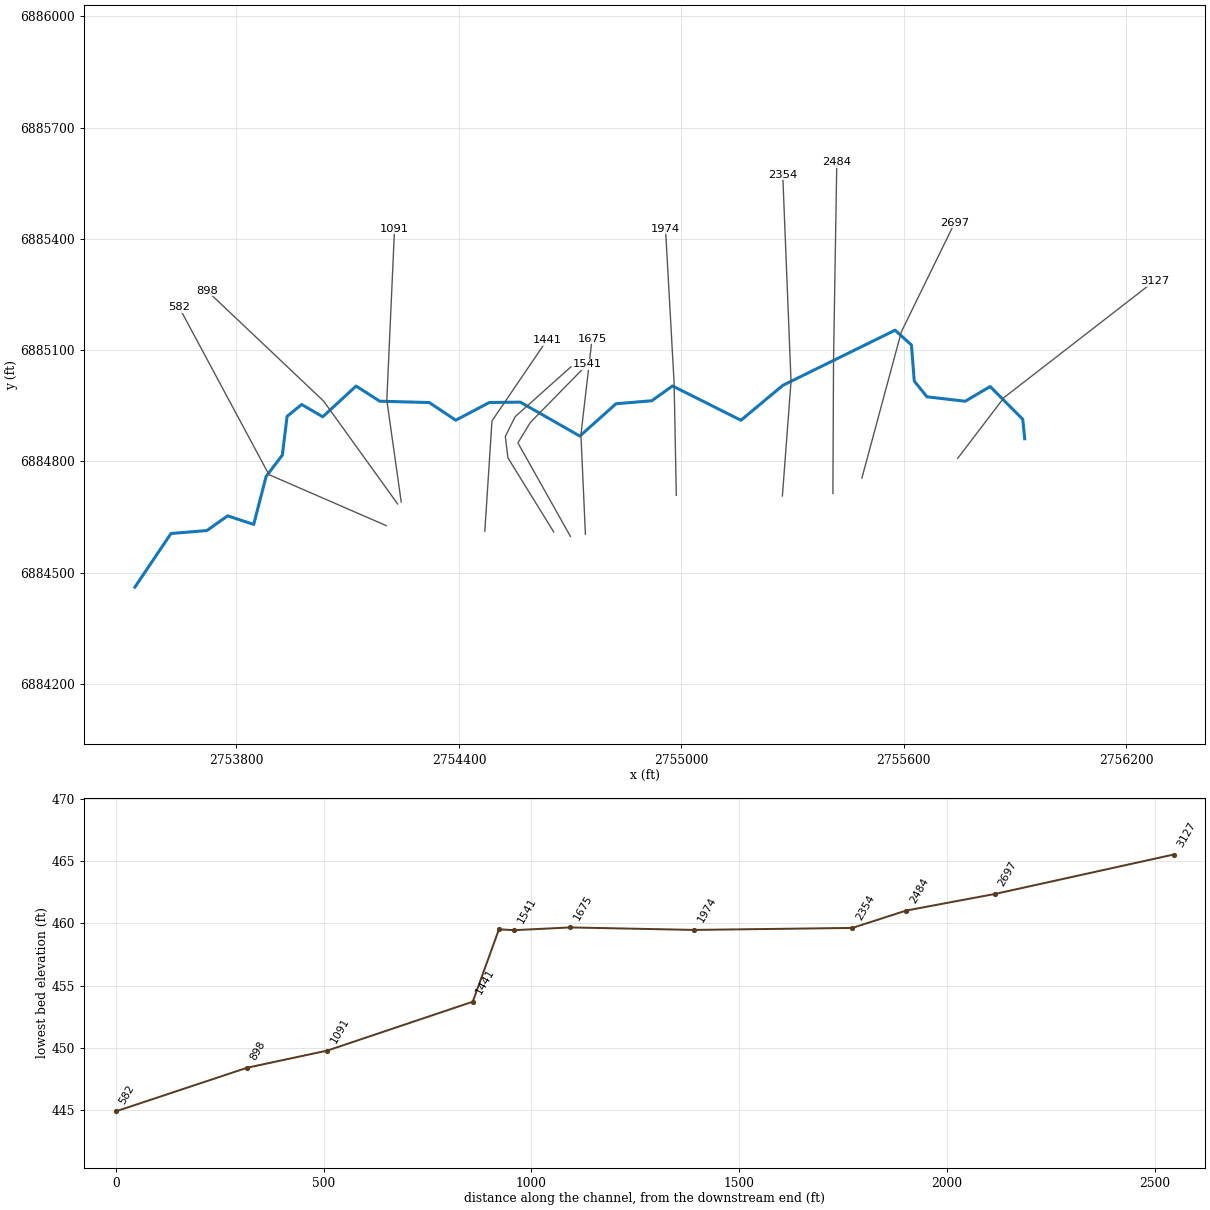
--- Lacy 069.prj (project) ---

Proj Title=Lacy 069 Base Level Engineering
Current Plan=p01
Default Exp/Contr=0.3,0.1
English Units
Geom File=g01
Flow File=f01
Plan File=p01
BEGIN DESCRIPTION:
Lacy 069
END DESCRIPTION:

--- Lacy 069.p01 (plan) ---

Plan Title=Multiple Run
Short Identifier=Multiple
Geom File=g01
Flow File=f01
Subcritical Flow
K Sum by GR= 0
Std Step Tol= 0.01
Critical Tol= 0.01
Num of Std Step Trials= 20
Max Error Tol= 0.3
Flow Tol Ratio= 0.001
Split Flow NTrial= 30
Split Flow Tol= 0.02
Split Flow Ratio= 0.02
Log Output Level= 0
Friction Slope Method= 1
Unsteady Friction Slope Method= 2
Unsteady Bridges Friction Slope Method= 1
Parabolic Critical Depth
Global Vel Dist=  1 , 1 , 1
Global Log Level= 0
CheckData=True
Encroach Param= -1, 0, 0, 0
BEGIN DESCRIPTION:
Multiple Run
END DESCRIPTION:

--- Lacy 069.f01 (steady flow) ---

Flow Title=Multiple
Number of Profiles=7
Profile Names=10-year,25-year,50-year,1pct_min,100-year,1pct_plu,500-year
River Rch & RM= Lacy 069,Reach-1,3127
     279     357     418     244     486     970     659
Boundary for River Rch & Prof#=Lacy 069,Reach-1,1
Up Type=0
Dn Type=3
Dn Slope=0.005
Boundary for River Rch & Prof#=Lacy 069,Reach-1,2
Up Type=0
Dn Type=3
Dn Slope=0.005
Boundary for River Rch & Prof#=Lacy 069,Reach-1,3
Up Type=0
Dn Type=3
Dn Slope=0.005
Boundary for River Rch & Prof#=Lacy 069,Reach-1,4
Up Type=0
Dn Type=3
Dn Slope=0.005
Boundary for River Rch & Prof#=Lacy 069,Reach-1,5
Up Type=0
Dn Type=3
Dn Slope=0.005
Boundary for River Rch & Prof#=Lacy 069,Reach-1,6
Up Type=0
Dn Type=3
Dn Slope=0.005
Boundary for River Rch & Prof#=Lacy 069,Reach-1,7
Up Type=0
Dn Type=3
Dn Slope=0.005

--- Lacy 069.g01 (geometry) ---

Geom Title=Existing Conditions

River Reach=Lacy 069,Reach-1
Reach XY= 30
      2755926.00      6884861.00      2755920.69      6884913.56
      2755832.75      6885001.90      2755765.51      6884962.27
      2755662.28      6884974.17      2755628.07      6885016.69
      2755620.48      6885113.98      2755576.33      6885153.81
      2755273.71      6885005.15      2755160.66      6884910.95
      2754976.01      6885003.47      2754920.10      6884963.56
      2754823.57      6884955.45      2754726.08      6884868.30
      2754565.46      6884959.91      2754481.97      6884958.81
      2754391.39      6884911.09      2754320.07      6884958.70
      2754186.44      6884962.40      2754122.58      6885003.18
      2754032.66      6884920.34      2753975.76      6884953.54
      2753936.52      6884921.49      2753923.64      6884816.98
      2753879.86      6884759.40      2753846.48      6884630.17
      2753776.11      6884653.19      2753720.11      6884613.55
      2753623.32      6884605.59      2753526.00      6884461.00

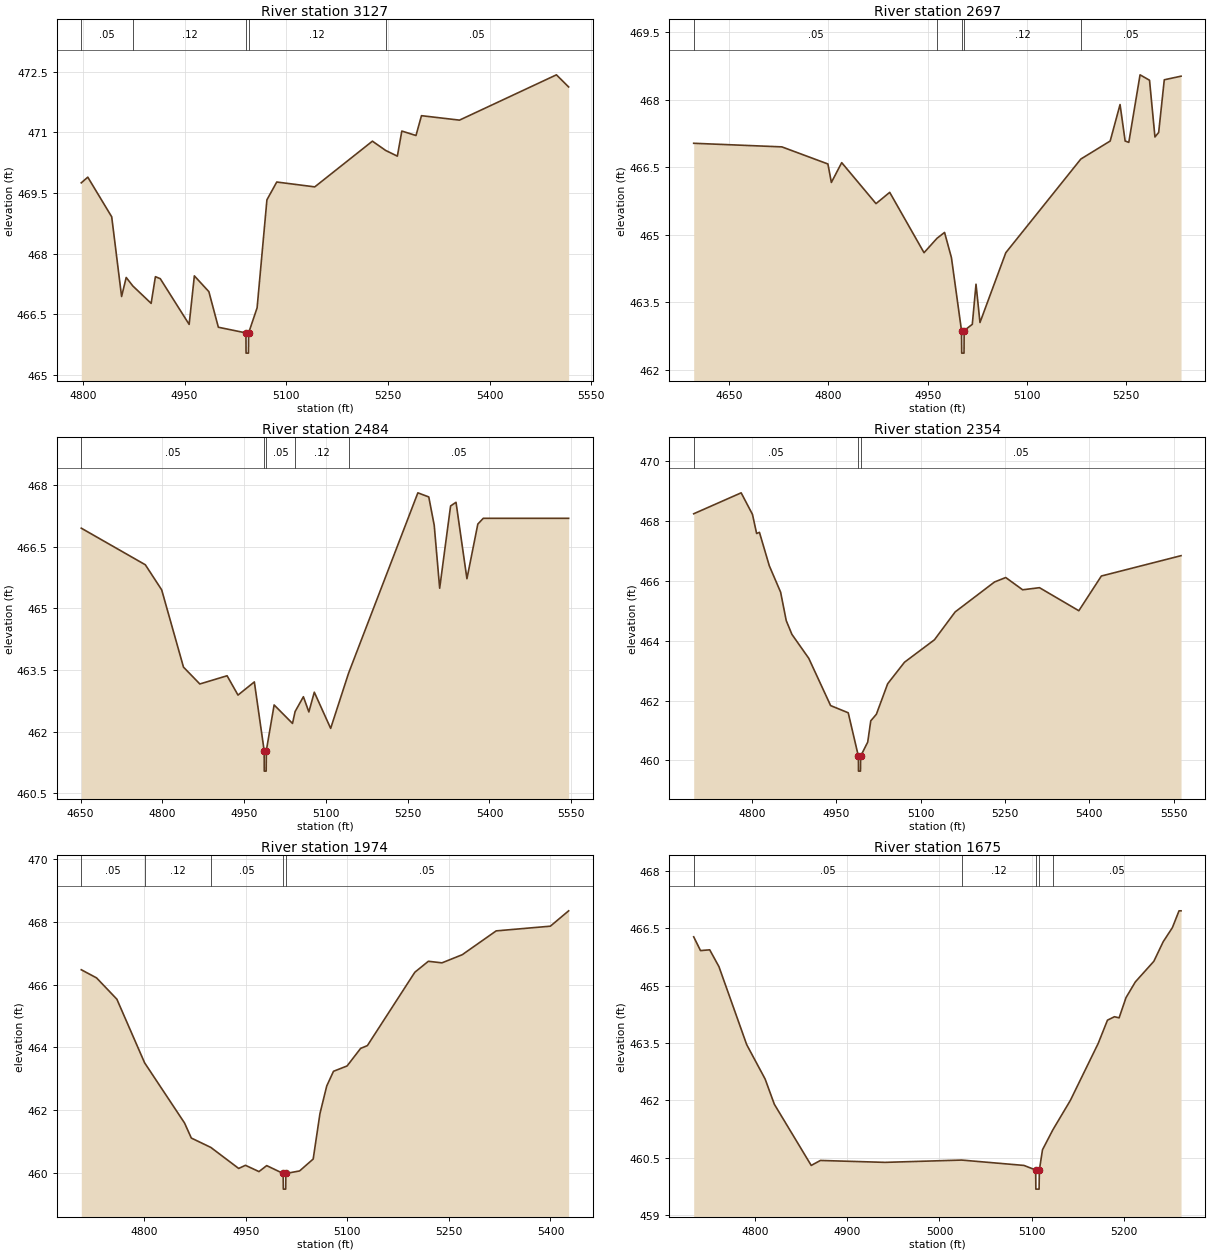
Type RM Length L Ch R = 1,3127,430,430,430
BEGIN DESCRIPTION:
Lacy 069 2338
END DESCRIPTION:
XS GIS Cut Line= 3
      2755745.25      6884808.31      2755870.38      6884972.43
      2756275.87      6885286.55
#Sta/Elev= 30
  4797.5  469.75  4807.1  469.89  4842.4  468.91  4857.0  466.94  4863.8  467.41
  4873.6  467.20  4900.6  466.77  4906.9  467.43  4914.1  467.38  4956.7  466.25
  4964.4  467.45  4985.8  467.06  4999.8  466.18  5040.5  466.04  5040.7  465.54
  5044.2  465.54  5044.5  466.04  5057.0  466.66  5071.5  469.33  5086.0  469.77
  5142.1  469.65  5227.2  470.78  5246.8  470.55  5264.0  470.41  5270.6  471.03
  5291.5  470.92  5299.6  471.41  5355.7  471.30  5498.8  472.42  5516.8  472.12
#Mann=5,-1,0
  4797.5    0.05       0  4873.6    0.12       0  5040.5    0.07       0
  5044.5    0.12       0  5246.8    0.05       0
Bank Sta=5040.5,5044.5
Exp/Cntr=0.3,0.1

Type RM Length L Ch R = 1,2697,213,213,213
BEGIN DESCRIPTION:
Lacy 069 2337
END DESCRIPTION:
XS GIS Cut Line= 3
      2755486.87      6884755.24      2755593.20      6885149.26
      2755737.17      6885443.73
#Sta/Elev= 30
  4596.7  467.03  4729.9  466.95  4799.4  466.57  4804.6  466.16  4820.2  466.60
  4872.0  465.69  4892.7  465.94  4944.5  464.60  4964.1  464.92  4975.5  465.05
  4985.9  464.49  5001.1  462.87  5001.4  462.37  5004.9  462.37  5005.1  462.87
  5017.4  463.01  5023.0  463.90  5029.0  463.05  5068.0  464.60  5181.3  466.68
  5225.6  467.08  5240.5  467.89  5248.2  467.08  5253.7  467.05  5270.7  468.55
  5285.0  468.43  5293.2  467.17  5298.8  467.27  5307.3  468.44  5332.6  468.52
#Mann=5,-1,0
  4596.7    0.05       0  4964.1    0.12       0  5001.1    0.07       0
  5005.1    0.12       0  5181.3    0.05       0
Bank Sta=5001.1,5005.1
Exp/Cntr=0.3,0.1

Type RM Length L Ch R = 1,2484,130,130,130
BEGIN DESCRIPTION:
Lacy 069 2336
END DESCRIPTION:
XS GIS Cut Line= 3
      2755408.67      6884713.52      2755410.30      6885068.61
      2755419.14      6885607.55
#Sta/Elev= 30
  4651.2  466.95  4768.7  466.06  4798.7  465.45  4838.7  463.57  4868.7  463.16
  4918.7  463.36  4938.7  462.89  4968.7  463.21  4986.7  461.54  4986.9  461.04
  4990.4  461.04  4990.7  461.54  5005.0  462.65  5038.7  462.20  5043.5  462.49
  5058.7  462.85  5068.7  462.48  5078.7  462.96  5108.7  462.08  5141.5  463.42
  5268.7  467.81  5288.7  467.71  5298.7  467.02  5308.7  465.49  5328.7  467.49
  5338.7  467.58  5358.7  465.72  5378.7  467.05  5388.7  467.19  5545.3  467.19
#Mann=5,-1,0
  4651.2    0.05       0  4986.7    0.04       0  4990.7    0.05       0
  5043.5    0.12       0  5141.5    0.05       0
Bank Sta=4986.7,4990.7
Exp/Cntr=0.3,0.1

Type RM Length L Ch R = 1,2354,380,380,380
BEGIN DESCRIPTION:
Lacy 069 2335
END DESCRIPTION:
XS GIS Cut Line= 3
      2755272.39      6884706.74      2755295.69      6885015.60
      2755273.35      6885572.72
#Sta/Elev= 30
  4696.0  468.24  4780.5  468.94  4800.6  468.22  4808.0  467.58  4813.0  467.62
  4830.6  466.50  4850.7  465.62  4860.7  464.67  4870.8  464.21  4900.8  463.41
  4939.7  461.83  4971.0  461.59  4989.1  460.14  4989.3  459.64  4992.8  459.64
  4993.1  460.14  5005.7  460.61  5011.1  461.32  5021.1  461.54  5041.2  462.56
  5071.2  463.28  5124.5  464.03  5161.3  464.96  5231.3  465.96  5251.3  466.11
  5281.4  465.70  5311.4  465.77  5381.4  465.00  5421.5  466.16  5563.3  466.84
#Mann=3,-1,0
  4696.0    0.05       0  4989.1    0.05       0  4993.1    0.05       0
Bank Sta=4989.1,4993.1
Exp/Cntr=0.3,0.1

Type RM Length L Ch R = 1,1974,299,299,299
BEGIN DESCRIPTION:
Lacy 069 2341
END DESCRIPTION:
XS GIS Cut Line= 3
      2754986.26      6884708.45      2754980.36      6885011.40
      2754957.10      6885427.94
#Sta/Elev= 30
  4706.7  466.48  4729.3  466.22  4759.3  465.54  4800.3  463.51  4859.3  461.59
  4869.3  461.11  4898.2  460.81  4939.3  460.14  4949.3  460.24  4969.3  460.04
  4980.7  460.23  5005.0  459.98  5005.3  459.48  5008.8  459.48  5009.0  459.98
  5029.3  460.06  5049.4  460.44  5059.4  461.89  5069.4  462.77  5079.4  463.24
  5099.5  463.41  5119.5  463.97  5129.5  464.06  5199.6  466.40  5219.6  466.75
  5239.7  466.70  5269.7  466.96  5319.8  467.72  5399.9  467.87  5426.9  468.36
#Mann=5,-1,0
  4706.7    0.05       0  4800.3    0.12       0  4898.2    0.05       0
  5005.0    0.04       0  5009.0    0.05       0
Bank Sta=5005,5009
Exp/Cntr=0.3,0.1

Type RM Length L Ch R = 1,1675,134,134,134
BEGIN DESCRIPTION:
Lacy 069 2333
END DESCRIPTION:
XS GIS Cut Line= 3
      2754741.11      6884603.61      2754729.00      6884872.21
      2754759.06      6885130.29
#Sta/Elev= 30
  4733.4  466.28  4740.8  465.92  4750.8  465.94  4760.8  465.50  4790.9  463.46
  4810.9  462.56  4820.9  461.90  4860.9  460.30  4870.9  460.43  4941.0  460.38
  5024.1  460.44  5091.7  460.30  5104.4  460.18  5104.6  459.68  5108.1  459.68
  5108.4  460.18  5111.8  460.71  5123.0  461.23  5142.0  462.00  5172.2  463.49
  5182.3  464.10  5189.9  464.19  5194.9  464.16  5202.4  464.69  5212.5  465.10
  5232.6  465.64  5242.7  466.15  5252.7  466.52  5259.9  466.96  5262.1  466.96
#Mann=5,-1,0
  4733.4    0.05       0  5024.1    0.12       0  5104.4    0.03       0
  5108.4    0.12       0  5123.0    0.05       0
Bank Sta=5104.4,5108.4
Exp/Cntr=0.3,0.1

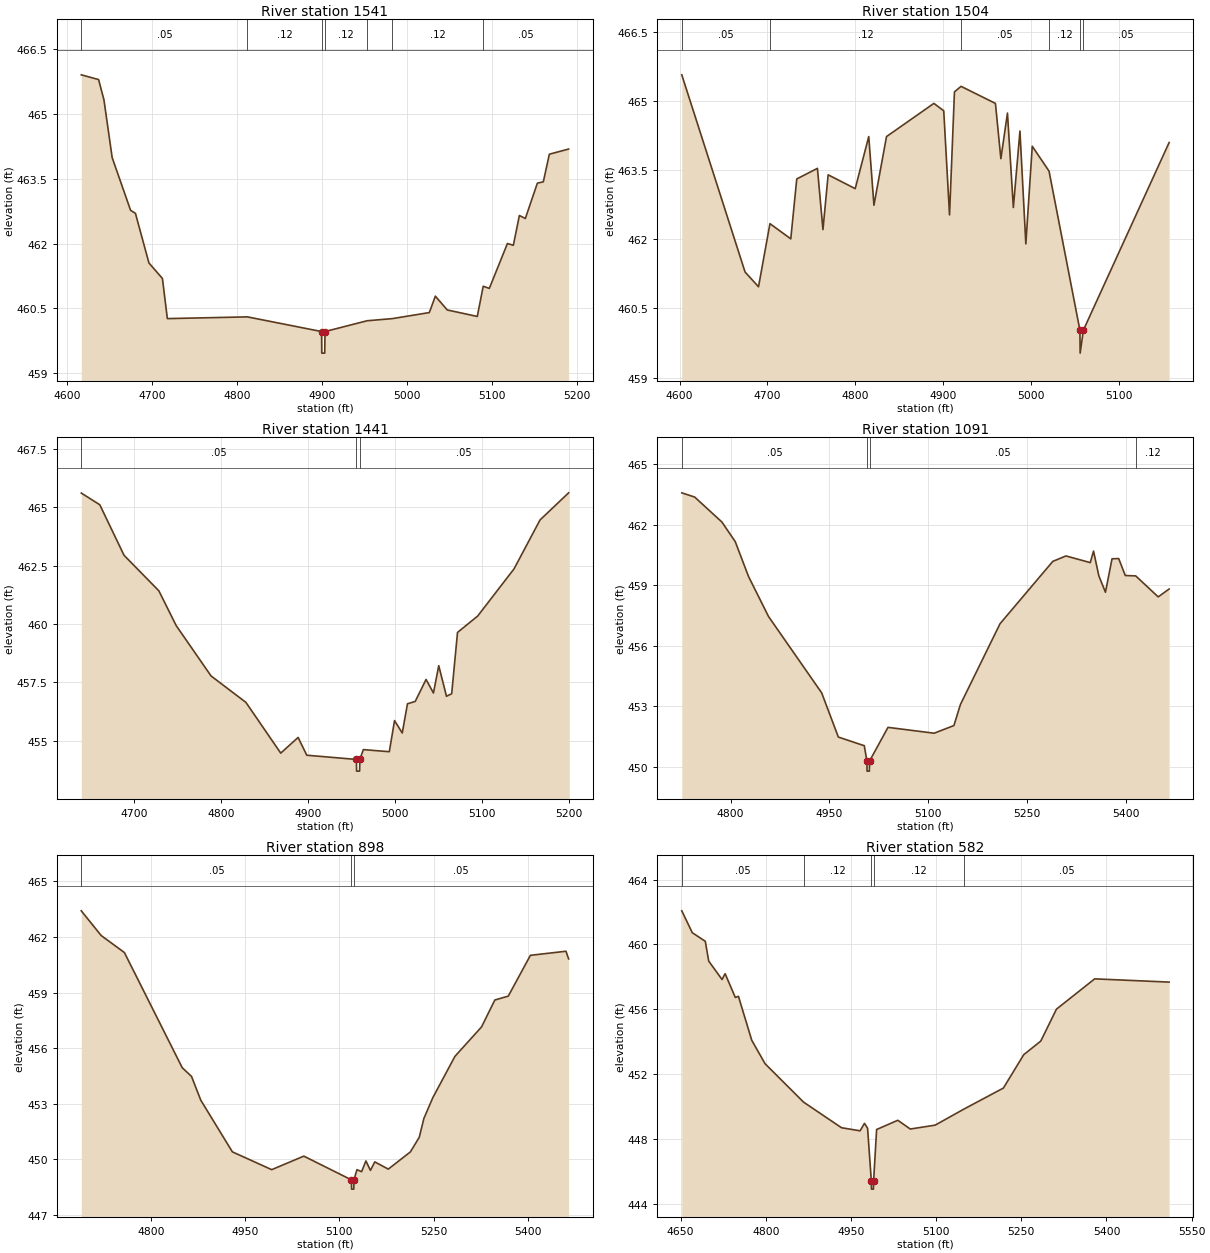
Type RM Length L Ch R = 1,1541,37,37,37
BEGIN DESCRIPTION:
Lacy 069 2334
END DESCRIPTION:
XS GIS Cut Line= 4
      2754700.73      6884597.68      2754559.05      6884849.94
      2754592.64      6884905.19      2754746.75      6885062.35
#Sta/Elev= 30
  4616.6  465.91  4637.0  465.80  4643.3  465.33  4653.0  463.99  4674.7  462.77
  4680.4  462.70  4696.3  461.55  4712.2  461.19  4718.0  460.26  4812.3  460.30
  4899.7  459.96  4899.9  459.46  4903.4  459.46  4903.7  459.96  4953.3  460.21
  4983.1  460.26  5026.6  460.40  5033.7  460.78  5047.8  460.46  5083.1  460.31
  5090.1  461.01  5097.3  460.96  5118.6  462.00  5125.6  461.96  5132.7  462.65
  5139.7  462.58  5153.9  463.40  5160.9  463.43  5168.0  464.07  5190.7  464.19
#Mann=7,-1,0
  4616.6    0.05       0  4812.3    0.12       0  4899.7    0.07       0
  4903.7    0.12       0  4953.3    0.05       0  4983.1    0.12       0
  5090.1    0.05       0
Bank Sta=4899.7,4903.7
Exp/Cntr=0.3,0.1

Type RM Length L Ch R = 1,1504,63,63,63
BEGIN DESCRIPTION:
Lacy 069 2332
END DESCRIPTION:
XS GIS Cut Line= 5
      2754655.74      6884609.76      2754532.08      6884809.69
      2754525.09      6884867.26      2754551.74      6884920.69
      2754702.09      6885055.02
#Sta/Elev= 30
  4602.6  465.57  4674.6  461.29  4689.9  460.97  4702.9  462.34  4726.6  462.01
  4733.4  463.31  4756.9  463.54  4763.2  462.21  4769.1  463.40  4799.9  463.10
  4815.3  464.23  4821.2  462.74  4835.5  464.23  4889.4  464.95  4900.6  464.79
  4907.2  462.53  4912.8  465.20  4920.3  465.32  4959.4  464.95  4965.6  463.75
  4973.1  464.74  4979.8  462.69  4987.3  464.35  4994.0  461.90  5001.3  464.02
  5020.4  463.48  5055.5  460.03  5055.8  459.53  5059.5  460.03  5157.0  464.10
#Mann=6,-1,0
  4602.6    0.05       0  4702.9    0.12       0  4920.3    0.05       0
  5020.4    0.12       0  5055.5    0.04       0  5059.5    0.05       0
Bank Sta=5055.5,5059.5
Exp/Cntr=0.3,0.1

Type RM Length L Ch R = 1,1441,350,350,350
BEGIN DESCRIPTION:
Lacy 069 2331
END DESCRIPTION:
XS GIS Cut Line= 3
      2754469.80      6884611.91      2754489.13      6884909.27
      2754637.13      6885126.69
#Sta/Elev= 30
  4638.9  465.60  4660.2  465.10  4688.1  462.94  4728.2  461.42  4748.2  459.93
  4788.3  457.78  4828.4  456.65  4868.5  454.48  4888.5  455.15  4898.5  454.39
  4955.6  454.21  4955.8  453.71  4959.3  453.71  4959.6  454.21  4963.6  454.63
  4993.5  454.54  4999.5  455.87  5008.4  455.34  5014.4  456.59  5023.3  456.69
  5035.8  457.63  5044.3  457.05  5050.4  458.22  5059.3  456.91  5065.3  457.02
  5072.0  459.64  5095.2  460.34  5137.1  462.36  5167.0  464.45  5199.9  465.61
#Mann=3,-1,0
  4638.9    0.05       0  4955.6    0.04       0  4959.6    0.05       0
Bank Sta=4955.6,4959.6
Exp/Cntr=0.3,0.1

Type RM Length L Ch R = 1,1091,193,193,193
BEGIN DESCRIPTION:
Lacy 069 2330
END DESCRIPTION:
XS GIS Cut Line= 3
      2754244.29      6884690.56      2754205.49      6884965.07
      2754226.30      6885427.56
#Sta/Elev= 30
  4726.0  463.58  4745.6  463.37  4787.0  462.13  4807.2  461.16  4827.4  459.43
  4857.7  457.45  4938.5  453.66  4963.8  451.47  5003.2  451.04  5007.2  450.28
  5007.4  449.78  5010.9  449.78  5011.2  450.28  5039.2  451.95  5109.3  451.66
  5139.3  452.04  5149.3  453.09  5209.4  457.09  5289.5  460.18  5309.5  460.45
  5346.4  460.12  5351.4  460.69  5359.5  459.46  5369.5  458.65  5379.5  460.31
  5389.6  460.32  5399.6  459.48  5415.5  459.46  5449.6  458.42  5466.2  458.81
#Mann=4,-1,0
  4726.0    0.05       0  5007.2    0.04       0  5011.2    0.05       0
  5415.5    0.12       0
Bank Sta=5007.2,5011.2
Exp/Cntr=0.3,0.1

Type RM Length L Ch R = 1,898,316,316,316
BEGIN DESCRIPTION:
Lacy 069 2329
END DESCRIPTION:
XS GIS Cut Line= 3
      2754234.64      6884685.35      2754035.06      6884962.58
      2753719.99      6885260.76
#Sta/Elev= 30
  4689.3  463.41  4720.9  462.08  4757.9  461.16  4849.9  454.95  4864.7  454.48
  4879.4  453.20  4929.7  450.41  4992.3  449.45  5043.4  450.18  5119.1  448.90
  5119.4  448.40  5122.9  448.40  5123.1  448.90  5128.0  449.45  5135.3  449.34
  5142.2  449.92  5149.4  449.41  5156.3  449.87  5177.8  449.48  5213.0  450.41
  5227.1  451.20  5234.4  452.21  5248.6  453.33  5283.8  455.56  5326.2  457.15
  5347.3  458.60  5368.7  458.81  5403.9  461.01  5460.5  461.23  5464.7  460.82
#Mann=3,-1,0
  4689.3    0.05       0  5119.1    0.04       0  5123.1    0.05       0
Bank Sta=5119.1,5123.1
Exp/Cntr=0.3,0.1

Type RM Length L Ch R = 1,582,0,0,0
BEGIN DESCRIPTION:
Lacy 069 2328
END DESCRIPTION:
XS GIS Cut Line= 3
      2754203.95      6884626.85      2753887.55      6884764.35
      2753644.85      6885216.55
#Sta/Elev= 30
  4652.1  462.07  4670.6  460.72  4693.5  460.19  4699.5  458.97  4723.0  457.83
  4728.4  458.19  4746.4  456.72  4751.9  456.79  4775.3  454.08  4798.8  452.63
  4866.6  450.26  4933.4  448.68  4966.1  448.49  4973.8  448.95  4979.3  448.65
  4985.9  445.39  4986.1  444.89  4989.6  444.89  4989.9  445.39  4995.2  448.57
  5032.5  449.14  5054.5  448.60  5098.3  448.84  5148.4  449.82  5218.5  451.13
  5254.3  453.19  5284.3  454.03  5311.9  456.00  5379.2  457.87  5510.3  457.67
#Mann=5,-1,0
  4652.1    0.05       0  4866.6    0.12       0  4985.9    0.07       0
  4989.9    0.12       0  5148.4    0.05       0
Bank Sta=4985.9,4989.9
Exp/Cntr=0.3,0.1

Chan Stop Cuts=-1