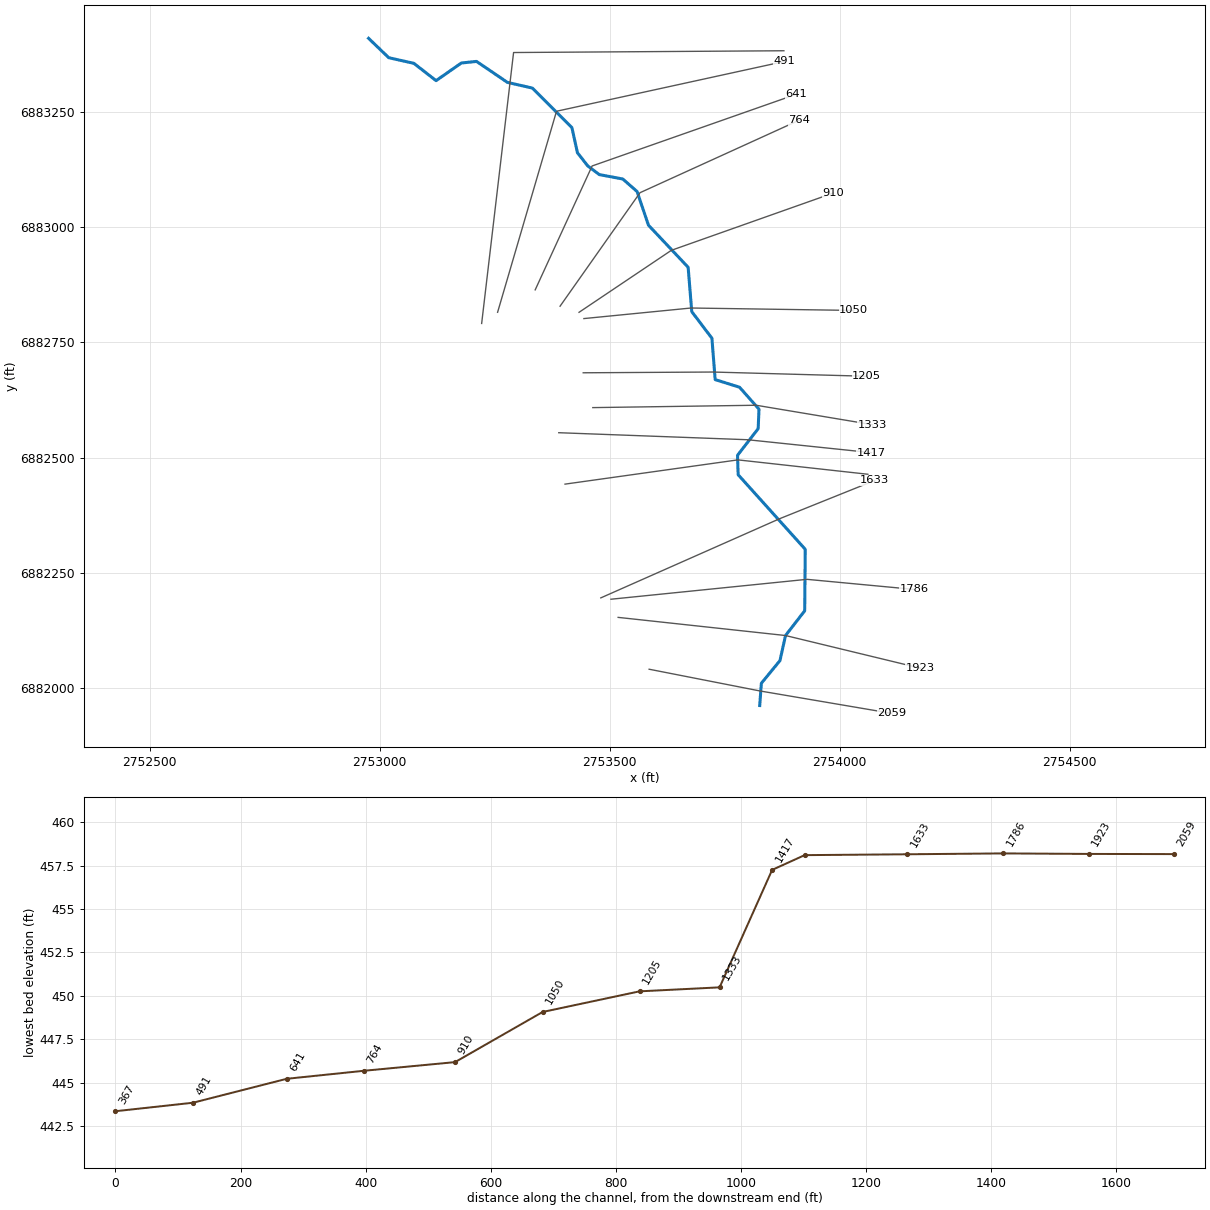
--- Lacy 070.prj (project) ---

Proj Title=Lacy 070 Base Level Engineering
Current Plan=p01
Default Exp/Contr=0.3,0.1
English Units
Geom File=g01
Flow File=f01
Plan File=p01
Y Axis Title=Elevation
X Axis Title(PF)=Main Channel Distance
X Axis Title(XS)=Station
BEGIN DESCRIPTION:
Lacy 070
END DESCRIPTION:
DSS Export Rating Curves= 0
DSS Export Rating Curve Sorted= 0
DSS Export Volume Flow Curves= 0
DXF OffsetX= 0
DXF OffsetY= 0
DXF ScaleX= 1
DXF ScaleY= 10

--- Lacy 070.p01 (plan) ---

Plan Title=Multiple Run
Short Identifier=Multiple
Geom File=g01
Flow File=f01
Subcritical Flow
K Sum by GR= 0
Std Step Tol= 0.01
Critical Tol= 0.01
Num of Std Step Trials= 20
Max Error Tol= 0.3
Flow Tol Ratio= 0.001
Split Flow NTrial= 30
Split Flow Tol= 0.02
Split Flow Ratio= 0.02
Log Output Level= 0
Friction Slope Method= 1
Unsteady Friction Slope Method= 2
Unsteady Bridges Friction Slope Method= 1
Parabolic Critical Depth
Global Vel Dist=  1 , 1 , 1
Global Log Level= 0
CheckData=True
Encroach Param= -1, 0, 0, 0
BEGIN DESCRIPTION:
Multiple Run
END DESCRIPTION:

--- Lacy 070.f01 (steady flow) ---

Flow Title=Multiple
Number of Profiles=7
Profile Names=10-year,25-year,50-year,1pct_min,100-year,1pct_plu,500-year
River Rch & RM= Lacy 070,Reach-1,2059
     144     177     202     115     229     457     295
Boundary for River Rch & Prof#=Lacy 070,Reach-1,1
Up Type=0
Dn Type=3
Dn Slope=0.005
Boundary for River Rch & Prof#=Lacy 070,Reach-1,2
Up Type=0
Dn Type=3
Dn Slope=0.005
Boundary for River Rch & Prof#=Lacy 070,Reach-1,3
Up Type=0
Dn Type=3
Dn Slope=0.005
Boundary for River Rch & Prof#=Lacy 070,Reach-1,4
Up Type=0
Dn Type=3
Dn Slope=0.005
Boundary for River Rch & Prof#=Lacy 070,Reach-1,5
Up Type=0
Dn Type=3
Dn Slope=0.005
Boundary for River Rch & Prof#=Lacy 070,Reach-1,6
Up Type=0
Dn Type=3
Dn Slope=0.005
Boundary for River Rch & Prof#=Lacy 070,Reach-1,7
Up Type=0
Dn Type=3
Dn Slope=0.005

--- Lacy 070.g01 (geometry) ---

Geom Title=Existing Conditions
Program Version=4.10

River Reach=Lacy 070        ,Reach-1
Reach XY= 30
        2753826.        6881961.       2753829.6      6882009.51
      2753870.05      6882058.75      2753882.11      6882113.19
      2753923.77      6882166.93      2753924.96      6882300.56
      2753779.13      6882462.64      2753777.81      6882504.88
      2753822.64      6882562.76      2753824.43      6882605.14
      2753782.08      6882652.82      2753729.19      6882669.35
      2753722.11      6882759.33      2753678.36      6882816.97
      2753670.46      6882913.42      2753584.19      6883004.98
       2753559.5      6883078.05      2753528.51      6883105.24
      2753477.46       6883114.9      2753452.17      6883133.86
      2753429.89      6883162.43      2753417.84      6883217.05
      2753332.07      6883302.87      2753277.74      6883315.25
      2753210.59      6883360.86      2753177.64       6883357.4
      2753122.69      6883319.05      2753074.42      6883356.67
      2753019.86      6883368.88        2752976.        6883411.

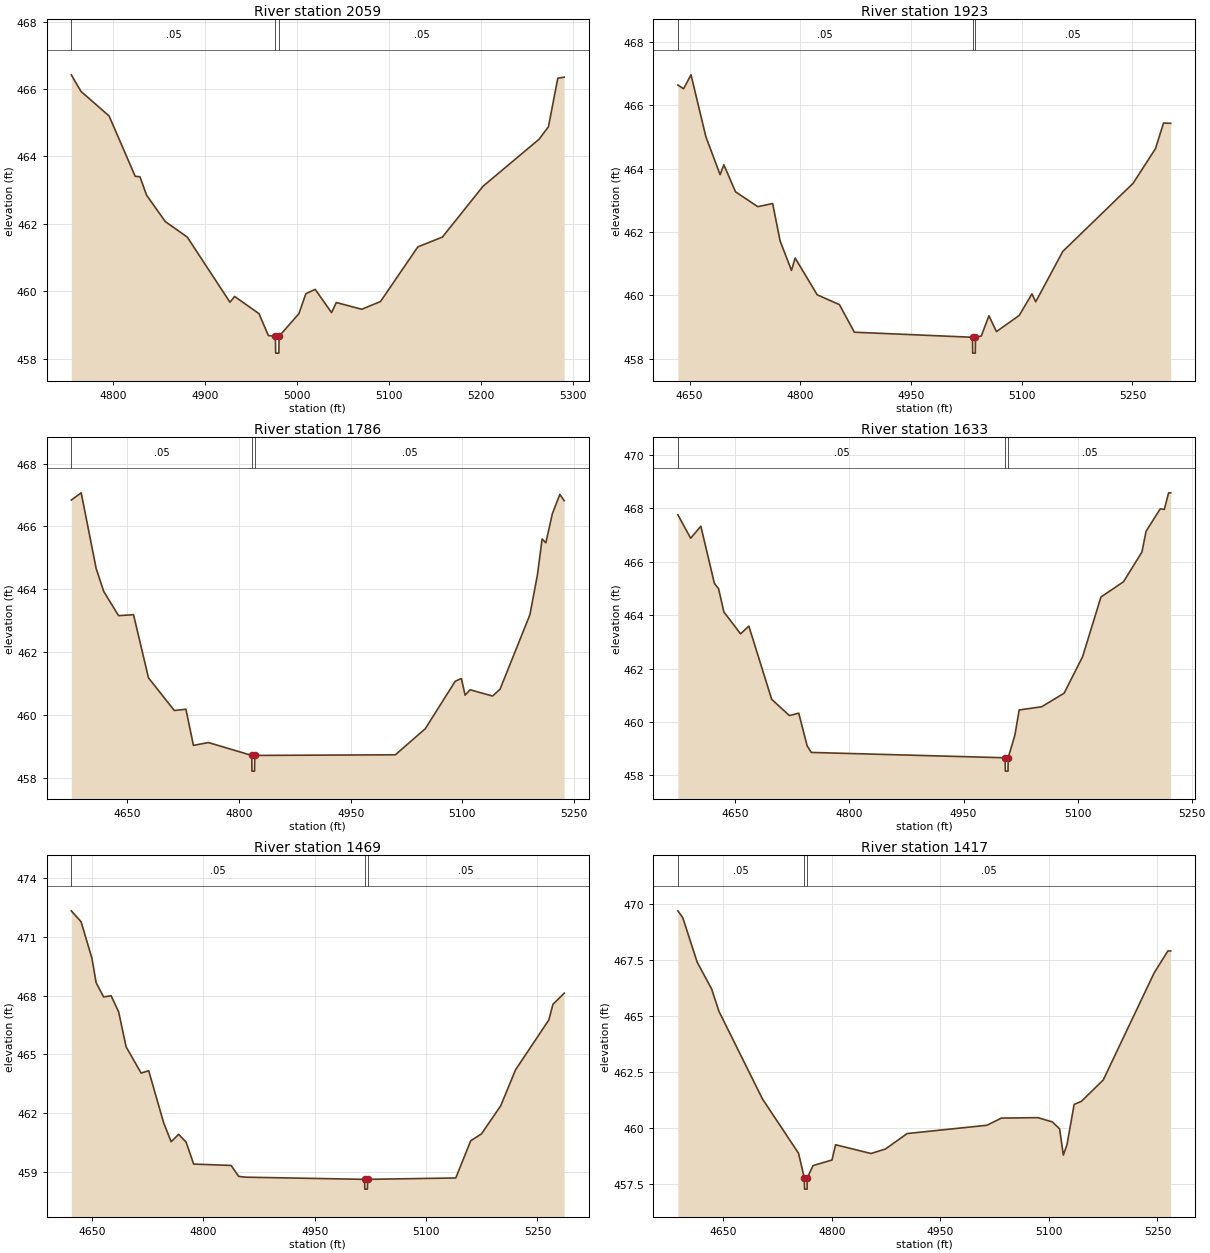
Type RM Length L Ch R = 1 ,2059    ,136,136,136
BEGIN DESCRIPTION:
Lacy 070 2302
END DESCRIPTION:
XS GIS Cut Line= 3
      2753585.68      6882039.96       2753826.1      6881992.81
      2754112.88      6881944.01
#Sta/Elev= 30
    4755  466.42  4765.5  465.93  4796.1   465.2  4824.5  463.41  4829.6   463.4
  4836.9  462.85  4857.2  462.07  4881.1  461.61  4927.5  459.68  4932.6  459.85
  4959.1  459.34  4969.3  458.69  4976.9  458.67  4977.2  458.17  4980.7  458.17
  4980.9  458.67  5002.5  459.34    5010  459.93  5020.2  460.06    5038  459.37
  5043.1  459.67  5070.9  459.47  5091.2   459.7  5131.8  461.32  5158.5  461.61
  5202.8  463.12  5263.6  464.51  5273.8  464.88    5284  466.32  5290.9  466.35
#Mann= 3 ,-1 , 0
    4755     .05       0  4976.9     .04       0  4980.9     .05       0
Bank Sta=4976.9,4980.9
XS Rating Curve= 0 ,0
Exp/Cntr=0.3,0.1

Type RM Length L Ch R = 1 ,1923    ,137,137,137
BEGIN DESCRIPTION:
Lacy 070 2301
END DESCRIPTION:
XS GIS Cut Line= 3
      2753518.34      6882152.63      2753882.11      6882113.19
      2754175.43      6882042.15
#Sta/Elev= 30
  4634.1  466.64  4641.8  466.52  4651.9  466.96    4672  465.01  4691.3  463.81
  4696.4  464.12  4712.2  463.27  4742.4   462.8  4762.5   462.9  4772.6  461.72
    4788  460.79    4793  461.18  4822.9  460.02    4853  459.71  4873.2  458.84
  5033.3  458.68  5033.5  458.18    5037  458.18  5037.3  458.68  5045.2  458.72
  5055.5  459.36  5065.7  458.86  5096.6  459.37  5113.8  460.05  5118.9   459.8
  5155.6  461.39  5250.9  463.54  5281.1  464.63  5292.1  465.44  5301.8  465.43
#Mann= 3 ,-1 , 0
  4634.1     .05       0  5033.3     .04       0  5037.3     .05       0
Bank Sta=5033.3,5037.3
XS Rating Curve= 0 ,0
Exp/Cntr=0.3,0.1

Type RM Length L Ch R = 1 ,1786    ,153,153,153
BEGIN DESCRIPTION:
Lacy 070 2299
END DESCRIPTION:
XS GIS Cut Line= 3
      2753502.79      6882192.08      2753928.67      6882235.31
      2754161.76      6882213.35
#Sta/Elev= 30
  4574.7  466.84    4588  467.07  4608.1  464.66  4618.3  463.93  4638.2  463.16
  4658.3  463.19  4678.4  461.18  4713.1  460.14  4728.7  460.18  4738.8  459.03
  4758.9  459.12  4817.2  458.71  4817.4  458.21  4820.9  458.21  4821.2  458.71
  5010.1  458.73  5050.3  459.56  5090.5  461.07  5098.8  461.16  5103.8  460.63
  5110.6   460.8  5140.7   460.6  5150.8  460.82  5190.9  463.19    5201  464.46
  5207.3   465.6  5212.3  465.48  5221.1  466.41  5231.1  467.02  5236.9  466.82
#Mann= 3 ,-1 , 0
  4574.7     .05       0  4817.2     .03       0  4821.2     .05       0
Bank Sta=4817.2,4821.2
XS Rating Curve= 0 ,0
Exp/Cntr=0.3,0.1

Type RM Length L Ch R = 1 ,1633    ,164,164,164
BEGIN DESCRIPTION:
Lacy 070 2298
END DESCRIPTION:
XS GIS Cut Line= 3
      2753480.66        6882195.      2753869.72      6882367.23
       2754076.1      6882450.19
#Sta/Elev= 30
  4574.5  467.76  4591.3  466.88  4604.7  467.33  4622.5  465.19    4628  464.99
    4635  464.12  4656.9   463.3  4667.8  463.59  4697.8  460.85  4721.1  460.24
  4733.4  460.33  4744.4  459.11  4749.9  458.86  5004.7  458.66    5005  458.16
  5008.5  458.16  5008.7  458.66  5017.5   459.5  5023.2  460.45  5052.8  460.57
  5082.3  461.08  5106.5  462.44  5130.7  464.68  5160.3  465.25  5184.5  466.36
    5190  467.14  5208.6  467.98    5214  467.96  5219.6  468.58  5222.4  468.58
#Mann= 3 ,-1 , 0
  4574.5     .05       0  5004.7     .03       0  5008.7     .05       0
Bank Sta=5004.7,5008.7
XS Rating Curve= 0 ,0
Exp/Cntr=0.3,0.1

Type RM Length L Ch R = 1 ,1469    ,52,52,52
BEGIN DESCRIPTION:
Lacy 070 2297
END DESCRIPTION:
XS GIS Cut Line= 3
      2753402.92      6882442.21      2753778.59      6882494.91
      2754061.02      6882463.66
#Sta/Elev= 30
  4622.4  472.33  4635.6  471.77  4650.2   469.9  4655.8  468.66  4665.9  467.93
    4676  467.99  4686.1  467.17  4696.2  465.38  4716.4  464.04  4726.6  464.16
  4746.7   461.5  4756.8  460.53  4766.9  460.91    4777  460.51  4787.1  459.39
  4837.6  459.32  4847.7  458.76  4857.8  458.72  5017.3  458.61  5017.5  458.11
    5021  458.11  5021.3  458.61    5140  458.68  5160.1  460.58  5174.5  460.93
  5200.4  462.36  5220.5  464.21  5265.2  466.75  5270.8  467.55  5285.9  468.12
#Mann= 3 ,-1 , 0
  4622.4     .05       0  5017.3     .03       0  5021.3     .05       0
Bank Sta=5017.3,5021.3
XS Rating Curve= 0 ,0
Exp/Cntr=0.3,0.1

Type RM Length L Ch R = 1 ,1417    ,84,84,84
BEGIN DESCRIPTION:
Lacy 070 2296
END DESCRIPTION:
XS GIS Cut Line= 3
       2753389.3      6882553.95      2753799.53      6882538.71
      2754068.75       6882510.6
#Sta/Elev= 30
  4587.1  469.68  4593.8  469.38  4613.8  467.39  4633.8  466.19  4643.8   465.2
  4703.9  461.29  4753.9  458.86  4761.9  457.76  4762.2  457.26  4765.7  457.26
  4765.9  457.76  4773.9  458.31  4800.1  458.56  4805.1  459.24    4854  458.85
    4874  459.05    4904  459.74  5014.2  460.11  5034.3  460.43  5084.6  460.45
  5104.7  460.26  5114.7  459.95  5119.9  458.78  5124.9  459.24  5134.8  461.04
  5144.9  461.18    5175  462.13  5245.4  466.91  5264.4  467.89  5268.3  467.89
#Mann= 3 ,-1 , 0
  4587.1     .05       0  4761.9     .04       0  4765.9     .05       0
Bank Sta=4761.9,4765.9
XS Rating Curve= 0 ,0
Exp/Cntr=0.3,0.1

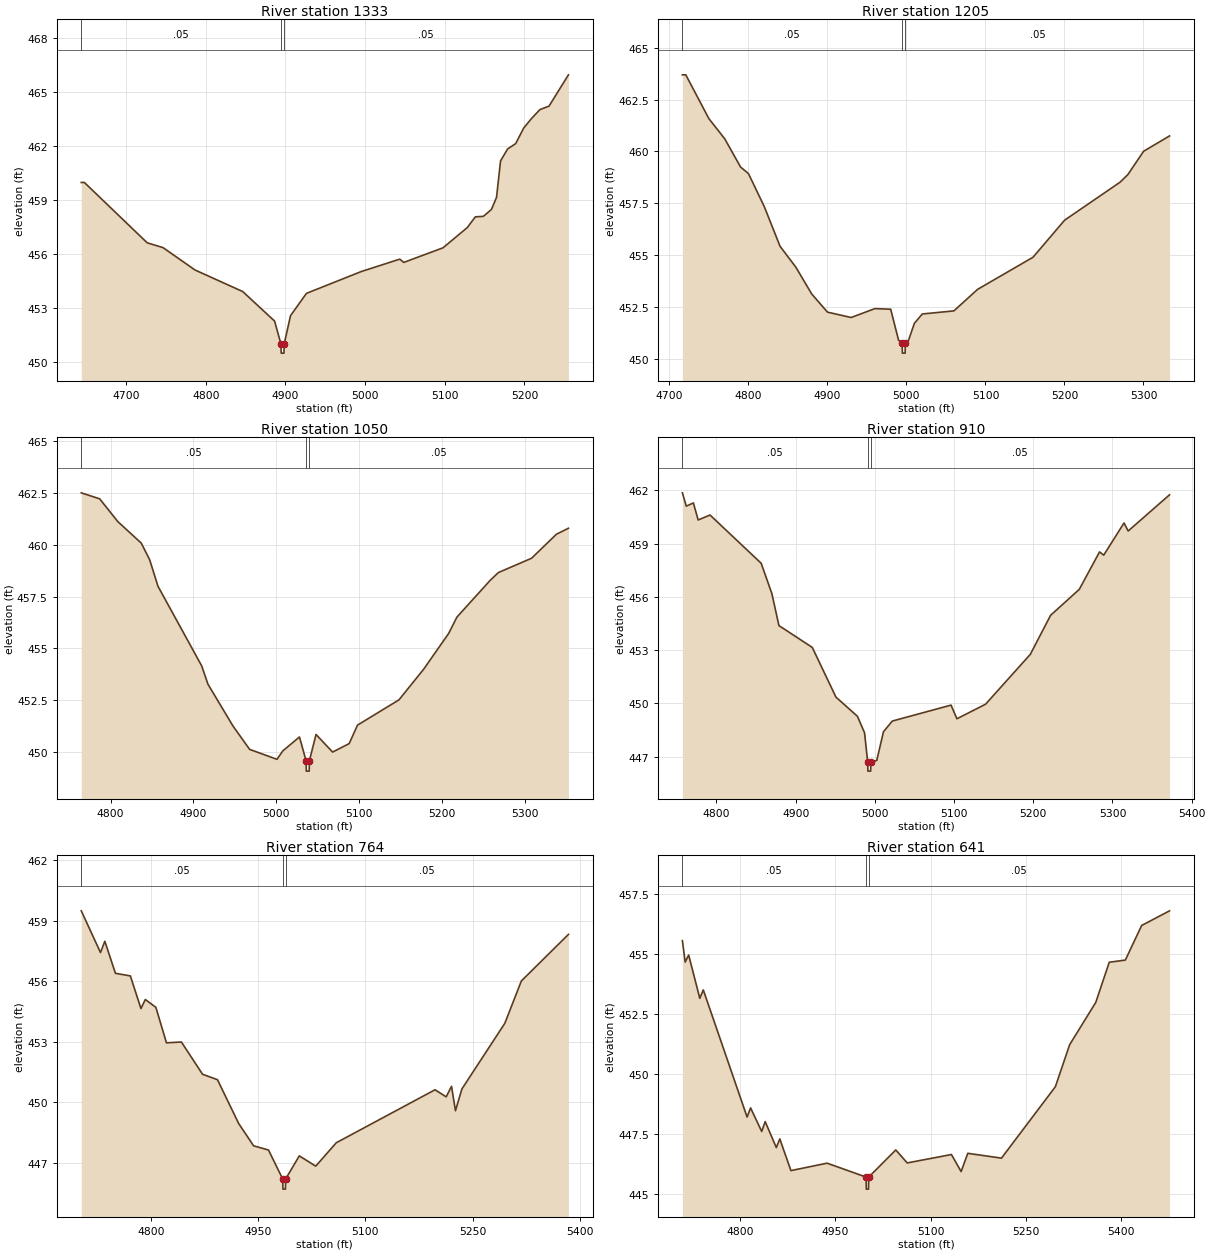
Type RM Length L Ch R = 1 ,1333    ,128,128,128
BEGIN DESCRIPTION:
Lacy 070 2295
END DESCRIPTION:
XS GIS Cut Line= 3
      2753463.28      6882608.49      2753818.26      6882613.63
      2754071.33      6882571.34
#Sta/Elev= 30
  4643.7  459.97  4647.6  459.97  4726.4  456.62  4746.4  456.35  4786.4  455.11
  4846.4  453.91  4886.4  452.27  4894.4  450.99  4894.7  450.49  4898.2  450.49
  4898.4  450.99  4906.4  452.57  4926.4  453.81  4995.1  455.02  5043.5  455.71
  5048.6  455.53  5097.8  456.34  5128.2  457.46  5138.4  458.06  5148.5  458.09
  5158.6  458.47    5165  459.14  5170.1  461.17  5178.9  461.83  5189.1  462.13
  5199.2     463  5209.3  463.54  5219.5  464.02  5230.9  464.21  5255.3  465.95
#Mann= 3 ,-1 , 0
  4643.7     .05       0  4894.4     .04       0  4898.4     .05       0
Bank Sta=4894.4,4898.4
XS Rating Curve= 0 ,0
Exp/Cntr=0.3,0.1

Type RM Length L Ch R = 1 ,1205    ,155,155,155
BEGIN DESCRIPTION:
Lacy 070 2292
END DESCRIPTION:
XS GIS Cut Line= 3
      2753442.41      6882684.18      2753724.07      6882685.82
      2754058.78      6882676.62
#Sta/Elev= 30
  4716.5   463.7  4720.8   463.7  4750.1  461.58  4770.1  460.61  4790.1  459.25
  4800.1  458.93  4820.1  457.34  4840.1  455.42  4860.1  454.41  4880.1  453.12
  4900.1  452.24  4930.1  451.98  4960.1  452.41  4980.1  452.38  4990.1  450.88
  4994.6  450.76  4994.9  450.26  4998.4  450.26  4998.6  450.76  5001.6  450.76
  5010.1   451.7  5020.1  452.15  5060.1   452.3  5090.1  453.34  5160.2  454.89
  5200.2  456.68  5270.2  458.51  5280.2  458.88  5300.2  460.01    5333  460.75
#Mann= 3 ,-1 , 0
  4716.5     .05       0  4994.6     .05       0  4998.6     .05       0
Bank Sta=4994.6,4998.6
XS Rating Curve= 0 ,0
Exp/Cntr=0.3,0.1

Type RM Length L Ch R = 1 ,1050    ,140,140,140
BEGIN DESCRIPTION:
Lacy 070 2293
END DESCRIPTION:
XS GIS Cut Line= 3
      2753443.92      6882801.98      2753676.68      6882824.94
      2754030.45      6882819.67
#Sta/Elev= 30
  4764.7  462.51  4786.9  462.22  4808.8  461.12  4837.1  460.08  4847.2  459.28
  4857.2     458    4910  454.15  4917.5  453.27  4947.7  451.25  4967.8  450.12
  5000.8  449.64  5007.9  450.05  5027.9  450.72  5035.9  449.57  5036.2  449.07
  5039.7  449.07  5039.9  449.57  5047.9  450.84  5067.9  449.99  5087.9   450.4
  5097.9  451.29  5147.9  452.51  5177.9     454  5207.9  455.72  5217.9  456.51
  5257.9  458.28  5267.9  458.66  5307.9  459.35  5337.9  460.51  5352.4   460.8
#Mann= 3 ,-1 , 0
  4764.7     .05       0  5035.9     .04       0  5039.9     .05       0
Bank Sta=5035.9,5039.9
XS Rating Curve= 0 ,0
Exp/Cntr=0.3,0.1

Type RM Length L Ch R = 1 ,910     ,146,146,146
BEGIN DESCRIPTION:
Lacy 070 2294
END DESCRIPTION:
XS GIS Cut Line= 3
      2753433.38       6882815.6      2753634.02      6882950.33
      2753986.05       6883074.9
#Sta/Elev= 30
    4757  461.86  4761.9  461.11  4770.9  461.29  4776.9  460.33  4791.9  460.61
  4856.5  457.89    4870  456.18  4878.9  454.38    4921  453.15  4950.9  450.35
    4978  449.27    4987  448.34    4991  446.68  4991.2  446.18  4994.7  446.18
    4995  446.68  5002.4  446.78  5010.9   448.4    5022     449  5096.2   449.9
  5103.6  449.13  5139.8  449.95  5196.3  452.76  5221.9  454.96  5258.1  456.42
  5283.7  458.53    5289  458.35  5314.6  460.16  5319.9  459.71  5372.1  461.75
#Mann= 3 ,-1 , 0
    4757     .05       0    4991     .04       0    4995     .05       0
Bank Sta=4991,4995
XS Rating Curve= 0 ,0
Exp/Cntr=0.3,0.1

Type RM Length L Ch R = 1 ,764     ,123,123,123
BEGIN DESCRIPTION:
Lacy 070 2290
END DESCRIPTION:
XS GIS Cut Line= 3
      2753392.13      6882828.87      2753565.88      6883075.53
       2753911.7      6883233.01
#Sta/Elev= 30
  4702.4  459.49  4729.3  457.42  4735.4  457.98  4750.2  456.39  4771.1  456.26
  4785.9  454.64    4792  455.09  4806.8   454.7  4821.6  452.94  4842.5  452.98
  4872.1  451.38    4893  451.11  4922.6  448.94  4943.5  447.83  4964.4  447.62
  4984.3  446.18  4984.6  445.68  4988.1  445.68  4988.3  446.18  5007.5  447.33
  5030.5  446.82  5059.2  447.98  5197.4  450.61    5213  450.26  5220.5  450.78
    5226  449.57    5235  450.65  5295.1  453.91  5318.2  456.01  5384.1  458.32
#Mann= 3 ,-1 , 0
  4702.4     .05       0  4984.3     .04       0  4988.3     .05       0
Bank Sta=4984.3,4988.3
XS Rating Curve= 0 ,0
Exp/Cntr=0.3,0.1

Type RM Length L Ch R = 1 ,641     ,150,150,150
BEGIN DESCRIPTION:
Lacy 070 2291
END DESCRIPTION:
XS GIS Cut Line= 3
      2753338.09      6882864.38      2753461.77      6883133.62
      2753905.52      6883289.43
#Sta/Elev= 30
  4709.4  455.56  4713.8  454.67  4719.3  454.96  4736.8  453.16  4742.3  453.51
  4811.2  448.22  4816.7   448.6  4834.2  447.62  4839.7  448.03  4857.2  446.95
  4862.7  447.31  4880.2  445.99  4937.1   446.3  4998.6  445.72  4998.8  445.22
  5002.3  445.22  5002.6  445.72  5045.2  446.85  5063.2  446.31  5132.8  446.66
    5148  445.95  5158.5  446.71  5211.5  446.51  5296.3  449.48  5318.8  451.23
  5359.9  452.99  5381.1  454.66  5406.4  454.75  5432.1  456.19    5476   456.8
#Mann= 3 ,-1 , 0
  4709.4     .05       0  4998.6     .04       0  5002.6     .05       0
Bank Sta=4998.6,5002.6
XS Rating Curve= 0 ,0
Exp/Cntr=0.3,0.1

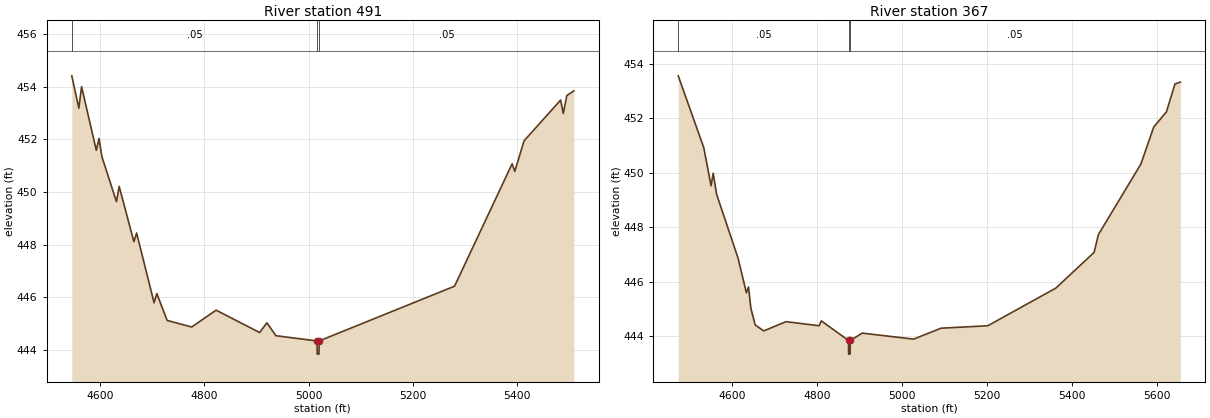
Type RM Length L Ch R = 1 ,491     ,124,124,124
BEGIN DESCRIPTION:
Lacy 070 2289
END DESCRIPTION:
XS GIS Cut Line= 3
      2753256.38      6882815.66      2753384.42      6883252.54
      2753879.19      6883360.66
#Sta/Elev= 30
  4546.4  454.41    4560  453.18  4565.2     454  4593.4  451.58  4598.6  452.03
  4604.1  451.34    4632  449.63  4637.2  450.21  4665.4  448.11  4670.6  448.44
  4704.1  445.79  4709.3  446.14  4729.1  445.12  4776.1  444.87  4822.9  445.51
  4906.3  444.66  4920.1  445.03  4937.5  444.54  5016.2  444.34  5016.5  443.84
    5020  443.84  5020.2  444.34  5279.6  446.42  5389.9  451.07    5395  450.78
  5412.7  451.94  5482.8  453.49  5487.9  452.98  5494.6  453.66  5508.1  453.84
#Mann= 3 ,-1 , 0
  4546.4     .05       0  5016.2     .04       0  5020.2     .05       0
Bank Sta=5016.2,5020.2
XS Rating Curve= 0 ,0
Exp/Cntr=0.3,0.1

Type RM Length L Ch R = 1 ,367     ,0,0,0
BEGIN DESCRIPTION:
Lacy 070 2300
END DESCRIPTION:
XS GIS Cut Line= 3
      2753221.74      6882791.37       2753291.1      6883380.16
      2753878.62      6883384.02
#Sta/Elev= 30
  4473.4  453.55  4533.4  450.92  4550.6  449.52  4555.6  449.98  4563.6  449.21
    4614  446.87  4633.6   445.6  4638.6  445.81  4644.2  445.03  4654.3  444.42
  4674.4   444.2  4726.7  444.54  4804.6  444.39  4809.7  444.57  4873.8  443.85
    4874  443.35  4877.5  443.35  4877.8  443.85    4906  444.12  5026.8   443.9
  5091.2   444.3  5201.2  444.39  5361.2  445.77  5451.2  447.08  5461.2  447.73
  5561.2  450.32  5591.2  451.67  5621.2  452.23  5641.2  453.25  5653.8  453.32
#Mann= 3 ,-1 , 0
  4473.4     .05       0  4873.8     .04       0  4877.8     .05       0
Bank Sta=4873.8,4877.8
XS Rating Curve= 0 ,0
Exp/Cntr=0.3,0.1

Chan Stop Cuts=-1
Use User Specified Reach Order=0
Composite Channel Slope=5