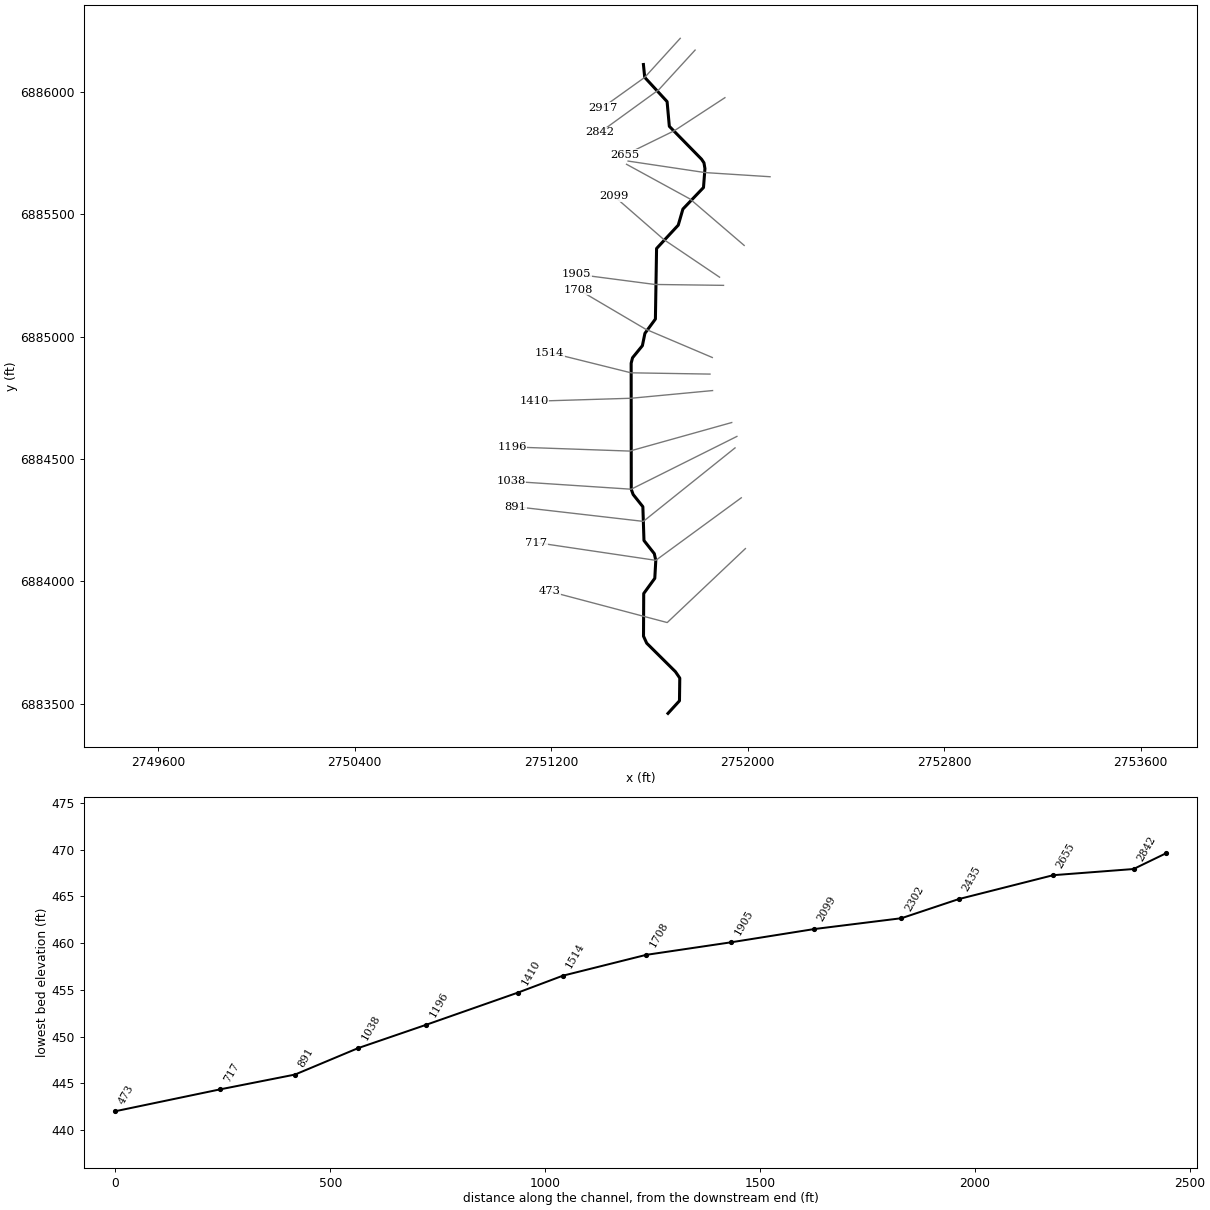
--- Lacy 071.prj (project) ---

Proj Title=Lacy 071 Base Level Engineering
Current Plan=p01
Default Exp/Contr=0.3,0.1
English Units
Geom File=g01
Flow File=f01
Plan File=p01
BEGIN DESCRIPTION:
Lacy 071
END DESCRIPTION:

--- Lacy 071.p01 (plan) ---

Plan Title=Multiple Run
Short Identifier=Multiple
Geom File=g01
Flow File=f01
Subcritical Flow
K Sum by GR= 0
Std Step Tol= 0.01
Critical Tol= 0.01
Num of Std Step Trials= 20
Max Error Tol= 0.3
Flow Tol Ratio= 0.001
Split Flow NTrial= 30
Split Flow Tol= 0.02
Split Flow Ratio= 0.02
Log Output Level= 0
Friction Slope Method= 1
Unsteady Friction Slope Method= 2
Unsteady Bridges Friction Slope Method= 1
Parabolic Critical Depth
Global Vel Dist=  1 , 1 , 1
Global Log Level= 0
CheckData=True
Encroach Param= -1, 0, 0, 0
BEGIN DESCRIPTION:
Multiple Run
END DESCRIPTION:

--- Lacy 071.f01 (steady flow) ---

Flow Title=Multiple
Number of Profiles=7
Profile Names=10-year,25-year,50-year,1pct_min,100-year,1pct_plu,500-year
River Rch & RM= Lacy 071,Reach-1,2917
     180     224     257     148     295     588     387
Boundary for River Rch & Prof#=Lacy 071,Reach-1,1
Up Type=0
Dn Type=3
Dn Slope=0.005
Boundary for River Rch & Prof#=Lacy 071,Reach-1,2
Up Type=0
Dn Type=3
Dn Slope=0.005
Boundary for River Rch & Prof#=Lacy 071,Reach-1,3
Up Type=0
Dn Type=3
Dn Slope=0.005
Boundary for River Rch & Prof#=Lacy 071,Reach-1,4
Up Type=0
Dn Type=3
Dn Slope=0.005
Boundary for River Rch & Prof#=Lacy 071,Reach-1,5
Up Type=0
Dn Type=3
Dn Slope=0.005
Boundary for River Rch & Prof#=Lacy 071,Reach-1,6
Up Type=0
Dn Type=3
Dn Slope=0.005
Boundary for River Rch & Prof#=Lacy 071,Reach-1,7
Up Type=0
Dn Type=3
Dn Slope=0.005

--- Lacy 071.g01 (geometry) ---

Geom Title=Existing Conditions

River Reach=Lacy 071,Reach-1
Reach XY= 30
      2751576.00      6886111.00      2751581.33      6886058.49
      2751672.39      6885959.50      2751681.52      6885858.57
      2751812.66      6885724.30      2751822.54      6885709.50
      2751826.51      6885686.04      2751820.59      6885608.58
      2751736.80      6885520.67      2751717.82      6885454.96
      2751629.55      6885359.53      2751624.80      6885071.50
      2751582.12      6885013.18      2751571.81      6884962.74
      2751531.71      6884913.35      2751526.06      6884890.97
      2751526.52      6884376.22      2751534.14      6884354.94
      2751573.73      6884305.06      2751578.27      6884166.94
      2751620.32      6884113.31      2751626.40      6884086.00
      2751622.30      6884012.60      2751577.22      6883950.50
      2751576.38      6883776.16      2751589.37      6883747.68
      2751706.41      6883631.16      2751724.05      6883605.12
      2751722.82      6883512.41      2751676.00      6883461.00

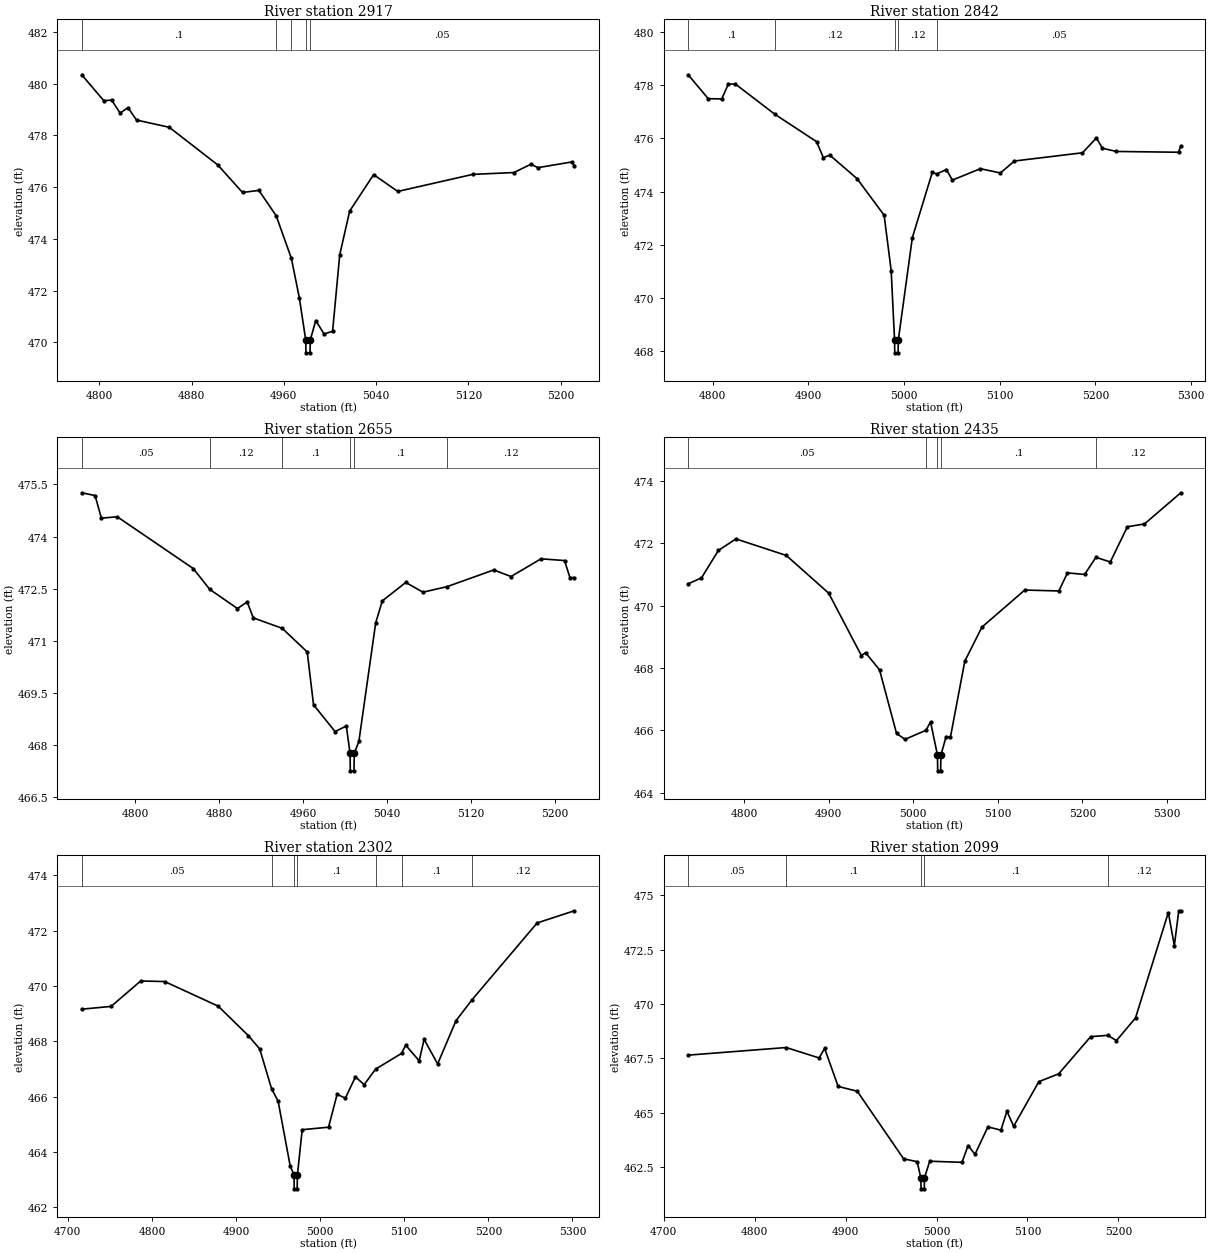
Type RM Length L Ch R = 1,2917,75,75,75
BEGIN DESCRIPTION:
Lacy 071 2288
END DESCRIPTION:
XS GIS Cut Line= 3
      2751725.89      6886217.90      2751581.33      6886058.49
      2751409.23      6885934.87
#Sta/Elev= 30
  4784.8  480.34  4803.9  479.34  4810.7  479.36  4818.1  478.86  4824.9  479.07
  4832.3  478.59  4860.7  478.31  4902.6  476.86  4924.2  475.79  4938.4  475.87
  4953.4  474.89  4966.6  473.24  4973.5  471.71  4979.0  470.09  4979.2  469.59
  4982.7  469.59  4983.0  470.09  4987.7  470.84  4994.9  470.32  5002.3  470.42
  5008.5  473.38  5017.1  475.07  5037.9  476.48  5058.8  475.83  5123.9  476.49
  5159.5  476.56  5174.2  476.88  5180.4  476.75  5209.8  476.97  5211.9  476.83
#Mann=5,-1,0
  4784.8     0.1       0  4953.4    0.12       0  4966.6    0.05       0
  4979.0    0.04       0  4983.0    0.05       0
Bank Sta=4979,4983
Exp/Cntr=0.3,0.1

Type RM Length L Ch R = 1,2842,187,187,187
BEGIN DESCRIPTION:
Lacy 071 2284
END DESCRIPTION:
XS GIS Cut Line= 3
      2751786.46      6886170.00      2751638.56      6886007.98
      2751399.76      6885834.23
#Sta/Elev= 30
  4774.6  478.40  4795.5  477.50  4809.7  477.49  4816.5  478.05  4823.9  478.05
  4865.2  476.91  4908.7  475.88  4915.8  475.28  4922.6  475.37  4950.9  474.49
  4979.3  473.11  4986.7  471.02  4990.2  468.42  4990.4  467.92  4993.9  467.92
  4994.2  468.42  5008.8  472.26  5029.7  474.73  5034.1  474.66  5044.4  474.83
  5050.6  474.43  5079.9  474.86  5100.8  474.70  5115.5  475.15  5186.6  475.46
  5201.2  476.02  5207.4  475.63  5222.1  475.51  5287.0  475.48  5289.3  475.72
#Mann=5,-1,0
  4774.6     0.1       0  4865.2    0.12       0  4990.2    0.07       0
  4994.2    0.12       0  5034.1    0.05       0
Bank Sta=4990.2,4994.2
Exp/Cntr=0.3,0.1

Type RM Length L Ch R = 1,2655,220,220,220
BEGIN DESCRIPTION:
Lacy 071 2283
END DESCRIPTION:
XS GIS Cut Line= 3
      2751907.80      6885975.52      2751702.02      6885840.67
      2751501.92      6885742.30
#Sta/Elev= 30
  4749.4  475.26  4762.1  475.18  4768.1  474.53  4783.2  474.57  4855.6  473.08
  4871.3  472.48  4897.7  471.93  4906.9  472.12  4912.8  471.66  4940.3  471.36
  4964.1  470.68  4970.1  469.16  4990.6  468.39  5001.3  468.55  5004.9  467.76
  5005.1  467.26  5008.6  467.26  5008.9  467.76  5013.3  468.11  5029.3  471.52
  5035.6  472.15  5057.9  472.68  5074.3  472.40  5097.3  472.56  5141.7  473.04
  5158.1  472.85  5186.7  473.36  5209.1  473.31  5214.2  472.82  5218.4  472.82
#Mann=6,-1,0
  4749.4    0.05       0  4871.3    0.12       0  4940.3     0.1       0
  5004.9    0.07       0  5008.9     0.1       0  5097.3    0.12       0
Bank Sta=5004.9,5008.9
Exp/Cntr=0.3,0.1

Type RM Length L Ch R = 1,2435,133,133,133
BEGIN DESCRIPTION:
Lacy 071 2282
END DESCRIPTION:
XS GIS Cut Line= 3
      2752091.67      6885652.67      2751827.19      6885669.65
      2751513.61      6885716.61
#Sta/Elev= 30
  4734.2  470.70  4749.9  470.89  4769.9  471.77  4790.6  472.14  4850.1  471.61
  4900.2  470.40  4938.8  468.40  4943.8  468.49  4960.3  467.94  4980.4  465.90
  4990.4  465.71  5015.1  466.00  5020.6  466.27  5028.8  465.20  5029.0  464.70
  5032.5  464.70  5032.8  465.20  5039.0  465.80  5044.0  465.77  5061.1  468.22
  5081.3  469.31  5131.9  470.50  5172.2  470.47  5182.4  471.05  5202.7  471.00
  5216.0  471.55  5233.0  471.40  5253.2  472.53  5273.4  472.62  5316.3  473.62
#Mann=5,-1,0
  4734.2    0.05       0  5015.1     0.1       0  5028.8    0.04       0
  5032.8     0.1       0  5216.0    0.12       0
Bank Sta=5028.8,5032.8
Exp/Cntr=0.3,0.1

Type RM Length L Ch R = 1,2302,203,203,203
BEGIN DESCRIPTION:
Lacy 071 2281
END DESCRIPTION:
XS GIS Cut Line= 3
      2751986.25      6885372.15      2751765.99      6885561.66
      2751507.27      6885703.48
#Sta/Elev= 30
  4716.6  469.16  4751.5  469.26  4786.7  470.18  4815.2  470.16  4878.8  469.27
  4914.8  468.20  4928.2  467.72  4942.3  466.28  4950.1  465.83  4964.4  463.49
  4969.0  463.16  4969.2  462.66  4972.7  462.66  4973.0  463.16  4978.7  464.80
  5010.0  464.89  5020.2  466.08  5030.0  465.94  5042.0  466.71  5052.4  466.43
  5065.9  466.99  5096.8  467.56  5101.7  467.86  5117.8  467.29  5123.6  468.07
  5139.7  467.18  5161.5  468.74  5180.3  469.49  5258.0  472.28  5302.2  472.72
#Mann=7,-1,0
  4716.6    0.05       0  4942.3     0.1       0  4969.0    0.07       0
  4973.0     0.1       0  5065.9    0.12       0  5096.8     0.1       0
  5180.3    0.12       0
Bank Sta=4969,4973
Exp/Cntr=0.3,0.1

Type RM Length L Ch R = 1,2099,194,194,194
BEGIN DESCRIPTION:
Lacy 071 2280
END DESCRIPTION:
XS GIS Cut Line= 3
      2751885.97      6885242.43      2751659.98      6885395.44
      2751457.65      6885572.38
#Sta/Elev= 30
  4726.9  467.65  4834.7  468.00  4870.9  467.52  4876.9  467.96  4891.8  466.21
  4912.8  465.99  4963.8  462.88  4978.7  462.75  4982.7  462.00  4983.0  461.50
  4986.5  461.50  4986.7  462.00  4992.5  462.77  5028.0  462.72  5034.7  463.49
  5042.3  463.09  5056.5  464.35  5070.8  464.20  5077.4  465.07  5084.8  464.38
  5112.5  466.43  5134.3  466.79  5169.5  468.50  5188.3  468.56  5197.9  468.32
  5218.8  469.36  5254.9  474.21  5261.5  472.69  5266.4  474.29  5268.6  474.29
#Mann=5,-1,0
  4726.9    0.05       0  4834.7     0.1       0  4982.7    0.07       0
  4986.7     0.1       0  5188.3    0.12       0
Bank Sta=4982.7,4986.7
Exp/Cntr=0.3,0.1

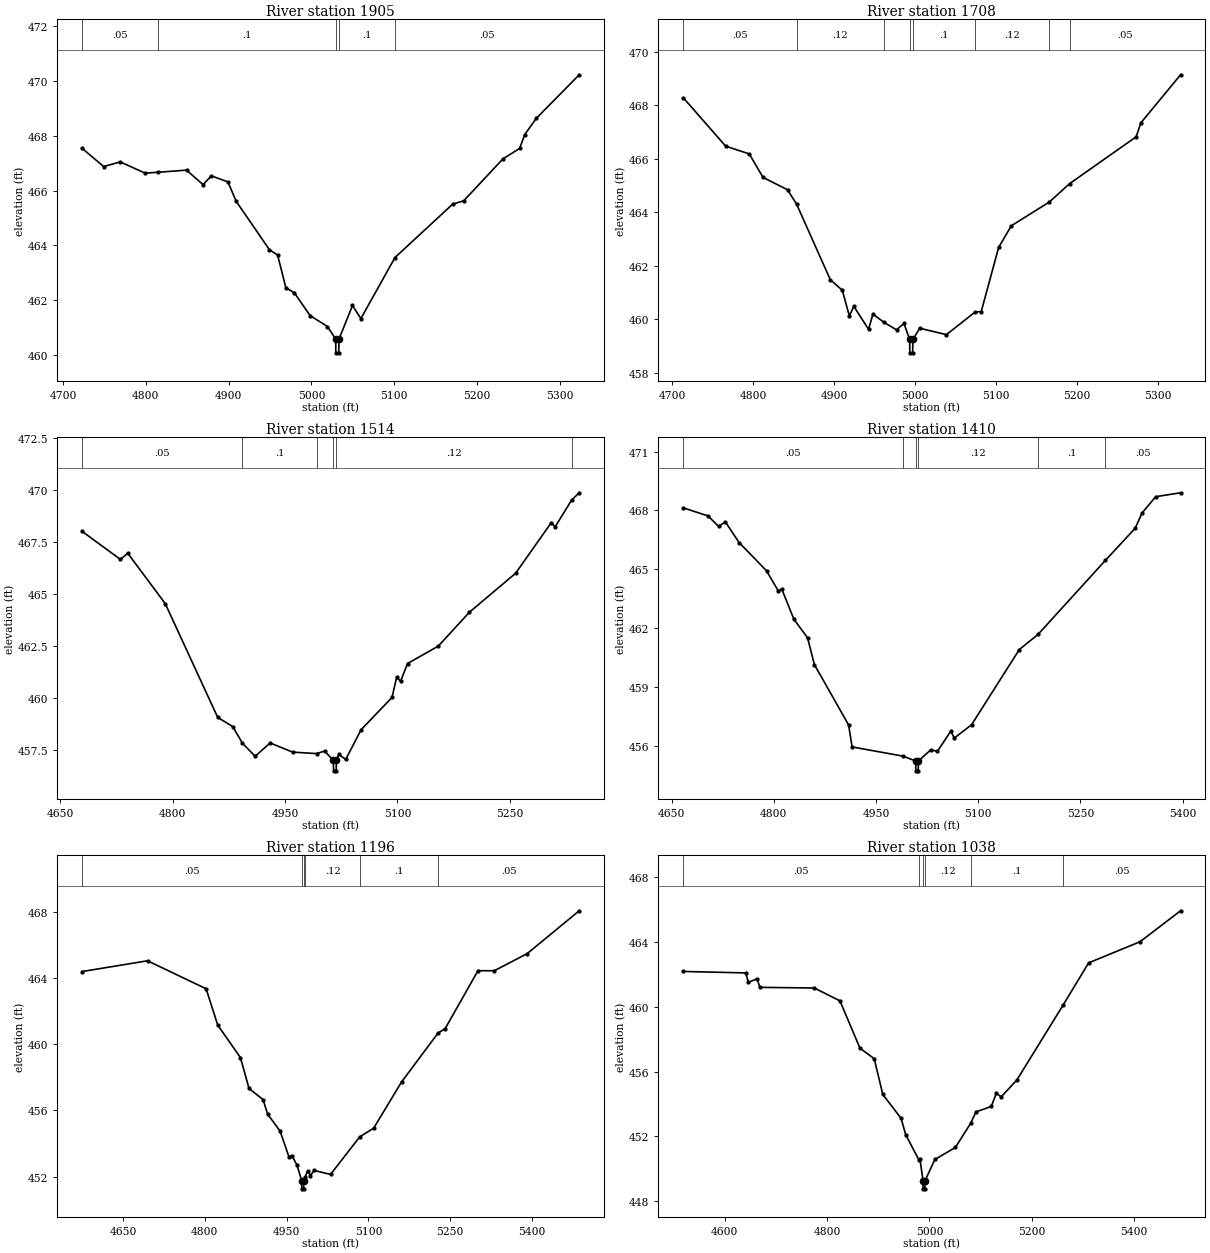
Type RM Length L Ch R = 1,1905,197,197,197
BEGIN DESCRIPTION:
Lacy 071 2279
END DESCRIPTION:
XS GIS Cut Line= 3
      2751902.20      6885209.07      2751622.59      6885212.70
      2751304.64      6885254.37
#Sta/Elev= 30
  4723.0  467.55  4749.2  466.88  4769.2  467.05  4799.2  466.64  4814.5  466.67
  4849.2  466.75  4869.2  466.22  4879.2  466.54  4899.2  466.32  4909.2  465.61
  4949.2  463.85  4959.2  463.65  4969.2  462.45  4979.2  462.28  4998.4  461.44
  5019.4  461.04  5029.3  460.58  5029.5  460.08  5033.0  460.08  5033.3  460.58
  5049.6  461.81  5059.7  461.33  5100.9  463.56  5170.6  465.51  5183.9  465.63
  5231.2  467.16  5251.3  467.54  5257.6  468.05  5271.5  468.64  5323.3  470.23
#Mann=5,-1,0
  4723.0    0.05       0  4814.5     0.1       0  5029.3    0.07       0
  5033.3     0.1       0  5100.9    0.05       0
Bank Sta=5029.3,5033.3
Exp/Cntr=0.3,0.1

Type RM Length L Ch R = 1,1708,194,194,194
BEGIN DESCRIPTION:
Lacy 071 2278
END DESCRIPTION:
XS GIS Cut Line= 3
      2751856.51      6884914.41      2751585.20      6885029.95
      2751310.79      6885192.04
#Sta/Elev= 30
  4714.1  468.28  4766.4  466.47  4795.5  466.18  4812.5  465.30  4842.7  464.84
  4854.1  464.29  4895.4  461.48  4910.3  461.08  4919.0  460.12  4924.5  460.48
  4942.7  459.62  4948.1  460.19  4961.2  459.89  4977.2  459.60  4986.4  459.84
  4993.4  459.24  4993.6  458.74  4997.1  458.74  4997.4  459.24  5005.8  459.66
  5038.8  459.42  5074.3  460.27  5081.7  460.28  5103.2  462.68  5118.8  463.49
  5165.7  464.38  5190.9  465.07  5272.9  466.82  5278.7  467.34  5327.7  469.14
#Mann=8,-1,0
  4714.1    0.05       0  4854.1    0.12       0  4961.2     0.1       0
  4993.4    0.07       0  4997.4     0.1       0  5074.3    0.12       0
  5165.7     0.1       0  5190.9    0.05       0
Bank Sta=4993.4,4997.4
Exp/Cntr=0.3,0.1

Type RM Length L Ch R = 1,1514,104,104,104
BEGIN DESCRIPTION:
Lacy 071 2277
END DESCRIPTION:
XS GIS Cut Line= 3
      2751847.15      6884846.66      2751525.69      6884851.87
      2751193.58      6884934.76
#Sta/Elev= 30
  4678.9  468.03  4730.1  466.68  4740.1  466.97  4790.1  464.55  4860.1  459.08
  4880.1  458.64  4893.1  457.84  4910.1  457.21  4930.1  457.85  4960.1  457.41
  4992.1  457.34  5002.8  457.46  5014.5  457.01  5014.8  456.51  5018.3  456.51
  5018.5  457.01  5021.7  457.30  5031.0  457.06  5051.6  458.49  5092.8  460.04
  5099.0  461.01  5104.2  460.81  5113.5  461.67  5154.7  462.51  5195.9  464.13
  5257.8  466.01  5305.3  468.44  5310.5  468.24  5332.6  469.53  5342.7  469.88
#Mann=6,-1,0
  4678.9    0.05       0  4893.1     0.1       0  4992.1    0.12       0
  5014.5    0.07       0  5018.5    0.12       0  5332.6    0.05       0
Bank Sta=5014.5,5018.5
Exp/Cntr=0.3,0.1

Type RM Length L Ch R = 1,1410,214,214,214
BEGIN DESCRIPTION:
Lacy 071 2276
END DESCRIPTION:
XS GIS Cut Line= 3
      2751857.51      6884779.37      2751526.00      6884747.97
      2751129.48      6884735.79
#Sta/Elev= 30
  4667.2  468.13  4703.4  467.72  4718.9  467.19  4729.0  467.41  4749.1  466.36
  4789.3  464.92  4806.6  463.89  4811.7  463.99  4829.4  462.45  4849.5  461.50
  4859.6  460.13  4909.8  457.05  4914.9  455.93  4989.7  455.46  5008.2  455.21
  5008.4  454.71  5011.9  454.71  5012.2  455.21  5030.2  455.78  5040.2  455.71
  5059.8  456.74  5064.8  456.38  5090.2  457.06  5160.3  460.90  5187.7  461.67
  5286.6  465.45  5330.3  467.09  5340.4  467.87  5360.4  468.70  5396.9  468.90
#Mann=6,-1,0
  4667.2    0.05       0  4989.7    0.12       0  5008.2    0.07       0
  5012.2    0.12       0  5187.7     0.1       0  5286.6    0.05       0
Bank Sta=5008.2,5012.2
Exp/Cntr=0.3,0.1

Type RM Length L Ch R = 1,1196,158,158,158
BEGIN DESCRIPTION:
Lacy 071 2275
END DESCRIPTION:
XS GIS Cut Line= 3
      2751935.57      6884648.79      2751520.22      6884532.22
      2751040.52      6884549.17
#Sta/Elev= 30
  4575.0  464.38  4695.2  465.03  4802.6  463.34  4823.8  461.15  4865.4  459.19
  4881.2  457.32  4906.9  456.65  4915.3  455.77  4938.1  454.75  4954.5  453.18
  4959.7  453.27  4969.2  452.69  4977.6  451.76  4977.9  451.26  4981.4  451.26
  4981.6  451.76  4984.4  452.00  4988.6  452.35  4993.8  452.06  5000.4  452.37
  5030.6  452.13  5084.1  454.40  5109.6  454.92  5160.7  457.71  5227.5  460.66
  5240.8  460.94  5300.8  464.43  5330.8  464.43  5390.9  465.46  5486.4  468.05
#Mann=6,-1,0
  4575.0    0.05       0  4977.6    0.07       0  4981.6    0.05       0
  4984.4    0.12       0  5084.1     0.1       0  5227.5    0.05       0
Bank Sta=4977.6,4981.6
Exp/Cntr=0.3,0.1

Type RM Length L Ch R = 1,1038,147,147,147
BEGIN DESCRIPTION:
Lacy 071 2274
END DESCRIPTION:
XS GIS Cut Line= 3
      2751956.68      6884592.13      2751526.18      6884376.50
      2751036.83      6884408.83
#Sta/Elev= 30
  4518.9  462.17  4640.7  462.08  4646.3  461.50  4663.0  461.72  4668.6  461.19
  4774.8  461.15  4825.0  460.36  4864.2  457.44  4892.1  456.79  4908.8  454.59
  4944.7  453.11  4953.5  452.11  4979.3  450.56  4981.5  450.61  4987.4  449.27
  4987.6  448.77  4991.1  448.77  4991.4  449.27  5010.6  450.58  5050.7  451.32
  5080.6  452.81  5090.8  453.51  5120.8  453.85  5130.8  454.66  5140.2  454.44
  5170.9  455.48  5261.1  460.09  5311.2  462.70  5411.5  464.00  5490.8  465.91
#Mann=6,-1,0
  4518.9    0.05       0  4979.3    0.12       0  4987.4    0.07       0
  4991.4    0.12       0  5080.6     0.1       0  5261.1    0.05       0
Bank Sta=4987.4,4991.4
Exp/Cntr=0.3,0.1

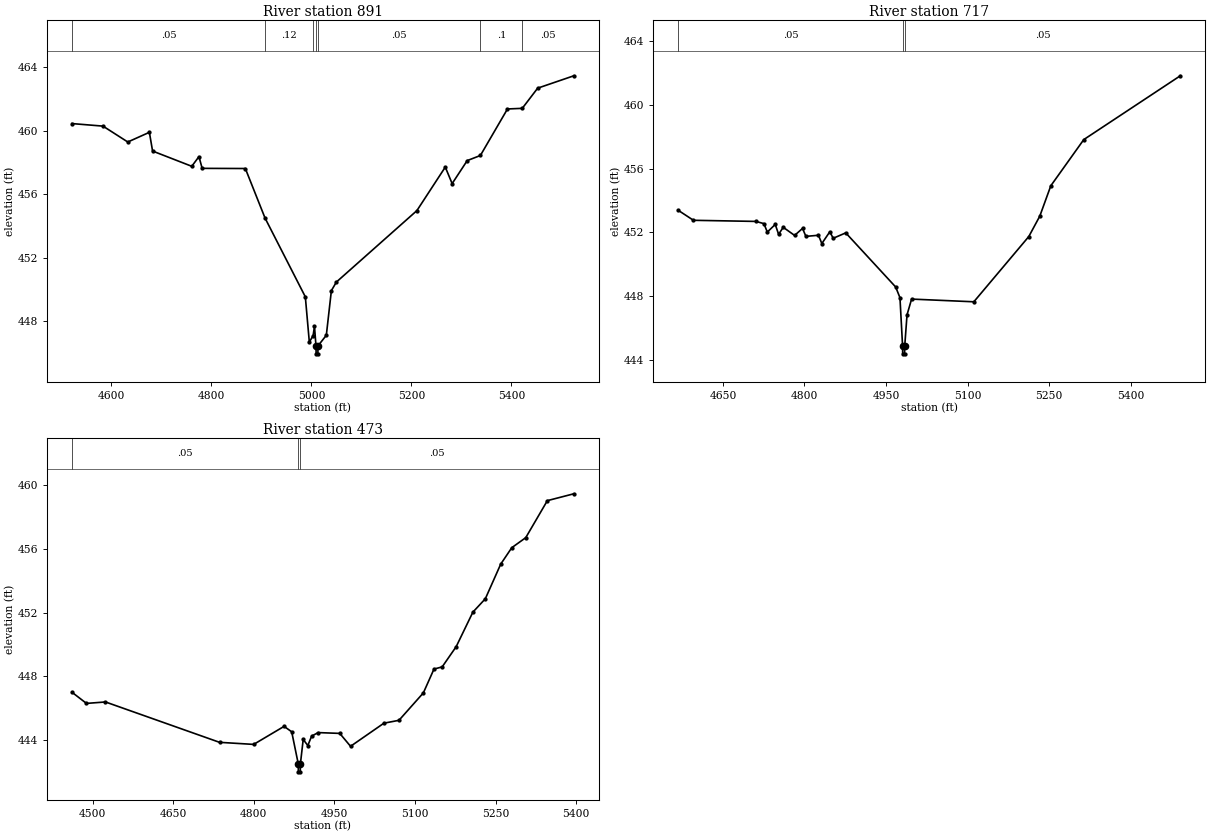
Type RM Length L Ch R = 1,891,174,174,174
BEGIN DESCRIPTION:
Lacy 071 2287
END DESCRIPTION:
XS GIS Cut Line= 3
      2751949.05      6884545.20      2751575.70      6884245.12
      2751054.06      6884305.33
#Sta/Elev= 30
  4521.0  460.44  4583.1  460.28  4632.7  459.28  4675.9  459.89  4682.3  458.71
  4760.7  457.75  4775.1  458.36  4781.5  457.62  4867.9  457.61  4907.3  454.49
  4987.9  449.53  4995.9  446.68  5003.5  447.09  5006.2  447.68  5009.2  446.44
  5009.5  445.94  5013.0  445.94  5013.2  446.44  5029.9  447.11  5040.0  449.92
  5050.0  450.46  5211.1  454.96  5267.9  457.70  5281.6  456.66  5311.8  458.11
  5338.1  458.43  5392.3  461.36  5421.9  461.40  5452.7  462.67  5525.1  463.45
#Mann=7,-1,0
  4521.0    0.05       0  4907.3    0.12       0  5003.5    0.05       0
  5009.2    0.07       0  5013.2    0.05       0  5338.1     0.1       0
  5421.9    0.05       0
Bank Sta=5009.2,5013.2
Exp/Cntr=0.3,0.1

Type RM Length L Ch R = 1,717,244,244,244
BEGIN DESCRIPTION:
Lacy 071 2286
END DESCRIPTION:
XS GIS Cut Line= 3
      2751974.52      6884341.47      2751626.40      6884086.00
      2751140.36      6884158.38
#Sta/Elev= 30
  4568.2  453.37  4595.9  452.75  4710.8  452.68  4725.5  452.54  4731.7  452.01
  4746.3  452.49  4752.5  451.87  4761.0  452.31  4781.9  451.80  4796.5  452.24
  4802.7  451.74  4825.8  451.81  4832.0  451.29  4846.7  452.03  4852.9  451.62
  4876.0  451.96  4967.8  448.56  4975.7  447.89  4980.5  444.86  4980.7  444.36
  4984.2  444.36  4984.5  444.86  4988.7  446.81  4997.1  447.80  5111.6  447.63
  5212.7  451.73  5232.9  453.01  5253.2  454.92  5313.8  457.82  5491.4  461.83
#Mann=3,-1,0
  4568.2    0.05       0  4980.5    0.04       0  4984.5    0.05       0
Bank Sta=4980.5,4984.5
Exp/Cntr=0.3,0.1

Type RM Length L Ch R = 1,473,0,0,0
BEGIN DESCRIPTION:
Lacy 071 2285
END DESCRIPTION:
XS GIS Cut Line= 3
      2751991.24      6884134.02      2751672.87      6883831.93
      2751194.41      6883958.91
#Sta/Elev= 30
  4461.7  447.01  4488.7  446.31  4524.1  446.40  4736.3  443.87  4799.8  443.74
  4856.4  444.87  4870.6  444.53  4882.8  442.52  4883.0  442.02  4886.5  442.02
  4886.8  442.52  4892.0  444.05  4900.6  443.67  4907.7  444.26  4919.8  444.48
  4960.0  444.43  4980.1  443.62  5042.2  445.07  5070.2  445.25  5115.6  446.97
  5135.3  448.46  5150.6  448.60  5176.7  449.87  5207.7  452.03  5230.9  452.87
  5259.5  455.04  5280.1  456.07  5306.1  456.70  5346.3  459.02  5395.6  459.45
#Mann=3,-1,0
  4461.7    0.05       0  4882.8    0.04       0  4886.8    0.05       0
Bank Sta=4882.8,4886.8
Exp/Cntr=0.3,0.1

Chan Stop Cuts=-1