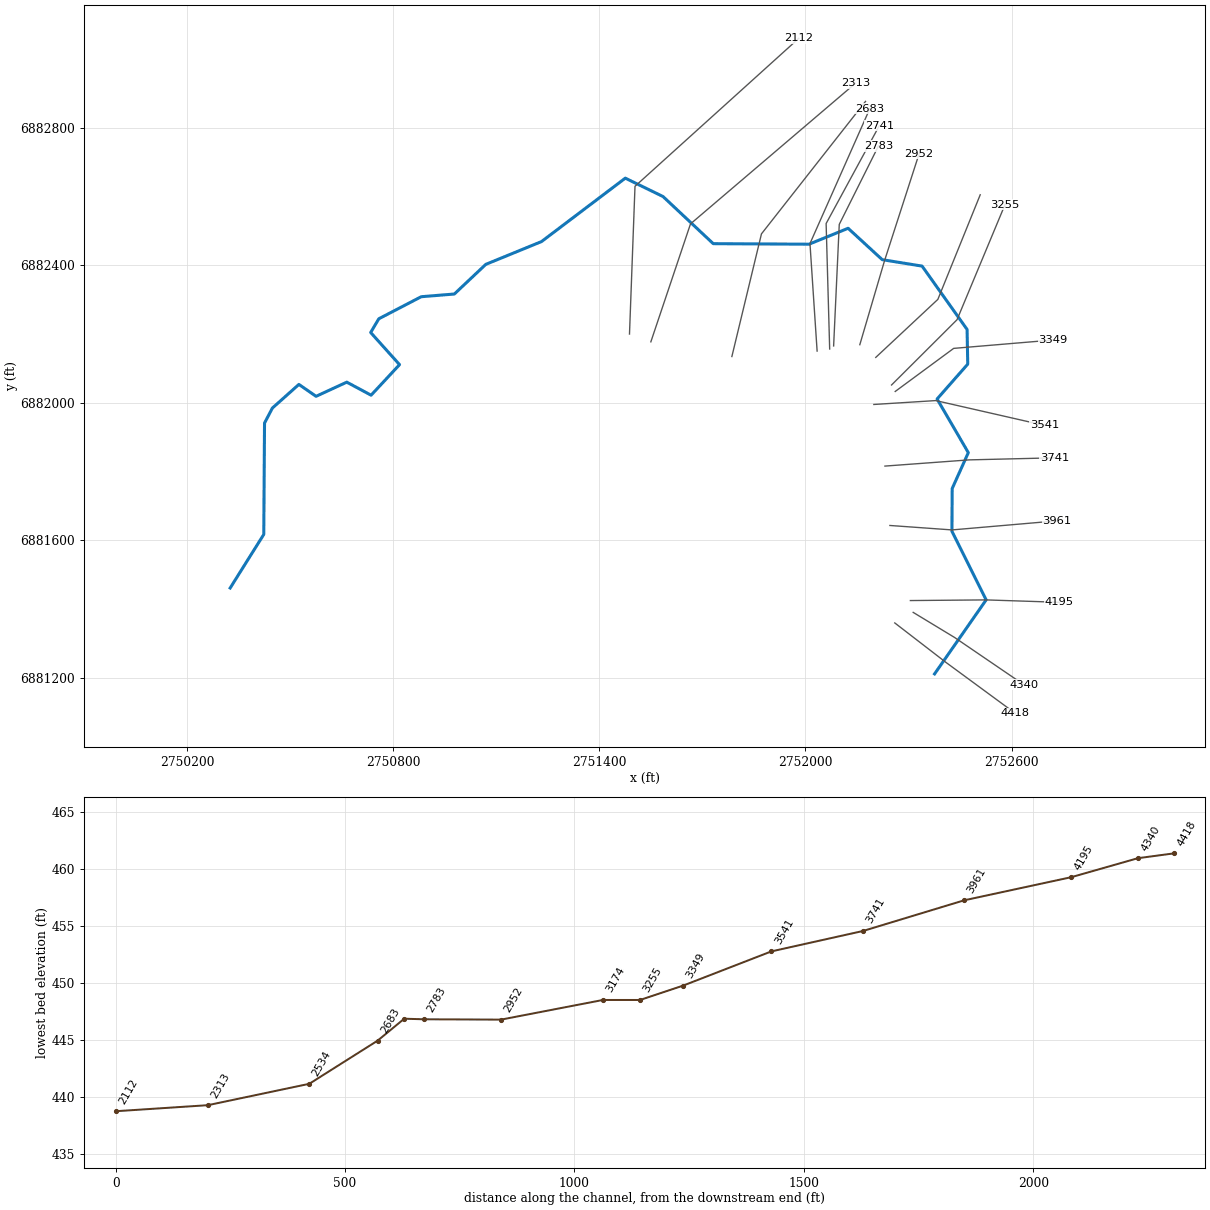
--- Lacy 072.prj (project) ---

Proj Title=Lacy 072 Base Level Engineering
Current Plan=p01
Default Exp/Contr=0.3,0.1
English Units
Geom File=g01
Flow File=f01
Plan File=p01
Y Axis Title=Elevation
X Axis Title(PF)=Main Channel Distance
X Axis Title(XS)=Station
BEGIN DESCRIPTION:
Lacy 072
END DESCRIPTION:
DSS Export Rating Curves= 0
DSS Export Rating Curve Sorted= 0
DSS Export Volume Flow Curves= 0
DXF OffsetX= 0
DXF OffsetY= 0
DXF ScaleX= 1
DXF ScaleY= 10

--- Lacy 072.p01 (plan) ---

Plan Title=Multiple Run
Short Identifier=Multiple
Geom File=g01
Flow File=f01
Subcritical Flow
K Sum by GR= 0
Std Step Tol= 0.01
Critical Tol= 0.01
Num of Std Step Trials= 20
Max Error Tol= 0.3
Flow Tol Ratio= 0.001
Split Flow NTrial= 30
Split Flow Tol= 0.02
Split Flow Ratio= 0.02
Log Output Level= 0
Friction Slope Method= 1
Unsteady Friction Slope Method= 2
Unsteady Bridges Friction Slope Method= 1
Parabolic Critical Depth
Global Vel Dist=  1 , 1 , 1
Global Log Level= 0
CheckData=True
Encroach Param= -1, 0, 0, 0
BEGIN DESCRIPTION:
Multiple Run
END DESCRIPTION:

--- Lacy 072.f01 (steady flow) ---

Flow Title=Multiple
Number of Profiles=7
Profile Names=10-year,25-year,50-year,1pct_min,100-year,1pct_plu,500-year
River Rch & RM= Lacy 072,Reach-1,4418
     156     191     216     123     245     489     314
Boundary for River Rch & Prof#=Lacy 072,Reach-1,1
Up Type=0
Dn Type=3
Dn Slope=0.005
Boundary for River Rch & Prof#=Lacy 072,Reach-1,2
Up Type=0
Dn Type=3
Dn Slope=0.005
Boundary for River Rch & Prof#=Lacy 072,Reach-1,3
Up Type=0
Dn Type=3
Dn Slope=0.005
Boundary for River Rch & Prof#=Lacy 072,Reach-1,4
Up Type=0
Dn Type=3
Dn Slope=0.005
Boundary for River Rch & Prof#=Lacy 072,Reach-1,5
Up Type=0
Dn Type=3
Dn Slope=0.005
Boundary for River Rch & Prof#=Lacy 072,Reach-1,6
Up Type=0
Dn Type=3
Dn Slope=0.005
Boundary for River Rch & Prof#=Lacy 072,Reach-1,7
Up Type=0
Dn Type=3
Dn Slope=0.005

--- Lacy 072.g01 (geometry) ---

Geom Title=Existing Conditions
Program Version=4.10

River Reach=Lacy 072        ,Reach-1
Reach XY= 30
        2752376.        6881211.      2752526.05      6881426.34
      2752426.49      6881626.22      2752427.23       6881750.5
       2752474.2      6881854.89       2752383.3      6882011.08
      2752472.52       6882112.5      2752470.59      6882213.42
      2752339.65      6882397.74      2752223.58      6882416.54
      2752124.36      6882507.86      2752010.79      6882461.54
      2751731.85      6882463.06      2751585.68      6882600.25
      2751475.92       6882653.7      2751232.05      6882469.16
      2751069.95      6882402.84      2750978.42      6882316.54
      2750881.97      6882308.67       2750758.4      6882244.36
      2750734.93      6882204.49       2750818.9      6882110.98
       2750736.1      6882022.11      2750665.36      6882060.01
      2750575.91      6882018.84      2750525.98      6882053.46
      2750448.86      6881984.64      2750425.96      6881941.03
      2750423.77      6881616.92        2750326.        6881461.

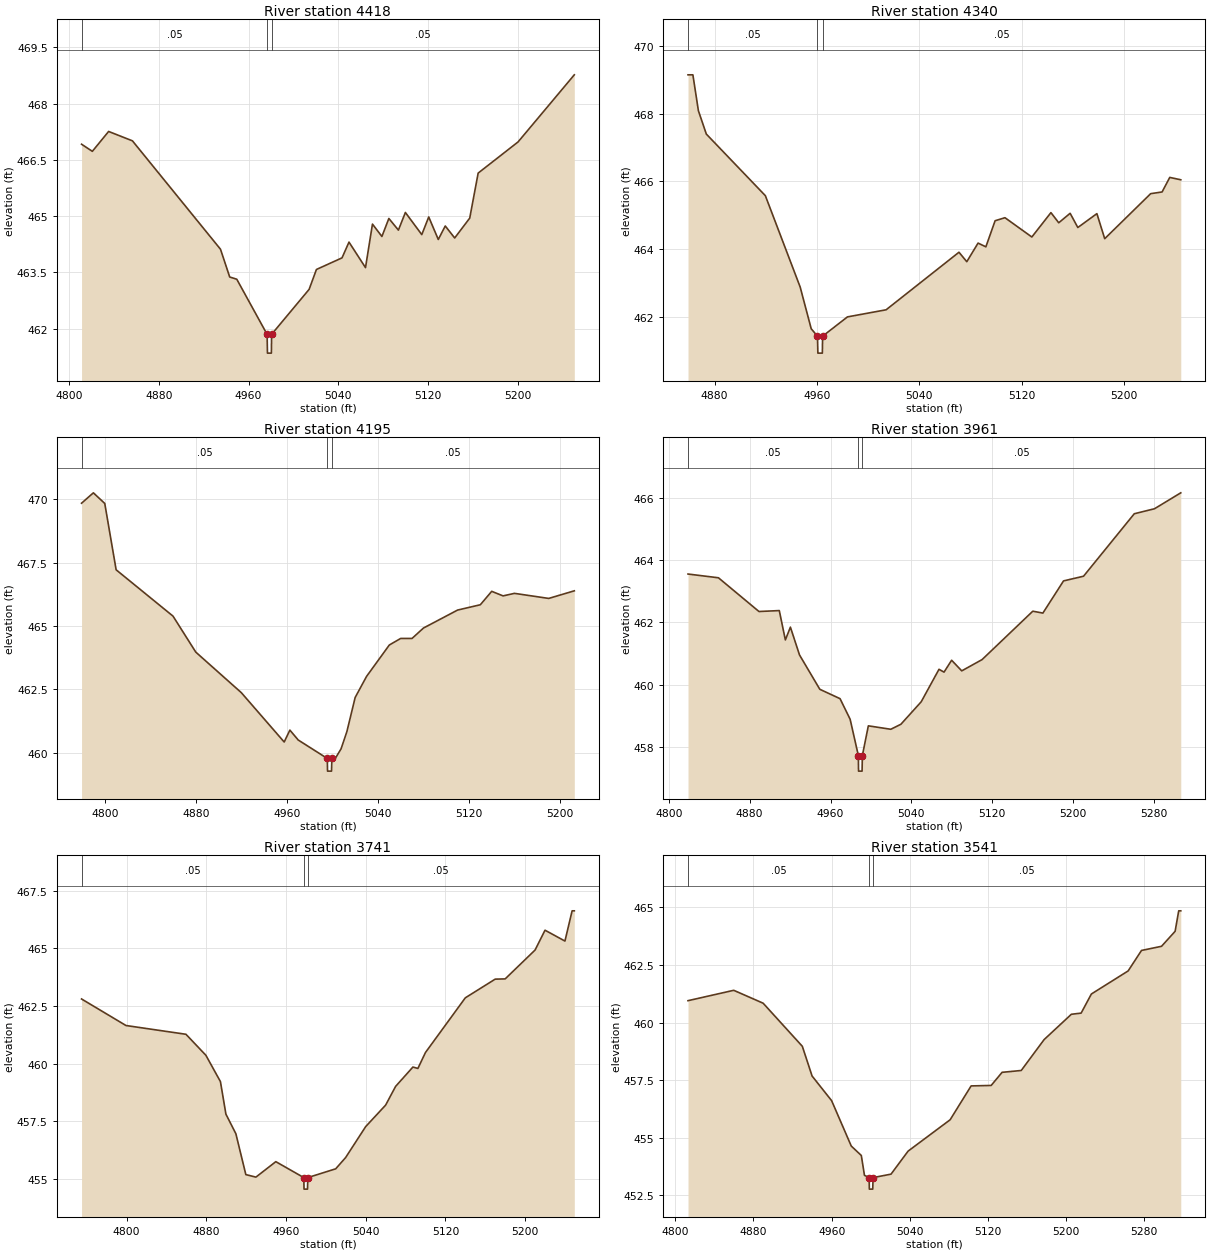
Type RM Length L Ch R = 1 ,4418    ,78,78,78
BEGIN DESCRIPTION:
Lacy 072 2268
END DESCRIPTION:
XS GIS Cut Line= 3
      2752260.14       6881359.3      2752409.58      6881244.08
      2752611.08       6881096.1
#Sta/Elev= 30
  4811.3  466.92  4820.9  466.73  4835.4  467.26  4856.6  467.01    4935  464.12
  4943.2  463.38  4949.5  463.32  4976.5  461.85  4976.8  461.35  4980.3  461.35
  4980.5  461.85  5013.9  463.05  5020.4  463.58  5043.2  463.89  5049.4  464.31
  5064.1  463.63  5070.3  464.79  5078.7  464.46  5084.9  464.94  5093.4  464.63
  5099.6   465.1  5114.2  464.51  5120.4  464.98  5128.9  464.38  5135.1  464.74
  5143.5  464.42  5156.9  464.95  5164.4  466.15  5199.9  466.98    5250  468.77
#Mann= 3 ,-1 , 0
  4811.3     .05       0  4976.5     .04       0  4980.5     .05       0
Bank Sta=4976.5,4980.5
XS Rating Curve= 0 ,0
Exp/Cntr=0.3,0.1

Type RM Length L Ch R = 1 ,4340    ,145,145,145
BEGIN DESCRIPTION:
Lacy 072 2267
END DESCRIPTION:
XS GIS Cut Line= 3
      2752313.75        6881390.      2752434.08      6881317.08
      2752635.77      6881179.59
#Sta/Elev= 30
  4859.3  469.15  4863.1  469.15  4867.4  468.09  4873.6   467.4  4919.7  465.58
  4946.9  462.88  4955.5  461.65  4960.4  461.43  4960.7  460.93  4964.2  460.93
  4964.4  461.43  4983.8     462    5014  462.21  5070.9  463.91    5077  463.63
  5085.8  464.18  5091.9  464.07  5099.1  464.84  5106.8  464.93  5127.8  464.36
  5142.7  465.08  5148.8  464.78  5157.7  465.06  5163.7  464.64  5178.6  465.05
  5184.7  464.31  5220.6  465.64  5229.5  465.69  5235.5  466.12  5244.1  466.05
#Mann= 3 ,-1 , 0
  4859.3     .05       0  4960.4     .04       0  4964.4     .05       0
Bank Sta=4960.4,4964.4
XS Rating Curve= 0 ,0
Exp/Cntr=0.3,0.1

Type RM Length L Ch R = 1 ,4195    ,234,234,234
BEGIN DESCRIPTION:
Lacy 072 2266
END DESCRIPTION:
XS GIS Cut Line= 3
      2752305.56      6881424.45      2752526.05      6881426.34
      2752738.53      6881419.35
#Sta/Elev= 30
  4779.5  469.85  4789.9  470.26  4799.9  469.84  4809.9  467.22  4859.9  465.39
  4879.9  463.97  4919.9  462.37  4957.6  460.42  4962.6  460.89  4969.9   460.5
  4995.5  459.77  4995.7  459.27  4999.2  459.27  4999.5  459.77  5002.5  459.77
  5007.6  460.15  5012.7  460.83    5020  462.18    5030  463.01    5050  464.25
    5060  464.51    5070  464.51    5080  464.92    5110  465.63    5130  465.84
    5140  466.37    5150  466.19    5160  466.29  5190.1  466.09  5212.6  466.39
#Mann= 3 ,-1 , 0
  4779.5     .05       0  4995.5     .04       0  4999.5     .05       0
Bank Sta=4995.5,4999.5
XS Rating Curve= 0 ,0
Exp/Cntr=0.3,0.1

Type RM Length L Ch R = 1 ,3961    ,220,220,220
BEGIN DESCRIPTION:
Lacy 072 2261
END DESCRIPTION:
XS GIS Cut Line= 3
      2752245.98      6881642.95      2752426.76      6881630.01
      2752731.87      6881656.39
#Sta/Elev= 30
    4819  463.55  4849.1  463.43  4889.2  462.35  4909.3  462.38  4915.3  461.44
  4920.3  461.85  4929.3  460.96  4949.4  459.86  4969.4  459.56  4979.4   458.9
  4987.5  457.74  4987.7  457.24  4991.2  457.24  4991.5  457.74  4997.4  458.69
  5019.6  458.58  5029.6  458.74  5049.7  459.46  5067.3   460.5  5072.3  460.41
  5079.8  460.79  5089.8  460.45  5109.9  460.81  5160.1  462.36  5170.1   462.3
  5190.5  463.33  5210.3  463.48  5260.5  465.48  5280.5  465.64  5306.5  466.15
#Mann= 3 ,-1 , 0
    4819     .05       0  4987.5     .04       0  4991.5     .05       0
Bank Sta=4987.5,4991.5
XS Rating Curve= 0 ,0
Exp/Cntr=0.3,0.1

Type RM Length L Ch R = 1 ,3741    ,200,200,200
BEGIN DESCRIPTION:
Lacy 072 2260
END DESCRIPTION:
XS GIS Cut Line= 3
      2752231.52      6881815.78      2752476.11      6881833.83
      2752725.38      6881839.86
#Sta/Elev= 30
  4754.8   462.8  4799.4  461.65  4859.6  461.27  4879.6  460.36  4894.2  459.22
  4899.7  457.81  4909.7  456.96  4919.7  455.19  4929.8  455.08  4949.8  455.75
  4977.9  455.06  4978.1  454.56  4981.6  454.56  4981.9  455.06  5009.9  455.44
  5019.9  455.93    5040  457.27    5060   458.2    5070  459.01  5087.4  459.85
  5092.4  459.79    5100  460.48    5140  462.85    5170  463.66    5180  463.67
    5210  464.92    5220  465.78    5240  465.31  5247.2  466.62  5249.4  466.62
#Mann= 3 ,-1 , 0
  4754.8     .05       0  4977.9     .04       0  4981.9     .05       0
Bank Sta=4977.9,4981.9
XS Rating Curve= 0 ,0
Exp/Cntr=0.3,0.1

Type RM Length L Ch R = 1 ,3541    ,192,192,192
BEGIN DESCRIPTION:
Lacy 072 2258
END DESCRIPTION:
XS GIS Cut Line= 3
      2752199.25       6881995.1       2752379.5       6882006.4
      2752695.19      6881934.39
#Sta/Elev= 30
    4813  460.95  4859.8   461.4  4889.9  460.84    4930  458.97    4940  457.68
    4960  456.61  4980.1  454.64  4990.4  454.23  4993.6  453.37  4998.4  453.27
  4998.6  452.77  5002.1  452.77  5002.4  453.27  5020.8  453.42  5038.3  454.42
  5081.3  455.78  5102.8  457.25  5123.3  457.27  5134.5  457.84  5154.1  457.92
  5177.5  459.26  5205.4  460.36  5215.4  460.41  5225.9  461.24  5263.5  462.24
  5277.2  463.13  5297.7  463.31  5311.6  463.96  5315.3  464.85  5317.4  464.85
#Mann= 3 ,-1 , 0
    4813     .05       0  4998.4     .04       0  5002.4     .05       0
Bank Sta=4998.4,5002.4
XS Rating Curve= 0 ,0
Exp/Cntr=0.3,0.1

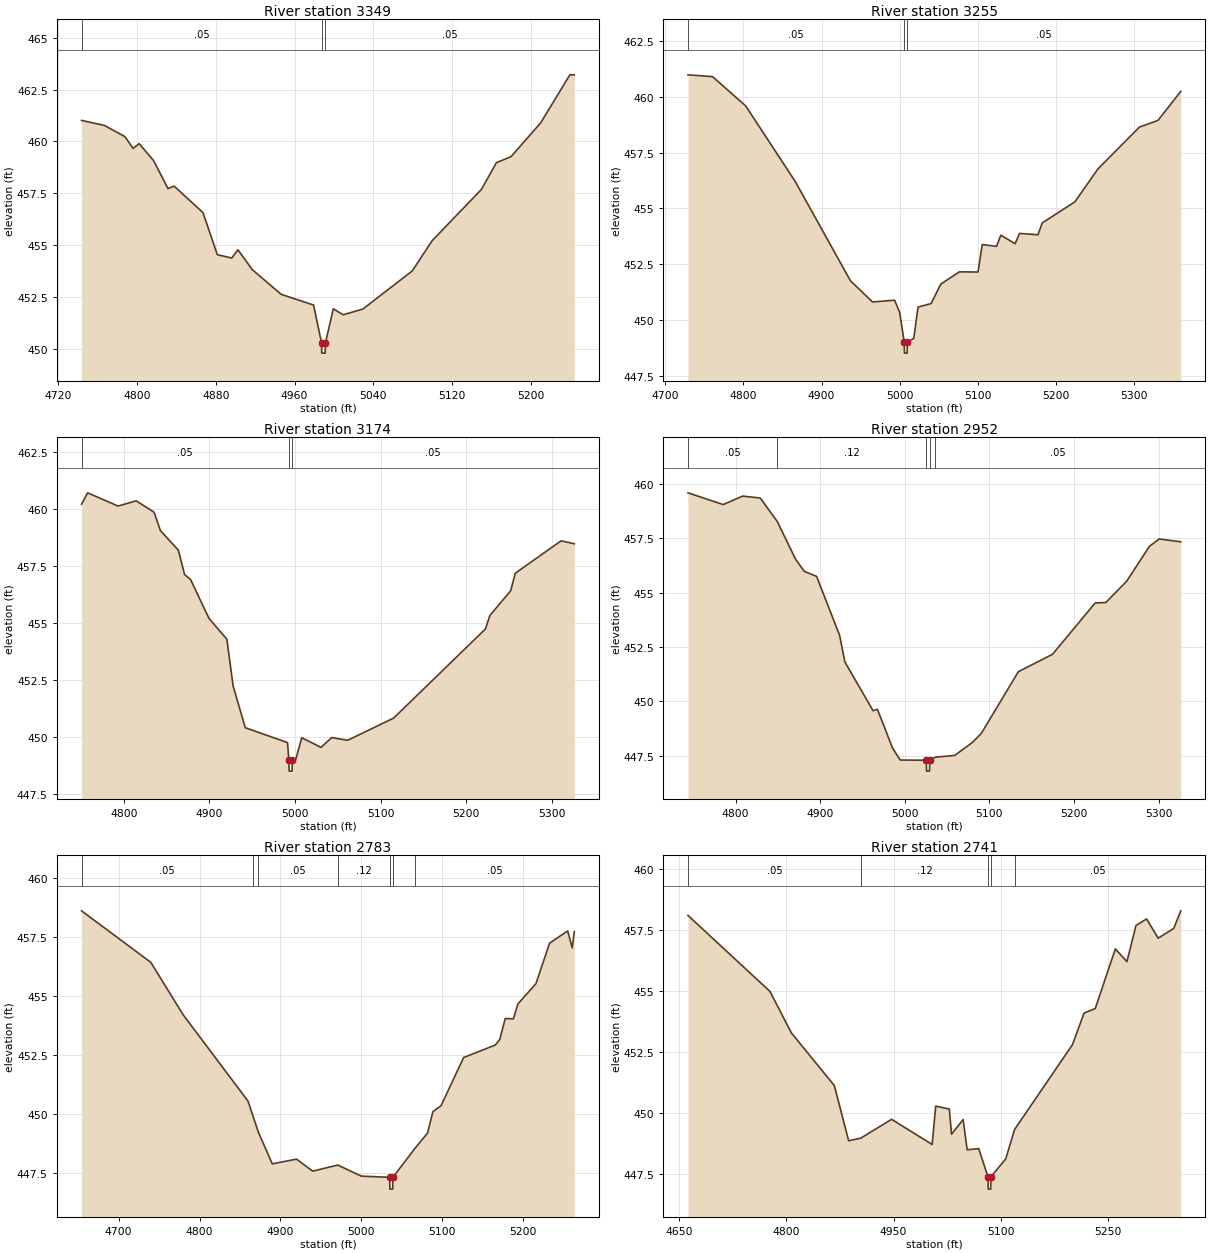
Type RM Length L Ch R = 1 ,3349    ,94,94,94
BEGIN DESCRIPTION:
Lacy 072 2259
END DESCRIPTION:
XS GIS Cut Line= 3
      2752261.46      6882032.97      2752431.57      6882158.33
      2752720.04      6882182.63
#Sta/Elev= 30
  4743.5  461.01  4766.6  460.77  4787.5  460.23  4795.9  459.66  4802.1  459.89
  4816.7  459.07  4831.4  457.72  4837.6  457.84  4866.9  456.56  4881.5  454.53
  4896.2  454.37  4902.4  454.77    4917  453.81  4946.3  452.62  4979.3   452.1
  4987.4  450.28  4987.6  449.78  4991.1  449.78  4991.4  450.28  4999.4  451.92
  5009.4  451.63  5029.5  451.91  5079.7  453.75  5099.7   455.2  5149.9  457.68
  5165.1  458.97    5180  459.26  5210.1  460.89  5239.8  463.21  5244.3  463.21
#Mann= 3 ,-1 , 0
  4743.5     .05       0  4987.4     .04       0  4991.4     .05       0
Bank Sta=4987.4,4991.4
XS Rating Curve= 0 ,0
Exp/Cntr=0.3,0.1

Type RM Length L Ch R = 1 ,3255    ,81,81,81
BEGIN DESCRIPTION:
Lacy 072 2256
END DESCRIPTION:
XS GIS Cut Line= 3
      2752250.76      6882051.78      2752441.29      6882241.69
      2752580.83      6882576.35
#Sta/Elev= 30
  4728.9  460.98  4760.3   460.9  4802.8  459.59  4866.4   456.2  4937.1  451.76
  4965.4  450.81  4993.7  450.89  5000.2  450.34    5006  449.02  5006.3  448.52
  5009.8  448.52    5010  449.02  5018.3  449.18  5023.7  450.58  5040.5  450.74
  5052.9  451.61  5076.8  452.16  5100.6  452.15    5106  453.38  5124.4   453.3
  5129.8   453.8  5148.2  453.42  5153.7  453.88  5177.5  453.82  5182.9  454.35
  5224.7  455.29  5254.4  456.77  5307.5  458.64  5331.3  458.94  5360.5  460.24
#Mann= 3 ,-1 , 0
  4728.9     .05       0    5006     .04       0    5010     .05       0
Bank Sta=5006,5010
XS Rating Curve= 0 ,0
Exp/Cntr=0.3,0.1

Type RM Length L Ch R = 1 ,3174    ,222,222,222
BEGIN DESCRIPTION:
Lacy 072 2255
END DESCRIPTION:
XS GIS Cut Line= 3
      2752204.82      6882132.08      2752385.57      6882300.95
      2752508.79      6882605.29
#Sta/Elev= 30
  4750.7   460.2  4757.8   460.7  4793.4  460.12  4814.5  460.35  4835.5  459.85
  4842.8  459.05  4863.8  458.19  4871.1  457.12    4878  456.91  4899.5  455.21
  4920.5  454.29  4927.8  452.24    4942  450.42  4991.3  449.77  4992.9  449.02
  4993.2  448.52  4996.7  448.52  4996.9  449.02  5000.8  449.02    5008  449.98
  5030.5  449.56  5042.9  449.99  5061.6  449.87  5115.3  450.84  5222.5  454.74
  5227.9  455.34    5252  456.41  5257.4  457.18    5311   458.6  5326.4  458.47
#Mann= 3 ,-1 , 0
  4750.7     .05       0  4992.9     .04       0  4996.9     .05       0
Bank Sta=4992.9,4996.9
XS Rating Curve= 0 ,0
Exp/Cntr=0.3,0.1

Type RM Length L Ch R = 1 ,2952    ,169,169,169
BEGIN DESCRIPTION:
Lacy 072 2257
END DESCRIPTION:
XS GIS Cut Line= 3
      2752158.41      6882169.05      2752230.26      6882413.22
      2752331.15      6882725.29
#Sta/Elev= 30
  4743.8  459.59  4785.4  459.05  4808.4  459.44  4829.2  459.35  4849.5  458.26
  4870.9  456.54  4881.3  455.98  4895.8  455.75    4923  453.04  4929.2  451.82
  4962.5  449.58  4967.7  449.64  4985.6  447.86  4994.6  447.31  5025.5   447.3
  5025.8   446.8  5029.3   446.8  5029.5   447.3  5036.2  447.44    5059  447.52
  5080.1  448.12  5090.6  448.54  5134.3  451.37  5174.7  452.17  5225.1  454.53
  5237.7  454.55  5262.4  455.53  5289.2  457.13  5300.8  457.47  5326.3  457.34
#Mann= 5 ,-1 , 0
  4743.8     .05       0  4849.5     .12       0  5025.5     .07       0
  5029.5     .12       0  5036.2     .05       0
Bank Sta=5025.5,5029.5
XS Rating Curve= 0 ,0
Exp/Cntr=0.3,0.1

Type RM Length L Ch R = 1 ,2783    ,42,42,42
BEGIN DESCRIPTION:
Lacy 072 2254
END DESCRIPTION:
XS GIS Cut Line= 3
       2752082.2       6882165.5      2752098.58      6882519.14
      2752212.64      6882747.41
#Sta/Elev= 30
  4654.1  458.61  4739.7  456.43  4779.7  454.21  4859.8  450.56  4866.1  449.92
  4872.7  449.24  4889.9   447.9  4919.9   448.1  4939.9  447.59  4970.8  447.85
    5000  447.38    5035  447.33  5035.3  446.83  5038.8  446.83    5039  447.33
  5066.4  448.56  5081.8   449.2  5088.5  450.11  5098.5  450.36  5126.5   452.4
  5165.6  452.93  5171.2  453.17  5177.9  454.05    5188  454.04  5193.6  454.67
  5215.9  455.53  5232.7  457.24  5255.1  457.76  5260.7  457.04  5263.3  457.73
#Mann= 7 ,-1 , 0
  4654.1     .05       0  4866.1     .12       0  4872.7     .05       0
  4970.8     .12       0    5035     .07       0    5039     .12       0
  5066.4     .05       0
Bank Sta=5035,5039
XS Rating Curve= 0 ,0
Exp/Cntr=0.3,0.1

Type RM Length L Ch R = 1 ,2741    ,58,58,58
BEGIN DESCRIPTION:
Lacy 072 2253
END DESCRIPTION:
XS GIS Cut Line= 3
      2752070.68      6882156.52      2752060.37      6882521.68
       2752214.9        6882806.
#Sta/Elev= 30
  4662.7  458.09  4777.2  454.98  4807.2  453.28  4867.3  451.12  4887.3  448.86
  4904.3  448.97  4947.3  449.74    5004  448.71    5009  450.28    5028  450.16
  5031.1  449.13  5047.3  449.73    5053  448.49  5069.1  448.54  5082.1  447.38
  5082.4  446.88  5085.9  446.88  5086.1  447.38  5106.9  448.12  5119.2  449.32
  5200.2   452.8  5216.4  454.09  5232.1  454.28  5260.1  456.72  5276.3   456.2
    5289  457.68  5303.8  457.95    5320  457.16  5341.8  457.56  5351.6  458.28
#Mann= 5 ,-1 , 0
  4662.7     .05       0  4904.3     .12       0  5082.1     .07       0
  5086.1     .12       0  5119.2     .05       0
Bank Sta=5082.1,5086.1
XS Rating Curve= 0 ,0
Exp/Cntr=0.3,0.1

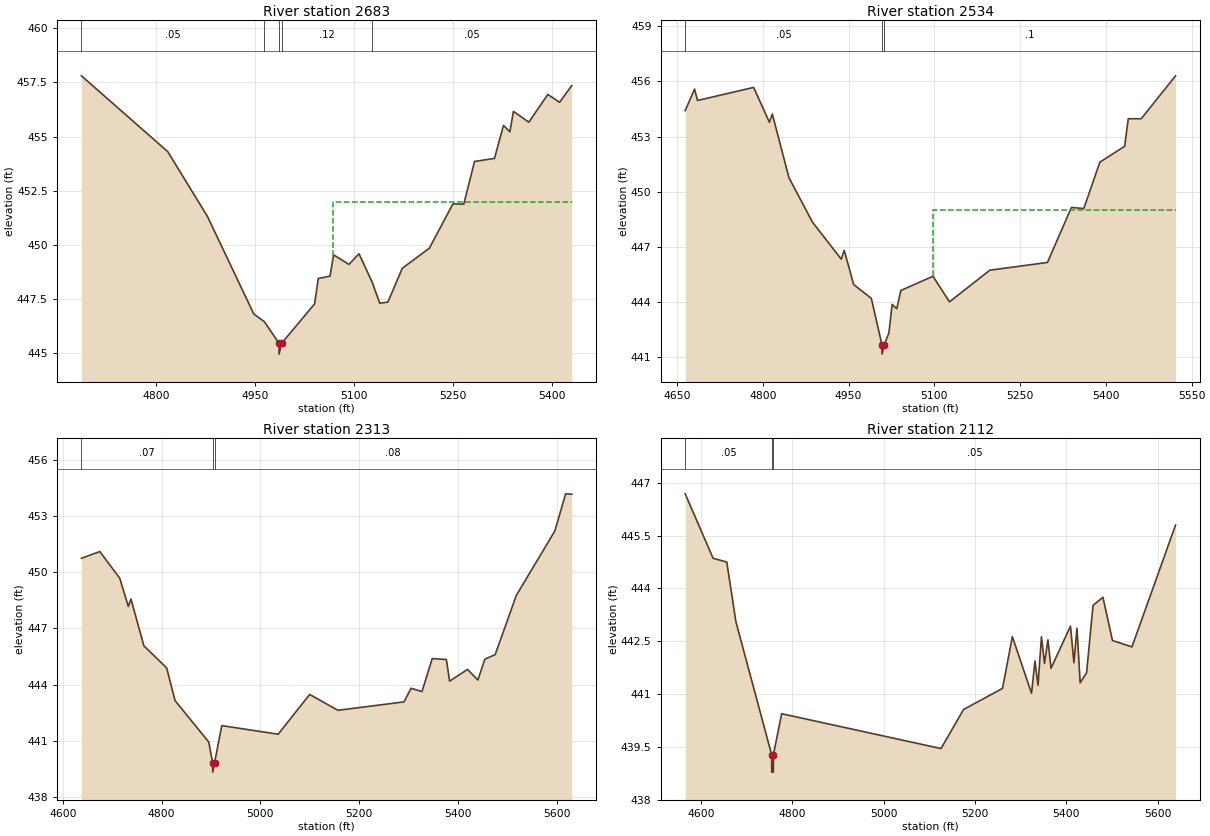
Type RM Length L Ch R = 1 ,2683    ,149,149,149
BEGIN DESCRIPTION:
Lacy 072 2265
END DESCRIPTION:
XS GIS Cut Line= 3
      2752034.14      6882150.47      2752013.36      6882463.39
      2752187.28      6882855.55
#Sta/Elev= 30
  4687.3   457.8  4818.1   454.3  4878.2  451.31  4948.4  446.81  4964.3  446.46
  4986.5  445.46  4986.7  444.96  4990.5  445.46  5040.5  447.28    5046  448.45
  5063.8  448.56  5069.2  449.54  5092.5   449.1  5107.7  449.59  5127.5  448.29
  5139.1  447.31  5151.4  447.36  5173.3  448.92  5214.3  449.85  5249.9  451.89
  5266.4  451.88  5282.7  453.85  5312.9  453.99  5326.5  455.51  5336.2  455.22
  5341.6  456.16  5364.9  455.66  5393.7  456.94  5411.5  456.58  5429.9  457.35
#Mann= 5 ,-1 , 0
  4687.3     .05       0  4964.3     .12       0  4986.5     .07       0
  4990.5     .12       0  5127.5     .05       0
#XS Ineff= 2 , 0
       0                    5069       0     452
Permanent Ineff=
       F       F
Bank Sta=4986.5,4990.5
XS Rating Curve= 0 ,0
Exp/Cntr=0.3,0.1

Type RM Length L Ch R = 1 ,2534    ,221,221,221
BEGIN DESCRIPTION:
Lacy 072 2264
END DESCRIPTION:
XS GIS Cut Line= 3
      2751786.07      6882134.59      2751872.16      6882491.57
      2752175.02      6882877.14
#Sta/Elev= 30
  4664.3  454.41  4680.7  455.58  4685.8  454.96    4784  455.67  4811.5  453.78
  4816.7  454.22  4845.8  450.76  4886.9  448.35  4937.2  446.34  4942.4  446.82
  4958.9  444.96  4989.8  444.21  5008.4  441.68  5008.6  441.18  5012.4  441.68
  5020.6  442.34  5026.2  443.88  5034.3  443.65  5041.5  444.64  5097.6  445.41
  5126.5  444.02    5197  445.74  5297.8  446.16  5339.8  449.15  5361.4  449.09
  5389.5  451.61  5432.8  452.47  5439.2  453.97  5461.8  453.97  5521.8   456.3
#Mann= 3 ,-1 , 0
  4664.3     .05       0  5008.4     .08       0  5012.4      .1       0
#XS Ineff= 2 , 0
       0                    5097       0     449
Permanent Ineff=
       F       F
Bank Sta=5008.4,5012.4
XS Rating Curve= 0 ,0
Exp/Cntr=0.3,0.1

Type RM Length L Ch R = 1 ,2313    ,201,201,201
BEGIN DESCRIPTION:
Lacy 072 2263
END DESCRIPTION:
XS GIS Cut Line= 3
      2751550.28       6882177.4      2751665.64      6882520.63
       2752145.4      6882929.57
#Sta/Elev= 30
  4637.9  450.76  4675.1  451.12  4715.5  449.69  4732.8  448.18  4738.1  448.58
  4764.4  446.07  4810.5  444.89  4827.4  443.14  4895.7  440.92  4903.4  439.81
  4903.7  439.31  4907.4  439.81    4922   441.8  5036.2  441.34  5099.9  443.47
    5157  442.62  5290.9  443.07  5305.2   443.8  5327.2  443.62    5348  445.39
  5376.6  445.34  5383.2  444.18  5419.4  444.81  5440.3  444.24  5454.6  445.36
  5475.4   445.6  5518.2  448.77  5596.2  452.22    5618  454.21  5630.4  454.19
#Mann= 3 ,-1 , 0
  4637.9     .07       0  4903.4     .12       0  4907.4     .08       0
Bank Sta=4903.4,4907.4
XS Rating Curve= 0 ,0
Exp/Cntr=0.3,0.1

Type RM Length L Ch R = 1 ,2112    ,0,0,0
BEGIN DESCRIPTION:
Lacy 072 2262
END DESCRIPTION:
XS GIS Cut Line= 3
      2751488.11      6882200.12      2751504.12      6882630.02
      2751980.82      6883060.65
#Sta/Elev= 30
  4566.1  446.69    4627  444.86    4657  444.75  4677.1  443.05  4755.1  439.28
  4755.4  438.78  4758.9  438.78  4759.1  439.28  4777.1  440.44  5125.7  439.45
    5175  440.56  5260.2  441.16  5281.8  442.63  5323.7  441.02  5331.2  441.94
  5337.9  441.25  5345.4  442.63  5352.1  441.87  5359.6  442.54  5366.3  441.73
  5408.9  442.93  5416.4  441.89  5423.1  442.87  5430.1  441.32  5444.1   441.6
  5458.3  443.52  5479.9  443.75  5500.8  442.52  5543.4  442.34  5638.7   445.8
#Mann= 3 ,-1 , 0
  4566.1     .05       0  4755.1     .05       0  4759.1     .05       0
Bank Sta=4755.1,4759.1
XS Rating Curve= 0 ,0
Exp/Cntr=0.3,0.1

Chan Stop Cuts=-1
Use User Specified Reach Order=0
Composite Channel Slope=5