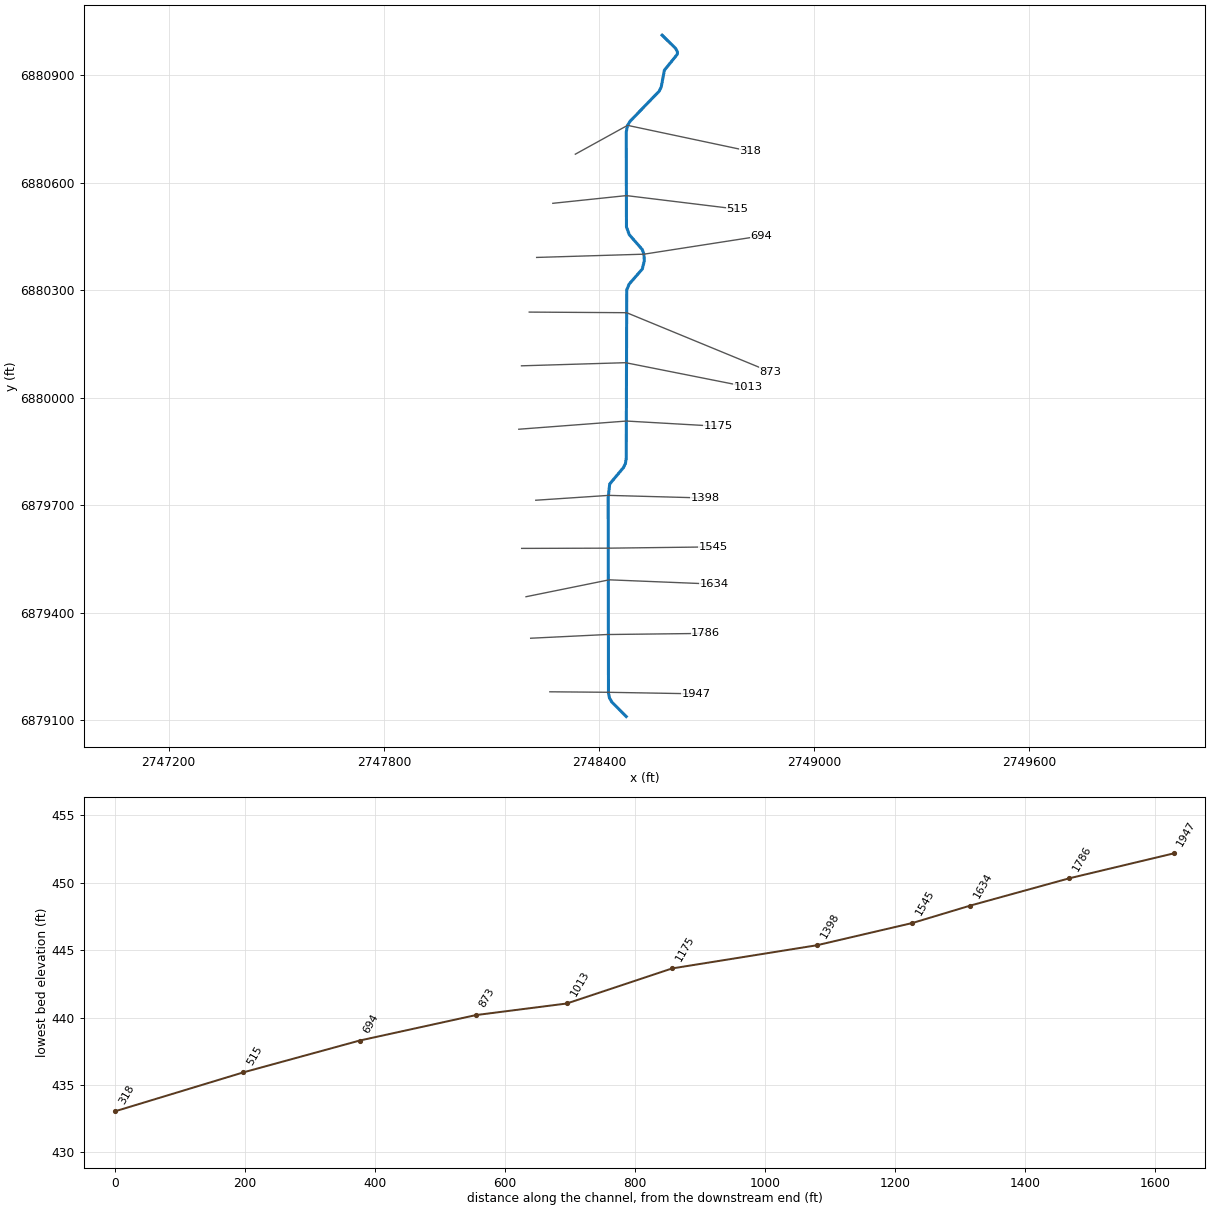
--- Lacy 073.prj (project) ---

Proj Title=Lacy 073 Base Level Engineering
Current Plan=p01
Default Exp/Contr=0.3,0.1
English Units
Geom File=g01
Flow File=f01
Plan File=p01
Y Axis Title=Elevation
X Axis Title(PF)=Main Channel Distance
X Axis Title(XS)=Station
BEGIN DESCRIPTION:
Lacy 073
END DESCRIPTION:
DSS Export Rating Curves= 0
DSS Export Rating Curve Sorted= 0
DSS Export Volume Flow Curves= 0
DXF OffsetX= 0
DXF OffsetY= 0
DXF ScaleX= 1
DXF ScaleY= 10

--- Lacy 073.p01 (plan) ---

Plan Title=Multiple Run
Short Identifier=Multiple
Geom File=g01
Flow File=f01
Subcritical Flow
K Sum by GR= 0
Std Step Tol= 0.01
Critical Tol= 0.01
Num of Std Step Trials= 20
Max Error Tol= 0.3
Flow Tol Ratio= 0.001
Split Flow NTrial= 30
Split Flow Tol= 0.02
Split Flow Ratio= 0.02
Log Output Level= 0
Friction Slope Method= 1
Unsteady Friction Slope Method= 2
Unsteady Bridges Friction Slope Method= 1
Parabolic Critical Depth
Global Vel Dist=  1 , 1 , 1
Global Log Level= 0
CheckData=True
Encroach Param= -1, 0, 0, 0
BEGIN DESCRIPTION:
Multiple Run
END DESCRIPTION:

--- Lacy 073.f01 (steady flow) ---

Flow Title=Multiple
Number of Profiles=7
Profile Names=10-year,25-year,50-year,1pct_min,100-year,1pct_plu,500-year
River Rch & RM= Lacy 073,Reach-1,1947
     114     138     155      88     175     348     220
Boundary for River Rch & Prof#=Lacy 073,Reach-1,1
Up Type=0
Dn Type=3
Dn Slope=0.005
Boundary for River Rch & Prof#=Lacy 073,Reach-1,2
Up Type=0
Dn Type=3
Dn Slope=0.005
Boundary for River Rch & Prof#=Lacy 073,Reach-1,3
Up Type=0
Dn Type=3
Dn Slope=0.005
Boundary for River Rch & Prof#=Lacy 073,Reach-1,4
Up Type=0
Dn Type=3
Dn Slope=0.005
Boundary for River Rch & Prof#=Lacy 073,Reach-1,5
Up Type=0
Dn Type=3
Dn Slope=0.005
Boundary for River Rch & Prof#=Lacy 073,Reach-1,6
Up Type=0
Dn Type=3
Dn Slope=0.005
Boundary for River Rch & Prof#=Lacy 073,Reach-1,7
Up Type=0
Dn Type=3
Dn Slope=0.005

--- Lacy 073.g01 (geometry) ---

Geom Title=Existing Conditions
Program Version=4.10

River Reach=Lacy 073        ,Reach-1
Reach XY= 27
        2748476.        6879111.      2748436.05      6879151.02
      2748429.29      6879162.36      2748426.36      6879176.15
      2748425.55      6879721.19      2748429.78      6879759.43
      2748467.86      6879804.94      2748473.74      6879816.94
      2748475.93      6879831.03      2748477.24       6880300.5
      2748484.19      6880317.08      2748520.62      6880358.82
      2748526.28      6880381.18      2748525.23      6880400.31
      2748520.62      6880413.18      2748484.19      6880454.92
      2748476.54      6880476.21      2748475.96      6880741.02
      2748479.55      6880759.53       2748486.5      6880770.79
      2748567.86      6880854.96      2748573.54      6880867.05
      2748582.29      6880913.31      2748618.42       6880957.8
       2748618.8      6880964.44      2748613.33       6880974.4
        2748576.        6881011.

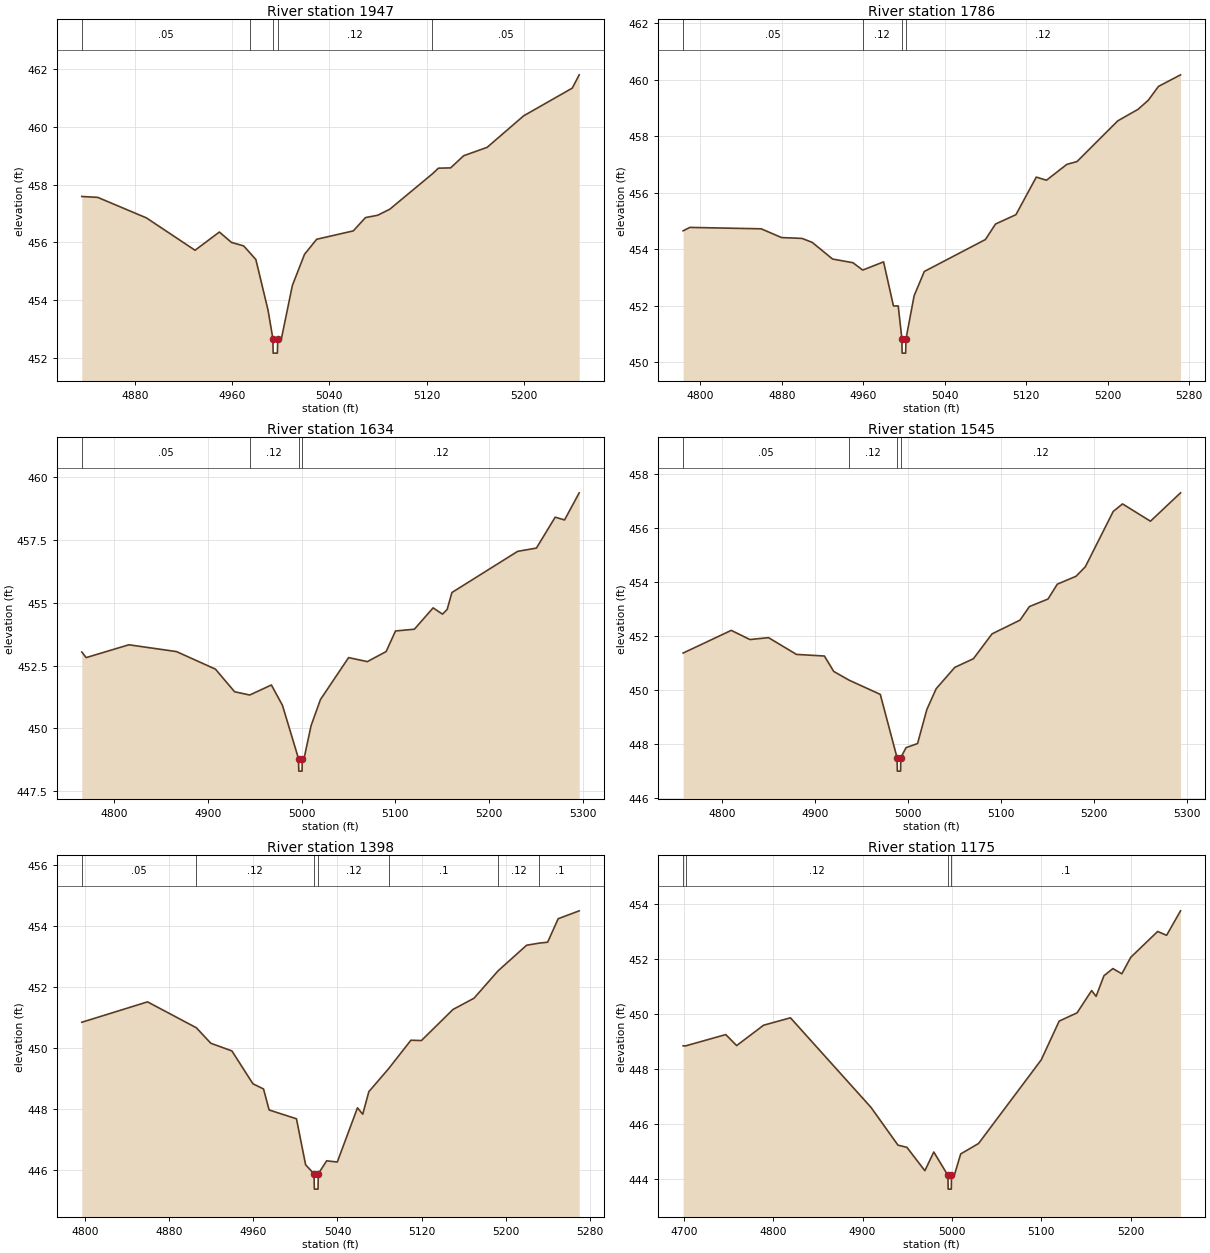
Type RM Length L Ch R = 1 ,1947    ,161,161,161
BEGIN DESCRIPTION:
Lacy 073 2240
END DESCRIPTION:
XS GIS Cut Line= 3
      2748262.86      6879179.97      2748422.86      6879178.62
      2748671.72      6879174.26
#Sta/Elev= 30
  4836.5  457.59  4849.6  457.56  4889.6  456.85  4929.6  455.73  4949.6  456.36
  4959.6     456  4969.6  455.88  4974.5  455.65  4979.6  455.41  4989.6  453.66
  4993.6  452.67  4993.8  452.17  4997.3  452.17  4997.6  452.67  5000.6  452.67
  5009.6  454.51  5019.6  455.59  5029.6  456.11  5059.7   456.4  5069.7  456.86
  5079.7  456.94  5089.7  457.15  5124.6  458.37  5129.7  458.57  5139.7  458.58
  5150.4     459  5169.7  459.29  5199.7  460.38  5239.7  461.34  5245.4   461.8
#Mann= 5 ,-1 , 0
  4836.5     .05       0  4974.5     .12       0  4993.6     .07       0
  4997.6     .12       0  5124.6     .05       0
Bank Sta=4993.6,4997.6
XS Rating Curve= 0 ,0
Exp/Cntr=0.3,0.1

Type RM Length L Ch R = 1 ,1786    ,152,152,152
BEGIN DESCRIPTION:
Lacy 073 2243
END DESCRIPTION:
XS GIS Cut Line= 3
      2748209.37      6879329.34      2748420.45      6879339.62
       2748697.7      6879342.84
#Sta/Elev= 30
    4783  454.65  4789.6  454.77  4859.7  454.72  4879.7  454.41  4899.8  454.38
  4909.8  454.24  4929.8  453.65  4949.8  453.52  4959.4  453.26  4979.9  453.55
  4989.6  451.99  4994.3  451.99  4997.9  450.82  4998.1  450.32  5001.6  450.32
  5001.9  450.82  5009.9  452.35  5019.9  453.21  5079.9  454.34  5089.9  454.89
  5109.9  455.22  5129.9  456.55  5139.9  456.44  5159.9     457  5169.9   457.1
  5209.9  458.54  5229.9  458.95  5239.9  459.27  5249.9  459.76  5271.6  460.17
#Mann= 4 ,-1 , 0
    4783     .05       0  4959.4     .12       0  4997.9     .07       0
  5001.9     .12       0
Bank Sta=4997.9,5001.9
XS Rating Curve= 0 ,0
Exp/Cntr=0.3,0.1

Type RM Length L Ch R = 1 ,1634    ,89,89,89
BEGIN DESCRIPTION:
Lacy 073 2242
END DESCRIPTION:
XS GIS Cut Line= 3
      2748196.38      6879445.07      2748428.51      6879492.22
      2748721.59      6879480.27
#Sta/Elev= 30
  4765.8  453.04  4770.5  452.82    4816  453.33  4866.7  453.06  4908.3  452.36
  4928.7  451.46  4944.8  451.33  4967.9  451.73  4979.7  450.92  4996.8   448.8
  4997.1   448.3  5000.6   448.3  5000.8   448.8  5002.7   448.8  5010.2  450.11
  5020.2  451.15  5050.2  452.82  5070.2  452.66  5090.2  453.06  5100.2  453.88
  5120.3  453.95  5140.3   454.8  5150.3  454.55  5155.3  454.74  5160.3  455.41
  5230.4  457.05  5250.4  457.18  5270.4  458.41  5280.4   458.3    5296  459.38
#Mann= 4 ,-1 , 0
  4765.8     .05       0  4944.8     .12       0  4996.8     .07       0
  5000.8     .12       0
Bank Sta=4996.8,5000.8
XS Rating Curve= 0 ,0
Exp/Cntr=0.3,0.1

Type RM Length L Ch R = 1 ,1545    ,147,147,147
BEGIN DESCRIPTION:
Lacy 073 2241
END DESCRIPTION:
XS GIS Cut Line= 3
      2748184.26      6879579.85      2748426.39      6879580.49
      2748718.34      6879584.06
#Sta/Elev= 30
  4758.5  451.38  4810.2  452.22  4830.2  451.88  4850.2  451.95  4880.2  451.33
  4910.2  451.27  4920.2   450.7  4936.5  450.38  4970.2  449.85  4988.2  447.51
  4988.5  447.01    4992  447.01  4992.2  447.51  4997.9  447.88  5010.2  448.03
  5020.2  449.29  5030.2  450.06  5050.2  450.85  5070.2  451.17  5090.2  452.09
  5120.3   452.6  5130.3   453.1  5150.3  453.38  5160.3  453.93  5180.3  454.22
  5190.3  454.57  5220.3  456.62  5230.3   456.9  5260.3  456.26  5292.6  457.31
#Mann= 4 ,-1 , 0
  4758.5     .05       0  4936.5     .12       0  4988.2     .07       0
  4992.2     .12       0
Bank Sta=4988.2,4992.2
XS Rating Curve= 0 ,0
Exp/Cntr=0.3,0.1

Type RM Length L Ch R = 1 ,1398    ,223,223,223
BEGIN DESCRIPTION:
Lacy 073 2239
END DESCRIPTION:
XS GIS Cut Line= 3
      2748223.61      6879714.15      2748427.24      6879727.71
      2748695.96      6879720.33
#Sta/Elev= 30
  4796.9  450.84  4859.4  451.51  4905.8  450.66  4919.6  450.15  4939.6   449.9
  4959.6  448.82  4969.7  448.65    4975  447.96    5001  447.67  5009.7  446.16
  5017.7  445.86    5018  445.36  5021.5  445.36  5021.7  445.86  5029.7  446.29
  5039.8  446.25    5059  448.03    5064  447.82  5069.8  448.56  5088.7  449.32
  5109.8  450.25  5119.8  450.24  5149.8  451.26  5169.8  451.63  5192.7  452.53
  5219.8  453.37    5232  453.44  5239.8  453.47  5249.8  454.24  5269.8   454.5
#Mann= 7 ,-1 , 0
  4796.9     .05       0  4905.8     .12       0  5017.7     .07       0
  5021.7     .12       0  5088.7      .1       0  5192.7     .12       0
    5232      .1       0
Bank Sta=5017.7,5021.7
XS Rating Curve= 0 ,0
Exp/Cntr=0.3,0.1

Type RM Length L Ch R = 1 ,1175    ,162,162,162
BEGIN DESCRIPTION:
Lacy 073 2238
END DESCRIPTION:
XS GIS Cut Line= 3
      2748176.28      6879912.16      2748476.54      6879934.98
       2748731.6       6879920.4
#Sta/Elev= 30
  4699.2  448.85  4702.1  448.85  4746.9  449.26  4759.1  448.86  4789.2   449.6
  4819.3  449.87  4909.5  446.61  4939.6  445.24  4949.6  445.16  4969.7  444.31
  4979.7  444.99  4995.5  444.14  4995.8  443.64  4999.3  443.64  4999.5  444.14
  5002.6  444.14  5009.8  444.92  5029.8   445.3  5099.9  448.34    5120  449.75
    5140  450.05  5156.3  450.86  5161.3  450.65  5170.1   451.4  5180.1  451.66
  5190.1  451.47  5200.1  452.07  5230.2  453.01  5240.2  452.87  5255.8  453.76
#Mann= 4 ,-1 , 0
  4699.2     .05       0  4702.1     .12       0  4995.5     .07       0
  4999.5      .1       0
Bank Sta=4995.5,4999.5
XS Rating Curve= 0 ,0
Exp/Cntr=0.3,0.1

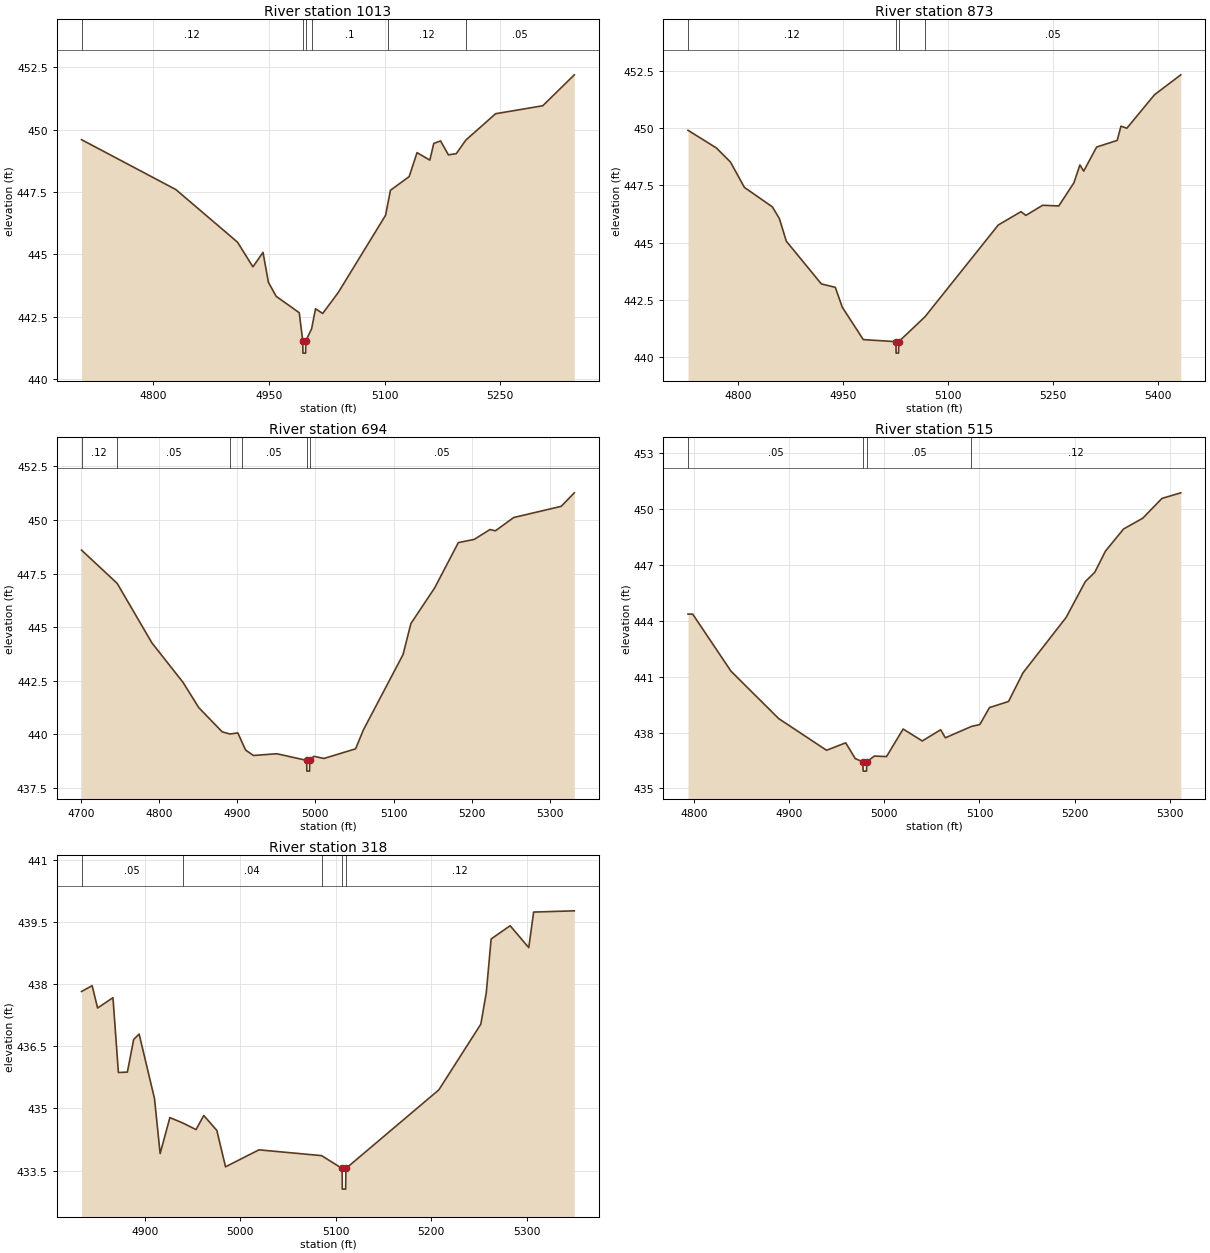
Type RM Length L Ch R = 1 ,1013    ,140,140,140
BEGIN DESCRIPTION:
Lacy 073 2237
END DESCRIPTION:
XS GIS Cut Line= 3
      2748183.75      6880088.99      2748474.09      6880097.71
      2748816.14      6880029.76
#Sta/Elev= 30
  4706.9   449.6  4829.2   447.6  4909.2  445.49  4929.2   444.5  4942.3  445.08
  4949.3  443.88  4959.3  443.32  4989.3  442.66  4993.8  441.54  4994.1  441.04
  4997.6  441.04  4997.8  441.54  5005.3  442.01  5010.4  442.82  5019.7  442.63
  5040.1  443.48  5101.3  446.57  5103.9  446.98  5107.6  447.57  5131.9  448.12
  5142.1  449.08  5158.7  448.78  5163.8  449.45  5172.6  449.55  5182.8  448.99
    5193  449.04  5205.3  449.58    5244  450.64  5305.2  450.96  5346.1   452.2
#Mann= 6 ,-1 , 0
  4706.9     .12       0  4993.8     .07       0  4997.8     .12       0
  5005.3      .1       0  5103.9     .12       0  5205.3     .05       0
Bank Sta=4993.8,4997.8
XS Rating Curve= 0 ,0
Exp/Cntr=0.3,0.1

Type RM Length L Ch R = 1 ,873     ,179,179,179
BEGIN DESCRIPTION:
Lacy 073 2247
END DESCRIPTION:
XS GIS Cut Line= 3
      2748205.37      6880238.81      2748477.06      6880237.13
      2748877.25      6880072.32
#Sta/Elev= 30
  4728.3   449.9  4768.9  449.13  4788.9  448.52  4808.9  447.41  4848.9  446.56
  4858.9  446.05  4868.9  445.06  4918.9   443.2  4938.9  443.05  4948.9  442.18
  4978.9  440.77  5025.6  440.68  5025.8  440.18  5029.3  440.18  5029.6  440.68
  5067.2  441.77  5171.9  445.77  5204.3  446.35  5211.4  446.19  5235.3  446.63
  5258.4   446.6    5280  447.61  5288.6  448.39    5294  448.12  5312.5  449.17
  5341.9  449.46  5347.3  450.08  5355.7  449.99  5395.2  451.45  5432.8  452.32
#Mann= 4 ,-1 , 0
  4728.3     .12       0  5025.6     .07       0  5029.6     .12       0
  5067.2     .05       0
Bank Sta=5025.6,5029.6
XS Rating Curve= 0 ,0
Exp/Cntr=0.3,0.1

Type RM Length L Ch R = 1 ,694     ,179,179,179
BEGIN DESCRIPTION:
Lacy 073 2246
END DESCRIPTION:
XS GIS Cut Line= 3
      2748226.07      6880391.22      2748525.23      6880400.31
      2748852.59      6880451.26
#Sta/Elev= 30
  4700.7  448.59  4746.3  447.04  4790.7  444.27  4830.7  442.42  4850.7  441.25
  4880.7  440.12  4890.6  440.02  4900.7  440.07  4905.9  439.65  4910.7  439.27
  4920.7  439.02  4950.7   439.1  4988.8  438.79    4989  438.29  4992.5  438.29
  4992.8  438.79  4997.9  438.98  5010.9  438.88  5051.4  439.33  5061.5  440.22
  5112.1  443.72  5122.2  445.17  5152.6  446.83  5182.9  448.94  5203.2  449.09
  5223.4  449.55  5230.3  449.49  5253.8  450.11  5314.5  450.63  5331.3  451.26
#Mann= 6 ,-1 , 0
  4700.7     .12       0  4746.3     .05       0  4890.6     .12       0
  4905.9     .05       0  4988.8     .04       0  4992.8     .05       0
Bank Sta=4988.8,4992.8
XS Rating Curve= 0 ,0
Exp/Cntr=0.3,0.1

Type RM Length L Ch R = 1 ,515     ,197,197,197
BEGIN DESCRIPTION:
Lacy 073 2245
END DESCRIPTION:
XS GIS Cut Line= 3
      2748271.17      6880542.16      2748476.35      6880563.67
      2748785.65      6880525.92
#Sta/Elev= 30
  4793.7  444.36  4798.6  444.36  4838.8   441.3    4889  438.75  4939.3  437.05
  4959.4  437.45  4969.5   436.6  4977.5  436.43  4977.8  435.93  4981.3  435.93
  4981.5  436.43  4989.6  436.74  5002.3  436.71  5019.8  438.19  5039.9  437.55
  5059.2  438.15  5064.2  437.72  5091.6  438.33  5100.4  438.43  5110.5  439.34
  5130.6  439.67  5145.8  441.21  5191.1  444.18  5211.2   446.1  5221.3  446.61
  5232.4  447.74  5251.5  448.93  5271.7  449.51  5291.8  450.57  5311.6  450.87
#Mann= 4 ,-1 , 0
  4793.7     .05       0  4977.5     .04       0  4981.5     .05       0
  5091.6     .12       0
Bank Sta=4977.5,4981.5
XS Rating Curve= 0 ,0
Exp/Cntr=0.3,0.1

Type RM Length L Ch R = 1 ,318     ,0,0,0
BEGIN DESCRIPTION:
Lacy 073 2244
END DESCRIPTION:
XS GIS Cut Line= 3
      2748333.95      6880679.17      2748479.55      6880759.53
      2748821.74      6880686.98
#Sta/Elev= 30
  4833.7  437.83  4844.8  437.97  4850.5  437.43  4866.6  437.68  4872.3  435.87
  4881.7  435.88  4888.3  436.67    4894   436.8  4910.1  435.24    4916  433.91
  4926.2  434.78  4939.7  434.65  4953.6  434.49  4961.7  434.83  4975.4  434.47
  4984.5  433.59  5019.5     434  5085.1  433.86  5106.6  433.55  5106.8  433.05
  5110.3  433.05  5110.6  433.55  5207.9  435.45  5251.9  437.04  5257.6   437.8
  5262.7   439.1  5282.6  439.42  5302.1  438.89  5307.2  439.75  5349.8  439.78
#Mann= 5 ,-1 , 0
  4833.7     .05       0  4939.7     .04       0  5085.1     .05       0
  5106.6     .07       0  5110.6     .12       0
Bank Sta=5106.6,5110.6
XS Rating Curve= 0 ,0
Exp/Cntr=0.3,0.1

Chan Stop Cuts=-1
Use User Specified Reach Order=0
Composite Channel Slope=5