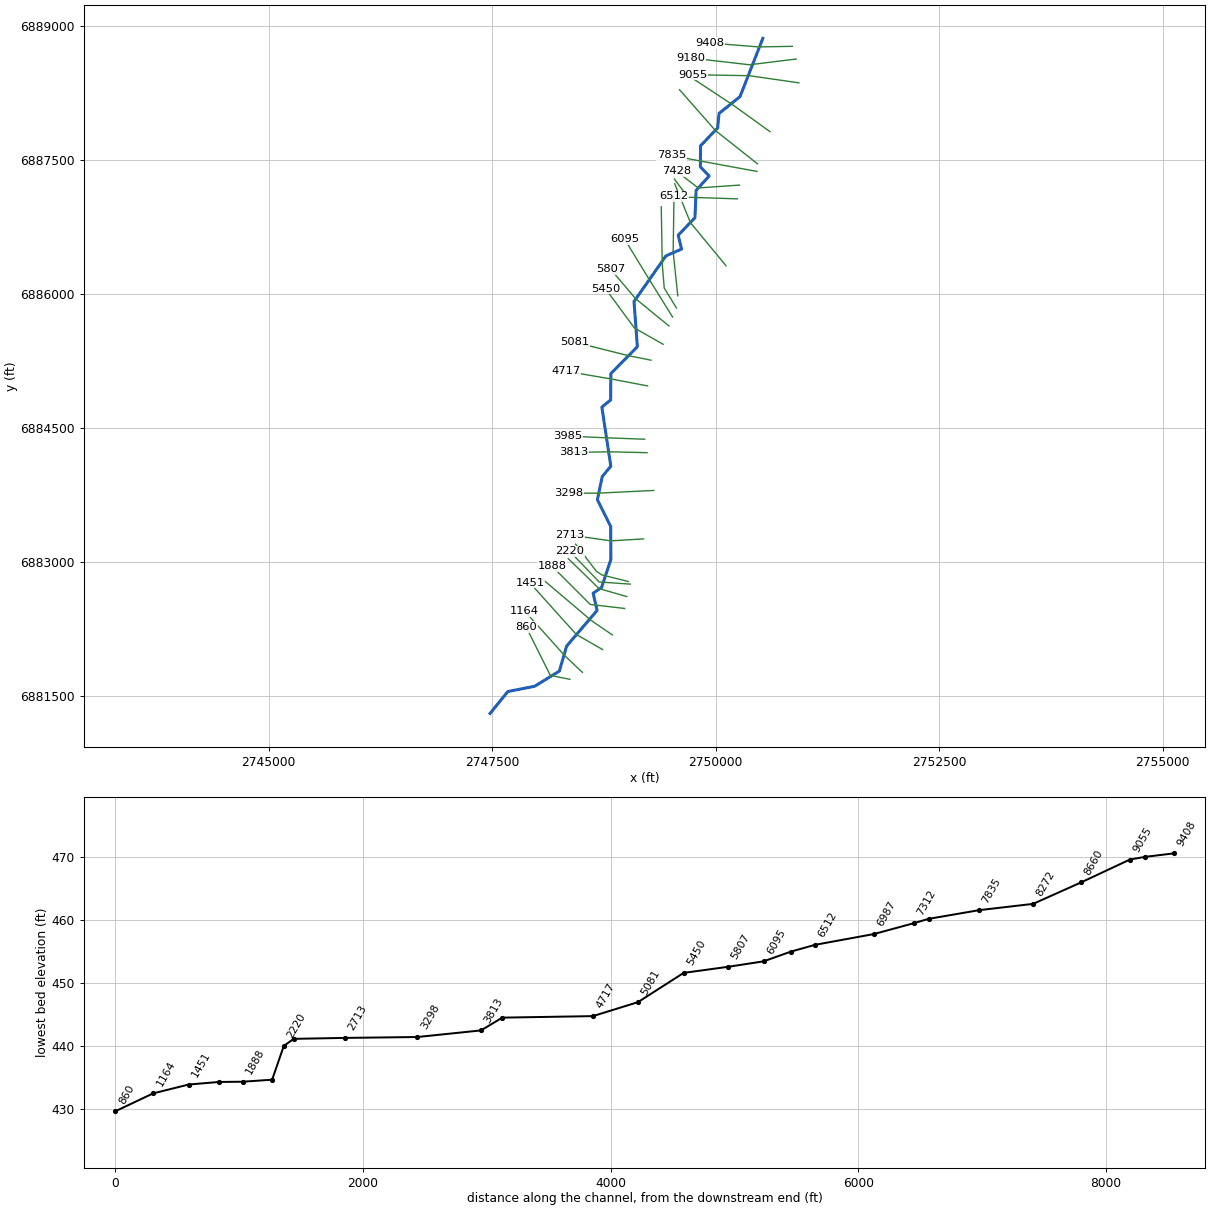
--- Lacy 074.prj (project) ---

Proj Title=Lacy 074 Base Level Engineering
Current Plan=p01
Default Exp/Contr=0.3,0.1
English Units
Geom File=g01
Flow File=f01
Plan File=p01
Y Axis Title=Elevation
X Axis Title(PF)=Main Channel Distance
X Axis Title(XS)=Station
BEGIN DESCRIPTION:
Lacy 074
END DESCRIPTION:
DSS Export Rating Curves= 0
DSS Export Rating Curve Sorted= 0
DSS Export Volume Flow Curves= 0
DXF OffsetX= 0
DXF OffsetY= 0
DXF ScaleX= 1
DXF ScaleY= 10

--- Lacy 074.p01 (plan) ---

Plan Title=Multiple Run
Short Identifier=Multiple
Geom File=g01
Flow File=f01
Subcritical Flow
K Sum by GR= 0
Std Step Tol= 0.01
Critical Tol= 0.01
Num of Std Step Trials= 20
Max Error Tol= 0.3
Flow Tol Ratio= 0.001
Split Flow NTrial= 30
Split Flow Tol= 0.02
Split Flow Ratio= 0.02
Log Output Level= 0
Friction Slope Method= 1
Unsteady Friction Slope Method= 2
Unsteady Bridges Friction Slope Method= 1
Parabolic Critical Depth
Global Vel Dist=  1 , 1 , 1
Global Log Level= 0
CheckData=True
Encroach Param= -1, 0, 0, 0
BEGIN DESCRIPTION:
Multiple Run
END DESCRIPTION:

--- Lacy 074.f01 (steady flow) ---

Flow Title=Multiple
Number of Profiles=7
Profile Names=10-year,25-year,50-year,1pct_min,100-year,1pct_plu,500-year
River Rch & RM= Lacy 074,Reach-1,9408
     293     373     434     252     502    1002     672
River Rch & RM= Lacy 074,Reach-1,5081
     493     650     775     459     916    1828    1282
Boundary for River Rch & Prof#=Lacy 074,Reach-1,1
Up Type=0
Dn Type=3
Dn Slope=0.005
Boundary for River Rch & Prof#=Lacy 074,Reach-1,2
Up Type=0
Dn Type=3
Dn Slope=0.005
Boundary for River Rch & Prof#=Lacy 074,Reach-1,3
Up Type=0
Dn Type=3
Dn Slope=0.005
Boundary for River Rch & Prof#=Lacy 074,Reach-1,4
Up Type=0
Dn Type=3
Dn Slope=0.005
Boundary for River Rch & Prof#=Lacy 074,Reach-1,5
Up Type=0
Dn Type=3
Dn Slope=0.005
Boundary for River Rch & Prof#=Lacy 074,Reach-1,6
Up Type=0
Dn Type=3
Dn Slope=0.005
Boundary for River Rch & Prof#=Lacy 074,Reach-1,7
Up Type=0
Dn Type=3
Dn Slope=0.005

--- Lacy 074.g01 (geometry) ---

Geom Title=Existing Conditions
Program Version=4.10

River Reach=Lacy 074        ,Reach-1
Reach XY= 30
        2750526.        6888861.      2750270.48      6888208.57
      2750036.35      6888021.12      2750020.53      6887858.55
      2749829.16      6887659.35      2749827.54      6887422.88
      2749925.47      6887321.68      2749779.54      6887159.54
       2749766.7      6886854.33      2749579.46       6886659.5
        2749617.      6886503.94      2749442.46      6886428.13
      2749085.13      6885917.74      2749122.54       6885412.5
        2748826.        6885111.      2748823.99      6884816.68
      2748725.48      6884736.12      2748825.61      6884076.16
      2748729.62       6883959.5      2748675.45      6883700.81
      2748824.78       6883400.5      2748825.94      6883031.03
      2748722.89      6882719.31      2748627.57      6882655.14
      2748672.33      6882462.58      2748331.52      6882063.43
      2748249.95      6881783.81      2747974.53      6881614.55
       2747673.7      6881555.17        2747476.        6881311.

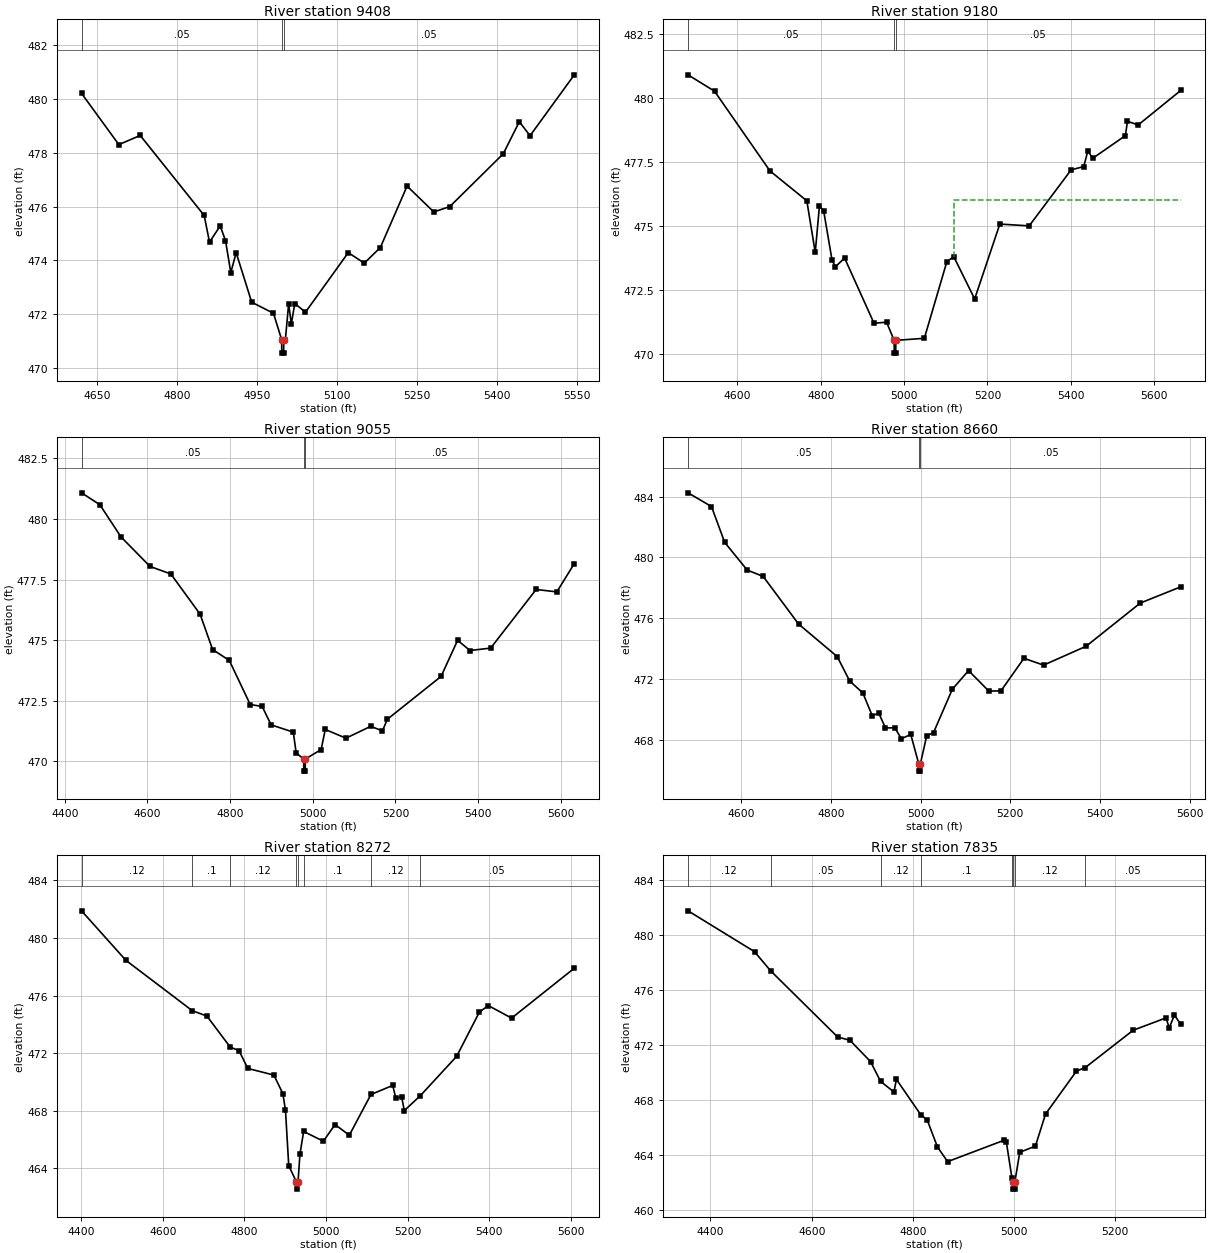
Type RM Length L Ch R = 1 ,9408    ,228,228,228
BEGIN DESCRIPTION:
Lacy 074 2236
END DESCRIPTION:
XS GIS Cut Line= 3
      2750856.04      6888771.63       2750476.2      6888765.02
      2749933.18      6888809.08
#Sta/Elev= 30
  4620.1   480.2  4690.1   478.3  4730.2  478.64  4850.2  475.67  4860.2  474.68
  4880.2  475.28  4890.2  474.74  4900.2  473.55  4910.2  474.29  4939.4  472.45
  4980.2  472.04  4995.6  471.06  4995.8  470.56  4999.3  470.56  4999.6  471.06
  5002.6  471.06  5008.7  472.39  5013.7  471.65  5020.3   472.4  5040.3  472.08
  5120.6  474.29  5150.7   473.9  5180.8  474.48    5231  476.76  5281.1   475.8
  5311.2     476  5411.5  477.96  5441.6  479.15  5461.7  478.63  5544.8  480.89
#Mann= 3 ,-1 , 0
  4620.1     .05       0  4995.6     .04       0  4999.6     .05       0
Bank Sta=4995.6,4999.6
XS Rating Curve= 0 ,0
Exp/Cntr=0.3,0.1

Type RM Length L Ch R = 1 ,9180    ,125,125,125
BEGIN DESCRIPTION:
Lacy 074 2232
END DESCRIPTION:
XS GIS Cut Line= 3
      2750899.09       6888629.8      2750376.97      6888565.23
      2749724.53       6888640.8
#Sta/Elev= 30
  4481.3  480.91  4544.9  480.27    4678  477.15  4766.5  475.98  4786.7  473.96
  4796.8  475.78  4806.9  475.59    4827  473.66  4835.1   473.4  4857.2  473.74
  4927.8  471.19    4958  471.23  4976.1  470.52  4976.4  470.02  4979.9  470.02
  4980.1  470.52  5048.6   470.6  5102.5  473.59  5119.1   473.8  5169.4  472.14
  5229.8  475.07  5300.3     475    5401  477.19  5431.2  477.32  5441.3  477.94
  5452.5  477.64  5531.2  478.53  5536.2  479.09  5562.1  478.95  5664.2   480.3
#Mann= 3 ,-1 , 0
  4481.3     .05       0  4976.1     .04       0  4980.1     .05       0
#XS Ineff= 2 , 0
       0                    5119       0     476
Permanent Ineff=
       F       F
Bank Sta=4976.1,4980.1
XS Rating Curve= 0 ,0
Exp/Cntr=0.3,0.1

Type RM Length L Ch R = 1 ,9055    ,395,395,395
BEGIN DESCRIPTION:
Lacy 074 2231
END DESCRIPTION:
XS GIS Cut Line= 3
      2750929.77      6888362.97      2750375.52       6888443.1
      2749743.72      6888453.82
#Sta/Elev= 30
  4440.7  481.08  4484.9  480.59  4536.1  479.26  4606.4  478.04  4656.7  477.73
  4727.4  476.07  4757.7  474.61  4798.1  474.16  4848.7  472.34  4877.6  472.26
  4899.2   471.5  4952.9   471.2  4959.8  470.34    4978  470.09  4978.3  469.59
  4981.8  469.59    4982  470.09  5020.2  470.48  5030.2  471.31  5080.2  470.95
  5140.2  471.44  5168.5  471.25  5180.3  471.73  5310.3   473.5  5350.3  474.99
  5380.3  474.57  5430.3  474.67  5540.3  477.09  5590.3  476.99  5632.6  478.16
#Mann= 3 ,-1 , 0
  4440.7     .05       0    4978     .05       0    4982     .05       0
Bank Sta=4978,4982
XS Rating Curve= 0 ,0
Exp/Cntr=0.3,0.1

Type RM Length L Ch R = 1 ,8660    ,388,388,388
BEGIN DESCRIPTION:
Lacy 074 2233
END DESCRIPTION:
XS GIS Cut Line= 3
      2750606.25      6887817.45      2750183.04      6888121.53
      2749700.51      6888439.49
#Sta/Elev= 30
  4481.1  484.25  4533.4  483.35  4562.9  480.99  4613.2  479.17  4648.8  478.75
  4727.7  475.62  4813.9  473.48  4841.6  471.88    4871  471.09  4891.9   469.6
  4906.6  469.76  4921.4  468.79  4942.3   468.8    4957  468.08  4977.9  468.36
  4995.5  466.45  4995.7  465.95  4999.2  465.95  4999.5  466.45  5013.5  468.28
  5028.6  468.48  5070.7  471.34  5106.8  472.56  5152.1  471.21  5179.1  471.23
  5230.3  473.37  5274.1  472.92  5368.9  474.16  5489.7     477  5580.1  478.07
#Mann= 3 ,-1 , 0
  4481.1     .05       0  4995.5     .04       0  4999.5     .05       0
Bank Sta=4995.5,4999.5
XS Rating Curve= 0 ,0
Exp/Cntr=0.3,0.1

Type RM Length L Ch R = 1 ,8272    ,437,437,437
BEGIN DESCRIPTION:
Lacy 074 2234
END DESCRIPTION:
XS GIS Cut Line= 3
      2750465.34      6887458.13      2749994.21      6887831.22
      2749593.97      6888286.29
#Sta/Elev= 30
  4400.9  481.89  4509.4  478.45    4672  474.95    4708  474.57  4765.2  472.41
  4786.6  472.17  4808.2  470.93    4872  470.47    4894  469.18  4900.4  468.03
  4908.4  464.17  4927.2  463.04  4927.5  462.54  4931.2  463.04  4935.8  464.96
  4944.9  466.55  4993.3  465.87  5021.7  467.03  5056.8  466.29  5109.8  469.12
  5163.1  469.75  5170.7  468.86  5184.9  468.96  5191.5     468  5230.5  469.03
  5319.6  471.77  5375.6  474.86  5397.4   475.3  5454.3  474.43  5607.9   477.9
#Mann= 8 ,-1 , 0
  4400.9     .12       0    4672      .1       0  4765.2     .12       0
  4927.2     .07       0  4931.2     .12       0  4944.9      .1       0
  5109.8     .12       0  5230.5     .05       0
Bank Sta=4927.2,4931.2
XS Rating Curve= 0 ,0
Exp/Cntr=0.3,0.1

Type RM Length L Ch R = 1 ,7835    ,407,407,407
BEGIN DESCRIPTION:
Lacy 074 2235
END DESCRIPTION:
XS GIS Cut Line= 3
      2750460.76      6887372.32      2749824.23      6887489.42
      2749503.65      6887551.82
#Sta/Elev= 30
  4355.6  481.79    4487  478.82  4518.7  477.43  4651.3  472.61  4675.6  472.37
  4716.3  470.82  4736.1  469.38  4762.5  468.61  4767.5  469.52  4815.4  466.96
  4828.2  466.58  4848.5  464.61  4868.6  463.54  4979.8  465.09  4984.8  464.94
  4995.9  462.32  4997.4  462.04  4997.6  461.54  5001.1  461.54  5001.4  462.04
  5011.2  464.22  5042.1  464.67  5062.1     467  5123.3  470.13  5140.8  470.39
  5235.3   473.1  5300.2     474  5306.6  473.28  5316.8   474.2  5329.4  473.53
#Mann= 8 ,-1 , 0
  4355.6     .12       0  4518.7     .05       0  4736.1     .12       0
  4815.4      .1       0  4995.9     .12       0  4997.4     .07       0
  5001.4     .12       0  5140.8     .05       0
Bank Sta=4997.4,5001.4
XS Rating Curve= 0 ,0
Exp/Cntr=0.3,0.1

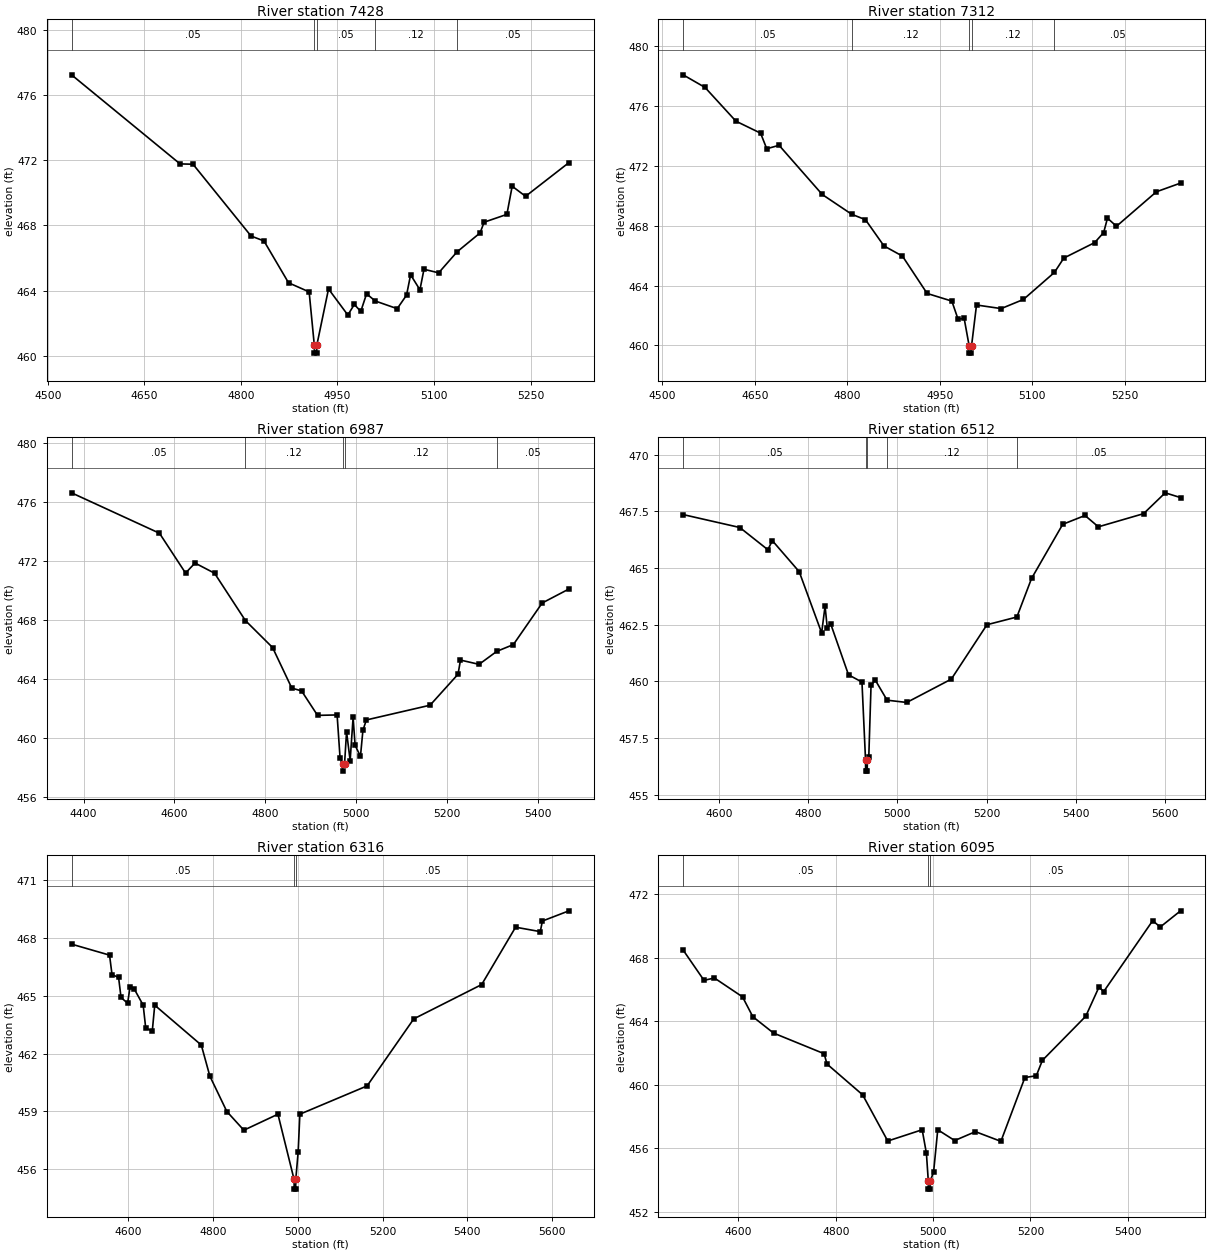
Type RM Length L Ch R = 1 ,7428    ,116,116,116
BEGIN DESCRIPTION:
Lacy 074 2230
END DESCRIPTION:
XS GIS Cut Line= 3
      2750264.21      6887219.49      2749802.91      6887187.57
      2749556.56      6887376.24
#Sta/Elev= 30
    4537  477.25  4705.6  471.78  4725.7  471.76  4815.9  467.35  4835.9  467.05
  4874.1  464.48  4906.1  463.92  4914.1  460.66  4914.4  460.16  4917.9  460.16
  4918.1  460.66  4936.2   464.1  4966.2   462.5  4976.3  463.15  4986.3  462.72
  4995.3   463.8  5008.9  463.36  5042.9  462.89  5057.4  463.72  5063.7  464.97
  5078.2  464.05  5084.5  465.31  5107.3  465.09  5135.9  466.38  5171.6  467.54
  5177.9   468.2  5213.3  468.68  5221.5  470.41  5242.3  469.79  5309.7  471.86
#Mann= 5 ,-1 , 0
    4537     .05       0  4914.1     .05       0  4918.1     .05       0
  5008.9     .12       0  5135.9     .05       0
Bank Sta=4914.1,4918.1
XS Rating Curve= 0 ,0
Exp/Cntr=0.3,0.1

Type RM Length L Ch R = 1 ,7312    ,325,325,325
BEGIN DESCRIPTION:
Lacy 074 2229
END DESCRIPTION:
XS GIS Cut Line= 3
      2750241.53      6887065.68      2749688.79       6887083.5
      2749537.06       6887286.8
#Sta/Elev= 30
  4533.5  478.05    4569  477.21  4619.1  474.96  4659.1  474.16  4669.1  473.12
  4689.1  473.35  4759.1  470.07  4806.9  468.75  4829.2  468.39  4859.2  466.64
  4889.2  465.96  4929.2  463.47  4969.3  462.96  4979.3  461.76  4989.3   461.8
  4997.3  459.99  4997.5  459.49    5001  459.49  5001.3  459.99  5009.3   462.7
  5049.3  462.46  5085.4  463.07  5135.6  464.87  5150.9  465.83  5200.9  466.86
  5215.5  467.53  5221.7  468.49  5236.3  467.95    5301  470.25  5340.2  470.83
#Mann= 5 ,-1 , 0
  4533.5     .05       0  4806.9     .12       0  4997.3     .07       0
  5001.3     .12       0  5135.6     .05       0
Bank Sta=4997.3,5001.3
XS Rating Curve= 0 ,0
Exp/Cntr=0.3,0.1

Type RM Length L Ch R = 1 ,6987    ,475,475,475
BEGIN DESCRIPTION:
Lacy 074 2228
END DESCRIPTION:
XS GIS Cut Line= 3
      2750114.41      6886317.05      2749715.42        6886801.
      2749540.44      6887234.39
#Sta/Elev= 30
  4373.6  476.62  4567.1  473.88  4624.5  471.18  4645.3  471.86  4688.3  471.17
  4756.2  467.96    4816  466.13  4858.3  463.38  4879.8  463.19    4915  461.53
    4958  461.56  4964.5  458.65  4970.4  458.25  4970.6  457.75  4974.4  458.25
  4978.8  460.42  4986.7  458.47  4993.2  461.39  4997.6   459.5  5009.4  458.75
  5014.8  460.52  5022.4  461.22  5162.6  462.22  5224.1  464.32  5229.5  465.28
  5270.4  464.99  5309.3  465.87  5345.9  466.33  5409.3  469.15  5468.2   470.1
#Mann= 5 ,-1 , 0
  4373.6     .05       0  4756.2     .12       0  4970.4     .07       0
  4974.4     .12       0  5309.3     .05       0
Bank Sta=4970.4,4974.4
XS Rating Curve= 0 ,0
Exp/Cntr=0.3,0.1

Type RM Length L Ch R = 1 ,6512    ,196,196,196
BEGIN DESCRIPTION:
Lacy 074 2225
END DESCRIPTION:
XS GIS Cut Line= 3
      2749574.54      6885981.92      2749523.12      6886471.64
      2749532.27      6887095.36
#Sta/Elev= 30
  4519.1  467.36  4646.3  466.79  4709.2  465.81  4719.3  466.21  4779.6  464.84
  4829.9  462.14  4837.6  463.32  4842.6  462.35    4850  462.55  4890.2  460.29
  4920.4  459.97  4928.4  456.54  4928.7  456.04  4932.2  456.04  4932.4  456.54
  4935.7  456.66  4940.8  459.84  4950.5  460.05  4976.8  459.17  5020.9  459.07
  5120.9   460.1  5200.9   462.5    5268  462.84  5300.9  464.54  5370.9  466.93
  5420.9  467.32  5450.9  466.82  5552.3   467.4  5600.9  468.32  5635.3  468.11
#Mann= 5 ,-1 , 0
  4519.1     .05       0  4928.4     .07       0  4932.4     .05       0
  4976.8     .12       0    5268     .05       0
Bank Sta=4928.4,4932.4
XS Rating Curve= 0 ,0
Exp/Cntr=0.3,0.1

Type RM Length L Ch R = 1 ,6316    ,221,221,221
BEGIN DESCRIPTION:
Lacy 074 2227
END DESCRIPTION:
XS GIS Cut Line= 4
      2749560.28      6885843.88       2749422.8      6886069.18
      2749400.76        6886344.      2749389.89      6886976.77
#Sta/Elev= 30
    4467  467.68  4556.6  467.11  4562.4   466.1  4577.9  465.95  4583.7  464.91
  4599.2  464.61    4605  465.48  4614.6  465.36  4635.9  464.51  4641.8  463.33
  4657.3  463.16  4663.1  464.51  4772.9  462.44    4793  460.83  4833.1  458.99
  4873.2  458.02  4953.5  458.85  4991.6  455.46  4991.8  454.96  4995.3  454.96
  4995.6  455.46  5001.2   456.9  5005.2  458.85  5163.7  460.32  5273.7   463.8
  5433.7  465.58  5513.7  468.56  5571.9  468.33  5576.9  468.88  5639.5  469.41
#Mann= 3 ,-1 , 0
    4467     .05       0  4991.6     .04       0  4995.6     .05       0
Bank Sta=4991.6,4995.6
XS Rating Curve= 0 ,0
Exp/Cntr=0.3,0.1

Type RM Length L Ch R = 1 ,6095    ,288,288,288
BEGIN DESCRIPTION:
Lacy 074 2226
END DESCRIPTION:
XS GIS Cut Line= 3
      2749516.48      6885744.09      2749239.45      6886189.44
      2748980.75      6886614.06
#Sta/Elev= 30
  4486.5  468.47  4529.4  466.56  4550.7  466.71  4608.5  465.52  4629.7  464.27
  4672.2  463.24  4776.1  461.94    4782  461.29  4855.2  459.35  4906.8  456.44
  4977.5  457.15  4986.2  455.67  4990.1  453.91  4990.4  453.41  4993.9  453.41
  4994.1  453.91    5001   454.5  5009.5  457.15  5044.3  456.47  5086.9  457.03
  5139.2  456.42  5188.5  460.44  5211.9  460.55  5224.4  461.52  5313.5   464.3
  5340.7  466.14  5350.3  465.85    5451  470.32  5466.5  469.92  5508.2  470.94
#Mann= 3 ,-1 , 0
  4486.5     .05       0  4990.1     .04       0  4994.1     .05       0
Bank Sta=4990.1,4994.1
XS Rating Curve= 0 ,0
Exp/Cntr=0.3,0.1

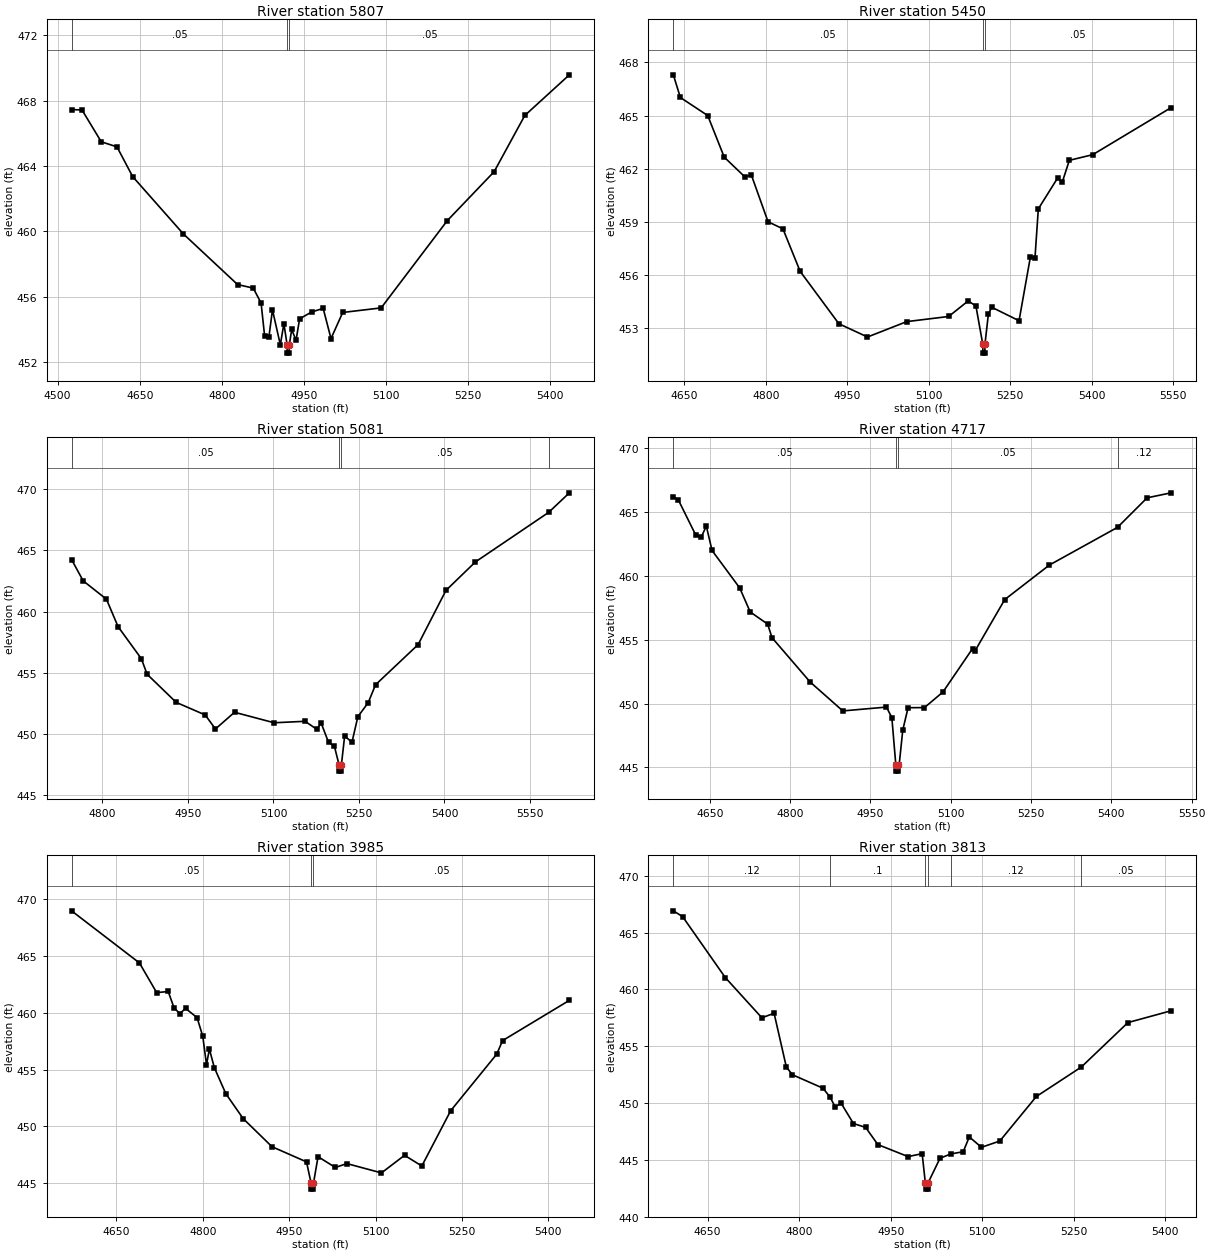
Type RM Length L Ch R = 1 ,5807    ,357,357,357
BEGIN DESCRIPTION:
Lacy 074 2216
END DESCRIPTION:
XS GIS Cut Line= 3
      2749475.82      6885643.97      2749105.38      6885946.79
      2748826.05      6886275.59
#Sta/Elev= 30
  4525.4  467.45  4544.5  467.43  4579.7  465.48  4608.4  465.17  4637.1  463.35
  4729.7  459.84  4828.8  456.74  4857.5  456.52  4871.8  455.61  4878.3  453.58
  4886.2  453.55  4892.6  455.19    4907  453.05  4913.5  454.35  4919.4  453.04
  4919.6  452.54  4923.1  452.54  4923.4  453.04  4927.8  453.99  4935.7  453.32
  4942.2  454.64  4964.3  455.06  4985.3  455.28  4999.6  453.43    5021  455.03
  5091.3  455.31  5212.1  460.65  5297.8  463.65  5353.8  467.09  5435.3  469.58
#Mann= 3 ,-1 , 0
  4525.4     .05       0  4919.4     .04       0  4923.4     .05       0
Bank Sta=4919.4,4923.4
XS Rating Curve= 0 ,0
Exp/Cntr=0.3,0.1

Type RM Length L Ch R = 1 ,5450    ,369,369,369
BEGIN DESCRIPTION:
Lacy 074 2215
END DESCRIPTION:
XS GIS Cut Line= 3
      2749411.05      6885438.95      2749089.38      6885621.69
       2748765.2      6886061.96
#Sta/Elev= 30
  4629.6   467.3  4642.5  466.02  4692.9     465  4723.3  462.65  4760.8  461.55
  4773.4  461.63    4804     459  4831.4   458.6  4863.1   456.2  4934.4  453.24
  4987.1  452.49  5059.4  453.36  5136.6  453.65  5172.6  454.53  5186.8  454.24
  5199.4  452.08  5199.7  451.58  5203.2  451.58  5203.4  452.08  5209.8   453.8
    5216  454.17  5266.2  453.41    5287     457  5295.5  456.95  5301.7  459.73
  5337.2  461.47  5345.6  461.22  5358.8  462.47  5401.9  462.79  5546.3  465.45
#Mann= 3 ,-1 , 0
  4629.6     .05       0  5199.4     .04       0  5203.4     .05       0
Bank Sta=5199.4,5203.4
XS Rating Curve= 0 ,0
Exp/Cntr=0.3,0.1

Type RM Length L Ch R = 1 ,5081    ,364,364,364
BEGIN DESCRIPTION:
Lacy 074 51
END DESCRIPTION:
XS GIS Cut Line= 3
      2749275.99        6885261.        2749026.        6885311.
      2748426.01        6885461.
#Sta/Elev= 30
  4745.8  464.26  4766.2  462.51    4807  461.01  4827.4  458.76  4868.2  456.14
  4878.4  454.86  4929.4  452.56  4980.3  451.53  4998.2  450.38  5031.7  451.75
  5101.2  450.89  5155.4  451.01    5176  450.36  5183.7  450.87  5196.6  449.29
  5206.9  448.97  5215.2  447.43  5215.5  446.93    5219  446.93  5219.2  447.43
  5224.9   449.8  5237.8   449.3  5248.1  451.39  5266.2  452.53  5279.1     454
  5353.8  457.29  5402.7  461.73  5454.3  464.06  5582.9  468.12  5619.2  469.72
#Mann= 4 ,-1 , 0
  4745.8     .05       0  5215.2     .04       0  5219.2     .05       0
  5582.9     .12       0
Bank Sta=5215.2,5219.2
XS Rating Curve= 0 ,0
Exp/Cntr=0.3,0.1

Type RM Length L Ch R = 1 ,4717    ,732,732,732
BEGIN DESCRIPTION:
Lacy 074 2214
END DESCRIPTION:
XS GIS Cut Line= 3
      2749237.06      6884973.66      2748822.53      6885052.42
       2748321.7      6885137.76
#Sta/Elev= 30
  4581.7  466.18  4591.1  465.92  4623.5  463.18  4633.7     463  4643.3  463.88
    4654  461.97  4705.7  459.04  4725.3  457.16  4757.9  456.21    4766  455.15
  4837.3  451.68  4898.3  449.42  4979.8  449.72  4989.9   448.9  4997.3  445.21
  4997.6  444.71  5001.1  444.71  5001.3  445.21  5003.6  445.21  5010.3  447.92
  5020.2  449.67  5050.8  449.68  5085.4   450.9  5140.6  454.29  5145.6  454.14
  5200.8  458.13  5284.2  460.83  5411.5  463.78  5466.8  466.09  5511.7  466.48
#Mann= 4 ,-1 , 0
  4581.7     .05       0  4997.3     .04       0  5001.3     .05       0
  5411.5     .12       0
Bank Sta=4997.3,5001.3
XS Rating Curve= 0 ,0
Exp/Cntr=0.3,0.1

Type RM Length L Ch R = 1 ,3985    ,172,172,172
BEGIN DESCRIPTION:
Lacy 074 2213
END DESCRIPTION:
XS GIS Cut Line= 3
      2749203.74      6884377.55      2748770.57      6884393.08
      2748340.08      6884412.95
#Sta/Elev= 30
    4572     469  4689.8  464.41  4719.8  461.79  4739.8  461.89  4749.9  460.46
  4759.9  459.93  4769.9   460.4  4789.9  459.59  4799.9  457.93  4806.3  455.44
  4811.3  456.81  4819.9  455.18  4839.9  452.88  4869.9  450.69    4920  448.21
    4980  446.87    4988  444.97  4988.3  444.47  4991.8  444.47    4992  444.97
    5000  447.33    5030  446.38  5050.1  446.72  5110.1   445.9  5150.2  447.45
  5180.2  446.51  5230.3  451.38  5310.3  456.37  5320.4  457.56  5436.4  461.11
#Mann= 3 ,-1 , 0
    4572     .05       0    4988     .05       0    4992     .05       0
Bank Sta=4988,4992
XS Rating Curve= 0 ,0
Exp/Cntr=0.3,0.1

Type RM Length L Ch R = 1 ,3813    ,515,515,515
BEGIN DESCRIPTION:
Lacy 074 2212
END DESCRIPTION:
XS GIS Cut Line= 3
       2749231.2      6884226.68       2748825.7      6884236.38
      2748415.06      6884230.82
#Sta/Elev= 30
  4593.7  466.92  4608.9  466.41  4678.9  461.05  4738.9  457.51  4758.9  457.91
    4779  453.18    4789   452.5    4839  451.32  4850.2  450.57    4859  449.69
    4869  449.98    4889  448.21    4909  447.87    4929  446.36  4978.6   445.3
  5001.7  445.56    5007  442.94  5007.3  442.44  5010.8  442.44    5011  442.94
  5030.9  445.15  5048.3  445.53    5069  445.73    5079  447.03    5099  446.12
    5129  446.67    5189  450.59  5262.7  453.18  5339.1  457.09    5410  458.13
#Mann= 6 ,-1 , 0
  4593.7     .12       0  4850.2      .1       0    5007     .07       0
    5011      .1       0  5048.3     .12       0  5262.7     .05       0
Bank Sta=5007,5011
XS Rating Curve= 0 ,0
Exp/Cntr=0.3,0.1

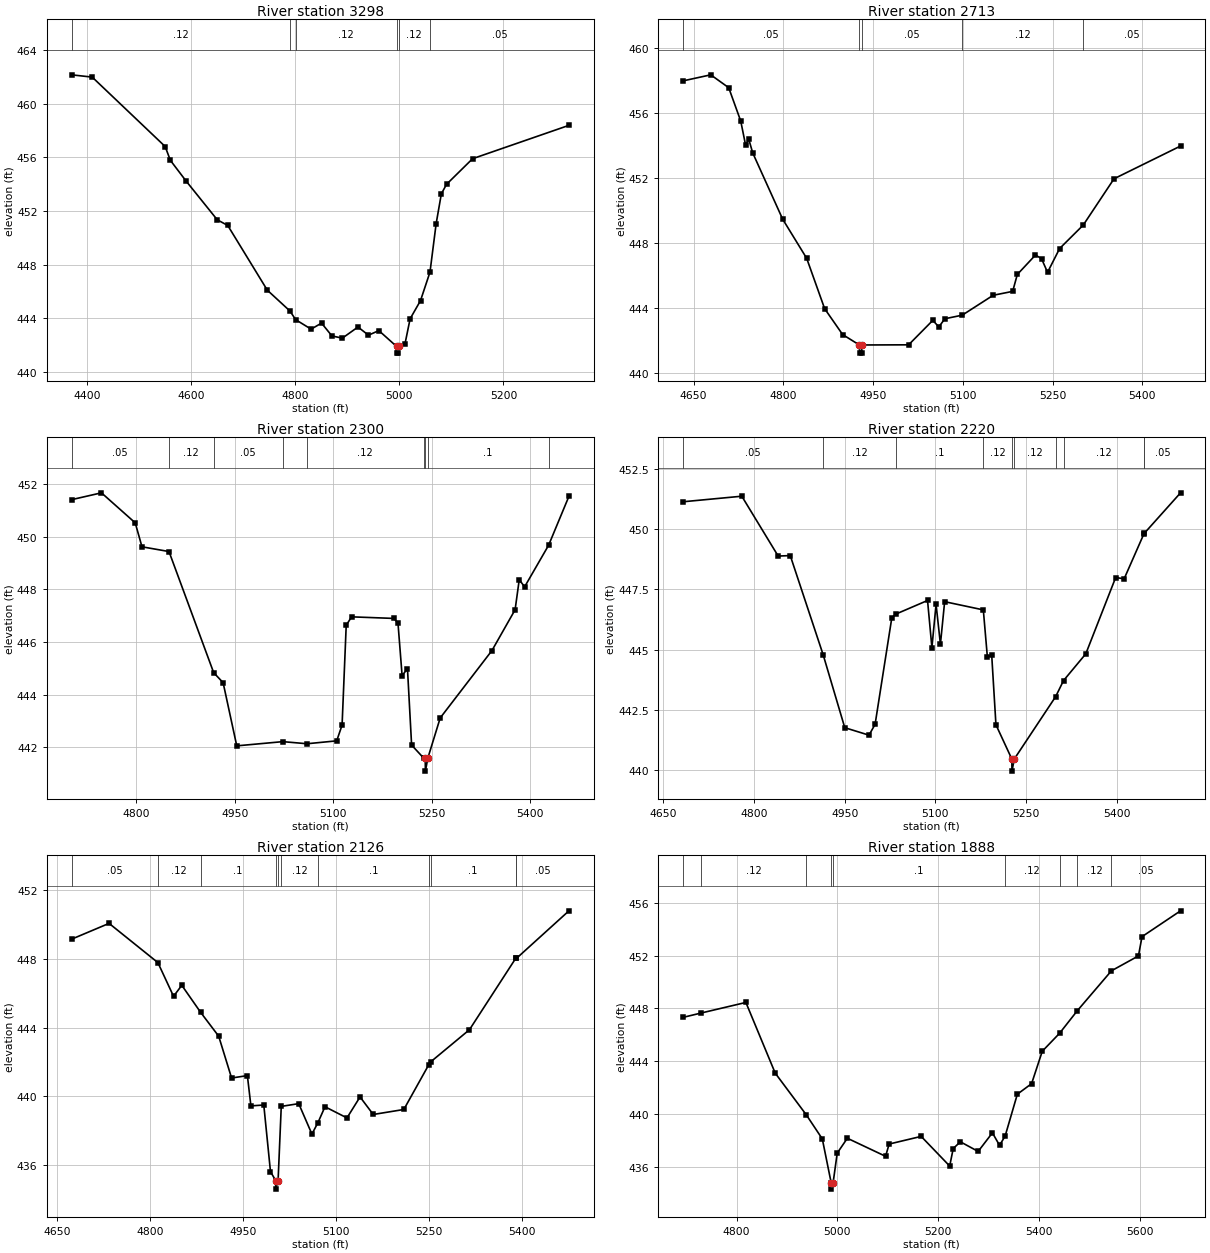
Type RM Length L Ch R = 1 ,3298    ,585,585,585
BEGIN DESCRIPTION:
Lacy 074 2211
END DESCRIPTION:
XS GIS Cut Line= 3
      2749305.61      6883804.18      2748679.13      6883773.92
      2748350.94      6883774.67
#Sta/Elev= 30
  4370.4  462.16  4410.1  461.99  4550.2  456.81  4560.2  455.78  4590.3  454.24
  4650.3  451.34  4670.4  450.92  4746.4  446.09    4790  444.53  4800.8  443.89
  4830.5  443.18  4850.6  443.63  4870.6  442.67  4890.6  442.51  4920.6  443.34
  4940.7  442.73  4960.7  443.07  4994.7  441.89  4994.9  441.39  4998.4  441.39
  4998.7  441.89  5010.7  442.05  5020.7  443.95  5040.7  445.31  5058.9  447.44
  5070.7  451.05  5080.7  453.28  5090.7  453.99  5140.7   455.9  5325.8  458.39
#Mann= 6 ,-1 , 0
  4370.4     .12       0    4790      .1       0  4800.8     .12       0
  4994.7     .07       0  4998.7     .12       0  5058.9     .05       0
Bank Sta=4994.7,4998.7
XS Rating Curve= 0 ,0
Exp/Cntr=0.3,0.1

Type RM Length L Ch R = 1 ,2713    ,413,413,413
BEGIN DESCRIPTION:
Lacy 074 2210
END DESCRIPTION:
XS GIS Cut Line= 3
      2749192.11      6883262.42       2748827.7      6883240.65
      2748365.86      6883305.28
#Sta/Elev= 30
  4632.5  457.96  4678.7  458.33  4708.7  457.54  4728.8  455.49    4737     454
    4742   454.4  4748.8  453.54  4798.9  449.47    4839  447.07    4869  443.98
  4899.1  442.39  4927.1  441.75  4927.4  441.25  4930.9  441.25  4931.1  441.75
  5009.4  441.76  5049.8  443.26  5059.9  442.86    5070  443.36    5099  443.58
  5150.7   444.8  5183.3  445.04  5191.1  446.08  5221.4  447.27  5231.5  447.05
  5241.6  446.21  5261.8  447.67  5301.3  449.11  5352.7  451.95  5463.9  453.96
#Mann= 5 ,-1 , 0
  4632.5     .05       0  4927.1     .05       0  4931.1     .05       0
    5099     .12       0  5301.3     .05       0
Bank Sta=4927.1,4931.1
XS Rating Curve= 0 ,0
Exp/Cntr=0.3,0.1

Type RM Length L Ch R = 1 ,2300    ,80,80,80
BEGIN DESCRIPTION:
Lacy 074 2209
END DESCRIPTION:
XS GIS Cut Line= 4
      2749020.22      6882786.36      2748726.85      6882859.39
      2748665.37      6882899.03      2748432.46      6883202.98
#Sta/Elev= 30
  4701.1  451.41  4746.7  451.67  4798.2  450.53  4808.5  449.62  4849.7  449.44
  4917.8  444.84  4932.2  444.46    4953  442.06  5023.3  442.22  5060.1  442.14
  5105.4  442.25  5113.6  442.85  5119.9  446.64  5128.1  446.96  5192.4   446.9
  5198.8  446.73  5205.1  444.73  5213.3  444.99  5219.6  442.09  5237.8   441.6
  5240.4   441.6  5240.6   441.1  5244.4   441.6  5263.2  443.12  5342.1  445.68
  5377.4  447.23  5383.7  448.37  5391.9   448.1  5428.5  449.68  5459.5  451.54
#Mann= 9 ,-1 , 0
  4701.1     .05       0  4849.7     .12       0  4917.8     .05       0
  5023.3      .1       0  5060.1     .12       0  5237.8      .1       0
  5240.4     .03       0  5244.4      .1       0  5428.5     .05       0
Bank Sta=5240.4,5244.4
XS Rating Curve= 0 ,0
Exp/Cntr=0.3,0.1

Type RM Length L Ch R = 1 ,2220    ,94,94,94
BEGIN DESCRIPTION:
Lacy 074 2206
END DESCRIPTION:
XS GIS Cut Line= 3
      2749042.89      6882756.61      2748695.73       6882780.7
      2748366.55      6883123.43
#Sta/Elev= 30
  4682.5  451.13  4779.6  451.36  4839.8  448.88  4859.8   448.9  4914.5  444.77
    4950  441.77  4990.1  441.46  5000.2  441.91  5027.9  446.33  5034.9  446.48
    5087  447.04  5094.2  445.09  5101.1  446.88  5108.3  445.23  5115.3  446.99
  5179.3  446.65    5186   444.7  5193.2  444.77  5200.2  441.89  5226.5  440.47
  5226.7  439.97  5230.5  440.47  5299.1  443.06    5312  443.72  5348.9  444.83
  5398.3  447.99  5412.4  447.94  5444.7  449.78  5445.6  449.82  5505.7   451.5
#Mann= 10 ,-1 , 0
  4682.5     .05       0  4914.5     .12       0  5034.9      .1       0
  5179.3     .12       0  5226.5     .07       0  5230.5     .12       0
  5299.1      .1       0    5312     .12       0  5444.7      .1       0
  5445.6     .05       0
Bank Sta=5226.5,5230.5
XS Rating Curve= 0 ,0
Exp/Cntr=0.3,0.1

Type RM Length L Ch R = 1 ,2126    ,238,238,238
BEGIN DESCRIPTION:
Lacy 074 2207
END DESCRIPTION:
XS GIS Cut Line= 3
      2749004.16      6882617.11      2748693.84      6882707.06
      2748349.64      6883041.62
#Sta/Elev= 30
  4673.2  449.14  4733.8  450.06  4812.6  447.78  4837.9  445.82  4851.2  446.46
  4881.6  444.89  4910.8   443.5  4931.6  441.07  4957.1  441.21  4962.8  439.45
  4983.6   439.5  4994.4  435.63  5002.7  435.11  5002.9  434.61  5006.7  435.11
  5011.8  439.42    5040  439.58  5061.3  437.81  5071.1  438.48  5082.4   439.4
  5117.9  438.75    5139  439.97  5160.3  438.95  5209.7  439.24  5250.1  441.85
  5253.1  442.01  5315.7  443.88  5390.2  448.02  5391.4  448.02  5476.3  450.79
#Mann= 11 ,-1 , 0
  4673.2     .05       0  4812.6     .12       0  4881.6      .1       0
  5002.7     .07       0  5006.7      .1       0  5011.8     .12       0
  5071.1      .1       0  5250.1     .12       0  5253.1      .1       0
  5390.2     .12       0  5391.4     .05       0
Bank Sta=5002.7,5006.7
XS Rating Curve= 0 ,0
Exp/Cntr=0.3,0.1

Type RM Length L Ch R = 1 ,1888    ,192,192,192
BEGIN DESCRIPTION:
Lacy 074 2208
END DESCRIPTION:
XS GIS Cut Line= 3
       2748979.8      6882484.49      2748595.42      6882529.34
      2748170.87      6882954.05
#Sta/Elev= 30
  4693.9  447.32  4729.8  447.65  4818.5  448.45  4876.7  443.09  4938.7  439.91
  4970.2   438.1  4987.7  434.79  4987.9  434.29  4991.7  434.79  4999.8  437.02
  5019.9  438.15  5095.8  436.78  5102.9  437.71  5166.5  438.29  5223.1  436.04
  5230.1  437.37  5244.3  437.88  5279.6  437.15  5307.9  438.56  5322.1  437.61
  5333.2  438.32  5357.4  441.49  5385.7  442.29  5406.9  444.75  5441.2  446.11
  5476.6  447.83  5544.2  450.85  5597.8  451.98  5604.9  453.44  5681.4   455.4
#Mann= 9 ,-1 , 0
  4693.9     .05       0  4729.8     .12       0  4938.7      .1       0
  4987.7     .07       0  4991.7      .1       0  5333.2     .12       0
  5441.2      .1       0  5476.6     .12       0  5544.2     .05       0
Bank Sta=4987.7,4991.7
XS Rating Curve= 0 ,0
Exp/Cntr=0.3,0.1

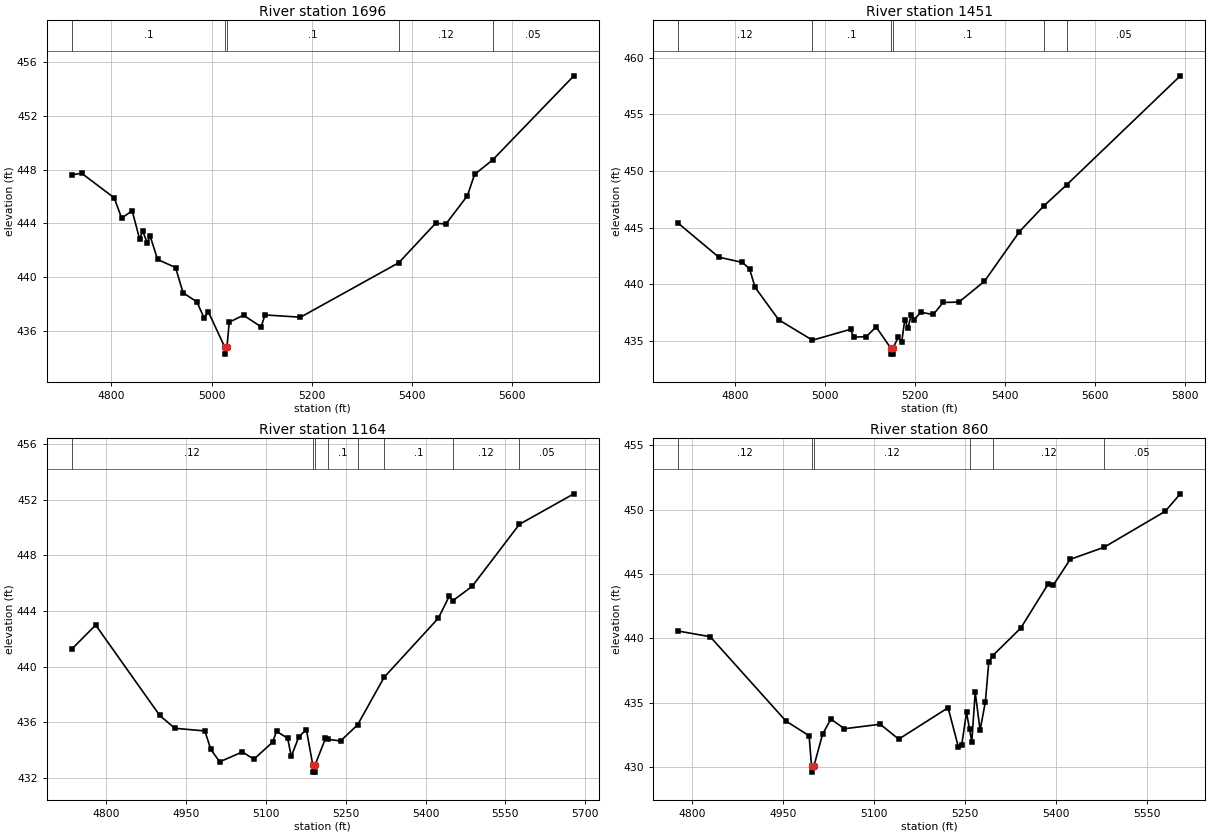
Type RM Length L Ch R = 1 ,1696    ,245,245,245
BEGIN DESCRIPTION:
Lacy 074 2205
END DESCRIPTION:
XS GIS Cut Line= 3
      2748842.06      6882188.91      2748607.08      6882349.95
      2748059.75      6882814.08
#Sta/Elev= 30
  4720.8   447.6  4740.3  447.73  4805.5  445.89  4820.4  444.38  4841.4  444.93
  4856.3  442.82  4862.4  443.43  4871.2  442.55  4877.3  443.04  4892.2   441.3
  4928.1   440.7    4943  438.82  4970.6  438.14  4984.9  436.96  4993.7  437.38
  5026.6  434.75  5026.9  434.25  5030.6  434.75  5035.2  436.63  5063.7  437.15
  5098.9  436.28  5106.6  437.17  5177.5     437  5373.8  441.06  5447.1  443.99
    5468  443.95  5510.8  446.05  5525.1  447.64  5561.3  448.72  5723.3  454.98
#Mann= 5 ,-1 , 0
  4720.8      .1       0  5026.6     .07       0  5030.6      .1       0
  5373.8     .12       0  5561.3     .05       0
Bank Sta=5026.6,5030.6
XS Rating Curve= 0 ,0
Exp/Cntr=0.3,0.1

Type RM Length L Ch R = 1 ,1451    ,287,287,287
BEGIN DESCRIPTION:
Lacy 074 2204
END DESCRIPTION:
XS GIS Cut Line= 3
      2748733.92      6882024.42      2748439.35      6882193.94
      2747920.86      6882770.14
#Sta/Elev= 30
  4673.7  445.39  4763.6   442.4  4816.4  441.93  4832.2  441.35  4844.4  439.73
  4896.8  436.87  4971.8  435.07  5056.3  436.03  5063.4  435.33  5091.5  435.39
  5113.1  436.24  5146.2  434.34  5146.5  433.84    5150  433.84  5150.3  434.34
  5162.5  435.35  5169.9  434.87  5176.7  436.87  5184.1  436.15  5190.9  437.31
  5197.9  436.88  5211.8  437.53  5240.2  437.34  5261.9   438.4    5297  438.43
  5353.8  440.27  5431.5  444.65  5485.1   446.9  5536.1  448.77  5788.7   458.4
#Mann= 6 ,-1 , 0
  4673.7     .12       0  4971.8      .1       0  5146.2     .07       0
  5150.3      .1       0  5485.1     .12       0  5536.1     .05       0
Bank Sta=5146.2,5150.3
XS Rating Curve= 0 ,0
Exp/Cntr=0.3,0.1

Type RM Length L Ch R = 1 ,1164    ,304,304,304
BEGIN DESCRIPTION:
Lacy 074 2217
END DESCRIPTION:
XS GIS Cut Line= 3
       2748508.3      6881769.54      2748315.11      6881951.37
      2747861.41      6882456.41
#Sta/Elev= 30
  4734.7  441.27  4779.6     443  4900.2   436.5  4928.5  435.58    4985  435.39
  4996.1  434.07  5012.9  433.17  5055.5  433.88  5077.2  433.36  5112.3  434.58
  5119.8  435.36  5140.7  434.87  5147.5  433.56  5161.7  434.97  5175.9  435.49
    5188  432.93  5188.3  432.43  5191.8  432.43  5192.1  432.93  5211.8  434.85
    5217  434.78  5240.2  434.67  5272.2  435.83  5322.2  439.25    5424  443.49
    5445   445.1    5451  444.74  5487.6  445.78  5576.5  450.24  5678.9  452.43
#Mann= 8 ,-1 , 0
  4734.7     .12       0    5188     .07       0  5192.1     .12       0
    5217      .1       0  5272.2     .12       0  5322.2      .1       0
    5451     .12       0  5576.5     .05       0
Bank Sta=5188,5192.1
XS Rating Curve= 0 ,0
Exp/Cntr=0.3,0.1

Type RM Length L Ch R = 1 ,860     ,0,0,0
BEGIN DESCRIPTION:
Lacy 074 3486
END DESCRIPTION:
XS GIS Cut Line= 3
      2748367.68      6881692.21      2748149.15      6881735.11
      2747878.87      6882276.27
#Sta/Elev= 30
  4777.3  440.56    4830  440.12    4955  433.56    4993  432.43    4997   430.1
  4997.3   429.6  5001.1   430.1  5015.2  432.54  5028.9  433.72  5051.3  432.97
  5110.3  433.32  5140.7  432.16  5222.1   434.6  5238.9  431.59  5244.5  431.68
  5252.5  434.24  5257.5  432.93  5261.2  431.96  5266.8  435.81  5274.9  432.86
  5283.6  435.07  5289.2  438.15  5295.7  438.65  5341.9  440.79  5386.6  444.18
  5395.5  444.12  5423.4  446.13  5479.3  447.07    5580  449.86  5604.9  451.22
#Mann= 6 ,-1 , 0
  4777.3     .12       0    4997     .07       0  5001.1     .12       0
  5257.5      .1       0  5295.7     .12       0  5479.3     .05       0
Bank Sta=4997,5001.1
XS Rating Curve= 0 ,0
Exp/Cntr=0.3,0.1

Chan Stop Cuts=-1
Use User Specified Reach Order=0
Composite Channel Slope=5