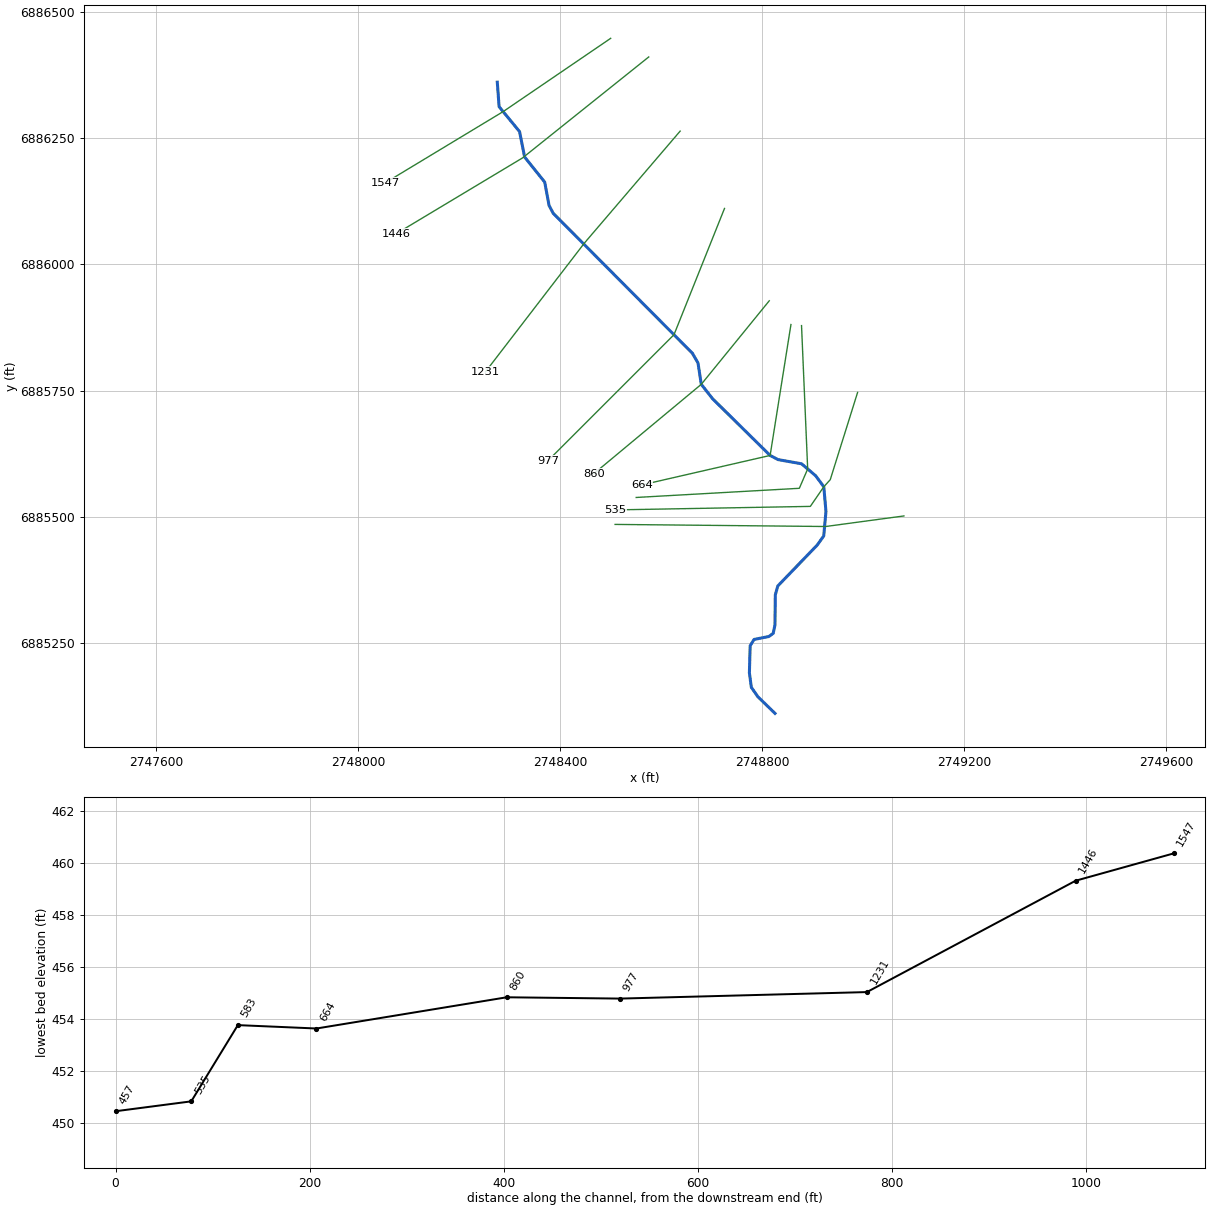
--- Lacy 075.prj (project) ---

Proj Title=Lacy 075 Base Level Engineering
Current Plan=p01
Default Exp/Contr=0.3,0.1
English Units
Geom File=g01
Flow File=f01
Plan File=p01
BEGIN DESCRIPTION:
Lacy 075
END DESCRIPTION:

--- Lacy 075.p01 (plan) ---

Plan Title=Multiple Run
Short Identifier=Multiple
Geom File=g01
Flow File=f01
Subcritical Flow
K Sum by GR= 0
Std Step Tol= 0.01
Critical Tol= 0.01
Num of Std Step Trials= 20
Max Error Tol= 0.3
Flow Tol Ratio= 0.001
Split Flow NTrial= 30
Split Flow Tol= 0.02
Split Flow Ratio= 0.02
Log Output Level= 0
Friction Slope Method= 1
Unsteady Friction Slope Method= 2
Unsteady Bridges Friction Slope Method= 1
Parabolic Critical Depth
Global Vel Dist=  1 , 1 , 1
Global Log Level= 0
CheckData=True
Encroach Param= -1, 0, 0, 0
BEGIN DESCRIPTION:
Multiple Run
END DESCRIPTION:

--- Lacy 075.f01 (steady flow) ---

Flow Title=Multiple
Number of Profiles=7
Profile Names=10-year,25-year,50-year,1pct_min,100-year,1pct_plu,500-year
River Rch & RM= Lacy 075,Reach-1,1547
     176     217     248     142     283     564     366
Boundary for River Rch & Prof#=Lacy 075,Reach-1,1
Up Type=0
Dn Type=3
Dn Slope=0.005
Boundary for River Rch & Prof#=Lacy 075,Reach-1,2
Up Type=0
Dn Type=3
Dn Slope=0.005
Boundary for River Rch & Prof#=Lacy 075,Reach-1,3
Up Type=0
Dn Type=3
Dn Slope=0.005
Boundary for River Rch & Prof#=Lacy 075,Reach-1,4
Up Type=0
Dn Type=3
Dn Slope=0.005
Boundary for River Rch & Prof#=Lacy 075,Reach-1,5
Up Type=0
Dn Type=3
Dn Slope=0.005
Boundary for River Rch & Prof#=Lacy 075,Reach-1,6
Up Type=0
Dn Type=3
Dn Slope=0.005
Boundary for River Rch & Prof#=Lacy 075,Reach-1,7
Up Type=0
Dn Type=3
Dn Slope=0.005

--- Lacy 075.g01 (geometry) ---

Geom Title=Existing Conditions

River Reach=Lacy 075,Reach-1
Reach XY= 30
      2748276.00      6886361.00      2748279.60      6886312.49
      2748320.05      6886263.25      2748330.14      6886212.72
      2748369.90      6886163.19      2748378.50      6886117.03
      2748386.76      6886101.32      2748662.37      6885824.21
      2748673.47      6885804.95      2748679.98      6885762.65
      2748702.30      6885734.18      2748816.34      6885621.79
      2748832.09      6885613.55      2748878.58      6885605.26
      2748906.58      6885581.54      2748922.63      6885559.72
      2748926.89      6885511.03      2748922.53      6885462.50
      2748909.56      6885444.26      2748831.56      6885363.36
      2748826.57      6885345.66      2748825.91      6885285.97
      2748822.44      6885269.50      2748813.75      6885263.20
      2748784.51      6885257.41      2748776.80      6885245.03
      2748775.28      6885191.21      2748779.15      6885162.50
      2748792.03      6885143.99      2748826.00      6885111.00

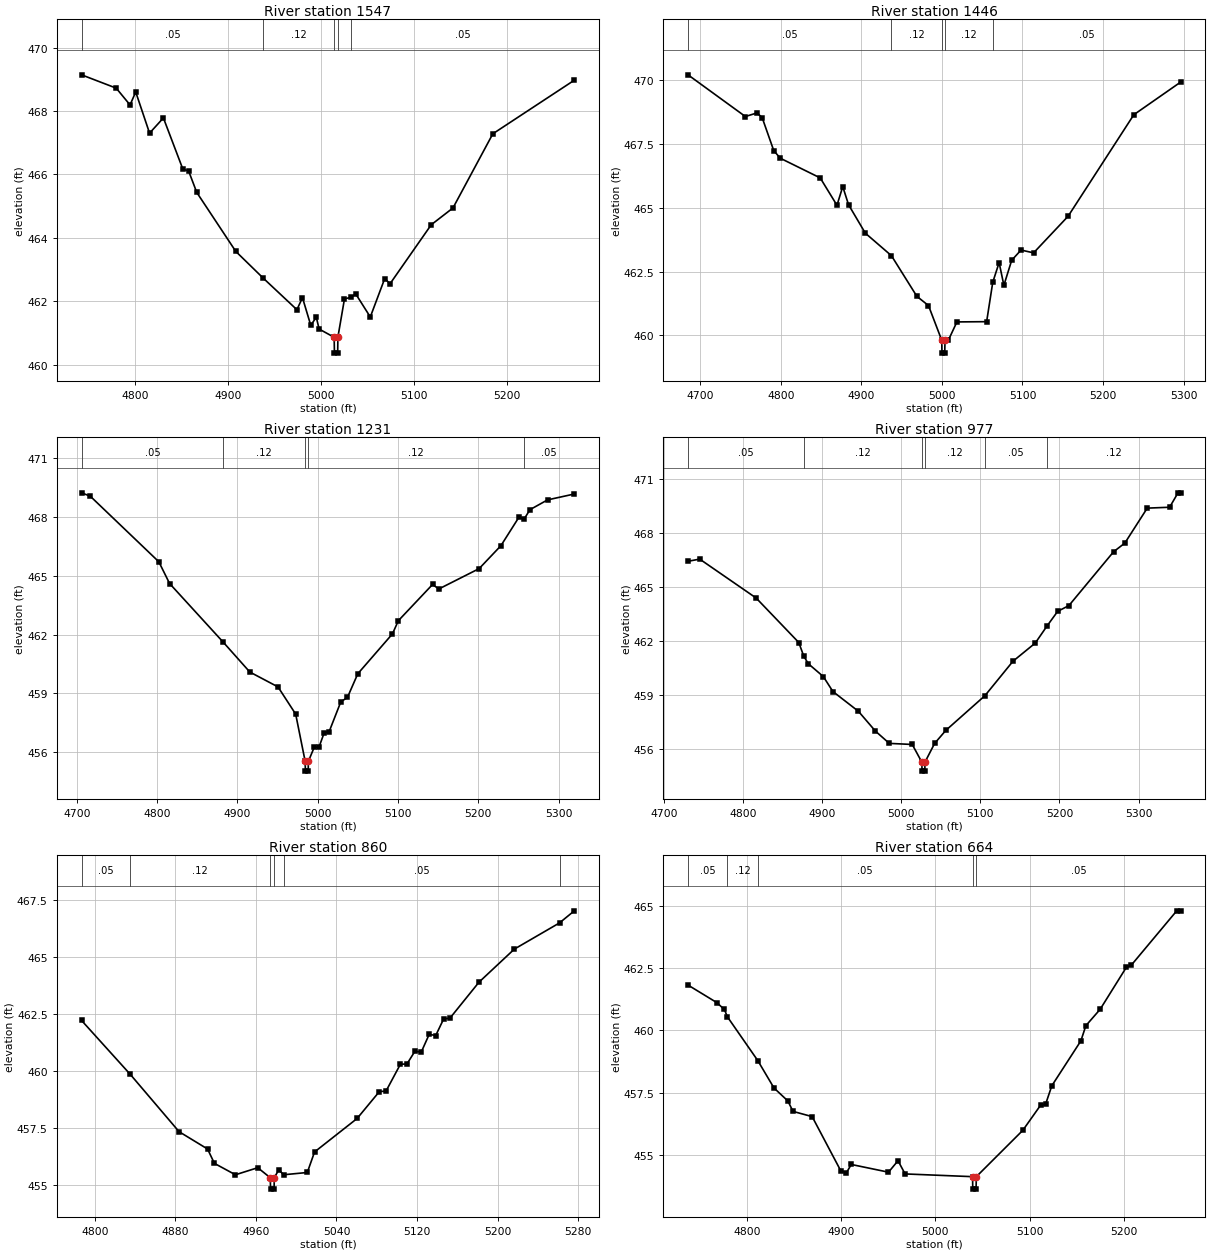
Type RM Length L Ch R = 1,1547,101,101,101
BEGIN DESCRIPTION:
Lacy 075 2224
END DESCRIPTION:
XS GIS Cut Line= 3
      2748500.59      6886447.83      2748287.62      6886302.73
      2748054.19      6886161.74
#Sta/Elev= 30
  4742.3  469.14  4779.6  468.72  4794.5  468.19  4800.6  468.60  4815.5  467.30
  4830.4  467.78  4851.4  466.16  4857.5  466.11  4866.3  465.43  4908.3  463.57
  4937.7  462.73  4974.1  461.73  4980.1  462.11  4989.0  461.24  4995.0  461.49
  4998.0  461.12  5014.2  460.86  5014.5  460.36  5018.0  460.36  5018.2  460.86
  5025.3  462.07  5031.9  462.12  5037.6  462.22  5053.1  461.50  5068.6  462.71
  5074.4  462.55  5118.7  464.41  5142.1  464.94  5185.0  467.28  5272.7  468.97
#Mann=5,-1,0
  4742.3    0.05       0  4937.7    0.12       0  5014.2    0.07       0
  5018.2    0.12       0  5031.9    0.05       0
Bank Sta=5014.2,5018.2
Exp/Cntr=0.3,0.1

Type RM Length L Ch R = 1,1446,215,215,215
BEGIN DESCRIPTION:
Lacy 075 75
END DESCRIPTION:
XS GIS Cut Line= 3
      2748576.00      6886411.00      2748326.00      6886211.00
      2748076.00      6886061.00
#Sta/Elev= 30
  4684.8  470.19  4756.0  468.56  4770.4  468.70  4776.8  468.52  4791.2  467.23
  4799.3  466.93  4848.9  466.16  4869.7  465.09  4876.9  465.82  4884.1  465.11
  4904.9  464.00  4937.3  463.12  4968.9  461.53  4983.3  461.17  4999.8  459.81
  5000.0  459.31  5003.5  459.31  5003.8  459.81  5007.9  459.81  5018.6  460.53
  5055.5  460.54  5063.1  462.08  5071.0  462.85  5076.9  461.96  5086.6  462.94
  5098.2  463.34  5113.8  463.23  5156.6  464.66  5238.2  468.63  5296.5  469.91
#Mann=5,-1,0
  4684.8    0.05       0  4937.3    0.12       0  4999.8    0.07       0
  5003.8    0.12       0  5063.1    0.05       0
Bank Sta=4999.8,5003.8
Exp/Cntr=0.3,0.1

Type RM Length L Ch R = 1,1231,254,254,254
BEGIN DESCRIPTION:
Lacy 075 2218
END DESCRIPTION:
XS GIS Cut Line= 3
      2748638.15      6886264.10      2748448.77      6886042.66
      2748252.47      6885787.26
#Sta/Elev= 30
  4706.0  469.24  4716.8  469.07  4802.2  465.72  4815.6  464.61  4882.7  461.60
  4915.5  460.09  4950.6  459.33  4972.6  457.94  4984.4  455.53  4984.7  455.03
  4988.2  455.03  4988.4  455.53  4995.7  456.25  5001.6  456.25  5008.0  456.98
  5014.3  457.05  5028.8  458.57  5037.0  458.79  5049.9  460.00  5093.1  462.04
  5100.4  462.71  5143.0  464.56  5150.8  464.33  5201.0  465.37  5228.1  466.54
  5250.8  468.01  5256.7  467.88  5264.3  468.38  5286.2  468.88  5319.5  469.18
#Mann=5,-1,0
  4706.0    0.05       0  4882.7    0.12       0  4984.4    0.07       0
  4988.4    0.12       0  5256.7    0.05       0
Bank Sta=4984.4,4988.4
Exp/Cntr=0.3,0.1

Type RM Length L Ch R = 1,977,117,117,117
BEGIN DESCRIPTION:
Lacy 075 74
END DESCRIPTION:
XS GIS Cut Line= 3
      2748725.99      6886110.99      2748626.00      6885861.00
      2748376.00      6885611.00
#Sta/Elev= 30
  4730.6  466.43  4745.4  466.55  4816.7  464.39  4870.6  461.92  4876.9  461.16
  4882.7  460.74  4901.6  460.03  4913.7  459.20  4946.0  458.10  4967.5  457.00
  4985.0  456.32  5014.0  456.26  5026.1  455.28  5026.4  454.78  5029.9  454.78
  5030.1  455.28  5042.3  456.32  5056.4  457.04  5105.9  458.97  5141.3  460.88
  5169.5  461.89  5184.4  462.84  5197.8  463.65  5212.0  463.97  5268.5  466.96
  5282.7  467.44  5311.0  469.38  5339.3  469.43  5349.9  470.23  5353.4  470.23
#Mann=6,-1,0
  4730.6    0.05       0  4876.9    0.12       0  5026.1    0.07       0
  5030.1    0.12       0  5105.9    0.05       0  5184.4    0.12       0
Bank Sta=5026.1,5030.1
Exp/Cntr=0.3,0.1

Type RM Length L Ch R = 1,860,196,196,196
BEGIN DESCRIPTION:
Lacy 075 2223
END DESCRIPTION:
XS GIS Cut Line= 3
      2748814.62      6885928.08      2748679.98      6885762.65
      2748467.54      6885585.97
#Sta/Elev= 30
  4786.7  462.23  4835.2  459.86  4883.6  457.35  4911.9  456.59  4918.7  455.96
  4939.6  455.46  4961.8  455.77  4974.2  455.33  4974.5  454.83  4978.0  454.83
  4978.2  455.33  4982.7  455.68  4987.4  455.46  5011.0  455.56  5018.2  456.46
  5060.5  457.93  5082.6  459.11  5089.2  459.13  5103.5  460.31  5110.0  460.32
  5117.8  460.87  5124.3  460.85  5132.1  461.62  5138.6  461.57  5146.4  462.29
  5152.9  462.34  5181.6  463.91  5216.7  465.36  5261.6  466.51  5276.3  467.04
#Mann=6,-1,0
  4786.7    0.05       0  4835.2    0.12       0  4974.2    0.04       0
  4978.2    0.12       0  4987.4    0.05       0  5261.6    0.12       0
Bank Sta=4974.2,4978.2
Exp/Cntr=0.3,0.1

Type RM Length L Ch R = 1,664,81,81,81
BEGIN DESCRIPTION:
Lacy 075 2222
END DESCRIPTION:
XS GIS Cut Line= 3
      2748857.56      6885881.03      2748816.34      6885621.79
      2748562.64      6885563.53
#Sta/Elev= 30
  4737.5  461.82  4767.9  461.12  4776.1  460.84  4779.2  460.55  4811.5  458.79
  4828.7  457.69  4843.4  457.17  4848.9  456.75  4869.2  456.54  4899.5  454.37
  4905.6  454.29  4910.7  454.62  4950.2  454.31  4960.3  454.77  4967.8  454.24
  5039.4  454.13  5039.6  453.63  5043.1  453.63  5043.4  454.13  5092.7  455.99
  5111.6  457.00  5116.8  457.03  5123.5  457.78  5154.3  459.58  5159.6  460.19
  5174.8  460.85  5202.5  462.53  5207.6  462.61  5256.0  464.80  5260.3  464.80
#Mann=5,-1,0
  4737.5    0.05       0  4779.2    0.12       0  4811.5    0.05       0
  5039.4    0.04       0  5043.4    0.05       0
Bank Sta=5039.4,5043.4
Exp/Cntr=0.3,0.1

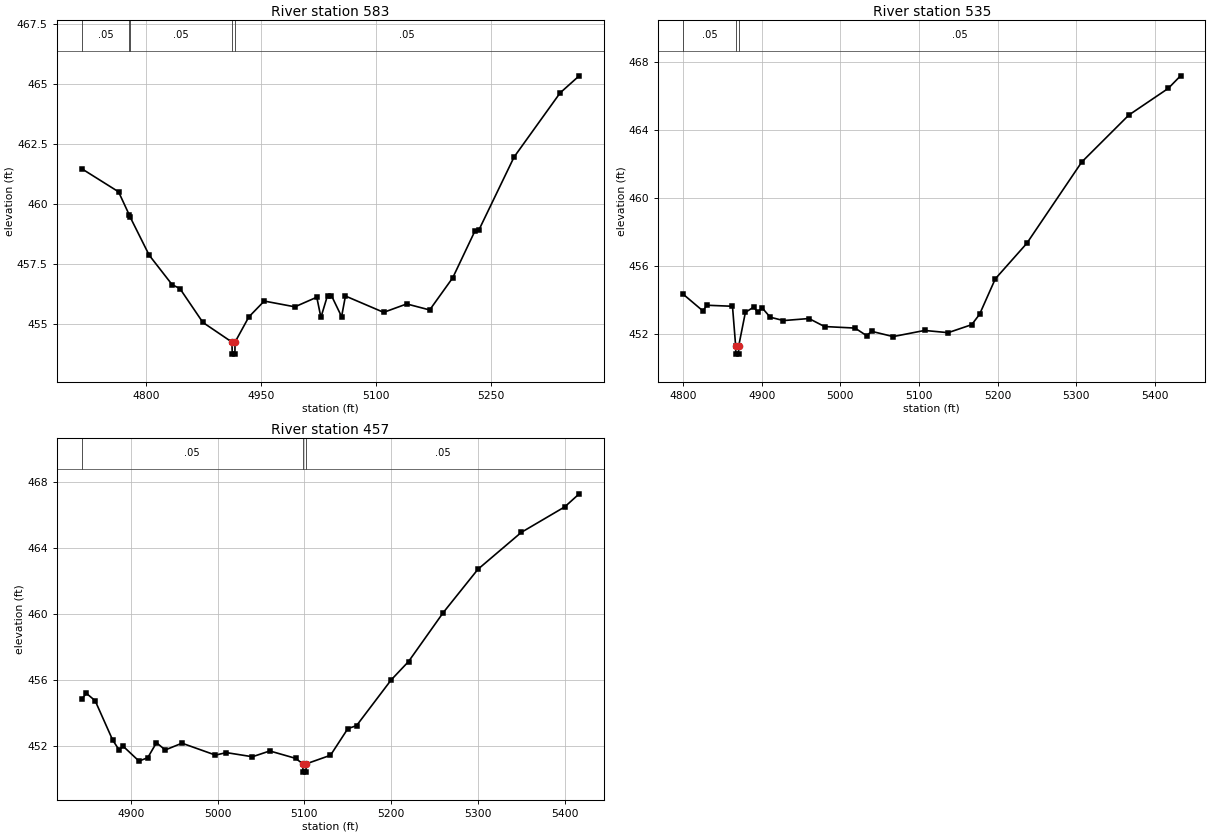
Type RM Length L Ch R = 1,583,48,48,48
BEGIN DESCRIPTION:
Lacy 075 2221
END DESCRIPTION:
XS GIS Cut Line= 4
      2748878.53      6885878.93      2748890.70      6885594.99
      2748874.19      6885556.75      2748551.15      6885538.58
#Sta/Elev= 30
  4715.8  461.48  4763.8  460.52  4777.6  459.57  4778.6  459.49  4803.8  457.88
  4833.8  456.65  4843.9  456.49  4873.9  455.08  4911.9  454.26  4912.2  453.76
  4915.7  453.76  4915.9  454.26  4933.9  455.31  4954.0  455.97  4994.0  455.73
  5022.6  456.13  5028.0  455.29  5036.6  456.20  5041.7  456.20  5055.0  455.32
  5060.0  456.18  5109.9  455.50  5140.0  455.85  5170.0  455.60  5200.1  456.94
  5229.1  458.89  5234.1  458.92  5280.2  461.97  5340.3  464.64  5365.2  465.35
#Mann=5,-1,0
  4715.8    0.05       0  4777.6    0.12       0  4778.6    0.05       0
  4911.9    0.04       0  4915.9    0.05       0
Bank Sta=4911.9,4915.9
Exp/Cntr=0.3,0.1

Type RM Length L Ch R = 1,535,78,78,78
BEGIN DESCRIPTION:
Lacy 075 2220
END DESCRIPTION:
XS GIS Cut Line= 5
      2748989.56      6885746.61      2748935.40      6885573.81
      2748922.63      6885559.72      2748895.96      6885520.91
      2748510.31      6885513.97
#Sta/Elev= 30
  4799.9  454.35  4825.0  453.37  4830.2  453.70  4862.7  453.64  4866.7  451.33
  4866.9  450.83  4870.4  450.83  4870.7  451.33  4879.1  453.28  4889.6  453.59
  4895.1  453.29  4900.4  453.55  4910.6  453.00  4927.6  452.80  4960.0  452.92
  4979.8  452.45  5018.6  452.36  5033.5  451.91  5039.6  452.17  5067.1  451.86
  5107.1  452.22  5137.1  452.09  5167.1  452.56  5177.1  453.17  5197.1  455.25
  5237.1  457.33  5307.1  462.11  5367.1  464.87  5417.1  466.43  5432.8  467.17
#Mann=3,-1,0
  4799.9    0.05       0  4866.7    0.04       0  4870.7    0.05       0
Bank Sta=4866.7,4870.7
Exp/Cntr=0.3,0.1

Type RM Length L Ch R = 1,457,0,0,0
BEGIN DESCRIPTION:
Lacy 075 2219
END DESCRIPTION:
XS GIS Cut Line= 3
      2749081.31      6885502.00      2748926.22      6885481.06
      2748509.34      6885485.22
#Sta/Elev= 30
  4843.5  454.88  4848.9  455.21  4858.9  454.77  4879.1  452.39  4886.3  451.81
  4891.3  452.01  4909.4  451.12  4919.5  451.32  4929.6  452.23  4939.7  451.79
  4959.0  452.20  4997.6  451.48  5010.2  451.63  5040.2  451.38  5060.2  451.73
  5090.2  451.28  5098.2  450.95  5098.5  450.45  5102.0  450.45  5102.2  450.95
  5130.2  451.47  5150.2  453.08  5160.2  453.26  5200.2  456.03  5220.2  457.14
  5260.2  460.10  5300.2  462.72  5350.2  464.95  5400.2  466.49  5416.9  467.28
#Mann=3,-1,0
  4843.5    0.05       0  5098.2    0.04       0  5102.2    0.05       0
Bank Sta=5098.2,5102.2
Exp/Cntr=0.3,0.1

Chan Stop Cuts=-1