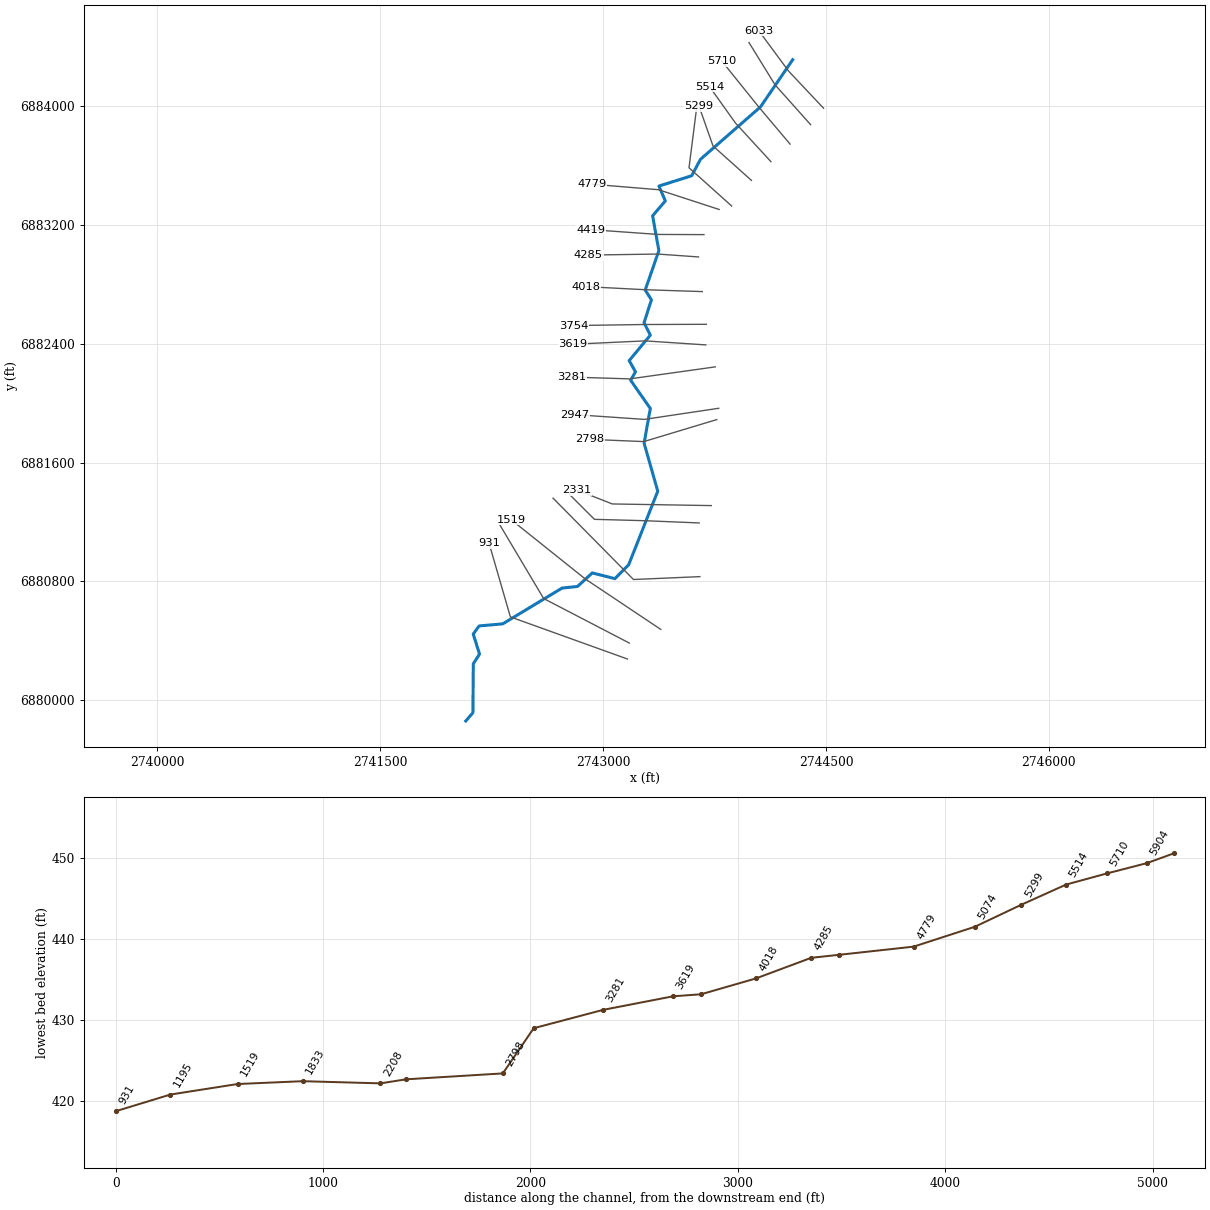
--- Lacy 077.prj (project) ---

Proj Title=Lacy 077 Base Level Engineering
Current Plan=p01
Default Exp/Contr=0.3,0.1
English Units
Geom File=g01
Flow File=f01
Plan File=p01
Y Axis Title=Elevation
X Axis Title(PF)=Main Channel Distance
X Axis Title(XS)=Station
BEGIN DESCRIPTION:
Lacy 077
END DESCRIPTION:
DSS Export Rating Curves= 0
DSS Export Rating Curve Sorted= 0
DSS Export Volume Flow Curves= 0
DXF OffsetX= 0
DXF OffsetY= 0
DXF ScaleX= 1
DXF ScaleY= 10

--- Lacy 077.p01 (plan) ---

Plan Title=Multiple Run
Short Identifier=Multiple
Geom File=g01
Flow File=f01
Subcritical Flow
K Sum by GR= 0
Std Step Tol= 0.01
Critical Tol= 0.01
Num of Std Step Trials= 20
Max Error Tol= 0.3
Flow Tol Ratio= 0.001
Split Flow NTrial= 30
Split Flow Tol= 0.02
Split Flow Ratio= 0.02
Log Output Level= 0
Friction Slope Method= 1
Unsteady Friction Slope Method= 2
Unsteady Bridges Friction Slope Method= 1
Parabolic Critical Depth
Global Vel Dist=  1 , 1 , 1
Global Log Level= 0
CheckData=True
Encroach Param= -1, 0, 0, 0
BEGIN DESCRIPTION:
Multiple Run
END DESCRIPTION:

--- Lacy 077.f01 (steady flow) ---

Flow Title=Multiple
Number of Profiles=7
Profile Names=10-year,25-year,50-year,1pct_min,100-year,1pct_plu,500-year
River Rch & RM= Lacy 077,Reach-1,6033
     208     261     302     174     348     694     461
River Rch & RM= Lacy 077,Reach-1,4779
     370     482     571     336     671    1338     927
Boundary for River Rch & Prof#=Lacy 077,Reach-1,1
Up Type=0
Dn Type=3
Dn Slope=0.005
Boundary for River Rch & Prof#=Lacy 077,Reach-1,2
Up Type=0
Dn Type=3
Dn Slope=0.005
Boundary for River Rch & Prof#=Lacy 077,Reach-1,3
Up Type=0
Dn Type=3
Dn Slope=0.005
Boundary for River Rch & Prof#=Lacy 077,Reach-1,4
Up Type=0
Dn Type=3
Dn Slope=0.005
Boundary for River Rch & Prof#=Lacy 077,Reach-1,5
Up Type=0
Dn Type=3
Dn Slope=0.005
Boundary for River Rch & Prof#=Lacy 077,Reach-1,6
Up Type=0
Dn Type=3
Dn Slope=0.005
Boundary for River Rch & Prof#=Lacy 077,Reach-1,7
Up Type=0
Dn Type=3
Dn Slope=0.005

--- Lacy 077.g01 (geometry) ---

Geom Title=Existing Conditions
Program Version=4.10

River Reach=Lacy 077        ,Reach-1
Reach XY= 30
        2744276.        6884311.       2744059.5      6883993.95
      2743655.62      6883641.16      2743596.54      6883530.47
        2743376.        6883461.      2743418.93      6883360.93
      2743333.34       6883261.1      2743375.48      6883026.22
      2743283.56        6882761.      2743325.48      6882695.78
      2743275.79      6882540.79      2743317.95      6882457.66
      2743175.56      6882286.08      2743218.16      6882210.91
      2743185.31      6882154.34      2743317.96      6881964.32
      2743276.07      6881731.03      2743367.96      6881407.68
      2743172.39      6880912.47      2743079.43      6880818.79
       2742927.5      6880857.53      2742828.42      6880766.54
      2742723.68      6880755.23      2742324.53      6880514.55
      2742165.82      6880500.67      2742126.19      6880445.92
      2742168.44        6880311.      2742126.66      6880245.84
      2742124.11      6879916.78        2742076.        6879861.

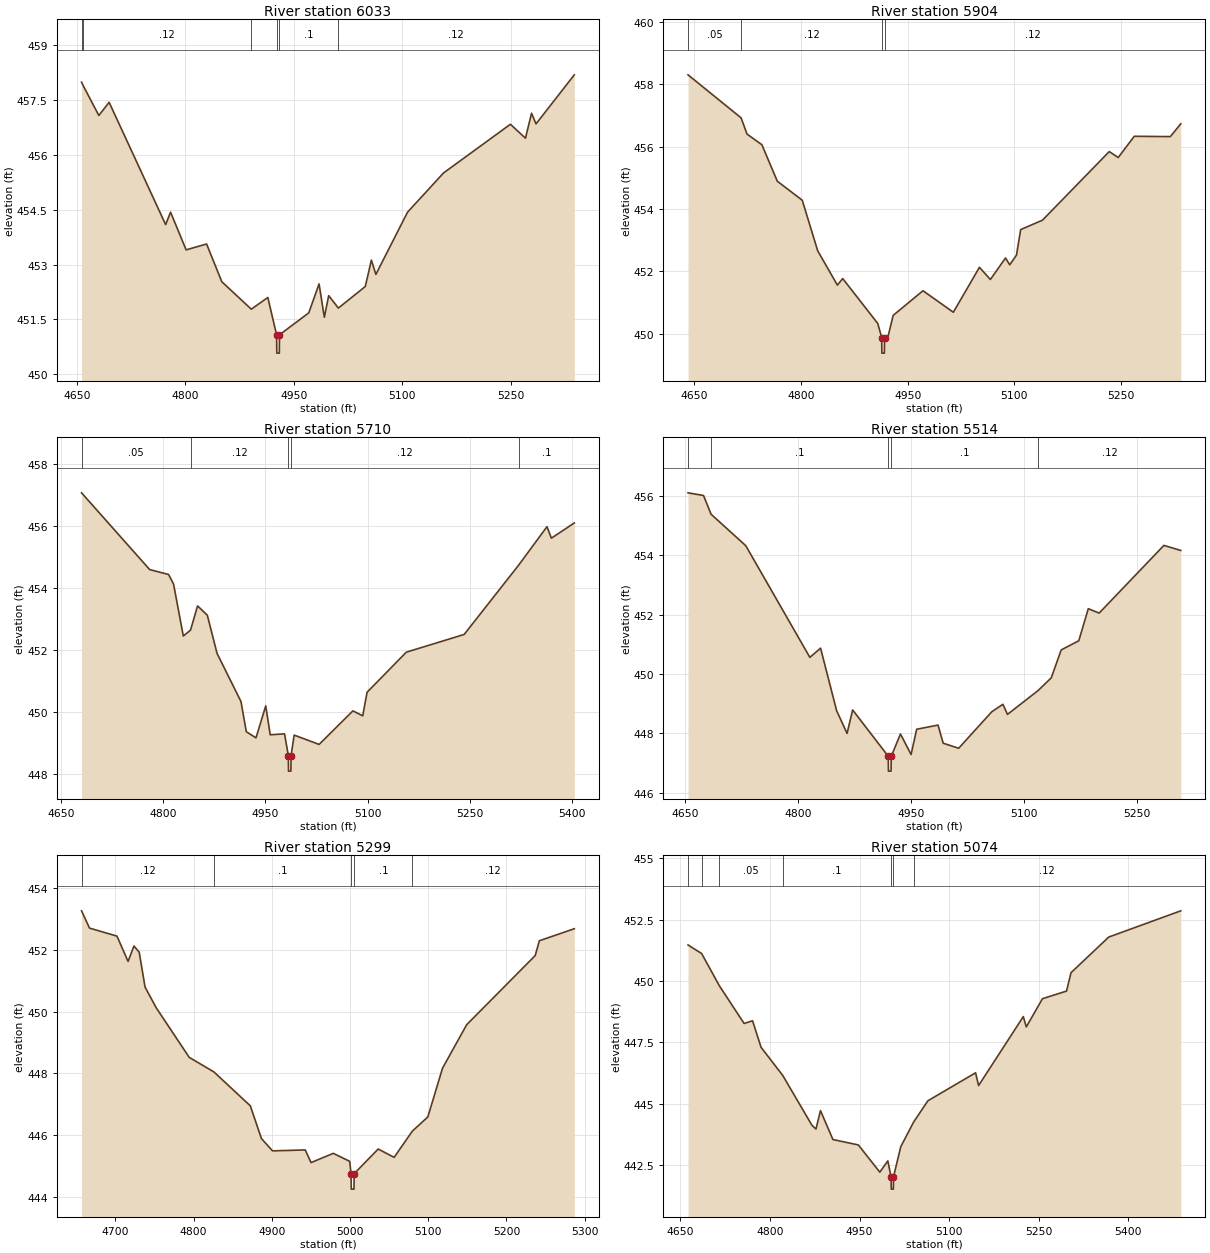
Type RM Length L Ch R = 1 ,6033    ,129,129,129
BEGIN DESCRIPTION:
Lacy 077 2144
END DESCRIPTION:
XS GIS Cut Line= 3
      2744483.85      6883984.83      2744248.52      6884234.78
      2744048.07      6884506.43
#Sta/Elev= 30
  4656.7  457.98  4659.1  457.88  4680.6  457.07  4694.8  457.43  4772.9  454.09
  4779.7  454.43  4801.2   453.4  4829.5  453.56  4850.5  452.53  4891.3  451.78
  4914.1   452.1  4926.2  451.08  4926.5  450.58    4930  450.58  4930.2  451.08
  4970.7  451.68  4984.9  452.47  4992.2  451.56  4998.2  452.15  5011.6  451.81
  5048.8   452.4  5057.2  453.12  5063.4  452.73  5107.2  454.43  5156.9   455.5
  5249.3  456.83  5270.1  456.45  5278.5  457.13  5284.7  456.84  5337.6  458.18
#Mann= 6 ,-1 , 0
  4656.7     .05       0  4659.1     .12       0  4891.3      .1       0
  4926.2     .07       0  4930.2      .1       0  5011.6     .12       0
Bank Sta=4926.2,4930.2
XS Rating Curve= 0 ,0
Exp/Cntr=0.3,0.1

Type RM Length L Ch R = 1 ,5904    ,194,194,194
BEGIN DESCRIPTION:
Lacy 077 2143
END DESCRIPTION:
XS GIS Cut Line= 3
      2744396.63      6883874.51      2744157.42      6884142.33
       2743982.2      6884426.69
#Sta/Elev= 30
  4640.9   458.3  4715.6  456.92  4723.9   456.4  4744.8  456.06  4766.5  454.89
  4801.6  454.28  4823.3  452.66    4851  451.56  4858.5  451.77  4907.8  450.33
  4913.3  449.88  4913.6  449.38  4917.1  449.38  4917.3  449.88    4922  449.89
  4929.5  450.59  4971.4  451.38  5014.1  450.69  5050.8  452.13  5066.2  451.74
  5087.5  452.43  5093.4  452.21  5102.9  452.52  5108.8  453.34  5139.4  453.64
  5233.4  455.84    5246  455.65  5268.6  456.33  5319.3  456.32    5334  456.73
#Mann= 4 ,-1 , 0
  4640.9     .05       0  4715.6     .12       0  4913.3     .07       0
  4917.3     .12       0
Bank Sta=4913.3,4917.3
XS Rating Curve= 0 ,0
Exp/Cntr=0.3,0.1

Type RM Length L Ch R = 1 ,5710    ,196,196,196
BEGIN DESCRIPTION:
Lacy 077 2142
END DESCRIPTION:
XS GIS Cut Line= 3
      2744258.62      6883743.41      2744049.07       6883991.7
      2743799.56      6884301.79
#Sta/Elev= 30
  4680.3  457.06  4780.2  454.59    4808  454.43  4815.3  454.12  4829.6  452.45
  4840.2  452.64  4850.5  453.42  4864.8  453.12  4879.1  451.89  4914.2  450.34
    4922  449.37  4936.2  449.17  4950.5   450.2  4957.1  449.27  4978.1   449.3
  4983.7   448.6  4983.9   448.1  4987.4   448.1  4987.7   448.6  4992.2  449.26
  5028.8  448.96  5078.4  450.04  5092.8  449.88  5099.2  450.64  5156.8  451.93
  5241.6   452.5  5321.5  454.73  5363.1  455.97  5369.6   455.6  5403.2  456.09
#Mann= 5 ,-1 , 0
  4680.3     .05       0  4840.2     .12       0  4983.7     .07       0
  4987.7     .12       0  5321.5      .1       0
Bank Sta=4983.7,4987.7
XS Rating Curve= 0 ,0
Exp/Cntr=0.3,0.1

Type RM Length L Ch R = 1 ,5514    ,215,215,215
BEGIN DESCRIPTION:
Lacy 077 2141
END DESCRIPTION:
XS GIS Cut Line= 3
      2744129.37      6883625.62       2743892.1      6883884.03
      2743715.63      6884130.93
#Sta/Elev= 30
    4654   456.1  4674.6  456.01  4684.6  455.38  4730.7  454.32  4815.8  450.56
    4830  450.87  4851.4  448.76  4865.2     448  4872.6  448.79  4919.9  447.23
  4920.1  446.73  4923.6  446.73  4923.9  447.23  4936.1  447.98  4950.2  447.29
  4957.6  448.14    4986  448.28  4992.8  447.67  5013.4   447.5  5057.4  448.73
  5072.1  448.98  5078.2  448.64  5118.7  449.44  5136.3  449.87  5149.5  450.81
  5172.9  451.12  5185.5   452.2  5199.9  452.05  5285.9  454.33  5308.3  454.16
#Mann= 5 ,-1 , 0
    4654     .12       0  4684.6      .1       0  4919.9     .07       0
  4923.9      .1       0  5118.7     .12       0
Bank Sta=4919.9,4923.9
XS Rating Curve= 0 ,0
Exp/Cntr=0.3,0.1

Type RM Length L Ch R = 1 ,5299    ,225,225,225
BEGIN DESCRIPTION:
Lacy 077 2140
END DESCRIPTION:
XS GIS Cut Line= 3
       2743998.5      6883499.11      2743739.88      6883731.02
      2743646.01      6883997.71
#Sta/Elev= 30
  4656.7  453.27  4666.9  452.71    4702  452.45  4716.2  451.63  4723.7  452.13
  4730.4  451.93  4737.9   450.8  4752.1  450.13  4794.4  448.52  4825.9  448.05
  4872.5  446.95  4886.7  445.89  4900.9  445.49  4942.7  445.52  4950.2  445.11
  4978.6  445.41  4999.6  445.15  5001.3  444.75  5001.6  444.25  5005.1  444.25
  5005.3  444.75    5036  445.55  5056.4  445.28  5079.7  446.13  5099.5  446.59
  5118.3  448.17  5149.2  449.58  5236.8  451.82  5242.1   452.3  5286.8  452.69
#Mann= 5 ,-1 , 0
  4656.7     .12       0  4825.9      .1       0  5001.3     .07       0
  5005.3      .1       0  5079.7     .12       0
Bank Sta=5001.3,5005.3
XS Rating Curve= 0 ,0
Exp/Cntr=0.3,0.1

Type RM Length L Ch R = 1 ,5074    ,295,295,295
BEGIN DESCRIPTION:
Lacy 077 2139
END DESCRIPTION:
XS GIS Cut Line= 3
       2743865.1      6883327.05      2743578.34      6883584.28
      2743633.91      6884020.73
#Sta/Elev= 30
  4662.7  451.47  4685.5  451.12  4715.1  449.81  4756.6  448.27  4770.8  448.38
    4785   447.3  4821.4  446.15  4870.3  444.12    4877  443.97  4884.5  444.72
  4905.4  443.54    4948  443.32  4983.9  442.21  4997.3  442.67  5002.8  442.02
  5003.1  441.52  5006.6  441.52  5006.8  442.02    5019  443.25  5040.7  444.26
  5064.4  445.12  5144.3  446.26  5149.3  445.74  5224.2  448.55  5229.2  448.13
  5256.3  449.28  5296.6  449.59  5304.1  450.34  5367.2  451.79  5487.9  452.86
#Mann= 7 ,-1 , 0
  4662.7     .12       0  4685.5      .1       0  4715.1     .05       0
  4821.4      .1       0  5002.8     .07       0  5006.8      .1       0
  5040.7     .12       0
Bank Sta=5002.8,5006.8
XS Rating Curve= 0 ,0
Exp/Cntr=0.3,0.1

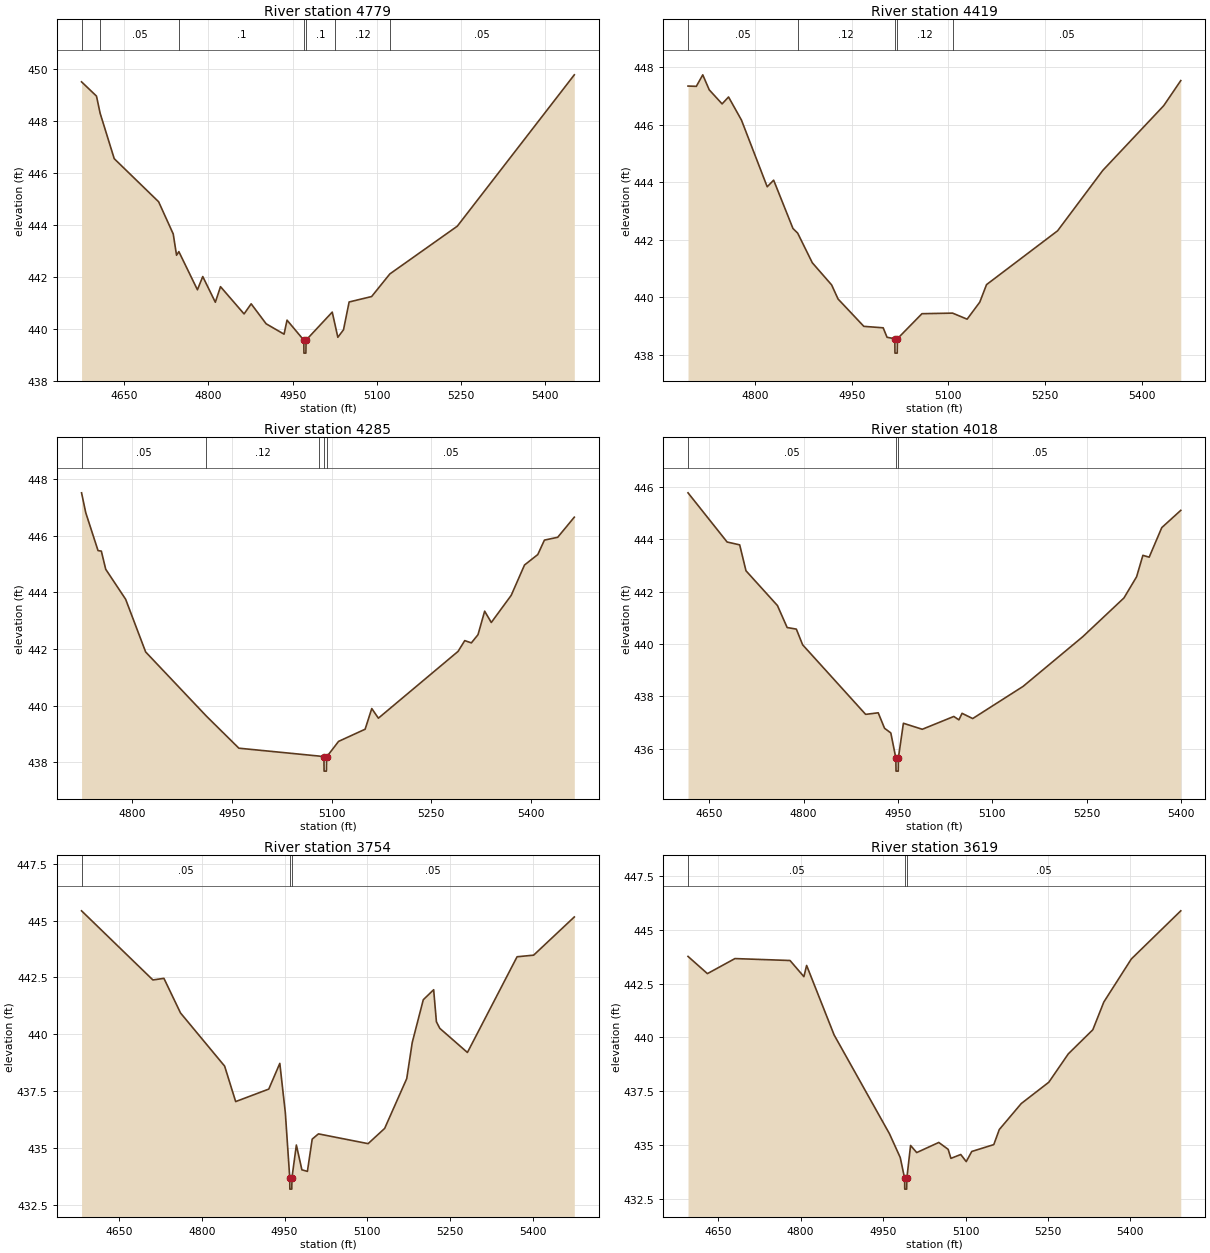
Type RM Length L Ch R = 1 ,4779    ,360,360,360
BEGIN DESCRIPTION:
Lacy 077 2135
END DESCRIPTION:
XS GIS Cut Line= 3
       2743781.3      6883303.39      2743372.81      6883436.48
      2742926.26      6883473.42
#Sta/Elev= 30
    4574  449.52  4600.6  448.97  4607.1  448.31  4632.2  446.56  4711.3   444.9
  4737.3  443.66  4743.2  442.84  4747.3  442.98  4780.4  441.51  4789.9  442.02
  4812.3  441.03  4821.5  441.63  4863.5  440.58  4876.1  440.97  4902.8   440.2
  4934.7   439.8    4940  440.34  4969.9  439.57  4970.1  439.07  4973.6  439.07
  4973.9  439.57  5020.5  440.65  5025.7  440.15  5030.5  439.68  5040.6  439.97
  5050.6  441.04  5090.7  441.25  5123.1  442.12  5243.3  443.96  5451.7  449.79
#Mann= 7 ,-1 , 0
    4574      .1       0  4607.1     .05       0  4747.3      .1       0
  4969.9     .07       0  4973.9      .1       0  5025.7     .12       0
  5123.1     .05       0
Bank Sta=4969.9,4973.9
XS Rating Curve= 0 ,0
Exp/Cntr=0.3,0.1

Type RM Length L Ch R = 1 ,4419    ,134,134,134
BEGIN DESCRIPTION:
Lacy 077 2138
END DESCRIPTION:
XS GIS Cut Line= 3
      2743678.93      6883134.26      2743369.01      6883135.49
      2742915.29      6883167.93
#Sta/Elev= 30
    4696  447.34  4708.9  447.33  4718.9  447.73  4728.9  447.21  4748.9  446.72
  4758.9  446.96  4778.9  446.16  4818.9  443.84  4828.9  444.07  4858.9  442.39
  4866.2  442.23  4888.9   441.2  4918.9  440.43  4928.9  439.94  4968.9  438.99
  4998.9  438.94  5004.9  438.61    5017  438.56  5017.2  438.06  5020.7  438.06
    5021  438.56  5059.1  439.43  5106.6  439.45  5129.2  439.24  5148.8  439.83
  5159.3  440.44  5269.6  442.31  5339.8  444.41  5434.4  446.66  5460.8  447.53
#Mann= 5 ,-1 , 0
    4696     .05       0  4866.2     .12       0    5017     .07       0
    5021     .12       0  5106.6     .05       0
Bank Sta=5017,5021
XS Rating Curve= 0 ,0
Exp/Cntr=0.3,0.1

Type RM Length L Ch R = 1 ,4285    ,267,267,267
BEGIN DESCRIPTION:
Lacy 077 2137
END DESCRIPTION:
XS GIS Cut Line= 3
      2743642.28      6882984.01      2743368.51      6883003.43
      2742901.01      6882996.57
#Sta/Elev= 30
  4723.5  447.52  4729.8  446.82  4748.3  445.48  4753.3  445.46  4759.9  444.82
  4789.9  443.76    4820   441.9  4911.6  439.63  4960.4   438.5  5081.8  438.22
  5088.5  438.19  5088.7  437.69  5092.2  437.69  5092.5  438.19  5110.5  438.74
  5150.5  439.17  5160.5   439.9  5170.5  439.56  5290.5  441.92  5300.5   442.3
  5310.5  442.22  5320.5  442.51  5330.5  443.34  5340.5  442.94  5370.5   443.9
  5390.5  444.97  5410.5  445.34  5420.5  445.85  5440.5  445.95  5465.5  446.66
#Mann= 5 ,-1 , 0
  4723.5     .05       0  4911.6     .12       0  5081.8     .05       0
  5088.5     .07       0  5092.5     .05       0
Bank Sta=5088.5,5092.5
XS Rating Curve= 0 ,0
Exp/Cntr=0.3,0.1

Type RM Length L Ch R = 1 ,4018    ,264,264,264
BEGIN DESCRIPTION:
Lacy 077 2136
END DESCRIPTION:
XS GIS Cut Line= 3
      2743668.03      6882750.83      2743286.22      6882763.34
      2742885.87      6882784.07
#Sta/Elev= 30
  4616.5  445.78  4678.6   443.9  4698.6  443.79  4708.6   442.8  4758.6  441.47
    4774  440.63  4788.6  440.57  4798.6  439.97  4898.7  437.31  4918.7  437.37
  4928.7  436.78  4938.7   436.6  4946.7  435.64    4947  435.14  4950.5  435.14
  4950.7  435.64  4958.7  436.97  4988.7  436.74  5038.8  437.23  5046.9   437.1
  5051.9  437.35  5068.8  437.15  5148.9  438.38  5243.7  440.28  5309.1  441.76
  5329.2  442.57  5339.2  443.39  5349.2  443.32  5369.2  444.45  5399.4  445.11
#Mann= 3 ,-1 , 0
  4616.5     .05       0  4946.7     .04       0  4950.7     .05       0
Bank Sta=4946.7,4950.7
XS Rating Curve= 0 ,0
Exp/Cntr=0.3,0.1

Type RM Length L Ch R = 1 ,3754    ,135,135,135
BEGIN DESCRIPTION:
Lacy 077 2134
END DESCRIPTION:
XS GIS Cut Line= 3
      2743695.25      6882530.68      2743273.48      6882529.24
      2742802.31       6882522.3
#Sta/Elev= 30
  4582.1  445.43  4711.4  442.39  4731.4  442.46  4761.4  440.94  4841.4   438.6
  4861.4  437.04  4921.4  437.59  4941.4  438.72  4951.4  436.55  4959.4  433.69
  4959.6  433.19  4963.1  433.19  4963.4  433.69  4971.4  435.13  4981.4  434.04
  4991.4  433.97  5000.1  435.39  5011.4  435.62  5101.4  435.19  5131.4  435.86
  5171.4  438.05  5181.4  439.64  5201.4  441.52  5220.2  441.96  5225.2  440.55
  5231.4  440.26  5281.4   439.2  5371.4  443.41  5401.4  443.48  5475.1  445.16
#Mann= 3 ,-1 , 0
  4582.1     .05       0  4959.4     .04       0  4963.4     .05       0
Bank Sta=4959.4,4963.4
XS Rating Curve= 0 ,0
Exp/Cntr=0.3,0.1

Type RM Length L Ch R = 1 ,3619    ,338,338,338
BEGIN DESCRIPTION:
Lacy 077 2131
END DESCRIPTION:
XS GIS Cut Line= 3
      2743691.22      6882392.05      2743283.46      6882419.08
      2742796.13       6882396.6
#Sta/Elev= 30
  4595.1  443.76  4630.4  442.96  4680.5  443.66  4780.7  443.57  4805.9  442.82
  4810.9  443.34  4860.9  440.11  4961.7  435.51  4981.2  434.41  4989.2  433.44
  4989.4  432.94  4992.9  432.94  4993.2  433.44    5000  434.97  5011.2  434.64
  5051.3  435.11  5068.4  434.79  5073.4  434.37  5091.3  434.55  5101.3  434.22
  5111.3  434.69  5151.4  435.01  5161.4  435.71  5201.4  436.92  5251.5  437.91
    5287  439.23  5331.6  440.35  5351.6  441.64  5401.6  443.64  5491.6  445.88
#Mann= 3 ,-1 , 0
  4595.1     .05       0  4989.2     .04       0  4993.2     .05       0
Bank Sta=4989.2,4993.2
XS Rating Curve= 0 ,0
Exp/Cntr=0.3,0.1

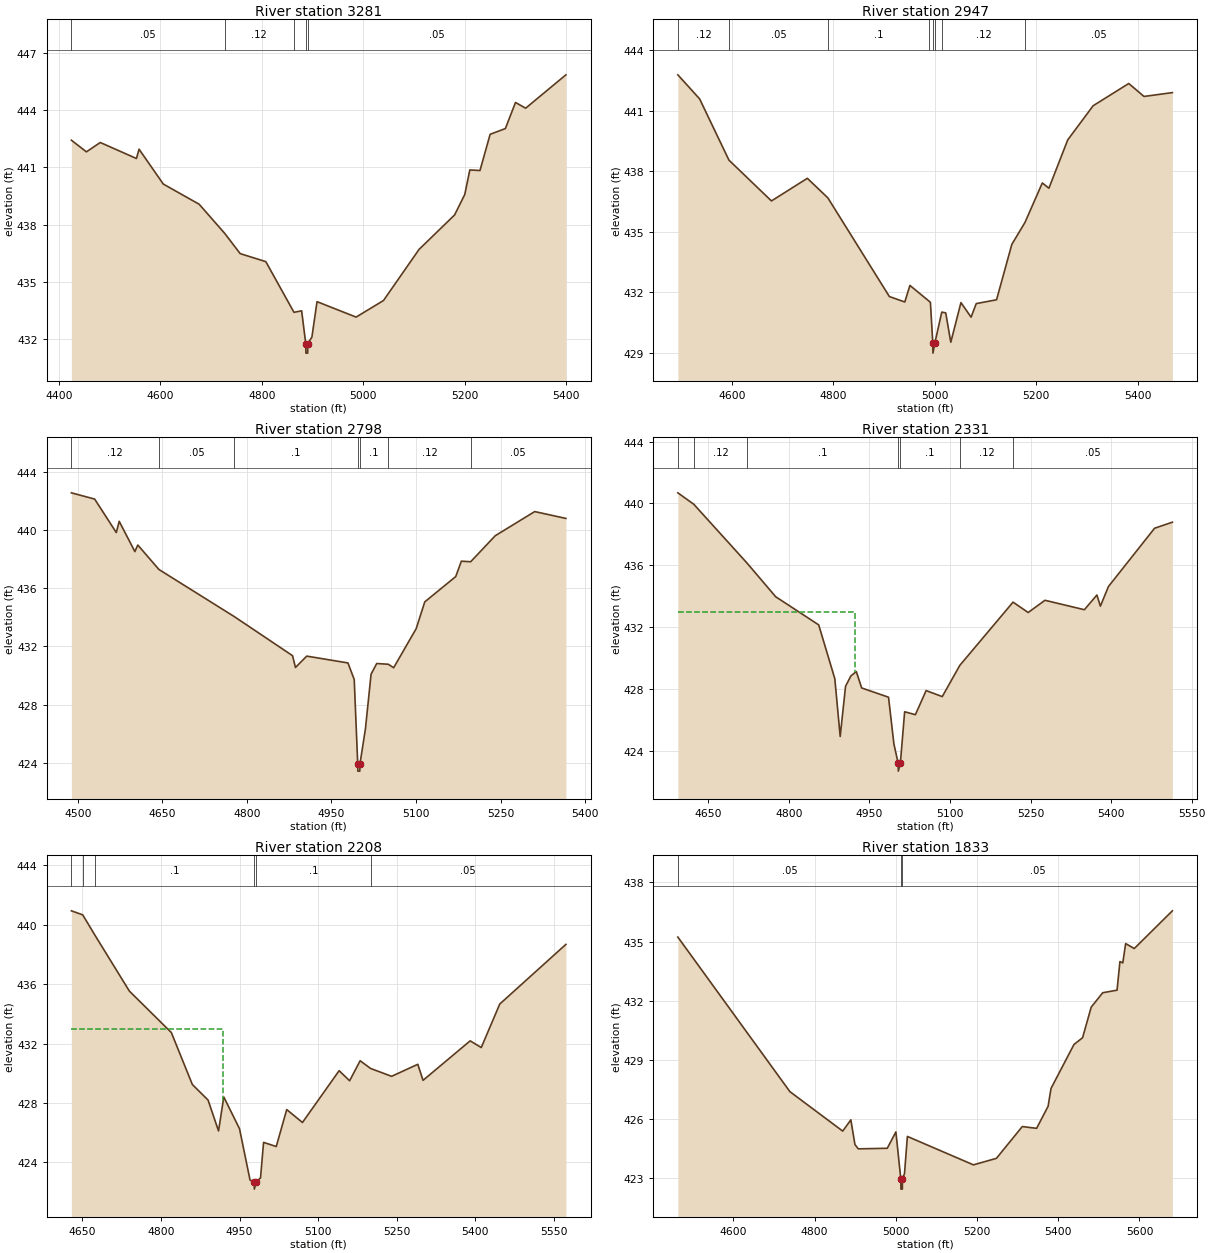
Type RM Length L Ch R = 1 ,3281    ,334,334,334
BEGIN DESCRIPTION:
Lacy 077 2133
END DESCRIPTION:
XS GIS Cut Line= 3
      2743755.33      6882244.21      2743179.54      6882163.32
      2742786.78      6882175.57
#Sta/Elev= 30
  4424.6  442.43  4454.2  441.82  4481.5  442.31  4552.8  441.47  4557.9  441.96
  4605.7  440.13  4676.4  439.07  4726.8  437.54  4757.2  436.48  4807.7  436.06
  4863.2   433.4  4878.3  433.48  4886.4  431.76  4886.7  431.26  4890.2  431.26
  4890.4  431.76  4898.5   432.1  4908.6  433.96  4985.6  433.15  5039.6  434.02
  5109.6   436.7  5179.7  438.51  5199.7  439.58  5209.7  440.87  5229.7  440.84
  5249.7  442.74  5279.7  443.04  5299.7  444.41  5319.7  444.11    5399  445.86
#Mann= 5 ,-1 , 0
  4424.6     .05       0  4726.8     .12       0  4863.2     .05       0
  4886.4     .04       0  4890.4     .05       0
Bank Sta=4886.4,4890.4
XS Rating Curve= 0 ,0
Exp/Cntr=0.3,0.1

Type RM Length L Ch R = 1 ,2947    ,149,149,149
BEGIN DESCRIPTION:
Lacy 077 2132
END DESCRIPTION:
XS GIS Cut Line= 3
      2743778.45      6881965.51      2743277.76      6881890.75
       2742810.2      6881922.77
#Sta/Elev= 30
  4493.3  442.77  4536.2  441.58    4594  438.55  4677.8  436.53  4748.6  437.65
  4789.1  436.68  4910.3   431.8  4940.7  431.53  4950.8  432.35  4988.6  431.57
  4991.2  431.51  4995.9   429.5  4996.2     429  4999.9   429.5  5013.6  431.03
  5021.4  430.99  5031.4  429.54  5051.4   431.5  5071.4  430.78  5081.5  431.45
  5121.6  431.64  5151.7  434.38  5177.7  435.47  5211.8  437.42  5224.8  437.16
  5261.9  439.55    5312  441.24  5382.2  442.34  5412.3   441.7  5468.2  441.89
#Mann= 8 ,-1 , 0
  4493.3     .12       0    4594     .05       0  4789.1      .1       0
  4988.6     .05       0  4995.9     .04       0  4999.9     .05       0
  5013.6     .12       0  5177.7     .05       0
Bank Sta=4995.9,4999.9
XS Rating Curve= 0 ,0
Exp/Cntr=0.3,0.1

Type RM Length L Ch R = 1 ,2798    ,467,467,467
BEGIN DESCRIPTION:
Lacy 077 2130
END DESCRIPTION:
XS GIS Cut Line= 3
      2743765.62      6881889.43        2743274.      6881741.29
      2742910.77      6881756.39
#Sta/Elev= 30
  4488.8  442.56  4530.1  442.13  4568.4  439.83  4573.6   440.6  4601.4  438.52
  4606.6  438.97    4644  437.29    4778  434.04    4881  431.36  4886.2  430.55
  4906.2  431.33  4979.3  430.86  4990.4  429.72  4996.6  423.92  4996.8  423.42
  5000.3  423.42  5000.6  423.92  5010.3  426.34  5020.3  430.09  5030.3  430.82
  5050.9  430.77  5060.3  430.53  5100.3  433.22  5115.5  435.06  5170.4   436.8
  5180.4  437.86  5196.9  437.82  5240.5  439.61  5310.5  441.27  5365.8   440.8
#Mann= 7 ,-1 , 0
  4488.8     .12       0    4644     .05       0    4778      .1       0
  4996.6     .07       0  5000.6      .1       0  5050.9     .12       0
  5196.9     .05       0
Bank Sta=4996.6,5000.6
XS Rating Curve= 0 ,0
Exp/Cntr=0.3,0.1

Type RM Length L Ch R = 1 ,2331    ,123,123,123
BEGIN DESCRIPTION:
Lacy 077 2129
END DESCRIPTION:
XS GIS Cut Line= 3
      2743728.12      6881310.56      2743062.09      6881321.64
      2742825.16      6881414.49
#Sta/Elev= 30
  4593.5  440.69  4623.2  439.95  4722.2  436.15  4775.6  433.97  4855.7  432.15
  4885.7  428.67  4895.7  424.93  4905.7  428.18  4915.7  428.85  4925.7  429.13
  4935.7  428.07  4985.7  427.47  4995.7  424.45  5003.7  423.19  5003.9  422.69
  5007.7  423.19  5015.7  426.53  5035.7  426.34  5055.7   427.9  5085.7  427.51
  5118.4  429.53  5217.5  433.62  5245.7  432.95  5276.9  433.74  5350.3  433.13
  5373.6  434.08  5380.1  433.36  5395.1  434.63    5481   438.4  5514.1  438.79
#Mann= 7 ,-1 , 0
  4593.5     .05       0  4623.2     .12       0  4722.2      .1       0
  5003.7     .07       0  5007.7      .1       0  5118.4     .12       0
  5217.5     .05       0
#XS Ineff= 2 , 0
       0    4924     433               0
Permanent Ineff=
       F       F
Bank Sta=5003.7,5007.7
XS Rating Curve= 0 ,0
Exp/Cntr=0.3,0.1

Type RM Length L Ch R = 1 ,2208    ,375,375,375
BEGIN DESCRIPTION:
Lacy 077 2128
END DESCRIPTION:
XS GIS Cut Line= 4
      2743646.58      6881193.87      2743279.41      6881208.89
      2742941.72      6881218.13      2742773.22      6881386.65
#Sta/Elev= 30
  4629.1  440.94  4650.7  440.67  4673.5  439.33  4739.8  435.53  4819.8  432.74
  4859.9  429.24  4889.9  428.19  4909.9  426.11  4919.9   428.4  4949.9  426.26
    4970   422.8    4978  422.69  4978.2  422.19    4982  422.69    4990  422.95
  4995.8  425.34    5020  425.06    5040  427.55    5070  426.68    5140  430.17
    5160  429.49  5180.1  430.84    5200  430.32  5240.1  429.79  5290.1   430.6
  5300.1  429.52    5390  432.18  5411.2  431.73  5446.5  434.66  5572.7  438.68
#Mann= 6 ,-1 , 0
  4629.1     .05       0  4650.7     .12       0  4673.5      .1       0
    4978     .07       0    4982      .1       0    5200     .05       0
#XS Ineff= 2 , 0
       0    4918     433               0
Permanent Ineff=
       F       F
Bank Sta=4978,4982
XS Rating Curve= 0 ,0
Exp/Cntr=0.3,0.1

Type RM Length L Ch R = 1 ,1833    ,314,314,314
BEGIN DESCRIPTION:
Lacy 077 2127
END DESCRIPTION:
XS GIS Cut Line= 3
      2743651.54      6880832.48      2743204.51      6880813.12
      2742663.21      6881360.82
#Sta/Elev= 30
  4463.5  435.23  4739.3   427.4  4869.4   425.4  4889.4  425.97  4899.5  424.72
  4907.7   424.5  4979.1  424.53  5000.3  425.36  5012.5  422.96  5012.7  422.46
  5016.2  422.46  5016.5  422.96  5021.5  423.25  5028.6  425.13  5191.2  423.69
  5247.8  424.02  5311.5  425.63  5346.8  425.54  5375.1  426.66  5382.2  427.56
  5438.8  429.79  5459.9  430.13  5481.2  431.68  5509.5  432.41  5544.8  432.54
  5551.9  433.99  5558.9  433.92    5566   434.9  5587.2  434.65    5681  436.56
#Mann= 3 ,-1 , 0
  4463.5     .05       0  5012.5     .04       0  5016.5     .05       0
Bank Sta=5012.5,5016.5
XS Rating Curve= 0 ,0
Exp/Cntr=0.3,0.1

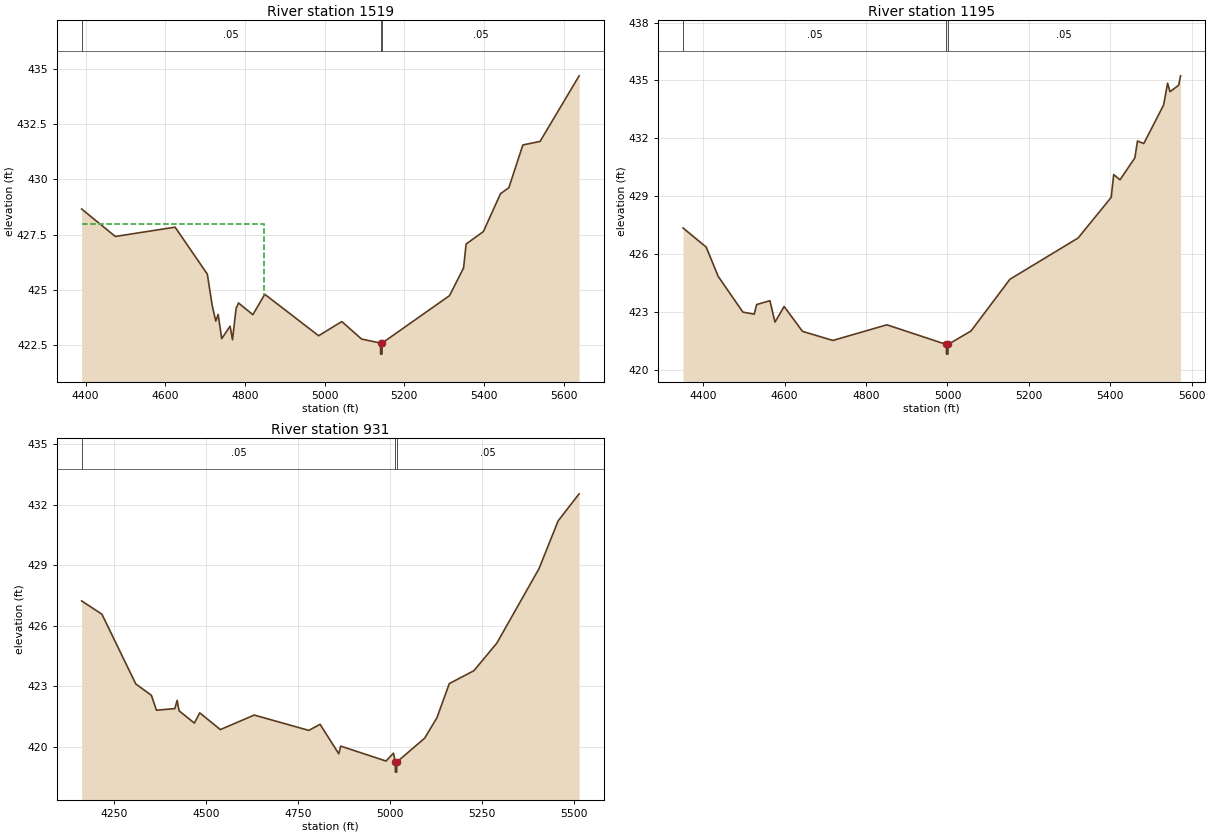
Type RM Length L Ch R = 1 ,1519    ,324,324,324
BEGIN DESCRIPTION:
Lacy 077 2126
END DESCRIPTION:
XS GIS Cut Line= 3
      2743388.47      6880477.21      2742881.16      6880816.11
      2742381.82      6881215.16
#Sta/Elev= 30
  4389.9  428.66  4474.4  427.42  4624.6  427.84  4705.5  425.72  4717.7  424.31
  4726.7   423.6  4732.7   423.9  4741.6  422.81  4762.7  423.37  4768.7  422.76
  4777.7  424.17  4783.7  424.42  4819.8  423.89  4849.8  424.81    4985  422.94
  5043.2  423.58  5092.9  422.79  5140.5  422.61  5140.7  422.11  5144.2  422.11
  5144.5  422.61  5313.8  424.75    5349     426  5355.4  427.08  5398.7  427.64
  5441.8  429.35  5462.7  429.62  5497.9  431.55  5541.1  431.71  5639.2  434.67
#Mann= 3 ,-1 , 0
  4389.9     .05       0  5140.5     .04       0  5144.5     .05       0
#XS Ineff= 2 , 0
       0    4849     428               0
Permanent Ineff=
       F       F
Bank Sta=5140.5,5144.5
XS Rating Curve= 0 ,0
Exp/Cntr=0.3,0.1

Type RM Length L Ch R = 1 ,1195    ,264,264,264
BEGIN DESCRIPTION:
Lacy 077 2125
END DESCRIPTION:
XS GIS Cut Line= 3
      2743176.45      6880385.54      2742599.95      6880685.13
      2742307.21      6881177.36
#Sta/Elev= 30
  4350.3  427.35  4407.2  426.36  4436.7  424.84  4497.3  422.99  4525.1  422.88
  4531.1  423.38  4563.7  423.58  4576.2  422.47  4598.7  423.28  4643.8  421.99
  4718.5  421.52  4851.2  422.33  4997.4  421.31  4997.7  420.81  5001.2  420.81
  5001.4  421.31  5057.9  422.01  5153.4  424.69    5321  426.83  5402.4  428.94
  5408.5  430.12  5424.1  429.85  5460.6  430.99  5466.9  431.86  5482.5  431.73
  5531.2  433.73    5541  434.86  5546.8  434.42  5568.2  434.75  5572.7  435.24
#Mann= 3 ,-1 , 0
  4350.3     .05       0  4997.4     .04       0  5001.4     .05       0
Bank Sta=4997.4,5001.4
XS Rating Curve= 0 ,0
Exp/Cntr=0.3,0.1

Type RM Length L Ch R = 1 ,931     ,0,0,0
BEGIN DESCRIPTION:
Lacy 077 2124
END DESCRIPTION:
XS GIS Cut Line= 3
      2743164.33      6880277.89      2742376.26      6880561.35
      2742233.06      6881055.73
#Sta/Elev= 30
  4162.5  427.24  4217.6  426.58  4309.7  423.12    4352  422.56  4365.8  421.82
  4415.8   421.9    4422  422.31  4427.3  421.79  4468.9  421.18  4483.4  421.69
  4539.5  420.86  4631.6  421.58  4779.9  420.82  4810.6  421.12  4861.4  419.66
  4866.7  420.04  4989.7   419.3    5010  419.69  5015.1  419.25  5015.3  418.75
  5018.8  418.75  5019.1  419.25  5094.7  420.43  5128.3  421.45  5161.8  423.14
  5228.7  423.78  5291.1  425.15  5405.7  428.84  5457.7  431.21  5514.7  432.55
#Mann= 3 ,-1 , 0
  4162.5     .05       0  5015.1     .04       0  5019.1     .05       0
Bank Sta=5015.1,5019.1
XS Rating Curve= 0 ,0
Exp/Cntr=0.3,0.1

Chan Stop Cuts=-1
Use User Specified Reach Order=0
Composite Channel Slope=5