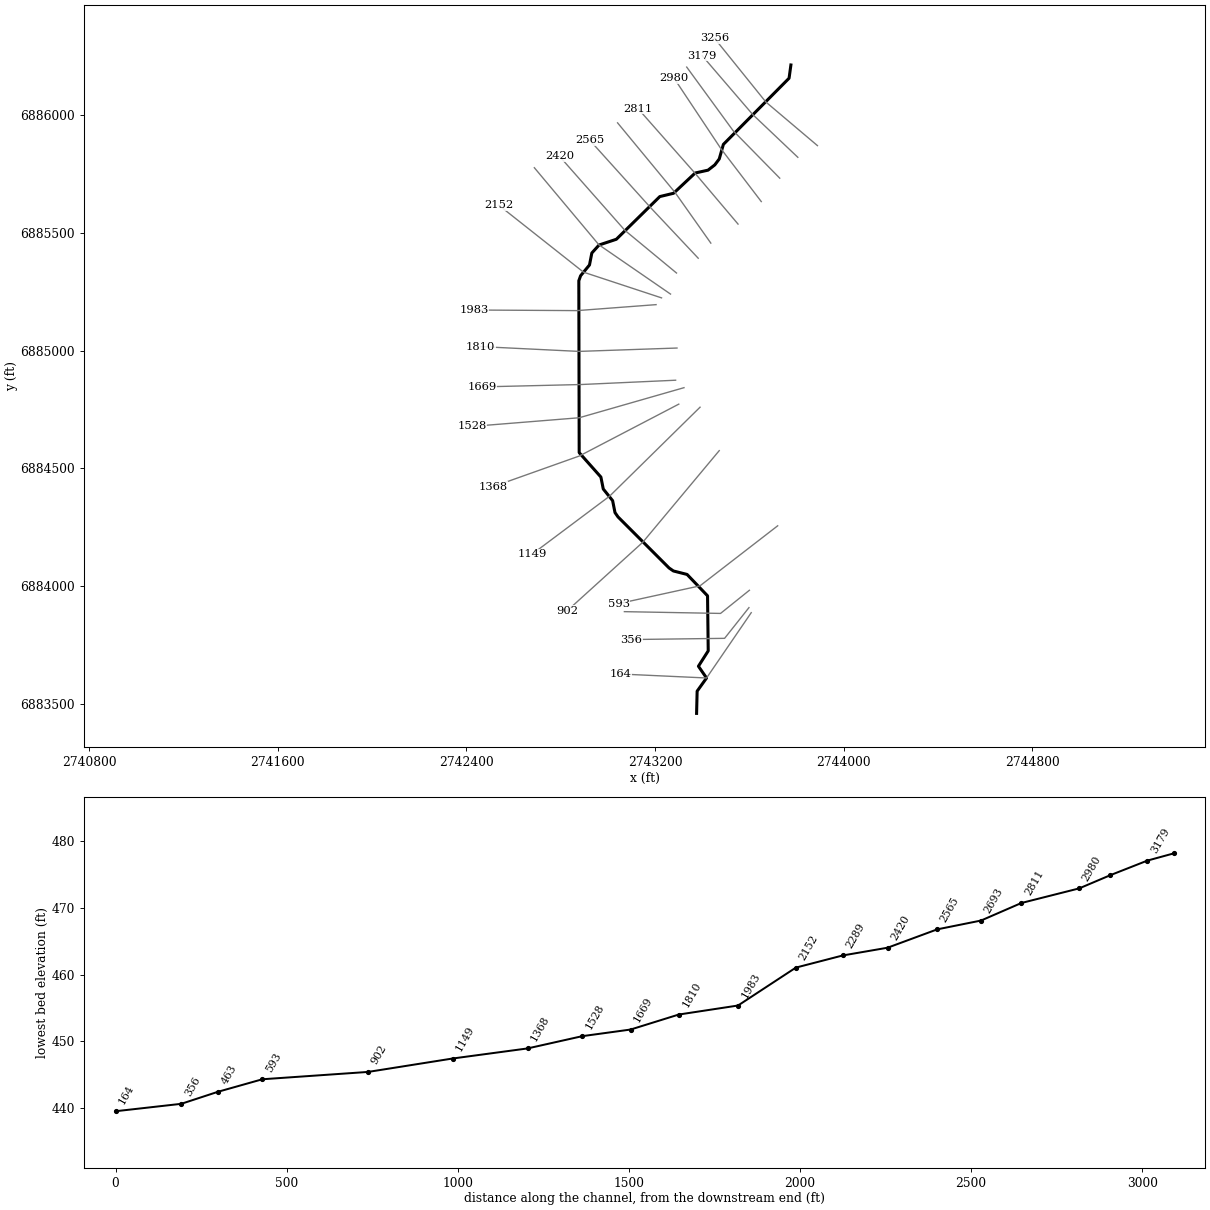
--- Lacy 078.prj (project) ---

Proj Title=Lacy 078 Base Level Engineering
Current Plan=p01
Default Exp/Contr=0.3,0.1
English Units
Geom File=g01
Flow File=f01
Plan File=p01
BEGIN DESCRIPTION:
Lacy 078
END DESCRIPTION:

--- Lacy 078.p01 (plan) ---

Plan Title=Multiple Run
Short Identifier=Multiple
Geom File=g01
Flow File=f01
Subcritical Flow
K Sum by GR= 0
Std Step Tol= 0.01
Critical Tol= 0.01
Num of Std Step Trials= 20
Max Error Tol= 0.3
Flow Tol Ratio= 0.001
Split Flow NTrial= 30
Split Flow Tol= 0.02
Split Flow Ratio= 0.02
Log Output Level= 0
Friction Slope Method= 1
Unsteady Friction Slope Method= 2
Unsteady Bridges Friction Slope Method= 1
Parabolic Critical Depth
Global Vel Dist=  1 , 1 , 1
Global Log Level= 0
CheckData=True
Encroach Param= -1, 0, 0, 0
BEGIN DESCRIPTION:
Multiple Run
END DESCRIPTION:

--- Lacy 078.f01 (steady flow) ---

Flow Title=Multiple
Number of Profiles=7
Profile Names=10-year,25-year,50-year,1pct_min,100-year,1pct_plu,500-year
River Rch & RM= Lacy 078,Reach-1,3256
     145     178     203     116     231     460     297
Boundary for River Rch & Prof#=Lacy 078,Reach-1,1
Up Type=0
Dn Type=3
Dn Slope=0.005
Boundary for River Rch & Prof#=Lacy 078,Reach-1,2
Up Type=0
Dn Type=3
Dn Slope=0.005
Boundary for River Rch & Prof#=Lacy 078,Reach-1,3
Up Type=0
Dn Type=3
Dn Slope=0.005
Boundary for River Rch & Prof#=Lacy 078,Reach-1,4
Up Type=0
Dn Type=3
Dn Slope=0.005
Boundary for River Rch & Prof#=Lacy 078,Reach-1,5
Up Type=0
Dn Type=3
Dn Slope=0.005
Boundary for River Rch & Prof#=Lacy 078,Reach-1,6
Up Type=0
Dn Type=3
Dn Slope=0.005
Boundary for River Rch & Prof#=Lacy 078,Reach-1,7
Up Type=0
Dn Type=3
Dn Slope=0.005

--- Lacy 078.g01 (geometry) ---

Geom Title=Existing Conditions

River Reach=Lacy 078,Reach-1
Reach XY= 30
      2743776.00      6886211.00      2743768.24      6886154.79
      2743489.64      6885874.20      2743472.11      6885812.43
      2743453.14      6885787.16      2743424.57      6885764.89
      2743369.98      6885752.82      2743278.28      6885666.87
      2743219.95      6885652.84      2743035.66      6885471.79
      2742962.44      6885447.51      2742931.73      6885413.55
      2742921.77      6885362.78      2742884.09      6885317.08
      2742876.51      6885295.79      2742878.06      6884566.86
      2742970.15      6884463.29      2742980.19      6884412.73
      2743019.90      6884363.19      2743029.95      6884312.63
      2743042.64      6884294.32      2743259.33      6884077.65
      2743277.65      6884064.98      2743335.70      6884050.23
      2743422.47      6883959.55      2743425.35      6883726.16
      2743383.79      6883660.90      2743418.25      6883611.09
      2743378.33      6883555.23      2743376.00      6883461.00

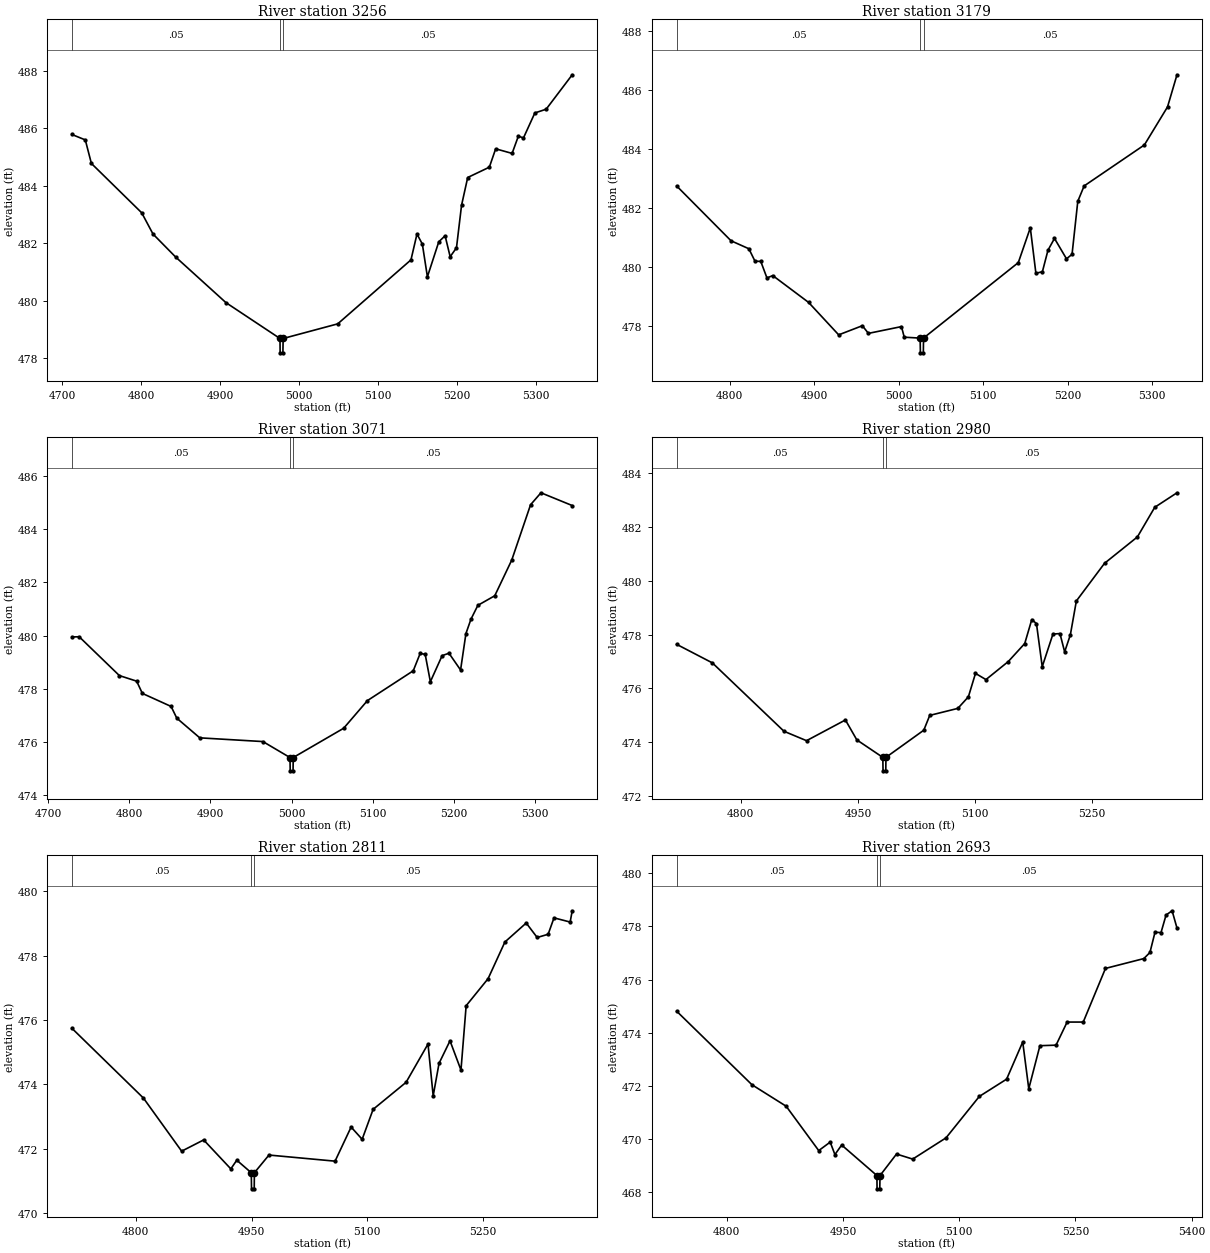
Type RM Length L Ch R = 1,3256,77,77,77
BEGIN DESCRIPTION:
Lacy 078 2162
END DESCRIPTION:
XS GIS Cut Line= 3
      2743888.60      6885868.98      2743669.57      6886054.27
      2743452.21      6886324.00
#Sta/Elev= 30
  4712.3  485.79  4729.3  485.60  4737.0  484.78  4800.7  483.06  4815.0  482.32
  4843.6  481.52  4907.3  479.93  4975.7  478.68  4975.9  478.18  4979.4  478.18
  4979.7  478.68  5048.8  479.19  5141.5  481.42  5149.1  482.32  5155.9  481.97
  5162.3  480.83  5176.7  482.05  5184.7  482.26  5191.1  481.53  5199.1  481.84
  5205.5  483.32  5213.3  484.29  5240.7  484.65  5248.7  485.29  5269.5  485.13
  5277.4  485.73  5283.9  485.67  5298.3  486.54  5312.6  486.67  5345.6  487.87
#Mann=3,-1,0
  4712.3    0.05       0  4975.7    0.04       0  4979.7    0.05       0
Bank Sta=4975.7,4979.7
Exp/Cntr=0.3,0.1

Type RM Length L Ch R = 1,3179,108,108,108
BEGIN DESCRIPTION:
Lacy 078 2161
END DESCRIPTION:
XS GIS Cut Line= 3
      2743805.36      6885819.43      2743614.00      6886000.98
      2743399.97      6886250.08
#Sta/Elev= 30
  4737.3  482.76  4801.7  480.90  4822.8  480.63  4830.0  480.21  4836.9  480.20
  4844.2  479.64  4851.1  479.72  4893.5  478.81  4929.1  477.71  4957.1  478.02
  4964.3  477.76  5003.4  477.99  5006.7  477.63  5025.5  477.60  5025.8  477.10
  5029.3  477.10  5029.5  477.60  5141.7  480.16  5155.9  481.34  5162.5  479.80
  5170.2  479.85  5176.8  480.58  5184.5  480.98  5198.7  480.29  5205.3  480.44
  5212.1  482.24  5219.6  482.76  5290.9  484.15  5318.3  485.44  5329.5  486.53
#Mann=3,-1,0
  4737.3    0.05       0  5025.5    0.04       0  5029.5    0.05       0
Bank Sta=5025.5,5029.5
Exp/Cntr=0.3,0.1

Type RM Length L Ch R = 1,3071,91,91,91
BEGIN DESCRIPTION:
Lacy 078 2160
END DESCRIPTION:
XS GIS Cut Line= 3
      2743728.69      6885730.94      2743531.30      6885931.90
      2743334.11      6886202.10
#Sta/Elev= 30
  4729.4  479.95  4738.4  479.96  4787.9  478.50  4809.2  478.29  4816.2  477.83
  4851.6  477.34  4858.6  476.90  4886.9  476.16  4964.7  476.02  4998.0  475.42
  4998.3  474.92  5001.8  474.92  5002.0  475.42  5064.1  476.52  5093.4  477.56
  5149.8  478.68  5158.3  479.33  5164.5  479.30  5170.9  478.27  5185.4  479.25
  5193.8  479.34  5208.1  478.71  5214.7  480.08  5220.9  480.62  5229.4  481.14
  5250.2  481.50  5271.1  482.84  5294.3  484.92  5307.1  485.37  5345.6  484.89
#Mann=3,-1,0
  4729.4    0.05       0  4998.0    0.04       0  5002.0    0.05       0
Bank Sta=4998,5002
Exp/Cntr=0.3,0.1

Type RM Length L Ch R = 1,2980,169,169,169
BEGIN DESCRIPTION:
Lacy 078 2159
END DESCRIPTION:
XS GIS Cut Line= 3
      2743650.35      6885631.68      2743479.96      6885854.90
      2743280.61      6886154.76
#Sta/Elev= 30
  4717.8  477.64  4763.6  476.95  4855.3  474.41  4884.2  474.06  4934.0  474.83
  4948.6  474.09  4981.9  473.44  4982.2  472.94  4985.7  472.94  4985.9  473.44
  5034.4  474.45  5042.0  475.00  5078.0  475.26  5091.5  475.69  5100.6  476.56
  5114.0  476.33  5142.6  477.00  5163.7  477.67  5172.7  478.56  5178.7  478.41
  5186.1  476.81  5199.8  478.02  5208.8  478.04  5214.8  477.36  5222.1  477.99
  5229.8  479.25  5265.9  480.65  5308.0  481.63  5330.2  482.73  5358.7  483.27
#Mann=3,-1,0
  4717.8    0.05       0  4981.9    0.04       0  4985.9    0.05       0
Bank Sta=4981.9,4985.9
Exp/Cntr=0.3,0.1

Type RM Length L Ch R = 1,2811,118,118,118
BEGIN DESCRIPTION:
Lacy 078 2158
END DESCRIPTION:
XS GIS Cut Line= 3
      2743551.77      6885536.24      2743366.83      6885754.78
      2743127.47      6886026.10
#Sta/Elev= 30
  4717.3  475.74  4810.0  473.57  4859.5  471.92  4888.0  472.27  4923.2  471.37
  4930.9  471.64  4949.7  471.25  4950.0  470.75  4953.5  470.75  4953.7  471.25
  4972.6  471.80  5058.2  471.61  5079.0  472.67  5093.3  472.29  5107.5  473.22
  5150.2  474.06  5178.6  475.25  5185.3  473.64  5192.9  474.65  5207.1  475.35
  5221.3  474.44  5228.0  476.44  5256.4  477.28  5278.2  478.42  5305.8  479.01
  5320.0  478.56  5334.2  478.66  5341.8  479.17  5362.7  479.04  5365.4  479.39
#Mann=3,-1,0
  4717.3    0.05       0  4949.7    0.04       0  4953.7    0.05       0
Bank Sta=4949.7,4953.7
Exp/Cntr=0.3,0.1

Type RM Length L Ch R = 1,2693,128,128,128
BEGIN DESCRIPTION:
Lacy 078 2157
END DESCRIPTION:
XS GIS Cut Line= 3
      2743436.35      6885455.53      2743284.49      6885670.55
      2743040.92      6885965.55
#Sta/Elev= 30
  4735.2  474.81  4832.4  472.04  4876.6  471.23  4918.6  469.56  4933.4  469.88
  4939.5  469.41  4948.2  469.77  4993.7  468.62  4993.9  468.12  4997.4  468.12
  4997.7  468.62  5019.0  469.43  5039.9  469.24  5082.9  470.04  5125.9  471.60
  5161.1  472.25  5181.9  473.65  5189.7  471.89  5204.1  473.51  5224.9  473.53
  5239.2  474.40  5260.0  474.40  5288.7  476.42  5338.2  476.79  5346.1  477.02
  5352.6  477.78  5360.4  477.77  5366.9  478.43  5374.7  478.59  5381.0  477.94
#Mann=3,-1,0
  4735.2    0.05       0  4993.7    0.04       0  4997.7    0.05       0
Bank Sta=4993.7,4997.7
Exp/Cntr=0.3,0.1

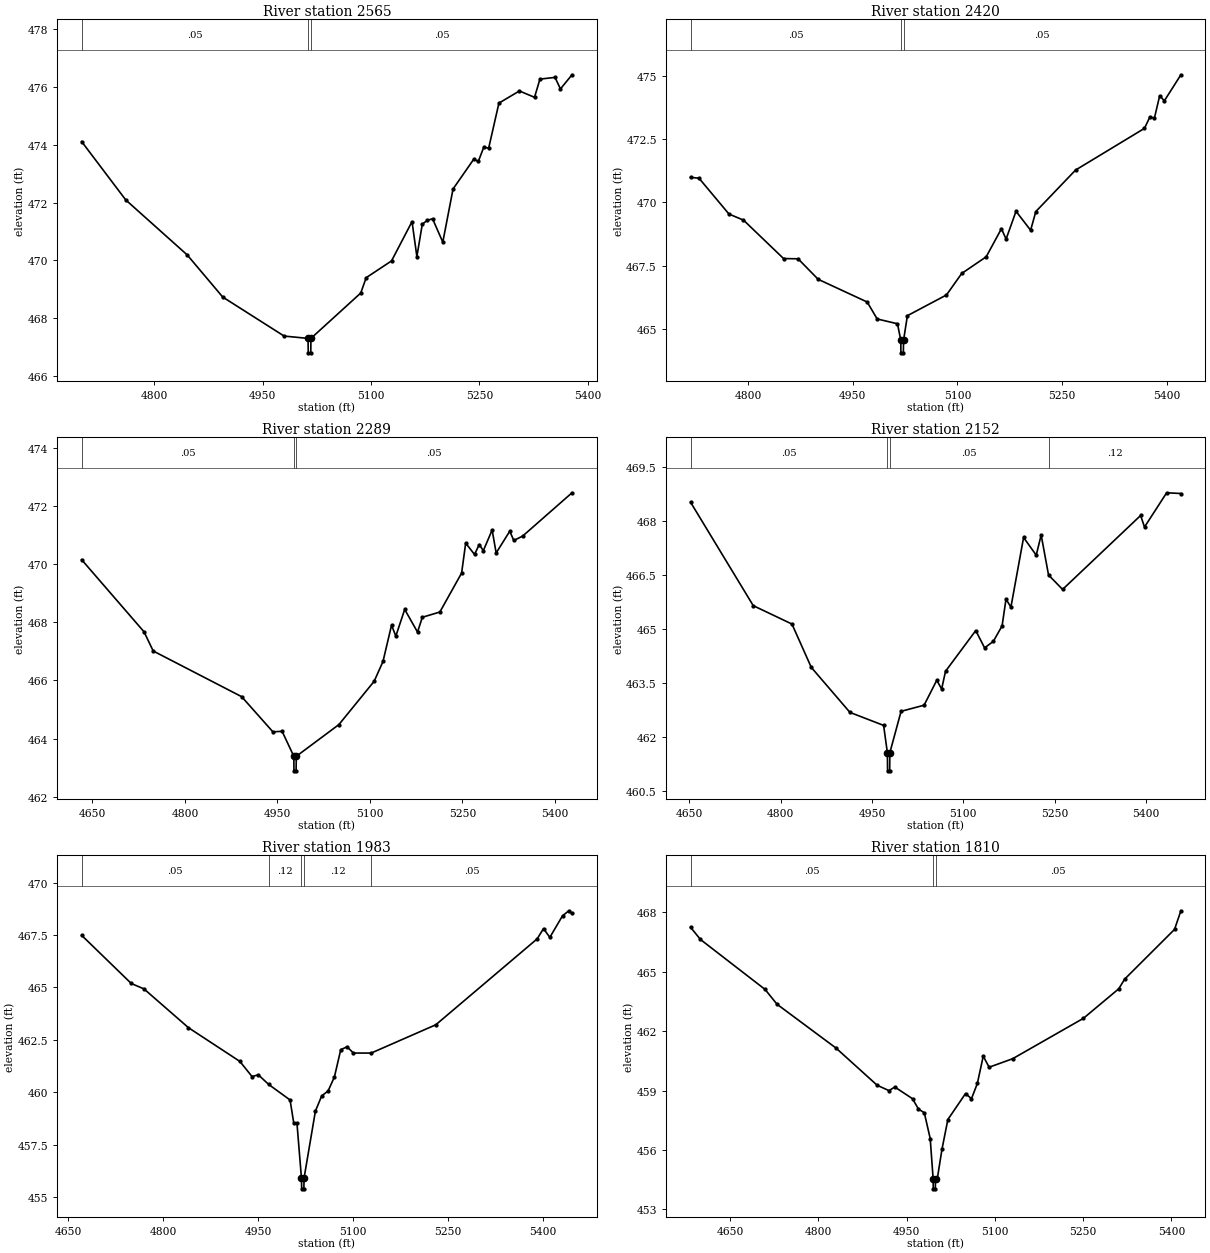
Type RM Length L Ch R = 1,2565,145,145,145
BEGIN DESCRIPTION:
Lacy 078 2156
END DESCRIPTION:
XS GIS Cut Line= 3
      2743382.88      6885391.47      2743179.64      6885607.42
      2742923.44      6885891.38
#Sta/Elev= 30
  4699.3  474.11  4760.4  472.09  4845.4  470.19  4894.7  468.73  4979.7  467.38
  5012.8  467.30  5013.1  466.80  5016.6  466.80  5016.8  467.30  5085.8  468.87
  5093.3  469.40  5128.4  469.98  5156.8  471.34  5163.5  470.13  5171.0  471.25
  5177.7  471.38  5185.2  471.44  5199.4  470.63  5213.6  472.47  5242.0  473.49
  5248.7  473.43  5256.2  473.92  5262.9  473.88  5277.1  475.44  5305.5  475.86
  5326.4  475.64  5333.9  476.27  5354.8  476.33  5362.3  475.93  5378.3  476.42
#Mann=3,-1,0
  4699.3    0.05       0  5012.8    0.04       0  5016.8    0.05       0
Bank Sta=5012.8,5016.8
Exp/Cntr=0.3,0.1

Type RM Length L Ch R = 1,2420,131,131,131
BEGIN DESCRIPTION:
Lacy 078 2155
END DESCRIPTION:
XS GIS Cut Line= 3
      2743290.81      6885328.69      2743071.95      6885509.60
      2742794.89      6885823.32
#Sta/Elev= 30
  4717.6  470.99  4729.7  470.96  4772.7  469.54  4793.5  469.30  4850.9  467.78
  4871.7  467.77  4900.4  466.96  4970.7  466.06  4985.0  465.39  5014.1  465.20
  5018.8  464.55  5019.0  464.05  5022.5  464.05  5022.8  464.55  5028.3  465.52
  5084.3  466.34  5106.1  467.19  5141.2  467.85  5163.0  468.96  5169.7  468.55
  5183.9  469.65  5204.8  468.90  5212.3  469.64  5269.2  471.28  5367.9  472.93
  5375.5  473.37  5382.2  473.34  5389.7  474.22  5396.4  474.02  5420.1  475.05
#Mann=3,-1,0
  4717.6    0.05       0  5018.8    0.04       0  5022.8    0.05       0
Bank Sta=5018.8,5022.8
Exp/Cntr=0.3,0.1

Type RM Length L Ch R = 1,2289,137,137,137
BEGIN DESCRIPTION:
Lacy 078 2154
END DESCRIPTION:
XS GIS Cut Line= 3
      2743265.44      6885239.33      2742961.55      6885448.51
      2742687.85      6885775.30
#Sta/Elev= 30
  4632.5  470.15  4733.7  467.67  4748.6  467.01  4892.0  465.44  4942.7  464.23
  4957.6  464.25  4976.6  463.39  4976.8  462.89  4980.3  462.89  4980.6  463.39
  5049.7  464.48  5106.9  465.97  5121.2  466.65  5135.1  467.90  5142.0  467.52
  5156.4  468.44  5177.2  467.66  5185.0  468.17  5213.4  468.35  5248.7  469.69
  5255.3  470.72  5269.6  470.33  5277.3  470.67  5283.9  470.46  5298.2  471.17
  5304.7  470.38  5326.8  471.13  5333.3  470.81  5347.6  470.96  5427.7  472.45
#Mann=3,-1,0
  4632.5    0.05       0  4976.6    0.04       0  4980.6    0.05       0
Bank Sta=4976.6,4980.6
Exp/Cntr=0.3,0.1

Type RM Length L Ch R = 1,2152,169,169,169
BEGIN DESCRIPTION:
Lacy 078 2153
END DESCRIPTION:
XS GIS Cut Line= 3
      2743227.37      6885223.23      2742896.48      6885332.22
      2742537.62      6885615.86
#Sta/Elev= 30
  4651.7  468.52  4754.8  465.65  4818.4  465.14  4850.1  463.94  4913.7  462.69
  4969.0  462.33  4975.2  461.57  4975.5  461.07  4979.0  461.07  4979.2  461.57
  4997.7  462.72  5035.5  462.89  5056.3  463.58  5064.4  463.34  5070.7  463.83
  5120.4  464.96  5134.9  464.48  5149.3  464.66  5163.7  465.09  5170.1  465.83
  5178.2  465.61  5199.0  467.54  5219.8  467.05  5227.9  467.61  5240.0  466.50
  5263.1  466.10  5391.3  468.15  5397.7  467.83  5434.1  468.78  5457.5  468.76
#Mann=4,-1,0
  4651.7    0.05       0  4975.2    0.04       0  4979.2    0.05       0
  5240.0    0.12       0
Bank Sta=4975.2,4979.2
Exp/Cntr=0.3,0.1

Type RM Length L Ch R = 1,1983,173,173,173
BEGIN DESCRIPTION:
Lacy 078 2152
END DESCRIPTION:
XS GIS Cut Line= 3
      2743204.19      6885194.55      2742869.20      6885169.21
      2742430.95      6885171.72
#Sta/Elev= 30
  4671.2  467.49  4749.6  465.19  4769.7  464.93  4839.9  463.08  4921.1  461.47
  4940.2  460.75  4950.2  460.83  4966.6  460.37  5000.3  459.63  5006.2  458.51
  5011.2  458.51  5018.3  455.89  5018.6  455.39  5022.1  455.39  5022.3  455.89
  5040.3  459.10  5050.3  459.83  5060.3  460.06  5070.3  460.73  5080.3  462.03
  5090.3  462.17  5100.3  461.87  5128.4  461.87  5230.4  463.22  5390.4  467.32
  5400.4  467.81  5410.4  467.39  5430.4  468.42  5440.4  468.66  5445.4  468.54
#Mann=5,-1,0
  4671.2    0.05       0  4966.6    0.12       0  5018.3    0.07       0
  5022.3    0.12       0  5128.4    0.05       0
Bank Sta=5018.3,5022.3
Exp/Cntr=0.3,0.1

Type RM Length L Ch R = 1,1810,141,141,141
BEGIN DESCRIPTION:
Lacy 078 2151
END DESCRIPTION:
XS GIS Cut Line= 3
      2743292.93      6885010.50      2742877.01      6884996.22
      2742460.57      6885016.54
#Sta/Elev= 30
  4582.9  467.25  4599.8  466.63  4709.5  464.11  4729.9  463.36  4830.0  461.15
  4900.0  459.27  4920.0  459.00  4930.0  459.18  4960.1  458.59  4970.1  458.07
  4980.1  457.88  4990.1  456.58  4995.1  454.54  4995.3  454.04  4998.8  454.04
  4999.1  454.54  5002.1  454.54  5010.1  456.04  5020.1  457.54  5050.1  458.85
  5060.2  458.59  5070.2  459.36  5080.2  460.74  5090.2  460.18  5130.2  460.61
  5250.4  462.65  5310.4  464.14  5320.5  464.63  5405.2  467.14  5416.0  468.08
#Mann=3,-1,0
  4582.9    0.05       0  4995.1    0.04       0  4999.1    0.05       0
Bank Sta=4995.1,4999.1
Exp/Cntr=0.3,0.1

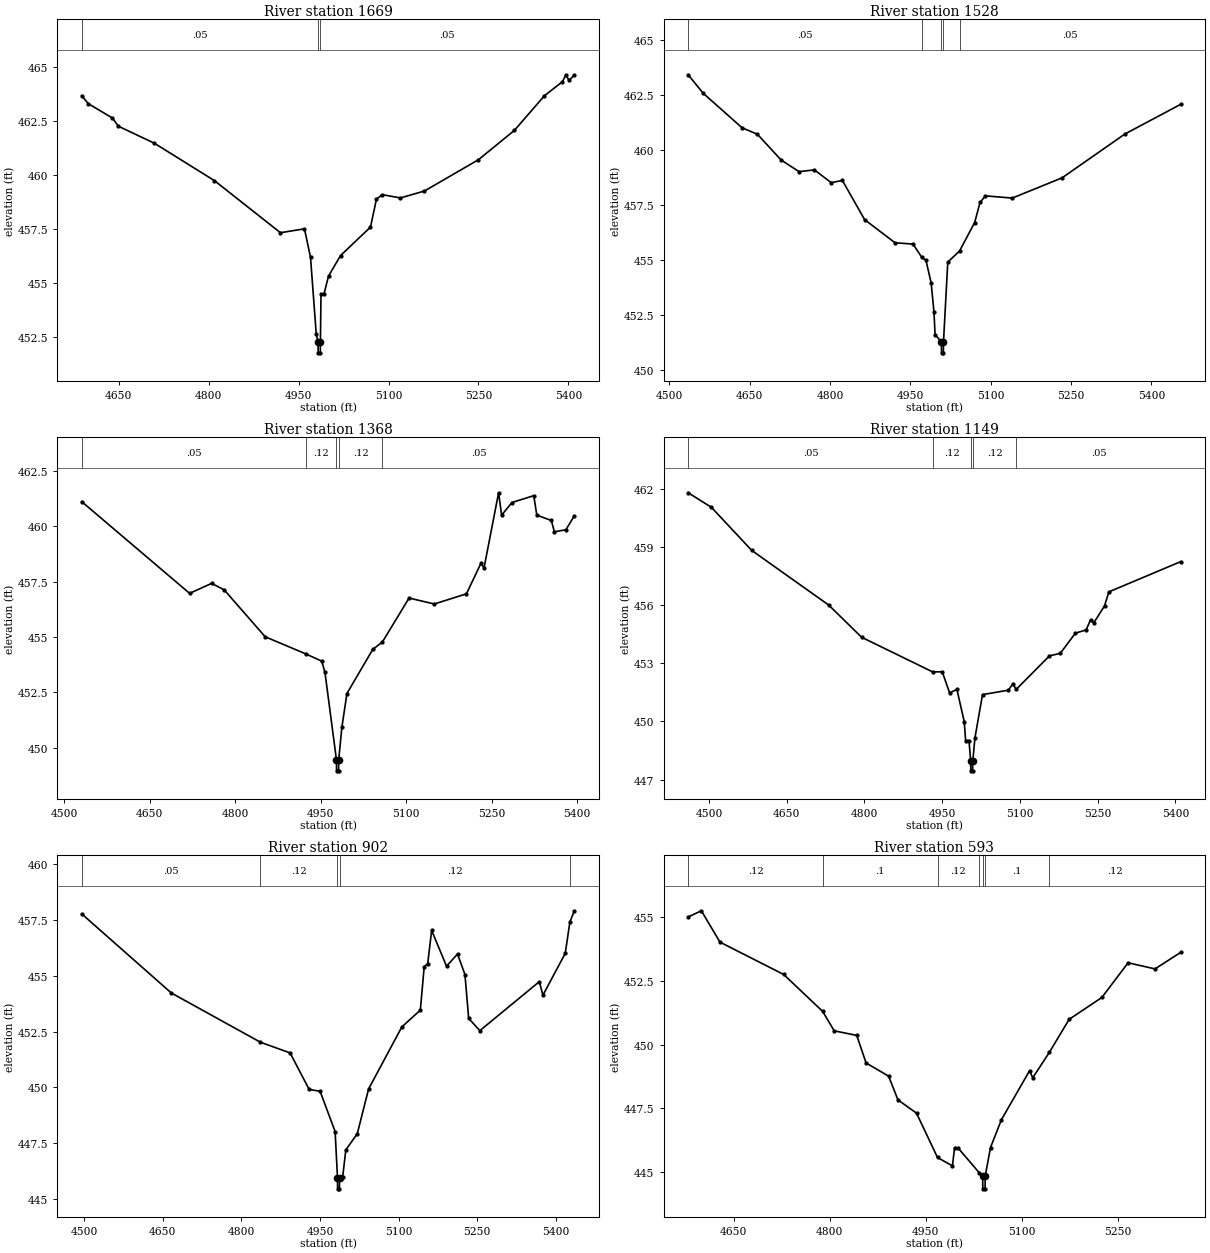
Type RM Length L Ch R = 1,1669,141,141,141
BEGIN DESCRIPTION:
Lacy 078 2149
END DESCRIPTION:
XS GIS Cut Line= 3
      2743287.06      6884873.98      2742885.87      6884855.72
      2742466.20      6884845.69
#Sta/Elev= 30
  4588.4  463.69  4599.5  463.32  4639.5  462.66  4649.5  462.28  4709.6  461.49
  4809.7  459.76  4919.8  457.35  4959.8  457.53  4969.9  456.21  4979.4  452.68
  4982.4  452.29  4982.7  451.79  4986.2  451.79  4986.4  452.29  4987.4  454.52
  4992.4  454.52  4999.9  455.34  5019.9  456.29  5069.9  457.61  5079.9  458.91
  5089.9  459.11  5119.9  458.96  5159.9  459.28  5250.0  460.73  5310.0  462.09
  5360.0  463.69  5390.0  464.34  5395.8  464.66  5400.8  464.40  5409.8  464.64
#Mann=3,-1,0
  4588.4    0.05       0  4982.4    0.04       0  4986.4    0.05       0
Bank Sta=4982.4,4986.4
Exp/Cntr=0.3,0.1

Type RM Length L Ch R = 1,1528,160,160,160
BEGIN DESCRIPTION:
Lacy 078 2150
END DESCRIPTION:
XS GIS Cut Line= 3
      2743322.64      6884842.36      2742878.24      6884714.83
      2742422.46      6884677.95
#Sta/Elev= 30
  4535.1  463.43  4563.1  462.59  4635.8  461.02  4664.3  460.73  4708.5  459.56
  4742.1  459.03  4770.7  459.11  4802.1  458.53  4822.9  458.63  4864.5  456.85
  4921.2  455.80  4954.9  455.74  4971.1  455.14  4979.0  455.00  4988.7  453.97
  4993.9  452.66  4996.0  451.63  5007.7  451.30  5008.0  450.80  5011.5  450.80
  5011.7  451.30  5019.7  454.92  5041.8  455.43  5069.9  456.72  5079.9  457.63
  5090.0  457.93  5140.1  457.83  5233.2  458.75  5350.4  460.74  5454.7  462.09
#Mann=5,-1,0
  4535.1    0.05       0  4971.1    0.12       0  5007.7    0.07       0
  5011.7    0.12       0  5041.8    0.05       0
Bank Sta=5007.7,5011.7
Exp/Cntr=0.3,0.1

Type RM Length L Ch R = 1,1368,219,219,219
BEGIN DESCRIPTION:
Lacy 078 2148
END DESCRIPTION:
XS GIS Cut Line= 3
      2743300.51      6884772.57      2742878.45      6884552.48
      2742512.96      6884422.52
#Sta/Elev= 30
  4531.0  461.11  4720.2  456.97  4758.7  457.42  4780.8  457.13  4852.8  455.01
  4923.8  454.24  4951.9  453.91  4957.6  453.40  4977.7  449.46  4977.9  448.96
  4981.4  448.96  4981.7  449.46  4987.2  450.92  4996.1  452.45  5041.4  454.44
  5058.4  454.78  5105.1  456.76  5149.3  456.49  5205.7  456.95  5231.2  458.33
  5236.5  458.11  5262.1  461.51  5267.4  460.50  5285.5  461.07  5323.8  461.38
  5329.1  460.50  5354.6  460.26  5359.9  459.75  5380.1  459.84  5394.9  460.47
#Mann=5,-1,0
  4531.0    0.05       0  4923.8    0.12       0  4977.7    0.07       0
  4981.7    0.12       0  5058.4    0.05       0
Bank Sta=4977.7,4981.7
Exp/Cntr=0.3,0.1

Type RM Length L Ch R = 1,1149,247,247,247
BEGIN DESCRIPTION:
Lacy 078 2147
END DESCRIPTION:
XS GIS Cut Line= 3
      2743390.67      6884759.59      2743007.23      6884382.38
      2742676.94      6884135.07
#Sta/Elev= 30
  4460.0  461.79  4504.8  461.04  4582.5  458.82  4731.1  456.00  4794.6  454.34
  4931.9  452.55  4950.2  452.56  4964.4  451.47  4978.5  451.65  4992.7  449.98
  4995.3  449.01  5001.8  449.01  5005.1  447.95  5005.3  447.45  5008.8  447.45
  5009.1  447.95  5013.3  449.15  5027.9  451.38  5077.9  451.61  5086.3  451.93
  5092.9  451.65  5157.1  453.38  5178.0  453.51  5207.1  454.55  5228.0  454.72
  5236.3  455.24  5242.6  455.08  5263.4  455.96  5271.7  456.68  5410.5  458.24
#Mann=5,-1,0
  4460.0    0.05       0  4931.9    0.12       0  5005.1    0.07       0
  5009.1    0.12       0  5092.9    0.05       0
Bank Sta=5005.1,5009.1
Exp/Cntr=0.3,0.1

Type RM Length L Ch R = 1,902,309,309,309
BEGIN DESCRIPTION:
Lacy 078 2146
END DESCRIPTION:
XS GIS Cut Line= 3
      2743472.08      6884575.34      2743147.62      6884186.59
      2742826.72      6883895.68
#Sta/Elev= 30
  4495.6  457.78  4666.5  454.23  4836.5  452.02  4893.0  451.54  4929.4  449.90
  4950.2  449.82  4978.9  448.01  4983.4  445.94  4983.6  445.44  4987.1  445.44
  4987.4  445.94  4993.2  445.95  4999.3  447.19  5021.1  447.91  5042.7  449.92
  5106.2  452.71  5141.4  453.46  5148.8  455.41  5155.5  455.55  5163.0  457.04
  5191.4  455.43  5212.3  455.98  5226.5  455.06  5233.6  453.09  5254.9  452.54
  5368.4  454.74  5375.2  454.13  5417.8  456.01  5426.6  457.41  5435.1  457.92
#Mann=5,-1,0
  4495.6    0.05       0  4836.5    0.12       0  4983.4    0.07       0
  4987.4    0.12       0  5426.6    0.05       0
Bank Sta=4983.4,4987.4
Exp/Cntr=0.3,0.1

Type RM Length L Ch R = 1,593,130,130,130
BEGIN DESCRIPTION:
Lacy 078 2145
END DESCRIPTION:
XS GIS Cut Line= 3
      2743719.93      6884256.55      2743390.45      6884001.90
      2743045.61      6883926.53
#Sta/Elev= 30
  4579.2  455.01  4599.8  455.25  4628.8  454.02  4728.4  452.75  4789.3  451.30
  4807.2  450.54  4842.5  450.36  4857.0  449.28  4892.3  448.76  4906.8  447.83
  4935.8  447.31  4968.6  445.57  4991.9  445.24  4995.3  445.95  5000.5  445.95
  5033.5  444.98  5039.1  444.84  5039.4  444.34  5042.9  444.34  5043.1  444.84
  5051.4  445.96  5068.4  447.05  5112.3  448.97  5117.4  448.70  5143.2  449.69
  5174.2  450.99  5225.4  451.85  5266.3  453.21  5308.3  452.97  5348.6  453.62
#Mann=7,-1,0
  4579.2    0.12       0  4789.3     0.1       0  4968.6    0.12       0
  5033.5     0.1       0  5039.1    0.07       0  5043.1     0.1       0
  5143.2    0.12       0
Bank Sta=5039.1,5043.1
Exp/Cntr=0.3,0.1

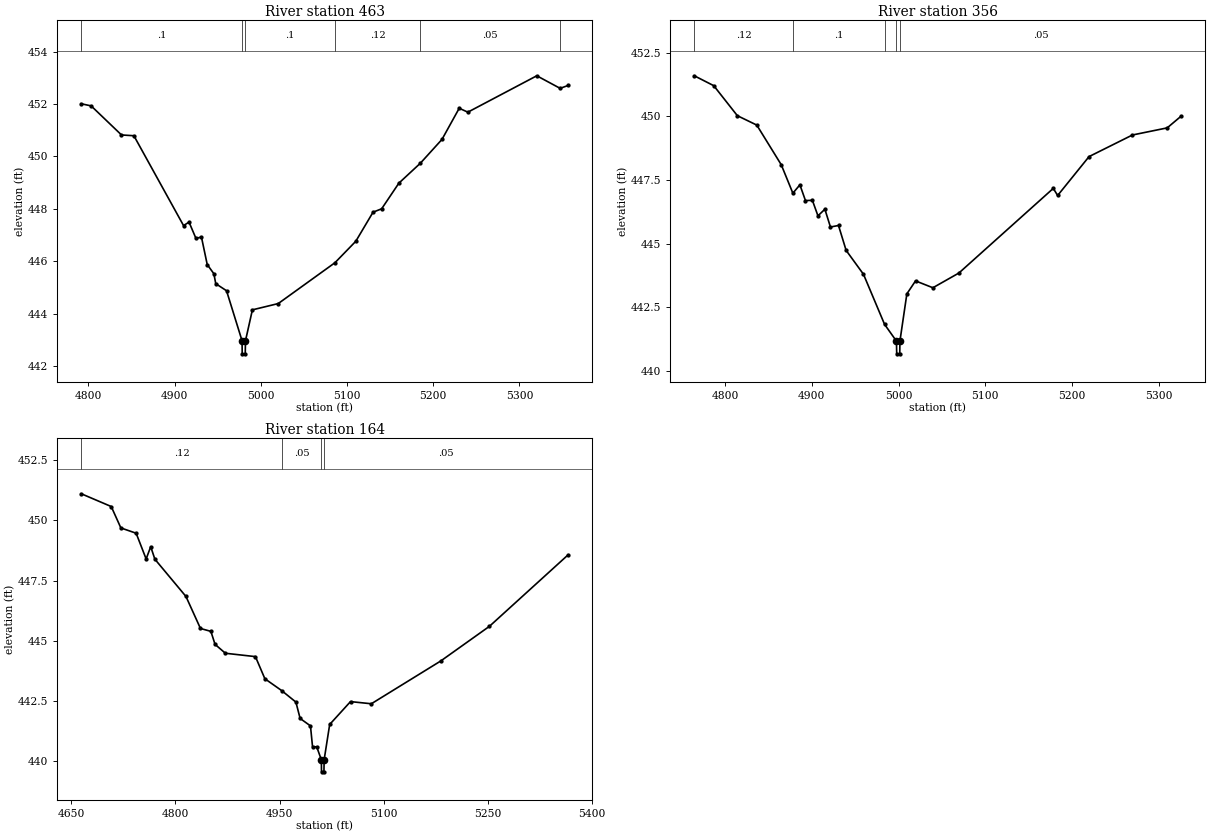
Type RM Length L Ch R = 1,463,107,107,107
BEGIN DESCRIPTION:
Lacy 078 2165
END DESCRIPTION:
XS GIS Cut Line= 3
      2743599.97      6883983.11      2743477.61      6883884.93
      2743069.75      6883892.43
#Sta/Elev= 30
  4791.7  452.01  4803.1  451.93  4838.3  450.82  4852.7  450.79  4910.3  447.36
  4916.7  447.49  4924.7  446.87  4931.1  446.92  4937.8  445.87  4945.5  445.52
  4947.7  445.14  4960.2  444.87  4978.2  442.96  4978.4  442.46  4981.9  442.46
  4982.2  442.96  4990.2  444.14  5020.2  444.38  5086.0  445.94  5110.2  446.76
  5130.2  447.87  5140.2  448.00  5160.2  448.98  5185.1  449.74  5210.2  450.65
  5230.2  451.84  5240.2  451.69  5320.2  453.08  5347.3  452.60  5356.5  452.71
#Mann=6,-1,0
  4791.7     0.1       0  4978.2    0.07       0  4982.2     0.1       0
  5086.0    0.12       0  5185.1    0.05       0  5347.3    0.12       0
Bank Sta=4978.2,4982.2
Exp/Cntr=0.3,0.1

Type RM Length L Ch R = 1,356,192,192,192
BEGIN DESCRIPTION:
Lacy 078 2164
END DESCRIPTION:
XS GIS Cut Line= 3
      2743598.09      6883909.49      2743494.81      6883779.27
      2743099.95      6883774.13
#Sta/Elev= 30
  4764.6  451.60  4787.0  451.21  4814.2  450.03  4836.6  449.66  4864.8  448.10
  4878.2  446.98  4886.3  447.31  4892.7  446.69  4900.7  446.70  4907.1  446.09
  4915.1  446.35  4921.5  445.65  4930.8  445.71  4939.6  444.73  4959.6  443.79
  4983.9  441.82  4997.6  441.16  4997.9  440.66  5001.4  440.66  5001.6  441.16
  5009.6  443.02  5019.6  443.53  5039.6  443.26  5069.6  443.84  5178.4  447.17
  5183.4  446.89  5219.6  448.42  5269.6  449.27  5309.7  449.55  5325.7  450.01
#Mann=5,-1,0
  4764.6    0.12       0  4878.2     0.1       0  4983.9    0.05       0
  4997.6    0.04       0  5001.6    0.05       0
Bank Sta=4997.6,5001.6
Exp/Cntr=0.3,0.1

Type RM Length L Ch R = 1,164,0,0,0
BEGIN DESCRIPTION:
Lacy 078 2163
END DESCRIPTION:
XS GIS Cut Line= 3
      2743607.76      6883888.06      2743418.25      6883611.09
      2743052.84      6883627.98
#Sta/Elev= 30
  4664.4  451.11  4707.5  450.58  4721.4  449.69  4743.4  449.47  4757.8  448.40
  4764.4  448.91  4770.4  448.39  4815.2  446.84  4836.1  445.51  4851.1  445.39
  4857.1  444.85  4872.0  444.48  4915.3  444.34  4928.9  443.42  4953.0  442.93
  4973.6  442.45  4979.7  441.77  4994.6  441.46  4997.6  440.59  5003.6  440.59
  5010.3  440.05  5010.5  439.55  5014.0  439.55  5014.3  440.05  5022.3  441.52
  5052.3  442.47  5082.3  442.38  5182.4  444.16  5252.5  445.60  5365.8  448.57
#Mann=4,-1,0
  4664.4    0.12       0  4953.0    0.05       0  5010.3    0.04       0
  5014.3    0.05       0
Bank Sta=5010.3,5014.3
Exp/Cntr=0.3,0.1

Chan Stop Cuts=-1