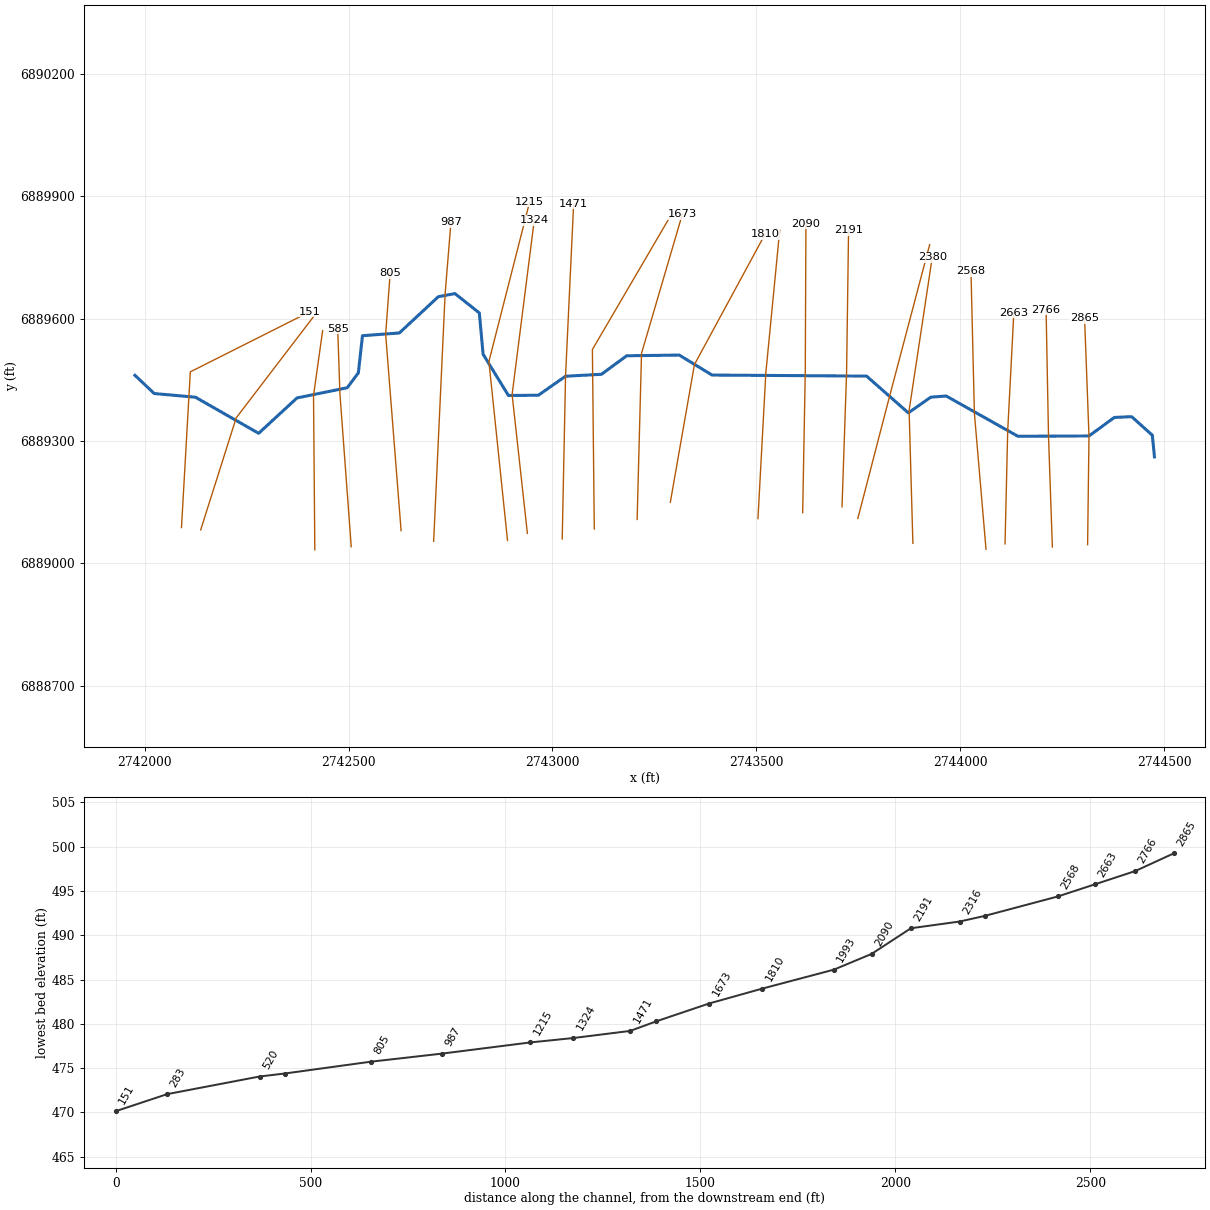
--- Lacy 079.prj (project) ---

Proj Title=Lacy 079 Base Level Engineering
Current Plan=p01
Default Exp/Contr=0.3,0.1
English Units
Geom File=g01
Flow File=f01
Plan File=p01
BEGIN DESCRIPTION:
Lacy 079
END DESCRIPTION:

--- Lacy 079.p01 (plan) ---

Plan Title=Multiple Run
Short Identifier=Multiple
Geom File=g01
Flow File=f01
Subcritical Flow
K Sum by GR= 0
Std Step Tol= 0.01
Critical Tol= 0.01
Num of Std Step Trials= 20
Max Error Tol= 0.3
Flow Tol Ratio= 0.001
Split Flow NTrial= 30
Split Flow Tol= 0.02
Split Flow Ratio= 0.02
Log Output Level= 0
Friction Slope Method= 1
Unsteady Friction Slope Method= 2
Unsteady Bridges Friction Slope Method= 1
Parabolic Critical Depth
Global Vel Dist=  1 , 1 , 1
Global Log Level= 0
CheckData=True
Encroach Param= -1, 0, 0, 0
BEGIN DESCRIPTION:
Multiple Run
END DESCRIPTION:

--- Lacy 079.f01 (steady flow) ---

Flow Title=Multiple
Number of Profiles=7
Profile Names=10-year,25-year,50-year,1pct_min,100-year,1pct_plu,500-year
River Rch & RM= Lacy 079,Reach-1,2865
     134     163     185     105     209     417     266
Boundary for River Rch & Prof#=Lacy 079,Reach-1,1
Up Type=0
Dn Type=3
Dn Slope=0.005
Boundary for River Rch & Prof#=Lacy 079,Reach-1,2
Up Type=0
Dn Type=3
Dn Slope=0.005
Boundary for River Rch & Prof#=Lacy 079,Reach-1,3
Up Type=0
Dn Type=3
Dn Slope=0.005
Boundary for River Rch & Prof#=Lacy 079,Reach-1,4
Up Type=0
Dn Type=3
Dn Slope=0.005
Boundary for River Rch & Prof#=Lacy 079,Reach-1,5
Up Type=0
Dn Type=3
Dn Slope=0.005
Boundary for River Rch & Prof#=Lacy 079,Reach-1,6
Up Type=0
Dn Type=3
Dn Slope=0.005
Boundary for River Rch & Prof#=Lacy 079,Reach-1,7
Up Type=0
Dn Type=3
Dn Slope=0.005

--- Lacy 079.g01 (geometry) ---

Geom Title=Existing Conditions

River Reach=Lacy 079,Reach-1
Reach XY= 30
      2744476.00      6889261.00      2744470.85      6889314.00
      2744420.11      6889359.55      2744377.76      6889357.67
      2744315.50      6889312.24      2744141.21      6889311.51
      2743965.30      6889410.20      2743927.63      6889407.39
      2743872.60      6889368.83      2743770.15      6889458.93
      2743391.22      6889461.52      2743310.78      6889510.49
      2743181.94      6889508.75      2743120.02      6889463.36
      2743031.97      6889458.64      2742965.34      6889412.05
      2742891.88      6889411.52      2742829.82      6889512.56
      2742820.58      6889613.75      2742760.78      6889661.17
      2742719.98      6889653.53      2742624.42      6889564.66
      2742534.01      6889557.97      2742523.89      6889466.78
      2742496.63      6889430.44      2742373.58      6889405.44
      2742279.40      6889318.78      2742124.43      6889407.20
      2742023.45      6889416.22      2741976.00      6889461.00

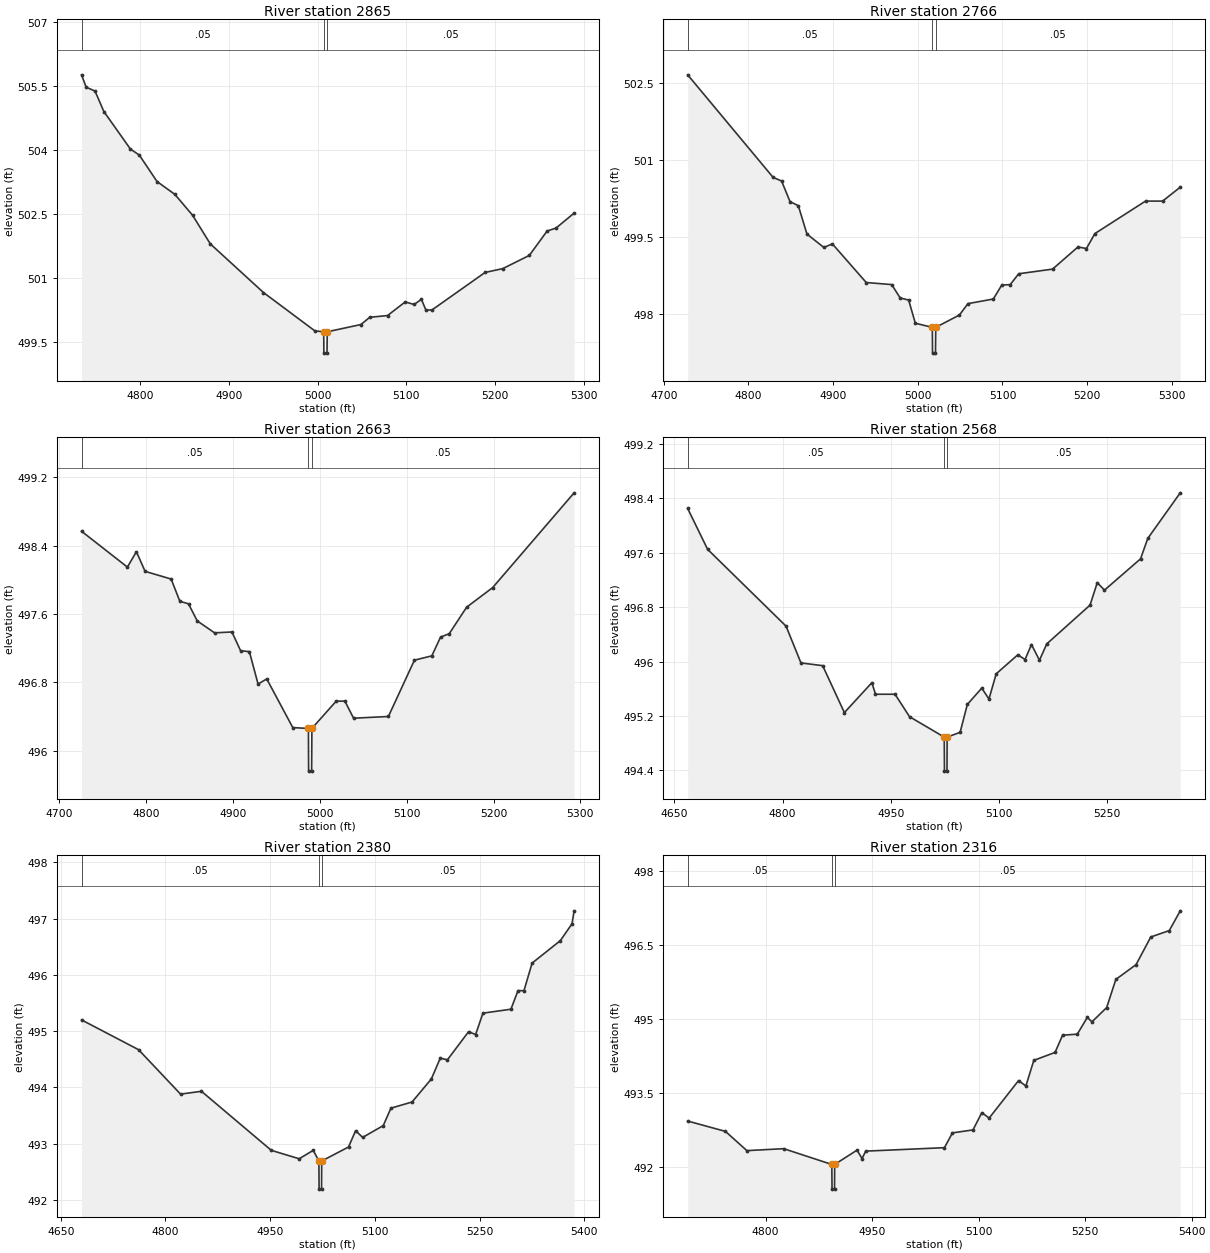
Type RM Length L Ch R = 1,2865,99,99,99
BEGIN DESCRIPTION:
Lacy 079 2123
END DESCRIPTION:
XS GIS Cut Line= 3
      2744312.13      6889045.76      2744315.50      6889312.24
      2744304.67      6889601.43
#Sta/Elev= 30
  4733.5  505.77  4738.7  505.48  4748.7  505.39  4758.7  504.91  4788.7  504.03
  4798.7  503.89  4818.7  503.27  4838.8  502.97  4858.8  502.48  4878.8  501.81
  4938.8  500.67  4996.9  499.77  5006.8  499.75  5007.0  499.25  5010.5  499.25
  5010.8  499.75  5048.8  499.92  5058.8  500.09  5078.8  500.13  5098.8  500.45
  5108.8  500.39  5117.1  500.51  5122.1  500.26  5128.9  500.26  5188.9  501.14
  5208.9  501.23  5238.9  501.54  5258.9  502.11  5269.0  502.18  5289.4  502.53
#Mann=3,-1,0
  4733.5    0.05       0  5006.8    0.04       0  5010.8    0.05       0
Bank Sta=5006.8,5010.8
Exp/Cntr=0.3,0.1

Type RM Length L Ch R = 1,2766,103,103,103
BEGIN DESCRIPTION:
Lacy 079 2113
END DESCRIPTION:
XS GIS Cut Line= 3
      2744225.71      6889040.18      2744216.26      6889311.88
      2744210.30      6889621.76
#Sta/Elev= 30
  4728.2  502.65  4829.1  500.66  4839.1  500.59  4849.1  500.19  4858.9  500.11
  4869.1  499.56  4889.1  499.30  4899.1  499.37  4939.1  498.62  4969.2  498.58
  4979.2  498.32  4989.2  498.28  4997.1  497.83  5017.2  497.75  5017.4  497.25
  5020.9  497.25  5021.2  497.75  5049.2  497.99  5059.2  498.21  5089.2  498.30
  5099.2  498.57  5109.2  498.58  5119.2  498.79  5159.2  498.88  5189.2  499.31
  5199.2  499.28  5209.2  499.57  5269.0  500.20  5289.2  500.20  5310.0  500.47
#Mann=3,-1,0
  4728.2    0.05       0  5017.2    0.04       0  5021.2    0.05       0
Bank Sta=5017.2,5021.2
Exp/Cntr=0.3,0.1

Type RM Length L Ch R = 1,2663,95,95,95
BEGIN DESCRIPTION:
Lacy 079 2112
END DESCRIPTION:
XS GIS Cut Line= 3
      2744109.64      6889047.80      2744116.20      6889325.07
      2744131.26      6889614.64
#Sta/Elev= 30
  4725.5  498.57  4778.3  498.15  4788.7  498.33  4798.7  498.10  4828.7  498.01
  4838.7  497.75  4848.7  497.72  4858.7  497.52  4878.7  497.38  4898.7  497.39
  4908.7  497.17  4918.8  497.16  4928.8  496.78  4938.8  496.84  4968.8  496.27
  4986.8  496.26  4987.0  495.76  4990.5  495.76  4990.8  496.26  5018.8  496.58
  5028.8  496.58  5038.8  496.38  5078.9  496.40  5108.9  497.06  5128.9  497.11
  5139.0  497.33  5149.0  497.37  5169.0  497.68  5199.0  497.91  5292.8  499.02
#Mann=3,-1,0
  4725.5    0.05       0  4986.8    0.04       0  4990.8    0.05       0
Bank Sta=4986.8,4990.8
Exp/Cntr=0.3,0.1

Type RM Length L Ch R = 1,2568,188,188,188
BEGIN DESCRIPTION:
Lacy 079 2111
END DESCRIPTION:
XS GIS Cut Line= 3
      2744063.02      6889034.61      2744034.49      6889368.14
      2744026.15      6889716.00
#Sta/Elev= 30
  4668.5  498.25  4696.1  497.65  4804.9  496.52  4825.5  495.98  4855.6  495.94
  4885.7  495.25  4923.8  495.69  4928.8  495.52  4955.9  495.52  4976.0  495.19
  5024.1  494.89  5024.4  494.39  5027.9  494.39  5028.1  494.89  5046.1  494.96
  5056.1  495.37  5076.1  495.61  5086.1  495.45  5096.1  495.82  5126.1  496.10
  5136.1  496.03  5145.0  496.25  5156.1  496.02  5166.2  496.26  5226.2  496.83
  5236.2  497.16  5246.2  497.05  5296.2  497.51  5306.2  497.81  5351.2  498.48
#Mann=3,-1,0
  4668.5    0.05       0  5024.1    0.04       0  5028.1    0.05       0
Bank Sta=5024.1,5028.1
Exp/Cntr=0.3,0.1

Type RM Length L Ch R = 1,2380,64,64,64
BEGIN DESCRIPTION:
Lacy 079 2110
END DESCRIPTION:
XS GIS Cut Line= 3
      2743883.70      6889049.30      2743874.44      6889374.69
      2743931.21      6889750.50
#Sta/Elev= 30
  4679.8  495.20  4761.5  494.67  4821.6  493.88  4851.6  493.93  4951.6  492.88
  4991.6  492.73  5011.7  492.88  5019.8  492.69  5020.1  492.19  5023.6  492.19
  5023.8  492.69  5062.3  492.94  5072.4  493.23  5082.5  493.11  5112.0  493.32
  5123.0  493.63  5153.3  493.74  5180.9  494.15  5193.7  494.52  5203.9  494.49
  5234.2  494.99  5244.3  494.94  5254.8  495.32  5294.9  495.39  5305.0  495.72
  5313.6  495.72  5325.2  496.21  5365.7  496.61  5382.4  496.91  5385.4  497.14
#Mann=3,-1,0
  4679.8    0.05       0  5019.8    0.04       0  5023.8    0.05       0
Bank Sta=5019.8,5023.8
Exp/Cntr=0.3,0.1

Type RM Length L Ch R = 1,2316,125,125,125
BEGIN DESCRIPTION:
Lacy 079 2109
END DESCRIPTION:
XS GIS Cut Line= 3
      2743748.75      6889110.18      2743826.66      6889409.92
      2743924.85      6889781.15
#Sta/Elev= 30
  4690.3  492.94  4743.5  492.73  4773.7  492.34  4825.5  492.38  4893.3  492.06
  4893.6  491.56  4897.1  491.56  4897.3  492.06  4928.8  492.35  4935.9  492.18
  4941.0  492.33  5051.9  492.40  5063.2  492.70  5092.1  492.76  5104.6  493.11
  5114.9  493.00  5156.3  493.76  5166.6  493.65  5177.8  494.17  5207.7  494.33
  5218.3  494.68  5239.0  494.70  5253.1  495.04  5259.7  494.95  5280.4  495.24
  5293.3  495.81  5321.8  496.11  5342.5  496.67  5368.6  496.80  5384.0  497.20
#Mann=3,-1,0
  4690.3    0.05       0  4893.3    0.04       0  4897.3    0.05       0
Bank Sta=4893.3,4897.3
Exp/Cntr=0.3,0.1

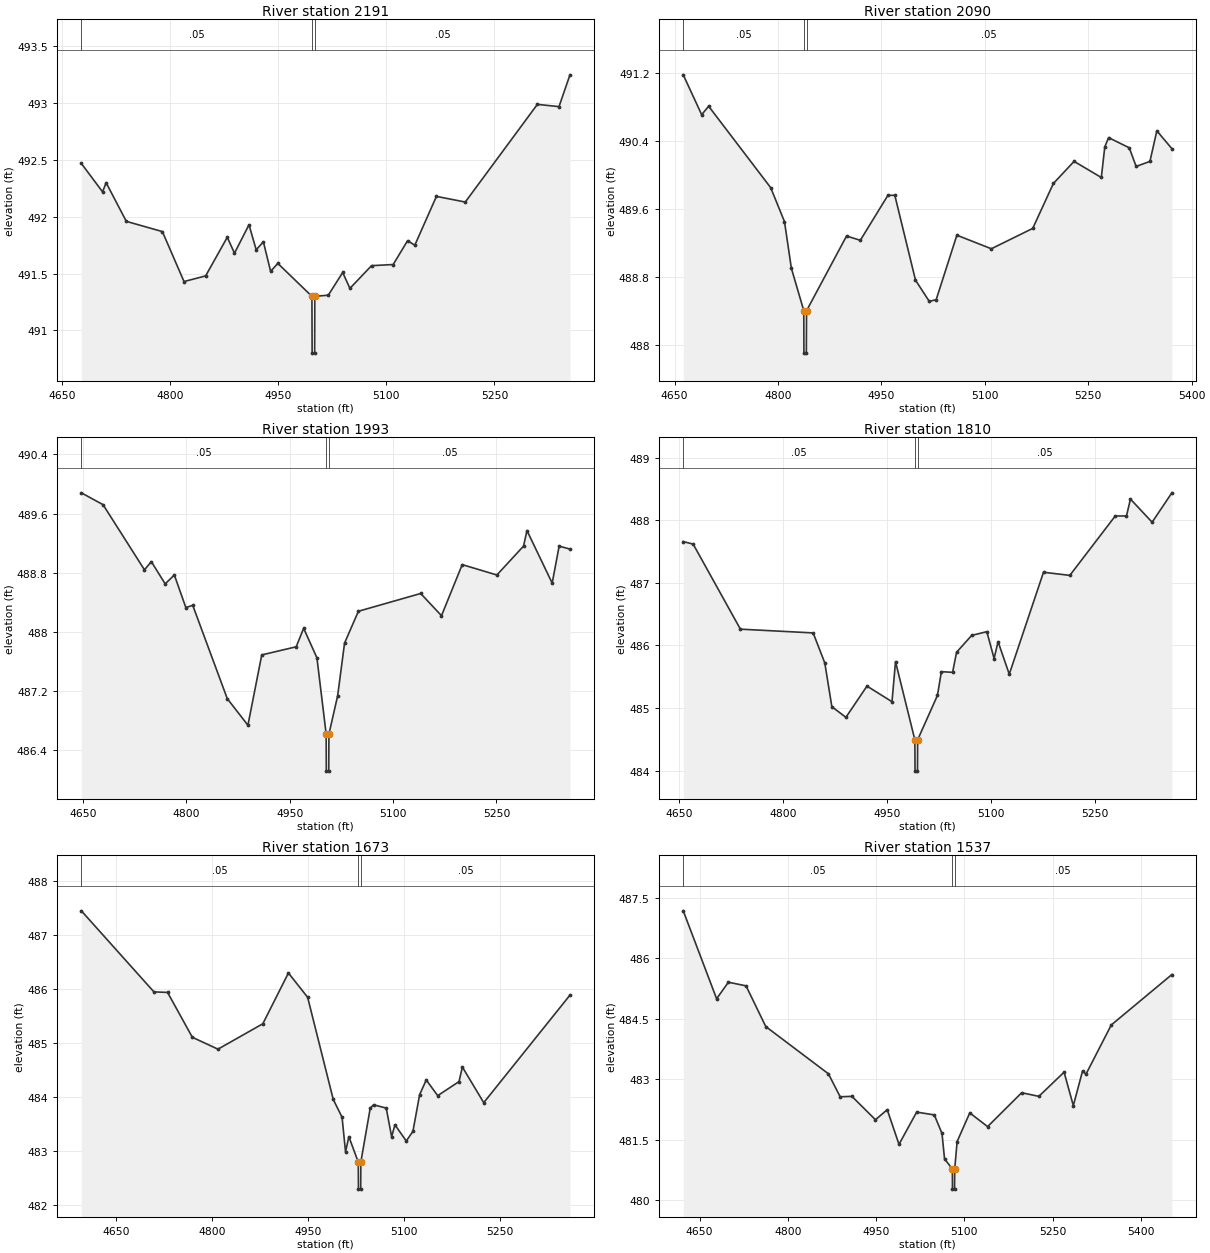
Type RM Length L Ch R = 1,2191,101,101,101
BEGIN DESCRIPTION:
Lacy 079 2108
END DESCRIPTION:
XS GIS Cut Line= 3
      2743709.93      6889138.68      2743721.12      6889468.00
      2743725.98      6889816.15
#Sta/Elev= 30
  4677.0  492.47  4706.4  492.22  4711.4  492.30  4739.4  491.96  4789.4  491.87
  4819.4  491.43  4849.4  491.48  4879.4  491.82  4889.4  491.68  4909.5  491.93
  4919.5  491.71  4929.5  491.78  4939.5  491.52  4949.5  491.59  4996.8  491.30
  4997.1  490.80  5000.6  490.80  5000.8  491.30  5019.5  491.31  5039.5  491.51
  5049.5  491.37  5079.5  491.57  5109.5  491.58  5129.5  491.79  5139.5  491.75
  5169.5  492.18  5209.5  492.13  5309.5  492.99  5339.5  492.97  5354.7  493.25
#Mann=3,-1,0
  4677.0    0.05       0  4996.8    0.04       0  5000.8    0.05       0
Bank Sta=4996.8,5000.8
Exp/Cntr=0.3,0.1

Type RM Length L Ch R = 1,2090,97,97,97
BEGIN DESCRIPTION:
Lacy 079 2106
END DESCRIPTION:
XS GIS Cut Line= 3
      2743613.46      6889124.26      2743619.83      6889470.77
      2743621.43      6889832.79
#Sta/Elev= 30
  4662.7  491.18  4689.4  490.71  4699.5  490.81  4789.5  489.85  4809.5  489.45
  4819.5  488.90  4837.5  488.40  4837.7  487.90  4841.2  487.90  4841.5  488.40
  4899.5  489.28  4919.5  489.23  4959.5  489.76  4969.5  489.76  4999.5  488.76
  5019.5  488.51  5029.5  488.53  5059.5  489.29  5109.5  489.13  5169.5  489.37
  5199.5  489.90  5229.5  490.16  5269.0  489.97  5274.0  490.33  5279.5  490.44
  5309.5  490.32  5319.5  490.10  5339.5  490.16  5349.5  490.52  5371.3  490.31
#Mann=3,-1,0
  4662.7    0.05       0  4837.5    0.04       0  4841.5    0.05       0
Bank Sta=4837.5,4841.5
Exp/Cntr=0.3,0.1

Type RM Length L Ch R = 1,1993,183,183,183
BEGIN DESCRIPTION:
Lacy 079 2107
END DESCRIPTION:
XS GIS Cut Line= 3
      2743503.80      6889109.52      2743523.12      6889466.72
      2743557.19      6889816.65
#Sta/Elev= 30
  4647.5  489.88  4679.0  489.72  4739.1  488.84  4749.1  488.95  4769.2  488.65
  4782.5  488.77  4799.2  488.33  4809.2  488.36  4859.3  487.10  4889.3  486.74
  4909.4  487.69  4959.4  487.80  4970.2  488.05  4989.5  487.65  5002.9  486.62
  5003.1  486.12  5006.6  486.12  5006.9  486.62  5019.6  487.14  5029.6  487.85
  5049.7  488.28  5140.1  488.52  5170.3  488.22  5200.4  488.91  5250.7  488.77
  5289.4  489.16  5294.4  489.37  5331.0  488.66  5341.1  489.16  5356.8  489.12
#Mann=3,-1,0
  4647.5    0.05       0  5002.9    0.04       0  5006.9    0.05       0
Bank Sta=5002.9,5006.9
Exp/Cntr=0.3,0.1

Type RM Length L Ch R = 1,1810,137,137,137
BEGIN DESCRIPTION:
Lacy 079 2105
END DESCRIPTION:
XS GIS Cut Line= 3
      2743288.91      6889149.74      2743348.06      6889487.33
      2743520.84      6889806.08
#Sta/Elev= 30
  4656.0  487.66  4670.3  487.62  4738.5  486.26  4843.5  486.20  4860.3  485.72
  4870.5  485.02  4890.8  484.85  4921.2  485.35  4957.3  485.10  4962.4  485.74
  4990.3  484.49  4990.6  483.99  4994.1  483.99  4994.3  484.49  5022.9  485.20
  5028.6  485.58  5044.8  485.57  5050.5  485.89  5072.3  486.16  5094.2  486.22
  5104.7  485.79  5110.4  486.06  5126.6  485.54  5176.0  487.17  5214.0  487.12
  5279.6  488.07  5295.8  488.07  5301.5  488.34  5332.8  487.97  5361.3  488.44
#Mann=3,-1,0
  4656.0    0.05       0  4990.3    0.04       0  4994.3    0.05       0
Bank Sta=4990.3,4994.3
Exp/Cntr=0.3,0.1

Type RM Length L Ch R = 1,1673,136,136,136
BEGIN DESCRIPTION:
Lacy 079 2104
END DESCRIPTION:
XS GIS Cut Line= 3
      2743207.53      6889107.64      2743218.32      6889514.84
      2743318.60      6889856.38
#Sta/Elev= 30
  4596.1  487.45  4709.5  485.95  4730.8  485.94  4769.5  485.11  4809.5  484.89
  4879.6  485.36  4919.6  486.30  4949.6  485.85  4989.6  483.96  5003.4  483.63
  5008.8  482.99  5014.0  483.27  5028.7  482.80  5029.0  482.30  5032.5  482.30
  5032.7  482.80  5047.4  483.80  5052.6  483.86  5072.4  483.80  5080.8  483.27
  5086.0  483.49  5103.7  483.19  5114.1  483.37  5124.6  484.05  5134.9  484.32
  5152.8  484.03  5186.1  484.29  5191.3  484.56  5224.7  483.90  5359.4  485.89
#Mann=3,-1,0
  4596.1    0.05       0  5028.7    0.04       0  5032.7    0.05       0
Bank Sta=5028.7,5032.7
Exp/Cntr=0.3,0.1

Type RM Length L Ch R = 1,1537,66,66,66
BEGIN DESCRIPTION:
Lacy 079 2103
END DESCRIPTION:
XS GIS Cut Line= 3
      2743102.47      6889084.32      2743097.81      6889524.08
      2743295.11      6889861.32
#Sta/Elev= 30
  4622.1  487.18  4678.8  485.00  4698.8  485.41  4728.8  485.32  4762.4  484.31
  4868.8  483.14  4888.8  482.57  4908.8  482.58  4948.8  482.00  4968.8  482.25
  4988.8  481.39  5018.8  482.19  5048.8  482.12  5061.9  481.66  5066.2  481.03
  5079.5  480.78  5079.7  480.28  5083.2  480.28  5083.5  480.78  5087.6  481.46
  5109.1  482.17  5139.4  481.83  5197.3  482.67  5226.5  482.58  5269.4  483.18
  5285.1  482.35  5300.8  483.21  5306.6  483.13  5349.6  484.35  5452.6  485.60
#Mann=3,-1,0
  4622.1    0.05       0  5079.5    0.04       0  5083.5    0.05       0
Bank Sta=5079.5,5083.5
Exp/Cntr=0.3,0.1

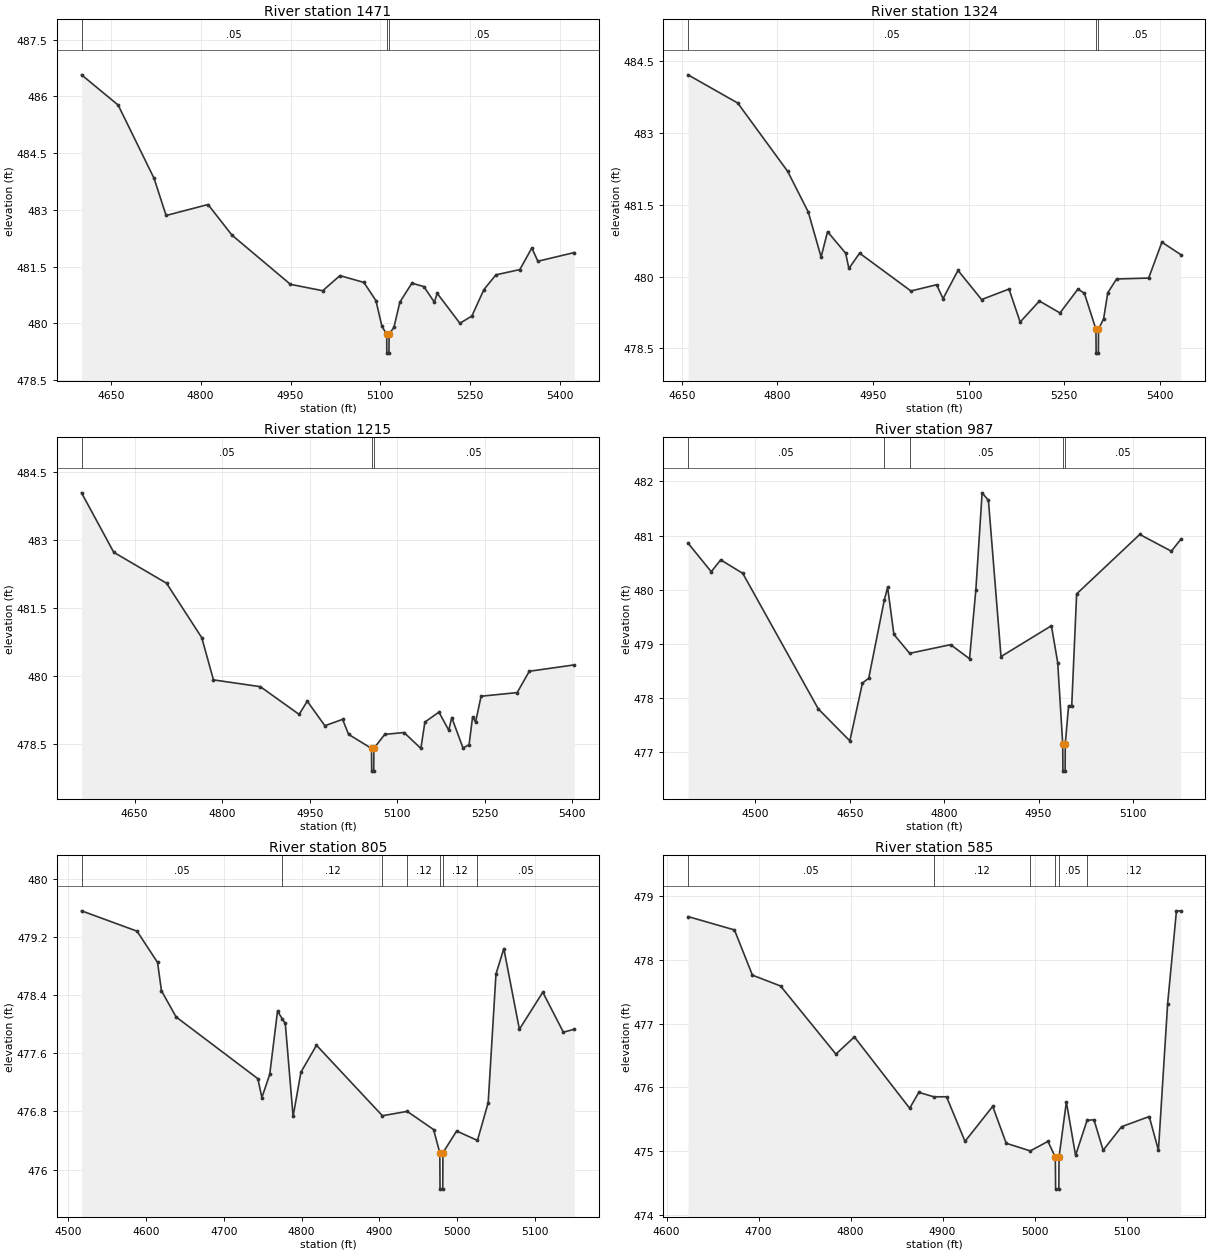
Type RM Length L Ch R = 1,1471,147,147,147
BEGIN DESCRIPTION:
Lacy 079 2122
END DESCRIPTION:
XS GIS Cut Line= 3
      2743023.84      6889059.92      2743031.97      6889458.64
      2743051.87      6889881.77
#Sta/Elev= 30
  4601.2  486.57  4662.3  485.77  4722.3  483.83  4742.3  482.85  4812.3  483.14
  4852.3  482.33  4949.8  481.03  5003.7  480.86  5032.4  481.26  5072.4  481.08
  5092.5  480.60  5102.5  479.92  5110.5  479.71  5110.7  479.21  5114.2  479.21
  5114.5  479.71  5122.5  479.89  5132.5  480.56  5152.5  481.06  5172.5  480.97
  5189.9  480.56  5194.9  480.79  5232.6  480.00  5252.6  480.19  5272.7  480.89
  5292.7  481.28  5332.7  481.42  5352.7  481.99  5362.8  481.64  5423.6  481.87
#Mann=3,-1,0
  4601.2    0.05       0  5110.5    0.04       0  5114.5    0.05       0
Bank Sta=5110.5,5114.5
Exp/Cntr=0.3,0.1

Type RM Length L Ch R = 1,1324,109,109,109
BEGIN DESCRIPTION:
Lacy 079 2121
END DESCRIPTION:
XS GIS Cut Line= 3
      2742938.44      6889073.43      2742900.96      6889413.73
      2742955.27      6889841.03
#Sta/Elev= 30
  4659.8  484.22  4737.8  483.63  4816.2  482.20  4848.5  481.35  4868.6  480.41
  4878.7  480.94  4907.1  480.49  4912.2  480.17  4929.0  480.49  5009.5  479.70
  5049.8  479.83  5059.9  479.54  5083.4  480.13  5120.4  479.52  5163.4  479.74
  5180.9  479.05  5211.1  479.49  5243.4  479.24  5271.6  479.74  5281.7  479.65
  5299.8  478.90  5300.1  478.40  5303.6  478.40  5303.8  478.90  5311.9  479.12
  5318.3  479.66  5332.1  479.95  5382.5  479.97  5403.3  480.72  5432.9  480.46
#Mann=3,-1,0
  4659.8    0.05       0  5299.8    0.04       0  5303.8    0.05       0
Bank Sta=5299.8,5303.8
Exp/Cntr=0.3,0.1

Type RM Length L Ch R = 1,1215,228,228,228
BEGIN DESCRIPTION:
Lacy 079 2120
END DESCRIPTION:
XS GIS Cut Line= 3
      2742889.69      6889056.14      2742844.06      6889494.77
      2742943.94      6889885.82
#Sta/Elev= 30
  4559.0  484.04  4614.2  482.73  4704.6  482.05  4765.0  480.85  4785.1  479.92
  4865.5  479.77  4931.9  479.16  4945.9  479.45  4976.1  478.91  5006.4  479.05
  5016.7  478.72  5056.0  478.41  5056.3  477.91  5059.8  477.91  5060.0  478.41
  5078.7  478.72  5111.8  478.76  5140.6  478.41  5147.5  478.99  5171.6  479.21
  5188.4  478.81  5193.5  479.09  5212.8  478.42  5223.2  478.49  5229.2  479.10
  5234.4  478.99  5243.8  479.56  5305.7  479.64  5326.4  480.11  5403.6  480.25
#Mann=3,-1,0
  4559.0    0.05       0  5056.0    0.04       0  5060.0    0.05       0
Bank Sta=5056,5060
Exp/Cntr=0.3,0.1

Type RM Length L Ch R = 1,987,182,182,182
BEGIN DESCRIPTION:
Lacy 079 2119
END DESCRIPTION:
XS GIS Cut Line= 3
      2742708.60      6889054.12      2742736.69      6889660.47
      2742751.00      6889835.98
#Sta/Elev= 30
  4393.0  480.86  4429.9  480.33  4444.9  480.55  4480.0  480.30  4600.1  477.79
  4650.2  477.20  4670.2  478.27  4680.2  478.36  4705.0  479.81  4710.2  480.04
  4720.2  479.17  4745.2  478.82  4810.3  478.98  4840.4  478.72  4850.4  479.99
  4860.4  481.79  4870.4  481.65  4890.4  478.76  4970.5  479.33  4980.5  478.65
  4988.5  477.14  4988.8  476.64  4992.3  476.64  4992.5  477.14  4997.8  477.85
  5002.8  477.85  5010.6  479.92  5110.9  481.02  5161.1  480.71  5176.1  480.93
#Mann=5,-1,0
  4393.0    0.05       0  4705.0    0.12       0  4745.2    0.05       0
  4988.5    0.04       0  4992.5    0.05       0
Bank Sta=4988.5,4992.5
Exp/Cntr=0.3,0.1

Type RM Length L Ch R = 1,805,220,220,220
BEGIN DESCRIPTION:
Lacy 079 2118
END DESCRIPTION:
XS GIS Cut Line= 3
      2742628.77      6889079.89      2742590.89      6889561.21
      2742601.93      6889711.40
#Sta/Elev= 30
  4517.2  479.56  4588.5  479.28  4614.9  478.85  4619.9  478.46  4638.7  478.10
  4743.8  477.25  4749.0  476.99  4759.1  477.31  4769.1  478.18  4775.4  478.07
  4779.1  478.01  4789.1  476.73  4799.2  477.34  4819.2  477.71  4903.9  476.74
  4935.8  476.80  4969.7  476.55  4977.7  476.23  4978.0  475.73  4981.5  475.73
  4981.7  476.23  4999.3  476.53  5026.1  476.40  5039.9  476.92  5049.9  478.69
  5060.0  479.04  5080.0  477.93  5110.1  478.44  5136.5  477.89  5150.6  477.93
#Mann=7,-1,0
  4517.2    0.05       0  4775.4    0.12       0  4903.9    0.05       0
  4935.8    0.12       0  4977.7    0.07       0  4981.7    0.12       0
  5026.1    0.05       0
Bank Sta=4977.7,4981.7
Exp/Cntr=0.3,0.1

Type RM Length L Ch R = 1,585,65,65,65
BEGIN DESCRIPTION:
Lacy 079 2117
END DESCRIPTION:
XS GIS Cut Line= 3
      2742506.49      6889040.64      2742478.71      6889416.41
      2742473.31      6889575.32
#Sta/Elev= 30
  4623.2  478.68  4673.7  478.47  4693.2  477.76  4723.8  477.59  4784.0  476.52
  4804.1  476.79  4864.2  475.67  4874.2  475.92  4890.4  475.85  4904.3  475.85
  4924.4  475.15  4954.5  475.70  4969.2  475.12  4995.4  475.00  5014.6  475.15
  5022.6  474.90  5022.9  474.40  5026.4  474.40  5026.6  474.90  5034.6  475.77
  5044.6  474.93  5057.1  475.48  5064.6  475.49  5074.6  475.01  5094.6  475.38
  5124.7  475.54  5134.7  475.01  5144.7  477.31  5154.3  478.77  5159.0  478.77
#Mann=6,-1,0
  4623.2    0.05       0  4890.4    0.12       0  4995.4    0.05       0
  5022.6    0.04       0  5026.6    0.05       0  5057.1    0.12       0
Bank Sta=5022.6,5026.6
Exp/Cntr=0.3,0.1

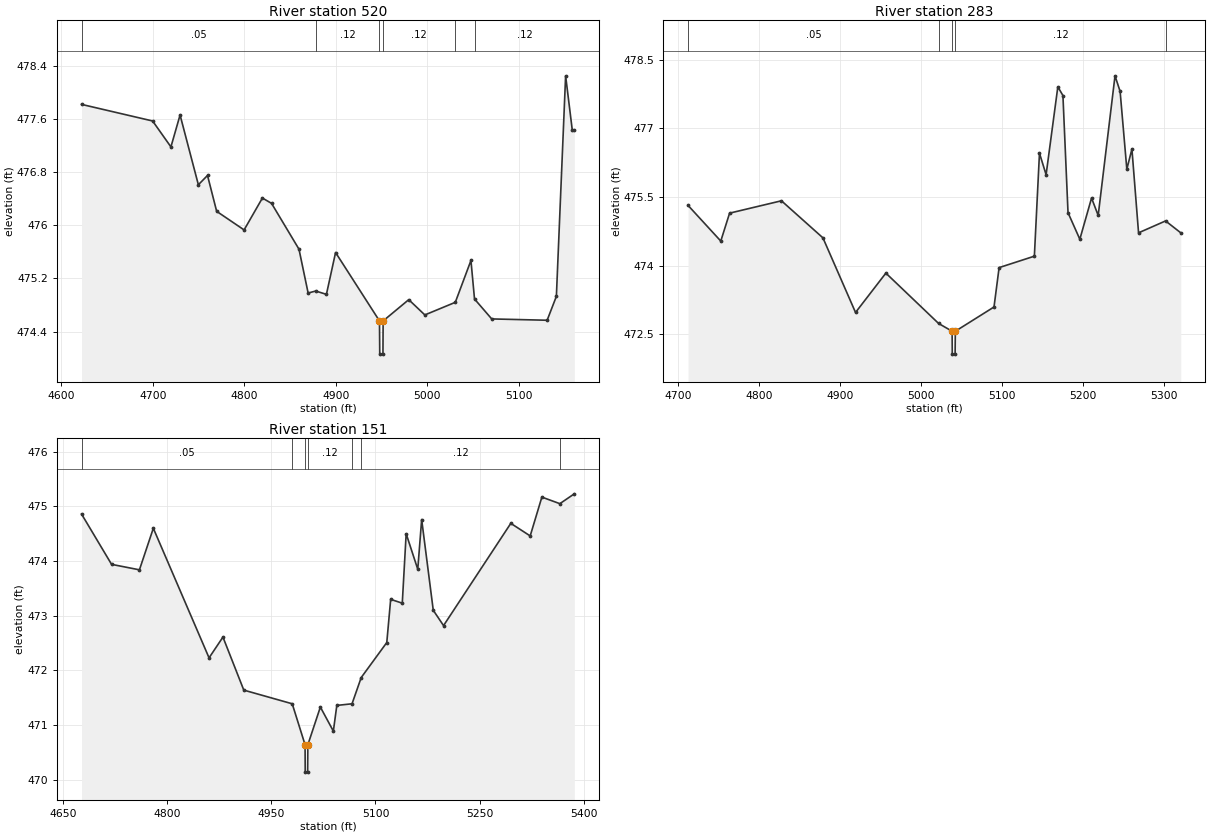
Type RM Length L Ch R = 1,520,237,237,237
BEGIN DESCRIPTION:
Lacy 079 2116
END DESCRIPTION:
XS GIS Cut Line= 3
      2742417.18      6889033.29      2742414.01      6889411.18
      2742436.37      6889570.41
#Sta/Elev= 30
  4622.1  477.82  4699.8  477.57  4719.8  477.18  4729.8  477.66  4749.8  476.61
  4759.8  476.75  4769.8  476.21  4799.8  475.93  4819.8  476.41  4829.8  476.33
  4859.8  475.64  4869.8  474.98  4878.1  475.01  4889.8  474.96  4899.8  475.59
  4947.8  474.56  4948.1  474.06  4951.6  474.06  4951.8  474.56  4979.8  474.88
  4997.4  474.65  5030.7  474.84  5047.8  475.47  5051.7  474.89  5070.5  474.59
  5131.1  474.57  5141.2  474.93  5151.3  478.25  5158.6  477.43  5160.8  477.43
#Mann=6,-1,0
  4622.1    0.05       0  4878.1    0.12       0  4947.8    0.07       0
  4951.8    0.12       0  5030.7    0.05       0  5051.7    0.12       0
Bank Sta=4947.8,4951.8
Exp/Cntr=0.3,0.1

Type RM Length L Ch R = 1,283,132,132,132
BEGIN DESCRIPTION:
Lacy 079 2115
END DESCRIPTION:
XS GIS Cut Line= 3
      2742137.31      6889082.04      2742224.37      6889356.57
      2742419.46      6889611.73
#Sta/Elev= 30
  4712.0  475.32  4752.5  474.54  4763.4  475.15  4827.5  475.42  4878.8  474.61
  4919.1  472.98  4956.6  473.84  5021.8  472.74  5038.5  472.57  5038.7  472.07
  5042.2  472.07  5042.5  472.57  5090.3  473.10  5096.6  473.96  5140.2  474.21
  5146.5  476.46  5154.7  475.99  5169.2  477.91  5175.5  477.72  5181.8  475.16
  5196.4  474.58  5210.9  475.48  5219.1  475.10  5239.9  478.15  5246.2  477.81
  5254.5  476.11  5260.8  476.55  5269.0  474.72  5302.4  474.98  5321.2  474.72
#Mann=5,-1,0
  4712.0    0.05       0  5021.8    0.12       0  5038.5    0.04       0
  5042.5    0.12       0  5302.4    0.05       0
Bank Sta=5038.5,5042.5
Exp/Cntr=0.3,0.1

Type RM Length L Ch R = 1,151,0,0,0
BEGIN DESCRIPTION:
Lacy 079 2114
END DESCRIPTION:
XS GIS Cut Line= 3
      2742090.23      6889087.83      2742111.91      6889469.33
      2742404.11      6889616.31
#Sta/Elev= 30
  4677.0  474.86  4720.2  473.94  4760.3  473.84  4780.3  474.60  4860.5  472.23
  4880.5  472.61  4910.5  471.64  4980.2  471.39  4998.7  470.64  4998.9  470.14
  5002.4  470.14  5002.7  470.64  5020.7  471.33  5039.4  470.89  5044.4  471.36
  5066.3  471.39  5079.5  471.87  5116.3  472.51  5121.9  473.30  5138.6  473.23
  5144.2  474.50  5160.9  473.85  5166.5  474.76  5183.2  473.10  5198.0  472.82
  5294.8  474.69  5322.7  474.46  5339.5  475.17  5365.4  475.05  5386.2  475.23
#Mann=7,-1,0
  4677.0    0.05       0  4980.2    0.12       0  4998.7    0.07       0
  5002.7    0.12       0  5066.3    0.05       0  5079.5    0.12       0
  5365.4    0.05       0
Bank Sta=4998.7,5002.7
Exp/Cntr=0.3,0.1

Chan Stop Cuts=-1