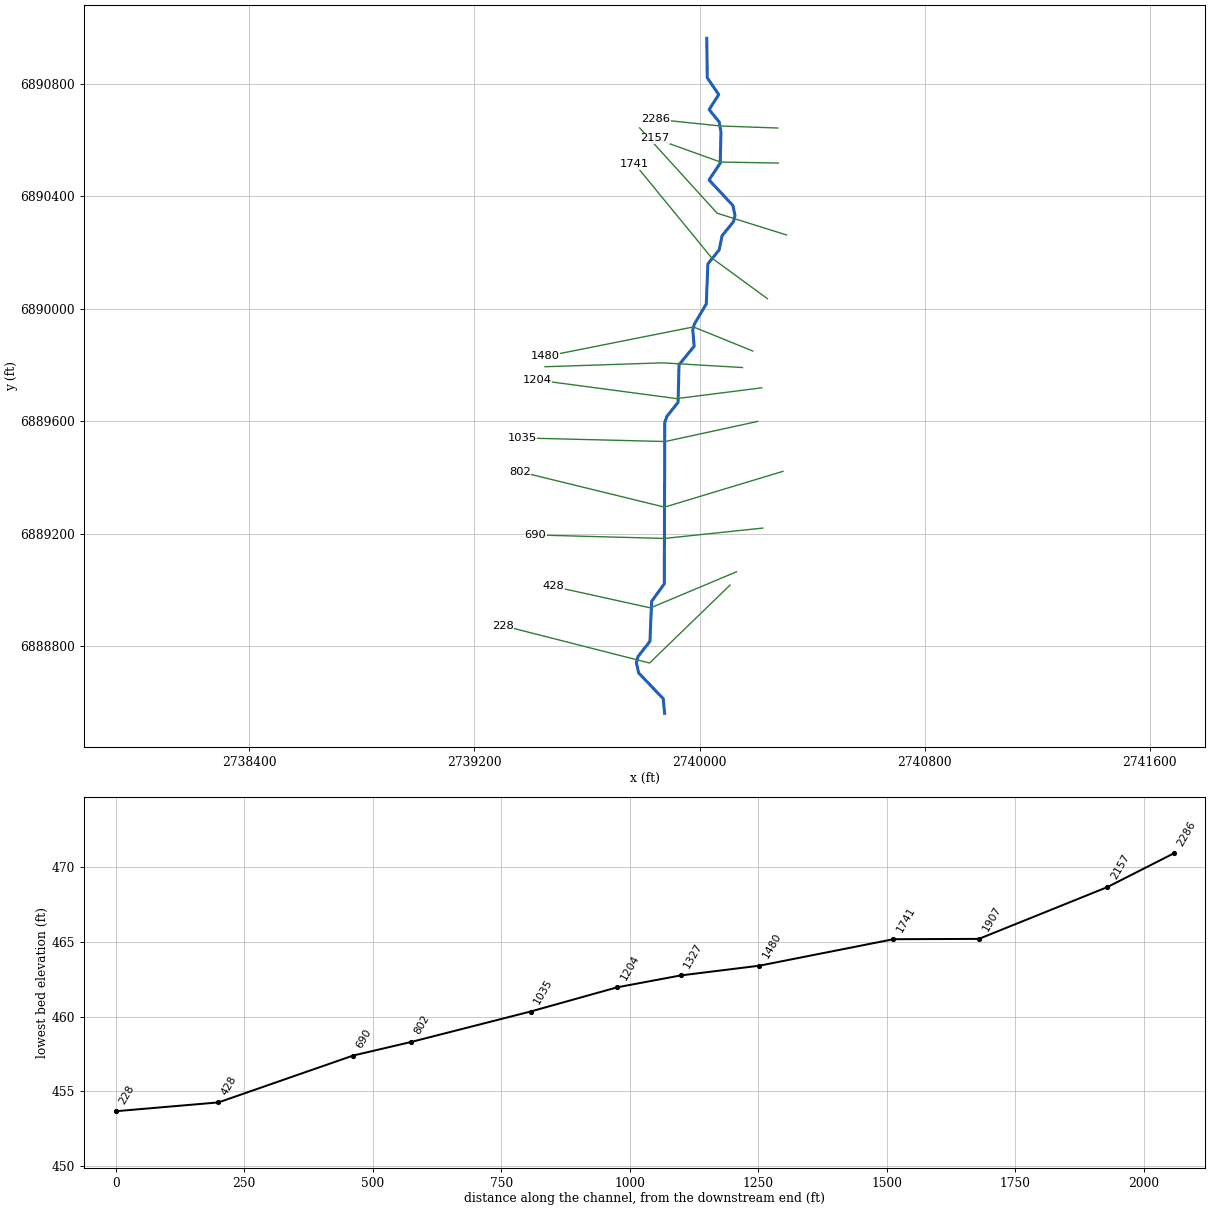
--- Lacy 081.prj (project) ---

Proj Title=Lacy 081 Base Level Engineering
Current Plan=p01
Default Exp/Contr=0.3,0.1
English Units
Geom File=g01
Flow File=f01
Plan File=p01
Y Axis Title=Elevation
X Axis Title(PF)=Main Channel Distance
X Axis Title(XS)=Station
BEGIN DESCRIPTION:
Lacy 081
END DESCRIPTION:
DSS Export Rating Curves= 0
DSS Export Rating Curve Sorted= 0
DSS Export Volume Flow Curves= 0
DXF OffsetX= 0
DXF OffsetY= 0
DXF ScaleX= 1
DXF ScaleY= 10

--- Lacy 081.p01 (plan) ---

Plan Title=Multiple Run
Short Identifier=Multiple
Geom File=g01
Flow File=f01
Subcritical Flow
K Sum by GR= 0
Std Step Tol= 0.01
Critical Tol= 0.01
Num of Std Step Trials= 20
Max Error Tol= 0.3
Flow Tol Ratio= 0.001
Split Flow NTrial= 30
Split Flow Tol= 0.02
Split Flow Ratio= 0.02
Log Output Level= 0
Friction Slope Method= 1
Unsteady Friction Slope Method= 2
Unsteady Bridges Friction Slope Method= 1
Parabolic Critical Depth
Global Vel Dist=  1 , 1 , 1
Global Log Level= 0
CheckData=True
Encroach Param= -1, 0, 0, 0
BEGIN DESCRIPTION:
Multiple Run
END DESCRIPTION:

--- Lacy 081.f01 (steady flow) ---

Flow Title=Multiple
Number of Profiles=7
Profile Names=10-year,25-year,50-year,1pct_min,100-year,1pct_plu,500-year
River Rch & RM= Lacy 081,Reach-1,2286
     146     179     203     115     229     457     293
River Rch & RM= Lacy 081,Reach-1,1327
     254     323     377     219     437     872     588
Boundary for River Rch & Prof#=Lacy 081,Reach-1,1
Up Type=0
Dn Type=3
Dn Slope=0.005
Boundary for River Rch & Prof#=Lacy 081,Reach-1,2
Up Type=0
Dn Type=3
Dn Slope=0.005
Boundary for River Rch & Prof#=Lacy 081,Reach-1,3
Up Type=0
Dn Type=3
Dn Slope=0.005
Boundary for River Rch & Prof#=Lacy 081,Reach-1,4
Up Type=0
Dn Type=3
Dn Slope=0.005
Boundary for River Rch & Prof#=Lacy 081,Reach-1,5
Up Type=0
Dn Type=3
Dn Slope=0.005
Boundary for River Rch & Prof#=Lacy 081,Reach-1,6
Up Type=0
Dn Type=3
Dn Slope=0.005
Boundary for River Rch & Prof#=Lacy 081,Reach-1,7
Up Type=0
Dn Type=3
Dn Slope=0.005

--- Lacy 081.g01 (geometry) ---

Geom Title=Existing Conditions
Program Version=4.10

River Reach=Lacy 081        ,Reach-1
Reach XY= 30
        2740026.        6890961.      2740027.33      6890821.41
      2740068.21       6890760.9      2740034.28      6890707.78
        2740070.      6890663.45      2740076.41      6890626.19
      2740073.54      6890516.86      2740033.81      6890457.59
      2740118.48      6890367.06      2740126.37       6890331.2
      2740120.69      6890308.81      2740080.22      6890259.28
      2740069.89      6890208.82      2740029.75      6890159.44
      2740024.09      6890016.79      2739981.45      6889944.58
      2739976.06      6889924.36      2739980.97      6889866.29
      2739927.21       6889800.5      2739923.73      6889666.94
      2739884.14      6889617.06      2739876.52      6889595.78
      2739874.78       6889021.5      2739829.79      6888959.43
       2739823.7      6888816.93      2739781.35      6888763.17
      2739775.64      6888740.79      2739783.48      6888704.94
      2739870.67      6888613.51        2739876.        6888561.

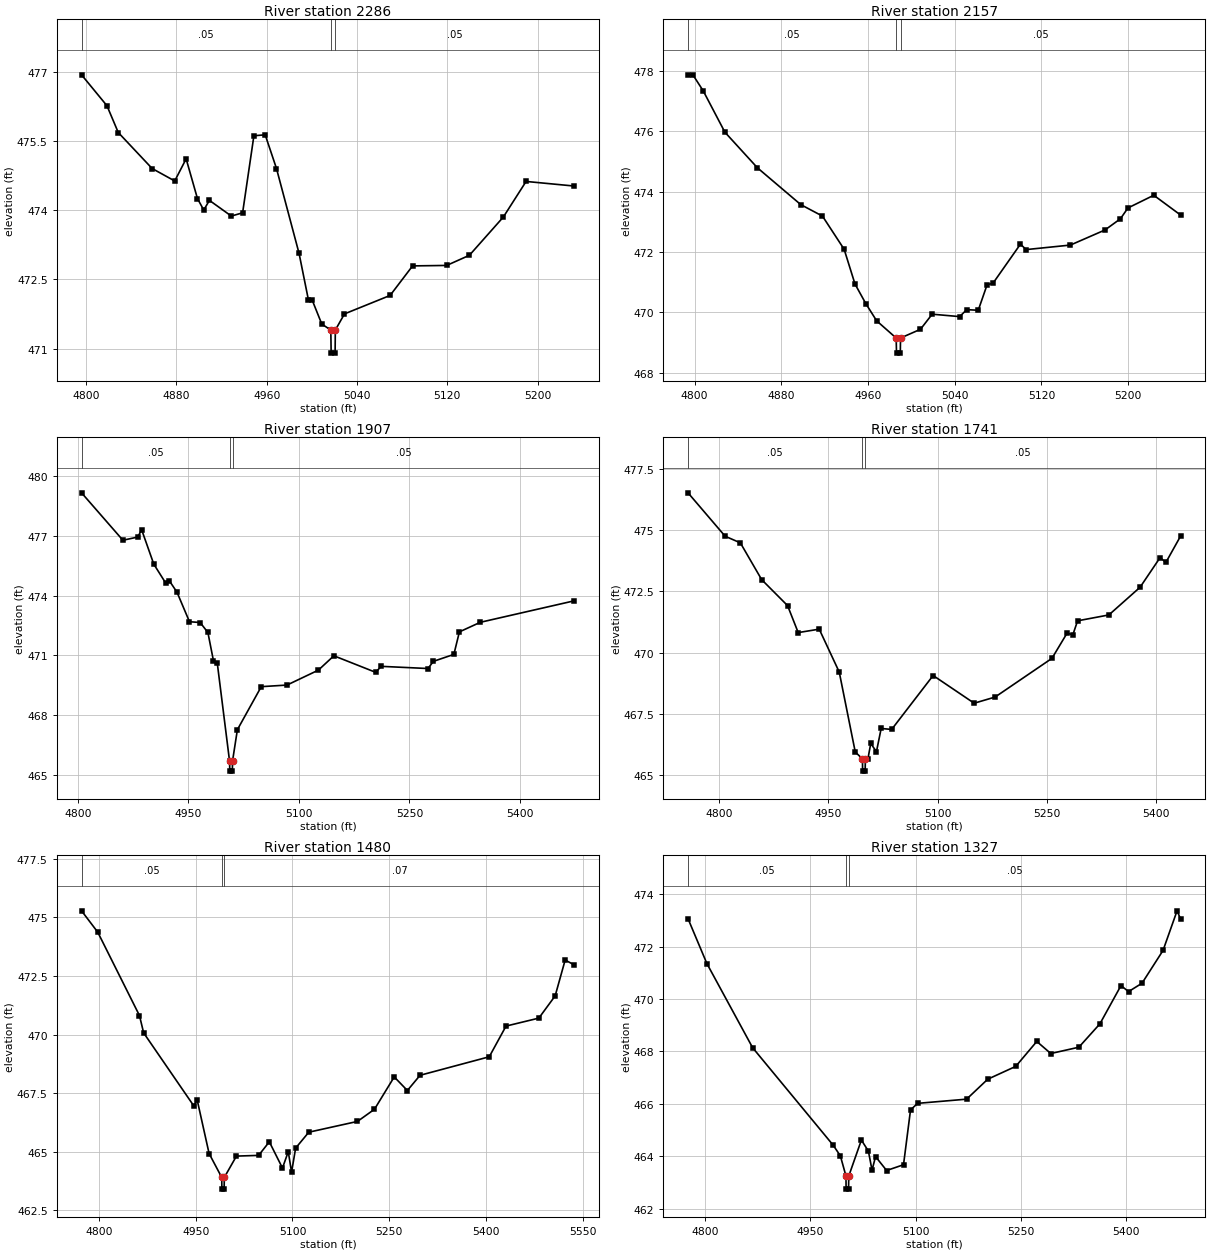
Type RM Length L Ch R = 1 ,2286    ,129,129,129
BEGIN DESCRIPTION:
Lacy 081 2077
END DESCRIPTION:
XS GIS Cut Line= 3
      2740278.49      6890642.13      2740074.42      6890649.39
      2739843.56      6890673.33
#Sta/Elev= 30
  4796.1  476.93  4818.6  476.26  4828.6  475.68  4858.6   474.9  4878.6  474.63
  4888.7  475.11  4898.7  474.25  4904.3     474  4909.3  474.21  4928.7  473.87
  4938.7  473.94  4948.7  475.61  4958.7  475.63  4968.7   474.9  4988.7  473.06
    4997  472.05  5000.3  472.05  5008.8  471.53  5016.8   471.4  5017.1   470.9
  5020.6   470.9  5020.8   471.4  5028.9  471.75  5069.3  472.15  5089.2  472.79
  5119.4   472.8  5139.5  473.02  5169.6  473.85  5189.7  474.62  5232.4  474.52
#Mann= 3 ,-1 , 0
  4796.1     .05       0  5016.8     .04       0  5020.8     .05       0
Bank Sta=5016.8,5020.8
XS Rating Curve= 0 ,0
Exp/Cntr=0.3,0.1

Type RM Length L Ch R = 1 ,2157    ,250,250,250
BEGIN DESCRIPTION:
Lacy 081 2076
END DESCRIPTION:
XS GIS Cut Line= 3
        2740280.      6890517.48      2740074.54      6890521.24
      2739840.18      6890605.37
#Sta/Elev= 30
    4794  477.87  4798.5  477.87    4808  477.34    4828  475.97    4858  474.79
    4898  473.57    4918  473.19    4938  472.09    4948  470.94    4958  470.29
    4968  469.72    4986  469.15  4986.3  468.65  4989.8  468.65    4990  469.15
  5008.4  469.44  5019.2  469.94  5044.5  469.86  5051.1  470.09  5061.7  470.07
  5069.9  470.92  5075.2  470.96  5100.6  472.26  5105.9  472.08  5146.7  472.23
  5178.6  472.73  5192.8   473.1  5199.8  473.46  5223.6  473.88  5248.5  473.22
#Mann= 3 ,-1 , 0
    4794     .05       0    4986     .04       0    4990     .05       0
Bank Sta=4986,4990
XS Rating Curve= 0 ,0
Exp/Cntr=0.3,0.1

Type RM Length L Ch R = 1 ,1907    ,166,166,166
BEGIN DESCRIPTION:
Lacy 081 2075
END DESCRIPTION:
XS GIS Cut Line= 3
      2740309.55      6890261.88      2740062.75      6890339.12
      2739787.12      6890642.51
#Sta/Elev= 30
  4805.1  479.16  4861.2  476.78  4881.4  476.94  4886.6  477.31  4903.1  475.58
  4919.1  474.64  4924.3  474.74  4934.6  474.17  4951.5  472.69    4966  472.65
  4976.5  472.15    4984  470.74  4989.2  470.62  5005.9  465.69  5006.2  465.19
  5009.7  465.19  5009.9  465.69  5016.5  467.27  5048.9  469.43  5083.8  469.51
  5126.4  470.26  5147.4  470.98  5204.1  470.15  5211.6  470.45  5275.1  470.34
  5282.4   470.7  5310.2  471.05  5317.7  472.18    5346  472.66  5473.6  473.74
#Mann= 3 ,-1 , 0
  4805.1     .05       0  5005.9     .04       0  5009.9     .05       0
Bank Sta=5005.9,5009.9
XS Rating Curve= 0 ,0
Exp/Cntr=0.3,0.1

Type RM Length L Ch R = 1 ,1741    ,261,261,261
BEGIN DESCRIPTION:
Lacy 081 3461
END DESCRIPTION:
XS GIS Cut Line= 3
       2740241.5      6890035.35      2740043.67      6890180.03
      2739769.92      6890514.24
#Sta/Elev= 30
  4757.1  476.52  4808.1  474.75    4829  474.48  4858.3  472.98  4893.9  471.92
  4908.5  470.82  4937.4  470.96  4964.9  469.21  4986.9  465.95  4996.8  465.67
    4997  465.17  5000.5  465.17  5000.8  465.67  5004.3  465.67  5008.2   466.3
    5016  465.96  5022.5  466.91  5036.9  466.87  5093.9  469.07  5150.3  467.94
    5179  468.19  5257.2  469.77    5278   470.8  5285.9  470.73  5292.4   471.3
  5335.4  471.54  5378.3  472.67  5405.8  473.88  5413.7  473.68  5434.2  474.77
#Mann= 3 ,-1 , 0
  4757.1     .05       0  4996.8     .04       0  5000.8     .05       0
Bank Sta=4996.8,5000.8
XS Rating Curve= 0 ,0
Exp/Cntr=0.3,0.1

Type RM Length L Ch R = 1 ,1480    ,153,153,153
BEGIN DESCRIPTION:
Lacy 081 3452
END DESCRIPTION:
XS GIS Cut Line= 3
      2740189.22      6889849.29      2739978.61      6889934.95
       2739452.1      6889830.17
#Sta/Elev= 30
  4772.9  475.28    4798  474.37  4862.7  470.81  4869.2  470.07  4946.8  466.96
  4952.2  467.21  4970.7  464.92  4990.3   463.9  4990.5   463.4    4994   463.4
  4994.3   463.9  5013.1  464.81  5047.5  464.84  5064.1  465.42  5084.5   464.3
  5093.5     465  5098.6  464.12  5104.9  465.15  5125.3  465.83  5200.8  466.29
  5227.2  466.81  5257.8  468.19  5278.2  467.61  5297.9  468.26  5405.2  469.05
  5431.2  470.36  5482.1   470.7  5507.4  471.65  5522.9  473.18  5537.1  472.97
#Mann= 3 ,-1 , 0
  4772.9     .05       0  4990.3     .03       0  4994.3     .07       0
Bank Sta=4990.3,4994.3
XS Rating Curve= 0 ,0
Exp/Cntr=0.3,0.1

Type RM Length L Ch R = 1 ,1327    ,123,123,123
BEGIN DESCRIPTION:
Lacy 081 3450
END DESCRIPTION:
XS GIS Cut Line= 3
      2740152.89      6889790.58       2739869.1      6889807.27
      2739450.71       6889793.4
#Sta/Elev= 30
  4775.3  473.06  4802.2  471.35  4867.5  468.14  4982.5  464.42  4992.6  464.02
  5000.6  463.25  5000.8  462.75  5004.3  462.75  5004.6  463.25  5022.6  464.62
  5032.6   464.2  5037.8  463.47  5042.8  463.99  5058.6  463.46  5082.7  463.68
  5092.7  465.77  5102.8  466.02  5172.7  466.18  5202.8  466.94  5242.8  467.43
  5272.8  468.38  5292.8  467.92  5332.8  468.16  5362.8  469.05  5392.9  470.51
  5403.7  470.28  5422.9   470.6  5452.9  471.85  5472.9  473.36  5478.2  473.03
#Mann= 3 ,-1 , 0
  4775.3     .05       0  5000.6     .04       0  5004.6     .05       0
Bank Sta=5000.6,5004.6
XS Rating Curve= 0 ,0
Exp/Cntr=0.3,0.1

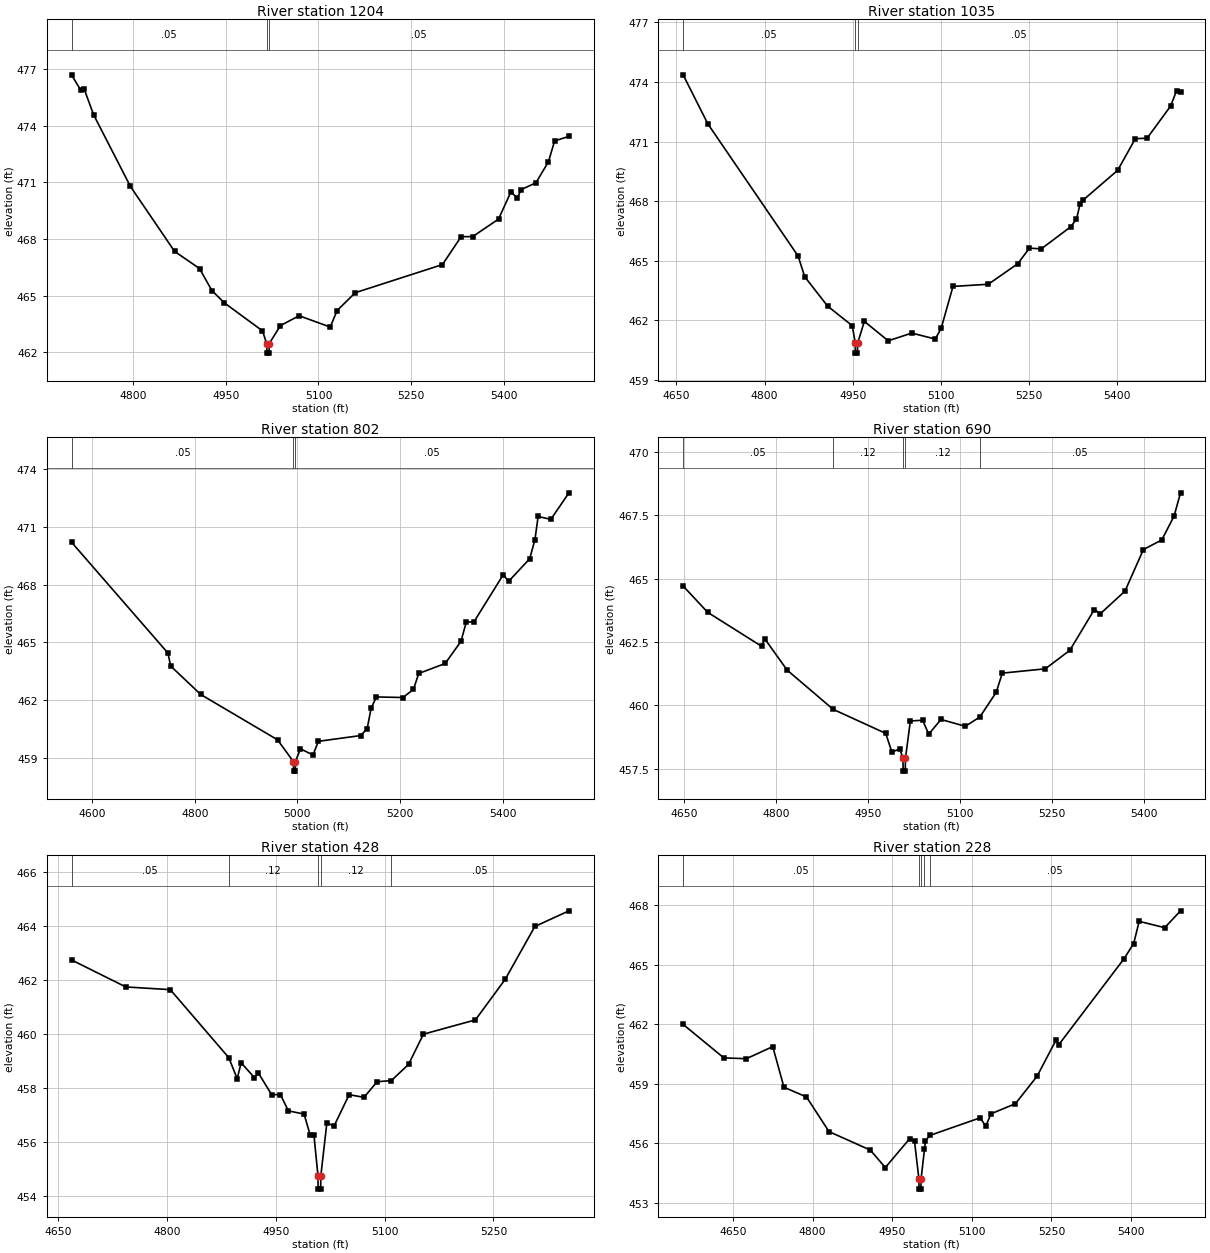
Type RM Length L Ch R = 1 ,1204    ,169,169,169
BEGIN DESCRIPTION:
Lacy 081 2071
END DESCRIPTION:
XS GIS Cut Line= 3
      2740221.51       6889718.5      2739918.81      6889680.11
        2739423.       6889746.1
#Sta/Elev= 30
  4700.2   476.7  4715.4  475.87  4720.5  475.96    4736  474.58  4795.5  470.79
    4867  467.35  4907.4  466.44  4927.5  465.27  4947.7  464.62  5009.3  463.14
  5016.2  462.46  5016.5  461.96    5020  461.96  5020.2  462.46  5038.4  463.42
  5068.7  463.94  5119.1  463.34    5130  464.21  5159.5  465.16  5300.7  466.65
    5331  468.13  5349.6  468.13  5391.5  469.06  5411.7  470.51  5421.8  470.16
  5427.9  470.62    5452  470.98  5472.2  472.09  5482.3   473.2  5505.5  473.44
#Mann= 3 ,-1 , 0
  4700.2     .05       0  5016.2     .04       0  5020.2     .05       0
Bank Sta=5016.2,5020.2
XS Rating Curve= 0 ,0
Exp/Cntr=0.3,0.1

Type RM Length L Ch R = 1 ,1035    ,233,233,233
BEGIN DESCRIPTION:
Lacy 081 2073
END DESCRIPTION:
XS GIS Cut Line= 3
      2740207.04      6889599.02      2739878.35      6889527.56
      2739369.17      6889540.23
#Sta/Elev= 30
  4661.6  474.36  4703.6  471.89  4857.1  465.23  4868.3  464.19  4907.2  462.71
  4949.2  461.72  4954.3  460.84  4954.5  460.34    4958  460.34  4958.3  460.84
  4969.7  461.94  5010.3  460.96  5050.3  461.35  5090.3  461.05  5100.3  461.59
  5120.4   463.7  5180.4  463.81  5230.4  464.84  5250.4  465.63  5270.4  465.59
  5320.4   466.7  5330.4  467.09  5336.3  467.83  5341.3  468.04  5400.4  469.55
  5430.4  471.14  5450.5  471.17  5490.5  472.79  5500.5  473.56  5507.3  473.47
#Mann= 3 ,-1 , 0
  4661.6     .05       0  4954.3     .04       0  4958.3     .05       0
Bank Sta=4954.3,4958.3
XS Rating Curve= 0 ,0
Exp/Cntr=0.3,0.1

Type RM Length L Ch R = 1 ,802     ,112,112,112
BEGIN DESCRIPTION:
Lacy 081 2081
END DESCRIPTION:
XS GIS Cut Line= 3
       2740296.8      6889421.56      2739875.61      6889294.28
      2739361.68      6889420.07
#Sta/Elev= 30
    4560  470.21  4747.9  464.44  4753.1  463.77  4811.6  462.29  4961.3  459.93
  4992.2   458.8  4992.5   458.3    4996   458.3  4996.2   458.8    5006  459.46
  5030.5  459.14  5040.8  459.85  5123.1  460.15    5136  460.51  5143.7  461.58
    5154  462.16  5205.5  462.13  5226.1  462.55  5236.4  463.38  5287.9   463.9
  5318.7  465.05    5329  466.05  5344.1  466.07  5401.1  468.52  5411.4  468.17
  5452.6  469.35  5462.9  470.35    5469  471.55  5493.8   471.4  5529.1  472.78
#Mann= 3 ,-1 , 0
    4560     .05       0  4992.2     .04       0  4996.2     .05       0
Bank Sta=4992.2,4996.2
XS Rating Curve= 0 ,0
Exp/Cntr=0.3,0.1

Type RM Length L Ch R = 1 ,690     ,262,262,262
BEGIN DESCRIPTION:
Lacy 081 2080
END DESCRIPTION:
XS GIS Cut Line= 3
      2740224.63      6889219.82      2739875.27      6889182.93
      2739415.44      6889195.34
#Sta/Elev= 30
  4648.7  464.71  4688.8  463.67  4776.7  462.33  4781.7  462.63  4818.3  461.39
  4893.4  459.84  4979.2  458.89  4989.2  458.15  5002.1  458.28  5007.3   457.9
  5007.5   457.4    5011   457.4  5011.3   457.9  5019.3  459.38  5039.3  459.41
  5049.3  458.86  5069.3  459.44    5109  459.17  5132.7  459.54  5159.3  460.51
  5169.3  461.27  5239.4  461.44  5279.4  462.17  5319.4  463.78  5329.4  463.62
  5369.4  464.51  5399.4  466.15  5429.4  466.53  5449.4  467.47    5460  468.39
#Mann= 5 ,-1 , 0
  4648.7     .05       0  4893.4     .12       0  5007.3     .07       0
  5011.3     .12       0  5132.7     .05       0
Bank Sta=5007.3,5011.3
XS Rating Curve= 0 ,0
Exp/Cntr=0.3,0.1

Type RM Length L Ch R = 1 ,428     ,200,200,200
BEGIN DESCRIPTION:
Lacy 081 2079
END DESCRIPTION:
XS GIS Cut Line= 3
      2740131.51      6889064.33      2739825.82      6888936.07
      2739480.11      6889012.24
#Sta/Elev= 30
  4668.5  462.76  4743.3  461.76  4804.6  461.66  4885.2  459.14  4896.8  458.36
  4902.2  458.95  4920.6   458.4    4926  458.57  4944.3  457.77  4956.4  457.77
  4967.3  457.17    4989  457.05  4997.2  456.29  5002.5  456.29  5008.1  454.77
  5008.3  454.27  5011.8  454.27  5012.1  454.77  5020.3  456.71  5030.5  456.62
  5051.1  457.77  5071.5  457.67  5089.7  458.25  5109.2  458.29  5132.9  458.89
  5153.4  460.01  5225.1  460.54  5266.1  462.04    5307     464    5354  464.58
#Mann= 5 ,-1 , 0
  4668.5     .05       0  4885.2     .12       0  5008.1     .07       0
  5012.1     .12       0  5109.2     .05       0
Bank Sta=5008.1,5012.1
XS Rating Curve= 0 ,0
Exp/Cntr=0.3,0.1

Type RM Length L Ch R = 1 ,228     ,0,0,0
BEGIN DESCRIPTION:
Lacy 081 2078
END DESCRIPTION:
XS GIS Cut Line= 3
      2740108.47      6889017.06       2739822.4      6888740.05
      2739300.46      6888872.94
#Sta/Elev= 30
  4556.3  461.99    4633   460.3  4675.4  460.26  4725.1  460.87  4746.2  458.82
  4788.6  458.33  4831.1  456.58  4908.8  455.65  4937.1  454.77  4982.8  456.22
  4992.1  456.09  5000.4  454.18  5000.6  453.68  5004.1  453.68  5004.4  454.18
  5010.8  455.68  5012.7  456.12  5021.1  456.39  5115.9  457.28  5126.2  456.85
  5136.1  457.48  5182.1  457.99    5223  459.38  5258.8  461.21  5263.9  460.97
  5386.6   465.3  5404.8  466.07  5415.2  467.19  5463.3  466.87  5493.1  467.72
#Mann= 5 ,-1 , 0
  4556.3     .05       0  5000.4     .04       0  5004.4     .05       0
  5010.8     .12       0  5021.1     .05       0
Bank Sta=5000.4,5004.4
XS Rating Curve= 0 ,0
Exp/Cntr=0.3,0.1

Chan Stop Cuts=-1
Use User Specified Reach Order=0
Composite Channel Slope=5