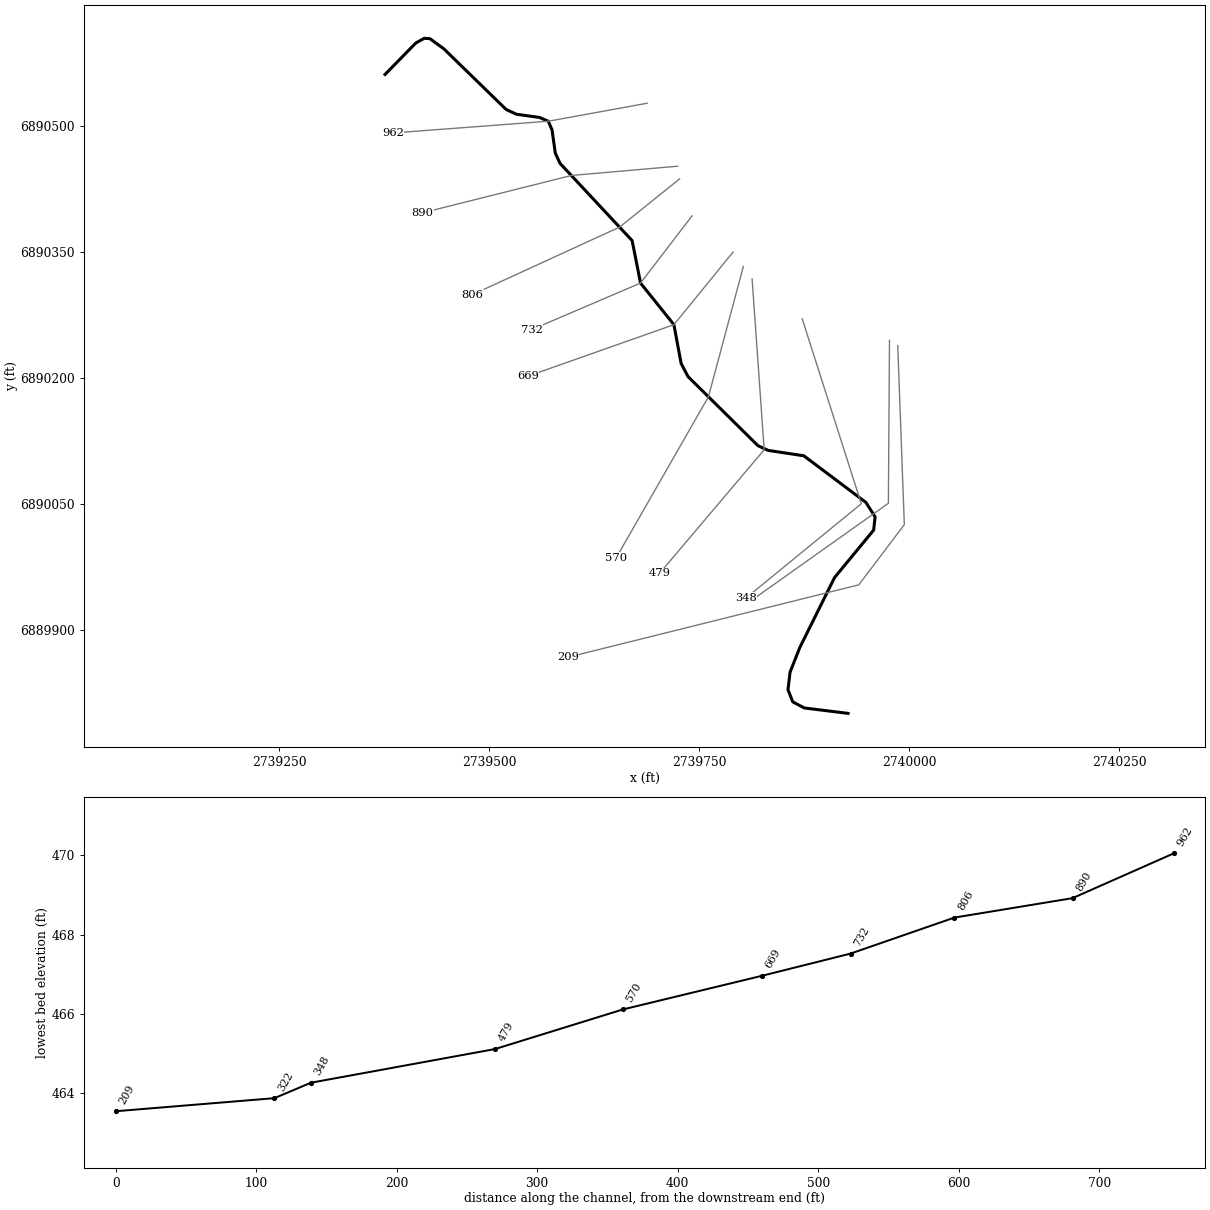
--- Lacy 082.prj (project) ---

Proj Title=Lacy 082 Base Level Engineering
Current Plan=p01
Default Exp/Contr=0.3,0.1
English Units
Geom File=g01
Flow File=f01
Plan File=p01
BEGIN DESCRIPTION:
Lacy 082
END DESCRIPTION:

--- Lacy 082.p01 (plan) ---

Plan Title=Multiple Run
Short Identifier=Multiple
Geom File=g01
Flow File=f01
Subcritical Flow
K Sum by GR= 0
Std Step Tol= 0.01
Critical Tol= 0.01
Num of Std Step Trials= 20
Max Error Tol= 0.3
Flow Tol Ratio= 0.001
Split Flow NTrial= 30
Split Flow Tol= 0.02
Split Flow Ratio= 0.02
Log Output Level= 0
Friction Slope Method= 1
Unsteady Friction Slope Method= 2
Unsteady Bridges Friction Slope Method= 1
Parabolic Critical Depth
Global Vel Dist=  1 , 1 , 1
Global Log Level= 0
CheckData=True
Encroach Param= -1, 0, 0, 0
BEGIN DESCRIPTION:
Multiple Run
END DESCRIPTION:

--- Lacy 082.f01 (steady flow) ---

Flow Title=Multiple
Number of Profiles=7
Profile Names=10-year,25-year,50-year,1pct_min,100-year,1pct_plu,500-year
River Rch & RM= Lacy 082,Reach-1,962
     146     177     199     112     224     446     280
Boundary for River Rch & Prof#=Lacy 082,Reach-1,1
Up Type=0
Dn Type=3
Dn Slope=0.005
Boundary for River Rch & Prof#=Lacy 082,Reach-1,2
Up Type=0
Dn Type=3
Dn Slope=0.005
Boundary for River Rch & Prof#=Lacy 082,Reach-1,3
Up Type=0
Dn Type=3
Dn Slope=0.005
Boundary for River Rch & Prof#=Lacy 082,Reach-1,4
Up Type=0
Dn Type=3
Dn Slope=0.005
Boundary for River Rch & Prof#=Lacy 082,Reach-1,5
Up Type=0
Dn Type=3
Dn Slope=0.005
Boundary for River Rch & Prof#=Lacy 082,Reach-1,6
Up Type=0
Dn Type=3
Dn Slope=0.005
Boundary for River Rch & Prof#=Lacy 082,Reach-1,7
Up Type=0
Dn Type=3
Dn Slope=0.005

--- Lacy 082.g01 (geometry) ---

Geom Title=Existing Conditions

River Reach=Lacy 082,Reach-1
Reach XY= 30
      2739376.00      6890561.00      2739412.66      6890598.49
      2739422.66      6890604.05      2739429.33      6890603.73
      2739445.99      6890591.61      2739520.25      6890519.31
      2739532.43      6890513.71      2739559.96      6890509.85
      2739570.38      6890505.38      2739574.85      6890494.96
      2739578.70      6890467.44      2739584.30      6890455.26
      2739670.15      6890363.29      2739680.19      6890312.73
      2739719.90      6890263.19      2739728.50      6890217.03
      2739736.76      6890201.30      2739819.95      6890119.16
      2739832.08      6890113.54      2739874.57      6890107.12
      2739948.49      6890051.58      2739959.41      6890034.46
      2739957.69      6890018.70      2739911.20      6889962.30
      2739869.77      6889878.88      2739858.15      6889849.51
      2739855.71      6889828.67      2739861.34      6889814.25
      2739875.01      6889806.96      2739927.21      6889800.50

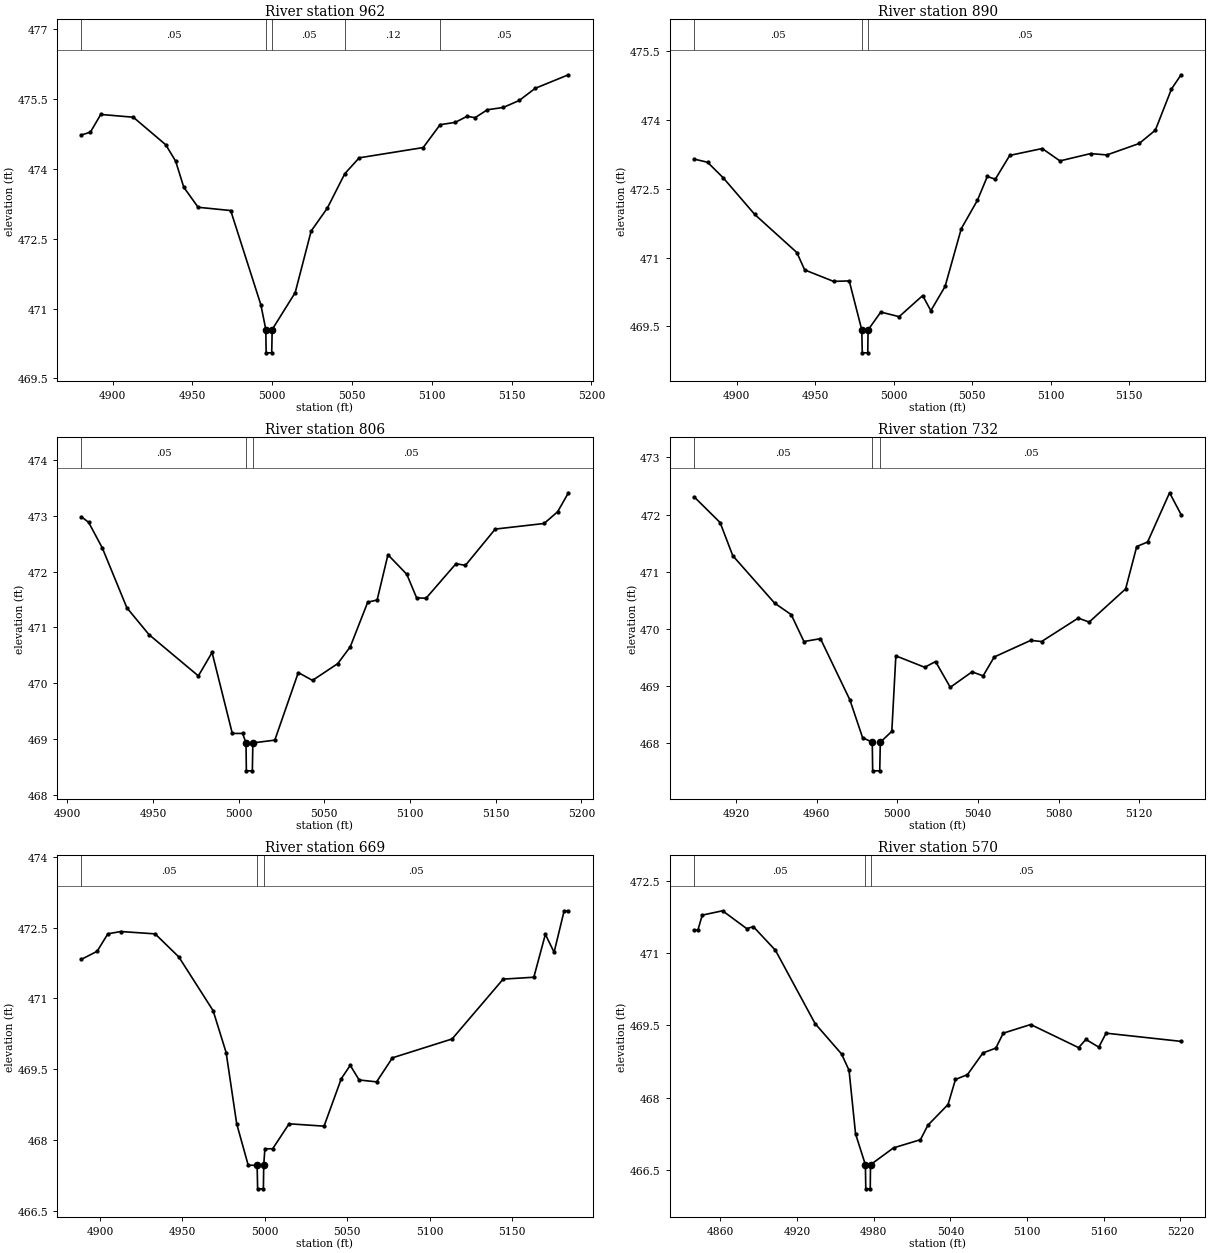
Type RM Length L Ch R = 1,962,72,72,72
BEGIN DESCRIPTION:
Lacy 082 2088
END DESCRIPTION:
XS GIS Cut Line= 3
      2739687.95      6890526.76      2739570.38      6890505.38
      2739385.31      6890491.40
#Sta/Elev= 29
  4880.5  474.72  4886.1  474.78  4892.6  475.16  4913.0  475.10  4933.3  474.51
  4939.5  474.16  4944.6  473.60  4953.6  473.17  4974.0  473.10  4992.9  471.08
  4996.0  470.55  4996.2  470.05  4999.7  470.05  5000.0  470.55  5014.4  471.34
  5024.4  472.66  5034.5  473.15  5045.5  473.89  5054.5  474.23  5094.6  474.45
  5105.2  474.94  5114.7  474.99  5122.1  475.12  5127.1  475.09  5134.8  475.26
  5144.8  475.31  5154.8  475.46  5164.8  475.72  5185.6  476.01
#Mann=5,-1,0
  4880.5    0.05       0  4996.0    0.04       0  5000.0    0.05       0
  5045.5    0.12       0  5105.2    0.05       0
Bank Sta=4996,5000
Exp/Cntr=0.3,0.1

Type RM Length L Ch R = 1,890,84,84,84
BEGIN DESCRIPTION:
Lacy 082 2087
END DESCRIPTION:
XS GIS Cut Line= 3
      2739724.53      6890451.85      2739597.81      6890440.79
      2739420.11      6890396.21
#Sta/Elev= 30
  4872.8  473.15  4881.4  473.08  4891.4  472.74  4911.5  471.94  4938.3  471.11
  4943.3  470.73  4961.7  470.48  4971.7  470.49  4979.7  469.42  4980.0  468.92
  4983.5  468.92  4983.7  469.42  4991.8  469.81  5003.5  469.71  5018.5  470.17
  5023.7  469.84  5032.8  470.37  5043.1  471.63  5053.4  472.25  5059.7  472.77
  5064.8  472.71  5074.0  473.23  5094.7  473.38  5106.0  473.11  5125.6  473.27
  5135.9  473.24  5156.5  473.49  5166.8  473.78  5177.1  474.68  5183.2  474.99
#Mann=3,-1,0
  4872.8    0.05       0  4979.7    0.04       0  4983.7    0.05       0
Bank Sta=4979.7,4983.7
Exp/Cntr=0.3,0.1

Type RM Length L Ch R = 1,806,74,74,74
BEGIN DESCRIPTION:
Lacy 082 2089
END DESCRIPTION:
XS GIS Cut Line= 3
      2739726.69      6890436.73      2739655.19      6890379.32
      2739480.32      6890299.09
#Sta/Elev= 30
  4908.3  472.98  4912.5  472.88  4920.5  472.42  4934.8  471.35  4947.7  470.87
  4976.5  470.13  4984.5  470.55  4996.3  469.10  5002.3  469.10  5004.3  468.93
  5004.5  468.43  5008.0  468.43  5008.3  468.93  5021.1  468.98  5034.8  470.19
  5043.1  470.05  5057.8  470.35  5065.1  470.65  5075.3  471.45  5080.8  471.49
  5087.1  472.30  5098.1  471.95  5103.8  471.53  5109.3  471.52  5126.8  472.14
  5132.3  472.11  5149.7  472.76  5178.2  472.86  5186.1  473.07  5192.4  473.41
#Mann=3,-1,0
  4908.3    0.05       0  5004.3    0.04       0  5008.3    0.05       0
Bank Sta=5004.3,5008.3
Exp/Cntr=0.3,0.1

Type RM Length L Ch R = 1,732,63,63,63
BEGIN DESCRIPTION:
Lacy 082 2086
END DESCRIPTION:
XS GIS Cut Line= 3
      2739741.52      6890392.73      2739680.19      6890312.73
      2739550.74      6890257.35
#Sta/Elev= 30
  4899.2  472.31  4912.1  471.86  4918.4  471.28  4939.2  470.45  4947.4  470.25
  4953.7  469.78  4961.9  469.83  4976.5  468.76  4982.8  468.10  4987.6  468.02
  4987.8  467.52  4991.3  467.52  4991.6  468.02  4997.3  468.21  4999.3  469.53
  5013.6  469.33  5019.0  469.43  5026.3  468.98  5037.1  469.25  5042.6  469.18
  5048.1  469.51  5066.2  469.80  5071.6  469.78  5089.8  470.19  5095.2  470.12
  5113.3  470.70  5118.8  471.44  5124.2  471.52  5135.1  472.38  5140.8  472.00
#Mann=3,-1,0
  4899.2    0.05       0  4987.6    0.04       0  4991.6    0.05       0
Bank Sta=4987.6,4991.6
Exp/Cntr=0.3,0.1

Type RM Length L Ch R = 1,669,99,99,99
BEGIN DESCRIPTION:
Lacy 082 2085
END DESCRIPTION:
XS GIS Cut Line= 3
      2739790.19      6890349.48      2739719.90      6890263.19
      2739546.19      6890201.90
#Sta/Elev= 30
  4888.7  471.83  4898.2  472.00  4904.7  472.37  4912.5  472.42  4933.4  472.37
  4947.8  471.88  4968.6  470.74  4976.5  469.85  4982.9  468.34  4989.9  467.46
  4995.3  467.46  4995.6  466.96  4999.1  466.96  4999.3  467.46  5000.0  467.81
  5004.7  467.81  5014.7  468.34  5035.9  468.29  5046.4  469.30  5051.8  469.58
  5057.2  469.27  5067.8  469.23  5077.4  469.74  5113.6  470.14  5144.6  471.41
  5163.2  471.45  5170.2  472.36  5175.5  471.98  5181.6  472.86  5184.2  472.86
#Mann=3,-1,0
  4888.7    0.05       0  4995.3    0.04       0  4999.3    0.05       0
Bank Sta=4995.3,4999.3
Exp/Cntr=0.3,0.1

Type RM Length L Ch R = 1,570,91,91,91
BEGIN DESCRIPTION:
Lacy 082 2084
END DESCRIPTION:
XS GIS Cut Line= 3
      2739802.55      6890332.50      2739761.00      6890177.36
      2739651.38      6889985.93
#Sta/Elev= 30
  4839.4  471.48  4842.4  471.48  4845.8  471.79  4861.7  471.88  4880.6  471.51
  4885.8  471.55  4903.1  471.06  4934.1  469.54  4954.8  468.91  4960.7  468.57
  4965.8  467.25  4973.5  466.61  4973.8  466.11  4977.3  466.11  4977.5  466.61
  4995.5  466.96  5016.6  467.13  5022.4  467.43  5038.2  467.86  5044.0  468.38
  5053.4  468.48  5065.5  468.93  5075.6  469.03  5081.4  469.34  5102.9  469.52
  5140.4  469.04  5146.1  469.21  5156.2  469.05  5161.9  469.34  5220.6  469.17
#Mann=3,-1,0
  4839.4    0.05       0  4973.5    0.04       0  4977.5    0.05       0
Bank Sta=4973.5,4977.5
Exp/Cntr=0.3,0.1

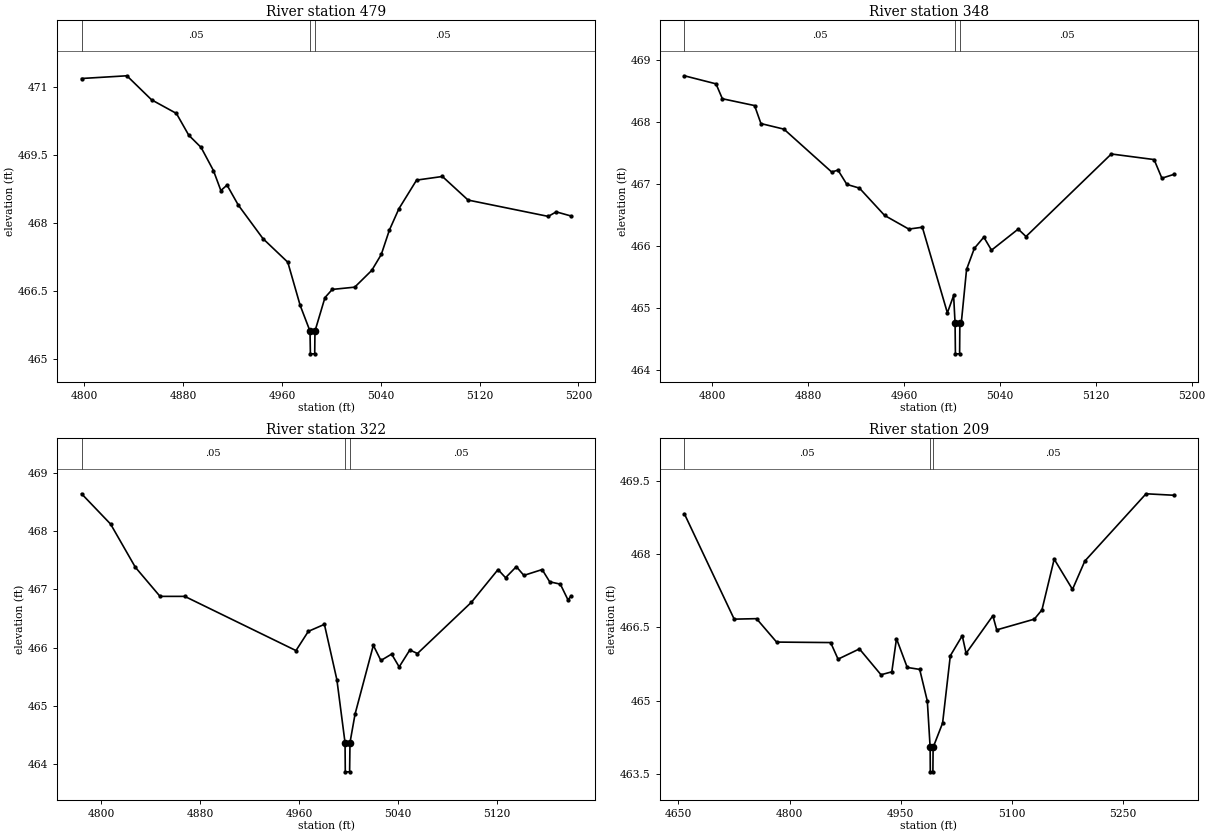
Type RM Length L Ch R = 1,479,131,131,131
BEGIN DESCRIPTION:
Lacy 082 2083
END DESCRIPTION:
XS GIS Cut Line= 3
      2739812.99      6890317.58      2739827.35      6890114.26
      2739703.05      6889967.44
#Sta/Elev= 30
  4797.7  471.18  4834.4  471.24  4854.4  470.71  4874.5  470.41  4884.5  469.93
  4894.5  469.66  4904.5  469.15  4910.5  468.71  4915.5  468.83  4924.6  468.39
  4944.6  467.65  4964.7  467.13  4974.7  466.18  4982.7  465.61  4983.0  465.11
  4986.5  465.11  4986.7  465.61  4994.8  466.35  5000.7  466.53  5018.9  466.58
  5032.7  466.95  5040.4  467.30  5047.0  467.84  5054.7  468.31  5069.0  468.94
  5089.9  469.02  5110.7  468.50  5175.6  468.14  5182.1  468.24  5193.9  468.15
#Mann=3,-1,0
  4797.7    0.05       0  4982.7    0.04       0  4986.7    0.05       0
Bank Sta=4982.7,4986.7
Exp/Cntr=0.3,0.1

Type RM Length L Ch R = 1,348,26,26,26
BEGIN DESCRIPTION:
Lacy 082 3486
END DESCRIPTION:
XS GIS Cut Line= 3
      2739872.62      6890270.14      2739942.97      6890050.05
      2739805.74      6889937.87
#Sta/Elev= 30
  4776.6  468.74  4803.0  468.61  4808.3  468.37  4835.2  468.26  4840.5  467.97
  4859.7  467.88  4899.5  467.19  4904.8  467.22  4912.2  466.99  4922.7  466.93
  4943.7  466.49  4963.9  466.27  4975.2  466.30  4996.1  464.92  5001.3  465.20
  5002.5  464.76  5002.8  464.26  5006.3  464.26  5006.5  464.76  5007.7  464.76
  5012.1  465.62  5018.6  465.96  5026.5  466.14  5032.9  465.93  5055.2  466.27
  5061.7  466.15  5132.9  467.48  5168.6  467.39  5175.1  467.09  5184.9  467.15
#Mann=3,-1,0
  4776.6    0.05       0  5002.5    0.04       0  5006.5    0.05       0
Bank Sta=5002.5,5006.5
Exp/Cntr=0.3,0.1

Type RM Length L Ch R = 1,322,113,113,113
BEGIN DESCRIPTION:
Lacy 082 3456
END DESCRIPTION:
XS GIS Cut Line= 3
      2739976.53      6890244.46      2739975.19      6890050.56
      2739810.43      6889933.71
#Sta/Elev= 30
  4784.1  468.64  4807.6  468.12  4827.6  467.38  4847.6  466.88  4867.6  466.88
  4957.6  465.95  4967.6  466.28  4980.6  466.40  4990.7  465.45  4997.3  464.37
  4997.5  463.87  5001.0  463.87  5001.3  464.37  5005.4  464.86  5020.2  466.04
  5026.3  465.78  5035.0  465.89  5041.1  465.67  5049.7  465.96  5055.9  465.90
  5099.6  466.78  5121.1  467.34  5127.2  467.20  5135.9  467.39  5142.0  467.24
  5156.8  467.34  5162.9  467.13  5171.5  467.09  5177.7  466.82  5180.0  466.88
#Mann=3,-1,0
  4784.1    0.05       0  4997.3    0.04       0  5001.3    0.05       0
Bank Sta=4997.3,5001.3
Exp/Cntr=0.3,0.1

Type RM Length L Ch R = 1,209,0,0,0
BEGIN DESCRIPTION:
Lacy 082 3476
END DESCRIPTION:
XS GIS Cut Line= 4
      2739986.36      6890238.20      2739994.18      6890025.15
      2739939.97      6889953.50      2739593.67      6889867.33
#Sta/Elev= 30
  4658.0  468.83  4725.2  466.67  4755.3  466.68  4782.4  466.20  4855.3  466.19
  4865.3  465.85  4894.1  466.06  4923.2  465.53  4937.8  465.59  4944.1  466.27
  4958.6  465.68  4975.4  465.64  4985.7  464.99  4989.5  464.04  4989.7  463.54
  4993.2  463.54  4993.5  464.04  5006.3  464.54  5016.7  465.92  5032.8  466.33
  5038.0  465.97  5074.1  466.74  5079.3  466.45  5130.0  466.67  5140.3  466.86
  5156.8  467.90  5181.5  467.28  5198.1  467.86  5280.7  469.24  5317.9  469.21
#Mann=3,-1,0
  4658.0    0.05       0  4989.5    0.04       0  4993.5    0.05       0
Bank Sta=4989.5,4993.5
Exp/Cntr=0.3,0.1

Chan Stop Cuts=-1