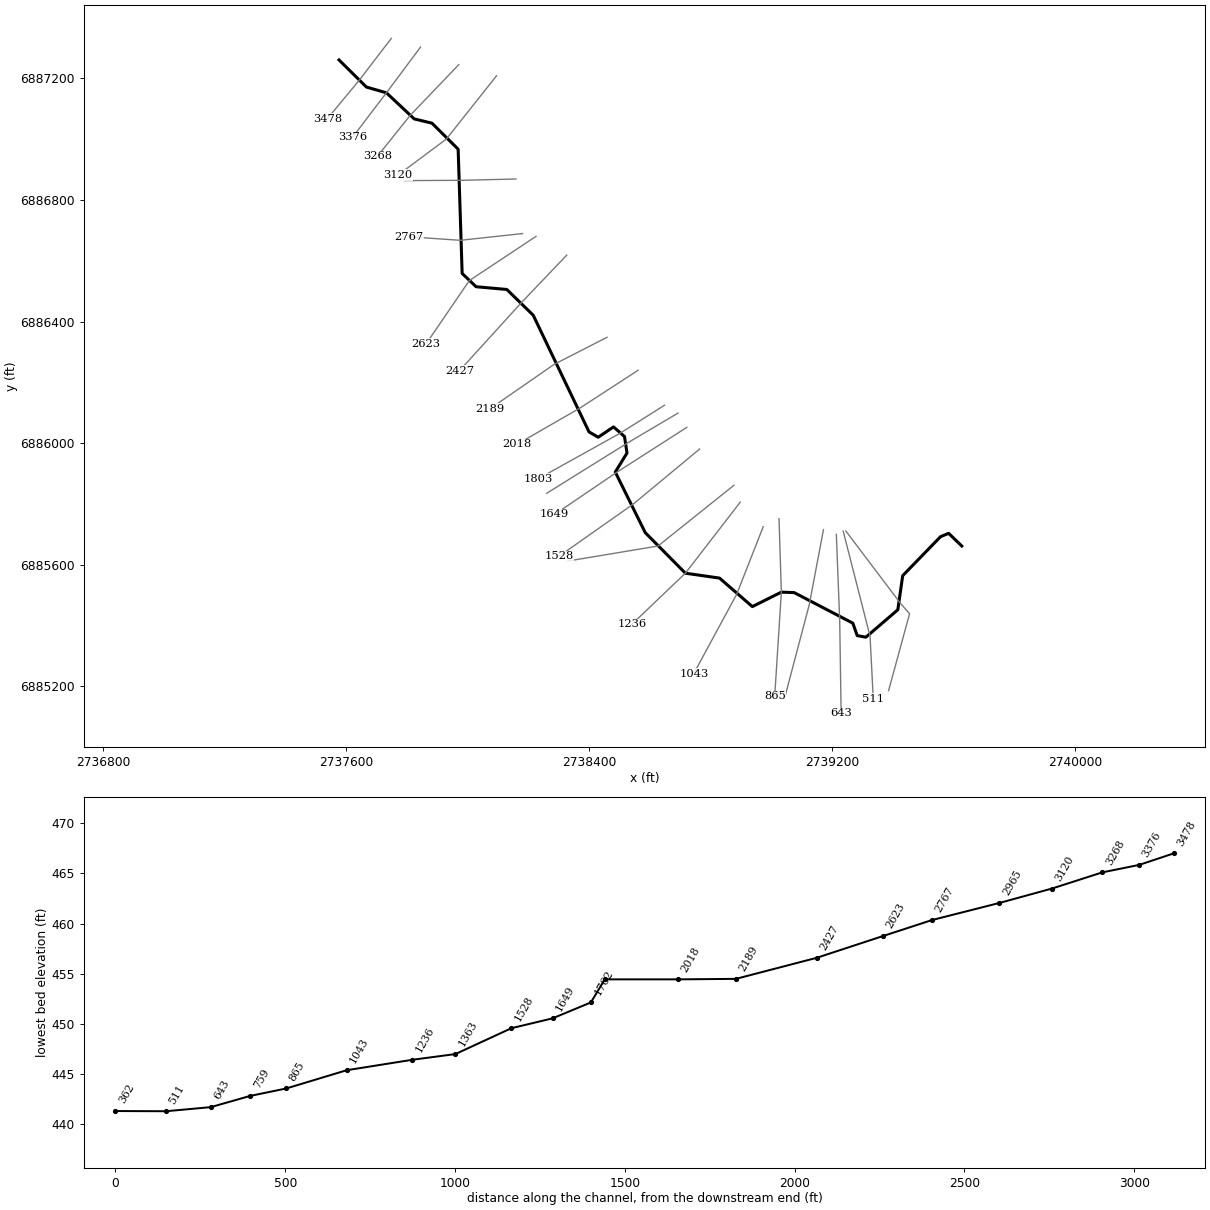
--- Lacy 083.prj (project) ---

Proj Title=Lacy 083 Base Level Engineering
Current Plan=p01
Default Exp/Contr=0.3,0.1
English Units
Geom File=g01
Flow File=f01
Plan File=p01
BEGIN DESCRIPTION:
Lacy 083
END DESCRIPTION:

--- Lacy 083.p01 (plan) ---

Plan Title=Multiple Run
Short Identifier=Multiple
Geom File=g01
Flow File=f01
Subcritical Flow
K Sum by GR= 0
Std Step Tol= 0.01
Critical Tol= 0.01
Num of Std Step Trials= 20
Max Error Tol= 0.3
Flow Tol Ratio= 0.001
Split Flow NTrial= 30
Split Flow Tol= 0.02
Split Flow Ratio= 0.02
Log Output Level= 0
Friction Slope Method= 1
Unsteady Friction Slope Method= 2
Unsteady Bridges Friction Slope Method= 1
Parabolic Critical Depth
Global Vel Dist=  1 , 1 , 1
Global Log Level= 0
CheckData=True
Encroach Param= -1, 0, 0, 0
BEGIN DESCRIPTION:
Multiple Run
END DESCRIPTION:

--- Lacy 083.f01 (steady flow) ---

Flow Title=Multiple
Number of Profiles=7
Profile Names=10-year,25-year,50-year,1pct_min,100-year,1pct_plu,500-year
River Rch & RM= Lacy 083,Reach-1,3478
     240     301     348     200     399     795     522
Boundary for River Rch & Prof#=Lacy 083,Reach-1,1
Up Type=0
Dn Type=3
Dn Slope=0.005
Boundary for River Rch & Prof#=Lacy 083,Reach-1,2
Up Type=0
Dn Type=3
Dn Slope=0.005
Boundary for River Rch & Prof#=Lacy 083,Reach-1,3
Up Type=0
Dn Type=3
Dn Slope=0.005
Boundary for River Rch & Prof#=Lacy 083,Reach-1,4
Up Type=0
Dn Type=3
Dn Slope=0.005
Boundary for River Rch & Prof#=Lacy 083,Reach-1,5
Up Type=0
Dn Type=3
Dn Slope=0.005
Boundary for River Rch & Prof#=Lacy 083,Reach-1,6
Up Type=0
Dn Type=3
Dn Slope=0.005
Boundary for River Rch & Prof#=Lacy 083,Reach-1,7
Up Type=0
Dn Type=3
Dn Slope=0.005

--- Lacy 083.g01 (geometry) ---

Geom Title=Existing Conditions

River Reach=Lacy 083,Reach-1
Reach XY= 30
      2737576.00      6887261.00      2737666.30      6887171.72
      2737732.04      6887152.83      2737823.72      6887066.87
      2737882.07      6887052.85      2737968.20      6886967.21
      2737981.34      6886558.26      2738027.25      6886514.51
      2738128.44      6886505.48      2738215.25      6886420.71
      2738399.01      6886036.64      2738429.17      6886019.09
      2738479.65      6886053.10      2738515.79      6886021.39
      2738524.02      6885967.13      2738485.43      6885904.39
      2738584.14      6885704.94      2738716.21      6885571.52
      2738828.42      6885555.46      2738936.63      6885461.61
      2739032.11      6885509.16      2739074.28      6885507.66
      2739267.38      6885407.03      2739281.77      6885366.11
      2739310.35      6885360.87      2739415.49      6885451.19
      2739431.52      6885563.43      2739556.00      6885691.66
      2739582.67      6885702.81      2739626.00      6885661.00

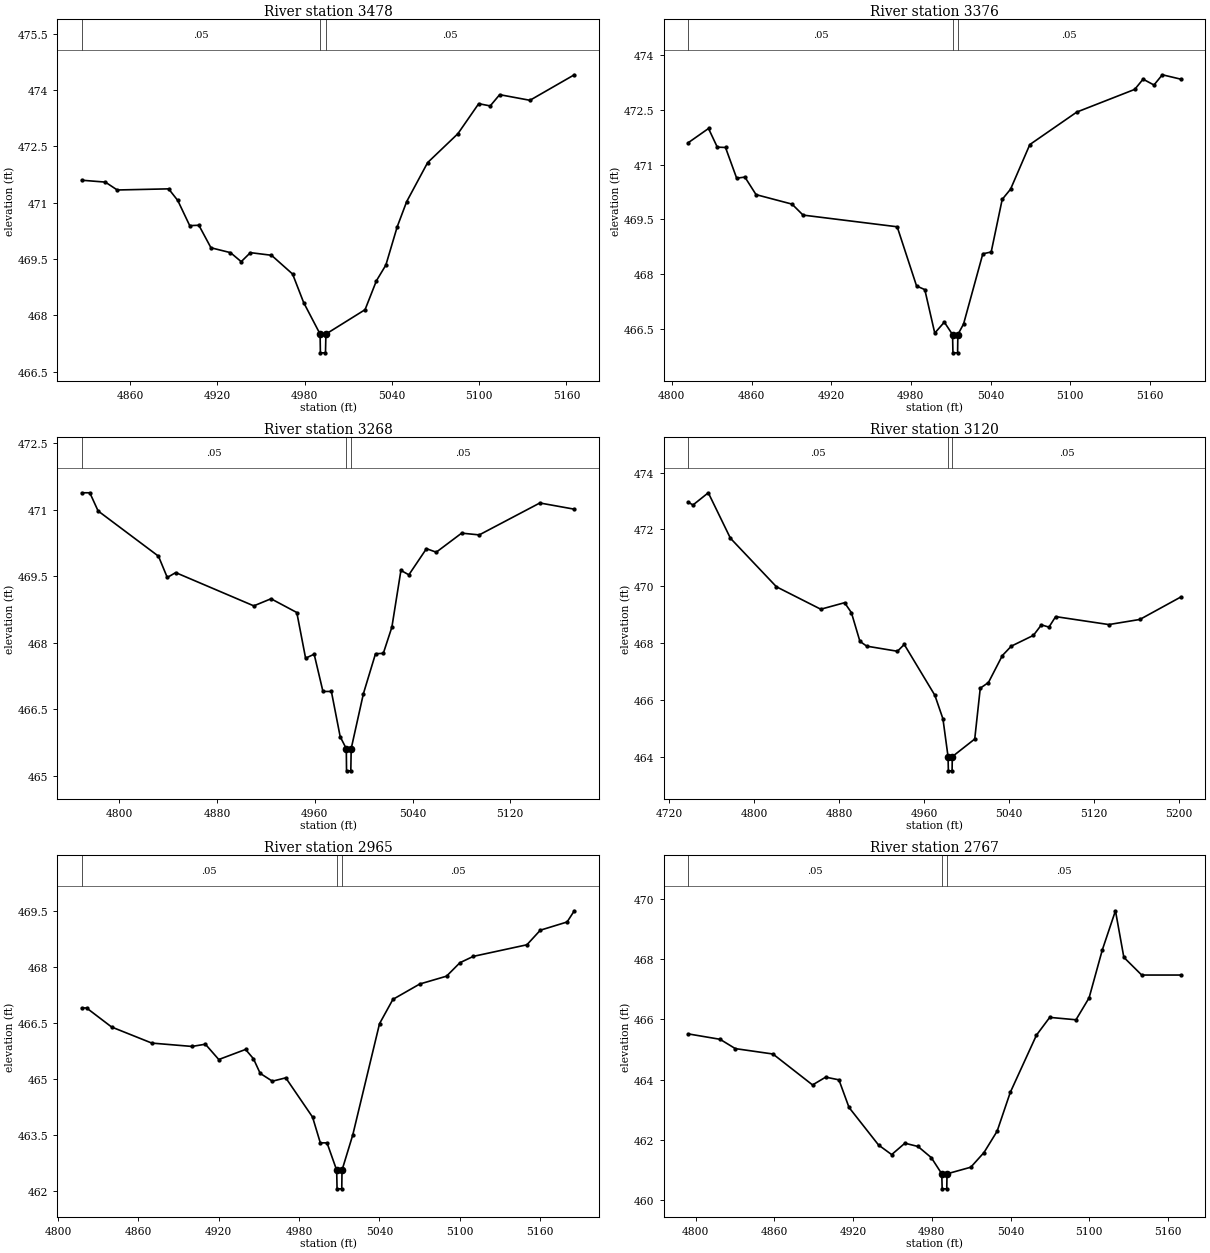
Type RM Length L Ch R = 1,3478,102,102,102
BEGIN DESCRIPTION:
Lacy 083 2057
END DESCRIPTION:
XS GIS Cut Line= 3
      2737748.30      6887332.12      2737643.09      6887194.66
      2737537.49      6887067.36
#Sta/Elev= 30
  4826.9  471.60  4843.1  471.55  4851.3  471.34  4886.6  471.37  4892.9  471.06
  4901.1  470.39  4907.4  470.40  4915.7  469.80  4929.1  469.67  4936.5  469.43
  4942.8  469.67  4957.3  469.60  4971.8  469.10  4979.4  468.34  4990.7  467.50
  4990.9  467.00  4994.4  467.00  4994.7  467.50  5021.6  468.15  5029.4  468.92
  5035.9  469.34  5043.7  470.36  5050.2  471.03  5064.6  472.07  5085.4  472.84
  5099.7  473.64  5107.6  473.58  5114.1  473.88  5134.9  473.73  5165.4  474.41
#Mann=3,-1,0
  4826.9    0.05       0  4990.7    0.04       0  4994.7    0.05       0
Bank Sta=4990.7,4994.7
Exp/Cntr=0.3,0.1

Type RM Length L Ch R = 1,3376,108,108,108
BEGIN DESCRIPTION:
Lacy 083 2056
END DESCRIPTION:
XS GIS Cut Line= 3
      2737844.34      6887303.24      2737732.04      6887152.83
      2737621.04      6887006.96
#Sta/Elev= 30
  4812.3  471.60  4827.6  471.99  4834.2  471.48  4840.4  471.47  4848.8  470.63
  4855.0  470.66  4863.4  470.18  4890.5  469.92  4898.8  469.62  4969.7  469.30
  4984.3  467.68  4990.5  467.58  4998.0  466.39  5005.2  466.69  5011.4  466.35
  5011.7  465.85  5015.2  465.85  5015.4  466.35  5019.7  466.64  5034.2  468.56
  5040.5  468.61  5048.8  470.05  5055.1  470.33  5069.6  471.55  5105.0  472.44
  5148.6  473.06  5154.9  473.34  5163.1  473.18  5169.4  473.46  5183.3  473.34
#Mann=3,-1,0
  4812.3    0.05       0  5011.4    0.04       0  5015.4    0.05       0
Bank Sta=5011.4,5015.4
Exp/Cntr=0.3,0.1

Type RM Length L Ch R = 1,3268,148,148,148
BEGIN DESCRIPTION:
Lacy 083 2055
END DESCRIPTION:
XS GIS Cut Line= 3
      2737970.38      6887245.59      2737810.77      6887079.01
      2737702.93      6886944.51
#Sta/Elev= 30
  4769.3  471.38  4775.9  471.38  4782.7  470.97  4832.1  469.95  4839.3  469.47
  4846.2  469.58  4910.1  468.83  4924.2  468.99  4945.3  468.68  4952.5  467.65
  4959.5  467.74  4966.7  466.90  4973.6  466.90  4980.8  465.88  4985.8  465.61
  4986.0  465.11  4989.5  465.11  4989.8  465.61  4999.8  466.85  5009.7  467.75
  5016.1  467.76  5023.1  468.35  5030.5  469.63  5037.0  469.53  5051.4  470.12
  5059.4  470.04  5080.2  470.47  5094.6  470.43  5144.2  471.15  5172.4  471.01
#Mann=3,-1,0
  4769.3    0.05       0  4985.8    0.04       0  4989.8    0.05       0
Bank Sta=4985.8,4989.8
Exp/Cntr=0.3,0.1

Type RM Length L Ch R = 1,3120,155,155,155
BEGIN DESCRIPTION:
Lacy 083 2047
END DESCRIPTION:
XS GIS Cut Line= 3
      2738094.46      6887208.68      2737929.27      6887000.44
      2737770.87      6886882.49
#Sta/Elev= 30
  4738.1  472.96  4742.6  472.86  4757.0  473.29  4777.8  471.69  4821.1  469.98
  4862.8  469.19  4885.2  469.42  4891.6  469.07  4899.6  468.06  4906.0  467.89
  4934.9  467.71  4941.3  467.95  4970.1  466.16  4977.7  465.33  4982.5  464.00
  4982.8  463.50  4986.3  463.50  4986.5  464.00  5007.6  464.62  5012.8  466.41
  5020.5  466.61  5033.6  467.56  5042.0  467.89  5062.8  468.27  5070.3  468.64
  5077.4  468.56  5083.7  468.93  5133.7  468.65  5162.9  468.83  5201.4  469.62
#Mann=3,-1,0
  4738.1    0.05       0  4982.5    0.04       0  4986.5    0.05       0
Bank Sta=4982.5,4986.5
Exp/Cntr=0.3,0.1

Type RM Length L Ch R = 1,2965,198,198,198
BEGIN DESCRIPTION:
Lacy 083 2046
END DESCRIPTION:
XS GIS Cut Line= 3
      2738158.29      6886869.07      2737979.43      6886864.82
      2737790.64      6886863.79
#Sta/Elev= 30
  4817.8  466.90  4821.4  466.90  4840.1  466.39  4870.1  465.96  4900.1  465.87
  4910.1  465.93  4920.1  465.52  4940.1  465.79  4946.0  465.54  4951.0  465.15
  4960.1  464.94  4970.1  465.03  4990.1  463.98  4995.9  463.29  5000.9  463.29
  5008.1  462.56  5008.4  462.06  5011.9  462.06  5012.1  462.56  5020.1  463.50
  5040.1  466.48  5050.1  467.13  5070.1  467.54  5090.1  467.75  5100.1  468.11
  5110.1  468.28  5150.1  468.59  5160.1  468.98  5180.1  469.20  5185.5  469.50
#Mann=3,-1,0
  4817.8    0.05       0  5008.1    0.04       0  5012.1    0.05       0
Bank Sta=5008.1,5012.1
Exp/Cntr=0.3,0.1

Type RM Length L Ch R = 1,2767,144,144,144
BEGIN DESCRIPTION:
Lacy 083 2045
END DESCRIPTION:
XS GIS Cut Line= 3
      2738180.21      6886689.49      2737975.33      6886667.30
      2737806.30      6886678.87
#Sta/Elev= 30
  4794.3  465.52  4818.6  465.34  4830.2  465.03  4858.9  464.85  4889.1  463.82
  4899.1  464.08  4909.2  463.99  4916.9  463.07  4939.4  461.82  4949.4  461.50
  4959.5  461.88  4969.5  461.77  4979.6  461.40  4987.6  460.86  4987.9  460.36
  4991.4  460.36  4991.6  460.86  5009.7  461.08  5019.8  461.57  5029.8  462.28
  5039.8  463.57  5059.8  465.48  5069.9  466.07  5089.9  465.99  5099.9  466.72
  5110.0  468.32  5120.0  469.62  5126.4  468.07  5140.0  467.48  5169.8  467.48
#Mann=3,-1,0
  4794.3    0.05       0  4987.6    0.04       0  4991.6    0.05       0
Bank Sta=4987.6,4991.6
Exp/Cntr=0.3,0.1

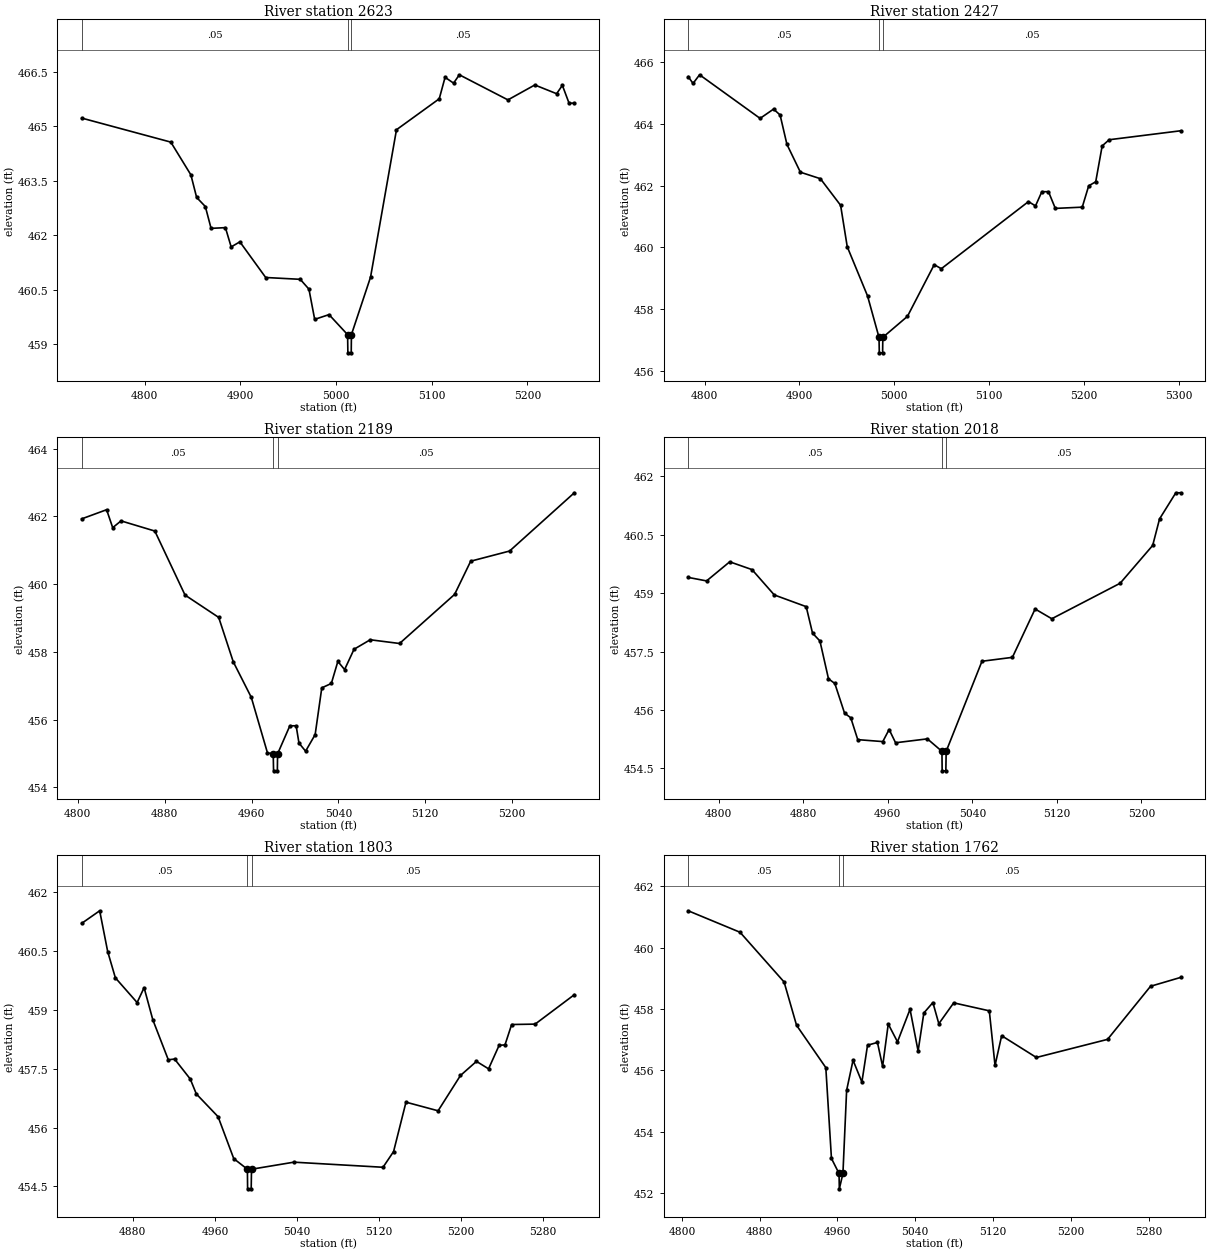
Type RM Length L Ch R = 1,2623,196,196,196
BEGIN DESCRIPTION:
Lacy 083 2044
END DESCRIPTION:
XS GIS Cut Line= 3
      2738224.45      6886680.17      2738004.89      6886534.65
      2737863.12      6886326.92
#Sta/Elev= 30
  4734.1  465.22  4827.2  464.56  4848.2  463.66  4854.2  463.04  4863.3  462.79
  4869.3  462.19  4884.3  462.21  4890.3  461.68  4899.4  461.82  4926.4  460.84
  4962.5  460.79  4971.6  460.52  4977.6  459.69  4992.6  459.82  5012.0  459.27
  5012.3  458.77  5015.8  458.77  5016.0  459.27  5036.0  460.85  5063.1  464.90
  5107.8  465.75  5113.9  466.34  5122.8  466.18  5128.8  466.41  5179.6  465.72
  5207.7  466.13  5230.5  465.89  5236.5  466.12  5243.5  465.63  5249.0  465.63
#Mann=3,-1,0
  4734.1    0.05       0  5012.0    0.04       0  5016.0    0.05       0
Bank Sta=5012,5016
Exp/Cntr=0.3,0.1

Type RM Length L Ch R = 1,2427,238,238,238
BEGIN DESCRIPTION:
Lacy 083 2043
END DESCRIPTION:
XS GIS Cut Line= 3
      2738325.63      6886618.47      2738176.77      6886462.54
      2737972.36      6886237.76
#Sta/Elev= 30
  4782.8  465.52  4787.9  465.30  4794.8  465.58  4858.6  464.17  4872.8  464.47
  4879.7  464.28  4886.9  463.33  4901.1  462.43  4922.2  462.22  4943.5  461.36
  4950.5  460.02  4971.9  458.43  4984.0  457.09  4984.3  456.59  4987.8  456.59
  4988.0  457.09  5014.0  457.77  5042.2  459.44  5049.7  459.31  5141.6  461.48
  5149.0  461.34  5155.7  461.80  5162.7  461.80  5169.9  461.26  5198.3  461.30
  5205.1  461.99  5212.5  462.12  5219.3  463.28  5226.7  463.48  5302.2  463.77
#Mann=3,-1,0
  4782.8    0.05       0  4984.0    0.04       0  4988.0    0.05       0
Bank Sta=4984,4988
Exp/Cntr=0.3,0.1

Type RM Length L Ch R = 1,2189,171,171,171
BEGIN DESCRIPTION:
Lacy 083 2042
END DESCRIPTION:
XS GIS Cut Line= 3
      2738458.25      6886348.02      2738284.31      6886259.01
      2738072.17      6886111.98
#Sta/Elev= 30
  4803.7  461.93  4826.6  462.20  4832.2  461.67  4839.9  461.87  4871.0  461.57
  4898.8  459.68  4929.8  459.02  4943.2  457.71  4959.8  456.66  4974.7  455.02
  4980.0  454.99  4980.3  454.49  4983.8  454.49  4984.0  454.99  4995.3  455.82
  5001.1  455.82  5003.7  455.31  5009.8  455.07  5018.6  455.56  5024.7  456.94
  5033.5  457.07  5039.5  457.72  5045.7  457.48  5054.4  458.08  5069.3  458.36
  5096.3  458.25  5147.0  459.70  5161.8  460.68  5197.6  460.98  5257.2  462.70
#Mann=3,-1,0
  4803.7    0.05       0  4980.0    0.04       0  4984.0    0.05       0
Bank Sta=4980,4984
Exp/Cntr=0.3,0.1

Type RM Length L Ch R = 1,2018,215,215,215
BEGIN DESCRIPTION:
Lacy 083 2041
END DESCRIPTION:
XS GIS Cut Line= 3
      2738560.56      6886239.60      2738369.87      6886115.58
      2738162.93      6885996.36
#Sta/Elev= 30
  4771.0  459.40  4788.4  459.31  4810.3  459.80  4831.4  459.60  4852.5  458.95
  4882.7  458.65  4888.7  457.97  4895.7  457.77  4903.8  456.80  4909.8  456.68
  4919.0  455.92  4924.9  455.80  4931.5  455.24  4955.2  455.19  4961.2  455.50
  4967.3  455.16  4997.4  455.26  5011.2  454.94  5011.4  454.44  5014.9  454.44
  5015.2  454.94  5049.1  457.25  5077.9  457.35  5099.4  458.59  5115.2  458.34
  5179.9  459.25  5210.7  460.22  5217.2  460.90  5232.6  461.57  5237.3  461.57
#Mann=3,-1,0
  4771.0    0.05       0  5011.2    0.04       0  5015.2    0.05       0
Bank Sta=5011.2,5015.2
Exp/Cntr=0.3,0.1

Type RM Length L Ch R = 1,1803,41,41,41
BEGIN DESCRIPTION:
Lacy 083 2040
END DESCRIPTION:
XS GIS Cut Line= 3
      2738647.44      6886124.33      2738500.73      6886031.91
      2738232.61      6885882.78
#Sta/Elev= 30
  4830.2  461.21  4847.7  461.53  4855.5  460.49  4863.0  459.82  4884.2  459.19
  4891.0  459.57  4899.5  458.75  4914.6  457.73  4920.7  457.75  4936.0  457.24
  4941.9  456.86  4963.1  456.28  4978.4  455.21  4991.7  454.94  4991.9  454.44
  4995.4  454.44  4995.7  454.94  5037.0  455.12  5123.9  454.99  5134.2  455.39
  5146.3  456.65  5177.6  456.43  5199.4  457.33  5215.0  457.69  5226.8  457.50
  5237.1  458.10  5242.8  458.11  5249.3  458.63  5272.2  458.64  5310.4  459.39
#Mann=3,-1,0
  4830.2    0.05       0  4991.7    0.04       0  4995.7    0.05       0
Bank Sta=4991.7,4995.7
Exp/Cntr=0.3,0.1

Type RM Length L Ch R = 1,1762,113,113,113
BEGIN DESCRIPTION:
Lacy 083 2039
END DESCRIPTION:
XS GIS Cut Line= 3
      2738691.89      6886098.51      2738527.73      6886001.53
      2738259.64      6885834.56
#Sta/Elev= 30
  4806.5  461.20  4859.8  460.50  4905.1  458.88  4917.9  457.47  4948.0  456.09
  4953.8  453.13  4961.6  452.64  4961.9  452.14  4965.6  452.64  4969.4  455.35
  4976.0  456.33  4985.1  455.62  4990.9  456.82  5001.1  456.91  5006.4  456.13
  5012.2  457.51  5021.7  456.93  5034.6  457.99  5042.9  456.63  5048.8  457.87
  5058.1  458.21  5064.2  457.52  5079.5  458.20  5116.1  457.94  5122.0  456.16
  5128.8  457.13  5164.5  456.42  5237.7  457.01  5281.9  458.74  5313.0  459.03
#Mann=3,-1,0
  4806.5    0.05       0  4961.6    0.04       0  4965.6    0.05       0
Bank Sta=4961.6,4965.6
Exp/Cntr=0.3,0.1

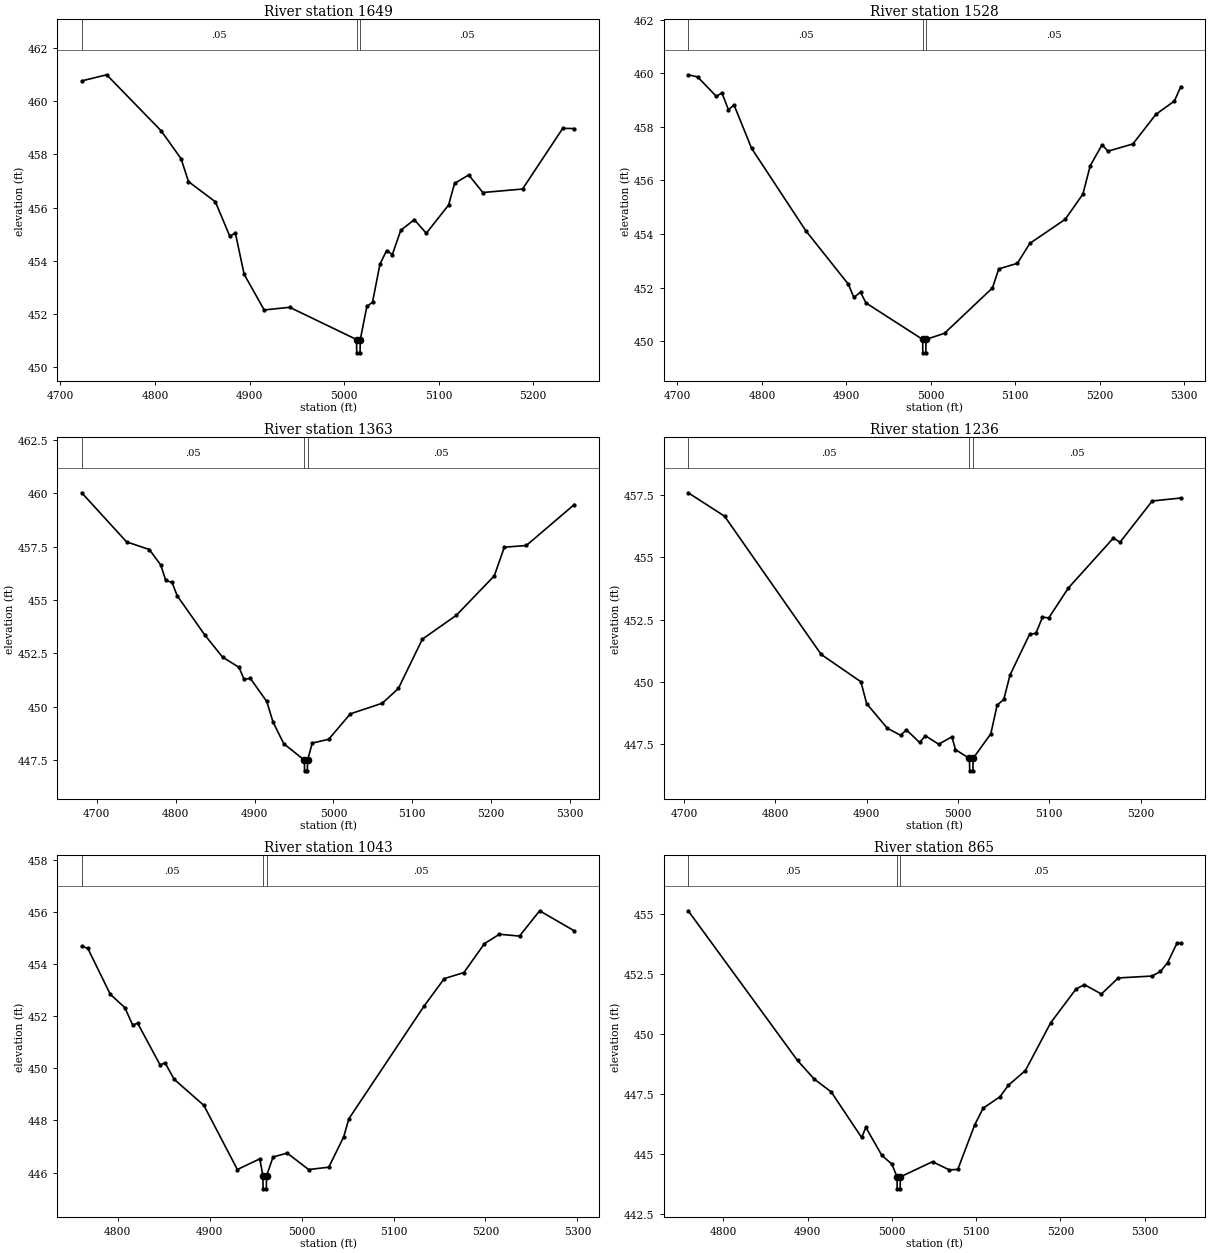
Type RM Length L Ch R = 1,1649,121,121,121
BEGIN DESCRIPTION:
Lacy 083 2038
END DESCRIPTION:
XS GIS Cut Line= 3
      2738721.07      6886051.64      2738489.76      6885903.40
      2738285.94      6885765.00
#Sta/Elev= 30
  4722.5  460.76  4748.9  460.99  4806.4  458.89  4827.6  457.84  4835.4  456.98
  4863.9  456.22  4879.1  454.93  4885.0  455.05  4894.3  453.50  4915.5  452.16
  4942.5  452.26  5013.2  451.05  5013.4  450.55  5016.9  450.55  5017.2  451.05
  5024.1  452.29  5030.1  452.45  5038.0  453.88  5045.0  454.39  5051.1  454.24
  5060.0  455.15  5074.3  455.55  5087.0  455.04  5110.6  456.10  5116.9  456.91
  5131.9  457.23  5146.8  456.57  5188.8  456.70  5231.4  458.98  5243.6  458.97
#Mann=3,-1,0
  4722.5    0.05       0  5013.2    0.04       0  5017.2    0.05       0
Bank Sta=5013.2,5017.2
Exp/Cntr=0.3,0.1

Type RM Length L Ch R = 1,1528,165,165,165
BEGIN DESCRIPTION:
Lacy 083 2037
END DESCRIPTION:
XS GIS Cut Line= 3
      2738763.10      6885980.26      2738544.81      6885799.21
      2738299.79      6885626.80
#Sta/Elev= 30
  4712.7  459.94  4723.9  459.86  4746.1  459.13  4752.6  459.27  4760.4  458.63
  4766.9  458.82  4787.7  457.20  4851.8  454.13  4902.3  452.13  4908.8  451.64
  4916.7  451.83  4923.2  451.43  4990.3  450.07  4990.5  449.57  4994.0  449.57
  4994.3  450.07  5016.2  450.30  5072.9  451.99  5080.4  452.70  5102.5  452.91
  5117.1  453.65  5159.1  454.55  5180.0  455.49  5188.7  456.55  5202.7  457.33
  5209.6  457.09  5239.2  457.36  5266.3  458.46  5288.3  458.96  5295.9  459.50
#Mann=3,-1,0
  4712.7    0.05       0  4990.3    0.04       0  4994.3    0.05       0
Bank Sta=4990.3,4994.3
Exp/Cntr=0.3,0.1

Type RM Length L Ch R = 1,1363,127,127,127
BEGIN DESCRIPTION:
Lacy 083 77
END DESCRIPTION:
XS GIS Cut Line= 3
      2738876.01      6885861.01      2738626.00      6885661.00
      2738326.01      6885611.00
#Sta/Elev= 30
  4681.0  460.02  4737.8  457.72  4766.7  457.36  4781.1  456.64  4787.5  455.91
  4795.5  455.82  4801.9  455.20  4837.1  453.35  4859.5  452.32  4880.3  451.84
  4886.7  451.28  4894.7  451.32  4915.5  450.24  4923.5  449.27  4937.1  448.26
  4963.2  447.49  4963.4  446.99  4966.9  446.99  4967.2  447.49  4973.2  448.29
  4994.0  448.47  5021.4  449.66  5062.0  450.16  5082.3  450.85  5112.7  453.16
  5155.8  454.28  5203.9  456.13  5216.6  457.47  5244.5  457.55  5305.3  459.47
#Mann=3,-1,0
  4681.0    0.05       0  4963.2    0.04       0  4967.2    0.05       0
Bank Sta=4963.2,4967.2
Exp/Cntr=0.3,0.1

Type RM Length L Ch R = 1,1236,193,193,193
BEGIN DESCRIPTION:
Lacy 083 2053
END DESCRIPTION:
XS GIS Cut Line= 3
      2738896.87      6885805.49      2738716.21      6885571.52
      2738539.72      6885403.04
#Sta/Elev= 30
  4704.4  457.60  4744.2  456.66  4850.1  451.10  4893.6  450.00  4899.9  449.12
  4922.6  448.13  4937.1  447.85  4943.4  448.07  4957.9  447.56  4964.3  447.83
  4978.8  447.49  4993.3  447.79  4997.2  447.27  5012.5  446.92  5012.8  446.42
  5016.3  446.42  5016.5  446.92  5035.9  447.91  5042.8  449.06  5050.1  449.29
  5057.0  450.28  5078.4  451.91  5085.3  451.95  5092.5  452.60  5099.4  452.57
  5120.8  453.77  5170.2  455.78  5177.4  455.61  5212.7  457.27  5244.0  457.39
#Mann=3,-1,0
  4704.4    0.05       0  5012.5    0.04       0  5016.5    0.05       0
Bank Sta=5012.5,5016.5
Exp/Cntr=0.3,0.1

Type RM Length L Ch R = 1,1043,178,178,178
BEGIN DESCRIPTION:
Lacy 083 2052
END DESCRIPTION:
XS GIS Cut Line= 3
      2738972.43      6885724.58      2738885.04      6885502.13
      2738743.85      6885241.29
#Sta/Elev= 30
  4761.0  454.68  4767.6  454.60  4792.0  452.84  4807.8  452.33  4816.4  451.66
  4821.8  451.73  4846.2  450.13  4851.6  450.21  4861.5  449.58  4893.8  448.58
  4930.2  446.12  4954.6  446.53  4958.0  445.88  4958.2  445.38  4961.7  445.38
  4962.0  445.88  4969.0  446.60  4984.4  446.75  5007.7  446.12  5029.6  446.21
  5045.8  447.37  5051.5  448.07  5133.3  452.39  5155.2  453.44  5176.5  453.67
  5198.9  454.78  5215.1  455.14  5237.0  455.07  5258.9  456.04  5296.6  455.27
#Mann=3,-1,0
  4761.0    0.05       0  4958.0    0.04       0  4962.0    0.05       0
Bank Sta=4958,4962
Exp/Cntr=0.3,0.1

Type RM Length L Ch R = 1,865,106,106,106
BEGIN DESCRIPTION:
Lacy 083 2051
END DESCRIPTION:
XS GIS Cut Line= 3
      2739024.37      6885750.63      2739032.11      6885509.16
      2739010.23      6885166.95
#Sta/Elev= 30
  4758.4  455.15  4888.1  448.91  4908.1  448.13  4928.1  447.60  4964.2  445.70
  4969.2  446.12  4988.1  444.96  5000.0  444.59  5006.2  444.06  5006.4  443.56
  5009.9  443.56  5010.2  444.06  5048.3  444.69  5068.3  444.35  5078.3  444.37
  5098.4  446.23  5108.4  446.92  5128.4  447.40  5138.4  447.88  5158.5  448.49
  5188.5  450.48  5218.6  451.89  5228.6  452.07  5248.7  451.68  5268.7  452.35
  5308.8  452.43  5318.8  452.62  5327.3  452.99  5338.4  453.80  5342.9  453.80
#Mann=3,-1,0
  4758.4    0.05       0  5006.2    0.04       0  5010.2    0.05       0
Bank Sta=5006.2,5010.2
Exp/Cntr=0.3,0.1

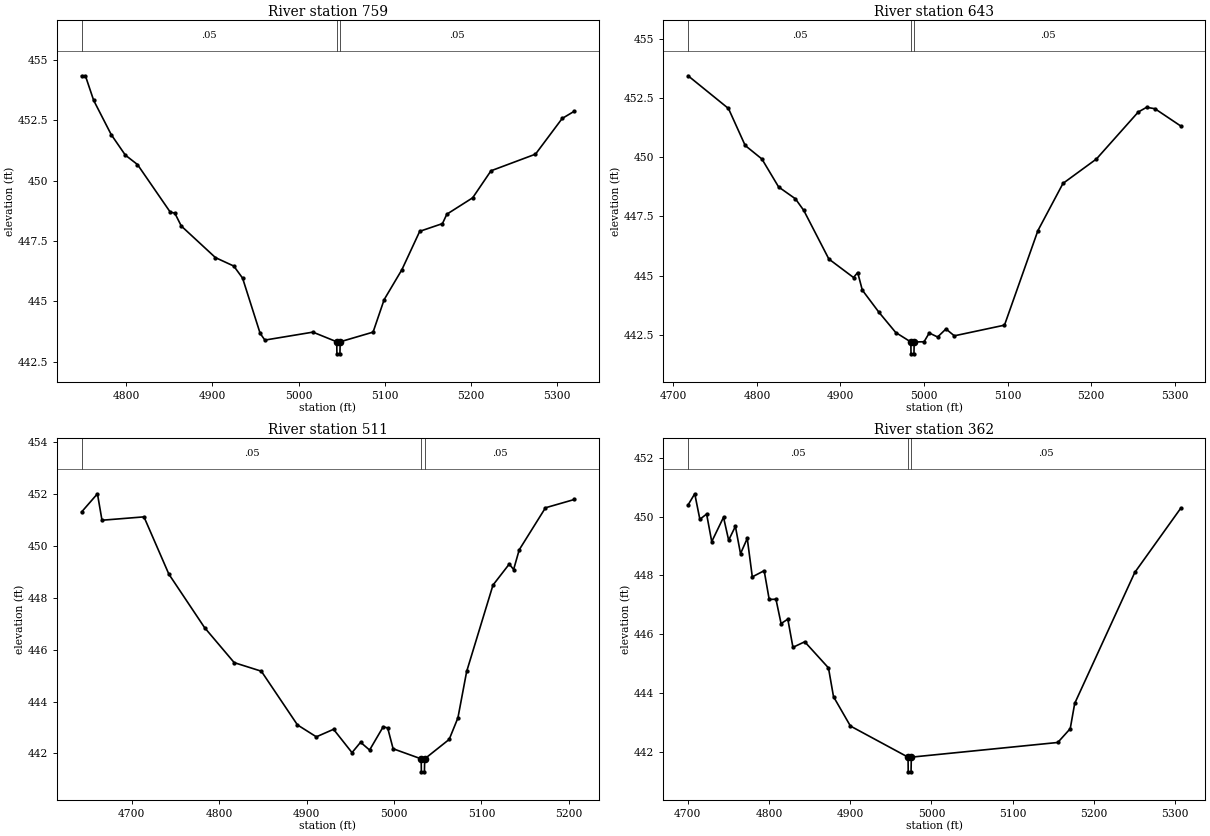
Type RM Length L Ch R = 1,759,116,116,116
BEGIN DESCRIPTION:
Lacy 083 2050
END DESCRIPTION:
XS GIS Cut Line= 3
      2739170.67      6885714.76      2739123.81      6885467.16
      2739042.01      6885157.37
#Sta/Elev= 30
  4748.0  454.35  4752.4  454.35  4762.0  453.33  4782.4  451.91  4798.8  451.06
  4812.9  450.67  4851.1  448.69  4856.2  448.66  4863.8  448.12  4903.5  446.81
  4924.8  446.46  4935.0  445.96  4955.4  443.67  4960.9  443.39  5016.7  443.72
  5044.4  443.32  5044.6  442.82  5048.1  442.82  5048.4  443.32  5086.6  443.72
  5099.5  445.07  5120.1  446.31  5140.8  447.90  5167.2  448.22  5172.3  448.61
  5202.3  449.29  5223.6  450.41  5275.3  451.10  5306.3  452.58  5320.4  452.88
#Mann=3,-1,0
  4748.0    0.05       0  5044.4    0.04       0  5048.4    0.05       0
Bank Sta=5044.4,5048.4
Exp/Cntr=0.3,0.1

Type RM Length L Ch R = 1,643,132,132,132
BEGIN DESCRIPTION:
Lacy 083 2049
END DESCRIPTION:
XS GIS Cut Line= 3
      2739213.10      6885699.26      2739224.12      6885417.17
      2739228.89      6885110.11
#Sta/Elev= 30
  4717.7  453.43  4766.0  452.05  4786.0  450.49  4806.0  449.92  4826.0  448.74
  4846.1  448.24  4856.1  447.75  4886.1  445.70  4915.6  444.92  4920.6  445.13
  4926.1  444.39  4946.1  443.45  4966.1  442.60  4984.2  442.20  4984.4  441.70
  4987.9  441.70  4988.2  442.20  5000.0  442.21  5006.2  442.58  5016.2  442.41
  5026.2  442.75  5036.2  442.46  5096.2  442.91  5136.2  446.90  5166.2  448.89
  5206.2  449.92  5256.2  451.90  5266.2  452.10  5276.2  452.04  5307.1  451.31
#Mann=3,-1,0
  4717.7    0.05       0  4984.2    0.04       0  4988.2    0.05       0
Bank Sta=4984.2,4988.2
Exp/Cntr=0.3,0.1

Type RM Length L Ch R = 1,511,149,149,149
BEGIN DESCRIPTION:
Lacy 083 2048
END DESCRIPTION:
XS GIS Cut Line= 3
      2739235.64      6885710.10      2739324.03      6885364.01
      2739334.64      6885158.08
#Sta/Elev= 30
  4642.8  451.31  4660.9  452.01  4666.1  450.99  4714.1  451.12  4742.6  448.91
  4783.4  446.85  4817.3  445.50  4848.3  445.17  4889.6  443.10  4911.2  442.64
  4930.9  442.93  4952.0  442.03  4961.8  442.43  4972.1  442.13  4987.7  443.03
  4992.8  442.98  4999.0  442.18  5031.1  441.79  5031.3  441.29  5034.8  441.29
  5035.1  441.79  5063.1  442.54  5073.1  443.37  5083.1  445.16  5113.2  448.49
  5131.8  449.30  5136.8  449.09  5143.2  449.85  5173.2  451.47  5206.2  451.79
#Mann=3,-1,0
  4642.8    0.05       0  5031.1    0.04       0  5035.1    0.05       0
Bank Sta=5031.1,5035.1
Exp/Cntr=0.3,0.1

Type RM Length L Ch R = 1,362,0,0,0
BEGIN DESCRIPTION:
Lacy 083 2054
END DESCRIPTION:
XS GIS Cut Line= 4
      2739244.37      6885710.37      2739424.84      6885471.47
      2739454.15      6885438.16      2739385.10      6885185.08
#Sta/Elev= 30
  4700.6  450.40  4708.8  450.78  4715.1  449.91  4723.4  450.09  4729.7  449.15
  4744.2  449.98  4750.5  449.20  4758.8  449.67  4765.1  448.74  4773.4  449.26
  4779.6  447.95  4794.2  448.16  4800.4  447.18  4808.7  447.19  4815.0  446.36
  4823.3  446.51  4829.6  445.55  4844.1  445.74  4873.3  444.85  4879.5  443.87
  4900.3  442.87  4971.2  441.81  4971.4  441.31  4974.9  441.31  4975.2  441.81
  5155.4  442.31  5170.7  442.78  5176.2  443.64  5250.1  448.10  5306.7  450.29
#Mann=3,-1,0
  4700.6    0.05       0  4971.2    0.04       0  4975.2    0.05       0
Bank Sta=4971.2,4975.2
Exp/Cntr=0.3,0.1

Chan Stop Cuts=-1