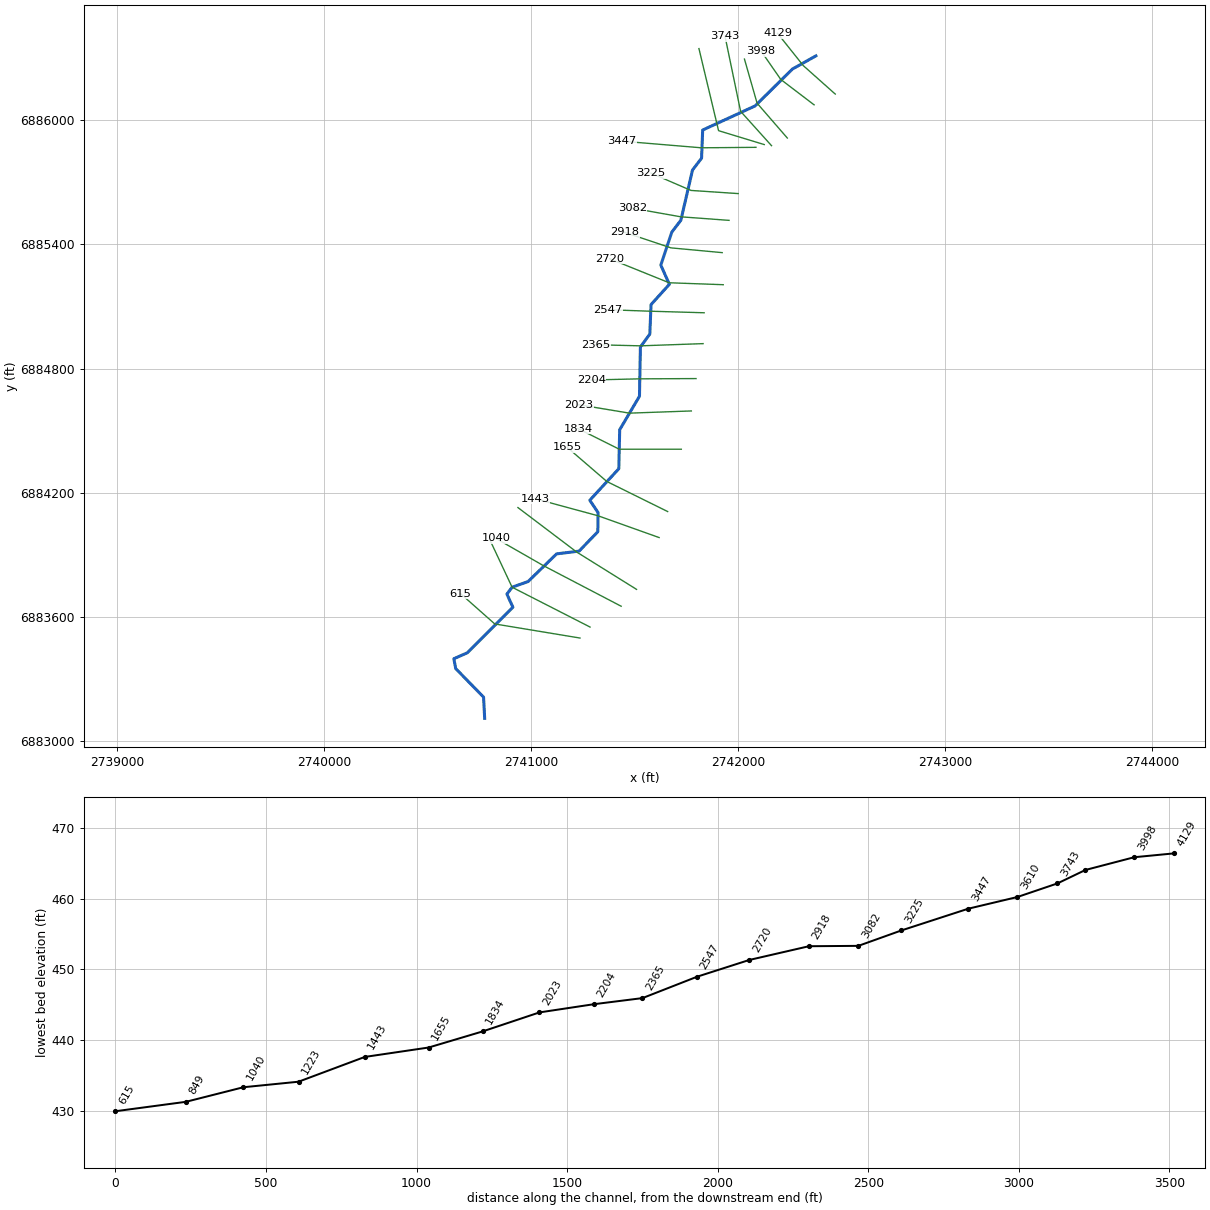
--- Lacy 085.prj (project) ---

Proj Title=Lacy 085 Base Level Engineering
Current Plan=p01
Default Exp/Contr=0.3,0.1
English Units
Geom File=g01
Flow File=f01
Plan File=p01
BEGIN DESCRIPTION:
Lacy 085
END DESCRIPTION:

--- Lacy 085.p01 (plan) ---

Plan Title=Multiple Run
Short Identifier=Multiple
Geom File=g01
Flow File=f01
Subcritical Flow
K Sum by GR= 0
Std Step Tol= 0.01
Critical Tol= 0.01
Num of Std Step Trials= 20
Max Error Tol= 0.3
Flow Tol Ratio= 0.001
Split Flow NTrial= 30
Split Flow Tol= 0.02
Split Flow Ratio= 0.02
Log Output Level= 0
Friction Slope Method= 1
Unsteady Friction Slope Method= 2
Unsteady Bridges Friction Slope Method= 1
Parabolic Critical Depth
Global Vel Dist=  1 , 1 , 1
Global Log Level= 0
CheckData=True
Encroach Param= -1, 0, 0, 0
BEGIN DESCRIPTION:
Multiple Run
END DESCRIPTION:

--- Lacy 085.f01 (steady flow) ---

Flow Title=Multiple
Number of Profiles=7
Profile Names=10-year,25-year,50-year,1pct_min,100-year,1pct_plu,500-year
River Rch & RM= Lacy 085,Reach-1,4129
     231     293     341     198     396     790     532
Boundary for River Rch & Prof#=Lacy 085,Reach-1,1
Up Type=0
Dn Type=3
Dn Slope=0.005
Boundary for River Rch & Prof#=Lacy 085,Reach-1,2
Up Type=0
Dn Type=3
Dn Slope=0.005
Boundary for River Rch & Prof#=Lacy 085,Reach-1,3
Up Type=0
Dn Type=3
Dn Slope=0.005
Boundary for River Rch & Prof#=Lacy 085,Reach-1,4
Up Type=0
Dn Type=3
Dn Slope=0.005
Boundary for River Rch & Prof#=Lacy 085,Reach-1,5
Up Type=0
Dn Type=3
Dn Slope=0.005
Boundary for River Rch & Prof#=Lacy 085,Reach-1,6
Up Type=0
Dn Type=3
Dn Slope=0.005
Boundary for River Rch & Prof#=Lacy 085,Reach-1,7
Up Type=0
Dn Type=3
Dn Slope=0.005

--- Lacy 085.g01 (geometry) ---

Geom Title=Existing Conditions

River Reach=Lacy 085,Reach-1
Reach XY= 30
      2742376.00      6886311.00      2742262.77      6886247.43
      2742082.06      6886069.14      2741829.07      6885952.72
      2741823.73      6885816.95      2741779.86      6885759.40
      2741723.65      6885516.97      2741679.85      6885459.40
      2741626.82      6885300.29      2741668.17      6885207.60
      2741579.57      6885109.53      2741573.73      6884966.94
      2741528.26      6884905.06      2741523.76      6884666.93
      2741428.24      6884505.07      2741423.94      6884316.85
      2741283.80      6884164.42      2741323.63      6884105.11
      2741322.54      6884012.49      2741232.19      6883918.86
      2741123.57      6883905.48      2740985.64      6883771.78
      2740908.47      6883744.35      2740883.47      6883711.21
      2740912.35      6883647.67      2740692.42      6883427.73
      2740627.12      6883398.97      2740636.06      6883351.58
      2740770.65      6883213.50      2740776.00      6883111.00

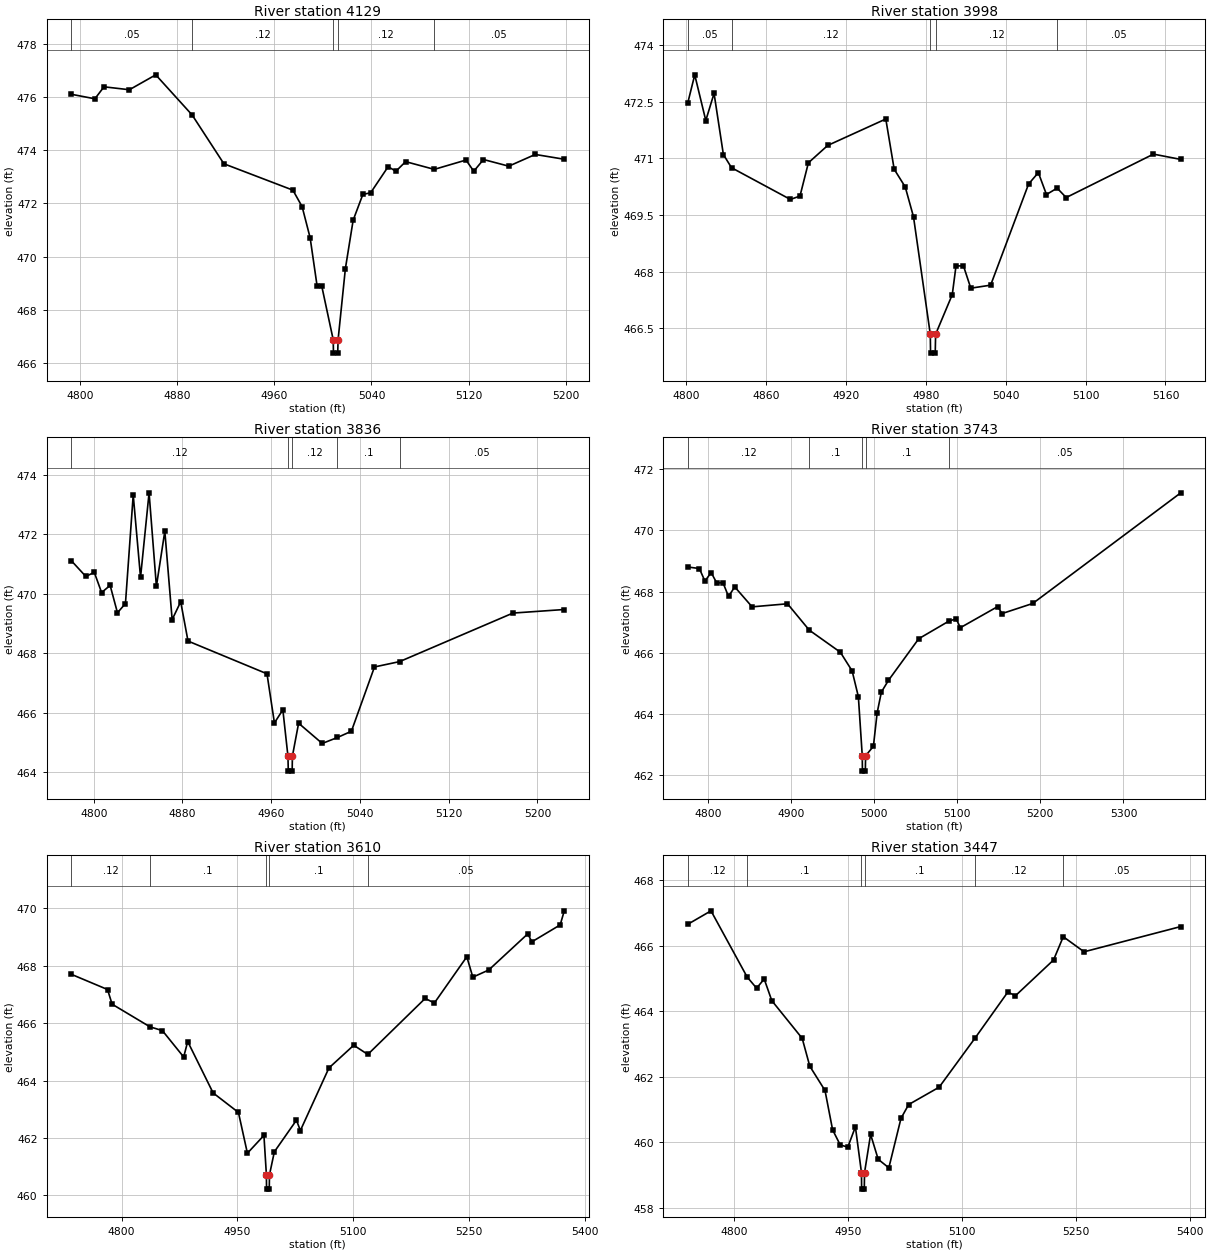
Type RM Length L Ch R = 1,4129,131,131,131
BEGIN DESCRIPTION:
Lacy 085 2031
END DESCRIPTION:
XS GIS Cut Line= 3
      2742469.36      6886126.58      2742315.39      6886263.56
      2742190.87      6886419.70
#Sta/Elev= 30
  4792.9  476.10  4812.3  475.93  4819.8  476.38  4840.7  476.27  4862.4  476.83
  4892.4  475.32  4918.5  473.49  4975.3  472.50  4982.9  471.88  4989.5  470.71
  4995.2  468.91  4999.0  468.91  5008.5  466.88  5008.7  466.38  5012.2  466.38
  5012.5  466.88  5018.5  469.55  5024.9  471.37  5032.9  472.34  5039.3  472.40
  5053.7  473.38  5060.1  473.21  5068.1  473.57  5091.7  473.28  5117.8  473.63
  5124.2  473.21  5132.2  473.65  5153.0  473.40  5174.8  473.84  5198.7  473.66
#Mann=5,-1,0
  4792.9    0.05       0  4892.4    0.12       0  5008.5    0.07       0
  5012.5    0.12       0  5091.7    0.05       0
Bank Sta=5008.5,5012.5
Exp/Cntr=0.3,0.1

Type RM Length L Ch R = 1,3998,162,162,162
BEGIN DESCRIPTION:
Lacy 085 2030
END DESCRIPTION:
XS GIS Cut Line= 3
      2742367.26      6886074.45      2742206.58      6886196.83
      2742110.68      6886334.80
#Sta/Elev= 30
  4801.5  472.47  4806.7  473.21  4815.0  472.00  4821.2  472.72  4828.2  471.10
  4834.3  470.75  4878.5  469.91  4885.7  470.00  4892.0  470.88  4906.5  471.34
  4950.1  472.04  4956.4  470.71  4964.7  470.24  4970.9  469.45  4983.5  466.34
  4983.7  465.84  4987.2  465.84  4987.5  466.34  5000.0  467.39  5002.8  468.15
  5008.4  468.15  5013.9  467.56  5028.8  467.64  5057.3  470.32  5064.6  470.62
  5070.7  470.04  5078.7  470.21  5085.5  469.96  5151.0  471.11  5171.5  470.97
#Mann=5,-1,0
  4801.5    0.05       0  4834.3    0.12       0  4983.5    0.07       0
  4987.5    0.12       0  5078.7    0.05       0
Bank Sta=4983.5,4987.5
Exp/Cntr=0.3,0.1

Type RM Length L Ch R = 1,3836,93,93,93
BEGIN DESCRIPTION:
Lacy 085 2029
END DESCRIPTION:
XS GIS Cut Line= 3
      2742237.87      6885914.17      2742091.91      6886082.38
      2742030.88      6886295.51
#Sta/Elev= 30
  4779.8  471.11  4792.9  470.58  4800.5  470.72  4807.1  470.04  4814.8  470.28
  4821.4  469.36  4828.6  469.67  4835.6  473.32  4842.2  470.55  4849.9  473.39
  4856.5  470.25  4864.1  472.10  4870.7  469.13  4878.4  469.73  4885.0  468.41
  4956.2  467.31  4962.9  465.66  4970.5  466.10  4975.1  464.54  4975.4  464.04
  4978.9  464.04  4979.1  464.54  4984.7  465.65  5006.0  464.97  5019.7  465.17
  5032.3  465.38  5053.1  467.54  5075.8  467.72  5177.9  469.35  5224.2  469.47
#Mann=5,-1,0
  4779.8    0.12       0  4975.1    0.07       0  4979.1    0.12       0
  5019.7     0.1       0  5075.8    0.05       0
Bank Sta=4975.1,4979.1
Exp/Cntr=0.3,0.1

Type RM Length L Ch R = 1,3743,133,133,133
BEGIN DESCRIPTION:
Lacy 085 2028
END DESCRIPTION:
XS GIS Cut Line= 3
      2742161.66      6885877.17      2742012.24      6886043.24
      2741936.99      6886405.51
#Sta/Elev= 30
  4775.6  468.80  4789.5  468.75  4796.2  468.34  4803.7  468.62  4810.4  468.28
  4817.9  468.29  4824.6  467.84  4832.1  468.15  4853.0  467.50  4895.6  467.60
  4921.8  466.74  4959.2  466.02  4973.4  465.41  4980.9  464.57  4985.6  462.64
  4985.8  462.14  4989.3  462.14  4989.6  462.64  4999.0  462.95  5003.5  464.04
  5008.6  464.72  5017.1  465.10  5053.6  466.46  5089.6  467.03  5098.6  467.11
  5103.7  466.82  5148.7  467.51  5153.8  467.28  5190.8  467.61  5369.0  471.22
#Mann=5,-1,0
  4775.6    0.12       0  4921.8     0.1       0  4985.6    0.07       0
  4989.6     0.1       0  5089.6    0.05       0
Bank Sta=4985.6,4989.6
Exp/Cntr=0.3,0.1

Type RM Length L Ch R = 1,3610,163,163,163
BEGIN DESCRIPTION:
Lacy 085 2024
END DESCRIPTION:
XS GIS Cut Line= 3
      2742126.51      6885882.54      2741905.82      6885949.68
      2741811.04      6886346.13
#Sta/Elev= 30
  4734.9  467.70  4781.8  467.17  4787.7  466.66  4836.8  465.87  4852.8  465.74
  4880.4  464.82  4885.6  465.36  4918.5  463.57  4951.3  462.89  4962.9  461.47
  4984.3  462.09  4987.5  460.72  4987.7  460.22  4991.2  460.22  4991.5  460.72
  4997.8  461.52  5026.4  462.62  5031.5  462.26  5068.5  464.44  5100.6  465.23
  5118.8  464.91  5193.1  466.86  5205.0  466.70  5247.0  468.31  5254.8  467.60
  5275.4  467.85  5326.0  469.11  5331.2  468.83  5367.9  469.42  5373.2  469.91
#Mann=5,-1,0
  4734.9    0.12       0  4836.8     0.1       0  4987.5    0.07       0
  4991.5     0.1       0  5118.8    0.05       0
Bank Sta=4987.5,4991.5
Exp/Cntr=0.3,0.1

Type RM Length L Ch R = 1,3447,222,222,222
BEGIN DESCRIPTION:
Lacy 085 2023
END DESCRIPTION:
XS GIS Cut Line= 3
      2742086.47      6885869.18      2741821.93      6885866.99
      2741439.21      6885899.03
#Sta/Elev= 30
  4739.6  466.65  4770.1  467.06  4817.7  465.04  4830.1  464.70  4840.1  464.98
  4850.1  464.32  4890.1  463.17  4900.1  462.32  4920.1  461.58  4930.1  460.38
  4940.1  459.92  4950.1  459.85  4960.1  460.47  4968.1  459.07  4968.3  458.57
  4971.8  458.57  4972.1  459.07  4980.1  460.24  4990.1  459.48  5004.1  459.22
  5020.1  460.73  5030.2  461.15  5070.3  461.68  5117.6  463.18  5160.6  464.58
  5170.7  464.47  5220.8  465.56  5233.6  466.27  5261.0  465.81  5388.2  466.58
#Mann=6,-1,0
  4739.6    0.12       0  4817.7     0.1       0  4968.1    0.07       0
  4972.1     0.1       0  5117.6    0.12       0  5233.6    0.05       0
Bank Sta=4968.1,4972.1
Exp/Cntr=0.3,0.1

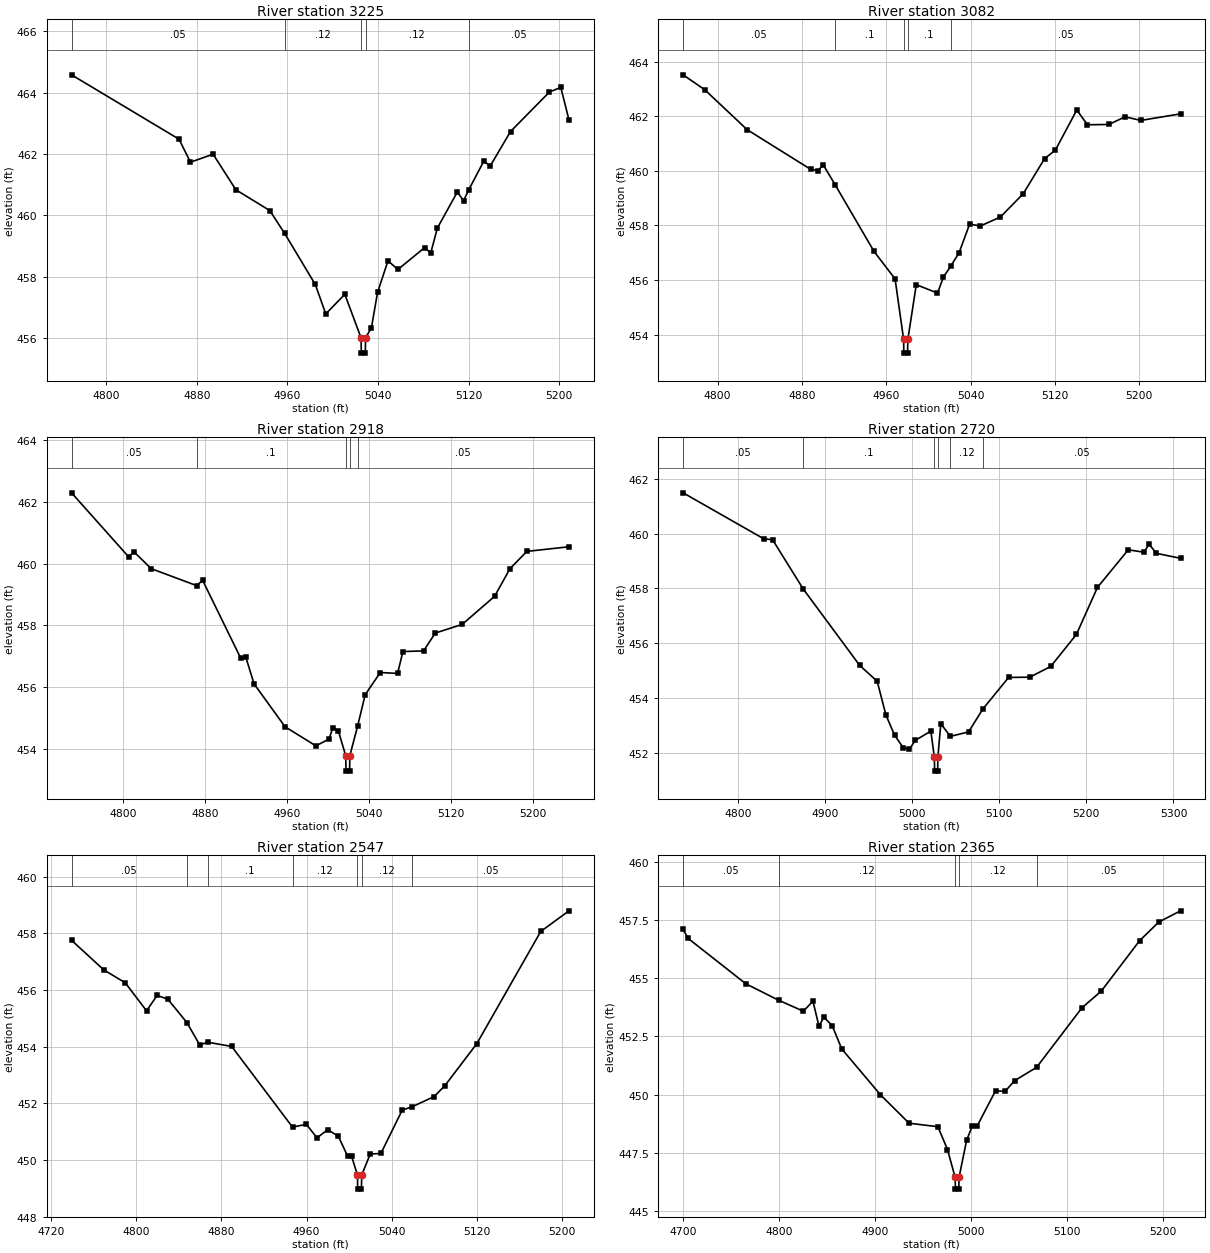
Type RM Length L Ch R = 1,3225,143,143,143
BEGIN DESCRIPTION:
Lacy 085 2027
END DESCRIPTION:
XS GIS Cut Line= 3
      2742000.74      6885645.78      2741772.53      6885661.02
      2741579.36      6885744.62
#Sta/Elev= 30
  4769.4  464.58  4864.3  462.48  4874.4  461.73  4894.4  461.99  4914.5  460.83
  4944.5  460.15  4957.5  459.41  4984.6  457.74  4993.9  456.78  5010.7  457.42
  5025.0  456.00  5025.3  455.50  5028.8  455.50  5029.0  456.00  5034.2  456.33
  5039.6  457.48  5048.8  458.51  5057.6  458.23  5081.1  458.94  5086.6  458.77
  5092.4  459.58  5110.1  460.76  5115.5  460.47  5120.0  460.82  5133.5  461.77
  5139.0  461.60  5157.0  462.73  5191.4  464.02  5201.4  464.17  5208.6  463.11
#Mann=5,-1,0
  4769.4    0.05       0  4957.5    0.12       0  5025.0    0.07       0
  5029.0    0.12       0  5120.0    0.05       0
Bank Sta=5025,5029
Exp/Cntr=0.3,0.1

Type RM Length L Ch R = 1,3082,164,164,164
BEGIN DESCRIPTION:
Lacy 085 2026
END DESCRIPTION:
XS GIS Cut Line= 3
      2741956.51      6885516.47      2741723.00      6885533.65
      2741489.11      6885575.25
#Sta/Elev= 30
  4767.4  463.52  4788.0  462.97  4828.1  461.51  4888.2  460.06  4895.3  460.01
  4900.3  460.22  4911.7  459.48  4948.4  457.05  4968.4  456.04  4976.5  453.82
  4976.7  453.32  4980.2  453.32  4980.5  453.82  4988.5  455.83  5008.6  455.52
  5014.3  456.11  5021.0  456.50  5029.0  456.99  5039.1  458.05  5049.3  457.98
  5068.3  458.31  5089.9  459.16  5110.2  460.45  5120.4  460.76  5140.7  462.23
  5150.8  461.69  5171.2  461.70  5186.3  461.98  5201.6  461.85  5239.1  462.09
#Mann=5,-1,0
  4767.4    0.05       0  4911.7     0.1       0  4976.5    0.07       0
  4980.5     0.1       0  5021.0    0.05       0
Bank Sta=4976.5,4980.5
Exp/Cntr=0.3,0.1

Type RM Length L Ch R = 1,2918,198,198,198
BEGIN DESCRIPTION:
Lacy 085 2025
END DESCRIPTION:
XS GIS Cut Line= 3
      2741923.37      6885360.54      2741675.76      6885383.58
      2741451.45      6885458.88
#Sta/Elev= 30
  4749.7  462.30  4805.5  460.22  4810.5  460.39  4827.4  459.84  4871.7  459.29
  4877.6  459.46  4914.7  456.94  4919.7  456.97  4927.8  456.10  4958.0  454.71
  4988.1  454.09  5000.9  454.31  5004.7  454.68  5010.0  454.58  5017.2  453.77
  5017.5  453.27  5021.0  453.27  5021.2  453.77  5028.8  454.73  5036.2  455.75
  5050.9  456.47  5067.8  456.44  5073.0  457.15  5093.1  457.17  5104.6  457.75
  5130.8  458.03  5162.4  458.94  5177.5  459.84  5193.9  460.40  5235.0  460.55
#Mann=5,-1,0
  4749.7    0.05       0  4871.7     0.1       0  5017.2    0.07       0
  5021.2     0.1       0  5028.8    0.05       0
Bank Sta=5017.2,5021.2
Exp/Cntr=0.3,0.1

Type RM Length L Ch R = 1,2720,173,173,173
BEGIN DESCRIPTION:
Lacy 085 2021
END DESCRIPTION:
XS GIS Cut Line= 3
      2741928.52      6885205.65      2741667.13      6885214.99
      2741380.40      6885330.82
#Sta/Elev= 30
  4737.3  461.49  4829.9  459.81  4839.9  459.78  4875.1  457.98  4939.9  455.19
  4960.0  454.61  4970.0  453.38  4980.0  452.64  4990.0  452.18  4996.9  452.12
  5003.5  452.45  5021.6  452.79  5025.6  451.83  5025.9  451.33  5029.4  451.33
  5029.6  451.83  5033.0  453.06  5044.0  452.60  5064.8  452.76  5081.3  453.60
  5110.8  454.75  5135.0  454.76  5159.1  455.15  5188.6  456.32  5212.8  458.04
  5248.1  459.41  5266.4  459.32  5271.8  459.62  5280.5  459.28  5308.1  459.10
#Mann=6,-1,0
  4737.3    0.05       0  4875.1     0.1       0  5025.6    0.07       0
  5029.6     0.1       0  5044.0    0.12       0  5081.3    0.05       0
Bank Sta=5025.6,5029.6
Exp/Cntr=0.3,0.1

Type RM Length L Ch R = 1,2547,182,182,182
BEGIN DESCRIPTION:
Lacy 085 2020
END DESCRIPTION:
XS GIS Cut Line= 3
      2741836.38      6885070.10      2741573.58      6885077.68
      2741369.52      6885084.84
#Sta/Elev= 30
  4739.3  457.76  4769.7  456.71  4789.7  456.26  4809.7  455.27  4819.7  455.81
  4829.7  455.68  4847.7  454.85  4859.7  454.06  4867.0  454.16  4889.7  454.01
  4946.8  451.16  4959.8  451.26  4969.8  450.78  4979.8  451.07  4989.8  450.84
  4998.5  450.14  5002.2  450.14  5007.8  449.47  5008.0  448.97  5011.5  448.97
  5011.8  449.47  5019.8  450.21  5029.8  450.23  5049.8  451.76  5059.2  451.88
  5079.8  452.24  5089.8  452.62  5119.9  454.11  5179.9  458.07  5206.4  458.80
#Mann=7,-1,0
  4739.3    0.05       0  4847.7    0.12       0  4867.0     0.1       0
  4946.8    0.12       0  5007.8    0.07       0  5011.8    0.12       0
  5059.2    0.05       0
Bank Sta=5007.8,5011.8
Exp/Cntr=0.3,0.1

Type RM Length L Ch R = 1,2365,161,161,161
BEGIN DESCRIPTION:
Lacy 085 2019
END DESCRIPTION:
XS GIS Cut Line= 3
      2741831.14      6884921.04      2741529.16      6884910.36
      2741313.39      6884915.60
#Sta/Elev= 30
  4699.9  457.10  4705.0  456.71  4765.1  454.76  4799.4  454.05  4825.1  453.58
  4835.1  454.01  4841.4  452.93  4846.4  453.33  4855.1  452.96  4865.1  451.96
  4905.2  450.00  4935.2  448.77  4965.2  448.62  4975.2  447.64  4983.2  446.44
  4983.5  445.94  4987.0  445.94  4987.2  446.44  4995.2  448.05  5001.1  448.65
  5006.1  448.65  5025.2  450.16  5035.2  450.14  5045.2  450.60  5068.0  451.17
  5115.3  453.73  5135.3  454.44  5175.3  456.61  5195.3  457.41  5217.9  457.89
#Mann=5,-1,0
  4699.9    0.05       0  4799.4    0.12       0  4983.2    0.07       0
  4987.2    0.12       0  5068.0    0.05       0
Bank Sta=4983.2,4987.2
Exp/Cntr=0.3,0.1

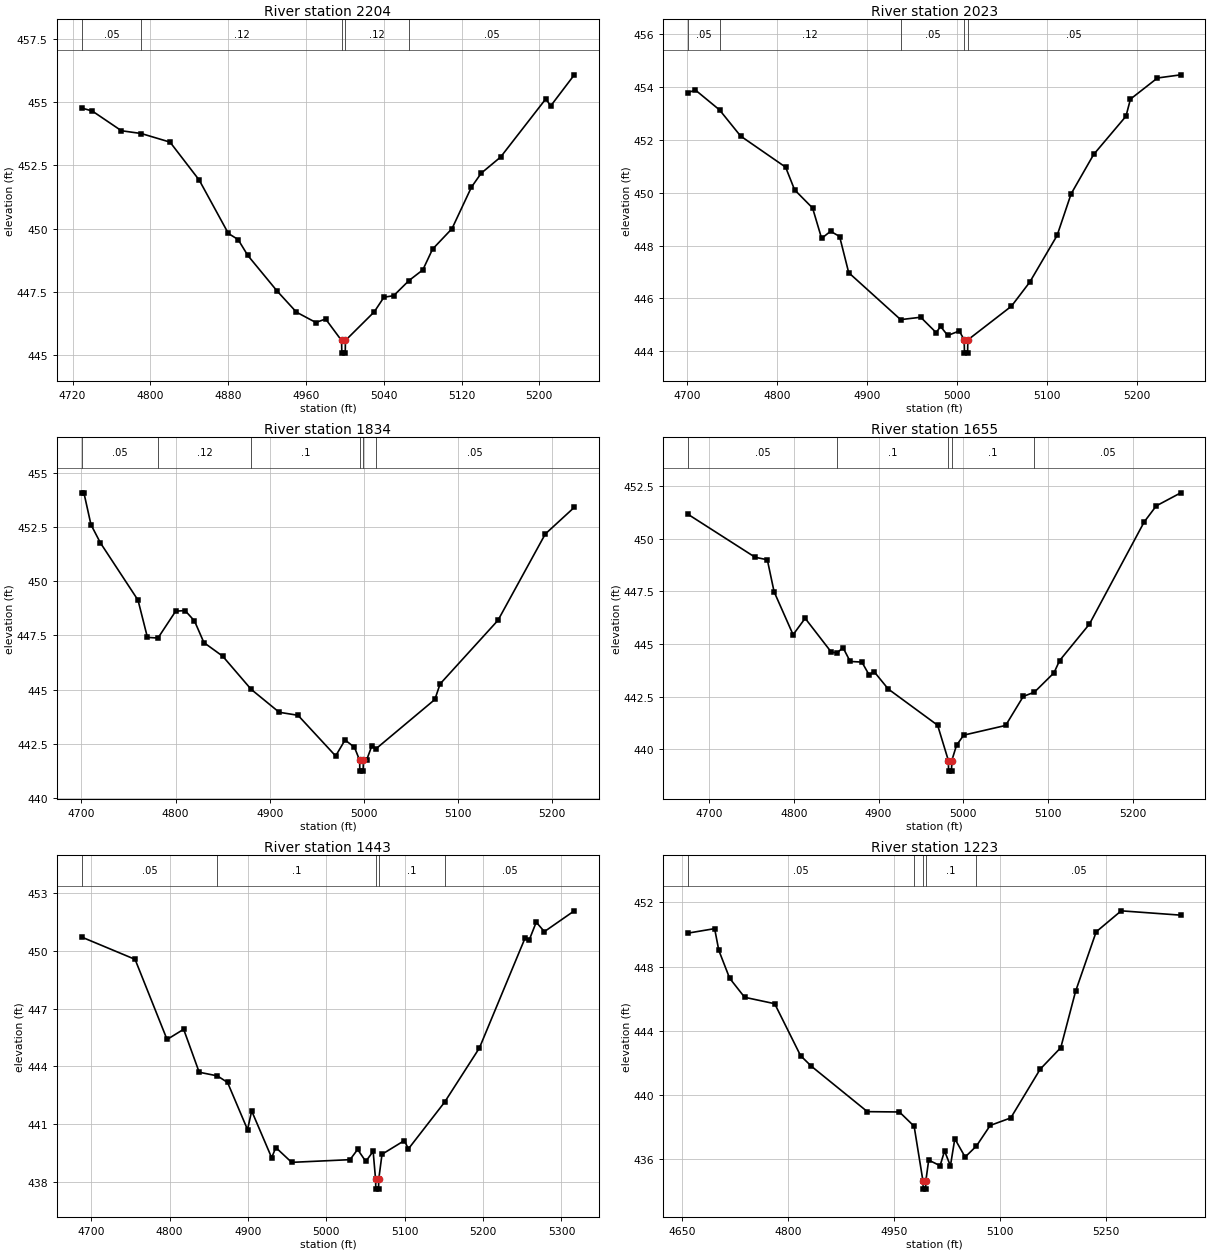
Type RM Length L Ch R = 1,2204,181,181,181
BEGIN DESCRIPTION:
Lacy 085 2018
END DESCRIPTION:
XS GIS Cut Line= 3
      2741797.00      6884752.24      2741524.17      6884750.92
      2741290.27      6884745.34
#Sta/Elev= 30
  4729.2  454.77  4740.2  454.65  4770.2  453.87  4790.6  453.76  4820.2  453.42
  4850.2  451.92  4880.2  449.81  4890.2  449.57  4900.2  448.94  4930.2  447.54
  4950.2  446.70  4970.2  446.29  4980.2  446.43  4996.6  445.58  4996.9  445.08
  5000.4  445.08  5000.6  445.58  5030.2  446.71  5040.2  447.29  5050.2  447.35
  5066.0  447.95  5080.2  448.37  5090.2  449.19  5110.2  450.00  5130.2  451.64
  5140.2  452.19  5160.2  452.83  5206.7  455.13  5211.7  454.85  5236.0  456.08
#Mann=5,-1,0
  4729.2    0.05       0  4790.6    0.12       0  4996.6    0.07       0
  5000.6    0.12       0  5066.0    0.05       0
Bank Sta=4996.6,5000.6
Exp/Cntr=0.3,0.1

Type RM Length L Ch R = 1,2023,189,189,189
BEGIN DESCRIPTION:
Lacy 085 2017
END DESCRIPTION:
XS GIS Cut Line= 3
      2741774.34      6884595.84      2741475.31      6884585.23
      2741230.49      6884625.93
#Sta/Elev= 30
  4701.3  453.80  4709.6  453.89  4736.3  453.14  4759.7  452.15  4809.7  450.97
  4819.7  450.11  4839.7  449.42  4849.7  448.27  4859.7  448.54  4869.7  448.34
  4879.8  446.97  4937.5  445.19  4959.8  445.28  4976.9  444.70  4981.9  444.93
  4989.8  444.59  5002.7  444.76  5008.1  444.42  5008.4  443.92  5011.9  443.92
  5012.1  444.42  5060.6  445.70  5080.9  446.61  5111.3  448.38  5126.9  449.96
  5151.9  451.45  5187.8  452.90  5192.8  453.55  5222.8  454.35  5248.7  454.47
#Mann=5,-1,0
  4701.3    0.05       0  4736.3    0.12       0  4937.5    0.05       0
  5008.1    0.04       0  5012.1    0.05       0
Bank Sta=5008.1,5012.1
Exp/Cntr=0.3,0.1

Type RM Length L Ch R = 1,1834,179,179,179
BEGIN DESCRIPTION:
Lacy 085 71
END DESCRIPTION:
XS GIS Cut Line= 3
      2741725.98      6884411.00      2741426.00      6884411.00
      2741225.99      6884511.01
#Sta/Elev= 30
  4700.1  454.09  4702.6  454.09  4710.1  452.62  4720.1  451.78  4760.1  449.13
  4770.1  447.41  4781.3  447.38  4800.1  448.62  4810.1  448.65  4820.1  448.17
  4830.1  447.17  4850.1  446.54  4880.3  445.01  4910.1  443.95  4930.1  443.81
  4970.1  441.93  4980.1  442.67  4990.1  442.33  4995.6  441.73  4995.8  441.23
  4999.3  441.23  4999.6  441.73  5002.9  441.73  5008.5  442.39  5012.9  442.26
  5075.5  444.54  5081.1  445.26  5142.6  448.20  5192.9  452.19  5223.7  453.42
#Mann=6,-1,0
  4700.1    0.05       0  4781.3    0.12       0  4880.3     0.1       0
  4995.6    0.07       0  4999.6     0.1       0  5012.9    0.05       0
Bank Sta=4995.6,4999.6
Exp/Cntr=0.3,0.1

Type RM Length L Ch R = 1,1655,212,212,212
BEGIN DESCRIPTION:
Lacy 085 2016
END DESCRIPTION:
XS GIS Cut Line= 3
      2741659.80      6884109.93      2741365.82      6884255.31
      2741174.09      6884420.44
#Sta/Elev= 30
  4675.3  451.16  4754.4  449.12  4768.8  449.00  4776.8  447.48  4799.2  445.44
  4813.4  446.22  4844.1  444.62  4851.0  444.57  4858.0  444.83  4866.5  444.17
  4880.3  444.14  4889.0  443.52  4894.6  443.69  4911.4  442.86  4969.6  441.14
  4982.3  439.46  4982.5  438.96  4986.0  438.96  4986.3  439.46  4991.9  440.19
  5000.4  440.67  5049.8  441.13  5070.6  442.51  5083.7  442.71  5106.8  443.63
  5113.4  444.21  5148.5  445.94  5213.2  450.80  5227.4  451.56  5256.3  452.18
#Mann=5,-1,0
  4675.3    0.05       0  4851.0     0.1       0  4982.3    0.07       0
  4986.3     0.1       0  5083.7    0.05       0
Bank Sta=4982.3,4986.3
Exp/Cntr=0.3,0.1

Type RM Length L Ch R = 1,1443,220,220,220
BEGIN DESCRIPTION:
Lacy 085 2015
END DESCRIPTION:
XS GIS Cut Line= 3
      2741618.73      6883984.28      2741322.83      6884089.76
      2741019.11      6884171.99
#Sta/Elev= 30
  4687.6  450.72  4755.9  449.56  4796.7  445.40  4817.9  445.93  4837.7  443.70
  4860.9  443.51  4873.9  443.17  4899.4  440.72  4904.7  441.69  4930.2  439.26
  4935.5  439.79  4955.7  439.02  5030.2  439.16  5039.9  439.69  5050.3  439.07
  5059.7  439.59  5062.8  438.13  5063.1  437.63  5066.6  437.63  5066.8  438.13
  5071.0  439.44  5099.5  440.15  5104.7  439.72  5150.8  442.14  5195.3  444.96
  5253.7  450.68  5258.9  450.57  5267.8  451.49  5278.2  451.00  5316.4  452.08
#Mann=5,-1,0
  4687.6    0.05       0  4860.9     0.1       0  5062.8    0.07       0
  5066.8     0.1       0  5150.8    0.05       0
Bank Sta=5062.8,5066.8
Exp/Cntr=0.3,0.1

Type RM Length L Ch R = 1,1223,183,183,183
BEGIN DESCRIPTION:
Lacy 085 2014
END DESCRIPTION:
XS GIS Cut Line= 3
      2741509.54      6883734.03      2741220.65      6883914.15
      2740936.75      6884129.05
#Sta/Elev= 30
  4658.7  450.09  4696.3  450.37  4702.2  449.02  4717.5  447.28  4738.7  446.09
  4781.2  445.69  4817.8  442.45  4833.1  441.79  4912.2  438.96  4957.5  438.94
  4978.3  438.05  4990.8  434.63  4991.1  434.13  4994.6  434.13  4994.8  434.63
  4998.9  435.94  5015.0  435.59  5021.3  436.51  5029.6  435.58  5035.8  437.27
  5050.4  436.13  5066.4  436.82  5085.8  438.10  5114.9  438.57  5156.5  441.61
  5185.6  442.95  5206.5  446.46  5235.6  450.17  5271.0  451.48  5355.2  451.21
#Mann=5,-1,0
  4658.7    0.05       0  4978.3     0.1       0  4990.8    0.07       0
  4994.8     0.1       0  5066.4    0.05       0
Bank Sta=4990.8,4994.8
Exp/Cntr=0.3,0.1

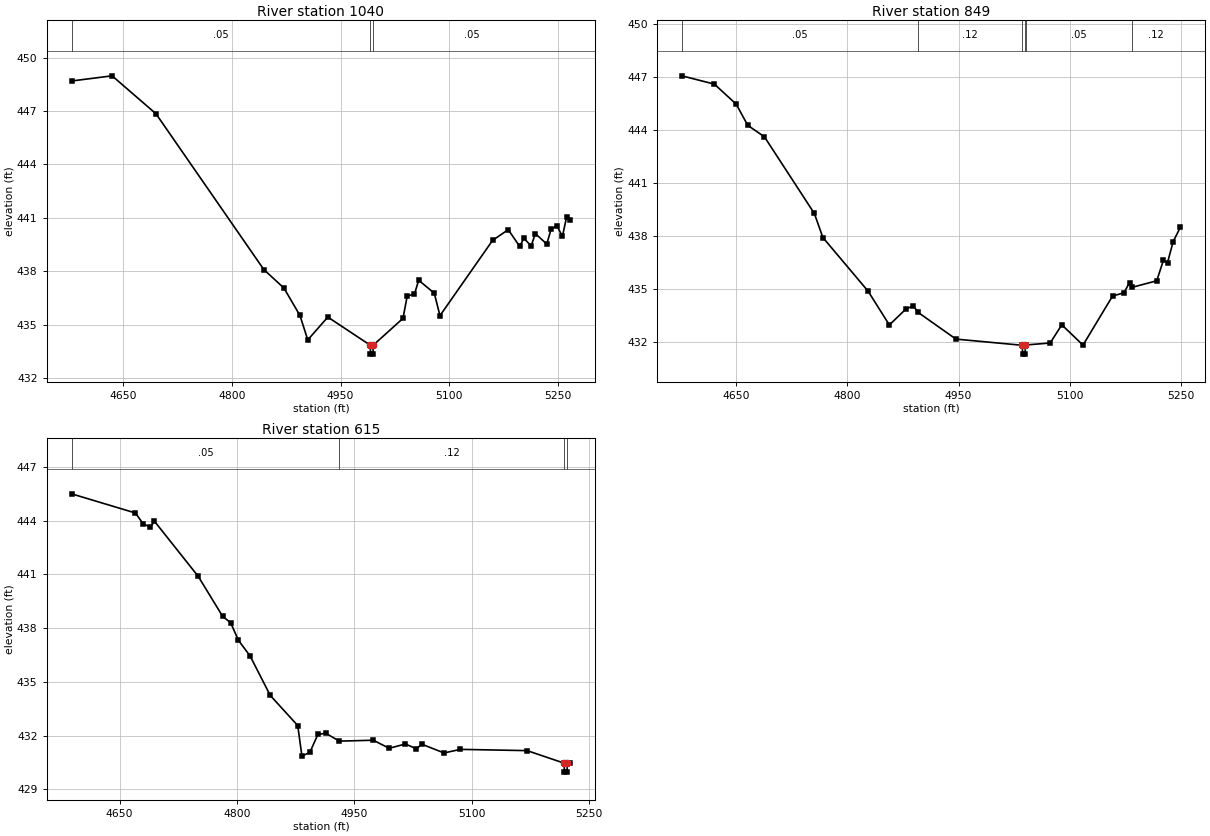
Type RM Length L Ch R = 1,1040,191,191,191
BEGIN DESCRIPTION:
Lacy 085 2013
END DESCRIPTION:
XS GIS Cut Line= 3
      2741435.20      6883652.59      2741060.85      6883847.99
      2740829.88      6883980.37
#Sta/Elev= 30
  4578.7  448.69  4634.6  448.98  4695.2  446.85  4844.1  438.10  4871.9  437.06
  4894.0  435.52  4904.8  434.15  4932.5  435.43  4991.1  433.85  4991.4  433.35
  4994.9  433.35  4995.1  433.85  5036.3  435.36  5042.1  436.62  5052.1  436.72
  5057.9  437.50  5079.5  436.77  5087.3  435.51  5160.0  439.74  5181.6  440.34
  5197.4  439.40  5203.2  439.86  5213.2  439.42  5219.0  440.12  5234.8  439.53
  5240.6  440.35  5248.6  440.57  5256.4  439.96  5262.2  441.06  5267.2  440.89
#Mann=3,-1,0
  4578.7    0.05       0  4991.1    0.05       0  4995.1    0.05       0
Bank Sta=4991.1,4995.1
Exp/Cntr=0.3,0.1

Type RM Length L Ch R = 1,849,234,234,234
BEGIN DESCRIPTION:
Lacy 085 2012
END DESCRIPTION:
XS GIS Cut Line= 3
      2741285.09      6883551.99      2740908.47      6883744.35
      2740802.66      6883969.97
#Sta/Elev= 30
  4577.1  447.04  4621.0  446.57  4650.5  445.43  4665.9  444.24  4688.4  443.59
  4755.7  439.25  4767.2  437.89  4828.2  434.85  4856.8  432.94  4879.3  433.85
  4889.3  434.02  4895.6  433.65  4946.6  432.14  5036.1  431.79  5036.3  431.29
  5039.8  431.29  5040.1  431.79  5041.2  431.81  5073.6  431.92  5089.2  432.95
  5117.8  431.80  5157.7  434.58  5173.0  434.76  5180.5  435.34  5183.9  435.07
  5217.2  435.44  5226.1  436.59  5231.7  436.46  5239.3  437.66  5249.2  438.48
#Mann=6,-1,0
  4577.1    0.05       0  4895.6    0.12       0  5036.1    0.07       0
  5040.1    0.12       0  5041.2    0.05       0  5183.9    0.12       0
Bank Sta=5036.1,5040.1
Exp/Cntr=0.3,0.1

Type RM Length L Ch R = 1,615,0,0,0
BEGIN DESCRIPTION:
Lacy 085 2011
END DESCRIPTION:
XS GIS Cut Line= 3
      2741236.47      6883498.89      2740824.79      6883566.98
      2740660.08      6883712.86
#Sta/Elev= 30
  4588.7  445.49  4670.3  444.42  4680.4  443.80  4689.5  443.64  4694.6  443.96
  4750.6  440.88  4781.8  438.65  4791.9  438.30  4802.0  437.31  4816.7  436.45
  4842.6  434.24  4877.7  432.56  4883.1  430.85  4893.3  431.07  4903.4  432.06
  4913.5  432.13  4930.9  431.69  4974.3  431.74  4994.6  431.29  5015.3  431.53
  5029.5  431.26  5036.2  431.52  5064.7  431.03  5085.6  431.23  5170.9  431.16
  5218.2  430.46  5218.5  429.96  5222.0  429.96  5222.2  430.46  5226.0  430.49
#Mann=4,-1,0
  4588.7    0.05       0  4930.9    0.12       0  5218.2    0.07       0
  5222.2    0.12       0
Bank Sta=5218.2,5222.2
Exp/Cntr=0.3,0.1

Chan Stop Cuts=-1