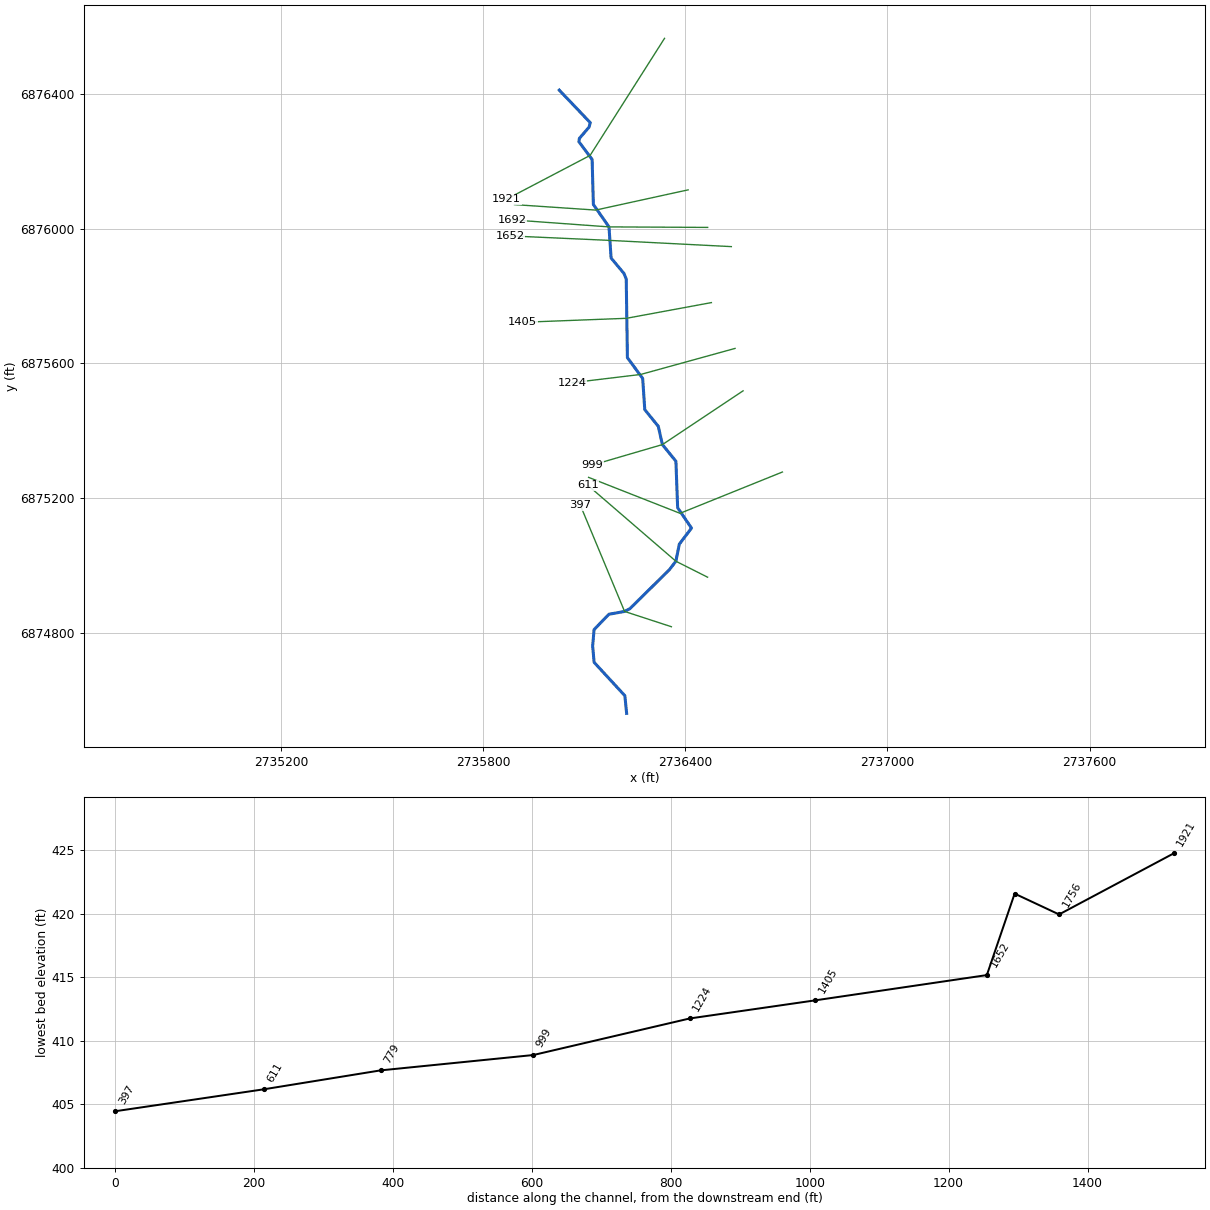
--- Lacy 086.prj (project) ---

Proj Title=Lacy 086 Base Level Engineering
Current Plan=p01
Default Exp/Contr=0.3,0.1
English Units
Geom File=g01
Flow File=f01
Plan File=p01
BEGIN DESCRIPTION:
Lacy 086
END DESCRIPTION:

--- Lacy 086.p01 (plan) ---

Plan Title=Multiple Run
Short Identifier=Multiple
Geom File=g01
Flow File=f01
Subcritical Flow
K Sum by GR= 0
Std Step Tol= 0.01
Critical Tol= 0.01
Num of Std Step Trials= 20
Max Error Tol= 0.3
Flow Tol Ratio= 0.001
Split Flow NTrial= 30
Split Flow Tol= 0.02
Split Flow Ratio= 0.02
Log Output Level= 0
Friction Slope Method= 1
Unsteady Friction Slope Method= 2
Unsteady Bridges Friction Slope Method= 1
Parabolic Critical Depth
Global Vel Dist=  1 , 1 , 1
Global Log Level= 0
CheckData=True
Encroach Param= -1, 0, 0, 0
BEGIN DESCRIPTION:
Multiple Run
END DESCRIPTION:

--- Lacy 086.f01 (steady flow) ---

Flow Title=Multiple
Number of Profiles=7
Profile Names=10-year,25-year,50-year,1pct_min,100-year,1pct_plu,500-year
River Rch & RM= Lacy 086,Reach-1,1921
     192     236     269     153     305     609     391
Boundary for River Rch & Prof#=Lacy 086,Reach-1,1
Up Type=0
Dn Type=3
Dn Slope=0.005
Boundary for River Rch & Prof#=Lacy 086,Reach-1,2
Up Type=0
Dn Type=3
Dn Slope=0.005
Boundary for River Rch & Prof#=Lacy 086,Reach-1,3
Up Type=0
Dn Type=3
Dn Slope=0.005
Boundary for River Rch & Prof#=Lacy 086,Reach-1,4
Up Type=0
Dn Type=3
Dn Slope=0.005
Boundary for River Rch & Prof#=Lacy 086,Reach-1,5
Up Type=0
Dn Type=3
Dn Slope=0.005
Boundary for River Rch & Prof#=Lacy 086,Reach-1,6
Up Type=0
Dn Type=3
Dn Slope=0.005
Boundary for River Rch & Prof#=Lacy 086,Reach-1,7
Up Type=0
Dn Type=3
Dn Slope=0.005

--- Lacy 086.g01 (geometry) ---

Geom Title=Existing Conditions

River Reach=Lacy 086,Reach-1
Reach XY= 30
      2736026.00      6876411.00      2736118.11      6876314.34
      2736114.33      6876301.01      2736085.77      6876267.74
      2736084.28      6876257.79      2736123.54      6876205.14
      2736127.23      6876071.51      2736173.64      6876005.02
      2736179.86      6875912.60      2736217.86      6875867.06
      2736224.78      6875850.50      2736228.26      6875616.94
      2736273.64      6875555.02      2736279.83      6875462.58
      2736319.89      6875413.18      2736332.12      6875358.82
      2736372.24      6875309.44      2736377.40      6875171.44
      2736418.47      6875110.99      2736382.41      6875063.28
      2736372.09      6875012.65      2736353.00      6874987.53
      2736235.66      6874871.79      2736219.91      6874863.55
      2736173.42      6874855.26      2736129.37      6874809.72
      2736125.11      6874761.03      2736129.45      6874712.50
      2736220.67      6874613.51      2736226.00      6874561.00

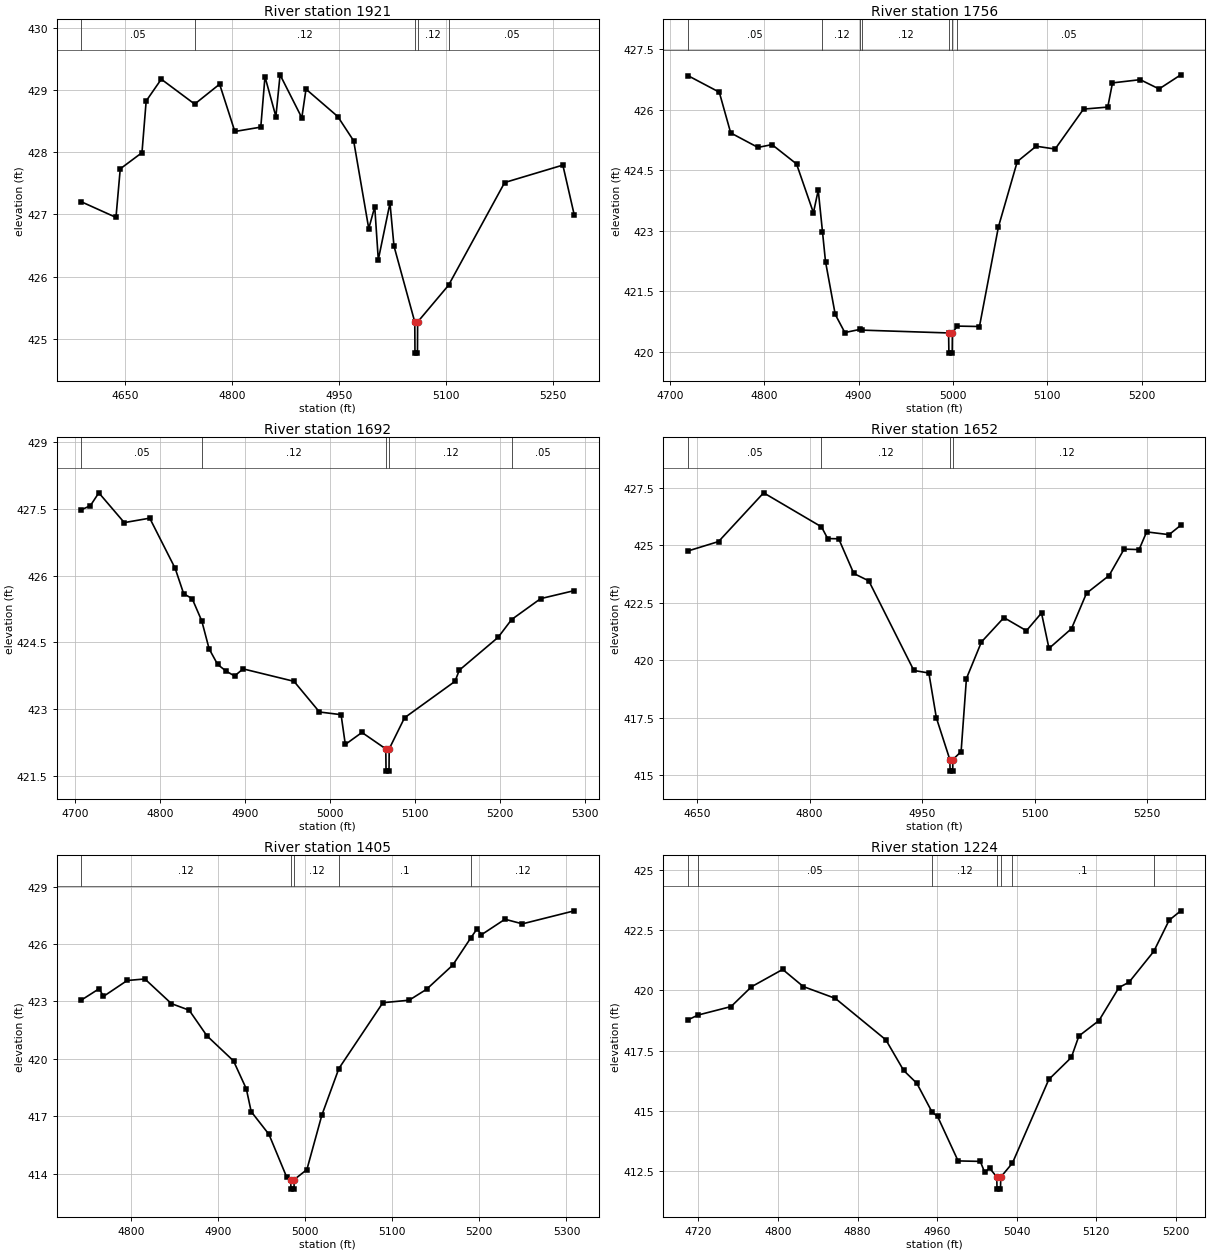
Type RM Length L Ch R = 1,1921,165,165,165
BEGIN DESCRIPTION:
Lacy 086 1981
END DESCRIPTION:
XS GIS Cut Line= 3
      2736338.47      6876564.72      2736117.56      6876217.19
      2735869.45      6876087.19
#Sta/Elev= 30
  4588.2  427.20  4636.7  426.95  4642.7  427.73  4673.2  427.99  4679.1  428.82
  4700.3  429.17  4747.2  428.77  4782.2  429.09  4803.6  428.33  4840.0  428.40
  4845.9  429.21  4861.2  428.57  4867.1  429.24  4897.6  428.55  4903.5  429.01
  4948.1  428.57  4970.4  428.18  4991.6  426.77  5000.0  427.12  5005.0  426.27
  5021.4  427.18  5027.0  426.49  5056.2  425.27  5056.5  424.77  5060.0  424.77
  5060.2  425.27  5103.6  425.86  5182.4  427.51  5264.1  427.79  5280.1  426.99
#Mann=5,-1,0
  4588.2    0.05       0  4747.2    0.12       0  5056.2    0.07       0
  5060.2    0.12       0  5103.6    0.05       0
Bank Sta=5056.2,5060.2
Exp/Cntr=0.3,0.1

Type RM Length L Ch R = 1,1756,64,64,64
BEGIN DESCRIPTION:
Lacy 086 1980
END DESCRIPTION:
XS GIS Cut Line= 3
      2736408.45      6876114.97      2736134.14      6876054.94
      2735893.09      6876071.14
#Sta/Elev= 30
  4719.2  426.84  4752.4  426.43  4764.5  425.42  4793.4  425.06  4808.3  425.13
  4834.3  424.65  4852.2  423.44  4857.3  424.00  4861.8  422.97  4865.0  422.23
  4875.3  420.92  4885.5  420.47  4901.9  420.55  4904.1  420.53  4995.5  420.46
  4995.8  419.96  4999.3  419.96  4999.5  420.46  5004.7  420.63  5028.2  420.62
  5048.3  423.09  5068.3  424.71  5088.3  425.09  5108.4  425.02  5138.5  426.01
  5164.2  426.06  5169.2  426.66  5198.6  426.74  5218.6  426.51  5241.6  426.86
#Mann=7,-1,0
  4719.2    0.05       0  4861.8    0.12       0  4901.9    0.05       0
  4904.1    0.12       0  4995.5    0.07       0  4999.5    0.12       0
  5004.7    0.05       0
Bank Sta=4995.5,4999.5
Exp/Cntr=0.3,0.1

Type RM Length L Ch R = 1,1692,40,40,40
BEGIN DESCRIPTION:
Lacy 086 1979
END DESCRIPTION:
XS GIS Cut Line= 3
      2736466.54      6876003.49      2736173.64      6876005.02
      2735886.50      6876025.85
#Sta/Elev= 30
  4707.1  427.48  4717.6  427.57  4727.6  427.86  4757.6  427.19  4787.6  427.29
  4817.6  426.16  4827.6  425.59  4837.6  425.48  4848.9  424.98  4857.6  424.35
  4867.6  424.00  4877.6  423.85  4887.6  423.74  4897.6  423.90  4957.6  423.62
  4987.6  422.93  5013.1  422.87  5018.1  422.20  5037.7  422.47  5065.8  422.10
  5066.1  421.60  5069.6  421.60  5069.8  422.10  5087.9  422.80  5147.4  423.62
  5152.4  423.87  5198.2  424.61  5214.1  425.01  5248.3  425.48  5287.9  425.66
#Mann=5,-1,0
  4707.1    0.05       0  4848.9    0.12       0  5065.8    0.07       0
  5069.8    0.12       0  5214.1    0.05       0
Bank Sta=5065.8,5069.8
Exp/Cntr=0.3,0.1

Type RM Length L Ch R = 1,1652,247,247,247
BEGIN DESCRIPTION:
Lacy 086 1972
END DESCRIPTION:
XS GIS Cut Line= 3
      2736536.78      6875946.47      2736175.05      6875964.98
      2735880.45      6875978.27
#Sta/Elev= 30
  4637.8  424.76  4678.6  425.17  4738.7  427.29  4815.8  425.81  4824.1  425.30
  4838.8  425.29  4858.9  423.78  4878.9  423.46  4939.0  419.56  4959.0  419.45
  4969.0  417.50  4987.0  415.68  4987.3  415.18  4990.8  415.18  4991.0  415.68
  5002.0  416.03  5009.1  419.21  5029.1  420.80  5059.1  421.86  5089.1  421.29
  5109.2  422.06  5119.2  420.52  5149.2  421.38  5169.2  422.92  5199.3  423.69
  5219.3  424.84  5239.3  424.82  5249.4  425.59  5279.3  425.47  5294.9  425.88
#Mann=4,-1,0
  4637.8    0.05       0  4815.8    0.12       0  4987.0    0.07       0
  4991.0    0.12       0
Bank Sta=4987,4991
Exp/Cntr=0.3,0.1

Type RM Length L Ch R = 1,1405,181,181,181
BEGIN DESCRIPTION:
Lacy 086 1978
END DESCRIPTION:
XS GIS Cut Line= 3
      2736477.59      6875780.30      2736225.26      6875733.66
      2735916.59      6875721.85
#Sta/Elev= 30
  4743.4  423.07  4763.7  423.66  4768.7  423.26  4795.9  424.09  4816.2  424.17
  4846.7  422.88  4867.0  422.54  4887.4  421.20  4917.9  419.89  4932.6  418.43
  4938.2  417.24  4958.6  416.05  4978.9  413.82  4983.6  413.69  4983.8  413.19
  4987.3  413.19  4987.6  413.69  5002.1  414.21  5019.3  417.06  5038.8  419.49
  5089.3  422.93  5119.4  423.06  5139.4  423.63  5169.4  424.89  5190.1  426.31
  5197.4  426.79  5202.4  426.48  5229.4  427.29  5249.4  427.05  5308.9  427.73
#Mann=5,-1,0
  4743.4    0.12       0  4983.6    0.07       0  4987.6    0.12       0
  5038.8     0.1       0  5190.1    0.12       0
Bank Sta=4983.6,4987.6
Exp/Cntr=0.3,0.1

Type RM Length L Ch R = 1,1224,225,225,225
BEGIN DESCRIPTION:
Lacy 086 1977
END DESCRIPTION:
XS GIS Cut Line= 3
      2736547.75      6875644.28      2736267.81      6875567.03
      2736064.38      6875542.54
#Sta/Elev= 30
  4709.6  418.78  4719.9  418.98  4752.9  419.33  4773.4  420.15  4804.8  420.87
  4825.5  420.16  4857.7  419.67  4908.5  417.95  4926.4  416.68  4939.6  416.15
  4955.0  414.95  4960.4  414.78  4981.1  412.93  5003.4  412.91  5007.8  412.46
  5012.8  412.63  5020.0  412.26  5020.2  411.76  5023.7  411.76  5024.0  412.26
  5035.7  412.84  5072.3  416.31  5094.9  417.22  5102.5  418.11  5122.7  418.75
  5142.8  420.12  5152.9  420.34  5177.8  421.62  5193.2  422.91  5204.9  423.30
#Mann=7,-1,0
  4709.6    0.12       0  4719.9    0.05       0  4955.0    0.12       0
  5020.0    0.07       0  5024.0    0.12       0  5035.7     0.1       0
  5177.8    0.12       0
Bank Sta=5020,5024
Exp/Cntr=0.3,0.1

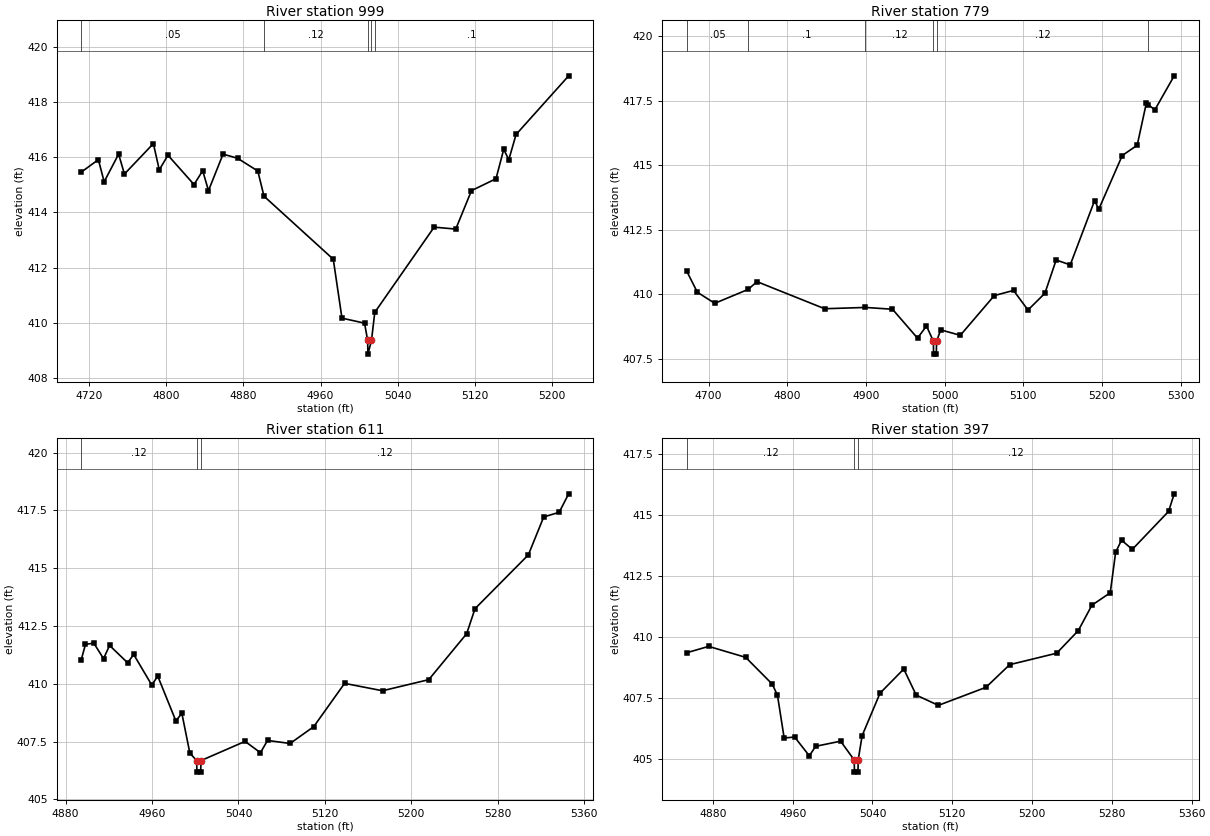
Type RM Length L Ch R = 1,999,220,220,220
BEGIN DESCRIPTION:
Lacy 086 1976
END DESCRIPTION:
XS GIS Cut Line= 3
      2736571.72      6875518.43      2736332.12      6875358.82
      2736123.73      6875297.93
#Sta/Elev= 30
  4712.1  415.46  4729.8  415.91  4735.8  415.11  4750.8  416.11  4756.8  415.39
  4786.8  416.49  4792.9  415.54  4801.9  416.07  4828.9  415.01  4837.9  415.51
  4843.9  414.79  4859.0  416.11  4874.0  415.96  4895.0  415.50  4901.4  414.59
  4973.2  412.31  4982.2  410.18  5005.6  410.00  5008.8  409.38  5009.1  408.88
  5012.8  409.38  5016.2  410.39  5077.7  413.47  5100.1  413.40  5116.4  414.79
  5141.8  415.22  5149.8  416.28  5155.1  415.91  5162.6  416.82  5217.1  418.94
#Mann=5,-1,0
  4712.1    0.05       0  4901.4    0.12       0  5008.8    0.07       0
  5012.8    0.12       0  5016.2     0.1       0
Bank Sta=5008.8,5012.8
Exp/Cntr=0.3,0.1

Type RM Length L Ch R = 1,779,168,168,168
BEGIN DESCRIPTION:
Lacy 086 1975
END DESCRIPTION:
XS GIS Cut Line= 3
      2736688.45      6875277.47      2736384.46      6875154.82
      2736113.09      6875261.54
#Sta/Elev= 30
  4672.2  410.88  4685.6  410.07  4707.7  409.64  4750.2  410.18  4761.4  410.48
  4847.4  409.43  4899.2  409.48  4933.6  409.41  4965.4  408.29  4976.8  408.76
  4985.6  408.17  4985.8  407.67  4989.3  407.67  4989.6  408.17  4994.9  408.61
  5019.8  408.40  5063.0  409.94  5087.4  410.14  5105.8  409.38  5127.3  410.03
  5141.6  411.32  5159.5  411.13  5190.4  413.62  5195.8  413.29  5225.6  415.37
  5244.6  415.77  5256.2  417.40  5258.8  417.34  5267.0  417.14  5291.6  418.46
#Mann=6,-1,0
  4672.2    0.05       0  4750.2     0.1       0  4899.2    0.12       0
  4985.6    0.07       0  4989.6    0.12       0  5258.8     0.1       0
Bank Sta=4985.6,4989.6
Exp/Cntr=0.3,0.1

Type RM Length L Ch R = 1,611,214,214,214
BEGIN DESCRIPTION:
Lacy 086 1974
END DESCRIPTION:
XS GIS Cut Line= 3
      2736466.32      6874965.21      2736372.09      6875012.65
      2736110.39      6875238.38
#Sta/Elev= 30
  4894.5  411.05  4898.4  411.71  4906.1  411.76  4915.1  411.09  4920.7  411.66
  4937.4  410.91  4943.0  411.27  4959.7  409.95  4965.3  410.33  4982.0  408.40
  4987.6  408.72  4995.0  407.00  5001.3  406.68  5001.5  406.18  5005.0  406.18
  5005.3  406.68  5046.1  407.51  5060.3  407.02  5066.9  407.55  5087.8  407.42
  5109.7  408.15  5138.2  410.02  5173.3  409.70  5216.1  410.18  5251.2  412.17
  5258.9  413.25  5308.3  415.58  5322.5  417.22  5336.8  417.42  5345.6  418.22
#Mann=3,-1,0
  4894.5    0.12       0  5001.3    0.07       0  5005.3    0.12       0
Bank Sta=5001.3,5005.3
Exp/Cntr=0.3,0.1

Type RM Length L Ch R = 1,397,0,0,0
BEGIN DESCRIPTION:
Lacy 086 1973
END DESCRIPTION:
XS GIS Cut Line= 3
      2736358.80      6874818.23      2736219.91      6874863.55
      2736088.23      6875179.73
#Sta/Elev= 30
  4853.9  409.35  4875.8  409.61  4912.9  409.16  4939.6  408.06  4944.8  407.60
  4951.5  405.85  4962.0  405.89  4976.7  405.12  4983.1  405.51  5008.1  405.72
  5021.7  404.95  5022.0  404.45  5025.5  404.45  5025.7  404.95  5029.7  405.95
  5047.6  407.69  5071.4  408.68  5083.9  407.61  5106.1  407.19  5153.8  407.93
  5177.6  408.86  5224.7  409.33  5246.4  410.26  5260.0  411.30  5278.4  411.81
  5283.8  413.47  5289.7  413.97  5300.5  413.59  5336.9  415.15  5342.5  415.87
#Mann=3,-1,0
  4853.9    0.12       0  5021.7    0.07       0  5025.7    0.12       0
Bank Sta=5021.7,5025.7
Exp/Cntr=0.3,0.1

Chan Stop Cuts=-1