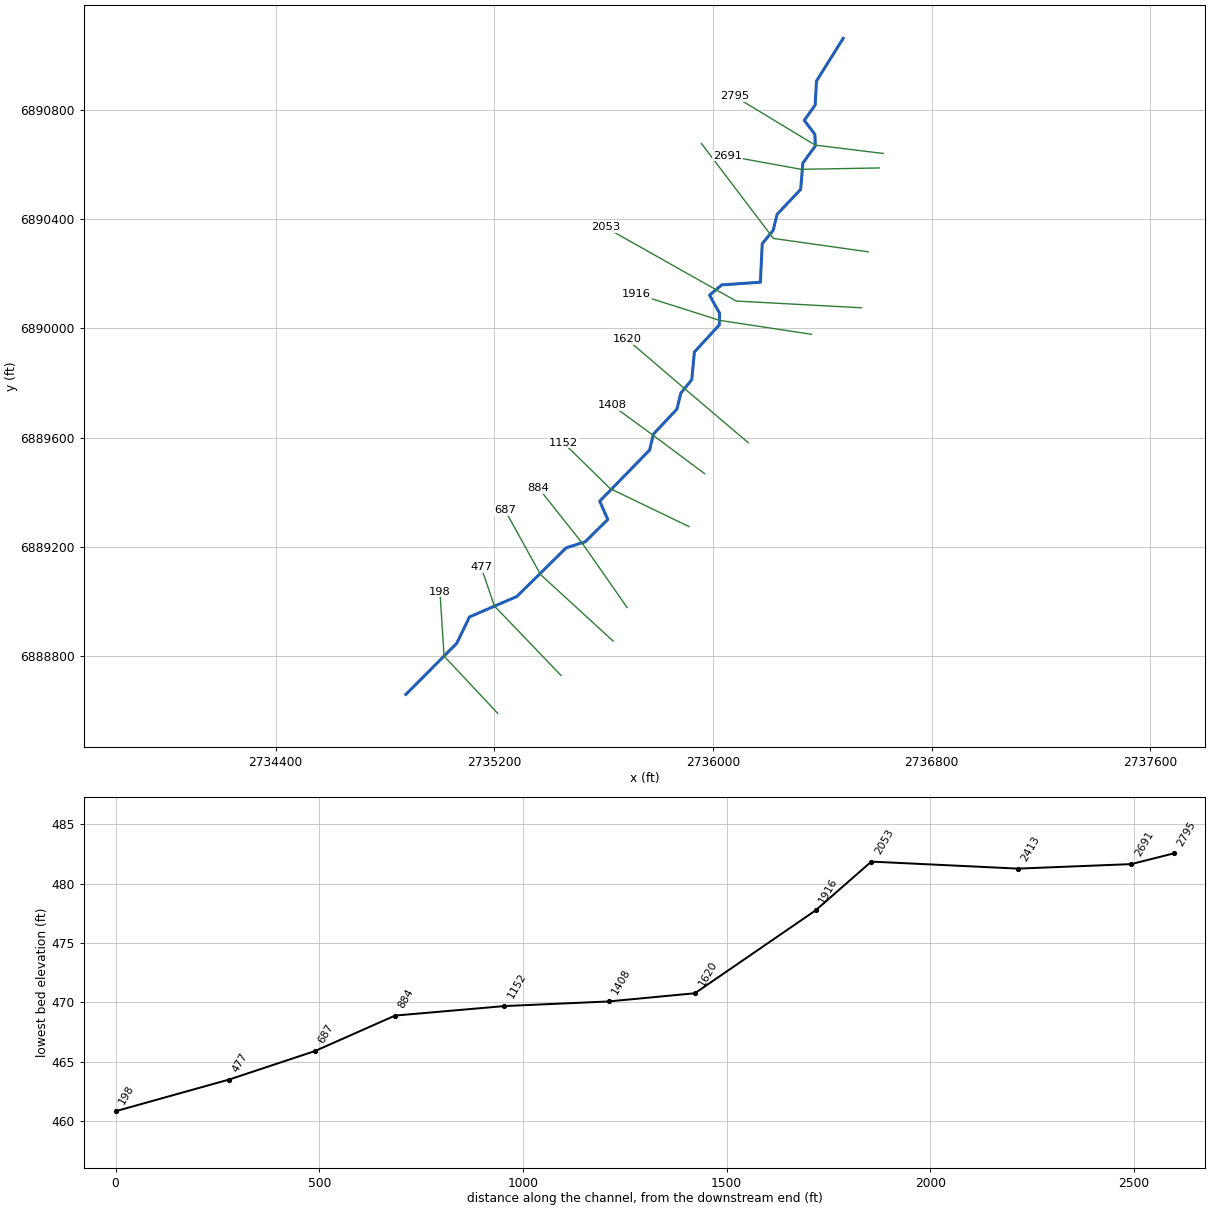
--- Lacy 087.prj (project) ---

Proj Title=Lacy 087 Base Level Engineering
Current Plan=p01
Default Exp/Contr=0.3,0.1
English Units
Geom File=g01
Flow File=f01
Plan File=p01
BEGIN DESCRIPTION:
Lacy 087
END DESCRIPTION:

--- Lacy 087.p01 (plan) ---

Plan Title=Multiple Run
Short Identifier=Multiple
Geom File=g01
Flow File=f01
Subcritical Flow
K Sum by GR= 0
Std Step Tol= 0.01
Critical Tol= 0.01
Num of Std Step Trials= 20
Max Error Tol= 0.3
Flow Tol Ratio= 0.001
Split Flow NTrial= 30
Split Flow Tol= 0.02
Split Flow Ratio= 0.02
Log Output Level= 0
Friction Slope Method= 1
Unsteady Friction Slope Method= 2
Unsteady Bridges Friction Slope Method= 1
Parabolic Critical Depth
Global Vel Dist=  1 , 1 , 1
Global Log Level= 0
CheckData=True
Encroach Param= -1, 0, 0, 0
BEGIN DESCRIPTION:
Multiple Run
END DESCRIPTION:

--- Lacy 087.f01 (steady flow) ---

Flow Title=Multiple
Number of Profiles=7
Profile Names=10-year,25-year,50-year,1pct_min,100-year,1pct_plu,500-year
River Rch & RM= Lacy 087,Reach-1,2795
     277     351     407     236     471     939     625
Boundary for River Rch & Prof#=Lacy 087,Reach-1,1
Up Type=0
Dn Type=3
Dn Slope=0.005
Boundary for River Rch & Prof#=Lacy 087,Reach-1,2
Up Type=0
Dn Type=3
Dn Slope=0.005
Boundary for River Rch & Prof#=Lacy 087,Reach-1,3
Up Type=0
Dn Type=3
Dn Slope=0.005
Boundary for River Rch & Prof#=Lacy 087,Reach-1,4
Up Type=0
Dn Type=3
Dn Slope=0.005
Boundary for River Rch & Prof#=Lacy 087,Reach-1,5
Up Type=0
Dn Type=3
Dn Slope=0.005
Boundary for River Rch & Prof#=Lacy 087,Reach-1,6
Up Type=0
Dn Type=3
Dn Slope=0.005
Boundary for River Rch & Prof#=Lacy 087,Reach-1,7
Up Type=0
Dn Type=3
Dn Slope=0.005

--- Lacy 087.g01 (geometry) ---

Geom Title=Existing Conditions

River Reach=Lacy 087,Reach-1
Reach XY= 30
      2736476.00      6891061.00      2736378.32      6890905.04
      2736373.45      6890816.89      2736333.59      6890760.99
      2736372.39      6890709.36      2736374.14      6890667.13
      2736328.38      6890605.03      2736320.46      6890508.58
      2736234.16      6890417.05      2736219.86      6890358.83
      2736179.76      6890309.44      2736173.08      6890168.92
      2736031.46      6890158.93      2735986.96      6890121.43
      2736024.01      6890054.96      2736022.83      6890012.65
      2735931.54      6889913.42      2735922.17      6889812.59
      2735882.14      6889763.17      2735867.84      6889704.95
      2735781.87      6889613.28      2735767.84      6889554.95
      2735585.30      6889367.67      2735614.77      6889300.98
      2735532.08      6889219.16      2735462.79      6889197.37
      2735282.06      6889019.14      2735108.95      6888944.51
      2735062.36      6888847.80      2734876.00      6888661.00

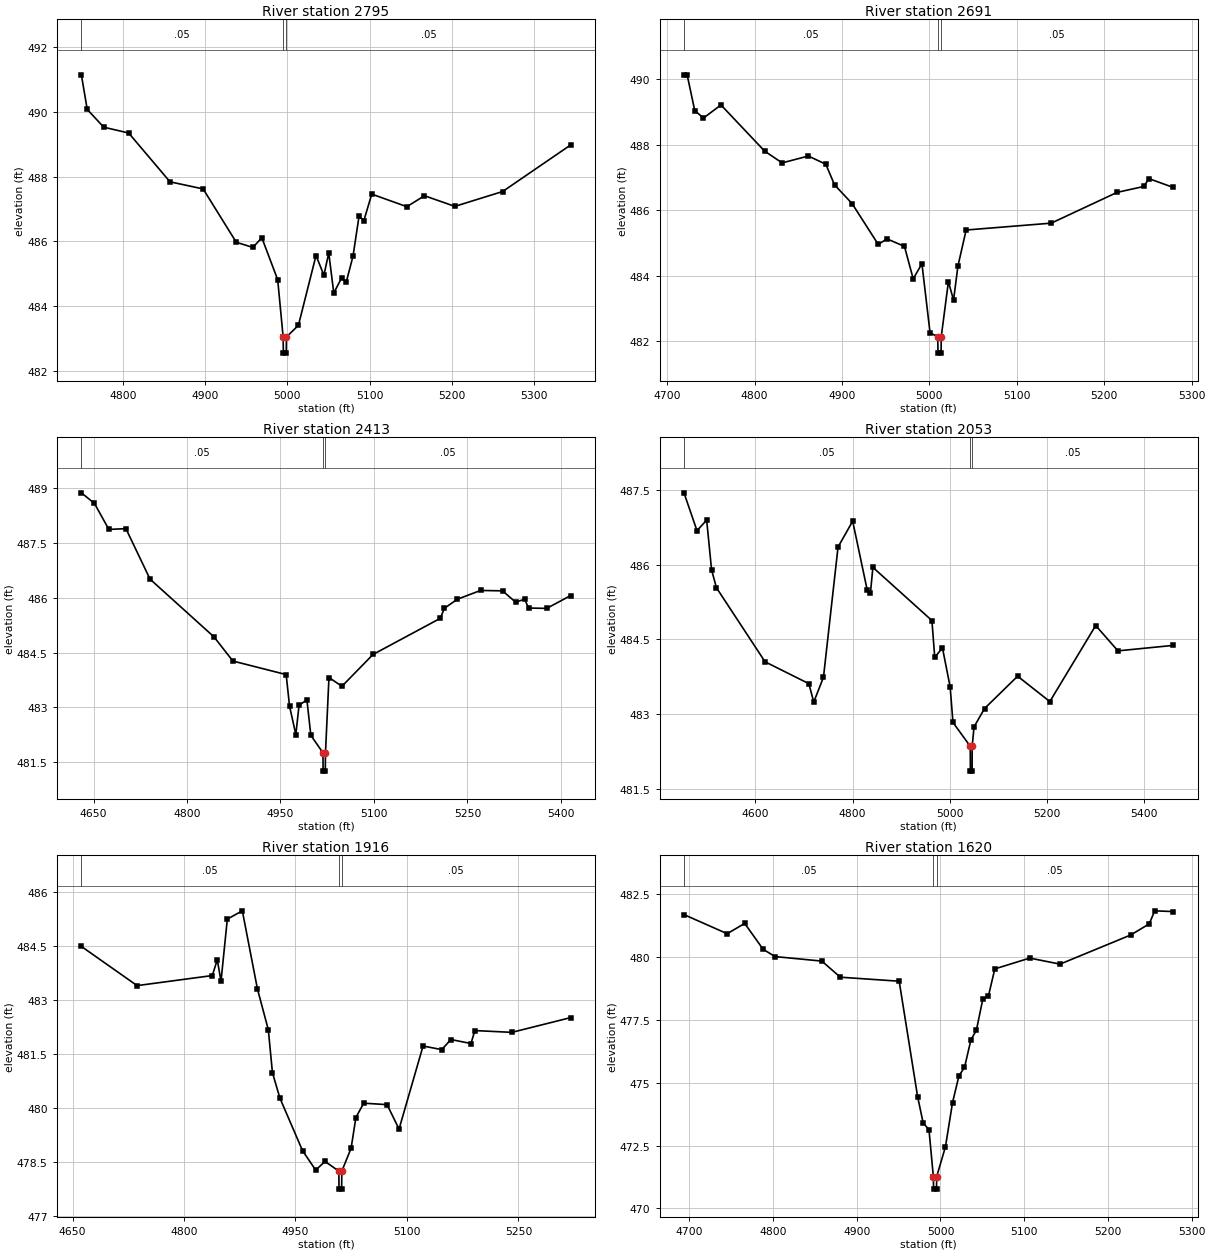
Type RM Length L Ch R = 1,2795,104,104,104
BEGIN DESCRIPTION:
Lacy 087 3483
END DESCRIPTION:
XS GIS Cut Line= 3
      2736623.04      6890639.74      2736373.92      6890670.35
      2736079.42      6890848.33
#Sta/Elev= 30
  4749.5  491.15  4756.6  490.08  4776.7  489.53  4807.0  489.35  4857.3  487.84
  4897.6  487.62  4937.9  485.97  4958.1  485.81  4969.0  486.11  4988.3  484.81
  4994.9  483.04  4995.2  482.54  4998.7  482.54  4998.9  483.04  5013.5  483.40
  5034.9  485.56  5044.5  484.95  5050.4  485.64  5056.5  484.40  5065.9  484.86
  5071.7  484.74  5079.9  485.54  5087.2  486.77  5093.1  486.64  5102.7  487.46
  5145.4  487.07  5166.8  487.41  5203.7  487.08  5261.9  487.54  5344.6  488.98
#Mann=3,-1,0
  4749.5    0.05       0  4994.9    0.04       0  4998.9    0.05       0
Bank Sta=4994.9,4998.9
Exp/Cntr=0.3,0.1

Type RM Length L Ch R = 1,2691,278,278,278
BEGIN DESCRIPTION:
Lacy 087 1965
END DESCRIPTION:
XS GIS Cut Line= 3
      2736608.29      6890586.88      2736322.42      6890581.83
      2736052.85      6890630.84
#Sta/Elev= 30
  4719.2  490.14  4722.8  490.14  4731.5  489.05  4741.5  488.82  4761.5  489.22
  4811.5  487.81  4831.5  487.45  4861.5  487.66  4881.5  487.41  4891.5  486.78
  4911.5  486.21  4941.5  484.96  4951.5  485.13  4971.5  484.90  4981.5  483.91
  4991.5  484.37  5000.8  482.26  5009.6  482.14  5009.9  481.64  5013.4  481.64
  5013.6  482.14  5021.8  483.82  5027.7  483.26  5032.7  484.30  5042.1  485.40
  5139.5  485.61  5214.9  486.55  5245.4  486.73  5251.3  486.97  5279.1  486.70
#Mann=3,-1,0
  4719.2    0.05       0  5009.6    0.04       0  5013.6    0.05       0
Bank Sta=5009.6,5013.6
Exp/Cntr=0.3,0.1

Type RM Length L Ch R = 1,2413,360,360,360
BEGIN DESCRIPTION:
Lacy 087 1964
END DESCRIPTION:
XS GIS Cut Line= 3
      2736566.82      6890280.14      2736220.63      6890328.98
      2735957.44      6890676.19
#Sta/Elev= 30
  4630.4  488.87  4651.4  488.58  4674.5  487.87  4701.9  487.89  4740.6  486.51
  4843.3  484.93  4873.6  484.27  4959.1  483.90  4964.5  483.04  4974.6  482.26
  4979.8  483.06  4992.4  483.21  4998.7  482.24  5018.2  481.76  5018.4  481.26
  5021.9  481.26  5022.2  481.76  5027.8  483.82  5048.6  483.58  5098.5  484.45
  5206.7  485.44  5212.9  485.71  5233.8  485.96  5271.1  486.20  5306.5  486.19
  5327.3  485.88  5341.9  485.96  5348.2  485.72  5377.3  485.71  5415.7  486.06
#Mann=3,-1,0
  4630.4    0.05       0  5018.2    0.04       0  5022.2    0.05       0
Bank Sta=5018.2,5022.2
Exp/Cntr=0.3,0.1

Type RM Length L Ch R = 1,2053,137,137,137
BEGIN DESCRIPTION:
Lacy 087 1962
END DESCRIPTION:
XS GIS Cut Line= 3
      2736542.67      6890075.34      2736084.49      6890099.94
      2735607.00      6890369.18
#Sta/Elev= 30
  4453.0  487.45  4479.7  486.69  4499.7  486.90  4509.8  485.90  4519.8  485.54
  4619.9  484.05  4710.0  483.61  4720.1  483.24  4740.1  483.74  4770.1  486.36
  4800.2  486.88  4830.2  485.49  4836.8  485.44  4841.8  485.95  4963.3  484.88
  4969.1  484.14  4985.0  484.33  5000.9  483.54  5006.6  482.83  5042.2  482.35
  5042.5  481.85  5046.0  481.85  5046.2  482.35  5050.0  482.74  5071.6  483.11
  5139.7  483.76  5206.0  483.25  5300.4  484.78  5346.2  484.27  5460.0  484.38
#Mann=3,-1,0
  4453.0    0.05       0  5042.2    0.04       0  5046.2    0.05       0
Bank Sta=5042.2,5046.2
Exp/Cntr=0.3,0.1

Type RM Length L Ch R = 1,1916,296,296,296
BEGIN DESCRIPTION:
Lacy 087 1961
END DESCRIPTION:
XS GIS Cut Line= 3
      2736360.19      6889978.33      2736024.56      6890029.25
      2735720.59      6890125.78
#Sta/Elev= 30
  4661.9  484.49  4736.9  483.40  4838.1  483.68  4844.8  484.12  4849.8  483.52
  4858.3  485.25  4878.5  485.48  4898.8  483.31  4913.5  482.17  4919.0  480.98
  4929.1  480.27  4959.5  478.81  4977.2  478.27  4989.8  478.51  5008.4  478.24
  5008.6  477.74  5012.1  477.74  5012.4  478.24  5024.9  478.88  5031.3  479.73
  5041.8  480.13  5073.3  480.09  5089.4  479.41  5121.7  481.72  5146.8  481.62
  5159.2  481.90  5186.2  481.79  5191.4  482.15  5241.2  482.10  5320.3  482.51
#Mann=3,-1,0
  4661.9    0.05       0  5008.4    0.04       0  5012.4    0.05       0
Bank Sta=5008.4,5012.4
Exp/Cntr=0.3,0.1

Type RM Length L Ch R = 1,1620,212,212,212
BEGIN DESCRIPTION:
Lacy 087 1960
END DESCRIPTION:
XS GIS Cut Line= 3
      2736129.04      6889581.48      2735891.03      6889783.63
      2735684.41      6889960.57
#Sta/Elev= 30
  4693.7  481.69  4745.3  480.93  4766.2  481.34  4788.2  480.31  4802.5  480.02
  4858.4  479.84  4880.4  479.20  4950.7  479.04  4972.7  474.45  4979.3  473.41
  4986.3  473.13  4991.5  471.27  4991.8  470.77  4995.3  470.77  4995.5  471.27
  5006.0  472.46  5014.4  474.21  5022.1  475.28  5028.7  475.61  5036.4  476.71
  5042.9  477.09  5050.6  478.33  5057.2  478.44  5064.9  479.53  5106.6  479.96
  5142.8  479.72  5227.3  480.88  5249.3  481.32  5255.9  481.84  5278.0  481.81
#Mann=3,-1,0
  4693.7    0.05       0  4991.5    0.04       0  4995.5    0.05       0
Bank Sta=4991.5,4995.5
Exp/Cntr=0.3,0.1

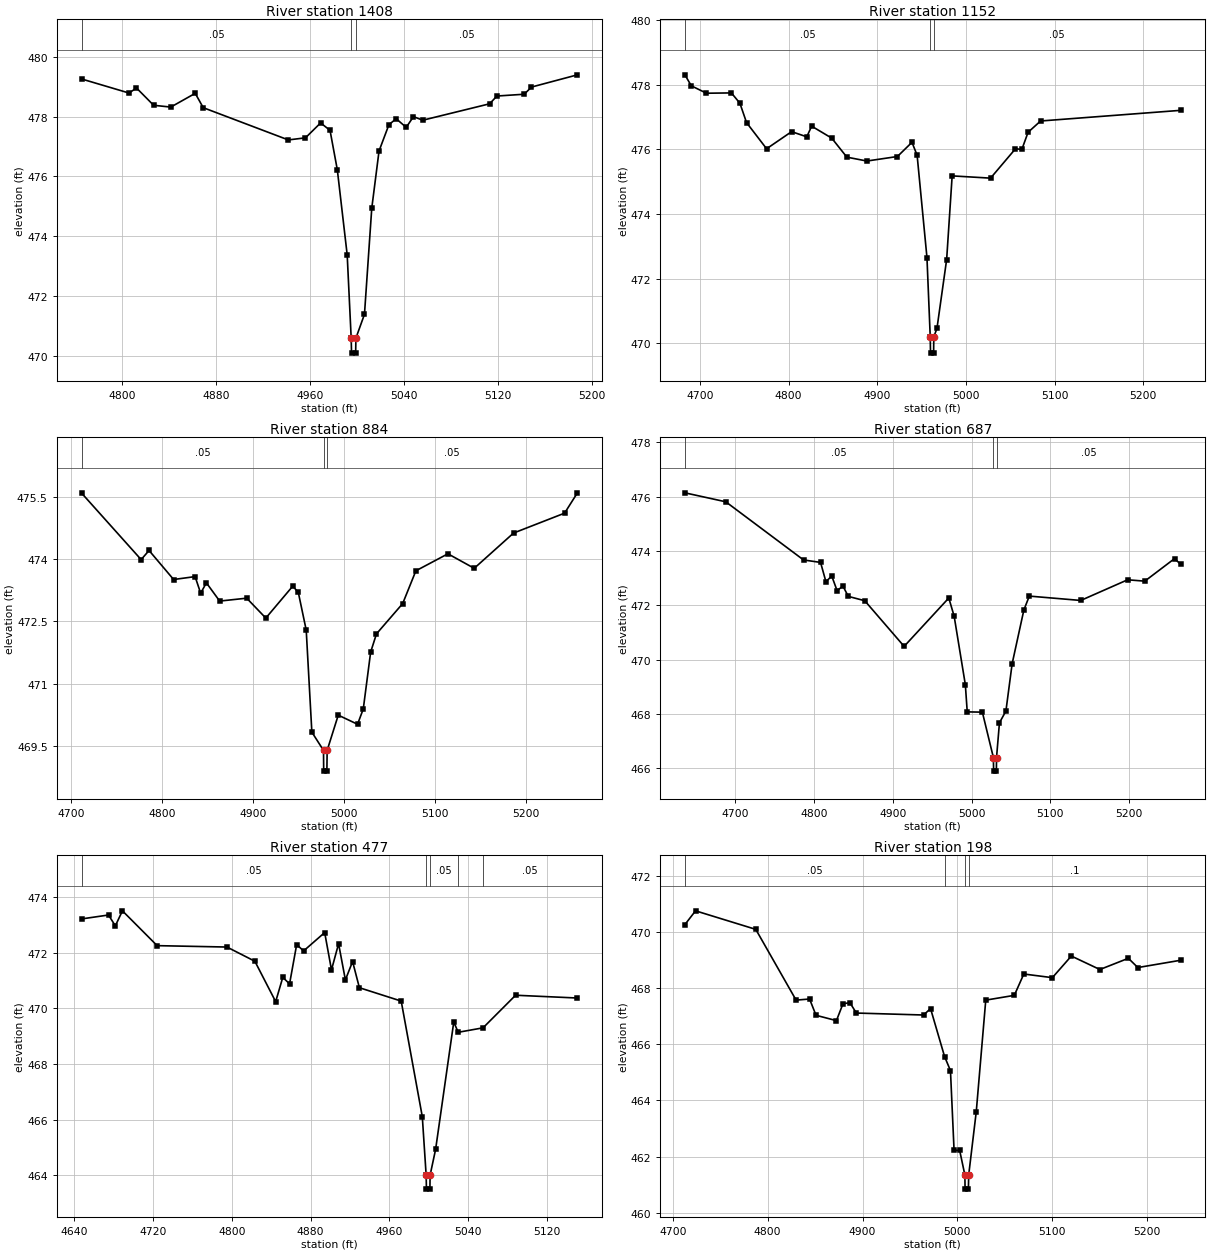
Type RM Length L Ch R = 1,1408,256,256,256
BEGIN DESCRIPTION:
Lacy 087 1959
END DESCRIPTION:
XS GIS Cut Line= 3
      2735968.91      6889468.57      2735782.25      6889607.88
      2735629.76      6889719.34
#Sta/Elev= 30
  4765.6  479.26  4805.9  478.79  4812.2  478.96  4826.8  478.38  4841.4  478.32
  4862.2  478.78  4869.0  478.30  4941.4  477.22  4956.0  477.29  4968.9  477.79
  4976.9  477.54  4983.1  476.22  4991.5  473.37  4994.9  470.58  4995.2  470.08
  4998.7  470.08  4998.9  470.58  5006.2  471.38  5012.4  474.93  5018.6  476.85
  5027.0  477.73  5033.2  477.93  5041.7  477.64  5047.9  478.00  5055.8  477.88
  5112.7  478.43  5118.9  478.69  5142.1  478.75  5148.3  478.99  5187.4  479.40
#Mann=3,-1,0
  4765.6    0.05       0  4994.9    0.04       0  4998.9    0.05       0
Bank Sta=4994.9,4998.9
Exp/Cntr=0.3,0.1

Type RM Length L Ch R = 1,1152,268,268,268
BEGIN DESCRIPTION:
Lacy 087 1958
END DESCRIPTION:
XS GIS Cut Line= 3
      2735911.86      6889275.00      2735624.03      6889413.63
      2735452.84      6889581.02
#Sta/Elev= 30
  4683.2  478.31  4690.4  477.97  4707.5  477.74  4735.6  477.75  4745.2  477.43
  4752.7  476.83  4775.3  476.02  4803.5  476.55  4820.6  476.39  4826.1  476.72
  4848.7  476.35  4865.8  475.76  4888.4  475.64  4922.8  475.78  4939.2  476.22
  4945.0  475.82  4956.1  472.65  4959.8  470.19  4960.1  469.69  4963.6  469.69
  4963.8  470.19  4967.4  470.46  4978.3  472.59  4984.5  475.18  5027.8  475.11
  5055.9  476.02  5063.1  476.00  5070.1  476.53  5084.2  476.88  5242.1  477.21
#Mann=3,-1,0
  4683.2    0.05       0  4959.8    0.04       0  4963.8    0.05       0
Bank Sta=4959.8,4963.8
Exp/Cntr=0.3,0.1

Type RM Length L Ch R = 1,884,197,197,197
BEGIN DESCRIPTION:
Lacy 087 1957
END DESCRIPTION:
XS GIS Cut Line= 3
      2735685.70      6888978.66      2735521.69      6889213.78
      2735361.44      6889416.02
#Sta/Elev= 30
  4712.1  475.59  4777.4  473.99  4786.1  474.21  4813.1  473.51  4836.7  473.58
  4842.8  473.18  4849.1  473.43  4863.7  472.99  4893.4  473.06  4914.4  472.58
  4944.0  473.35  4950.1  473.20  4958.8  472.29  4965.0  469.83  4977.8  469.39
  4978.0  468.89  4981.5  468.89  4981.8  469.39  4994.0  470.24  5015.2  470.02
  5021.5  470.39  5029.6  471.76  5036.0  472.20  5064.8  472.93  5079.3  473.72
  5114.5  474.13  5143.4  473.78  5186.6  474.63  5242.7  475.11  5256.8  475.60
#Mann=3,-1,0
  4712.1    0.05       0  4977.8    0.04       0  4981.8    0.05       0
Bank Sta=4977.8,4981.8
Exp/Cntr=0.3,0.1

Type RM Length L Ch R = 1,687,210,210,210
BEGIN DESCRIPTION:
Lacy 087 1956
END DESCRIPTION:
XS GIS Cut Line= 3
      2735634.28      6888856.27      2735368.91      6889099.32
      2735238.66      6889335.19
#Sta/Elev= 30
  4636.1  476.14  4688.0  475.81  4786.7  473.67  4808.3  473.58  4815.1  472.87
  4822.5  473.08  4829.3  472.54  4836.7  472.71  4843.5  472.33  4864.4  472.17
  4914.4  470.49  4971.1  472.27  4977.9  471.60  4992.1  469.08  4994.5  468.08
  5013.7  468.07  5027.7  466.40  5028.0  465.90  5031.5  465.90  5031.7  466.40
  5035.4  467.68  5043.6  468.11  5051.5  469.85  5066.4  471.83  5073.3  472.34
  5138.6  472.18  5198.1  472.94  5219.9  472.89  5257.7  473.72  5265.4  473.51
#Mann=3,-1,0
  4636.1    0.05       0  5027.7    0.04       0  5031.7    0.05       0
Bank Sta=5027.7,5031.7
Exp/Cntr=0.3,0.1

Type RM Length L Ch R = 1,477,279,279,279
BEGIN DESCRIPTION:
Lacy 087 1969
END DESCRIPTION:
XS GIS Cut Line= 3
      2735443.69      6888730.46      2735199.96      6888984.57
      2735151.41      6889127.13
#Sta/Elev= 30
  4647.9  473.21  4675.1  473.35  4682.0  472.96  4689.2  473.50  4724.4  472.25
  4795.2  472.20  4823.5  471.69  4844.6  470.24  4851.8  471.11  4858.7  470.88
  4865.9  472.29  4872.9  472.06  4894.3  472.72  4901.2  471.38  4908.4  472.32
  4915.3  471.02  4922.6  471.68  4929.5  470.74  4971.9  470.26  4993.3  466.11
  4997.2  464.01  4997.5  463.51  5001.0  463.51  5001.2  464.01  5006.8  464.94
  5025.2  469.51  5029.7  469.14  5054.9  469.30  5087.9  470.47  5150.6  470.37
#Mann=5,-1,0
  4647.9    0.05       0  4997.2    0.04       0  5001.2    0.05       0
  5029.7     0.1       0  5054.9    0.05       0
Bank Sta=4997.2,5001.2
Exp/Cntr=0.3,0.1

Type RM Length L Ch R = 1,198,0,0,0
BEGIN DESCRIPTION:
Lacy 087 1968
END DESCRIPTION:
XS GIS Cut Line= 3
      2735212.27      6888591.64      2735015.82      6888801.14
      2735001.00      6889035.98
#Sta/Elev= 30
  4712.8  470.26  4724.0  470.75  4787.5  470.09  4830.0  467.57  4844.2  467.61
  4851.0  467.03  4872.5  466.84  4879.4  467.44  4886.7  467.48  4893.5  467.11
  4964.4  467.04  4971.7  467.27  4986.5  465.56  4992.7  465.06  4996.5  462.22
  5002.4  462.22  5007.9  461.34  5008.1  460.84  5011.6  460.84  5011.9  461.34
  5019.9  463.60  5029.9  467.57  5060.0  467.74  5070.0  468.50  5100.1  468.37
  5120.1  469.14  5150.2  468.66  5180.2  469.06  5190.2  468.73  5235.3  468.99
#Mann=4,-1,0
  4712.8    0.05       0  4986.5     0.1       0  5007.9    0.07       0
  5011.9     0.1       0
Bank Sta=5007.9,5011.9
Exp/Cntr=0.3,0.1

Chan Stop Cuts=-1