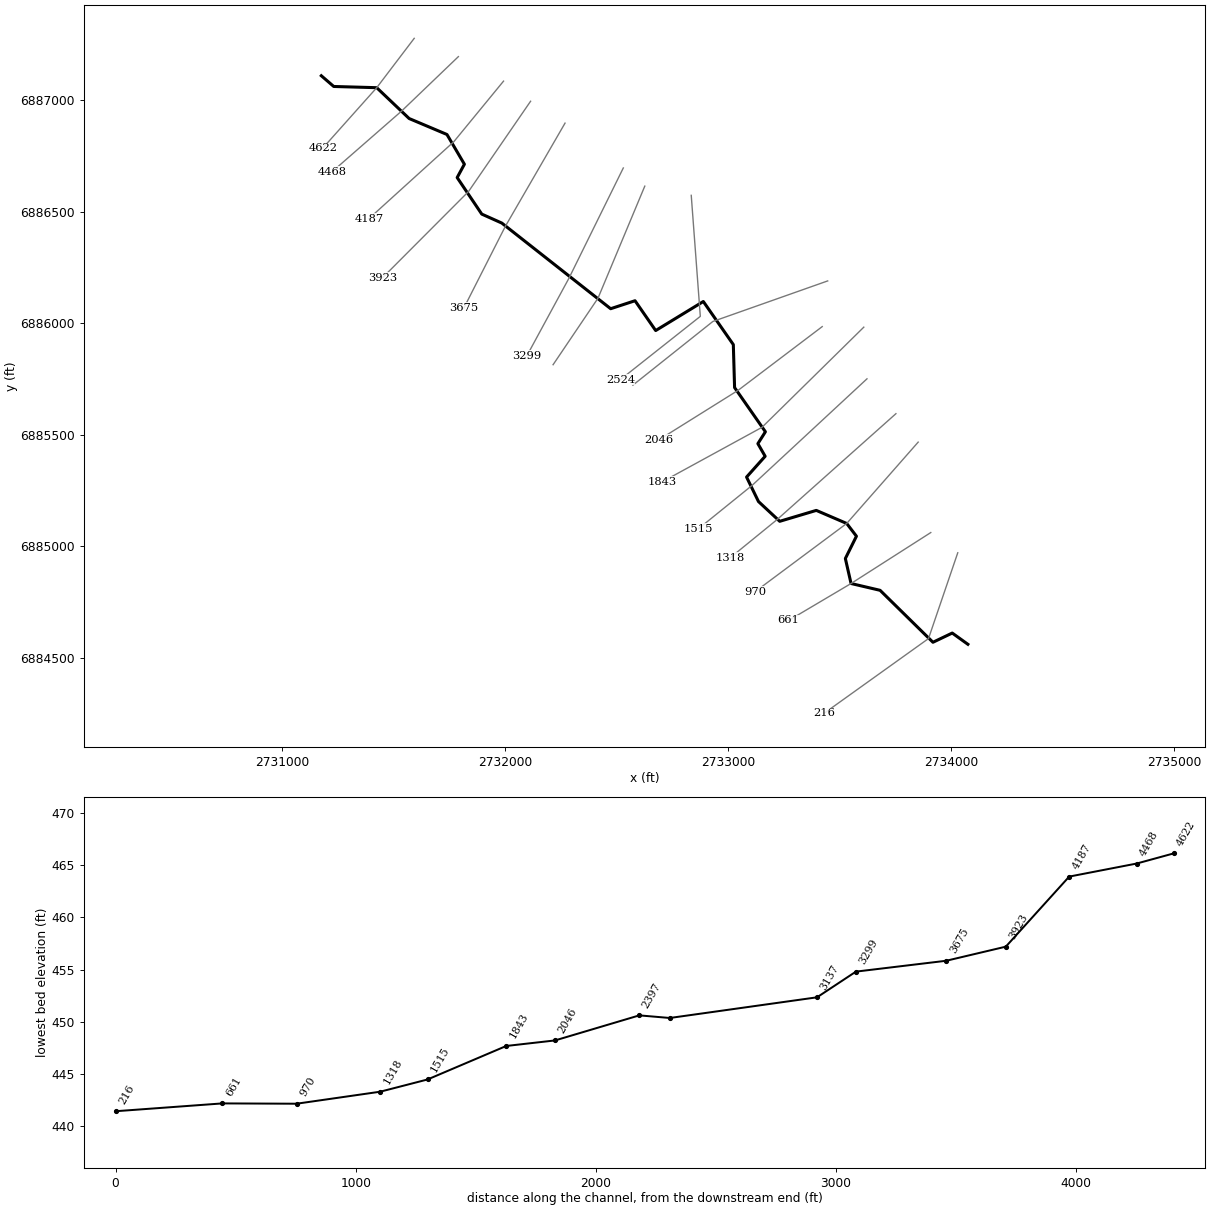
--- Lacy 089.prj (project) ---

Proj Title=Lacy 089 Base Level Engineering
Current Plan=p01
Default Exp/Contr=0.3,0.1
English Units
Geom File=g01
Flow File=f01
Plan File=p01
BEGIN DESCRIPTION:
Lacy 089
END DESCRIPTION:

--- Lacy 089.p01 (plan) ---

Plan Title=Multiple Run
Short Identifier=Multiple
Geom File=g01
Flow File=f01
Subcritical Flow
K Sum by GR= 0
Std Step Tol= 0.01
Critical Tol= 0.01
Num of Std Step Trials= 20
Max Error Tol= 0.3
Flow Tol Ratio= 0.001
Split Flow NTrial= 30
Split Flow Tol= 0.02
Split Flow Ratio= 0.02
Log Output Level= 0
Friction Slope Method= 1
Unsteady Friction Slope Method= 2
Unsteady Bridges Friction Slope Method= 1
Parabolic Critical Depth
Global Vel Dist=  1 , 1 , 1
Global Log Level= 0
CheckData=True
Encroach Param= -1, 0, 0, 0
BEGIN DESCRIPTION:
Multiple Run
END DESCRIPTION:

--- Lacy 089.f01 (steady flow) ---

Flow Title=Multiple
Number of Profiles=7
Profile Names=10-year,25-year,50-year,1pct_min,100-year,1pct_plu,500-year
River Rch & RM= Lacy 089,Reach-1,4622
     268     339     394     228     455     907     603
River Rch & RM= Lacy 089,Reach-1,2397
     471     617     733     433     864    1724    1196
Boundary for River Rch & Prof#=Lacy 089,Reach-1,1
Up Type=0
Dn Type=3
Dn Slope=0.005
Boundary for River Rch & Prof#=Lacy 089,Reach-1,2
Up Type=0
Dn Type=3
Dn Slope=0.005
Boundary for River Rch & Prof#=Lacy 089,Reach-1,3
Up Type=0
Dn Type=3
Dn Slope=0.005
Boundary for River Rch & Prof#=Lacy 089,Reach-1,4
Up Type=0
Dn Type=3
Dn Slope=0.005
Boundary for River Rch & Prof#=Lacy 089,Reach-1,5
Up Type=0
Dn Type=3
Dn Slope=0.005
Boundary for River Rch & Prof#=Lacy 089,Reach-1,6
Up Type=0
Dn Type=3
Dn Slope=0.005
Boundary for River Rch & Prof#=Lacy 089,Reach-1,7
Up Type=0
Dn Type=3
Dn Slope=0.005

--- Lacy 089.g01 (geometry) ---

Geom Title=Existing Conditions

River Reach=Lacy 089,Reach-1
Reach XY= 30
      2731176.00      6887111.00      2731231.78      6887062.89
      2731424.54      6887057.46      2731569.94      6886919.14
      2731739.57      6886847.53      2731817.75      6886714.23
      2731785.31      6886654.34      2731895.63      6886490.53
      2731985.66      6886450.21      2732473.72      6886066.13
      2732583.01      6886101.96      2732675.70      6885968.20
      2732889.34      6886098.49      2733023.94      6885905.15
      2733029.55      6885712.47      2733167.77      6885514.23
      2733134.04      6885461.00      2733166.67      6885404.33
      2733083.31      6885311.09      2733136.74      6885201.30
      2733232.02      6885112.61      2733396.05      6885161.60
      2733532.43      6885102.98      2733576.10      6885045.79
      2733526.39      6884945.72      2733551.96      6884833.67
      2733682.17      6884803.14      2733919.27      6884570.13
      2734005.75      6884611.46      2734076.00      6884561.00

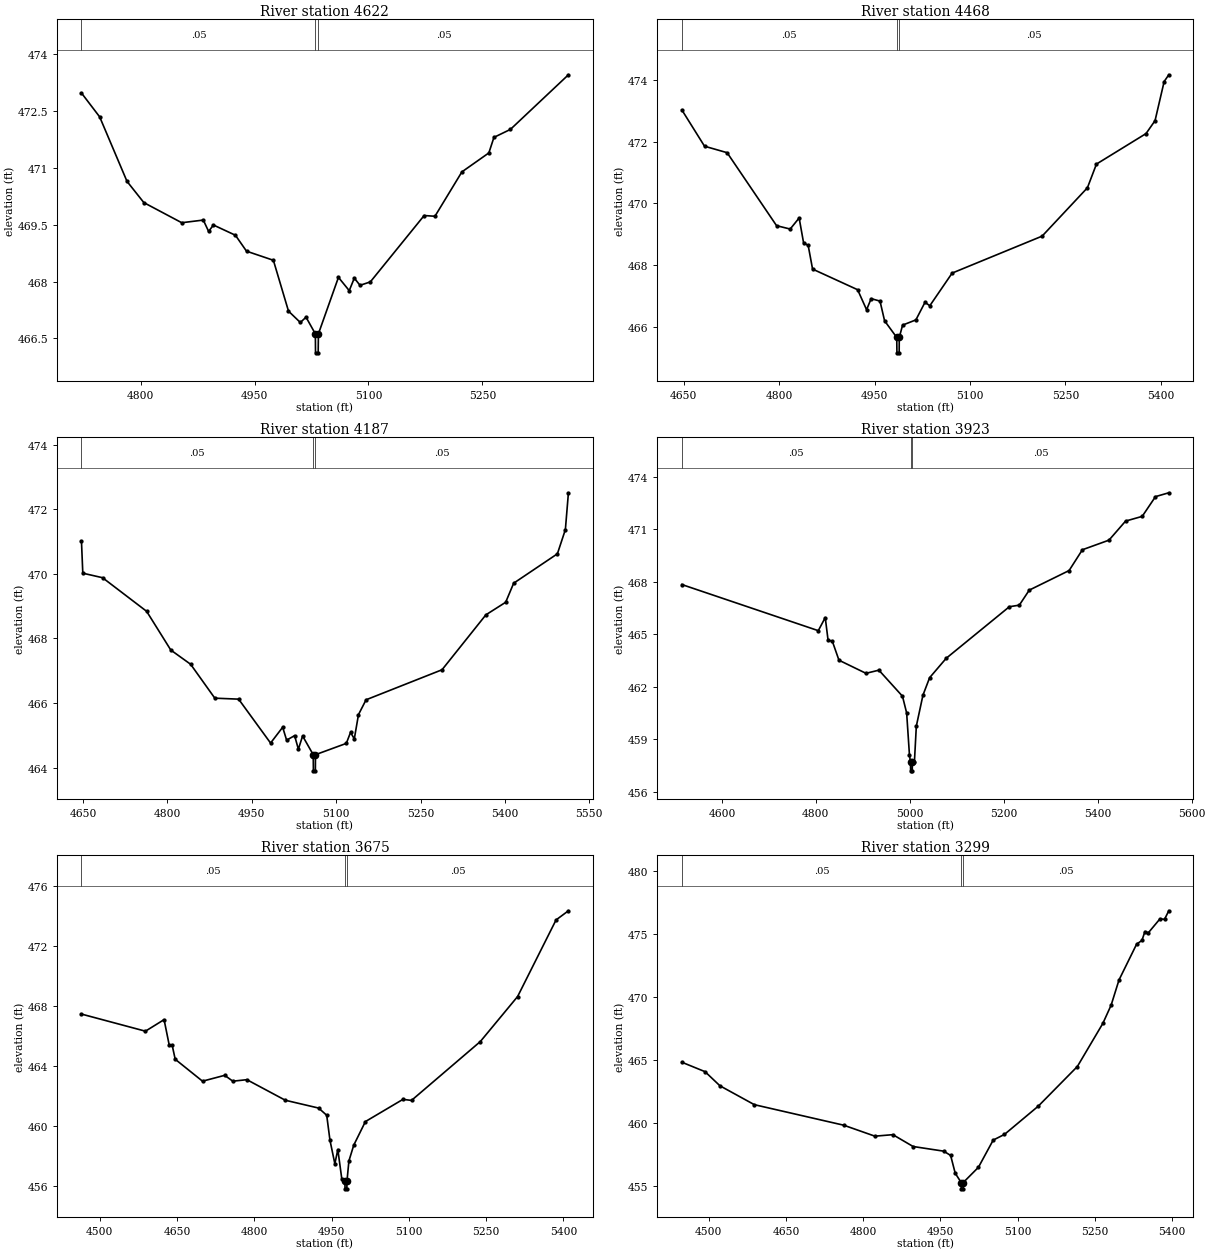
Type RM Length L Ch R = 1,4622,154,154,154
BEGIN DESCRIPTION:
Lacy 089 1937
END DESCRIPTION:
XS GIS Cut Line= 3
      2731592.74      6887278.80      2731424.54      6887057.46
      2731182.55      6886786.35
#Sta/Elev= 30
  4722.0  472.97  4746.0  472.34  4782.0  470.64  4804.2  470.08  4854.1  469.55
  4882.5  469.62  4889.5  469.32  4895.8  469.49  4924.8  469.22  4939.4  468.80
  4974.8  468.56  4994.7  467.22  5010.3  466.92  5017.8  467.06  5030.1  466.62
  5030.3  466.12  5033.8  466.12  5034.1  466.62  5060.5  468.11  5074.7  467.76
  5081.4  468.09  5088.9  467.90  5102.5  467.99  5173.4  469.74  5187.6  469.72
  5223.1  470.89  5258.6  471.39  5265.3  471.80  5287.0  472.01  5363.4  473.45
#Mann=3,-1,0
  4722.0    0.05       0  5030.1    0.04       0  5034.1    0.05       0
Bank Sta=5030.1,5034.1
Exp/Cntr=0.3,0.1

Type RM Length L Ch R = 1,4468,281,281,281
BEGIN DESCRIPTION:
Lacy 089 1936
END DESCRIPTION:
XS GIS Cut Line= 3
      2731790.82      6887196.81      2731536.22      6886952.72
      2731225.36      6886681.28
#Sta/Elev= 30
  4647.1  473.04  4682.8  471.86  4718.3  471.65  4796.0  469.28  4817.4  469.17
  4831.5  469.53  4838.5  468.72  4845.7  468.64  4852.6  467.87  4923.4  467.20
  4937.5  466.55  4944.7  466.91  4958.6  466.83  4965.8  466.19  4984.9  465.65
  4985.2  465.15  4988.7  465.15  4988.9  465.65  4994.1  466.05  5015.0  466.22
  5029.3  466.79  5036.9  466.68  5072.0  467.74  5213.4  468.94  5284.6  470.51
  5298.8  471.28  5376.7  472.27  5390.9  472.69  5405.2  473.96  5412.5  474.18
#Mann=3,-1,0
  4647.1    0.05       0  4984.9    0.04       0  4988.9    0.05       0
Bank Sta=4984.9,4988.9
Exp/Cntr=0.3,0.1

Type RM Length L Ch R = 1,4187,264,264,264
BEGIN DESCRIPTION:
Lacy 089 1935
END DESCRIPTION:
XS GIS Cut Line= 3
      2731993.31      6887086.87      2731770.51      6886815.38
      2731389.58      6886470.00
#Sta/Elev= 30
  4647.4  471.02  4649.8  470.02  4684.9  469.88  4763.2  468.84  4806.2  467.64
  4841.4  467.20  4884.4  466.15  4926.7  466.12  4983.5  464.76  5005.0  465.25
  5012.0  464.85  5026.2  464.99  5032.9  464.57  5040.4  464.98  5059.3  464.40
  5059.6  463.90  5063.1  463.90  5063.3  464.40  5118.1  464.75  5125.6  465.09
  5132.3  464.89  5139.7  465.64  5153.2  466.10  5288.2  467.03  5366.1  468.73
  5401.3  469.12  5415.5  469.71  5493.2  470.62  5507.4  471.37  5512.8  472.51
#Mann=3,-1,0
  4647.4    0.05       0  5059.3    0.04       0  5063.3    0.05       0
Bank Sta=5059.3,5063.3
Exp/Cntr=0.3,0.1

Type RM Length L Ch R = 1,3923,248,248,248
BEGIN DESCRIPTION:
Lacy 089 1934
END DESCRIPTION:
XS GIS Cut Line= 3
      2732114.64      6886996.67      2731836.30      6886591.80
      2731451.23      6886205.73
#Sta/Elev= 30
  4514.7  467.85  4805.2  465.21  4820.0  465.96  4826.1  464.65  4834.9  464.62
  4849.2  463.52  4906.7  462.77  4934.2  462.95  4984.4  461.46  4993.3  460.50
  4999.3  458.08  5001.5  457.69  5001.7  457.19  5005.2  457.19  5005.5  457.69
  5009.8  457.69  5013.9  459.75  5028.0  461.52  5042.2  462.52  5077.5  463.63
  5211.9  466.58  5233.1  466.67  5254.3  467.53  5339.1  468.65  5367.4  469.84
  5424.0  470.39  5459.3  471.48  5494.7  471.75  5523.0  472.88  5551.3  473.10
#Mann=3,-1,0
  4514.7    0.05       0  5001.5    0.04       0  5005.5    0.05       0
Bank Sta=5001.5,5005.5
Exp/Cntr=0.3,0.1

Type RM Length L Ch R = 1,3675,376,376,376
BEGIN DESCRIPTION:
Lacy 089 1933
END DESCRIPTION:
XS GIS Cut Line= 3
      2732269.15      6886898.56      2732001.35      6886435.50
      2731815.58      6886069.57
#Sta/Elev= 30
  4464.5  467.48  4588.7  466.34  4624.9  467.11  4634.9  465.41  4640.7  465.39
  4646.5  464.47  4699.5  463.01  4742.6  463.40  4758.3  463.01  4785.6  463.11
  4860.3  461.74  4924.9  461.22  4940.6  460.74  4946.9  459.08  4956.4  457.51
  4962.2  458.46  4970.0  456.47  4975.9  456.34  4976.2  455.84  4979.7  455.84
  4979.9  456.34  4983.7  457.70  4993.1  458.75  5015.7  460.32  5088.6  461.80
  5105.2  461.73  5238.8  465.65  5311.2  468.65  5385.8  473.75  5409.8  474.36
#Mann=3,-1,0
  4464.5    0.05       0  4975.9    0.04       0  4979.9    0.05       0
Bank Sta=4975.9,4979.9
Exp/Cntr=0.3,0.1

Type RM Length L Ch R = 1,3299,162,162,162
BEGIN DESCRIPTION:
Lacy 089 1932
END DESCRIPTION:
XS GIS Cut Line= 3
      2732530.46      6886697.40      2732286.85      6886203.25
      2732098.50      6885855.97
#Sta/Elev= 30
  4447.7  464.85  4492.8  464.10  4521.7  462.98  4588.6  461.48  4762.3  459.85
  4822.8  458.98  4857.7  459.10  4897.0  458.16  4956.5  457.79  4969.9  457.45
  4978.8  456.04  4990.4  455.30  4990.7  454.80  4994.2  454.80  4994.4  455.30
  5023.9  456.51  5052.6  458.67  5074.5  459.12  5140.1  461.36  5216.1  464.51
  5265.6  467.93  5281.7  469.38  5297.0  471.38  5331.2  474.22  5341.6  474.52
  5347.3  475.22  5353.9  475.12  5376.6  476.23  5385.4  476.19  5393.7  476.87
#Mann=3,-1,0
  4447.7    0.05       0  4990.4    0.04       0  4994.4    0.05       0
Bank Sta=4990.4,4994.4
Exp/Cntr=0.3,0.1

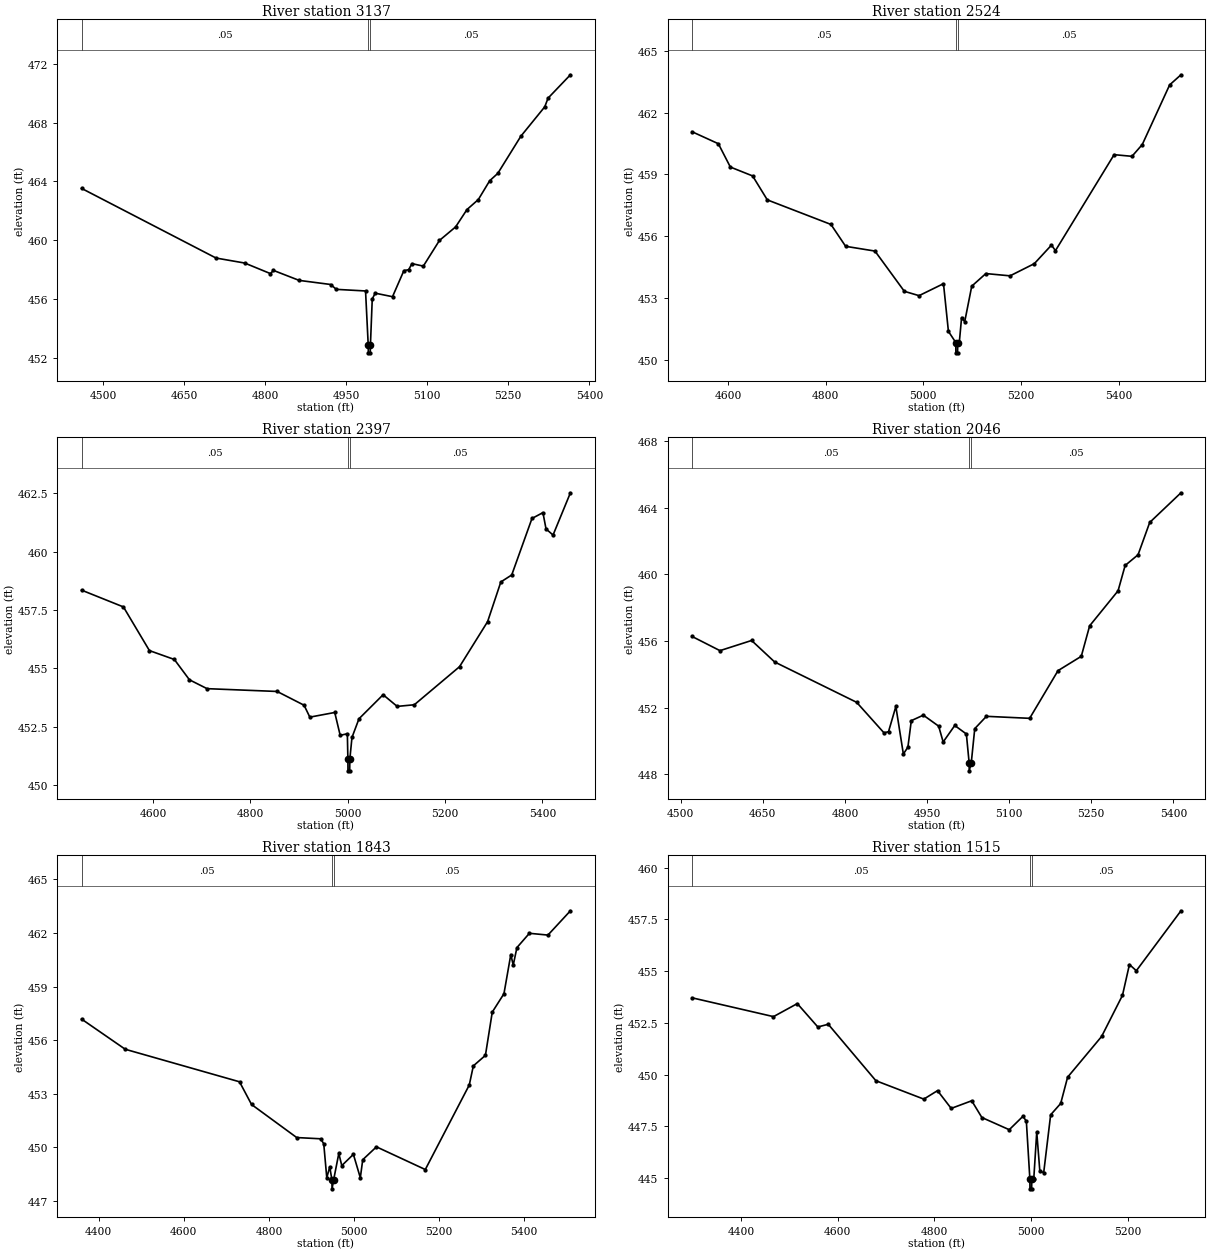
Type RM Length L Ch R = 1,3137,613,613,613
BEGIN DESCRIPTION:
Lacy 089 3479
END DESCRIPTION:
XS GIS Cut Line= 3
      2732626.82      6886615.91      2732416.83      6886113.11
      2732215.55      6885814.99
#Sta/Elev= 30
  4460.4  463.53  4709.3  458.79  4762.3  458.45  4810.0  457.73  4815.4  457.95
  4863.0  457.27  4921.5  456.99  4931.7  456.66  4985.9  456.55  4990.9  452.84
  4991.1  452.34  4994.6  452.34  4994.9  452.84  4998.3  456.00  5003.7  456.40
  5035.8  456.16  5056.8  457.93  5065.7  458.00  5071.8  458.41  5092.8  458.24
  5122.7  459.99  5152.6  460.91  5173.6  462.09  5194.6  462.77  5215.6  464.05
  5230.6  464.55  5273.3  467.08  5317.5  469.08  5323.6  469.67  5365.0  471.26
#Mann=3,-1,0
  4460.4    0.05       0  4990.9    0.04       0  4994.9    0.05       0
Bank Sta=4990.9,4994.9
Exp/Cntr=0.3,0.1

Type RM Length L Ch R = 1,2524,127,127,127
BEGIN DESCRIPTION:
Lacy 089 1912
END DESCRIPTION:
XS GIS Cut Line= 3
      2732835.17      6886574.69      2732875.87      6886031.85
      2732517.26      6885748.02
#Sta/Elev= 30
  4526.2  461.07  4580.0  460.49  4604.6  459.36  4650.2  458.93  4680.3  457.77
  4810.7  456.58  4840.8  455.52  4900.9  455.29  4961.1  453.34  4991.2  453.13
  5041.3  453.71  5051.4  451.40  5066.5  450.86  5066.7  450.36  5070.2  450.36
  5070.5  450.86  5073.7  450.86  5078.4  452.07  5084.8  451.87  5099.2  453.59
  5128.1  454.20  5177.7  454.09  5227.4  454.68  5262.6  455.58  5270.7  455.31
  5390.9  459.96  5427.5  459.88  5448.6  460.45  5504.7  463.34  5527.9  463.83
#Mann=3,-1,0
  4526.2    0.05       0  5066.5    0.04       0  5070.5    0.05       0
Bank Sta=5066.5,5070.5
Exp/Cntr=0.3,0.1

Type RM Length L Ch R = 1,2397,351,351,351
BEGIN DESCRIPTION:
Lacy 089 1911
END DESCRIPTION:
XS GIS Cut Line= 3
      2733447.18      6886190.82      2732932.15      6886008.94
      2732573.57      6885723.36
#Sta/Elev= 30
  4452.9  458.35  4539.0  457.63  4592.4  455.76  4643.6  455.38  4674.6  454.51
  4710.8  454.13  4854.8  454.01  4910.2  453.42  4922.0  452.91  4973.2  453.11
  4984.4  452.13  4999.1  452.20  5000.2  451.11  5000.4  450.61  5003.9  450.61
  5004.2  451.11  5008.6  452.04  5023.0  452.84  5072.6  453.87  5101.5  453.37
  5136.7  453.44  5229.6  455.07  5287.3  457.00  5314.5  458.70  5336.9  459.00
  5378.5  461.42  5401.0  461.67  5407.4  460.97  5421.8  460.71  5457.5  462.52
#Mann=3,-1,0
  4452.9    0.05       0  5000.2    0.04       0  5004.2    0.05       0
Bank Sta=5000.2,5004.2
Exp/Cntr=0.3,0.1

Type RM Length L Ch R = 1,2046,203,203,203
BEGIN DESCRIPTION:
Lacy 089 1910
END DESCRIPTION:
XS GIS Cut Line= 3
      2733422.69      6885985.89      2733045.08      6885699.89
      2732689.51      6885477.66
#Sta/Elev= 30
  4520.9  456.27  4571.8  455.42  4629.6  456.03  4671.7  454.74  4821.5  452.32
  4871.4  450.49  4879.7  450.56  4893.1  452.07  4906.8  449.22  4915.1  449.63
  4921.3  451.22  4943.3  451.55  4971.3  450.89  4979.5  449.94  5000.7  450.93
  5021.9  450.42  5026.9  448.71  5027.1  448.21  5030.9  448.71  5037.2  450.74
  5058.5  451.48  5137.5  451.36  5189.3  454.22  5231.8  455.08  5247.1  456.91
  5299.0  459.01  5311.9  460.53  5335.5  461.17  5356.8  463.11  5413.9  464.89
#Mann=3,-1,0
  4520.9    0.05       0  5026.9    0.04       0  5030.9    0.05       0
Bank Sta=5026.9,5030.9
Exp/Cntr=0.3,0.1

Type RM Length L Ch R = 1,1843,328,328,328
BEGIN DESCRIPTION:
Lacy 089 1919
END DESCRIPTION:
XS GIS Cut Line= 3
      2733609.08      6885983.40      2733152.42      6885534.15
      2732705.62      6885290.11
#Sta/Elev= 30
  4359.4  457.18  4462.2  455.49  4730.9  453.67  4759.2  452.40  4865.4  450.55
  4921.9  450.48  4929.0  450.20  4936.1  448.30  4943.1  448.91  4948.2  448.18
  4948.5  447.68  4952.2  448.18  4964.4  449.66  4971.4  448.98  4998.7  449.61
  5015.0  448.30  5020.7  449.31  5052.9  450.03  5167.8  448.76  5271.2  453.49
  5280.8  454.56  5309.2  455.15  5325.3  457.57  5352.8  458.60  5368.9  460.79
  5374.6  460.20  5383.3  461.18  5412.6  461.98  5456.2  461.88  5509.1  463.24
#Mann=3,-1,0
  4359.4    0.05       0  4948.2    0.04       0  4952.2    0.05       0
Bank Sta=4948.2,4952.2
Exp/Cntr=0.3,0.1

Type RM Length L Ch R = 1,1515,197,197,197
BEGIN DESCRIPTION:
Lacy 089 1918
END DESCRIPTION:
XS GIS Cut Line= 3
      2733623.35      6885751.66      2733107.96      6885273.62
      2732867.59      6885079.21
#Sta/Elev= 30
  4298.5  453.71  4467.0  452.80  4516.3  453.43  4558.8  452.30  4580.4  452.43
  4679.0  449.70  4778.2  448.81  4806.6  449.22  4834.9  448.36  4877.4  448.73
  4898.4  447.92  4955.1  447.33  4983.5  447.98  4990.5  447.74  4997.7  444.97
  4998.0  444.47  5001.5  444.47  5001.7  444.97  5005.9  444.97  5012.0  447.22
  5018.4  445.33  5026.4  445.25  5040.8  448.05  5061.6  448.60  5075.9  449.87
  5146.3  451.84  5189.5  453.83  5203.9  455.32  5218.2  455.02  5310.6  457.92
#Mann=3,-1,0
  4298.5    0.05       0  4997.7    0.04       0  5001.7    0.05       0
Bank Sta=4997.7,5001.7
Exp/Cntr=0.3,0.1

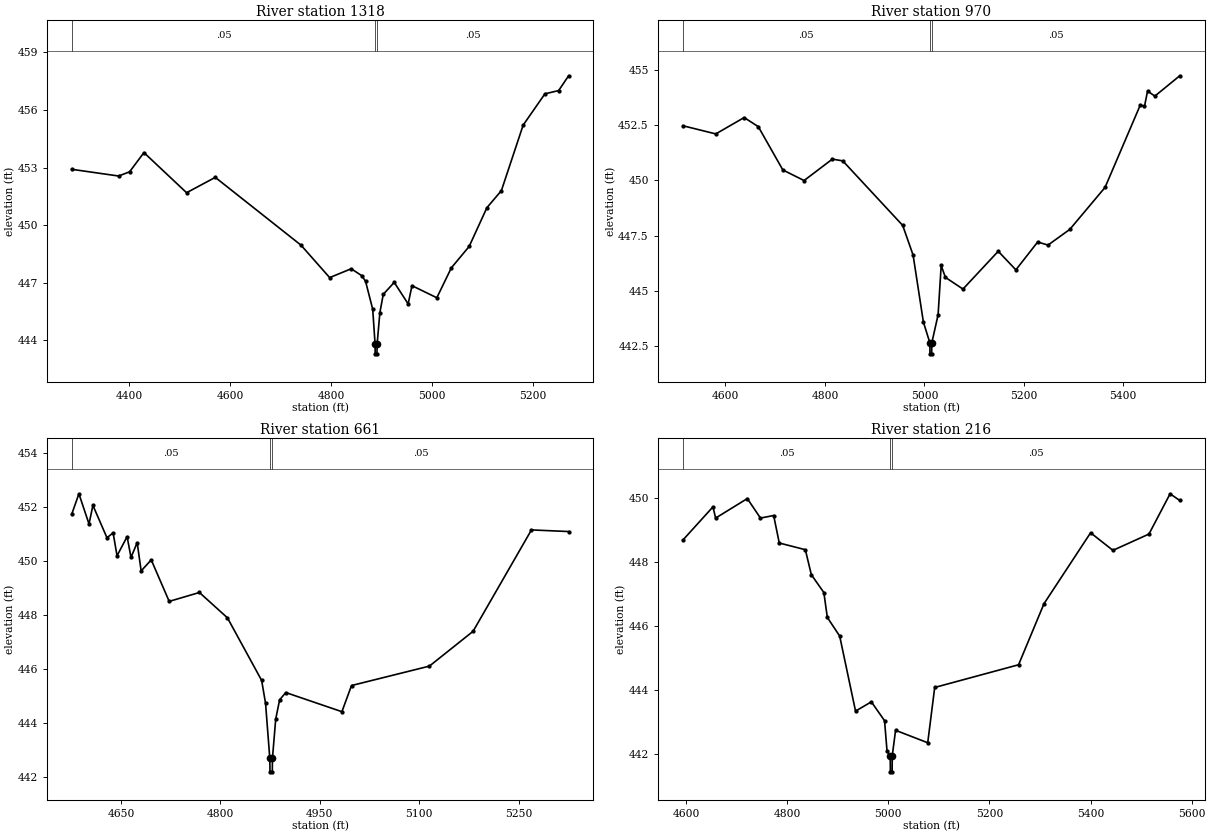
Type RM Length L Ch R = 1,1318,348,348,348
BEGIN DESCRIPTION:
Lacy 089 1917
END DESCRIPTION:
XS GIS Cut Line= 3
      2733753.19      6885595.39      2733220.08      6885120.28
      2733010.49      6884949.59
#Sta/Elev= 30
  4285.9  452.91  4378.9  452.56  4400.6  452.78  4429.0  453.78  4513.5  451.69
  4570.3  452.49  4740.1  448.96  4796.9  447.27  4839.6  447.73  4860.5  447.37
  4868.0  447.08  4882.2  445.62  4886.9  443.80  4887.1  443.30  4890.6  443.30
  4890.9  443.80  4896.4  445.45  4903.1  446.40  4924.8  447.02  4952.4  445.90
  4960.0  446.85  5009.2  446.22  5038.0  447.78  5073.2  448.89  5108.4  450.91
  5137.1  451.80  5180.2  455.21  5223.3  456.84  5250.5  457.01  5270.3  457.78
#Mann=3,-1,0
  4285.9    0.05       0  4886.9    0.04       0  4890.9    0.05       0
Bank Sta=4886.9,4890.9
Exp/Cntr=0.3,0.1

Type RM Length L Ch R = 1,970,309,309,309
BEGIN DESCRIPTION:
Lacy 089 1916
END DESCRIPTION:
XS GIS Cut Line= 3
      2733853.02      6885467.85      2733532.43      6885102.98
      2733120.62      6884796.24
#Sta/Elev= 30
  4514.3  452.47  4580.6  452.10  4637.6  452.84  4666.0  452.43  4715.4  450.47
  4758.1  449.99  4815.0  450.96  4835.9  450.88  4956.4  447.96  4977.3  446.62
  4998.0  443.59  5011.0  442.65  5011.2  442.15  5014.7  442.15  5015.0  442.65
  5027.6  443.92  5033.8  446.15  5042.2  445.61  5077.6  445.08  5148.5  446.79
  5184.0  445.95  5227.8  447.21  5248.6  447.07  5292.4  447.78  5363.3  449.68
  5434.2  453.41  5442.6  453.35  5448.8  454.04  5463.4  453.81  5513.5  454.73
#Mann=3,-1,0
  4514.3    0.05       0  5011.0    0.04       0  5015.0    0.05       0
Bank Sta=5011,5015
Exp/Cntr=0.3,0.1

Type RM Length L Ch R = 1,661,445,445,445
BEGIN DESCRIPTION:
Lacy 089 1915
END DESCRIPTION:
XS GIS Cut Line= 3
      2733909.56      6885062.23      2733551.96      6884833.67
      2733271.94      6884667.92
#Sta/Elev= 30
  4575.6  451.73  4586.5  452.49  4601.7  451.37  4607.6  452.06  4628.8  450.86
  4638.1  451.04  4644.0  450.19  4659.2  450.90  4665.1  450.13  4674.4  450.68
  4680.4  449.63  4695.6  450.04  4722.7  448.50  4768.3  448.83  4810.6  447.89
  4862.2  445.57  4868.1  444.72  4874.5  442.68  4874.8  442.18  4878.3  442.18
  4878.5  442.68  4883.4  444.13  4889.3  444.85  4898.6  445.12  4983.3  444.41
  4997.8  445.38  5115.3  446.10  5181.2  447.39  5269.3  451.15  5325.4  451.09
#Mann=3,-1,0
  4575.6    0.05       0  4874.5    0.04       0  4878.5    0.05       0
Bank Sta=4874.5,4878.5
Exp/Cntr=0.3,0.1

Type RM Length L Ch R = 1,216,0,0,0
BEGIN DESCRIPTION:
Lacy 089 1914
END DESCRIPTION:
XS GIS Cut Line= 3
      2734030.54      6884971.56      2733899.31      6884586.72
      2733430.50      6884251.22
#Sta/Elev= 30
  4593.4  448.68  4653.0  449.72  4658.3  449.37  4721.0  449.98  4747.0  449.37
  4773.1  449.45  4784.2  448.59  4835.8  448.38  4847.6  447.60  4872.4  447.04
  4879.3  446.26  4903.7  445.68  4935.1  443.33  4966.4  443.62  4992.5  443.03
  4997.4  442.08  5003.7  441.93  5004.0  441.43  5007.5  441.43  5007.7  441.93
  5014.3  442.73  5077.9  442.34  5091.7  444.07  5257.6  444.78  5307.9  446.69
  5400.1  448.91  5444.3  448.36  5515.6  448.87  5557.4  450.13  5576.5  449.92
#Mann=3,-1,0
  4593.4    0.05       0  5003.7    0.04       0  5007.7    0.05       0
Bank Sta=5003.7,5007.7
Exp/Cntr=0.3,0.1

Chan Stop Cuts=-1