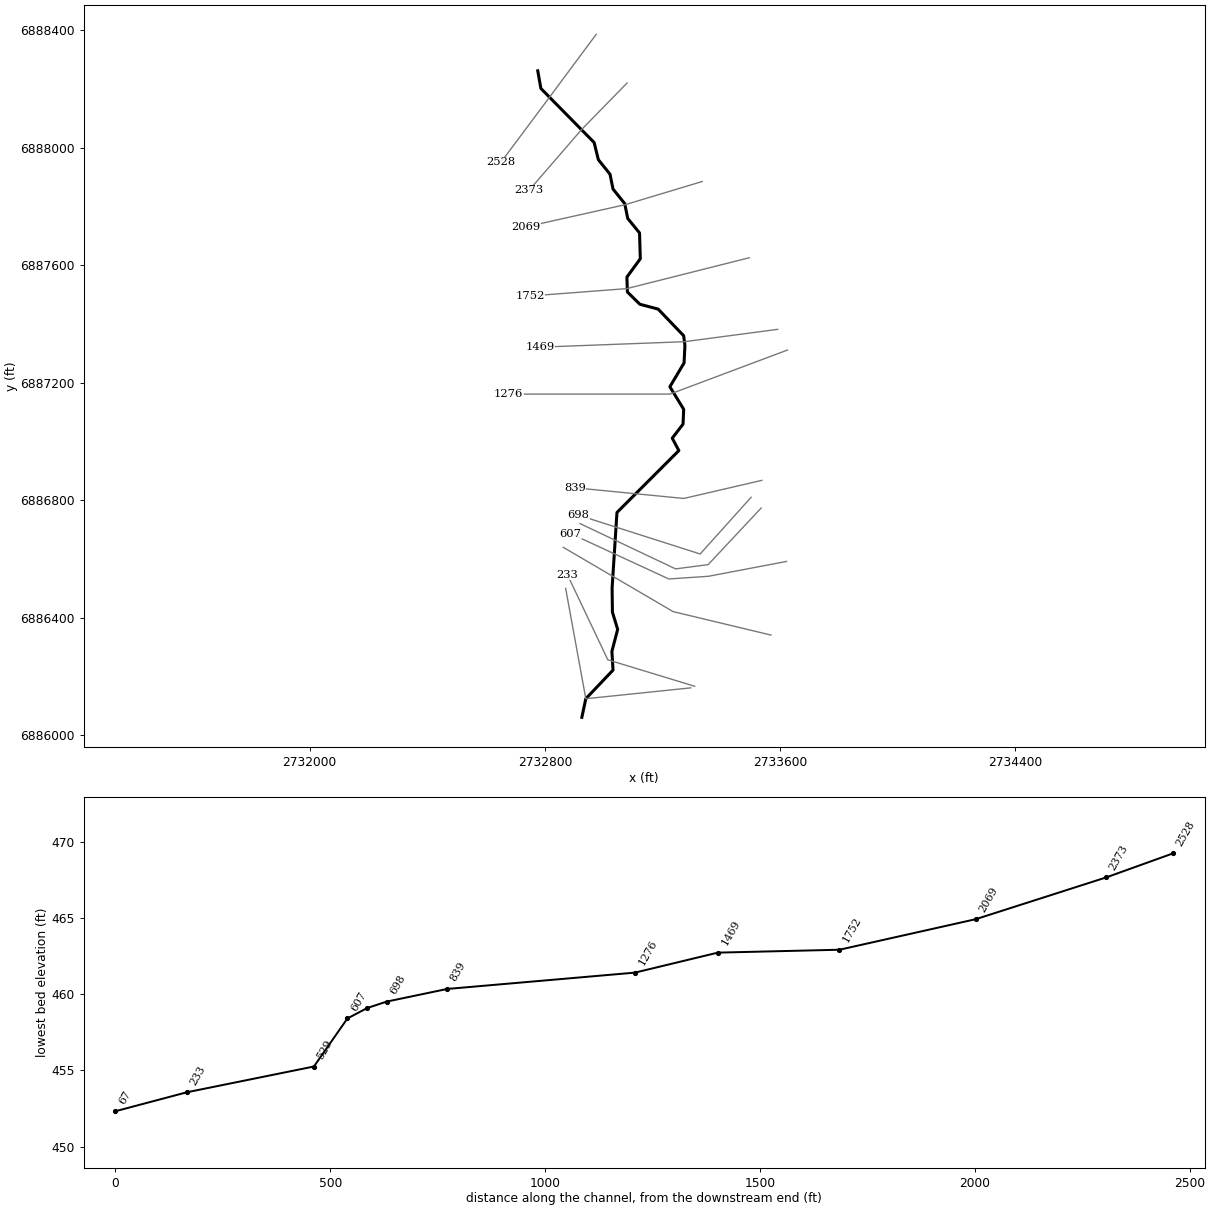
--- Lacy 090.prj (project) ---

Proj Title=Lacy 090 Base Level Engineering
Current Plan=p01
Default Exp/Contr=0.3,0.1
English Units
Geom File=g01
Flow File=f01
Plan File=p01
BEGIN DESCRIPTION:
Lacy 090
END DESCRIPTION:

--- Lacy 090.p01 (plan) ---

Plan Title=Multiple Run
Short Identifier=Multiple
Geom File=g01
Flow File=f01
Subcritical Flow
K Sum by GR= 0
Std Step Tol= 0.01
Critical Tol= 0.01
Num of Std Step Trials= 20
Max Error Tol= 0.3
Flow Tol Ratio= 0.001
Split Flow NTrial= 30
Split Flow Tol= 0.02
Split Flow Ratio= 0.02
Log Output Level= 0
Friction Slope Method= 1
Unsteady Friction Slope Method= 2
Unsteady Bridges Friction Slope Method= 1
Parabolic Critical Depth
Global Vel Dist=  1 , 1 , 1
Global Log Level= 0
CheckData=True
Encroach Param= -1, 0, 0, 0
BEGIN DESCRIPTION:
Multiple Run
END DESCRIPTION:

--- Lacy 090.f01 (steady flow) ---

Flow Title=Multiple
Number of Profiles=7
Profile Names=10-year,25-year,50-year,1pct_min,100-year,1pct_plu,500-year
River Rch & RM= Lacy 090,Reach-1,2528
     215     267     306     175     349     696     451
Boundary for River Rch & Prof#=Lacy 090,Reach-1,1
Up Type=0
Dn Type=3
Dn Slope=0.005
Boundary for River Rch & Prof#=Lacy 090,Reach-1,2
Up Type=0
Dn Type=3
Dn Slope=0.005
Boundary for River Rch & Prof#=Lacy 090,Reach-1,3
Up Type=0
Dn Type=3
Dn Slope=0.005
Boundary for River Rch & Prof#=Lacy 090,Reach-1,4
Up Type=0
Dn Type=3
Dn Slope=0.005
Boundary for River Rch & Prof#=Lacy 090,Reach-1,5
Up Type=0
Dn Type=3
Dn Slope=0.005
Boundary for River Rch & Prof#=Lacy 090,Reach-1,6
Up Type=0
Dn Type=3
Dn Slope=0.005
Boundary for River Rch & Prof#=Lacy 090,Reach-1,7
Up Type=0
Dn Type=3
Dn Slope=0.005

--- Lacy 090.g01 (geometry) ---

Geom Title=Existing Conditions

River Reach=Lacy 090,Reach-1
Reach XY= 30
      2732776.00      6888261.00      2732786.52      6888201.21
      2732967.86      6888017.06      2732982.10      6887958.81
      2733021.84      6887909.28      2733032.08      6887858.80
      2733071.84      6887809.28      2733082.12      6887758.82
      2733122.33      6887709.42      2733124.88      6887621.54
      2733079.33      6887559.22      2733080.99      6887508.45
      2733123.39      6887466.75      2733185.68      6887450.22
      2733272.54      6887359.52      2733276.77      6887326.09
      2733273.81      6887266.97      2733225.61      6887186.00
      2733272.57      6887109.26      2733270.35      6887058.71
      2733233.59      6887011.01      2733256.12      6886968.73
      2733045.47      6886758.11      2733028.94      6886500.94
      2733030.02      6886419.11      2733047.88      6886360.31
      2733028.26      6886285.47      2733032.10      6886221.74
      2732939.47      6886124.28      2732926.00      6886061.00

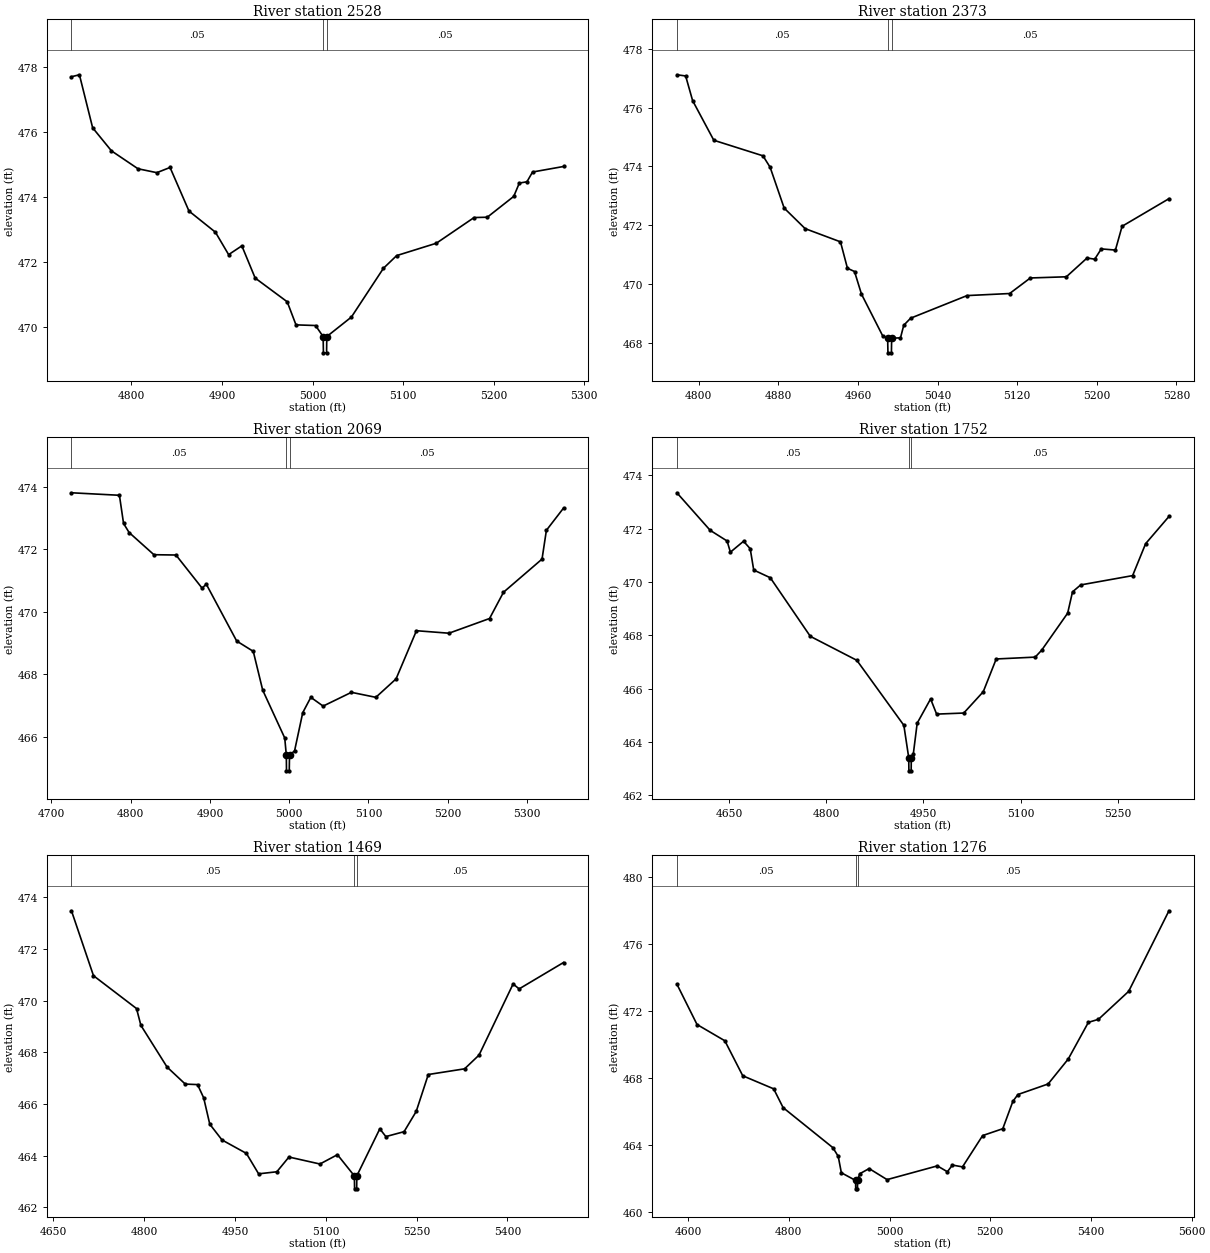
Type RM Length L Ch R = 1,2528,155,155,155
BEGIN DESCRIPTION:
Lacy 090 1931
END DESCRIPTION:
XS GIS Cut Line= 3
      2732974.71      6888385.12      2732815.96      6888171.31
      2732650.07      6887949.23
#Sta/Elev= 30
  4733.7  477.71  4742.5  477.77  4757.1  476.14  4777.9  475.43  4807.2  474.88
  4828.0  474.76  4842.6  474.92  4863.5  473.58  4892.7  472.93  4907.3  472.24
  4921.9  472.51  4936.6  471.52  4972.0  470.79  4981.7  470.08  5003.3  470.06
  5011.7  469.72  5012.0  469.22  5015.5  469.22  5015.7  469.72  5042.9  470.32
  5078.3  471.82  5092.9  472.21  5136.7  472.59  5178.4  473.38  5193.0  473.39
  5222.2  474.03  5228.4  474.44  5236.8  474.48  5243.0  474.78  5277.2  474.95
#Mann=3,-1,0
  4733.7    0.05       0  5011.7    0.04       0  5015.7    0.05       0
Bank Sta=5011.7,5015.7
Exp/Cntr=0.3,0.1

Type RM Length L Ch R = 1,2373,304,304,304
BEGIN DESCRIPTION:
Lacy 090 1930
END DESCRIPTION:
XS GIS Cut Line= 3
      2733079.80      6888219.57      2732924.72      6888060.87
      2732746.45      6887854.64
#Sta/Elev= 30
  4778.1  477.12  4786.9  477.08  4793.9  476.24  4815.2  474.89  4864.6  474.36
  4871.8  473.97  4885.9  472.58  4907.0  471.88  4942.5  471.43  4949.5  470.53
  4956.6  470.42  4963.6  469.65  4984.9  468.23  4989.9  468.15  4990.2  467.65
  4993.7  467.65  4993.9  468.15  5002.8  468.16  5006.1  468.59  5013.0  468.83
  5069.7  469.60  5112.5  469.67  5133.3  470.20  5169.5  470.24  5190.3  470.88
  5198.0  470.84  5204.6  471.19  5218.8  471.15  5225.5  471.96  5272.6  472.90
#Mann=3,-1,0
  4778.1    0.05       0  4989.9    0.04       0  4993.9    0.05       0
Bank Sta=4989.9,4993.9
Exp/Cntr=0.3,0.1

Type RM Length L Ch R = 1,2069,317,317,317
BEGIN DESCRIPTION:
Lacy 090 1923
END DESCRIPTION:
XS GIS Cut Line= 3
      2733335.60      6887884.45      2733073.46      6887805.54
      2732734.94      6887730.01
#Sta/Elev= 30
  4725.4  473.80  4785.9  473.72  4791.1  472.82  4798.1  472.53  4829.4  471.82
  4857.2  471.81  4890.2  470.75  4895.4  470.88  4933.8  469.06  4954.7  468.73
  4966.6  467.49  4994.4  465.96  4996.4  465.41  4996.6  464.91  5000.1  464.91
  5000.4  465.41  5006.8  465.55  5017.1  466.77  5027.3  467.26  5042.8  466.98
  5078.5  467.42  5109.3  467.26  5134.8  467.85  5160.5  469.39  5201.5  469.31
  5252.7  469.78  5270.3  470.62  5318.9  471.68  5324.4  472.60  5346.0  473.31
#Mann=3,-1,0
  4725.4    0.05       0  4996.4    0.04       0  5000.4    0.05       0
Bank Sta=4996.4,5000.4
Exp/Cntr=0.3,0.1

Type RM Length L Ch R = 1,1752,283,283,283
BEGIN DESCRIPTION:
Lacy 090 1921
END DESCRIPTION:
XS GIS Cut Line= 3
      2733495.80      6887625.02      2733078.74      6887519.92
      2732750.09      6887494.88
#Sta/Elev= 30
  4569.4  473.35  4620.8  471.94  4646.9  471.54  4652.0  471.12  4672.3  471.53
  4682.6  471.25  4688.0  470.45  4713.6  470.16  4775.4  467.96  4847.2  467.06
  4919.8  464.62  4927.3  463.41  4927.6  462.91  4931.1  462.91  4931.3  463.41
  4934.5  463.56  4940.4  464.70  4961.1  465.61  4970.4  465.04  5012.3  465.08
  5042.4  465.88  5062.4  467.11  5122.6  467.18  5132.6  467.44  5172.7  468.83
  5180.2  469.63  5192.8  469.89  5273.0  470.24  5293.1  471.44  5329.1  472.46
#Mann=3,-1,0
  4569.4    0.05       0  4927.3    0.04       0  4931.3    0.05       0
Bank Sta=4927.3,4931.3
Exp/Cntr=0.3,0.1

Type RM Length L Ch R = 1,1469,193,193,193
BEGIN DESCRIPTION:
Lacy 090 1922
END DESCRIPTION:
XS GIS Cut Line= 3
      2733592.52      6887381.39      2733275.18      6887339.26
      2732782.76      6887320.70
#Sta/Elev= 30
  4679.8  473.47  4716.2  470.96  4787.3  469.69  4794.5  469.04  4837.7  467.43
  4867.8  466.77  4888.1  466.75  4898.2  466.24  4908.3  465.22  4928.5  464.61
  4968.8  464.09  4989.0  463.30  5019.1  463.38  5039.1  463.95  5090.3  463.68
  5119.2  464.04  5147.2  463.22  5147.5  462.72  5151.0  462.72  5151.2  463.22
  5189.2  465.04  5199.2  464.74  5229.3  464.93  5249.3  465.71  5269.3  467.14
  5329.3  467.36  5353.1  467.89  5409.4  470.64  5419.4  470.45  5492.7  471.47
#Mann=3,-1,0
  4679.8    0.05       0  5147.2    0.04       0  5151.2    0.05       0
Bank Sta=5147.2,5151.2
Exp/Cntr=0.3,0.1

Type RM Length L Ch R = 1,1276,437,437,437
BEGIN DESCRIPTION:
Lacy 090 83
END DESCRIPTION:
XS GIS Cut Line= 3
      2733625.99      6887311.00      2733226.00      6887161.00
      2732675.99      6887161.00
#Sta/Elev= 30
  4577.7  473.63  4617.7  471.22  4672.9  470.25  4708.5  468.16  4769.9  467.38
  4788.6  466.26  4887.4  463.87  4898.1  463.35  4904.3  462.37  4932.6  461.91
  4932.8  461.41  4936.3  461.41  4936.6  461.91  4940.8  462.31  4959.5  462.62
  4995.1  461.96  5094.9  462.78  5114.9  462.43  5124.9  462.83  5144.9  462.72
  5184.9  464.59  5224.9  465.00  5244.9  466.63  5254.9  467.04  5314.9  467.67
  5354.9  469.16  5394.9  471.35  5414.9  471.53  5474.9  473.20  5554.9  478.01
#Mann=3,-1,0
  4577.7    0.05       0  4932.6    0.04       0  4936.6    0.05       0
Bank Sta=4932.6,4936.6
Exp/Cntr=0.3,0.1

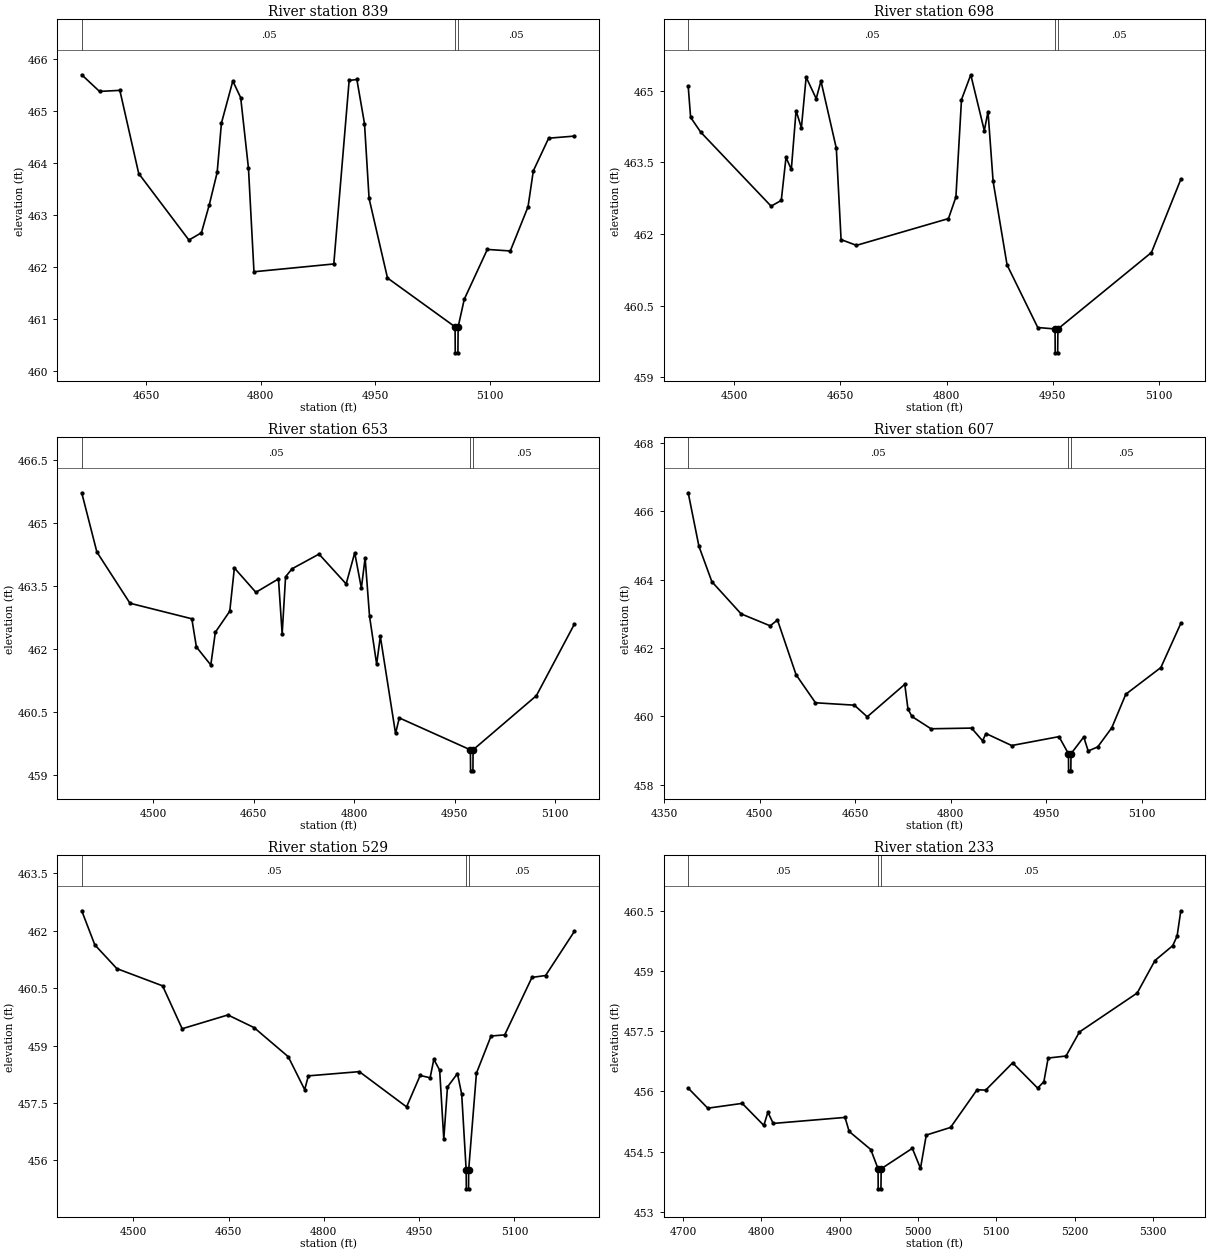
Type RM Length L Ch R = 1,839,141,141,141
BEGIN DESCRIPTION:
Lacy 090 1920
END DESCRIPTION:
XS GIS Cut Line= 3
      2733538.66      6886867.52      2733273.11      6886805.82
      2732902.60      6886842.09
#Sta/Elev= 30
  4565.9  465.69  4589.2  465.37  4615.8  465.39  4640.5  463.79  4706.2  462.51
  4722.6  462.65  4732.9  463.19  4743.2  463.81  4748.8  464.76  4763.7  465.57
  4774.0  465.25  4784.2  463.89  4791.4  461.90  4895.9  462.05  4916.0  465.58
  4926.1  465.60  4936.1  464.75  4942.1  463.31  4966.2  461.78  5054.7  460.84
  5054.9  460.34  5058.4  460.34  5058.7  460.84  5066.7  461.37  5096.9  462.33
  5127.0  462.30  5150.2  463.15  5157.1  463.84  5177.2  464.47  5210.8  464.51
#Mann=3,-1,0
  4565.9    0.05       0  5054.7    0.04       0  5058.7    0.05       0
Bank Sta=5054.7,5058.7
Exp/Cntr=0.3,0.1

Type RM Length L Ch R = 1,698,45,45,45
BEGIN DESCRIPTION:
Lacy 090 1929
END DESCRIPTION:
XS GIS Cut Line= 3
      2733502.05      6886809.93      2733328.56      6886616.89
      2732913.72      6886749.28
#Sta/Elev= 30
  4435.5  465.09  4438.9  464.44  4453.1  464.13  4552.5  462.58  4566.8  462.70
  4573.5  463.60  4581.0  463.35  4587.7  464.58  4595.2  464.22  4601.9  465.28
  4616.1  464.83  4622.8  465.20  4644.5  463.79  4651.2  461.88  4672.9  461.76
  4802.7  462.32  4813.2  462.77  4821.1  464.81  4834.2  465.33  4853.3  464.16
  4858.5  464.56  4865.7  463.10  4885.4  461.35  4928.7  460.04  4953.1  460.01
  4953.3  459.51  4956.8  459.51  4957.1  460.01  5089.1  461.61  5130.5  463.14
#Mann=3,-1,0
  4435.5    0.05       0  4953.1    0.04       0  4957.1    0.05       0
Bank Sta=4953.1,4957.1
Exp/Cntr=0.3,0.1

Type RM Length L Ch R = 1,653,46,46,46
BEGIN DESCRIPTION:
Lacy 090 1928
END DESCRIPTION:
XS GIS Cut Line= 4
      2733535.93      6886773.07      2733355.81      6886580.67
      2733244.85      6886566.17      2732919.91      6886720.30
#Sta/Elev= 30
  4393.5  465.71  4416.1  464.30  4465.5  463.08  4557.8  462.71  4564.6  462.04
  4586.1  461.61  4592.9  462.39  4614.4  462.89  4621.3  463.92  4653.4  463.34
  4687.1  463.66  4692.6  462.35  4697.7  463.71  4707.3  463.90  4747.6  464.25
  4788.1  463.54  4800.9  464.28  4810.8  463.44  4816.4  464.16  4823.0  462.77
  4833.6  461.63  4839.1  462.29  4861.8  459.98  4867.4  460.35  4973.5  459.59
  4973.8  459.09  4977.3  459.09  4977.5  459.59  5072.0  460.88  5128.6  462.58
#Mann=3,-1,0
  4393.5    0.05       0  4973.5    0.04       0  4977.5    0.05       0
Bank Sta=4973.5,4977.5
Exp/Cntr=0.3,0.1

Type RM Length L Ch R = 1,607,78,78,78
BEGIN DESCRIPTION:
Lacy 090 1927
END DESCRIPTION:
XS GIS Cut Line= 4
      2733622.51      6886591.54      2733356.71      6886540.97
      2733222.01      6886531.86      2732887.56      6886686.38
#Sta/Elev= 30
  4387.4  466.54  4404.2  464.98  4424.6  463.94  4470.5  463.00  4516.2  462.65
  4527.7  462.82  4556.9  461.22  4587.4  460.40  4648.5  460.33  4668.7  459.99
  4727.7  460.94  4732.7  460.22  4738.9  460.00  4768.9  459.64  4832.6  459.66
  4849.9  459.29  4855.4  459.50  4895.7  459.15  4970.0  459.41  4984.9  458.91
  4985.1  458.41  4988.6  458.41  4988.9  458.91  5008.9  459.40  5015.9  458.99
  5030.9  459.11  5053.0  459.67  5075.0  460.65  5130.1  461.43  5161.4  462.72
#Mann=3,-1,0
  4387.4    0.05       0  4984.9    0.04       0  4988.9    0.05       0
Bank Sta=4984.9,4988.9
Exp/Cntr=0.3,0.1

Type RM Length L Ch R = 1,529,296,296,296
BEGIN DESCRIPTION:
Lacy 090 1926
END DESCRIPTION:
XS GIS Cut Line= 3
      2733569.79      6886340.92      2733236.78      6886420.68
      2732863.00      6886639.40
#Sta/Elev= 30
  4418.8  462.52  4439.4  461.63  4474.1  461.01  4546.1  460.56  4576.9  459.44
  4648.9  459.80  4690.1  459.47  4743.9  458.71  4769.8  457.85  4775.6  458.21
  4855.8  458.32  4930.2  457.40  4951.6  458.22  4967.3  458.16  4973.1  458.64
  4982.3  458.36  4988.8  456.56  4994.6  457.92  5010.3  458.27  5017.0  457.73
  5024.0  455.76  5024.3  455.26  5027.8  455.26  5028.0  455.76  5040.2  458.28
  5063.2  459.25  5084.7  459.28  5127.6  460.78  5149.1  460.83  5194.3  461.98
#Mann=3,-1,0
  4418.8    0.05       0  5024.0    0.04       0  5028.0    0.05       0
Bank Sta=5024,5028
Exp/Cntr=0.3,0.1

Type RM Length L Ch R = 1,233,166,166,166
BEGIN DESCRIPTION:
Lacy 090 1925
END DESCRIPTION:
XS GIS Cut Line= 3
      2733309.88      6886166.79      2733014.32      6886256.79
      2732876.98      6886546.09
#Sta/Elev= 30
  4706.4  456.08  4731.4  455.58  4775.4  455.70  4803.0  455.15  4808.2  455.48
  4815.0  455.20  4906.7  455.35  4912.0  455.00  4939.6  454.55  4948.9  454.07
  4949.1  453.57  4952.6  453.57  4952.9  454.07  4992.7  454.58  5003.1  454.08
  5010.5  454.91  5041.5  455.10  5075.4  456.04  5086.4  456.03  5120.8  456.71
  5152.8  456.08  5160.7  456.24  5166.2  456.83  5189.0  456.88  5206.2  457.48
  5279.9  458.45  5302.6  459.26  5325.3  459.63  5330.9  459.87  5335.6  460.50
#Mann=3,-1,0
  4706.4    0.05       0  4948.9    0.04       0  4952.9    0.05       0
Bank Sta=4948.9,4952.9
Exp/Cntr=0.3,0.1

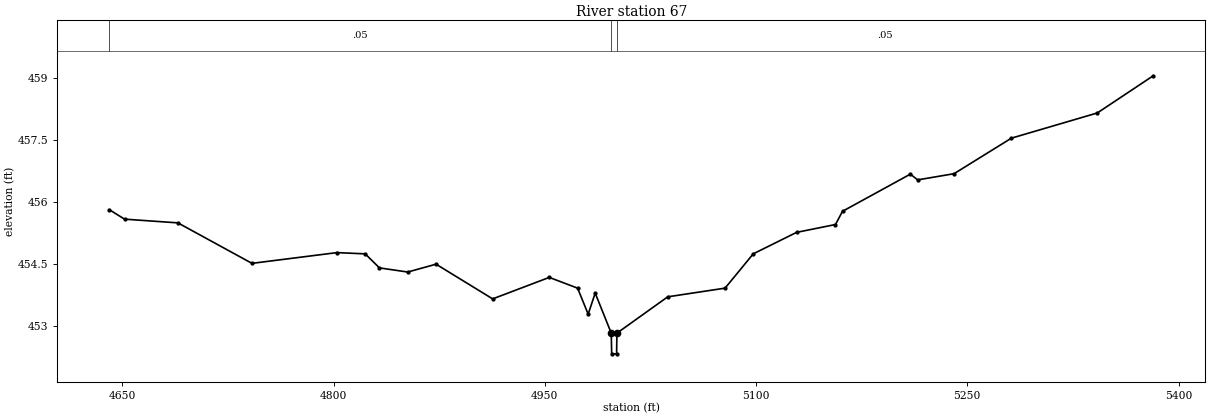
Type RM Length L Ch R = 1,67,0,0,0
BEGIN DESCRIPTION:
Lacy 090 1924
END DESCRIPTION:
XS GIS Cut Line= 3
      2733296.76      6886161.29      2732939.47      6886124.28
      2732870.83      6886500.06
#Sta/Elev= 30
  4640.8  455.82  4651.6  455.59  4689.5  455.50  4742.1  454.52  4802.4  454.78
  4822.5  454.75  4832.6  454.41  4852.7  454.31  4872.8  454.50  4913.0  453.66
  4953.2  454.18  4973.3  453.92  4980.8  453.29  4985.8  453.80  4997.2  452.83
  4997.5  452.33  5001.0  452.33  5001.2  452.83  5037.3  453.71  5078.0  453.92
  5098.0  454.75  5128.8  455.27  5156.4  455.46  5161.4  455.78  5209.6  456.68
  5214.7  456.54  5240.6  456.69  5281.3  457.55  5342.3  458.16  5382.0  459.06
#Mann=3,-1,0
  4640.8    0.05       0  4997.2    0.04       0  5001.2    0.05       0
Bank Sta=4997.2,5001.2
Exp/Cntr=0.3,0.1

Chan Stop Cuts=-1