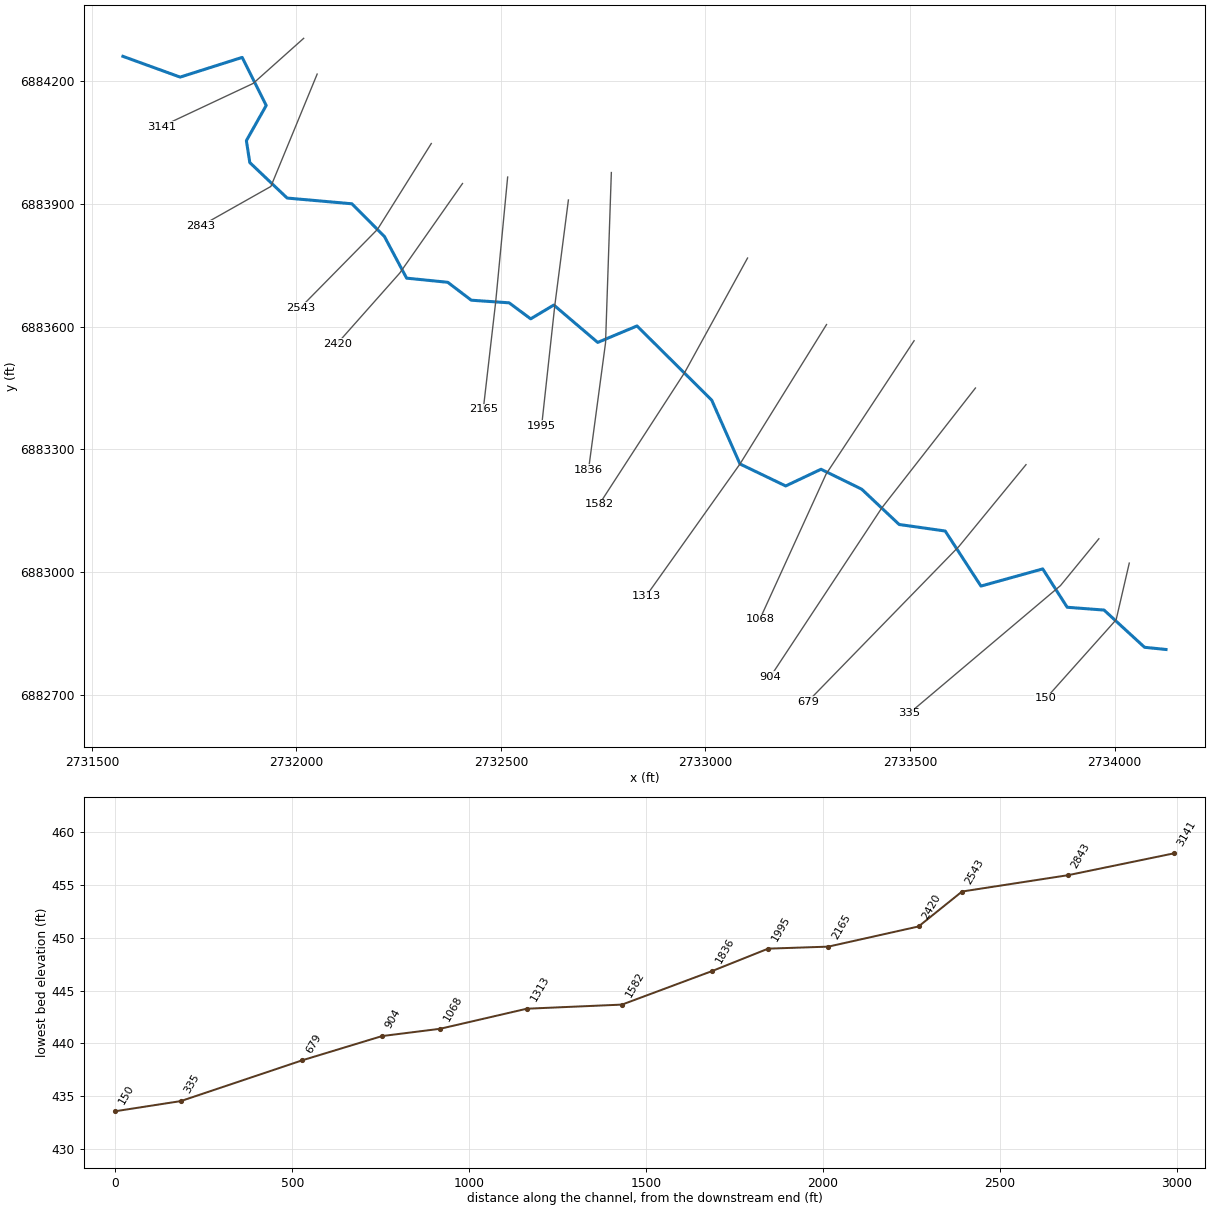
--- Lacy 091.prj (project) ---

Proj Title=Lacy 091 Base Level Engineering
Current Plan=p01
Default Exp/Contr=0.3,0.1
English Units
Geom File=g01
Flow File=f01
Plan File=p01
BEGIN DESCRIPTION:
Lacy 091
END DESCRIPTION:

--- Lacy 091.p01 (plan) ---

Plan Title=Multiple Run
Short Identifier=Multiple
Geom File=g01
Flow File=f01
Subcritical Flow
K Sum by GR= 0
Std Step Tol= 0.01
Critical Tol= 0.01
Num of Std Step Trials= 20
Max Error Tol= 0.3
Flow Tol Ratio= 0.001
Split Flow NTrial= 30
Split Flow Tol= 0.02
Split Flow Ratio= 0.02
Log Output Level= 0
Friction Slope Method= 1
Unsteady Friction Slope Method= 2
Unsteady Bridges Friction Slope Method= 1
Parabolic Critical Depth
Global Vel Dist=  1 , 1 , 1
Global Log Level= 0
CheckData=True
Encroach Param= -1, 0, 0, 0
BEGIN DESCRIPTION:
Multiple Run
END DESCRIPTION:

--- Lacy 091.f01 (steady flow) ---

Flow Title=Multiple
Number of Profiles=7
Profile Names=10-year,25-year,50-year,1pct_min,100-year,1pct_plu,500-year
River Rch & RM= Lacy 091,Reach-1,3141
     184     226     257     146     291     581     371
Boundary for River Rch & Prof#=Lacy 091,Reach-1,1
Up Type=0
Dn Type=3
Dn Slope=0.005
Boundary for River Rch & Prof#=Lacy 091,Reach-1,2
Up Type=0
Dn Type=3
Dn Slope=0.005
Boundary for River Rch & Prof#=Lacy 091,Reach-1,3
Up Type=0
Dn Type=3
Dn Slope=0.005
Boundary for River Rch & Prof#=Lacy 091,Reach-1,4
Up Type=0
Dn Type=3
Dn Slope=0.005
Boundary for River Rch & Prof#=Lacy 091,Reach-1,5
Up Type=0
Dn Type=3
Dn Slope=0.005
Boundary for River Rch & Prof#=Lacy 091,Reach-1,6
Up Type=0
Dn Type=3
Dn Slope=0.005
Boundary for River Rch & Prof#=Lacy 091,Reach-1,7
Up Type=0
Dn Type=3
Dn Slope=0.005

--- Lacy 091.g01 (geometry) ---

Geom Title=Existing Conditions

River Reach=Lacy 091,Reach-1
Reach XY= 30
      2731576.00      6884261.00      2731715.95      6884210.21
      2731867.54      6884258.38      2731926.29      6884140.84
      2731877.81      6884054.87      2731886.18      6884001.29
      2731977.45      6883914.54      2732135.82      6883900.53
      2732215.22      6883820.68      2732269.55      6883718.74
      2732370.02      6883708.64      2732427.60      6883664.85
      2732520.11      6883658.46      2732572.78      6883619.29
      2732629.33      6883652.99      2732736.64      6883561.66
      2732832.73      6883601.85      2733015.23      6883420.68
      2733084.46      6883264.50      2733196.19      6883210.77
      2733282.61      6883251.57      2733382.04      6883202.86
      2733473.58      6883116.54      2733586.10      6883100.61
      2733673.46      6882965.99      2733824.57      6883007.93
      2733884.35      6882914.19      2733974.43      6882907.36
      2734073.49      6882816.33      2734126.00      6882811.00

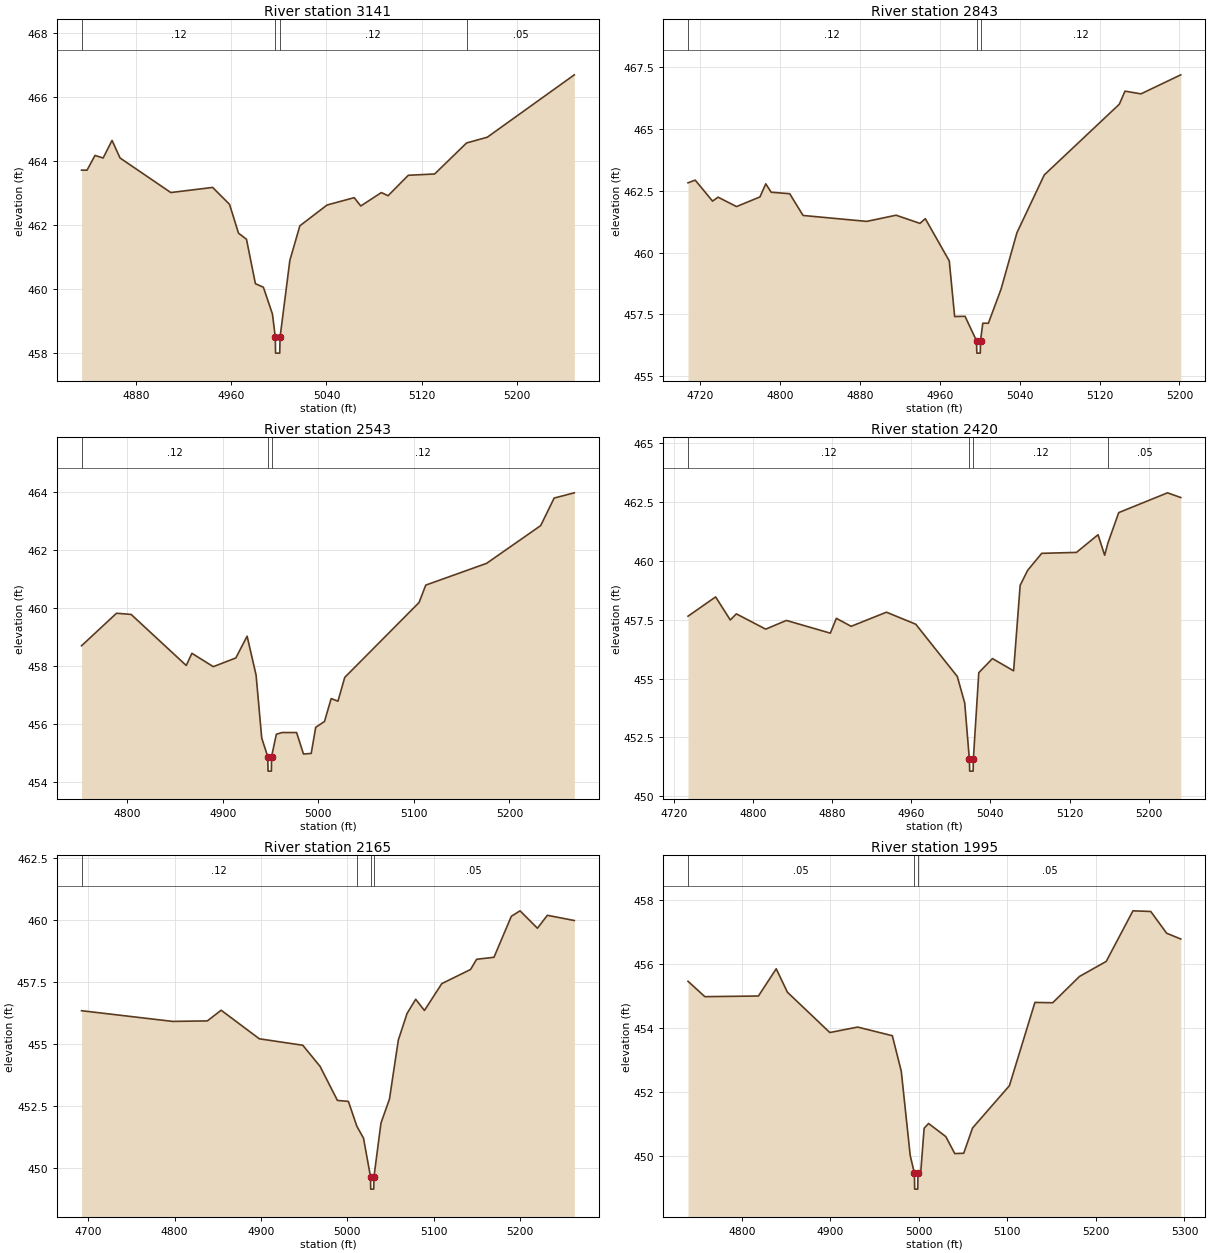
Type RM Length L Ch R = 1,3141,298,298,298
BEGIN DESCRIPTION:
Lacy 091 1882
END DESCRIPTION:
XS GIS Cut Line= 3
      2732017.86      6884304.99      2731894.41      6884194.76
      2731669.95      6884089.31
#Sta/Elev= 30
  4834.5  463.71  4839.1  463.71  4845.8  464.17  4852.6  464.09  4860.1  464.64
  4866.8  464.09  4909.4  463.01  4944.5  463.17  4958.7  462.64  4966.2  461.74
  4972.9  461.55  4980.4  460.16  4987.1  460.05  4994.7  459.21  4997.1  458.49
  4997.3  457.99  5000.8  457.99  5001.1  458.49  5009.3  460.89  5017.7  461.97
  5040.5  462.62  5063.3  462.85  5068.8  462.59  5086.1  463.01  5091.7  462.91
  5108.7  463.55  5130.8  463.59  5157.6  464.56  5175.0  464.74  5248.0  466.69
#Mann=4,-1,0
  4834.5    0.12       0  4997.1    0.07       0  5001.1    0.12       0
  5157.6    0.05       0
Bank Sta=4997.1,5001.1
Exp/Cntr=0.3,0.1

Type RM Length L Ch R = 1,2843,300,300,300
BEGIN DESCRIPTION:
Lacy 091 3481
END DESCRIPTION:
XS GIS Cut Line= 3
      2732050.87      6884217.63      2731937.70      6883942.91
      2731766.40      6883846.26
#Sta/Elev= 30
  4707.5  462.82  4714.7  462.93  4732.1  462.08  4737.6  462.24  4756.1  461.86
  4779.6  462.25  4785.4  462.78  4790.8  462.44  4809.4  462.38  4822.8  461.50
  4886.6  461.26  4916.0  461.51  4939.9  461.18  4945.3  461.37  4969.3  459.66
  4974.7  457.41  4985.1  457.42  4996.6  456.43  4996.9  455.93  5000.4  455.93
  5000.6  456.43  5002.9  457.14  5008.5  457.14  5021.2  458.52  5037.1  460.80
  5064.5  463.14  5139.7  466.00  5145.4  466.53  5161.4  466.42  5201.3  467.19
#Mann=3,-1,0
  4707.5    0.12       0  4996.6    0.07       0  5000.6    0.12       0
Bank Sta=4996.6,5000.6
Exp/Cntr=0.3,0.1

Type RM Length L Ch R = 1,2543,123,123,123
BEGIN DESCRIPTION:
Lacy 091 3480
END DESCRIPTION:
XS GIS Cut Line= 3
      2732329.85      6884047.86      2732198.40      6883838.08
      2732010.23      6883646.91
#Sta/Elev= 30
  4752.1  458.70  4788.7  459.82  4804.0  459.78  4861.7  458.02  4867.6  458.44
  4890.0  457.98  4913.6  458.28  4925.4  459.03  4934.8  457.69  4940.7  455.52
  4947.0  454.88  4947.3  454.38  4950.8  454.38  4951.0  454.88  4956.0  455.65
  4961.9  455.71  4977.2  455.71  4984.4  454.97  4992.5  454.99  4997.2  455.89
  5006.4  456.09  5013.4  456.88  5020.5  456.79  5027.6  457.61  5105.4  460.19
  5112.4  460.79  5176.1  461.54  5232.7  462.84  5246.8  463.79  5267.9  463.97
#Mann=3,-1,0
  4752.1    0.12       0  4947.0    0.07       0  4951.0    0.12       0
Bank Sta=4947,4951
Exp/Cntr=0.3,0.1

Type RM Length L Ch R = 1,2420,255,255,255
BEGIN DESCRIPTION:
Lacy 091 1871
END DESCRIPTION:
XS GIS Cut Line= 3
      2732406.14      6883950.09      2732252.88      6883731.34
      2732099.78      6883558.62
#Sta/Elev= 30
  4734.5  457.65  4762.4  458.47  4777.2  457.49  4783.3  457.75  4813.0  457.10
  4833.9  457.47  4878.3  456.93  4884.4  457.56  4899.3  457.22  4935.0  457.82
  4964.6  457.31  5006.6  455.09  5014.1  453.96  5018.8  451.57  5019.1  451.07
  5022.6  451.07  5022.8  451.57  5028.3  455.25  5042.1  455.85  5063.5  455.33
  5070.1  458.96  5077.7  459.60  5091.9  460.32  5127.0  460.36  5148.8  461.11
  5155.5  460.24  5158.8  460.76  5169.7  462.05  5219.0  462.89  5232.4  462.69
#Mann=4,-1,0
  4734.5    0.12       0  5018.8    0.07       0  5022.8    0.12       0
  5158.8    0.05       0
Bank Sta=5018.8,5022.8
Exp/Cntr=0.3,0.1

Type RM Length L Ch R = 1,2165,170,170,170
BEGIN DESCRIPTION:
Lacy 091 1870
END DESCRIPTION:
XS GIS Cut Line= 3
      2732516.51      6883965.89      2732487.27      6883660.75
      2732457.01      6883398.63
#Sta/Elev= 30
  4692.4  456.34  4797.8  455.91  4838.0  455.93  4854.0  456.36  4898.2  455.21
  4948.5  454.95  4968.5  454.10  4988.6  452.73  5001.3  452.69  5011.1  451.69
  5018.8  451.21  5026.9  449.66  5027.1  449.16  5030.6  449.16  5030.9  449.66
  5039.0  451.82  5048.8  452.78  5059.1  455.16  5069.2  456.23  5079.2  456.80
  5089.3  456.35  5109.4  457.43  5142.7  458.00  5149.7  458.41  5169.8  458.49
  5189.9  460.14  5200.0  460.36  5220.1  459.66  5231.6  460.18  5262.8  459.97
#Mann=4,-1,0
  4692.4    0.12       0  5011.1    0.05       0  5026.9    0.07       0
  5030.9    0.05       0
Bank Sta=5026.9,5030.9
Exp/Cntr=0.3,0.1

Type RM Length L Ch R = 1,1995,159,159,159
BEGIN DESCRIPTION:
Lacy 091 1869
END DESCRIPTION:
XS GIS Cut Line= 3
      2732665.03      6883909.82      2732631.86      6883652.58
      2732599.58      6883357.30
#Sta/Elev= 30
  4739.4  455.46  4758.4  454.98  4818.9  455.00  4839.0  455.85  4851.6  455.12
  4899.5  453.86  4931.0  454.03  4970.1  453.76  4980.2  452.65  4990.3  450.02
  4995.0  449.47  4995.3  448.97  4998.8  448.97  4999.0  449.47  5002.1  449.47
  5006.0  450.87  5011.0  451.02  5030.5  450.61  5040.6  450.08  5050.7  450.09
  5060.7  450.88  5102.3  452.20  5131.1  454.80  5151.2  454.79  5181.4  455.61
  5211.6  456.08  5241.8  457.66  5261.9  457.64  5279.9  456.96  5295.8  456.78
#Mann=3,-1,0
  4739.4    0.05       0  4995.0    0.04       0  4999.0    0.05       0
Bank Sta=4995,4999
Exp/Cntr=0.3,0.1

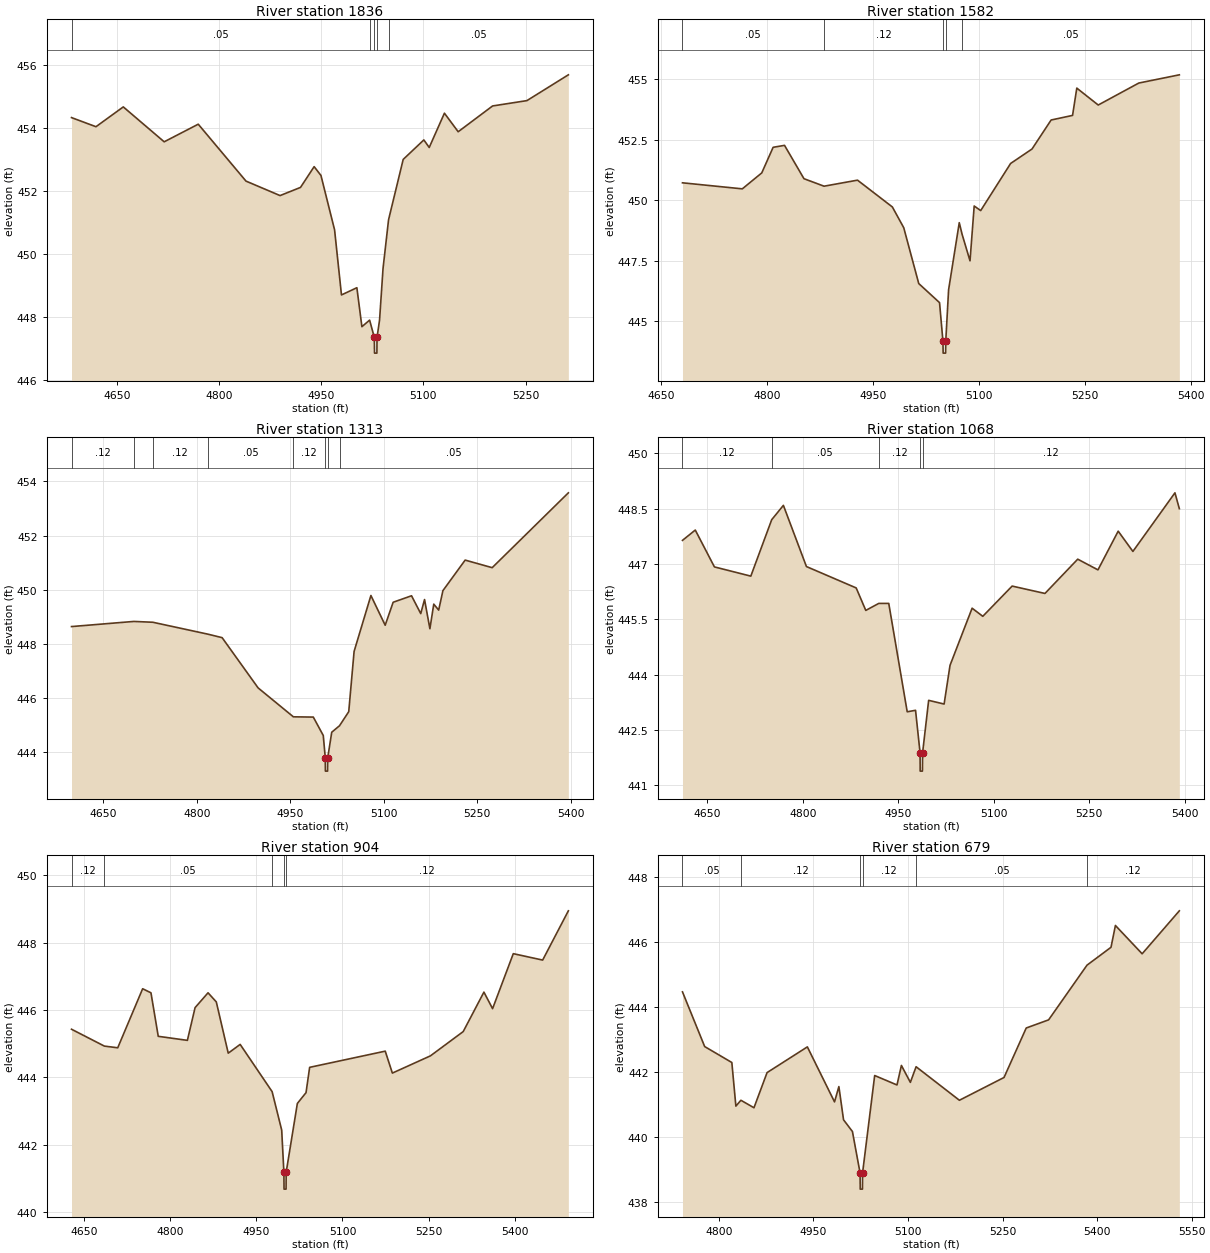
Type RM Length L Ch R = 1,1836,254,254,254
BEGIN DESCRIPTION:
Lacy 091 1881
END DESCRIPTION:
XS GIS Cut Line= 3
      2732770.00      6883976.92      2732755.84      6883560.76
      2732714.24      6883250.74
#Sta/Elev= 30
  4583.6  454.33  4619.5  454.04  4659.6  454.67  4719.6  453.56  4769.6  454.12
  4839.7  452.31  4889.7  451.85  4919.7  452.11  4939.7  452.77  4949.7  452.49
  4969.7  450.76  4979.8  448.69  5002.4  448.92  5009.8  447.68  5021.1  447.89
  5028.0  447.34  5028.3  446.84  5031.8  446.84  5032.0  447.34  5035.7  447.89
  5040.8  449.53  5048.9  451.08  5070.4  453.00  5100.7  453.62  5108.6  453.38
  5130.9  454.47  5151.1  453.88  5201.6  454.70  5252.0  454.87  5312.8  455.69
#Mann=5,-1,0
  4583.6    0.05       0  5021.1    0.12       0  5028.0    0.04       0
  5032.0    0.12       0  5048.9    0.05       0
Bank Sta=5028,5032
Exp/Cntr=0.3,0.1

Type RM Length L Ch R = 1,1582,269,269,269
BEGIN DESCRIPTION:
Lacy 091 1880
END DESCRIPTION:
XS GIS Cut Line= 3
      2733102.96      6883767.92      2732949.03      6883487.72
      2732740.79      6883166.40
#Sta/Elev= 30
  4680.3  450.72  4764.9  450.47  4792.4  451.13  4808.5  452.19  4824.6  452.27
  4852.1  450.89  4880.5  450.58  4927.8  450.83  4977.1  449.72  4993.2  448.86
  5014.4  446.55  5043.8  445.76  5048.6  444.17  5048.9  443.67  5052.4  443.67
  5052.6  444.17  5056.6  446.29  5071.7  449.07  5075.6  448.60  5086.9  447.49
  5092.8  449.76  5102.0  449.57  5144.3  451.52  5174.6  452.12  5201.6  453.32
  5231.9  453.51  5237.9  454.64  5268.2  453.94  5325.6  454.85  5382.9  455.19
#Mann=5,-1,0
  4680.3    0.05       0  4880.5    0.12       0  5048.6    0.07       0
  5052.6    0.12       0  5075.6    0.05       0
Bank Sta=5048.6,5052.6
Exp/Cntr=0.3,0.1

Type RM Length L Ch R = 1,1313,245,245,245
BEGIN DESCRIPTION:
Lacy 091 1879
END DESCRIPTION:
XS GIS Cut Line= 3
      2733296.06      6883605.36      2733084.46      6883264.50
      2732854.74      6882941.32
#Sta/Elev= 30
  4598.8  448.63  4698.8  448.82  4729.3  448.79  4817.6  448.35  4840.6  448.22
  4898.4  446.36  4955.0  445.29  4987.0  445.28  5003.0  444.60  5006.2  443.78
  5006.4  443.28  5009.9  443.28  5010.2  443.78  5016.6  444.72  5029.1  444.96
  5043.9  445.48  5052.5  447.71  5079.5  449.78  5102.4  448.68  5115.2  449.53
  5144.7  449.77  5159.5  449.11  5165.6  449.63  5174.2  448.55  5180.4  449.46
  5188.3  449.24  5195.1  449.96  5230.8  451.09  5274.2  450.81  5396.5  453.58
#Mann=8,-1,0
  4598.8    0.12       0  4698.8    0.05       0  4729.3    0.12       0
  4817.6    0.05       0  4955.0    0.12       0  5006.2    0.07       0
  5010.2    0.12       0  5029.1    0.05       0
Bank Sta=5006.2,5010.2
Exp/Cntr=0.3,0.1

Type RM Length L Ch R = 1,1068,164,164,164
BEGIN DESCRIPTION:
Lacy 091 1878
END DESCRIPTION:
XS GIS Cut Line= 3
      2733510.11      6883565.76      2733294.91      6883239.65
      2733132.91      6882884.68
#Sta/Elev= 30
  4610.9  447.64  4631.0  447.92  4661.1  446.92  4718.3  446.67  4751.1  448.20
  4769.5  448.59  4805.7  446.93  4883.9  446.35  4899.0  445.74  4919.4  445.93
  4935.1  445.93  4964.1  442.99  4977.2  443.03  4984.3  441.88  4984.5  441.38
  4988.0  441.38  4988.3  441.88  4997.8  443.30  5022.1  443.20  5031.4  444.25
  5066.1  445.80  5082.9  445.58  5129.0  446.40  5180.6  446.20  5232.1  447.13
  5263.9  446.84  5295.7  447.89  5318.8  447.34  5384.9  448.93  5391.8  448.50
#Mann=5,-1,0
  4610.9    0.12       0  4751.1    0.05       0  4919.4    0.12       0
  4984.3    0.07       0  4988.3    0.12       0
Bank Sta=4984.3,4988.3
Exp/Cntr=0.3,0.1

Type RM Length L Ch R = 1,904,225,225,225
BEGIN DESCRIPTION:
Lacy 091 1877
END DESCRIPTION:
XS GIS Cut Line= 3
      2733660.07      6883450.19      2733430.93      6883156.76
      2733158.92      6882744.63
#Sta/Elev= 30
  4627.7  445.43  4685.0  444.93  4708.3  444.88  4751.7  446.63  4766.2  446.51
  4778.9  445.22  4829.7  445.10  4843.1  446.07  4865.7  446.51  4880.1  446.24
  4900.9  444.72  4921.7  444.98  4977.4  443.58  4994.1  442.44  4997.9  441.19
  4998.2  440.69  5001.7  440.69  5001.9  441.19  5021.4  443.23  5036.5  443.55
  5042.8  444.30  5174.6  444.78  5187.0  444.13  5253.3  444.64  5310.5  445.36
  5346.6  446.53  5361.7  446.04  5397.8  447.67  5449.0  447.48  5493.8  448.94
#Mann=5,-1,0
  4627.7    0.12       0  4685.0    0.05       0  4977.4    0.12       0
  4997.9    0.07       0  5001.9    0.12       0
Bank Sta=4997.9,5001.9
Exp/Cntr=0.3,0.1

Type RM Length L Ch R = 1,679,344,344,344
BEGIN DESCRIPTION:
Lacy 091 1876
END DESCRIPTION:
XS GIS Cut Line= 3
      2733783.66      6883262.81      2733620.25      6883063.54
      2733250.12      6882683.50
#Sta/Elev= 30
  4742.3  444.46  4777.5  442.78  4820.6  442.29  4827.0  440.95  4835.0  441.13
  4855.7  440.90  4876.5  441.98  4940.4  442.77  4983.5  441.08  4990.4  441.55
  4997.8  440.53  5011.9  440.17  5024.0  438.90  5024.3  438.40  5027.8  438.40
  5028.0  438.90  5047.2  441.89  5082.6  441.60  5089.6  442.20  5103.8  441.68
  5112.9  442.16  5181.6  441.13  5252.4  441.83  5287.6  443.35  5323.1  443.60
  5384.0  445.28  5422.1  445.83  5429.1  446.50  5471.5  445.63  5530.5  446.95
#Mann=6,-1,0
  4742.3    0.05       0  4835.0    0.12       0  5024.0    0.07       0
  5028.0    0.12       0  5112.9    0.05       0  5384.0    0.12       0
Bank Sta=5024,5028
Exp/Cntr=0.3,0.1

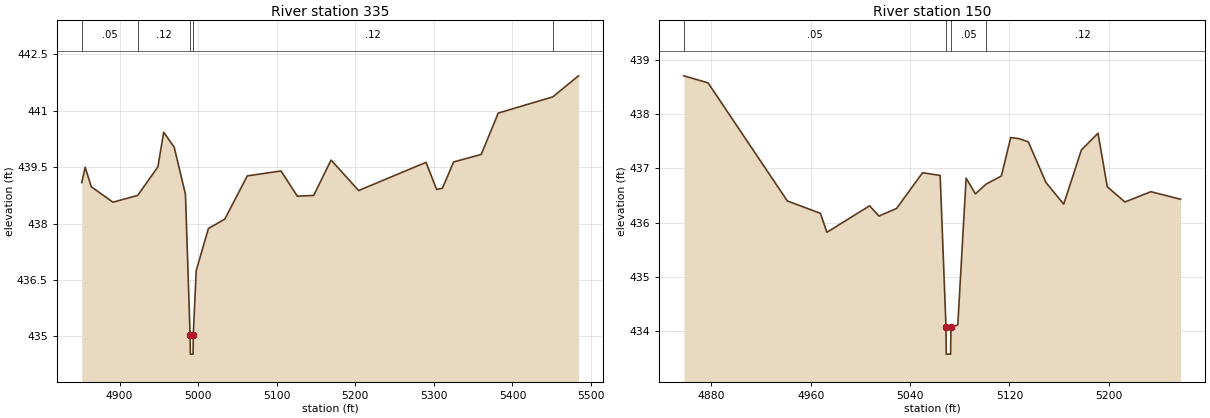
Type RM Length L Ch R = 1,335,185,185,185
BEGIN DESCRIPTION:
Lacy 091 1875
END DESCRIPTION:
XS GIS Cut Line= 3
      2733961.79      6883081.68      2733867.82      6882967.08
      2733498.02      6882654.82
#Sta/Elev= 30
  4851.8  439.09  4856.1  439.50  4864.0  438.98  4891.5  438.57  4923.0  438.75
  4948.7  439.51  4956.1  440.43  4969.5  440.03  4983.8  438.78  4989.7  435.03
  4990.0  434.53  4993.5  434.53  4993.7  435.03  4997.5  436.75  5013.0  437.87
  5033.9  438.12  5062.5  439.27  5105.4  439.40  5126.2  438.73  5147.0  438.75
  5169.1  439.69  5204.2  438.88  5290.0  439.63  5303.4  438.91  5310.8  438.94
  5325.1  439.64  5360.2  439.84  5381.9  440.94  5451.3  441.37  5484.0  441.93
#Mann=5,-1,0
  4851.8    0.05       0  4923.0    0.12       0  4989.7    0.07       0
  4993.7    0.12       0  5451.3    0.05       0
Bank Sta=4989.7,4993.7
Exp/Cntr=0.3,0.1

Type RM Length L Ch R = 1,150,0,0,0
BEGIN DESCRIPTION:
Lacy 091 1874
END DESCRIPTION:
XS GIS Cut Line= 3
      2734036.07      6883022.16      2734003.98      6882883.63
      2733832.22      6882691.38
#Sta/Elev= 30
  4857.8  438.71  4877.3  438.58  4941.1  436.40  4967.8  436.17  4973.0  435.82
  5007.4  436.31  5014.9  436.12  5029.1  436.26  5050.0  436.92  5064.2  436.87
  5068.9  434.07  5069.1  433.57  5072.6  433.57  5072.9  434.07  5078.4  434.11
  5085.1  436.82  5092.6  436.53  5101.2  436.71  5113.5  436.86  5121.0  437.57
  5127.7  437.55  5135.2  437.49  5149.4  436.74  5163.7  436.34  5177.9  437.34
  5191.3  437.65  5198.8  436.66  5213.0  436.38  5233.9  436.57  5257.8  436.43
#Mann=4,-1,0
  4857.8    0.05       0  5068.9    0.04       0  5072.9    0.05       0
  5101.2    0.12       0
Bank Sta=5068.9,5072.9
Exp/Cntr=0.3,0.1

Chan Stop Cuts=-1