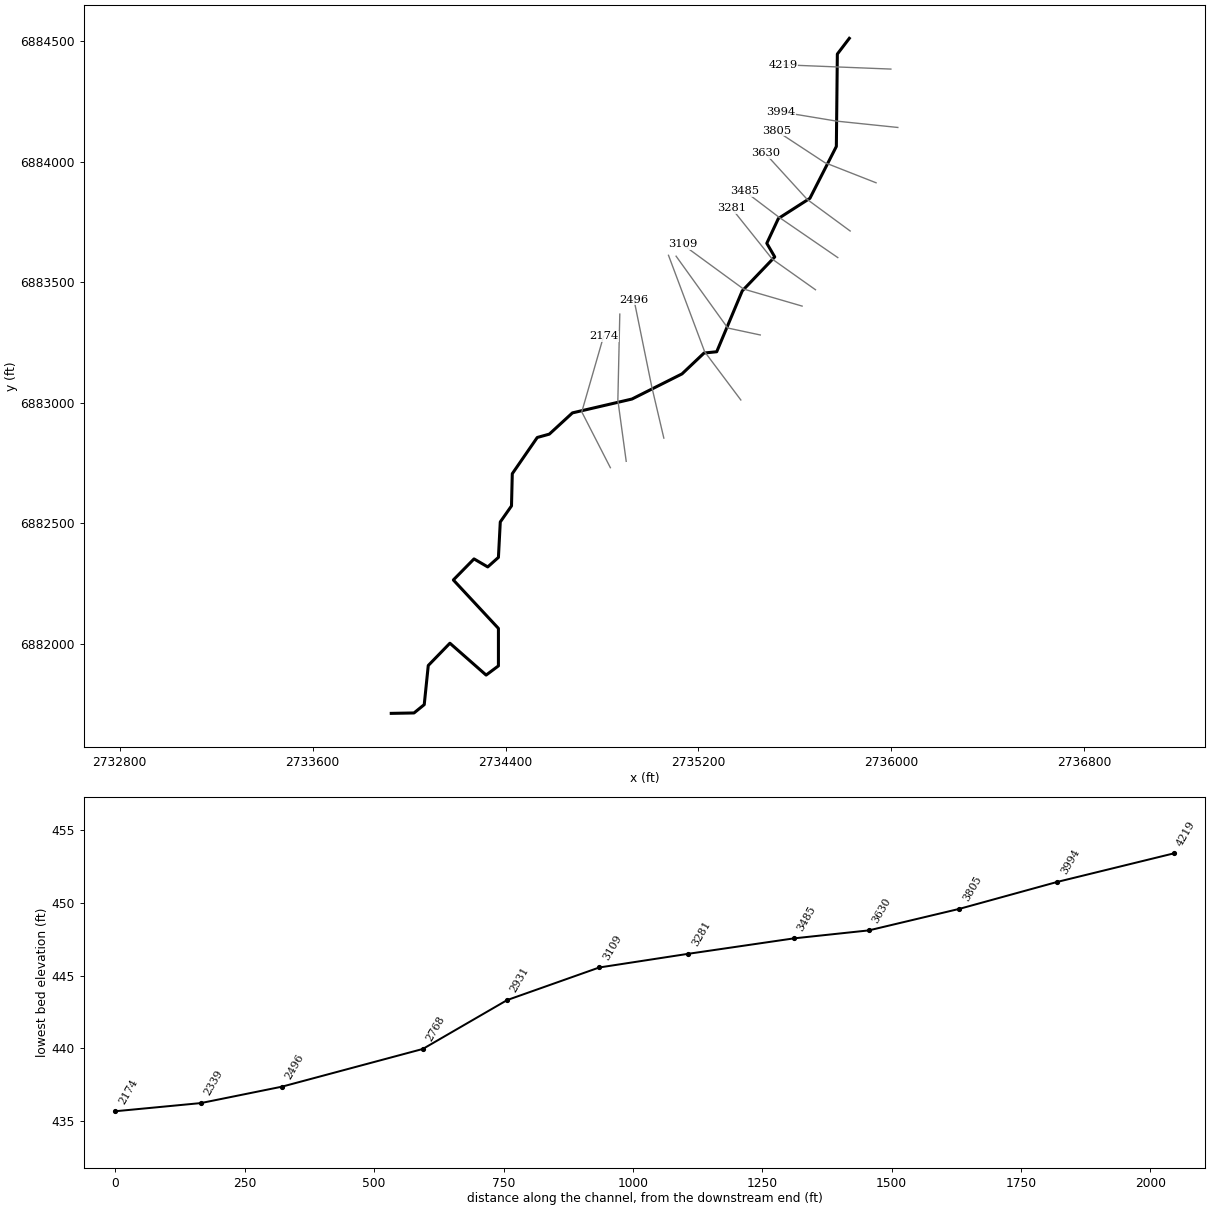
--- Lacy 092.prj (project) ---

Proj Title=Lacy 092 Base Level Engineering
Current Plan=p01
Default Exp/Contr=0.3,0.1
English Units
Geom File=g01
Flow File=f01
Plan File=p01
Y Axis Title=Elevation
X Axis Title(PF)=Main Channel Distance
X Axis Title(XS)=Station
BEGIN DESCRIPTION:
Lacy 092
END DESCRIPTION:
DSS Export Rating Curves= 0
DSS Export Rating Curve Sorted= 0
DSS Export Volume Flow Curves= 0
DXF OffsetX= 0
DXF OffsetY= 0
DXF ScaleX= 1
DXF ScaleY= 10

--- Lacy 092.p01 (plan) ---

Plan Title=Multiple Run
Short Identifier=Multiple
Geom File=g01
Flow File=f01
Subcritical Flow
K Sum by GR= 0
Std Step Tol= 0.01
Critical Tol= 0.01
Num of Std Step Trials= 20
Max Error Tol= 0.3
Flow Tol Ratio= 0.001
Split Flow NTrial= 30
Split Flow Tol= 0.02
Split Flow Ratio= 0.02
Log Output Level= 0
Friction Slope Method= 1
Unsteady Friction Slope Method= 2
Unsteady Bridges Friction Slope Method= 1
Parabolic Critical Depth
Global Vel Dist=  1 , 1 , 1
Global Log Level= 0
CheckData=True
Encroach Param= -1, 0, 0, 0
BEGIN DESCRIPTION:
Multiple Run
END DESCRIPTION:

--- Lacy 092.f01 (steady flow) ---

Flow Title=Multiple
Number of Profiles=7
Profile Names=10-year,25-year,50-year,1pct_min,100-year,1pct_plu,500-year
River Rch & RM= Lacy 092,Reach-1,4219
     153     186     209     117     234     467     293
River Rch & RM= Lacy 092,Reach-1,2768
     357     458     537     313     625    1246     842
Boundary for River Rch & Prof#=Lacy 092,Reach-1,1
Up Type=0
Dn Type=3
Dn Slope=0.005
Boundary for River Rch & Prof#=Lacy 092,Reach-1,2
Up Type=0
Dn Type=3
Dn Slope=0.005
Boundary for River Rch & Prof#=Lacy 092,Reach-1,3
Up Type=0
Dn Type=3
Dn Slope=0.005
Boundary for River Rch & Prof#=Lacy 092,Reach-1,4
Up Type=0
Dn Type=3
Dn Slope=0.005
Boundary for River Rch & Prof#=Lacy 092,Reach-1,5
Up Type=0
Dn Type=3
Dn Slope=0.005
Boundary for River Rch & Prof#=Lacy 092,Reach-1,6
Up Type=0
Dn Type=3
Dn Slope=0.005
Boundary for River Rch & Prof#=Lacy 092,Reach-1,7
Up Type=0
Dn Type=3
Dn Slope=0.005

--- Lacy 092.g01 (geometry) ---

Geom Title=Existing Conditions
Program Version=4.10

River Reach=Lacy 092        ,Reach-1
Reach XY= 30
        2735826.        6884511.      2735776.36      6884445.85
      2735772.25      6884062.55      2735662.52      6883847.44
       2735531.7      6883763.54      2735483.77      6883660.91
       2735516.7      6883604.33      2735381.83       6883463.3
        2735276.        6883211.      2735223.49      6883205.67
      2735132.05      6883119.14      2734924.42      6883014.83
       2734677.5      6882957.38      2734581.74       6882869.3
      2734531.62      6882855.38      2734428.07      6882705.14
      2734424.77      6882571.51      2734378.27      6882505.06
      2734370.53      6882358.01      2734326.24      6882318.46
       2734269.3      6882351.69      2734183.59      6882264.36
      2734370.55      6882063.45      2734370.55      6881907.98
      2734319.51      6881869.88      2734169.31      6882002.05
      2734079.54      6881909.56      2734062.83      6881747.27
      2734020.48      6881712.76        2733926.        6881711.

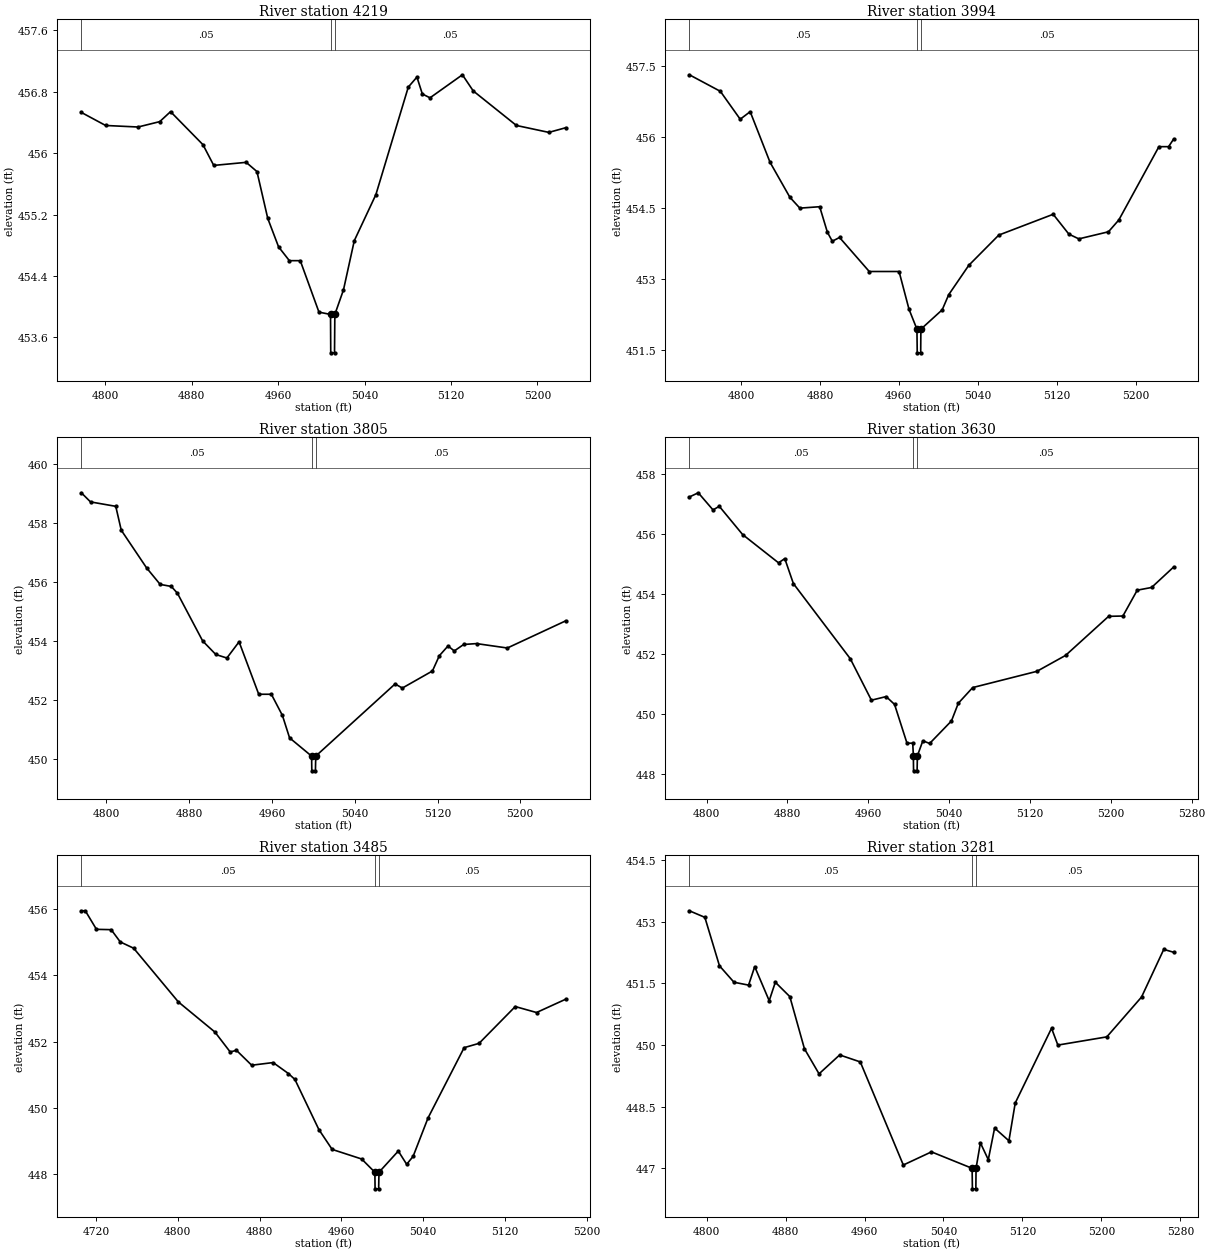
Type RM Length L Ch R = 1 ,4219    ,225,225,225
BEGIN DESCRIPTION:
Lacy 092 1902
END DESCRIPTION:
XS GIS Cut Line= 3
       2735998.5      6884383.49      2735776.37      6884392.32
      2735550.55      6884401.42
#Sta/Elev= 30
  4777.7  456.53  4800.2  456.36  4830.2  456.34  4850.3  456.41  4860.3  456.54
  4890.3  456.11  4900.3  455.84  4930.3  455.88  4940.3  455.76  4950.3  455.15
  4960.3  454.78  4970.3   454.6  4980.4   454.6  4997.7  453.93  5008.4   453.9
  5008.6   453.4  5012.1   453.4  5012.4   453.9  5020.4  454.22  5030.4  454.86
  5050.4  455.46  5080.4  456.86  5088.4  456.99  5093.4  456.77  5100.5  456.72
  5130.5  457.02  5140.5  456.81  5180.5  456.36  5210.5  456.27    5226  456.33
#Mann= 3 ,-1 , 0
  4777.7     .05       0  5008.4     .04       0  5012.4     .05       0
Bank Sta=5008.4,5012.4
XS Rating Curve= 0 ,0
Exp/Cntr=0.3,0.1

Type RM Length L Ch R = 1 ,3994    ,189,189,189
BEGIN DESCRIPTION:
Lacy 092 1901
END DESCRIPTION:
XS GIS Cut Line= 3
      2736027.27      6884141.29       2735772.5      6884167.72
       2735541.3      6884206.04
#Sta/Elev= 30
  4747.8  457.32  4779.2  456.97  4799.3  456.38  4809.4  456.54  4829.5  455.47
  4849.6  454.73  4859.7   454.5  4879.8  454.53  4887.6  453.99  4892.6   453.8
  4899.9  453.88    4930  453.16  4960.2  453.16  4970.3  452.36  4978.3  451.94
  4978.6  451.44  4982.1  451.44  4982.3  451.94  5003.9  452.35  5010.5  452.67
  5030.8  453.29  5061.2  453.93  5116.3  454.37  5132.2  453.95  5142.3  453.85
  5172.3     454  5182.8  454.25  5223.4   455.8  5233.2   455.8  5238.3  455.96
#Mann= 3 ,-1 , 0
  4747.8     .05       0  4978.3     .04       0  4982.3     .05       0
Bank Sta=4978.3,4982.3
XS Rating Curve= 0 ,0
Exp/Cntr=0.3,0.1

Type RM Length L Ch R = 1 ,3805    ,175,175,175
BEGIN DESCRIPTION:
Lacy 092 1900
END DESCRIPTION:
XS GIS Cut Line= 3
      2735936.97      6883911.87      2735724.87      6883995.15
      2735524.07      6884127.04
#Sta/Elev= 30
  4775.7  459.03  4784.6  458.72    4809  458.57  4814.3  457.76  4838.8  456.48
  4851.9  455.92  4862.7  455.85  4868.6  455.62    4893     454  4905.7  453.54
  4916.4  453.42  4928.2  453.97  4947.2  452.19  4959.4  452.19  4970.1  451.47
    4977  450.71  4998.3  450.09  4998.5  449.59    5002  449.59  5002.3  450.09
    5079  452.54    5086   452.4  5115.1  452.98  5121.8   453.5  5130.2  453.83
  5136.2  453.66  5145.3  453.88  5157.7  453.91  5187.5  453.76  5243.8  454.68
#Mann= 3 ,-1 , 0
  4775.7     .05       0  4998.3     .04       0  5002.3     .05       0
Bank Sta=4998.3,5002.3
XS Rating Curve= 0 ,0
Exp/Cntr=0.3,0.1

Type RM Length L Ch R = 1 ,3630    ,145,145,145
BEGIN DESCRIPTION:
Lacy 092 1899
END DESCRIPTION:
XS GIS Cut Line= 3
      2735829.54      6883711.86      2735651.46      6883842.74
      2735477.52      6884033.41
#Sta/Elev= 30
    4783  457.22  4791.8  457.36  4806.4  456.79  4812.6  456.91  4835.7  455.97
  4871.2  455.03  4877.4  455.17  4885.9  454.34  4942.2  451.84  4963.1  450.46
  4977.7  450.58    4986  450.32  4998.3  449.03    5004  449.03  5004.6  448.61
  5004.8  448.11  5008.3  448.11  5008.6  448.61    5014  449.11  5020.7  449.02
  5042.3  449.77  5049.1  450.36  5063.3  450.88  5126.8  451.42  5155.2  451.95
  5197.8  453.25  5211.9  453.26  5226.1  454.12  5240.3  454.21  5262.1  454.89
#Mann= 3 ,-1 , 0
    4783     .05       0  5004.6     .04       0  5008.6     .05       0
Bank Sta=5004.6,5008.6
XS Rating Curve= 0 ,0
Exp/Cntr=0.3,0.1

Type RM Length L Ch R = 1 ,3485    ,204,204,204
BEGIN DESCRIPTION:
Lacy 092 1898
END DESCRIPTION:
XS GIS Cut Line= 3
      2735778.18      6883601.58      2735533.25       6883769.8
      2735392.64      6883876.43
#Sta/Elev= 30
  4705.6  455.95  4709.5  455.95  4720.4  455.39  4734.8  455.38  4743.7  455.01
  4756.8  454.82  4800.5   453.2  4836.3  452.29  4851.2  451.69  4857.3  451.74
  4872.2  451.29  4893.2  451.37  4908.1  451.04  4914.5  450.86  4937.9  449.35
  4950.9  448.75  4979.8  448.46  4992.7  448.06  4992.9  447.56  4996.4  447.56
  4996.7  448.06  5015.6   448.7  5023.8   448.3  5030.1  448.54  5044.7   449.7
    5080  451.82  5094.6  451.95    5130  453.06  5150.8  452.88  5179.2  453.28
#Mann= 3 ,-1 , 0
  4705.6     .05       0  4992.7     .04       0  4996.7     .05       0
Bank Sta=4992.7,4996.7
XS Rating Curve= 0 ,0
Exp/Cntr=0.3,0.1

Type RM Length L Ch R = 1 ,3281    ,172,172,172
BEGIN DESCRIPTION:
Lacy 092 1897
END DESCRIPTION:
XS GIS Cut Line= 3
      2735685.62       6883468.2      2735506.58      6883595.13
      2735337.26      6883807.02
#Sta/Elev= 30
  4782.5  453.27  4798.2  453.11    4813  451.93  4827.7  451.53  4842.5  451.46
  4848.7  451.91  4863.4  451.08  4869.6  451.53  4884.3  451.18  4899.1  449.91
  4913.9   449.3  4934.8  449.76  4955.7  449.59  4999.3  447.08  5027.8   447.4
    5069     447  5069.3   446.5  5072.8   446.5    5073     447  5077.4  447.62
  5085.4  447.21  5091.8  447.98  5106.3  447.67  5112.7  448.59  5149.5  450.41
  5155.9     450  5205.5   450.2  5240.7  451.17  5263.2  452.33  5273.2  452.26
#Mann= 3 ,-1 , 0
  4782.5     .05       0    5069     .04       0    5073     .05       0
Bank Sta=5069,5073
XS Rating Curve= 0 ,0
Exp/Cntr=0.3,0.1

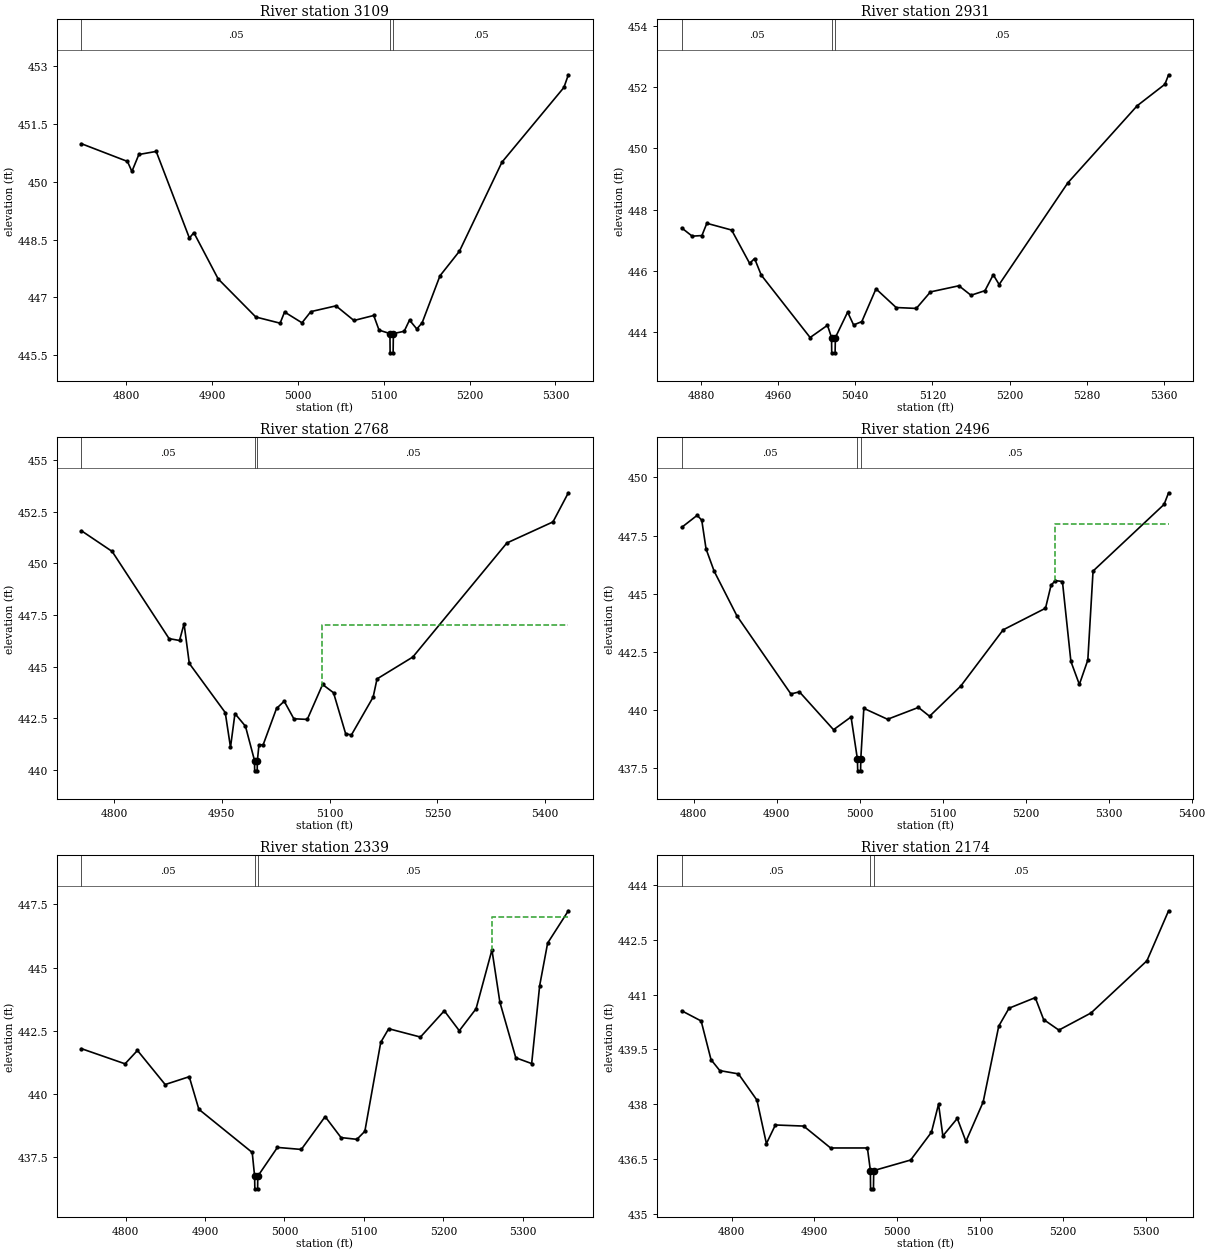
Type RM Length L Ch R = 1 ,3109    ,178,178,178
BEGIN DESCRIPTION:
Lacy 092 1886
END DESCRIPTION:
XS GIS Cut Line= 3
      2735630.26      6883400.37      2735387.31      6883471.15
      2735133.54      6883656.65
#Sta/Elev= 30
  4747.7  450.99  4801.3  450.53  4806.5  450.27  4814.6  450.71  4834.8  450.79
  4873.5  448.54  4878.7  448.68    4907  447.48  4950.9  446.49  4979.2  446.33
  4984.4  446.62  5004.7  446.34    5015  446.63  5044.3  446.78  5065.2   446.4
  5088.3  446.53  5094.5  446.15  5107.2  446.06  5107.4  445.56  5110.9  445.56
  5111.2  446.06  5123.8  446.12    5130  446.41  5138.5  446.18  5144.7  446.34
  5165.5  447.56  5188.2   448.2  5237.7  450.51  5309.9  452.45  5315.1  452.78
#Mann= 3 ,-1 , 0
  4747.7     .05       0  5107.2     .04       0  5111.2     .05       0
Bank Sta=5107.2,5111.2
XS Rating Curve= 0 ,0
Exp/Cntr=0.3,0.1

Type RM Length L Ch R = 1 ,2931    ,163,163,163
BEGIN DESCRIPTION:
Lacy 092 1885
END DESCRIPTION:
XS GIS Cut Line= 3
      2735456.65      6883280.57      2735321.78      6883309.41
      2735107.55      6883607.36
#Sta/Elev= 30
    4860   447.4  4870.9  447.13    4881  447.15  4886.1  447.55  4911.8  447.33
  4930.5  446.24  4935.6   446.4  4942.5  445.86  4993.2  443.82  5011.2  444.22
  5015.4  443.82  5015.6  443.32  5019.1  443.32  5019.4  443.82  5032.1  444.65
  5038.3  444.23  5046.8  444.34  5061.5  445.41  5082.4   444.8  5103.3  444.77
    5118  445.31  5147.5  445.51    5160   445.2  5174.5  445.35  5183.1  445.87
  5189.2  445.55  5260.4  448.87  5332.4  451.39  5361.1  452.09  5364.9   452.4
#Mann= 3 ,-1 , 0
    4860     .05       0  5015.4     .04       0  5019.4     .05       0
Bank Sta=5015.4,5019.4
XS Rating Curve= 0 ,0
Exp/Cntr=0.3,0.1

Type RM Length L Ch R = 1 ,2768    ,272,272,272
BEGIN DESCRIPTION:
Lacy 092 66
END DESCRIPTION:
XS GIS Cut Line= 3
      2735375.99      6883011.01        2735226.        6883211.
      2735075.99      6883611.02
#Sta/Elev= 30
  4754.9  451.58  4797.6  450.58  4876.8  446.36  4891.3  446.27  4897.6  447.08
  4904.9  445.16  4954.9  442.78  4962.2   441.1  4968.4  442.73    4983  442.12
  4995.6  440.46  4995.8  439.96  4999.3  439.96  4999.6  440.46  5001.8  441.22
  5007.6  441.22  5026.2  442.98  5036.9  443.33  5050.3  442.48    5069  442.45
  5090.3  444.14  5105.5  443.74  5122.4  441.75  5130.4   441.7  5160.6  443.53
    5166  444.41  5215.8  445.47  5346.6  450.99  5410.7  452.01  5432.1  453.42
#Mann= 3 ,-1 , 0
  4754.9     .05       0  4995.6     .04       0  4999.6     .05       0
#XS Ineff= 2 , 0
       0                    5089       0     447
Permanent Ineff=
       F       F
Bank Sta=4995.6,4999.6
XS Rating Curve= 0 ,0
Exp/Cntr=0.3,0.1

Type RM Length L Ch R = 1 ,2496    ,157,157,157
BEGIN DESCRIPTION:
Lacy 092 1884
END DESCRIPTION:
XS GIS Cut Line= 3
      2735056.64      6882852.84      2735006.34      6883066.99
      2734933.04      6883426.31
#Sta/Elev= 30
  4785.4  447.85  4804.1  448.37  4809.6  448.16  4814.8  446.92  4824.6  445.96
    4852  444.04    4917  440.68  4927.3  440.77  4968.4  439.14  4989.5  439.69
  4997.2  437.87  4997.5  437.37    5001  437.37  5001.2  437.87  5004.9  440.06
  5033.5  439.59  5070.7   440.1  5084.1  439.72  5121.7  441.02  5172.8  443.44
  5223.8  444.37  5230.5  445.36  5235.7  445.56  5244.2  445.52  5254.4  442.08
  5264.6  441.09  5274.8  442.14  5281.1  445.97  5366.7  448.84  5372.1  449.34
#Mann= 3 ,-1 , 0
  4785.4     .05       0  4997.2     .04       0  5001.2     .05       0
#XS Ineff= 2 , 0
       0                    5235       0     448
Permanent Ineff=
       F       F
Bank Sta=4997.2,5001.2
XS Rating Curve= 0 ,0
Exp/Cntr=0.3,0.1

Type RM Length L Ch R = 1 ,2339    ,165,165,165
BEGIN DESCRIPTION:
Lacy 092 1883
END DESCRIPTION:
XS GIS Cut Line= 3
      2734900.59      6882756.59      2734865.94      6883010.27
      2734874.02      6883367.14
#Sta/Elev= 30
  4744.4  441.79  4799.3  441.19  4814.9  441.72  4849.8  440.37  4880.1  440.68
  4892.2  439.39  4959.4  437.68  4962.4  436.74  4962.7  436.24  4966.2  436.24
  4966.4  436.74  4991.1  437.88  5021.2   437.8  5051.2   439.1  5071.2  438.27
  5091.2   438.2  5101.2  438.52  5121.2  442.04  5131.2  442.58  5171.2  442.25
  5201.2  443.29  5220.1   442.5  5241.2  443.37  5261.2   445.7  5271.2  443.63
  5291.2  441.43  5311.2   441.2  5321.3  444.29  5331.3  445.97  5357.4  447.25
#Mann= 3 ,-1 , 0
  4744.4     .05       0  4962.4     .04       0  4966.4     .05       0
#XS Ineff= 2 , 0
       0                    5261       0     447
Permanent Ineff=
       F       F
Bank Sta=4962.4,4966.4
XS Rating Curve= 0 ,0
Exp/Cntr=0.3,0.1

Type RM Length L Ch R = 1 ,2174    ,0,0,0
BEGIN DESCRIPTION:
Lacy 092 1887
END DESCRIPTION:
XS GIS Cut Line= 3
      2734834.88      6882730.07      2734716.27      6882961.55
      2734806.87      6883275.85
#Sta/Elev= 30
  4739.9  440.56  4763.4  440.28  4775.3  439.22  4785.9  438.92  4808.4  438.83
  4830.7  438.11  4842.1  436.92  4852.9  437.43    4887   437.4  4919.5   436.8
  4963.9   436.8  4967.5  436.18  4967.7  435.68  4971.2  435.68  4971.5  436.18
  5016.1  436.47  5041.1  437.23  5049.7     438  5054.9  437.13  5072.3  437.61
  5082.7  436.98  5103.5  438.06  5122.3  440.14  5134.7  440.63  5166.3  440.92
  5176.4  440.32  5194.8  440.03  5233.6   440.5    5301  441.93  5327.1   443.3
#Mann= 3 ,-1 , 0
  4739.9     .05       0  4967.5     .04       0  4971.5     .05       0
Bank Sta=4967.5,4971.5
XS Rating Curve= 0 ,0
Exp/Cntr=0.3,0.1

Chan Stop Cuts=-1
Use User Specified Reach Order=0
Composite Channel Slope=5