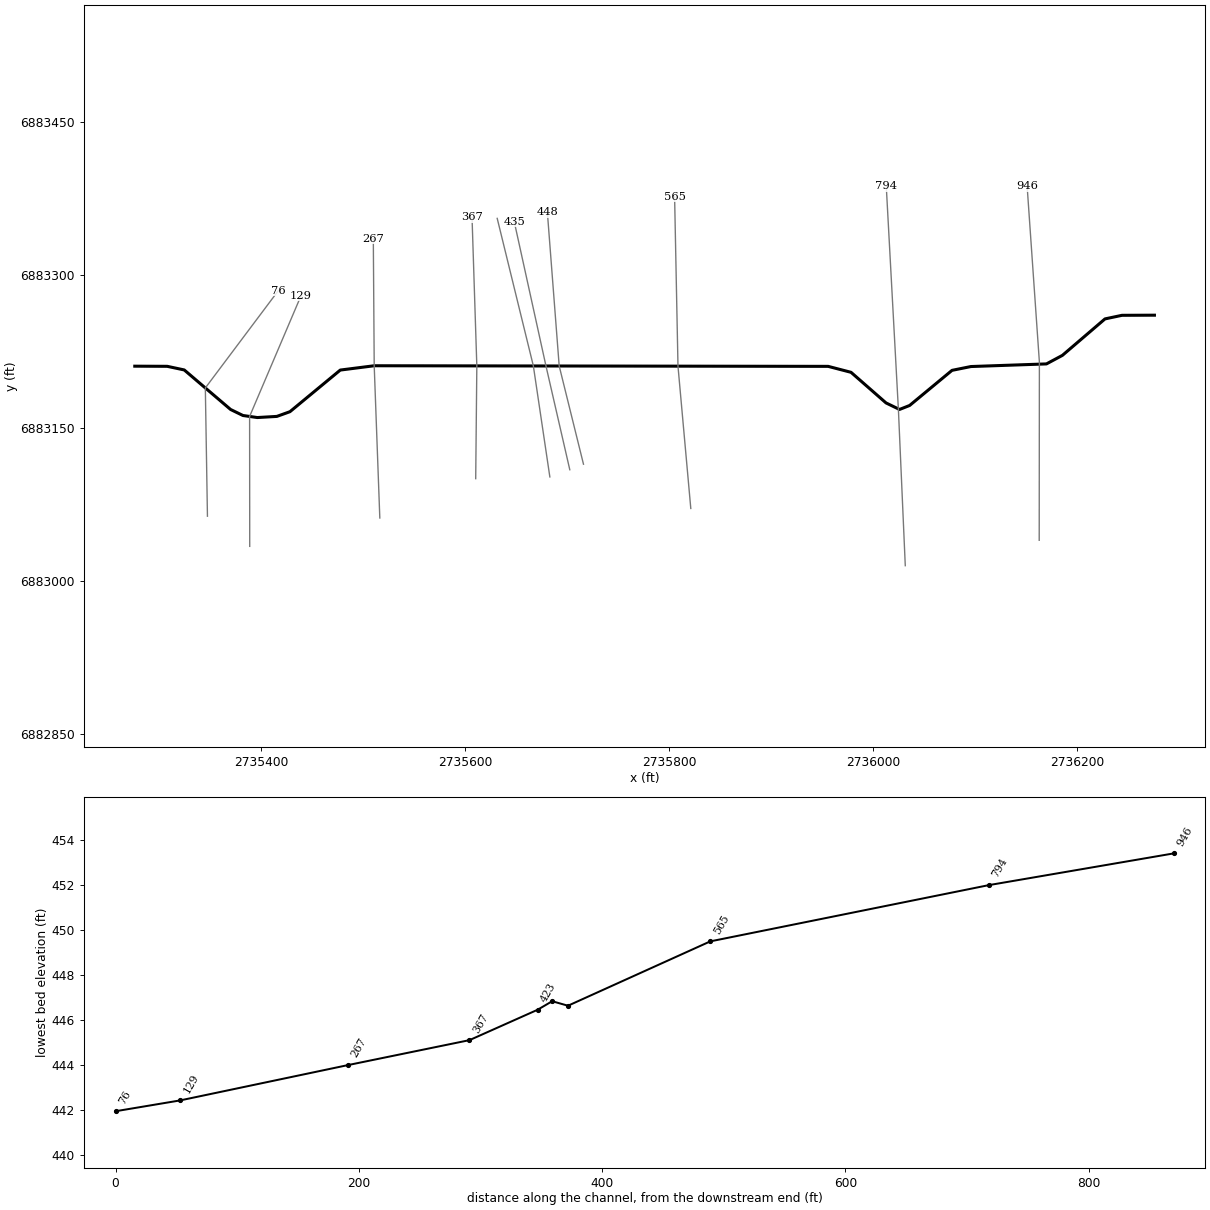
--- Lacy 093.prj (project) ---

Proj Title=Lacy 093 Base Level Engineering
Current Plan=p01
Default Exp/Contr=0.3,0.1
English Units
Geom File=g01
Flow File=f01
Plan File=p01
BEGIN DESCRIPTION:
Lacy 093
END DESCRIPTION:

--- Lacy 093.p01 (plan) ---

Plan Title=Multiple Run
Short Identifier=Multiple
Geom File=g01
Flow File=f01
Subcritical Flow
K Sum by GR= 0
Std Step Tol= 0.01
Critical Tol= 0.01
Num of Std Step Trials= 20
Max Error Tol= 0.3
Flow Tol Ratio= 0.001
Split Flow NTrial= 30
Split Flow Tol= 0.02
Split Flow Ratio= 0.02
Log Output Level= 0
Friction Slope Method= 1
Unsteady Friction Slope Method= 2
Unsteady Bridges Friction Slope Method= 1
Parabolic Critical Depth
Global Vel Dist=  1 , 1 , 1
Global Log Level= 0
CheckData=True
Encroach Param= -1, 0, 0, 0
BEGIN DESCRIPTION:
Multiple Run
END DESCRIPTION:

--- Lacy 093.f01 (steady flow) ---

Flow Title=Multiple
Number of Profiles=7
Profile Names=10-year,25-year,50-year,1pct_min,100-year,1pct_plu,500-year
River Rch & RM= Lacy 093,Reach-1,946
     126     149     166      92     184     367     224
Boundary for River Rch & Prof#=Lacy 093,Reach-1,1
Up Type=0
Dn Type=3
Dn Slope=0.005
Boundary for River Rch & Prof#=Lacy 093,Reach-1,2
Up Type=0
Dn Type=3
Dn Slope=0.005
Boundary for River Rch & Prof#=Lacy 093,Reach-1,3
Up Type=0
Dn Type=3
Dn Slope=0.005
Boundary for River Rch & Prof#=Lacy 093,Reach-1,4
Up Type=0
Dn Type=3
Dn Slope=0.005
Boundary for River Rch & Prof#=Lacy 093,Reach-1,5
Up Type=0
Dn Type=3
Dn Slope=0.005
Boundary for River Rch & Prof#=Lacy 093,Reach-1,6
Up Type=0
Dn Type=3
Dn Slope=0.005
Boundary for River Rch & Prof#=Lacy 093,Reach-1,7
Up Type=0
Dn Type=3
Dn Slope=0.005

--- Lacy 093.g01 (geometry) ---

Geom Title=Existing Conditions

River Reach=Lacy 093,Reach-1
Reach XY= 22
      2736276.00      6883261.00      2736244.20      6883260.88
      2736227.51      6883257.36      2736185.75      6883221.61
      2736170.08      6883213.22      2736096.05      6883210.65
      2736077.50      6883206.91      2736035.91      6883172.47
      2736026.00      6883168.56      2736012.79      6883174.95
      2735978.45      6883204.98      2735956.02      6883210.82
      2735510.82      6883211.42      2735477.55      6883207.19
      2735428.18      6883166.37      2735415.32      6883161.74
      2735396.17      6883160.63      2735382.08      6883162.64
      2735369.99      6883168.52      2735324.51      6883207.31
      2735307.81      6883210.86      2735276.00      6883211.00

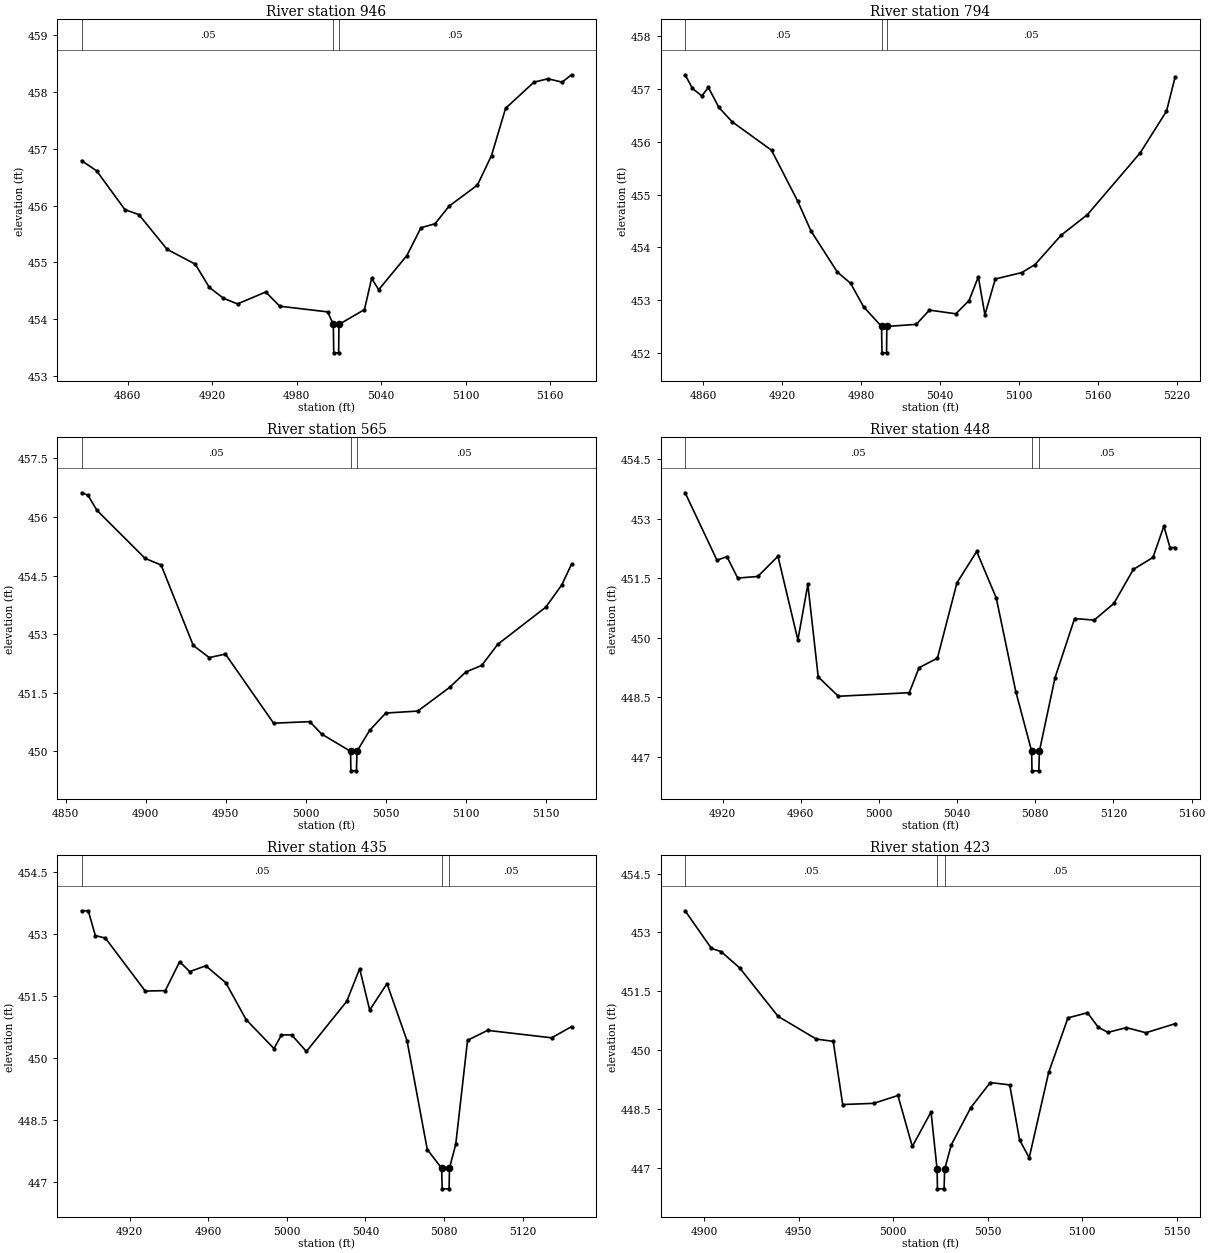
Type RM Length L Ch R = 1,946,152,152,152
BEGIN DESCRIPTION:
Lacy 093 1890
END DESCRIPTION:
XS GIS Cut Line= 3
      2736163.00      6883040.28      2736163.17      6883214.97
      2736151.14      6883387.66
#Sta/Elev= 30
  4827.3  456.79  4838.0  456.61  4858.0  455.93  4868.0  455.84  4888.0  455.23
  4908.0  454.97  4918.0  454.56  4928.0  454.37  4938.0  454.27  4958.0  454.48
  4968.0  454.23  5002.0  454.13  5006.0  453.91  5006.3  453.41  5009.8  453.41
  5010.0  453.91  5028.1  454.17  5033.2  454.72  5038.2  454.52  5058.2  455.12
  5068.2  455.61  5078.2  455.68  5088.2  455.99  5108.3  456.36  5118.3  456.88
  5128.3  457.71  5148.4  458.17  5158.4  458.23  5168.4  458.17  5175.1  458.30
#Mann=3,-1,0
  4827.3    0.05       0  5006.0    0.04       0  5010.0    0.05       0
Bank Sta=5006,5010
Exp/Cntr=0.3,0.1

Type RM Length L Ch R = 1,794,229,229,229
BEGIN DESCRIPTION:
Lacy 093 1889
END DESCRIPTION:
XS GIS Cut Line= 3
      2736031.65      6883015.36      2736024.96      6883167.30
      2736013.00      6883387.49
#Sta/Elev= 30
  4846.1  457.27  4851.7  457.01  4858.8  456.87  4863.8  457.03  4871.8  456.65
  4881.8  456.38  4911.8  455.84  4931.8  454.87  4941.8  454.31  4961.9  453.53
  4971.9  453.32  4981.9  452.87  4995.5  452.50  4995.8  452.00  4999.3  452.00
  4999.5  452.50  5021.9  452.54  5031.9  452.81  5052.0  452.74  5062.0  452.99
  5069.1  453.44  5074.1  452.72  5082.0  453.40  5102.0  453.52  5112.1  453.67
  5132.1  454.23  5152.1  454.62  5192.2  455.79  5212.2  456.58  5218.7  457.22
#Mann=3,-1,0
  4846.1    0.05       0  4995.5    0.04       0  4999.5    0.05       0
Bank Sta=4995.5,4999.5
Exp/Cntr=0.3,0.1

Type RM Length L Ch R = 1,565,117,117,117
BEGIN DESCRIPTION:
Lacy 093 1888
END DESCRIPTION:
XS GIS Cut Line= 3
      2735821.30      6883071.48      2735808.74      6883210.94
      2735805.42      6883377.08
#Sta/Elev= 25
  4859.9  456.62  4863.8  456.56  4869.5  456.17  4899.6  454.94  4909.6  454.77
  4929.7  452.71  4939.7  452.40  4949.8  452.49  4979.9  450.72  5002.5  450.76
  5010.0  450.44  5028.0  450.00  5028.2  449.50  5031.7  449.50  5032.0  450.00
  5040.0  450.54  5050.0  450.98  5070.0  451.03  5090.0  451.64  5100.0  452.03
  5110.0  452.20  5120.0  452.74  5150.0  453.69  5160.0  454.26  5166.1  454.79
#Mann=3,-1,0
  4859.9    0.05       0  5028.0    0.04       0  5032.0    0.05       0
Bank Sta=5028,5032
Exp/Cntr=0.3,0.1

Type RM Length L Ch R = 1,448,13,13,13
BEGIN DESCRIPTION:
Lacy 093 1896
END DESCRIPTION:
XS GIS Cut Line= 3
      2735716.06      6883114.88      2735692.24      6883211.18
      2735680.61      6883362.23
#Sta/Elev= 30
  4900.8  453.65  4917.1  451.95  4922.2  452.04  4927.7  451.50  4938.0  451.54
  4948.3  452.05  4958.5  449.94  4963.6  451.34  4968.9  449.01  4979.2  448.52
  5015.5  448.61  5020.5  449.24  5029.9  449.48  5039.9  451.38  5050.0  452.17
  5060.0  451.00  5070.0  448.64  5078.1  447.14  5078.3  446.64  5081.8  446.64
  5082.1  447.14  5090.1  448.99  5100.1  450.48  5110.1  450.44  5120.2  450.86
  5130.2  451.72  5140.2  452.02  5145.8  452.81  5148.9  452.27  5151.5  452.27
#Mann=3,-1,0
  4900.8    0.05       0  5078.1    0.04       0  5082.1    0.05       0
Bank Sta=5078.1,5082.1
Exp/Cntr=0.3,0.1

Type RM Length L Ch R = 1,435,12,12,12
BEGIN DESCRIPTION:
Lacy 093 1895
END DESCRIPTION:
XS GIS Cut Line= 3
      2735702.63      6883109.44      2735679.27      6883211.19
      2735648.15      6883352.71
#Sta/Elev= 30
  4895.6  453.56  4899.0  453.56  4902.6  452.96  4907.7  452.90  4928.0  451.62
  4938.2  451.63  4945.5  452.33  4950.6  452.09  4958.8  452.23  4969.0  451.82
  4979.3  450.93  4993.5  450.23  4997.3  450.56  5002.5  450.56  5010.0  450.16
  5030.5  451.37  5037.1  452.16  5042.2  451.16  5051.0  451.80  5061.2  450.42
  5071.5  447.79  5078.8  447.34  5079.1  446.84  5082.6  446.84  5082.8  447.34
  5086.0  447.92  5092.0  450.43  5102.2  450.67  5134.8  450.49  5144.9  450.76
#Mann=3,-1,0
  4895.6    0.05       0  5078.8    0.04       0  5082.8    0.05       0
Bank Sta=5078.8,5082.8
Exp/Cntr=0.3,0.1

Type RM Length L Ch R = 1,423,56,56,56
BEGIN DESCRIPTION:
Lacy 093 1894
END DESCRIPTION:
XS GIS Cut Line= 3
      2735683.07      6883102.41      2735666.90      6883211.21
      2735631.44      6883355.93
#Sta/Elev= 30
  4890.0  453.55  4903.9  452.59  4909.0  452.51  4918.9  452.09  4939.1  450.86
  4959.3  450.28  4968.3  450.22  4973.3  448.61  4989.7  448.64  5002.5  448.84
  5010.1  447.54  5020.0  448.42  5023.2  446.96  5023.4  446.46  5026.9  446.46
  5027.2  446.96  5030.7  447.58  5041.0  448.53  5051.3  449.17  5061.6  449.11
  5066.8  447.71  5071.9  447.25  5082.2  449.43  5092.4  450.82  5102.7  450.95
  5108.4  450.58  5113.5  450.45  5123.3  450.57  5133.6  450.44  5149.0  450.67
#Mann=3,-1,0
  4890.0    0.05       0  5023.2    0.04       0  5027.2    0.05       0
Bank Sta=5023.2,5027.2
Exp/Cntr=0.3,0.1

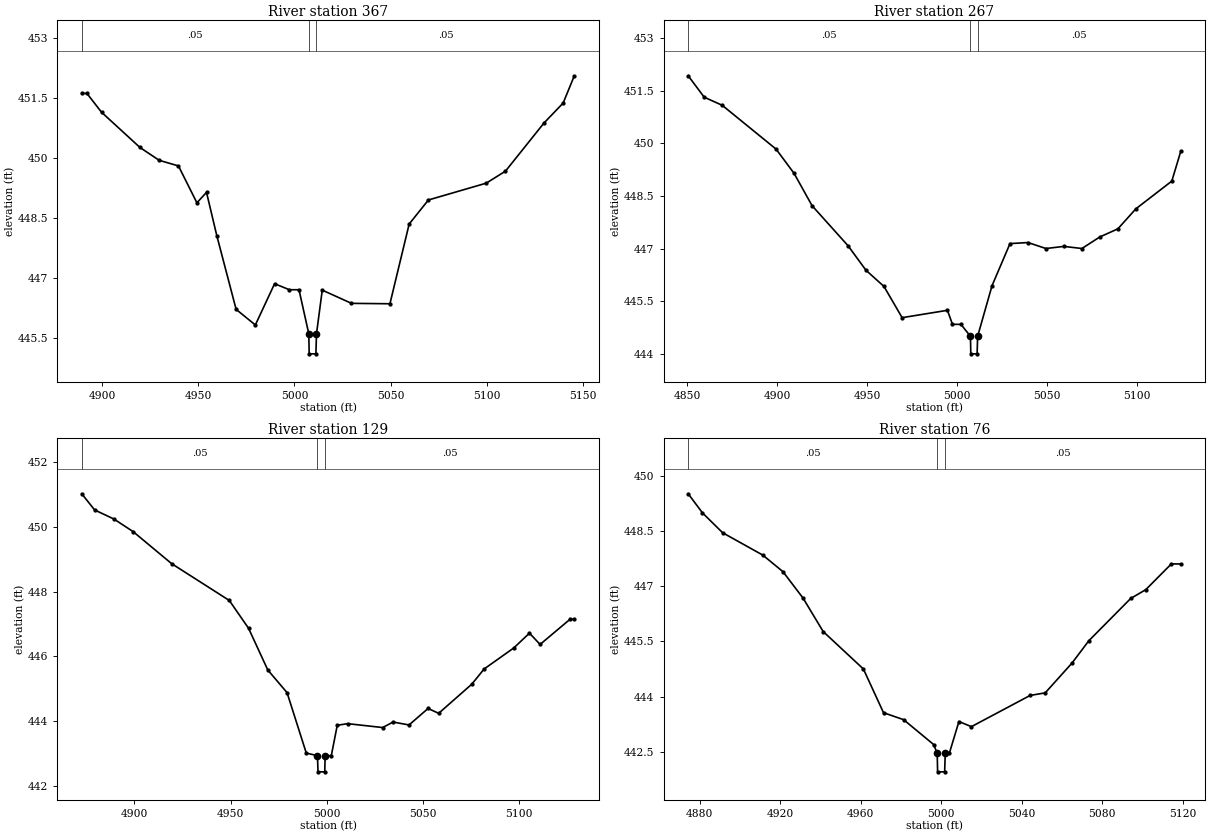
Type RM Length L Ch R = 1,367,100,100,100
BEGIN DESCRIPTION:
Lacy 093 1893
END DESCRIPTION:
XS GIS Cut Line= 3
      2735610.36      6883100.69      2735611.46      6883211.29
      2735606.76      6883356.81
#Sta/Elev= 28
  4889.4  451.61  4892.1  451.61  4899.7  451.14  4919.7  450.26  4929.7  449.94
  4939.7  449.80  4949.3  448.88  4954.3  449.14  4959.7  448.05  4969.7  446.22
  4979.7  445.83  4989.7  446.86  4997.4  446.71  5002.4  446.71  5007.5  445.61
  5007.7  445.11  5011.2  445.11  5011.5  445.61  5014.5  446.70  5029.7  446.37
  5049.7  446.36  5059.7  448.35  5069.7  448.95  5099.8  449.37  5109.8  449.67
  5129.8  450.87  5139.8  451.37  5145.6  452.05
#Mann=3,-1,0
  4889.4    0.05       0  5007.5    0.04       0  5011.5    0.05       0
Bank Sta=5007.5,5011.5
Exp/Cntr=0.3,0.1

Type RM Length L Ch R = 1,267,138,138,138
BEGIN DESCRIPTION:
Lacy 093 1892
END DESCRIPTION:
XS GIS Cut Line= 3
      2735516.32      6883062.13      2735510.82      6883211.42
      2735509.94      6883336.02
#Sta/Elev= 28
  4850.6  451.92  4859.5  451.31  4869.5  451.08  4899.5  449.83  4909.5  449.14
  4919.5  448.22  4939.5  447.08  4949.5  446.38  4959.5  445.92  4969.6  445.03
  4994.8  445.24  4997.6  444.84  5002.3  444.84  5007.6  444.50  5007.8  444.00
  5011.3  444.00  5011.6  444.50  5019.6  445.94  5029.6  447.14  5039.6  447.17
  5049.6  447.00  5059.6  447.06  5069.6  447.00  5079.6  447.33  5089.6  447.56
  5099.6  448.13  5119.6  448.92  5124.6  449.77
#Mann=3,-1,0
  4850.6    0.05       0  5007.6    0.04       0  5011.6    0.05       0
Bank Sta=5007.6,5011.6
Exp/Cntr=0.3,0.1

Type RM Length L Ch R = 1,129,53,53,53
BEGIN DESCRIPTION:
Lacy 093 1891
END DESCRIPTION:
XS GIS Cut Line= 3
      2735388.73      6883034.31      2735388.62      6883161.71
      2735439.01      6883280.03
#Sta/Elev= 29
  4872.6  451.03  4879.3  450.53  4889.3  450.25  4899.3  449.86  4919.3  448.87
  4949.3  447.73  4959.3  446.87  4969.3  445.58  4979.3  444.88  4989.3  443.01
  4995.1  442.93  4995.4  442.43  4998.9  442.43  4999.1  442.93  5002.3  442.93
  5005.4  443.87  5010.8  443.92  5029.0  443.80  5034.4  443.97  5042.7  443.88
  5052.6  444.39  5058.1  444.24  5075.3  445.14  5081.7  445.61  5097.1  446.26
  5105.3  446.72  5110.8  446.37  5126.4  447.15  5128.6  447.15
#Mann=3,-1,0
  4872.6    0.05       0  4995.1    0.04       0  4999.1    0.05       0
Bank Sta=4995.1,4999.1
Exp/Cntr=0.3,0.1

Type RM Length L Ch R = 1,76,0,0,0
BEGIN DESCRIPTION:
Lacy 093 3482
END DESCRIPTION:
XS GIS Cut Line= 3
      2735347.27      6883063.88      2735345.20      6883189.66
      2735416.68      6883284.93
#Sta/Elev= 26
  4874.2  449.52  4881.3  449.00  4891.3  448.46  4911.3  447.85  4921.3  447.40
  4931.3  446.68  4941.3  445.77  4961.3  444.75  4971.3  443.56  4981.3  443.37
  4996.3  442.69  4998.0  442.45  4998.2  441.95  5001.7  441.95  5002.0  442.45
  5004.0  442.45  5008.8  443.32  5015.0  443.18  5044.2  444.03  5051.7  444.10
  5065.0  444.91  5073.4  445.52  5094.2  446.67  5101.7  446.91  5114.4  447.61
  5119.1  447.61
#Mann=3,-1,0
  4874.2    0.05       0  4998.0    0.04       0  5002.0    0.05       0
Bank Sta=4998,5002
Exp/Cntr=0.3,0.1

Chan Stop Cuts=-1