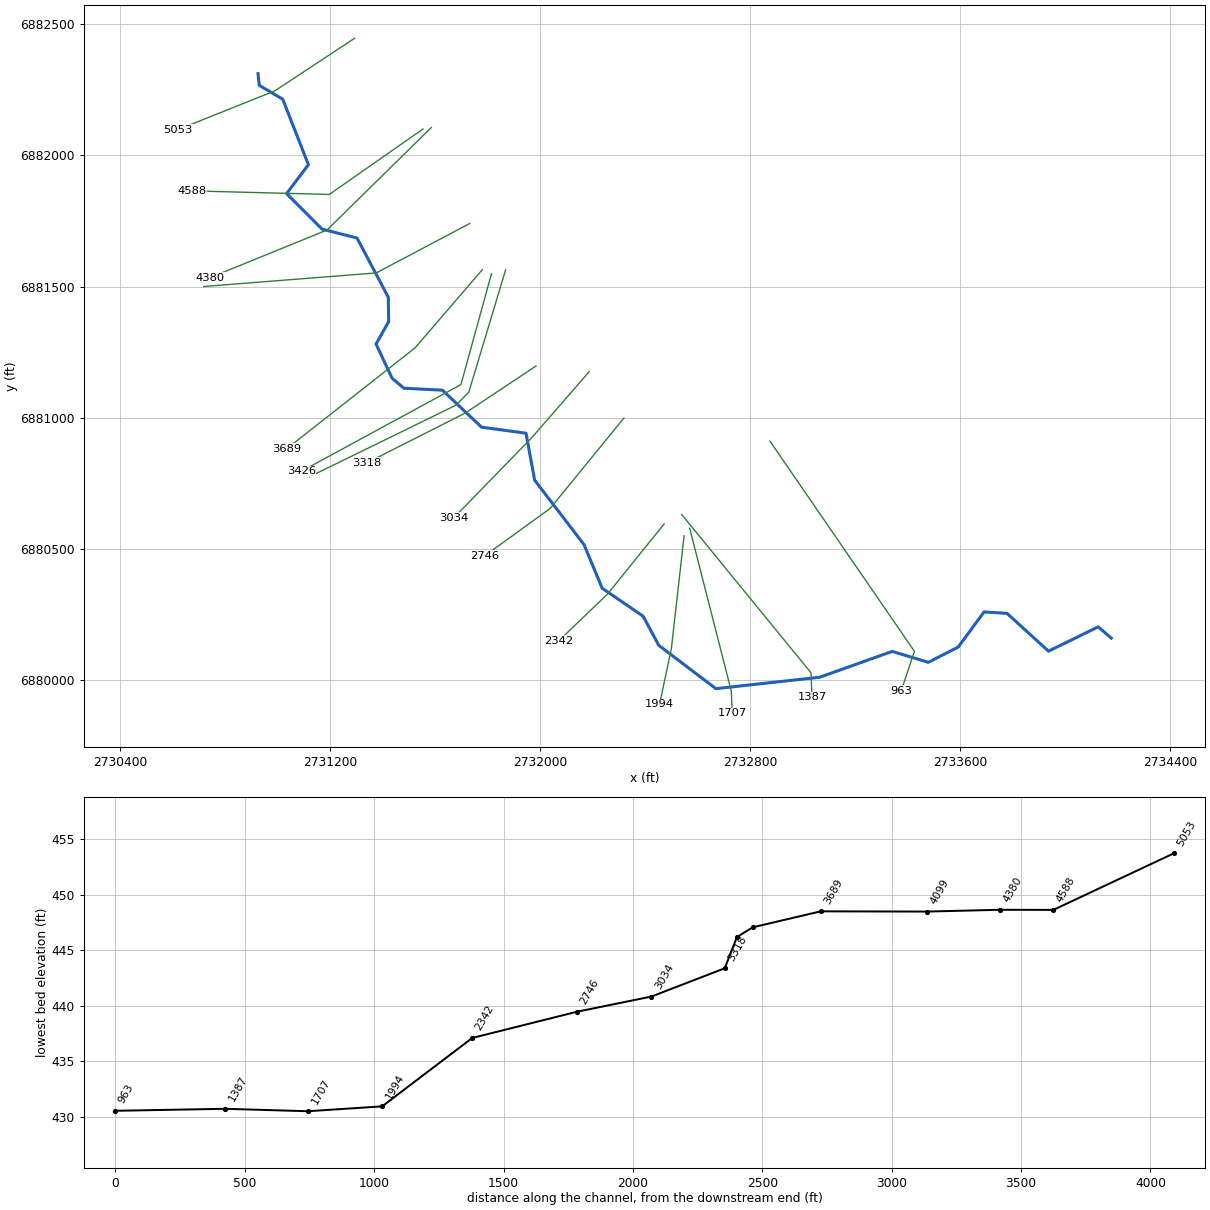
--- Lacy 094.prj (project) ---

Proj Title=Lacy 094 Base Level Engineering
Current Plan=p01
Default Exp/Contr=0.3,0.1
English Units
Geom File=g01
Flow File=f01
Plan File=p01
BEGIN DESCRIPTION:
Lacy 094
END DESCRIPTION:

--- Lacy 094.p01 (plan) ---

Plan Title=Multiple Run
Short Identifier=Multiple
Geom File=g01
Flow File=f01
Subcritical Flow
K Sum by GR= 0
Std Step Tol= 0.01
Critical Tol= 0.01
Num of Std Step Trials= 20
Max Error Tol= 0.3
Flow Tol Ratio= 0.001
Split Flow NTrial= 30
Split Flow Tol= 0.02
Split Flow Ratio= 0.02
Log Output Level= 0
Friction Slope Method= 1
Unsteady Friction Slope Method= 2
Unsteady Bridges Friction Slope Method= 1
Parabolic Critical Depth
Global Vel Dist=  1 , 1 , 1
Global Log Level= 0
CheckData=True
Encroach Param= -1, 0, 0, 0
BEGIN DESCRIPTION:
Multiple Run
END DESCRIPTION:

--- Lacy 094.f01 (steady flow) ---

Flow Title=Multiple
Number of Profiles=7
Profile Names=10-year,25-year,50-year,1pct_min,100-year,1pct_plu,500-year
River Rch & RM= Lacy 094,Reach-1,5053
     349     448     524     304     607    1212     815
Boundary for River Rch & Prof#=Lacy 094,Reach-1,1
Up Type=0
Dn Type=3
Dn Slope=0.005
Boundary for River Rch & Prof#=Lacy 094,Reach-1,2
Up Type=0
Dn Type=3
Dn Slope=0.005
Boundary for River Rch & Prof#=Lacy 094,Reach-1,3
Up Type=0
Dn Type=3
Dn Slope=0.005
Boundary for River Rch & Prof#=Lacy 094,Reach-1,4
Up Type=0
Dn Type=3
Dn Slope=0.005
Boundary for River Rch & Prof#=Lacy 094,Reach-1,5
Up Type=0
Dn Type=3
Dn Slope=0.005
Boundary for River Rch & Prof#=Lacy 094,Reach-1,6
Up Type=0
Dn Type=3
Dn Slope=0.005
Boundary for River Rch & Prof#=Lacy 094,Reach-1,7
Up Type=0
Dn Type=3
Dn Slope=0.005

--- Lacy 094.g01 (geometry) ---

Geom Title=Existing Conditions

River Reach=Lacy 094,Reach-1
Reach XY= 30
      2730926.00      6882311.00      2730930.96      6882266.34
      2731020.26      6882213.54      2731118.11      6881964.22
      2731034.97      6881854.33      2731169.83      6881718.86
      2731303.19      6881684.95      2731422.33      6881459.42
      2731423.81      6881366.97      2731375.71      6881281.17
      2731436.61      6881150.94      2731481.67      6881112.99
      2731628.45      6881105.53      2731777.47      6880964.54
      2731946.65      6880941.60      2731979.76      6880762.56
      2732167.86      6880517.06      2732236.76      6880351.30
      2732393.05      6880244.50      2732452.17      6880133.87
      2732669.83      6879968.76      2733065.50      6880012.22
      2733341.28      6880110.61      2733479.32      6880069.04
      2733593.05      6880127.48      2733691.09      6880260.82
      2733778.42      6880255.61      2733936.62      6880111.59
      2734126.12      6880204.13      2734176.00      6880161.00

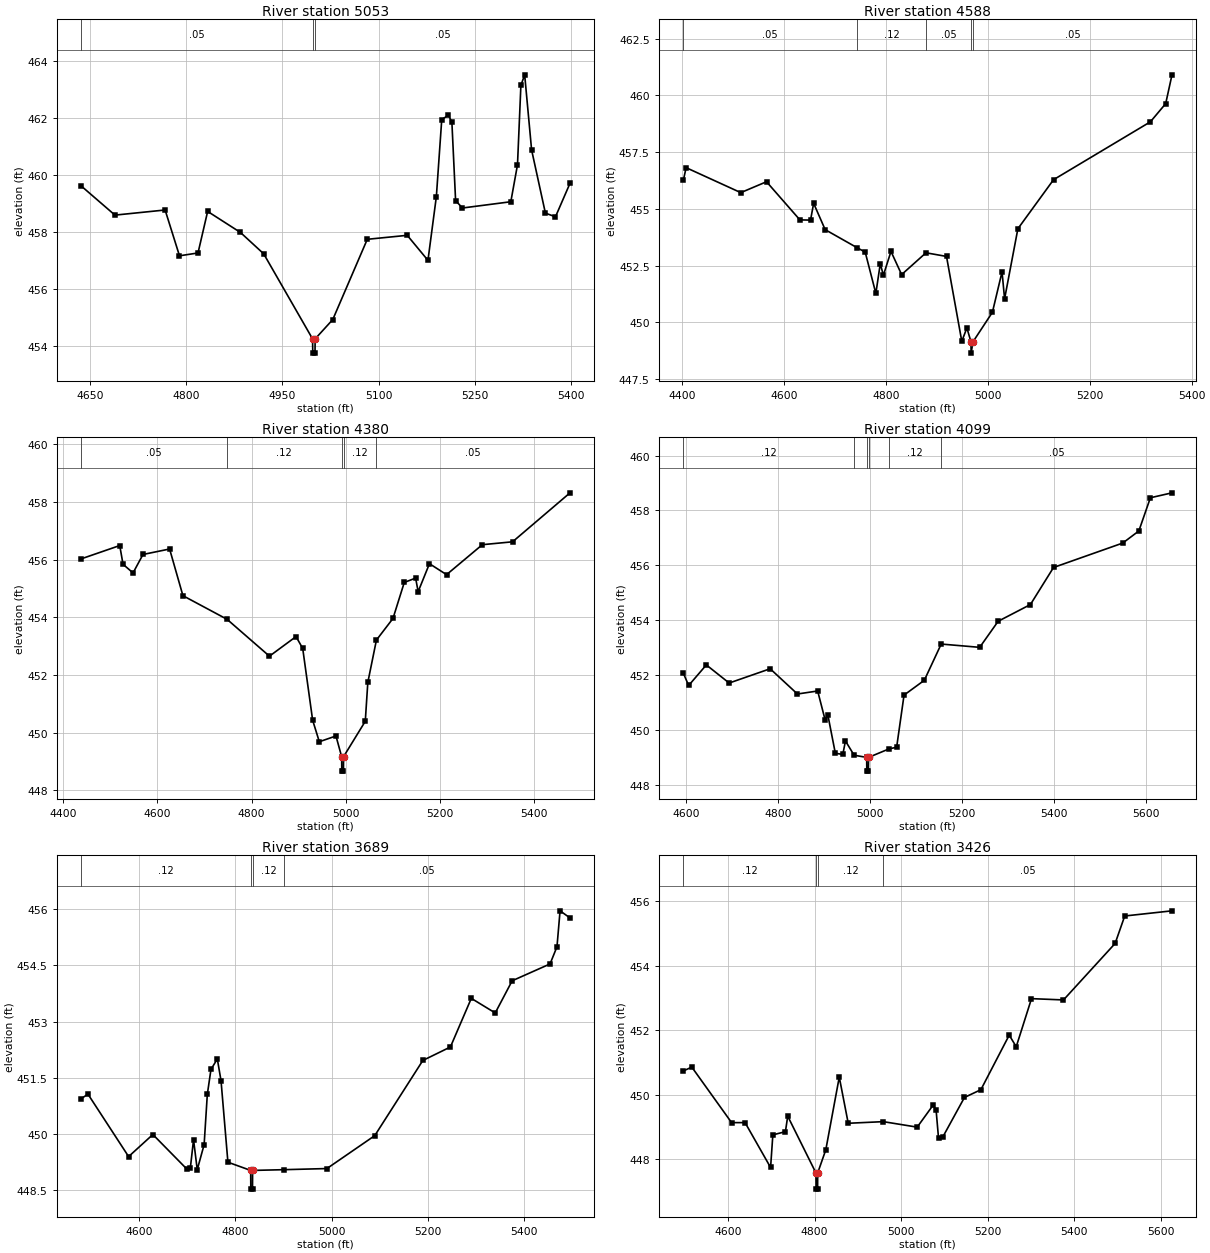
Type RM Length L Ch R = 1,5053,465,465,465
BEGIN DESCRIPTION:
Lacy 094 1864
END DESCRIPTION:
XS GIS Cut Line= 3
      2731293.72      6882445.49      2730990.30      6882245.50
      2730620.36      6882097.37
#Sta/Elev= 30
  4636.6  459.61  4689.0  458.59  4767.2  458.77  4789.6  457.16  4818.5  457.26
  4833.5  458.72  4884.7  457.98  4920.9  457.23  4997.1  454.24  4997.4  453.74
  5000.9  453.74  5001.1  454.24  5028.6  454.92  5082.4  457.74  5144.7  457.88
  5177.0  457.00  5190.1  459.24  5198.5  461.95  5208.9  462.10  5214.3  461.86
  5220.1  459.10  5230.8  458.84  5306.2  459.06  5316.6  460.36  5321.9  463.15
  5327.8  463.52  5338.6  460.88  5360.1  458.66  5375.8  458.53  5398.5  459.71
#Mann=3,-1,0
  4636.6    0.05       0  4997.1    0.04       0  5001.1    0.05       0
Bank Sta=4997.1,5001.1
Exp/Cntr=0.3,0.1

Type RM Length L Ch R = 1,4588,208,208,208
BEGIN DESCRIPTION:
Lacy 094 1863
END DESCRIPTION:
XS GIS Cut Line= 3
      2731554.19      6882100.06      2731197.66      6881850.94
      2730673.58      6881864.57
#Sta/Elev= 30
  4402.2  456.26  4407.7  456.82  4515.0  455.72  4565.5  456.20  4631.0  454.52
  4651.9  454.51  4658.0  455.25  4680.6  454.09  4743.6  453.29  4759.2  453.10
  4780.1  451.28  4788.8  452.59  4794.9  452.08  4809.8  453.13  4830.7  452.11
  4878.5  453.07  4918.8  452.91  4948.8  449.17  4958.8  449.76  4966.8  449.15
  4967.1  448.65  4970.8  449.15  5008.9  450.45  5027.8  452.23  5032.8  451.04
  5058.9  454.13  5128.9  456.29  5319.0  458.84  5349.0  459.64  5361.4  460.91
#Mann=5,-1,0
  4402.2    0.05       0  4743.6    0.12       0  4878.5    0.05       0
  4966.8    0.04       0  4970.8    0.05       0
Bank Sta=4966.8,4970.8
Exp/Cntr=0.3,0.1

Type RM Length L Ch R = 1,4380,281,281,281
BEGIN DESCRIPTION:
Lacy 094 1862
END DESCRIPTION:
XS GIS Cut Line= 3
      2731586.31      6882106.00      2731189.11      6881715.66
      2730742.99      6881533.71
#Sta/Elev= 30
  4438.2  456.03  4519.8  456.49  4526.8  455.84  4548.1  455.54  4569.2  456.18
  4625.8  456.37  4654.1  454.75  4747.9  453.93  4838.0  452.65  4894.5  453.33
  4908.7  452.92  4929.8  450.43  4944.0  449.68  4979.4  449.88  4991.5  449.16
  4991.8  448.66  4995.3  448.66  4995.5  449.16  5041.7  450.39  5047.1  451.74
  5065.4  453.21  5100.6  453.96  5124.6  455.21  5148.7  455.36  5154.1  454.89
  5178.1  455.86  5214.5  455.48  5290.5  456.52  5354.8  456.62  5476.9  458.32
#Mann=5,-1,0
  4438.2    0.05       0  4747.9    0.12       0  4991.5    0.07       0
  4995.5    0.12       0  5065.4    0.05       0
Bank Sta=4991.5,4995.5
Exp/Cntr=0.3,0.1

Type RM Length L Ch R = 1,4099,410,410,410
BEGIN DESCRIPTION:
Lacy 094 1861
END DESCRIPTION:
XS GIS Cut Line= 3
      2731732.87      6881740.61      2731376.37      6881552.09
      2730719.18      6881500.34
#Sta/Elev= 30
  4593.7  452.07  4605.3  451.62  4643.7  452.37  4693.4  451.71  4782.5  452.23
  4841.8  451.31  4885.8  451.42  4902.1  450.36  4907.8  450.56  4924.2  449.15
  4940.5  449.11  4946.2  449.60  4965.0  449.08  4992.4  449.00  4992.6  448.50
  4996.1  448.50  4996.4  449.00  5040.9  449.31  5057.5  449.37  5073.6  451.27
  5117.7  451.81  5154.4  453.13  5238.1  453.01  5278.2  453.96  5348.4  454.57
  5398.6  455.92  5549.1  456.81  5584.1  457.25  5609.2  458.46  5656.2  458.64
#Mann=6,-1,0
  4593.7    0.12       0  4965.0    0.05       0  4992.4   0.035       0
  4996.4    0.05       0  5040.9    0.12       0  5154.4    0.05       0
Bank Sta=4992.4,4996.4
Exp/Cntr=0.3,0.1

Type RM Length L Ch R = 1,3689,263,263,263
BEGIN DESCRIPTION:
Lacy 094 1860
END DESCRIPTION:
XS GIS Cut Line= 3
      2731781.02      6881565.10      2731523.95      6881266.36
      2731035.57      6880882.50
#Sta/Elev= 30
  4480.0  450.94  4493.7  451.06  4578.2  449.39  4628.6  449.98  4698.9  449.06
  4706.5  449.09  4713.1  449.84  4720.8  449.04  4735.1  449.71  4741.7  451.05
  4749.3  451.72  4762.5  452.00  4770.2  451.42  4784.5  449.24  4831.8  449.02
  4832.1  448.52  4835.6  448.52  4835.8  449.02  4901.4  449.04  4990.2  449.07
  5089.6  449.95  5189.5  451.96  5246.8  452.32  5290.2  453.62  5339.9  453.23
  5375.1  454.09  5453.8  454.54  5468.2  455.00  5474.6  455.96  5495.3  455.77
#Mann=4,-1,0
  4480.0    0.12       0  4831.8    0.05       0  4835.8    0.12       0
  4901.4    0.05       0
Bank Sta=4831.8,4835.8
Exp/Cntr=0.3,0.1

Type RM Length L Ch R = 1,3426,61,61,61
BEGIN DESCRIPTION:
Lacy 094 1859
END DESCRIPTION:
XS GIS Cut Line= 3
      2731815.16      6881548.63      2731698.91      6881126.75
      2731090.48      6880796.26
#Sta/Elev= 30
  4496.4  450.74  4516.0  450.86  4608.0  449.14  4639.2  449.14  4698.2  447.75
  4703.4  448.76  4732.5  448.86  4737.8  449.34  4803.1  447.58  4803.4  447.08
  4806.9  447.08  4807.1  447.58  4825.9  448.30  4857.0  450.55  4877.7  449.12
  4958.8  449.17  5037.2  449.00  5073.9  449.68  5080.9  449.53  5086.6  448.65
  5096.6  448.70  5146.5  449.92  5184.5  450.16  5250.0  451.85  5266.2  451.49
  5301.5  452.98  5375.5  452.94  5494.9  454.69  5517.1  455.54  5626.4  455.70
#Mann=4,-1,0
  4496.4    0.12       0  4803.1    0.05       0  4807.1    0.12       0
  4958.8    0.05       0
Bank Sta=4803.1,4807.1
Exp/Cntr=0.3,0.1

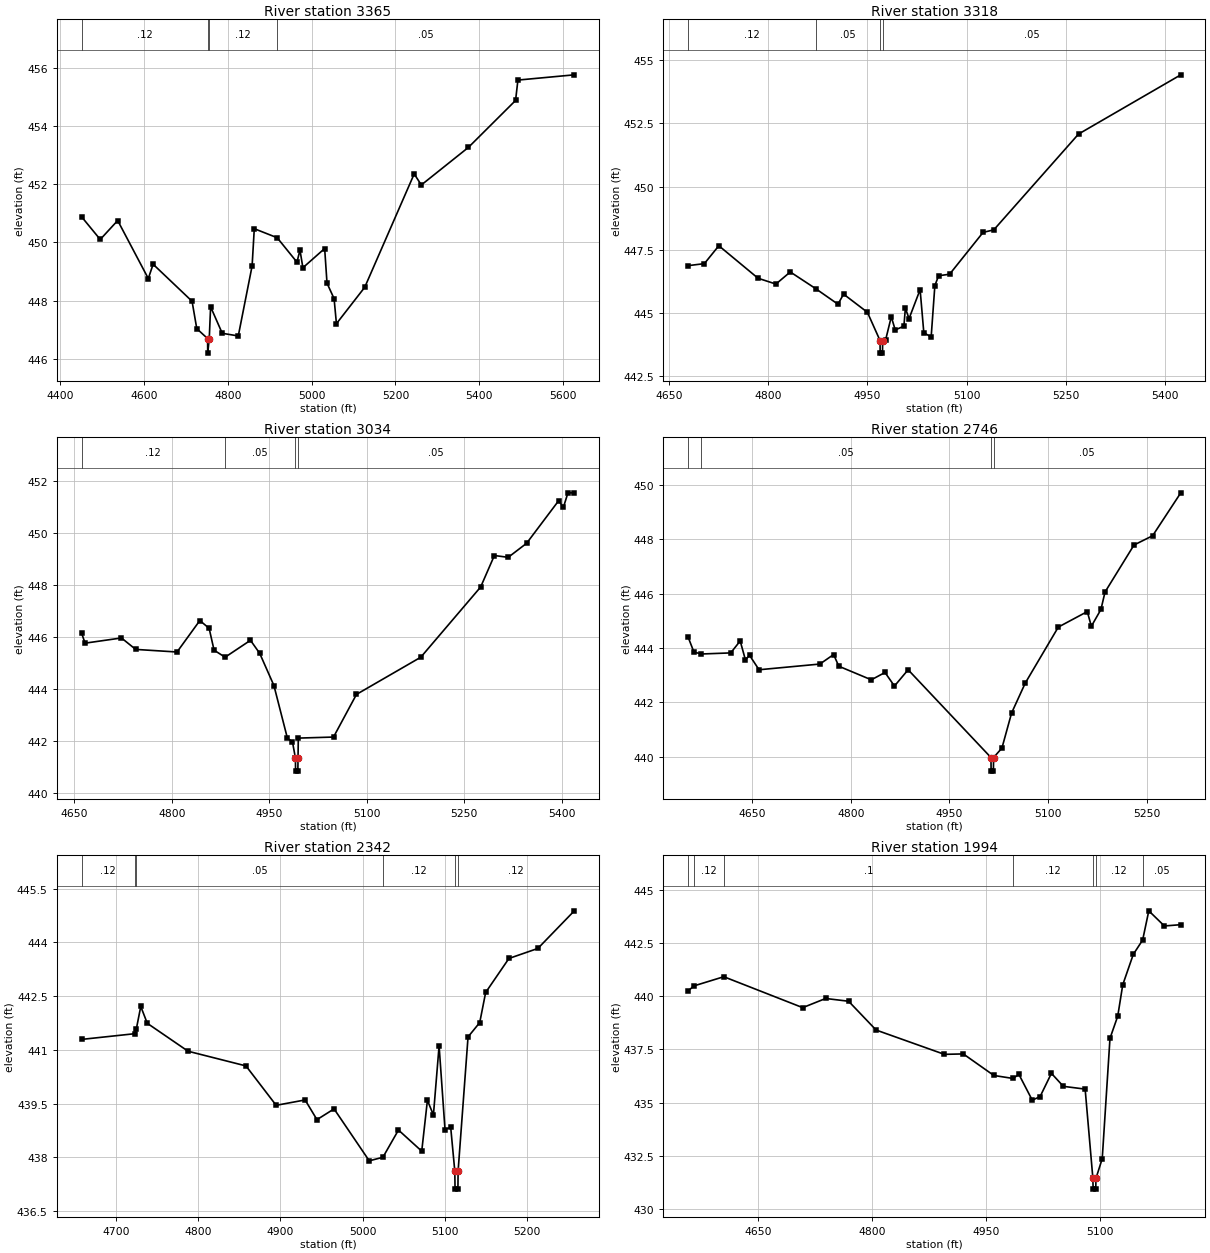
Type RM Length L Ch R = 1,3365,47,47,47
BEGIN DESCRIPTION:
Lacy 094 1858
END DESCRIPTION:
XS GIS Cut Line= 4
      2731869.07      6881563.67      2731728.93      6881098.01
      2731680.22      6881048.38      2731122.31      6880775.72
#Sta/Elev= 30
  4450.3  450.88  4494.9  450.10  4536.6  450.75  4609.7  448.76  4621.2  449.25
  4714.2  447.98  4725.5  447.04  4751.3  446.70  4751.6  446.20  4755.3  446.70
  4758.5  447.79  4786.3  446.88  4824.6  446.79  4857.6  449.19  4862.8  450.47
  4917.5  450.16  4964.8  449.32  4971.9  449.74  4978.9  449.13  5030.9  449.79
  5036.5  448.60  5053.4  448.07  5059.0  447.21  5126.6  448.46  5244.7  452.35
  5261.7  451.97  5374.2  453.26  5486.8  454.87  5492.4  455.57  5627.1  455.75
#Mann=4,-1,0
  4450.3    0.12       0  4751.3    0.05       0  4755.3    0.12       0
  4917.5    0.05       0
Bank Sta=4751.3,4755.3
Exp/Cntr=0.3,0.1

Type RM Length L Ch R = 1,3318,284,284,284
BEGIN DESCRIPTION:
Lacy 094 1857
END DESCRIPTION:
XS GIS Cut Line= 3
      2731984.79      6881197.54      2731714.68      6881018.02
      2731339.31      6880828.11
#Sta/Elev= 30
  4678.7  446.86  4703.4  446.94  4725.3  447.65  4784.6  446.36  4811.6  446.13
  4833.3  446.61  4871.6  445.95  4905.4  445.33  4913.9  445.73  4949.9  445.01
  4969.0  443.89  4969.2  443.39  4972.7  443.39  4973.0  443.89  4977.4  443.91
  4986.0  444.83  4992.0  444.31  5005.1  444.46  5007.3  445.17  5012.9  444.76
  5029.6  445.91  5035.2  444.20  5046.3  444.03  5051.9  446.07  5057.6  446.46
  5074.2  446.52  5124.8  448.18  5141.0  448.28  5269.1  452.08  5423.7  454.43
#Mann=4,-1,0
  4678.7    0.12       0  4871.6    0.05       0  4969.0    0.05       0
  4973.0    0.05       0
Bank Sta=4969,4973
Exp/Cntr=0.3,0.1

Type RM Length L Ch R = 1,3034,288,288,288
BEGIN DESCRIPTION:
Lacy 094 1856
END DESCRIPTION:
XS GIS Cut Line= 3
      2732187.80      6881176.38      2731967.81      6880923.54
      2731672.68      6880620.43
#Sta/Elev= 30
  4661.2  446.15  4666.6  445.76  4722.6  445.96  4744.5  445.52  4808.1  445.42
  4843.2  446.63  4857.5  446.33  4865.1  445.49  4882.1  445.22  4921.1  445.87
  4935.3  445.37  4957.2  444.13  4978.0  442.10  4985.7  441.97  4990.3  441.34
  4990.5  440.84  4994.0  440.84  4994.3  441.34  4994.7  442.11  5048.9  442.15
  5084.2  443.79  5183.2  445.22  5275.3  447.92  5296.4  449.13  5317.7  449.06
  5346.0  449.60  5395.4  451.24  5402.6  450.98  5409.6  451.54  5419.4  451.54
#Mann=4,-1,0
  4661.2    0.12       0  4882.1    0.05       0  4990.3    0.04       0
  4994.3    0.05       0
Bank Sta=4990.3,4994.3
Exp/Cntr=0.3,0.1

Type RM Length L Ch R = 1,2746,404,404,404
BEGIN DESCRIPTION:
Lacy 094 1855
END DESCRIPTION:
XS GIS Cut Line= 3
      2732319.64      6880999.40      2732038.70      6880655.06
      2731791.22      6880475.78
#Sta/Elev= 30
  4552.1  444.41  4561.1  443.85  4572.6  443.78  4617.1  443.82  4631.5  444.26
  4639.4  443.57  4645.8  443.73  4660.2  443.20  4752.8  443.41  4773.7  443.76
  4781.6  443.33  4831.1  442.83  4851.9  443.10  4866.3  442.60  4887.1  443.20
  5013.2  439.97  5013.4  439.47  5016.9  439.47  5017.2  439.97  5029.9  440.32
  5044.6  441.61  5065.4  442.71  5115.7  444.77  5159.8  445.34  5166.0  444.80
  5180.6  445.42  5186.8  446.06  5230.9  447.79  5259.2  448.13  5302.1  449.71
#Mann=4,-1,0
  4552.1    0.12       0  4572.6    0.05       0  5013.2    0.04       0
  5017.2    0.05       0
Bank Sta=5013.2,5017.2
Exp/Cntr=0.3,0.1

Type RM Length L Ch R = 1,2342,348,348,348
BEGIN DESCRIPTION:
Lacy 094 1854
END DESCRIPTION:
XS GIS Cut Line= 3
      2732472.94      6880596.04      2732257.67      6880329.45
      2732072.60      6880151.93
#Sta/Elev= 30
  4658.2  441.29  4723.1  441.45  4724.7  441.57  4730.2  442.21  4738.1  441.74
  4787.7  440.96  4858.1  440.55  4894.8  439.45  4930.0  439.60  4944.4  439.05
  4965.2  439.35  5008.0  437.90  5024.6  438.00  5043.5  438.76  5071.8  438.17
  5078.7  439.59  5086.0  439.18  5092.9  441.11  5100.1  438.77  5107.0  438.84
  5112.0  437.61  5112.3  437.11  5115.8  437.11  5116.0  437.61  5128.1  441.36
  5142.3  441.76  5149.5  442.60  5177.8  443.55  5213.0  443.83  5257.3  444.88
#Mann=6,-1,0
  4658.2    0.12       0  4723.1     0.1       0  4724.7    0.05       0
  5024.6    0.12       0  5112.0    0.04       0  5116.0    0.12       0
Bank Sta=5112,5116
Exp/Cntr=0.3,0.1

Type RM Length L Ch R = 1,1994,287,287,287
BEGIN DESCRIPTION:
Lacy 094 1853
END DESCRIPTION:
XS GIS Cut Line= 3
      2732548.83      6880551.08      2732500.30      6880120.44
      2732455.38      6879909.85
#Sta/Elev= 30
  4557.7  440.24  4565.5  440.48  4604.8  440.91  4708.7  439.46  4738.9  439.89
  4769.1  439.76  4805.3  438.41  4895.2  437.27  4920.1  437.29  4960.3  436.28
  4985.5  436.14  4993.3  436.33  5010.9  435.12  5021.2  435.29  5036.1  436.38
  5051.8  435.77  5080.5  435.64  5090.7  431.45  5091.0  430.95  5094.5  430.95
  5094.7  431.45  5103.0  432.38  5113.2  438.02  5123.4  439.06  5130.0  440.53
  5143.9  441.96  5156.2  442.63  5164.3  444.00  5184.8  443.29  5206.4  443.35
#Mann=7,-1,0
  4557.7     0.1       0  4565.5    0.12       0  4604.8     0.1       0
  4985.5    0.12       0  5090.7    0.07       0  5094.7    0.12       0
  5156.2    0.05       0
Bank Sta=5090.7,5094.7
Exp/Cntr=0.3,0.1

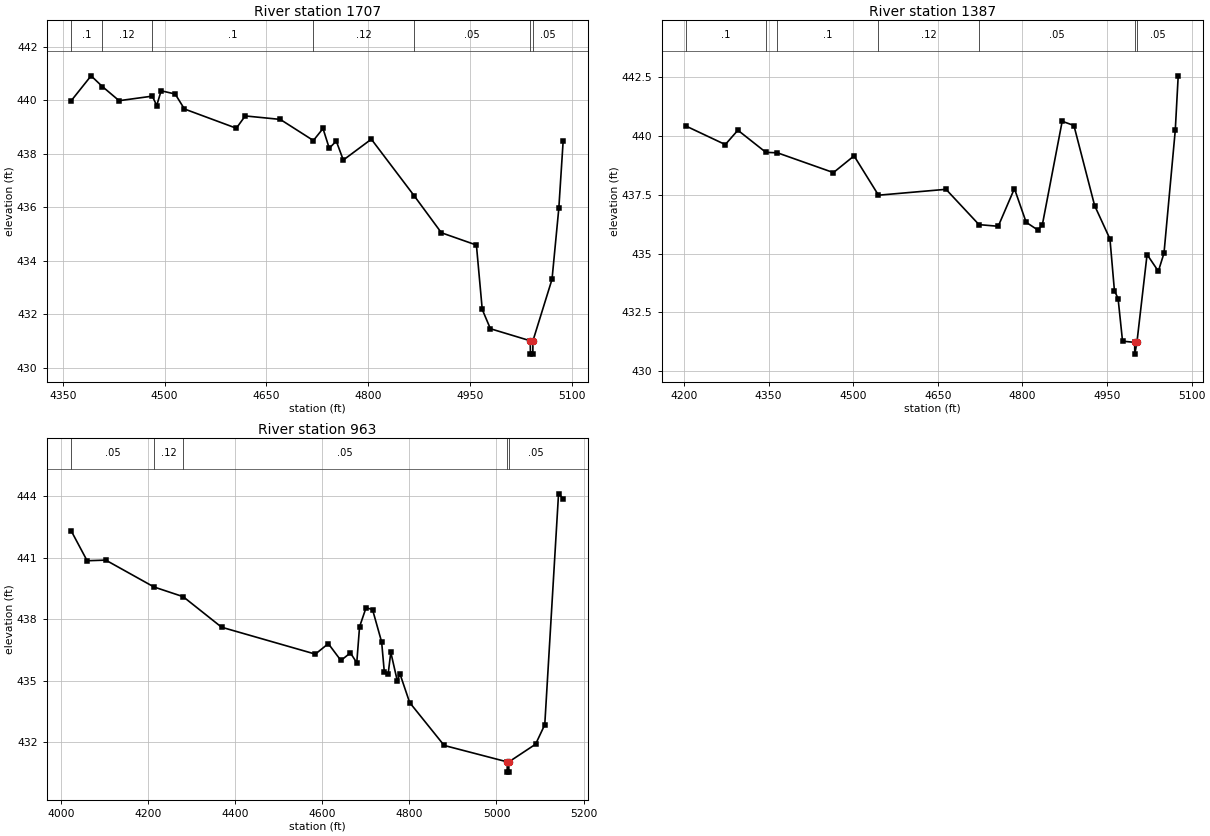
Type RM Length L Ch R = 1,1707,320,320,320
BEGIN DESCRIPTION:
Lacy 094 1852
END DESCRIPTION:
XS GIS Cut Line= 3
      2732570.17      6880579.28      2732728.59      6879959.57
      2732732.04      6879874.58
#Sta/Elev= 30
  4362.4  439.99  4391.6  440.92  4408.2  440.52  4432.9  439.99  4481.8  440.16
  4488.3  439.81  4494.8  440.36  4515.5  440.24  4529.1  439.68  4605.6  438.96
  4618.7  439.42  4670.3  439.29  4719.1  438.50  4733.3  438.95  4742.5  438.21
  4752.8  438.48  4763.2  437.77  4804.5  438.55  4867.7  436.43  4907.7  435.05
  4959.3  434.59  4967.9  432.18  4979.9  431.46  5038.6  431.01  5038.9  430.51
  5042.4  430.51  5042.6  431.01  5070.7  433.31  5080.7  435.96  5087.1  438.48
#Mann=7,-1,0
  4362.4     0.1       0  4408.2    0.12       0  4481.8     0.1       0
  4719.1    0.12       0  4867.7    0.05       0  5038.6    0.05       0
  5042.6    0.05       0
Bank Sta=5038.6,5042.6
Exp/Cntr=0.3,0.1

Type RM Length L Ch R = 1,1387,424,424,424
BEGIN DESCRIPTION:
Lacy 094 1851
END DESCRIPTION:
XS GIS Cut Line= 3
      2732539.55      6880632.27      2733032.15      6880029.09
      2733035.81      6879935.82
#Sta/Elev= 30
  4204.1  440.41  4273.2  439.63  4295.5  440.24  4345.2  439.30  4365.7  439.28
  4464.9  438.44  4501.5  439.15  4544.8  437.48  4664.5  437.73  4723.0  436.23
  4757.1  436.16  4785.8  437.76  4806.6  436.33  4827.4  436.00  4835.3  436.22
  4870.5  440.62  4891.3  440.44  4928.0  437.04  4955.2  435.62  4963.1  433.43
  4969.6  433.09  4977.5  431.28  4999.0  431.23  4999.2  430.73  5003.0  431.23
  5021.0  434.96  5041.0  434.25  5051.0  435.02  5071.0  440.24  5076.2  442.55
#Mann=7,-1,0
  4204.1     0.1       0  4345.2    0.12       0  4365.7     0.1       0
  4544.8    0.12       0  4723.0    0.05       0  4999.0    0.05       0
  5003.0    0.05       0
Bank Sta=4999,5003
Exp/Cntr=0.3,0.1

Type RM Length L Ch R = 1,963,0,0,0
BEGIN DESCRIPTION:
Lacy 094 65
END DESCRIPTION:
XS GIS Cut Line= 3
      2732875.98      6880911.03      2733426.00      6880111.00
      2733375.99      6879960.98
#Sta/Elev= 30
  4024.1  442.30  4060.5  440.85  4103.3  440.88  4214.1  439.57  4280.8  439.10
  4369.2  437.61  4584.3  436.30  4614.1  436.81  4643.0  435.99  4664.8  436.36
  4679.4  435.88  4685.8  437.63  4700.7  438.56  4715.6  438.47  4736.5  436.89
  4742.6  435.43  4751.4  435.33  4757.5  436.39  4772.4  435.00  4778.5  435.34
  4800.8  433.94  4880.0  431.85  5024.6  431.05  5024.8  430.55  5028.3  430.55
  5028.6  431.05  5089.8  431.91  5110.9  432.86  5142.5  444.11  5153.1  443.88
#Mann=5,-1,0
  4024.1    0.05       0  4214.1    0.12       0  4280.8    0.05       0
  5024.6    0.04       0  5028.6    0.05       0
Bank Sta=5024.6,5028.6
Exp/Cntr=0.3,0.1

Chan Stop Cuts=-1