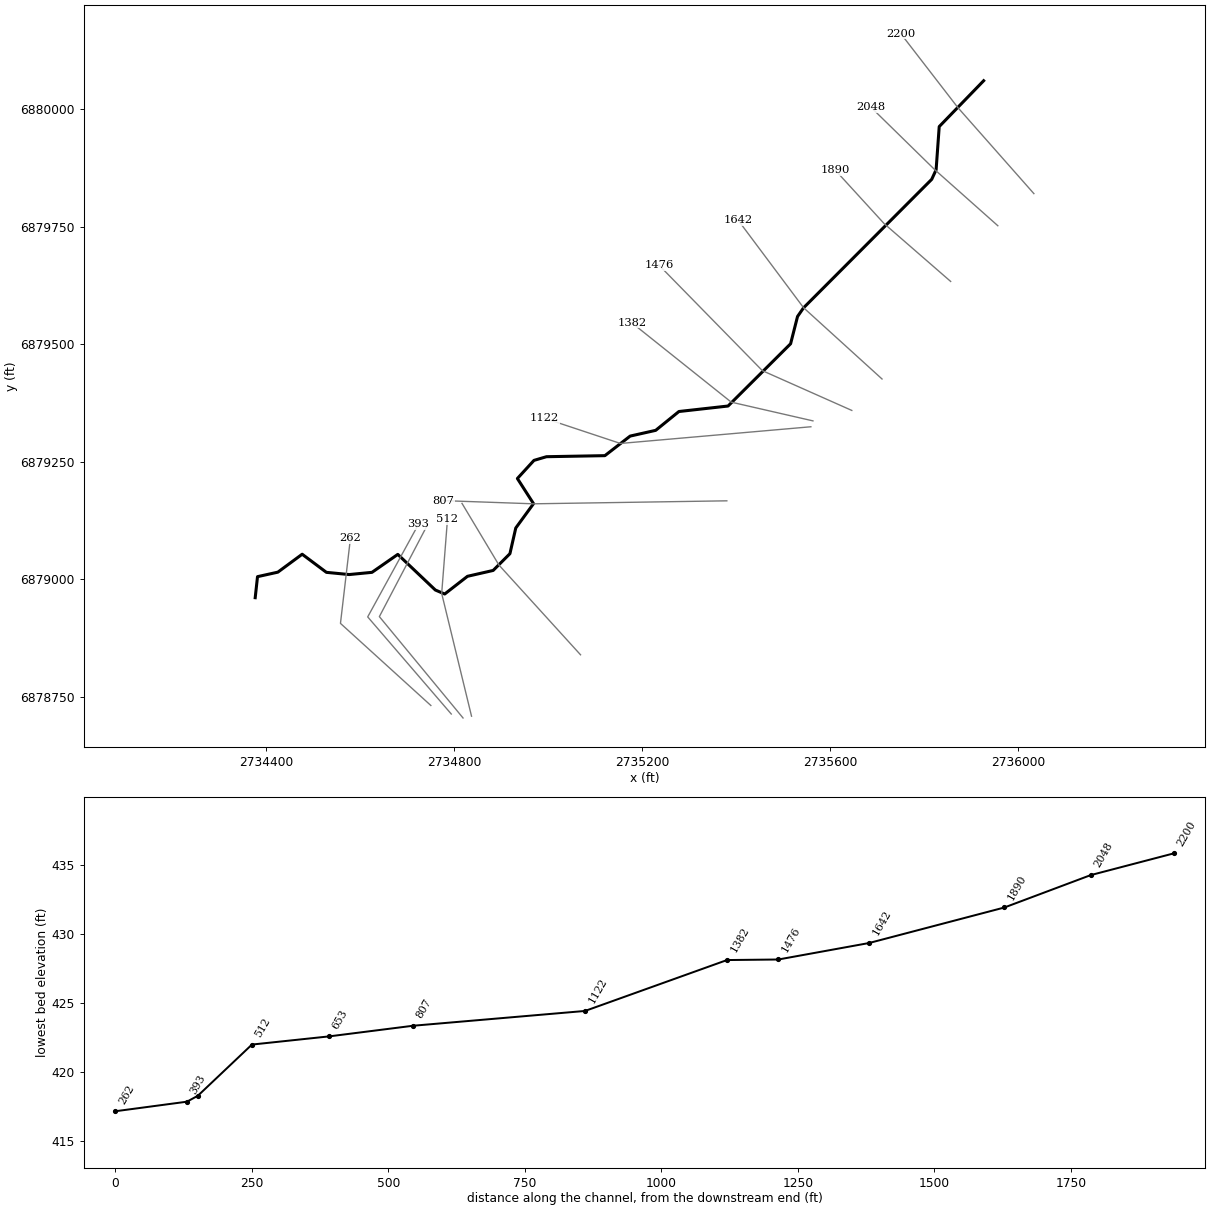
--- Lacy 095.prj (project) ---

Proj Title=Lacy 095 Base Level Engineering
Current Plan=p01
Default Exp/Contr=0.3,0.1
English Units
Geom File=g01
Flow File=f01
Plan File=p01
BEGIN DESCRIPTION:
Lacy 095
END DESCRIPTION:

--- Lacy 095.p01 (plan) ---

Plan Title=Multiple Run
Short Identifier=Multiple
Geom File=g01
Flow File=f01
Subcritical Flow
K Sum by GR= 0
Std Step Tol= 0.01
Critical Tol= 0.01
Num of Std Step Trials= 20
Max Error Tol= 0.3
Flow Tol Ratio= 0.001
Split Flow NTrial= 30
Split Flow Tol= 0.02
Split Flow Ratio= 0.02
Log Output Level= 0
Friction Slope Method= 1
Unsteady Friction Slope Method= 2
Unsteady Bridges Friction Slope Method= 1
Parabolic Critical Depth
Global Vel Dist=  1 , 1 , 1
Global Log Level= 0
CheckData=True
Encroach Param= -1, 0, 0, 0
BEGIN DESCRIPTION:
Multiple Run
END DESCRIPTION:

--- Lacy 095.f01 (steady flow) ---

Flow Title=Multiple
Number of Profiles=7
Profile Names=10-year,25-year,50-year,1pct_min,100-year,1pct_plu,500-year
River Rch & RM= Lacy 095,Reach-1,2200
     229     286     328     188     376     750     490
Boundary for River Rch & Prof#=Lacy 095,Reach-1,1
Up Type=0
Dn Type=3
Dn Slope=0.005
Boundary for River Rch & Prof#=Lacy 095,Reach-1,2
Up Type=0
Dn Type=3
Dn Slope=0.005
Boundary for River Rch & Prof#=Lacy 095,Reach-1,3
Up Type=0
Dn Type=3
Dn Slope=0.005
Boundary for River Rch & Prof#=Lacy 095,Reach-1,4
Up Type=0
Dn Type=3
Dn Slope=0.005
Boundary for River Rch & Prof#=Lacy 095,Reach-1,5
Up Type=0
Dn Type=3
Dn Slope=0.005
Boundary for River Rch & Prof#=Lacy 095,Reach-1,6
Up Type=0
Dn Type=3
Dn Slope=0.005
Boundary for River Rch & Prof#=Lacy 095,Reach-1,7
Up Type=0
Dn Type=3
Dn Slope=0.005

--- Lacy 095.g01 (geometry) ---

Geom Title=Existing Conditions

River Reach=Lacy 095,Reach-1
Reach XY= 30
      2735926.00      6880061.00      2735831.46      6879963.45
      2735824.84      6879871.48      2735815.48      6879851.21
      2735542.65      6879577.67      2735529.98      6879559.35
      2735515.22      6879501.32      2735382.17      6879368.86
      2735277.59      6879357.17      2735228.18      6879317.11
      2735173.82      6879304.88      2735120.07      6879263.25
      2734995.77      6879261.02      2734969.18      6879253.18
      2734933.87      6879214.62      2734968.22      6879161.10
      2734930.45      6879109.32      2734918.00      6879054.67
      2734882.33      6879019.00      2734827.68      6879006.52
      2734779.23      6878968.85      2734759.30      6878977.35
      2734679.42      6879053.17      2734624.50      6879014.95
      2734576.00      6879010.25      2734527.50      6879014.94
      2734475.96      6879053.51      2734424.19      6879015.35
      2734380.92      6879005.77      2734376.00      6878961.00

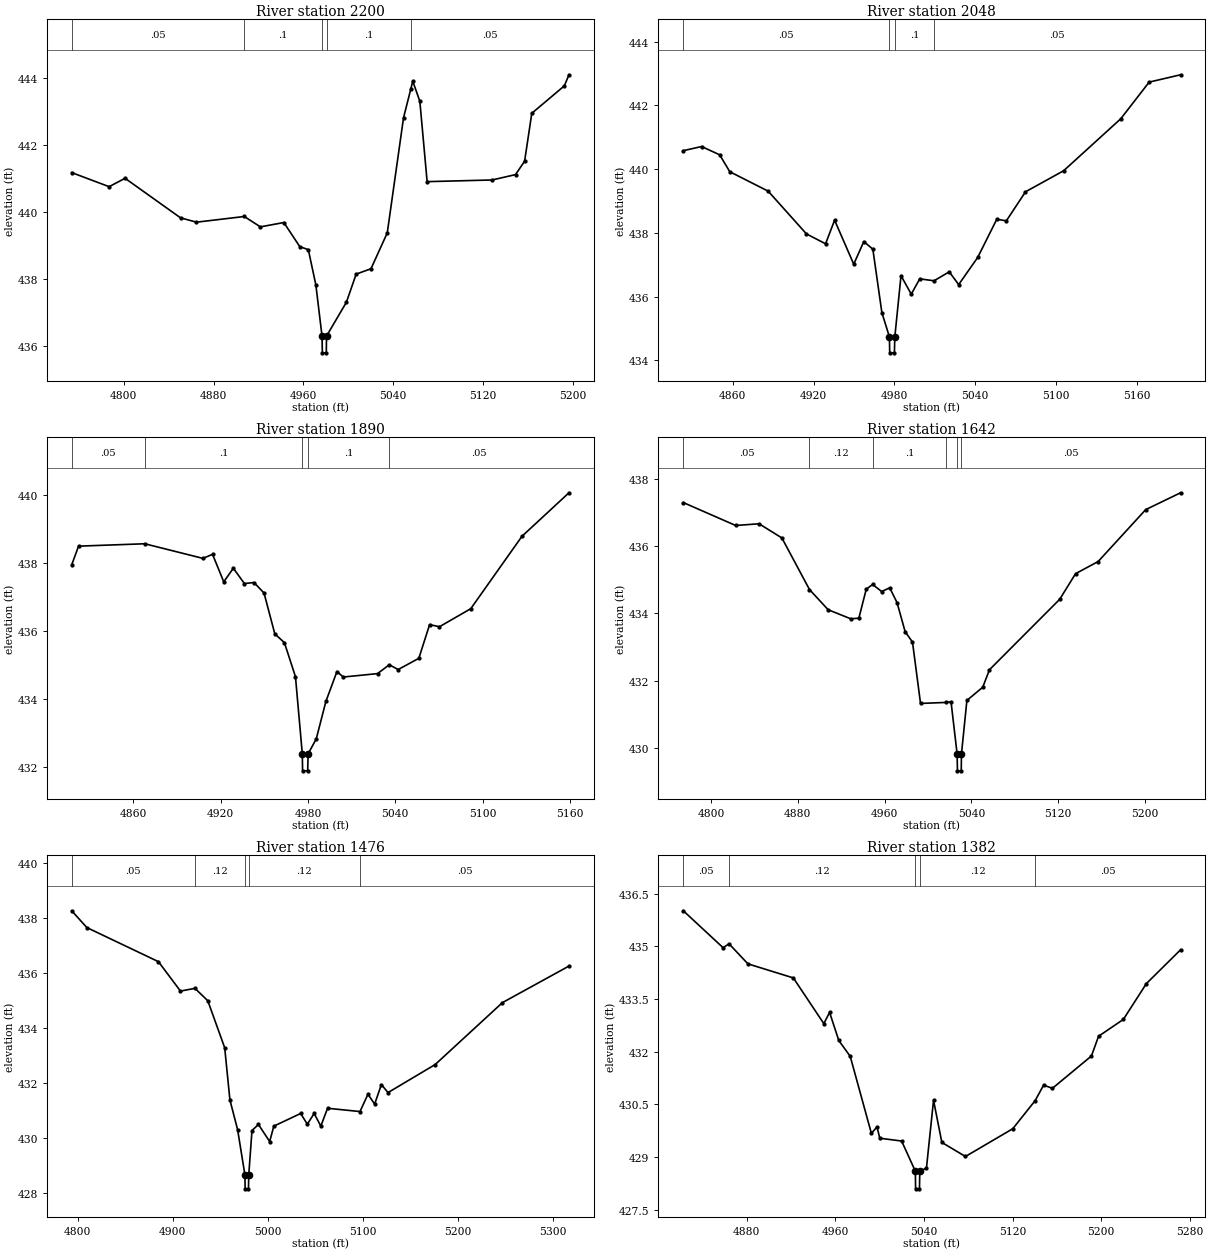
Type RM Length L Ch R = 1,2200,152,152,152
BEGIN DESCRIPTION:
Lacy 095 1847
END DESCRIPTION:
XS GIS Cut Line= 3
      2736032.88      6879820.82      2735870.88      6880004.18
      2735749.82      6880161.02
#Sta/Elev= 30
  4753.7  441.19  4787.0  440.77  4801.2  441.02  4850.6  439.84  4864.8  439.71
  4907.4  439.88  4921.7  439.57  4942.6  439.70  4956.8  438.98  4964.4  438.89
  4971.1  437.84  4976.6  436.31  4976.9  435.81  4980.4  435.81  4980.6  436.31
  4998.3  437.32  5007.0  438.16  5020.2  438.32  5034.7  439.39  5049.2  442.83
  5055.7  443.69  5057.4  443.92  5063.7  443.32  5070.2  440.92  5128.1  440.97
  5148.9  441.13  5157.0  441.53  5163.4  442.96  5192.4  443.78  5196.5  444.11
#Mann=5,-1,0
  4753.7    0.05       0  4907.4     0.1       0  4976.6    0.07       0
  4980.6     0.1       0  5055.7    0.05       0
Bank Sta=4976.6,4980.6
Exp/Cntr=0.3,0.1

Type RM Length L Ch R = 1,2048,158,158,158
BEGIN DESCRIPTION:
Lacy 095 1846
END DESCRIPTION:
XS GIS Cut Line= 3
      2735956.16      6879752.48      2735821.46      6879872.20
      2735686.48      6880004.33
#Sta/Elev= 30
  4823.3  440.58  4836.9  440.71  4850.3  440.45  4857.8  439.92  4886.3  439.31
  4914.7  437.97  4928.9  437.66  4935.6  438.40  4949.8  437.02  4957.3  437.73
  4964.0  437.49  4970.7  435.50  4976.3  434.74  4976.5  434.24  4980.0  434.24
  4980.3  434.74  4984.9  436.66  4992.5  436.08  4998.8  436.56  5009.4  436.50
  5020.7  436.78  5027.7  436.38  5041.8  437.23  5056.0  438.43  5063.1  438.38
  5077.3  439.29  5105.6  439.95  5148.0  441.58  5169.1  442.73  5192.4  442.96
#Mann=4,-1,0
  4823.3    0.05       0  4976.3    0.07       0  4980.3     0.1       0
  5009.4    0.05       0
Bank Sta=4976.3,4980.3
Exp/Cntr=0.3,0.1

Type RM Length L Ch R = 1,1890,248,248,248
BEGIN DESCRIPTION:
Lacy 095 1845
END DESCRIPTION:
XS GIS Cut Line= 3
      2735855.79      6879633.95      2735714.33      6879756.91
      2735610.16      6879870.83
#Sta/Elev= 30
  4817.6  437.96  4822.3  438.51  4867.8  438.58  4907.8  438.15  4914.4  438.27
  4922.1  437.46  4928.7  437.86  4936.3  437.41  4942.9  437.44  4949.8  437.13
  4957.2  435.93  4963.8  435.67  4971.4  434.67  4976.1  432.40  4976.3  431.90
  4979.8  431.90  4980.1  432.40  4985.7  432.84  4992.3  433.94  4999.9  434.82
  5004.3  434.66  5027.8  434.76  5035.9  435.02  5042.0  434.88  5056.2  435.21
  5063.6  436.20  5070.4  436.14  5091.9  436.67  5127.1  438.80  5159.4  440.08
#Mann=5,-1,0
  4817.6    0.05       0  4867.8     0.1       0  4976.1    0.07       0
  4980.1     0.1       0  5035.9    0.05       0
Bank Sta=4976.1,4980.1
Exp/Cntr=0.3,0.1

Type RM Length L Ch R = 1,1642,166,166,166
BEGIN DESCRIPTION:
Lacy 095 1843
END DESCRIPTION:
XS GIS Cut Line= 3
      2735709.76      6879426.39      2735542.77      6879578.07
      2735403.64      6879764.22
#Sta/Elev= 30
  4774.6  437.29  4822.8  436.61  4844.4  436.66  4865.4  436.24  4890.8  434.71
  4908.0  434.11  4928.9  433.84  4936.3  433.86  4943.1  434.72  4949.0  434.86
  4957.3  434.65  4964.7  434.76  4971.5  434.32  4978.9  433.46  4985.7  433.15
  4993.1  431.33  5017.0  431.36  5021.2  431.38  5026.8  429.83  5027.1  429.33
  5030.6  429.33  5030.8  429.83  5035.8  431.42  5050.4  431.81  5056.6  432.33
  5121.3  434.42  5135.9  435.18  5156.7  435.54  5200.5  437.08  5232.6  437.58
#Mann=6,-1,0
  4774.6    0.05       0  4890.8    0.12       0  4949.0     0.1       0
  5017.0    0.05       0  5026.8    0.07       0  5030.8    0.05       0
Bank Sta=5026.8,5030.8
Exp/Cntr=0.3,0.1

Type RM Length L Ch R = 1,1476,94,94,94
BEGIN DESCRIPTION:
Lacy 095 1844
END DESCRIPTION:
XS GIS Cut Line= 3
      2735645.44      6879359.48      2735455.19      6879444.06
      2735234.87      6879668.90
#Sta/Elev= 30
  4793.7  438.25  4809.6  437.64  4884.9  436.40  4908.1  435.33  4923.3  435.43
  4936.8  434.98  4954.6  433.27  4960.1  431.37  4968.2  430.29  4975.9  428.64
  4976.1  428.14  4979.6  428.14  4979.9  428.64  4983.3  430.26  4990.1  430.48
  5001.9  429.86  5006.3  430.42  5034.5  430.88  5041.5  430.49  5048.7  430.88
  5055.7  430.42  5062.8  431.07  5096.9  430.95  5105.3  431.58  5112.3  431.22
  5119.4  431.93  5126.4  431.64  5176.0  432.66  5246.7  434.91  5316.7  436.24
#Mann=5,-1,0
  4793.7    0.05       0  4923.3    0.12       0  4975.9    0.07       0
  4979.9    0.12       0  5096.9    0.05       0
Bank Sta=4975.9,4979.9
Exp/Cntr=0.3,0.1

Type RM Length L Ch R = 1,1382,260,260,260
BEGIN DESCRIPTION:
Lacy 095 1842
END DESCRIPTION:
XS GIS Cut Line= 3
      2735562.78      6879337.24      2735388.94      6879377.09
      2735177.63      6879545.73
#Sta/Elev= 30
  4822.9  436.01  4858.8  434.96  4864.2  435.07  4881.2  434.50  4922.2  434.10
  4949.7  432.80  4954.9  433.12  4963.2  432.32  4973.5  431.87  4992.6  429.68
  4997.7  429.86  5000.2  429.54  5019.9  429.46  5032.3  428.60  5032.5  428.10
  5036.0  428.10  5036.3  428.60  5042.3  428.69  5048.7  430.62  5056.2  429.42
  5077.5  429.02  5120.2  429.81  5140.4  430.61  5148.0  431.05  5156.0  430.96
  5191.2  431.88  5197.6  432.44  5220.0  432.92  5240.8  433.94  5271.6  434.90
#Mann=5,-1,0
  4822.9    0.05       0  4864.2    0.12       0  5032.3    0.07       0
  5036.3    0.12       0  5140.4    0.05       0
Bank Sta=5032.3,5036.3
Exp/Cntr=0.3,0.1

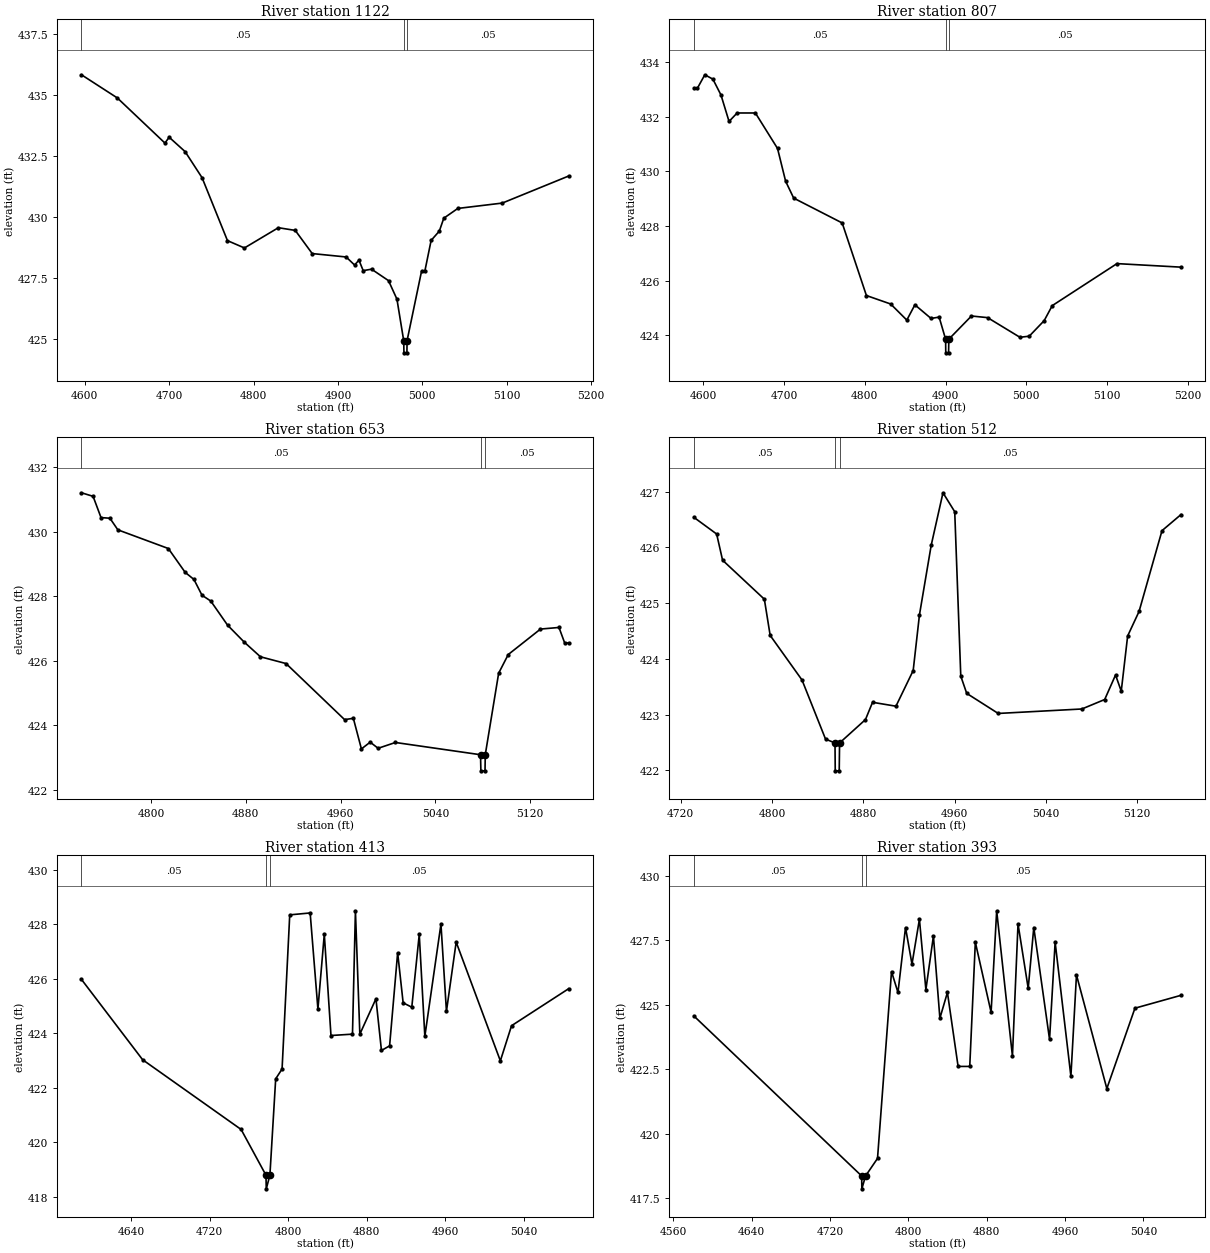
Type RM Length L Ch R = 1,1122,315,315,315
BEGIN DESCRIPTION:
Lacy 095 1841
END DESCRIPTION:
XS GIS Cut Line= 3
      2735558.38      6879324.73      2735153.13      6879289.20
      2734991.31      6879342.89
#Sta/Elev= 30
  4596.1  435.82  4638.6  434.87  4695.0  433.02  4700.0  433.26  4718.9  432.67
  4739.0  431.60  4769.1  429.02  4789.2  428.72  4829.4  429.55  4849.4  429.44
  4869.5  428.49  4909.7  428.35  4919.7  428.02  4924.9  428.22  4929.9  427.79
  4939.8  427.85  4959.9  427.38  4969.9  426.62  4977.9  424.92  4978.2  424.42
  4981.7  424.42  4981.9  424.92  4999.0  427.76  5002.9  427.76  5010.4  429.03
  5020.1  429.41  5025.4  429.94  5042.0  430.34  5094.7  430.56  5173.4  431.67
#Mann=3,-1,0
  4596.1    0.05       0  4977.9    0.05       0  4981.9    0.05       0
Bank Sta=4977.9,4981.9
Exp/Cntr=0.3,0.1

Type RM Length L Ch R = 1,807,154,154,154
BEGIN DESCRIPTION:
Lacy 095 1840
END DESCRIPTION:
XS GIS Cut Line= 3
      2735379.55      6879167.14      2734967.96      6879160.78
      2734776.72      6879167.53
#Sta/Elev= 30
  4588.5  433.04  4592.8  433.04  4602.1  433.54  4612.1  433.38  4622.1  432.80
  4632.1  431.83  4642.1  432.14  4664.7  432.14  4692.1  430.84  4702.1  429.64
  4712.1  429.02  4772.1  428.11  4802.1  425.45  4832.1  425.14  4852.1  424.55
  4862.1  425.11  4882.1  424.61  4892.1  424.66  4900.1  423.85  4900.3  423.35
  4903.8  423.35  4904.1  423.85  4932.1  424.70  4952.1  424.64  4992.1  423.92
  5003.6  423.96  5022.1  424.53  5032.1  425.08  5112.2  426.62  5191.5  426.49
#Mann=3,-1,0
  4588.5    0.05       0  4900.1    0.04       0  4904.1    0.05       0
Bank Sta=4900.1,4904.1
Exp/Cntr=0.3,0.1

Type RM Length L Ch R = 1,653,141,141,141
BEGIN DESCRIPTION:
Lacy 095 1839
END DESCRIPTION:
XS GIS Cut Line= 3
      2735068.26      6878839.51      2734894.61      6879030.50
      2734816.01      6879161.72
#Sta/Elev= 30
  4741.3  431.21  4751.1  431.10  4757.8  430.44  4765.3  430.42  4772.0  430.06
  4814.6  429.48  4828.8  428.74  4836.2  428.52  4843.0  428.03  4850.4  427.85
  4864.6  427.10  4878.5  426.58  4892.3  426.12  4913.9  425.91  4963.3  424.17
  4970.7  424.21  4977.5  423.26  4984.9  423.47  4991.6  423.28  5006.2  423.46
  5078.0  423.08  5078.3  422.58  5081.8  422.58  5082.0  423.08  5093.3  425.61
  5101.4  426.19  5128.6  426.98  5144.2  427.03  5149.0  426.55  5152.4  426.55
#Mann=3,-1,0
  4741.3    0.05       0  5078.0    0.04       0  5082.0    0.05       0
Bank Sta=5078,5082
Exp/Cntr=0.3,0.1

Type RM Length L Ch R = 1,512,99,99,99
BEGIN DESCRIPTION:
Lacy 095 1838
END DESCRIPTION:
XS GIS Cut Line= 3
      2734836.30      6878708.87      2734772.79      6878970.11
      2734785.13      6879127.68
#Sta/Elev= 30
  4731.6  426.54  4751.6  426.24  4756.8  425.77  4793.4  425.07  4798.5  424.42
  4826.4  423.62  4847.0  422.56  4855.3  422.49  4855.5  421.99  4859.0  421.99
  4859.3  422.49  4882.0  422.91  4888.2  423.22  4908.7  423.15  4923.8  423.79
  4929.3  424.79  4939.6  426.04  4949.9  426.98  4960.2  426.64  4965.5  423.69
  4970.7  423.38  4998.3  423.02  5071.6  423.10  5091.6  423.27  5101.1  423.71
  5106.1  423.42  5111.7  424.41  5121.7  424.85  5141.8  426.30  5158.5  426.59
#Mann=3,-1,0
  4731.6    0.05       0  4855.3    0.04       0  4859.3    0.05       0
Bank Sta=4855.3,4859.3
Exp/Cntr=0.3,0.1

Type RM Length L Ch R = 1,413,20,20,20
BEGIN DESCRIPTION:
Lacy 095 1850
END DESCRIPTION:
XS GIS Cut Line= 3
      2734818.24      6878705.07      2734640.20      6878920.74
      2734740.74      6879112.53
#Sta/Elev= 30
  4589.5  425.98  4651.8  423.03  4752.1  420.47  4777.4  418.79  4777.7  418.29
  4781.4  418.79  4787.3  422.33  4793.8  422.69  4801.6  428.35  4822.4  428.42
  4830.3  424.89  4836.8  427.64  4843.6  423.92  4865.5  423.97  4868.5  428.50
  4873.0  423.97  4889.4  425.27  4895.0  423.37  4903.3  423.54  4911.5  426.96
  4917.1  425.12  4925.9  424.96  4933.5  427.63  4939.2  423.89  4955.6  428.01
  4961.2  424.81  4971.1  427.35  5016.1  422.99  5027.5  424.28  5085.7  425.64
#Mann=3,-1,0
  4589.5    0.05       0  4777.4    0.04       0  4781.4    0.05       0
Bank Sta=4777.4,4781.4
Exp/Cntr=0.3,0.1

Type RM Length L Ch R = 1,393,131,131,131
BEGIN DESCRIPTION:
Lacy 095 1849
END DESCRIPTION:
XS GIS Cut Line= 3
      2734793.18      6878713.52      2734615.38      6878920.15
      2734723.55      6879117.44
#Sta/Elev= 30
  4580.8  424.57  4752.2  418.36  4752.4  417.86  4756.2  418.36  4768.4  419.04
  4782.7  426.29  4789.3  425.48  4797.0  428.00  4803.6  426.58  4811.2  428.32
  4817.8  425.59  4825.5  427.67  4832.1  424.48  4839.8  425.48  4850.7  422.61
  4862.6  422.61  4868.3  427.43  4884.4  424.71  4890.1  428.65  4906.2  423.01
  4911.9  428.14  4922.3  425.64  4928.0  428.00  4944.1  423.66  4949.8  427.43
  4965.9  422.23  4971.6  426.16  5002.6  421.75  5031.3  424.87  5078.4  425.37
#Mann=3,-1,0
  4580.8    0.05       0  4752.2    0.04       0  4756.2    0.05       0
Bank Sta=4752.2,4756.2
Exp/Cntr=0.3,0.1

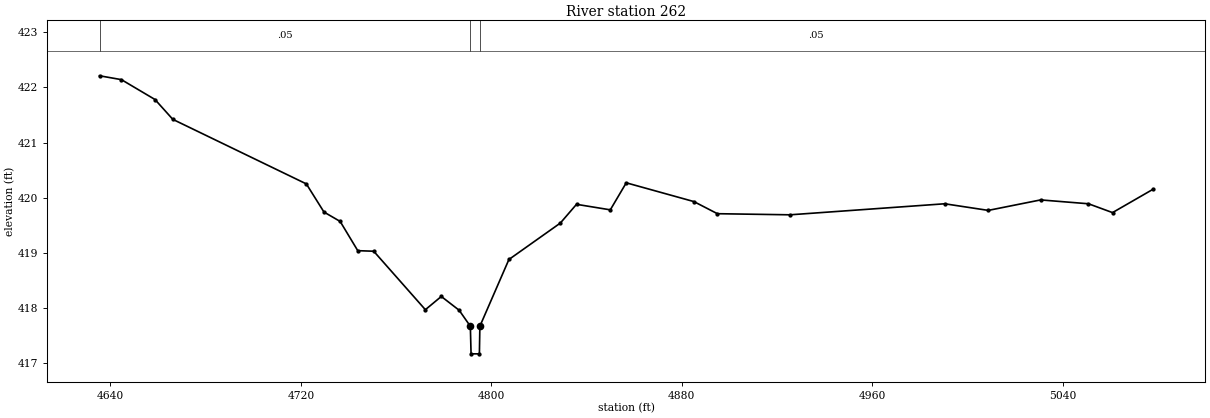
Type RM Length L Ch R = 1,262,0,0,0
BEGIN DESCRIPTION:
Lacy 095 1848
END DESCRIPTION:
XS GIS Cut Line= 3
      2734749.76      6878731.65      2734557.42      6878906.37
      2734578.68      6879087.78
#Sta/Elev= 30
  4635.4  422.21  4644.6  422.14  4658.7  421.78  4666.2  421.42  4722.3  420.25
  4729.7  419.74  4736.5  419.57  4743.9  419.04  4750.6  419.03  4772.3  417.97
  4779.0  418.21  4786.5  417.96  4791.2  417.67  4791.5  417.17  4795.0  417.17
  4795.2  417.67  4807.4  418.88  4829.0  419.54  4835.8  419.88  4850.0  419.78
  4856.7  420.27  4885.1  419.93  4895.0  419.71  4925.5  419.69  4990.5  419.89
  5008.8  419.77  5030.8  419.96  5050.9  419.89  5061.0  419.73  5077.9  420.15
#Mann=3,-1,0
  4635.4    0.05       0  4791.2    0.04       0  4795.2    0.05       0
Bank Sta=4791.2,4795.2
Exp/Cntr=0.3,0.1

Chan Stop Cuts=-1