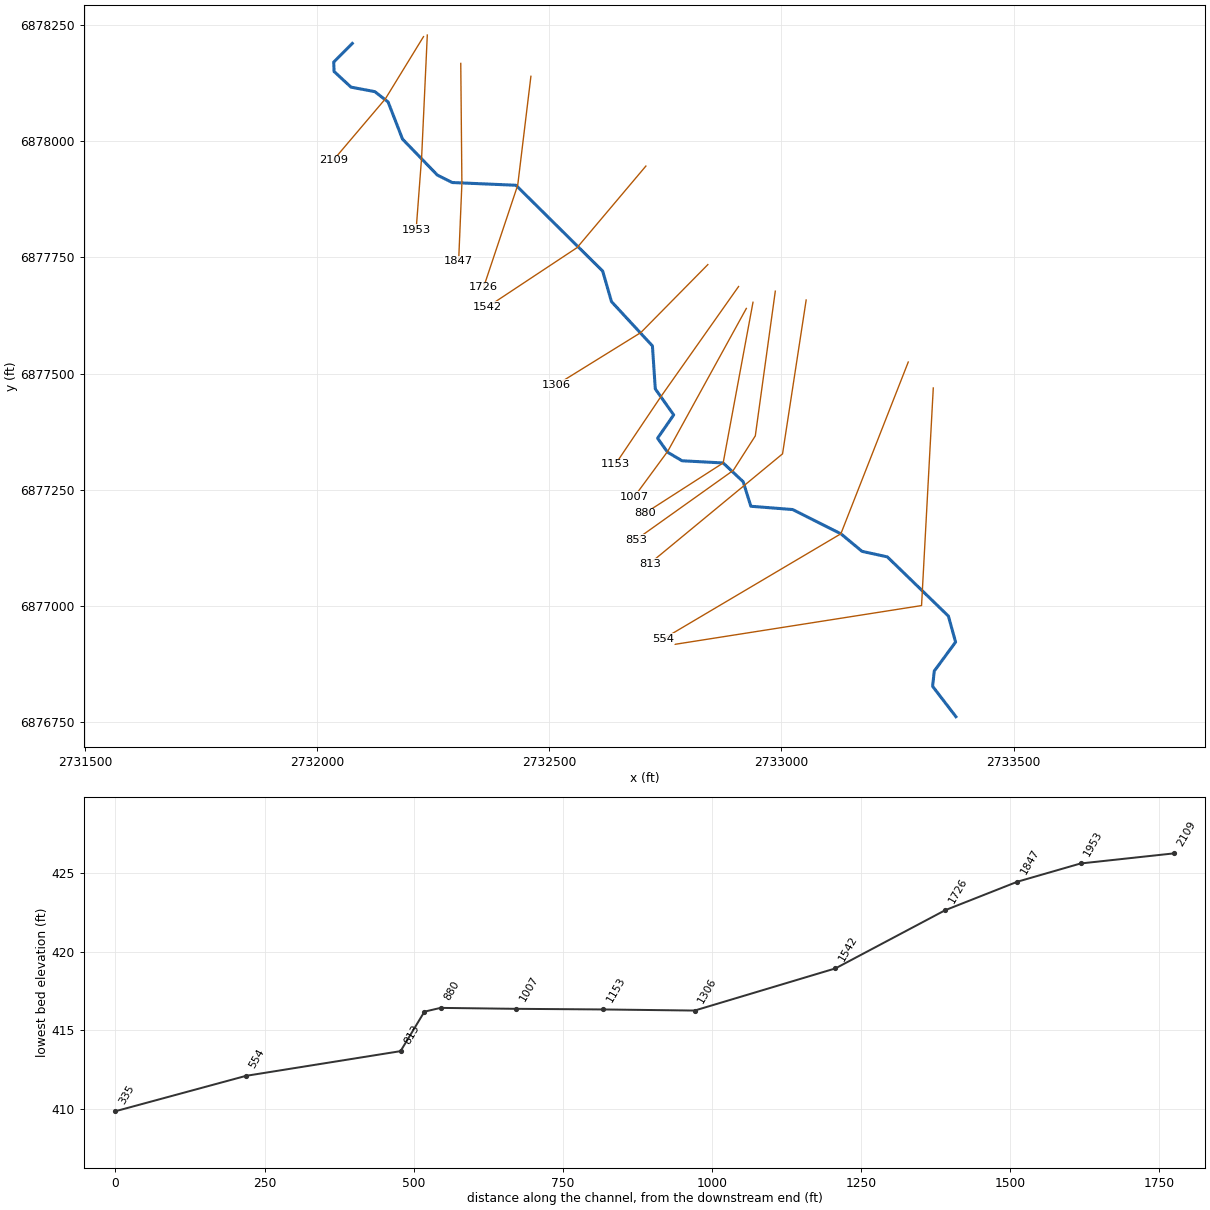
--- Lacy 096.prj (project) ---

Proj Title=Lacy 096 Base Level Engineering
Current Plan=p01
Default Exp/Contr=0.3,0.1
English Units
Geom File=g01
Flow File=f01
Plan File=p01
BEGIN DESCRIPTION:
Lacy 096
END DESCRIPTION:

--- Lacy 096.p01 (plan) ---

Plan Title=Multiple Run
Short Identifier=Multiple
Geom File=g01
Flow File=f01
Subcritical Flow
K Sum by GR= 0
Std Step Tol= 0.01
Critical Tol= 0.01
Num of Std Step Trials= 20
Max Error Tol= 0.3
Flow Tol Ratio= 0.001
Split Flow NTrial= 30
Split Flow Tol= 0.02
Split Flow Ratio= 0.02
Log Output Level= 0
Friction Slope Method= 1
Unsteady Friction Slope Method= 2
Unsteady Bridges Friction Slope Method= 1
Parabolic Critical Depth
Global Vel Dist=  1 , 1 , 1
Global Log Level= 0
CheckData=True
Encroach Param= -1, 0, 0, 0
BEGIN DESCRIPTION:
Multiple Run
END DESCRIPTION:

--- Lacy 096.f01 (steady flow) ---

Flow Title=Multiple
Number of Profiles=7
Profile Names=10-year,25-year,50-year,1pct_min,100-year,1pct_plu,500-year
River Rch & RM= Lacy 096,Reach-1,2109
     228     285     327     188     374     747     487
Boundary for River Rch & Prof#=Lacy 096,Reach-1,1
Up Type=0
Dn Type=3
Dn Slope=0.005
Boundary for River Rch & Prof#=Lacy 096,Reach-1,2
Up Type=0
Dn Type=3
Dn Slope=0.005
Boundary for River Rch & Prof#=Lacy 096,Reach-1,3
Up Type=0
Dn Type=3
Dn Slope=0.005
Boundary for River Rch & Prof#=Lacy 096,Reach-1,4
Up Type=0
Dn Type=3
Dn Slope=0.005
Boundary for River Rch & Prof#=Lacy 096,Reach-1,5
Up Type=0
Dn Type=3
Dn Slope=0.005
Boundary for River Rch & Prof#=Lacy 096,Reach-1,6
Up Type=0
Dn Type=3
Dn Slope=0.005
Boundary for River Rch & Prof#=Lacy 096,Reach-1,7
Up Type=0
Dn Type=3
Dn Slope=0.005

--- Lacy 096.g01 (geometry) ---

Geom Title=Existing Conditions

River Reach=Lacy 096,Reach-1
Reach XY= 30
      2732076.00      6878211.00      2732036.02      6878170.81
      2732036.72      6878150.59      2732073.24      6878116.83
      2732124.52      6878107.13      2732153.13      6878084.84
      2732184.16      6878004.95      2732259.20      6877927.42
      2732291.16      6877911.40      2732428.45      6877905.53
      2732615.22      6877720.68      2732634.18      6877654.96
      2732722.38      6877559.50      2732728.55      6877466.89
      2732768.19      6877410.89      2732733.45      6877360.75
      2732754.95      6877330.63      2732786.16      6877312.17
      2732874.70      6877307.44      2732917.83      6877267.03
      2732934.35      6877214.19      2733024.34      6877207.14
      2733128.20      6877154.92      2733173.81      6877117.10
      2733228.30      6877105.17      2733359.78      6876977.68
      2733375.28      6876921.70      2733329.38      6876859.33
      2733325.76      6876826.40      2733376.00      6876761.00

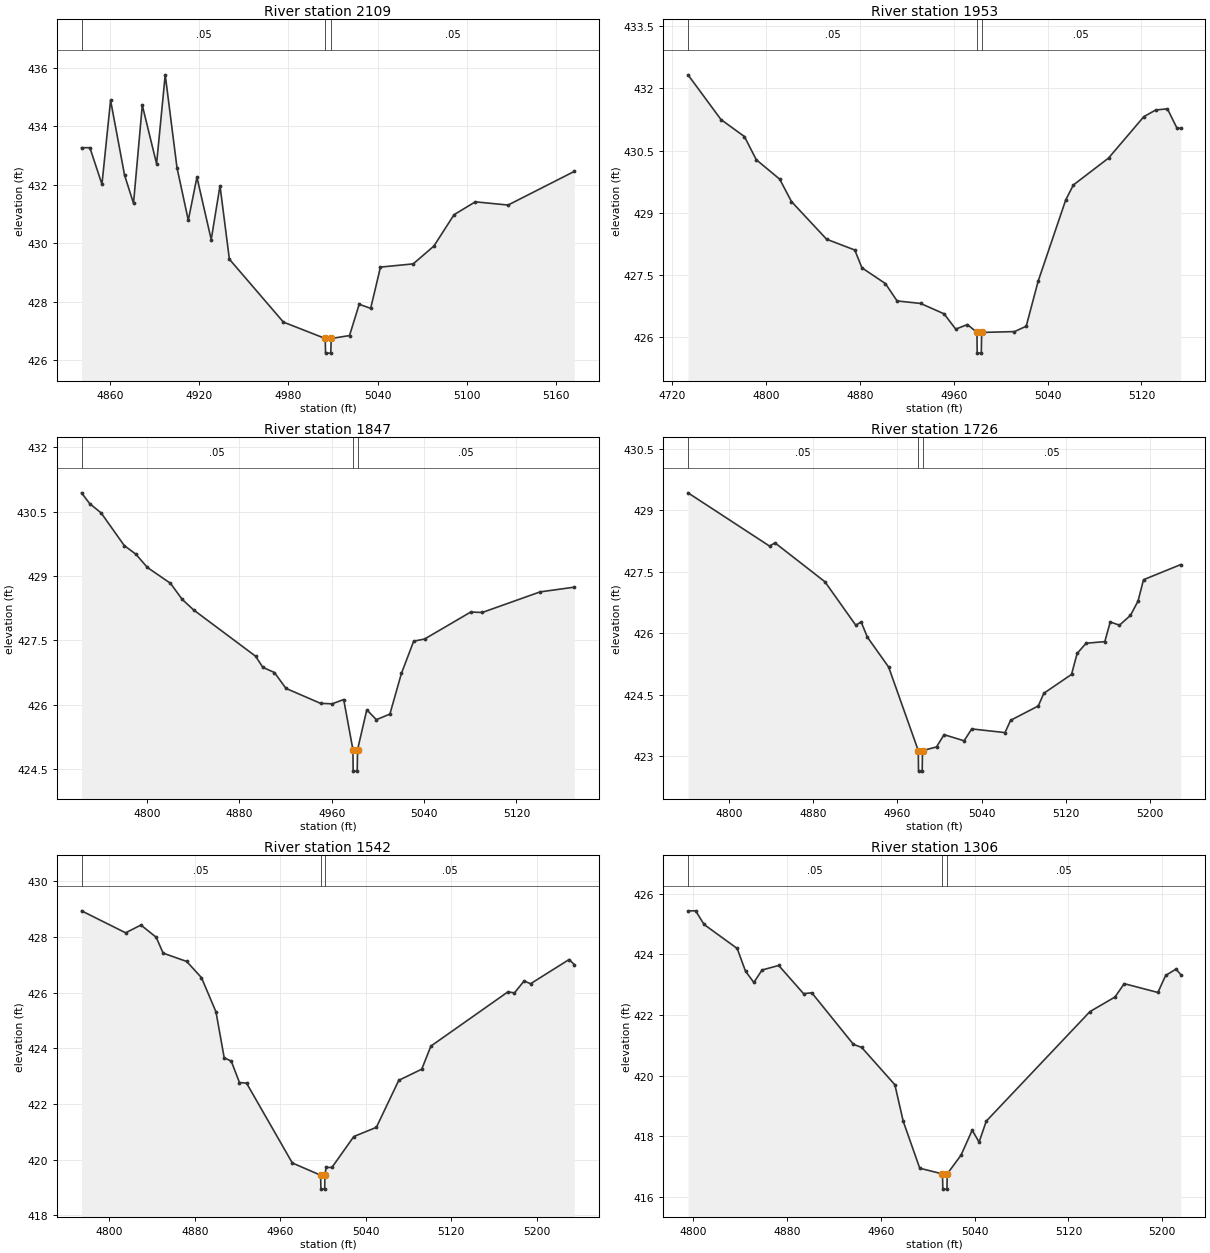
Type RM Length L Ch R = 1,2109,156,156,156
BEGIN DESCRIPTION:
Lacy 096 1823
END DESCRIPTION:
XS GIS Cut Line= 3
      2732229.37      6878225.62      2732147.23      6878091.63
      2732034.78      6877959.07
#Sta/Elev= 30
  4841.1  433.27  4846.7  433.27  4854.8  432.02  4860.6  434.89  4870.0  432.33
  4876.0  431.37  4881.9  434.72  4891.5  432.72  4897.3  435.76  4905.2  432.59
  4912.8  430.79  4918.6  432.26  4928.2  430.13  4934.1  431.97  4940.4  429.46
  4976.7  427.31  5004.8  426.75  5005.0  426.25  5008.5  426.25  5008.8  426.75
  5021.1  426.85  5027.6  427.92  5035.3  427.78  5041.9  429.19  5063.9  429.30
  5077.8  429.91  5091.3  430.98  5105.6  431.42  5127.6  431.31  5172.1  432.46
#Mann=3,-1,0
  4841.1    0.05       0  5004.8    0.04       0  5008.8    0.05       0
Bank Sta=5004.8,5008.8
Exp/Cntr=0.3,0.1

Type RM Length L Ch R = 1,1953,106,106,106
BEGIN DESCRIPTION:
Lacy 096 1822
END DESCRIPTION:
XS GIS Cut Line= 3
      2732237.54      6878229.09      2732225.38      6877966.84
      2732213.50      6877809.62
#Sta/Elev= 30
  4733.3  432.33  4761.4  431.25  4781.4  430.84  4791.5  430.28  4811.5  429.81
  4821.5  429.27  4851.5  428.36  4875.5  428.10  4881.6  427.67  4901.6  427.29
  4911.6  426.87  4931.6  426.81  4951.6  426.56  4961.6  426.19  4971.6  426.30
  4979.7  426.11  4979.9  425.61  4983.4  425.61  4983.7  426.11  5011.7  426.13
  5021.7  426.26  5031.8  427.34  5055.4  429.31  5061.9  429.67  5091.9  430.32
  5122.0  431.32  5132.1  431.48  5142.1  431.51  5150.3  431.04  5153.5  431.04
#Mann=3,-1,0
  4733.3    0.05       0  4979.7    0.05       0  4983.7    0.05       0
Bank Sta=4979.7,4983.7
Exp/Cntr=0.3,0.1

Type RM Length L Ch R = 1,1847,121,121,121
BEGIN DESCRIPTION:
Lacy 096 1821
END DESCRIPTION:
XS GIS Cut Line= 3
      2732309.60      6878167.96      2732312.03      6877909.35
      2732304.99      6877741.42
#Sta/Elev= 30
  4743.4  430.94  4750.4  430.69  4760.4  430.47  4780.4  429.71  4790.4  429.51
  4800.4  429.20  4820.4  428.83  4830.4  428.46  4840.4  428.21  4894.1  427.13
  4900.4  426.87  4910.4  426.75  4920.4  426.38  4950.4  426.03  4960.4  426.02
  4970.4  426.12  4978.4  424.95  4978.6  424.45  4982.1  424.45  4982.4  424.95
  4990.4  425.88  4998.7  425.65  5010.4  425.78  5020.4  426.73  5031.0  427.48
  5040.4  427.53  5080.4  428.16  5090.4  428.15  5140.5  428.63  5170.1  428.74
#Mann=3,-1,0
  4743.4    0.05       0  4978.4    0.04       0  4982.4    0.05       0
Bank Sta=4978.4,4982.4
Exp/Cntr=0.3,0.1

Type RM Length L Ch R = 1,1726,184,184,184
BEGIN DESCRIPTION:
Lacy 096 1820
END DESCRIPTION:
XS GIS Cut Line= 3
      2732460.66      6878140.20      2732432.26      6877905.69
      2732358.71      6877685.68
#Sta/Elev= 30
  4761.0  429.43  4838.5  428.13  4843.6  428.21  4891.1  427.26  4920.4  426.20
  4925.5  426.28  4931.4  425.91  4951.6  425.18  4979.8  423.14  4980.0  422.64
  4983.5  422.64  4983.8  423.14  4997.1  423.23  5004.3  423.53  5023.3  423.38
  5030.6  423.67  5062.2  423.58  5067.5  423.88  5093.8  424.23  5099.1  424.54
  5125.4  425.00  5130.7  425.51  5139.2  425.76  5157.0  425.80  5162.2  426.28
  5170.9  426.20  5181.4  426.44  5188.6  426.79  5193.8  427.31  5229.2  427.68
#Mann=3,-1,0
  4761.0    0.05       0  4979.8    0.04       0  4983.8    0.05       0
Bank Sta=4979.8,4983.8
Exp/Cntr=0.3,0.1

Type RM Length L Ch R = 1,1542,236,236,236
BEGIN DESCRIPTION:
Lacy 096 1819
END DESCRIPTION:
XS GIS Cut Line= 3
      2732708.25      6877946.84      2732560.16      6877771.25
      2732366.89      6877643.28
#Sta/Elev= 30
  4773.9  428.94  4815.2  428.15  4829.5  428.43  4843.8  427.99  4850.3  427.42
  4872.4  427.12  4886.2  426.54  4899.8  425.31  4907.5  423.66  4914.1  423.54
  4921.8  422.77  4928.4  422.75  4971.3  419.88  4997.8  419.44  4998.1  418.94
  5001.6  418.94  5001.8  419.44  5002.9  419.72  5008.4  419.72  5028.9  420.83
  5050.0  421.16  5071.0  422.85  5092.5  423.25  5101.1  424.08  5173.3  426.03
  5179.3  425.99  5188.4  426.42  5194.4  426.32  5230.5  427.19  5235.4  427.01
#Mann=3,-1,0
  4773.9    0.05       0  4997.8    0.04       0  5001.8    0.05       0
Bank Sta=4997.8,5001.8
Exp/Cntr=0.3,0.1

Type RM Length L Ch R = 1,1306,153,153,153
BEGIN DESCRIPTION:
Lacy 096 1818
END DESCRIPTION:
XS GIS Cut Line= 3
      2732841.68      6877734.62      2732697.46      6877588.33
      2732515.05      6877475.35
#Sta/Elev= 30
  4795.8  425.43  4802.3  425.43  4809.5  424.98  4837.7  424.19  4844.8  423.44
  4851.9  423.07  4858.9  423.48  4873.1  423.63  4894.3  422.70  4901.3  422.73
  4936.8  421.03  4943.8  420.93  4972.1  419.70  4979.2  418.50  4993.3  416.95
  5012.7  416.76  5013.0  416.26  5016.5  416.26  5016.7  416.76  5028.5  417.38
  5038.0  418.20  5043.9  417.81  5050.0  418.50  5138.4  422.11  5159.7  422.59
  5167.6  423.03  5196.3  422.74  5202.9  423.30  5211.7  423.51  5215.8  423.33
#Mann=3,-1,0
  4795.8    0.05       0  5012.7    0.04       0  5016.7    0.05       0
Bank Sta=5012.7,5016.7
Exp/Cntr=0.3,0.1

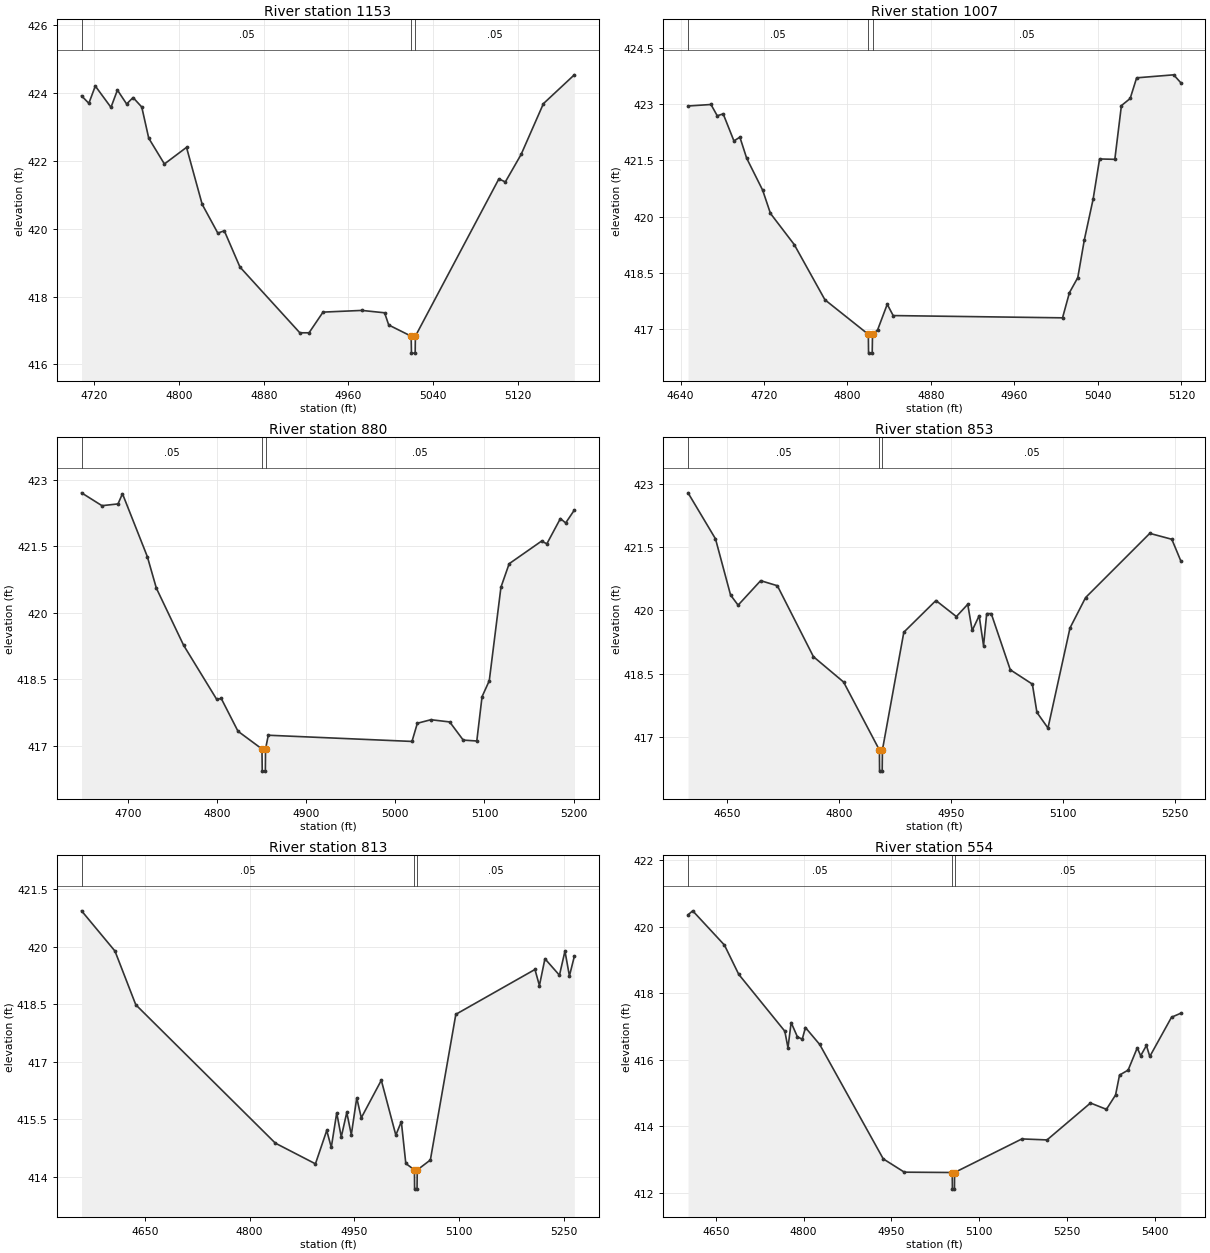
Type RM Length L Ch R = 1,1153,146,146,146
BEGIN DESCRIPTION:
Lacy 096 1817
END DESCRIPTION:
XS GIS Cut Line= 3
      2732907.90      6877687.47      2732740.17      6877449.71
      2732642.68      6877304.71
#Sta/Elev= 30
  4707.8  423.92  4714.7  423.70  4720.8  424.21  4735.6  423.58  4741.7  424.09
  4750.4  423.68  4756.5  423.87  4764.7  423.59  4771.3  422.67  4786.1  421.91
  4807.0  422.40  4821.8  420.72  4836.6  419.87  4842.7  419.94  4857.5  418.87
  4914.1  416.93  4922.8  416.93  4936.0  417.54  4972.7  417.59  4994.2  417.52
  4998.1  417.16  5019.3  416.83  5019.6  416.33  5023.1  416.33  5023.3  416.83
  5102.2  421.47  5108.3  421.38  5123.2  422.19  5144.3  423.69  5173.5  424.54
#Mann=3,-1,0
  4707.8    0.05       0  5019.3    0.04       0  5023.3    0.05       0
Bank Sta=5019.3,5023.3
Exp/Cntr=0.3,0.1

Type RM Length L Ch R = 1,1007,127,127,127
BEGIN DESCRIPTION:
Lacy 096 1816
END DESCRIPTION:
XS GIS Cut Line= 3
      2732924.61      6877640.25      2732755.76      6877333.18
      2732683.64      6877235.06
#Sta/Elev= 30
  4647.2  422.95  4669.2  422.99  4675.2  422.69  4680.9  422.74  4691.2  422.02
  4696.9  422.12  4703.4  421.56  4718.7  420.71  4726.2  420.09  4749.0  419.26
  4778.4  417.79  4820.0  416.87  4820.2  416.37  4823.7  416.37  4824.0  416.87
  4828.9  416.99  4838.1  417.67  4843.8  417.37  5006.1  417.31  5012.7  417.98
  5020.7  418.38  5027.0  419.39  5035.4  420.47  5041.6  421.54  5056.2  421.53
  5062.5  422.96  5070.9  423.15  5077.1  423.70  5112.6  423.78  5119.4  423.57
#Mann=3,-1,0
  4647.2    0.05       0  4820.0    0.04       0  4824.0    0.05       0
Bank Sta=4820,4824
Exp/Cntr=0.3,0.1

Type RM Length L Ch R = 1,880,27,27,27
BEGIN DESCRIPTION:
Lacy 096 1827
END DESCRIPTION:
XS GIS Cut Line= 3
      2732938.95      6877653.53      2732874.70      6877307.44
      2732705.77      6877198.89
#Sta/Elev= 30
  4648.0  422.71  4670.9  422.42  4688.9  422.46  4693.9  422.69  4721.8  421.27
  4731.9  420.56  4762.5  419.27  4799.6  418.05  4804.7  418.07  4823.5  417.33
  4850.4  416.93  4850.7  416.43  4854.2  416.43  4854.4  416.93  4857.5  417.24
  5018.7  417.10  5024.7  417.51  5039.9  417.59  5061.0  417.54  5076.2  417.13
  5091.4  417.11  5097.3  418.11  5105.4  418.47  5118.5  420.58  5127.7  421.11
  5164.0  421.62  5170.0  421.56  5185.2  422.13  5191.1  422.03  5200.8  422.32
#Mann=3,-1,0
  4648.0    0.05       0  4850.4    0.04       0  4854.4    0.05       0
Bank Sta=4850.4,4854.4
Exp/Cntr=0.3,0.1

Type RM Length L Ch R = 1,853,40,40,40
BEGIN DESCRIPTION:
Lacy 096 1825
END DESCRIPTION:
XS GIS Cut Line= 4
      2732987.00      6877677.42      2732943.92      6877365.77
      2732896.49      6877291.43      2732686.92      6877142.16
#Sta/Elev= 30
  4597.2  422.78  4634.0  421.69  4654.2  420.36  4664.3  420.12  4694.5  420.70
  4716.9  420.58  4765.2  418.90  4805.6  418.30  4853.6  416.69  4853.8  416.19
  4857.3  416.19  4857.6  416.69  4886.3  419.48  4929.3  420.23  4956.7  419.85
  4971.9  420.14  4977.9  419.52  4987.2  419.87  4993.1  419.16  4997.3  419.92
  5003.4  419.92  5028.9  418.59  5058.5  418.25  5064.6  417.58  5079.4  417.21
  5108.9  419.58  5129.8  420.30  5215.8  421.82  5245.3  421.68  5257.3  421.17
#Mann=3,-1,0
  4597.2    0.05       0  4853.6    0.04       0  4857.6    0.05       0
Bank Sta=4853.6,4857.6
Exp/Cntr=0.3,0.1

Type RM Length L Ch R = 1,813,259,259,259
BEGIN DESCRIPTION:
Lacy 096 1826
END DESCRIPTION:
XS GIS Cut Line= 3
      2733053.48      6877658.39      2733002.61      6877327.10
      2732716.50      6877090.86
#Sta/Elev= 30
  4559.1  420.94  4607.0  419.89  4636.8  418.49  4836.8  414.88  4894.3  414.34
  4910.5  415.21  4917.0  414.77  4924.8  415.67  4931.3  415.04  4939.2  415.68
  4945.7  415.10  4953.5  416.06  4960.0  415.54  4988.7  416.52  5009.5  415.09
  5017.4  415.44  5023.8  414.35  5036.2  414.18  5036.4  413.68  5039.9  413.68
  5040.2  414.18  5059.0  414.44  5095.5  418.24  5208.9  419.41  5215.3  418.99
  5223.2  419.69  5244.0  419.26  5251.9  419.89  5258.3  419.24  5265.3  419.75
#Mann=3,-1,0
  4559.1    0.05       0  5036.2    0.04       0  5040.2    0.05       0
Bank Sta=5036.2,5040.2
Exp/Cntr=0.3,0.1

Type RM Length L Ch R = 1,554,219,219,219
BEGIN DESCRIPTION:
Lacy 096 1824
END DESCRIPTION:
XS GIS Cut Line= 3
      2733273.35      6877524.86      2733128.20      6877154.92
      2732745.97      6876928.81
#Sta/Elev= 30
  4602.6  420.36  4610.6  420.48  4664.8  419.45  4689.2  418.57  4767.9  416.86
  4773.3  416.36  4778.7  417.12  4789.4  416.69  4797.7  416.62  4803.1  416.97
  4827.5  416.46  4936.0  413.02  4972.0  412.62  5053.8  412.61  5054.1  412.11
  5057.6  412.11  5057.8  412.61  5172.8  413.62  5215.7  413.59  5289.9  414.70
  5317.1  414.51  5332.7  414.94  5339.5  415.54  5354.2  415.69  5369.8  416.36
  5375.6  416.12  5385.4  416.43  5391.2  416.10  5428.3  417.28  5444.1  417.40
#Mann=3,-1,0
  4602.6    0.05       0  5053.8    0.04       0  5057.8    0.05       0
Bank Sta=5053.8,5057.8
Exp/Cntr=0.3,0.1

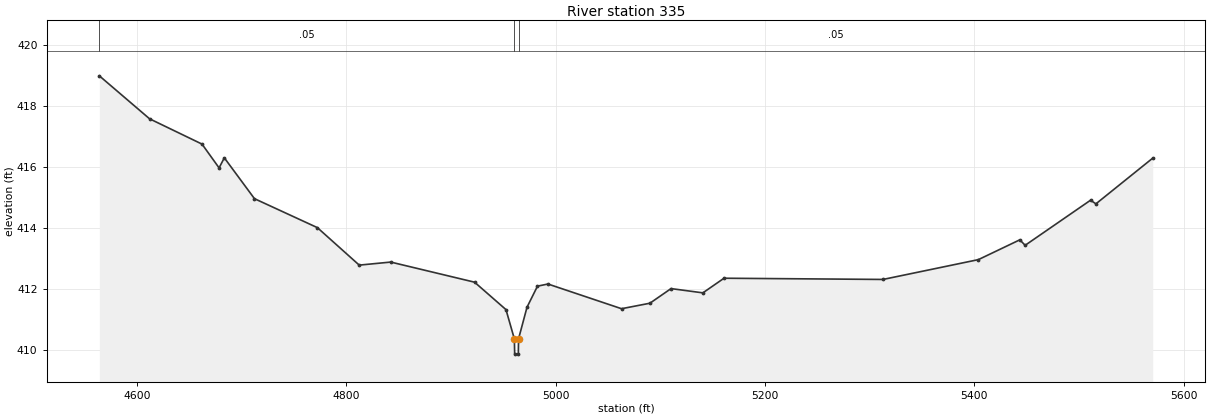
Type RM Length L Ch R = 1,335,0,0,0
BEGIN DESCRIPTION:
Lacy 096 3483
END DESCRIPTION:
XS GIS Cut Line= 3
      2733327.23      6877468.97      2733301.96      6877000.33
      2732771.40      6876916.93
#Sta/Elev= 30
  4564.1  418.99  4612.1  417.58  4662.2  416.75  4678.5  415.97  4683.5  416.30
  4712.3  414.96  4772.4  414.01  4812.4  412.78  4842.5  412.88  4922.6  412.22
  4952.6  411.32  4960.6  410.36  4960.9  409.86  4964.4  409.86  4964.6  410.36
  4972.7  411.40  4982.7  412.09  4992.7  412.16  5063.0  411.35  5090.1  411.53
  5110.3  412.01  5140.7  411.87  5160.9  412.35  5312.8  412.31  5403.9  412.96
  5443.5  413.61  5448.6  413.43  5511.1  414.91  5516.2  414.79  5570.5  416.29
#Mann=3,-1,0
  4564.1    0.05       0  4960.6    0.04       0  4964.6    0.05       0
Bank Sta=4960.6,4964.6
Exp/Cntr=0.3,0.1

Chan Stop Cuts=-1