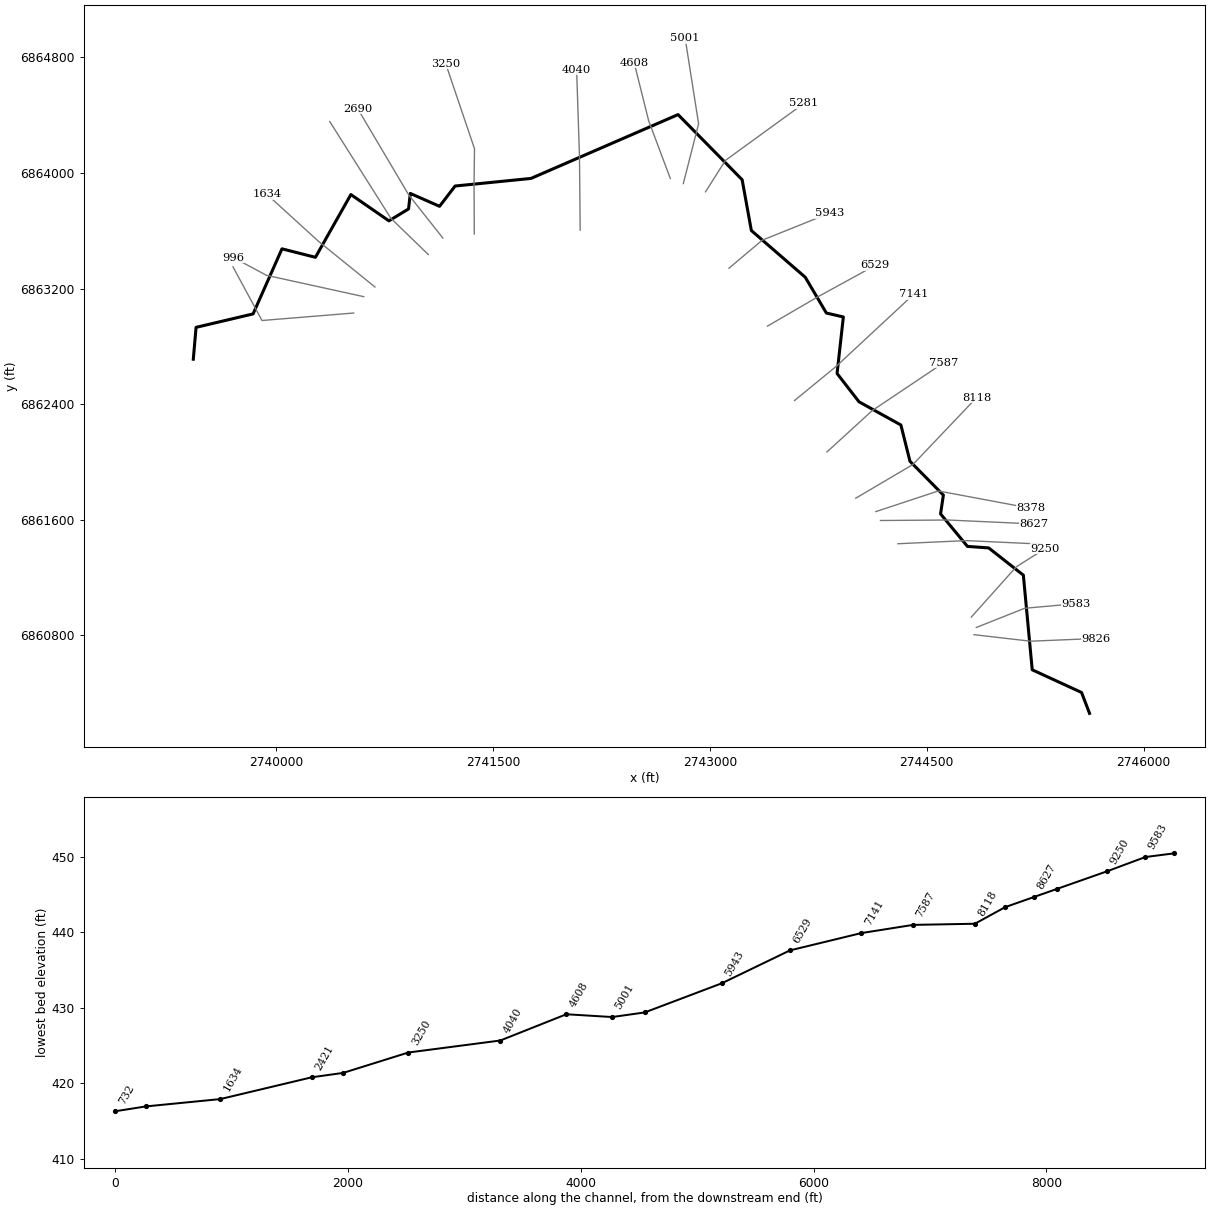
--- Lacy 098.prj (project) ---

Proj Title=Lacy 098 Base Level Engineering
Current Plan=p01
Default Exp/Contr=0.3,0.1
English Units
Geom File=g01
Flow File=f01
Plan File=p01
BEGIN DESCRIPTION:
Lacy 098
END DESCRIPTION:

--- Lacy 098.p01 (plan) ---

Plan Title=Multiple Run
Short Identifier=Multiple
Geom File=g01
Flow File=f01
Subcritical Flow
K Sum by GR= 0
Std Step Tol= 0.01
Critical Tol= 0.01
Num of Std Step Trials= 20
Max Error Tol= 0.3
Flow Tol Ratio= 0.001
Split Flow NTrial= 30
Split Flow Tol= 0.02
Split Flow Ratio= 0.02
Log Output Level= 0
Friction Slope Method= 1
Unsteady Friction Slope Method= 2
Unsteady Bridges Friction Slope Method= 1
Parabolic Critical Depth
Global Vel Dist=  1 , 1 , 1
Global Log Level= 0
CheckData=True
Encroach Param= -1, 0, 0, 0
BEGIN DESCRIPTION:
Multiple Run
END DESCRIPTION:

--- Lacy 098.f01 (steady flow) ---

Flow Title=Multiple
Number of Profiles=7
Profile Names=10-year,25-year,50-year,1pct_min,100-year,1pct_plu,500-year
River Rch & RM= Lacy 098,Reach-1,9826
     338     435     511     298     595    1188     809
River Rch & RM= Lacy 098,Reach-1,8118
     694     942    1146     693    1382    2757    2013
River Rch & RM= Lacy 098,Reach-1,5001
    1026    1424    1757    1075    2146    4281    3210
River Rch & RM= Lacy 098,Reach-1,3250
    1205    1682    2085    1281    2556    5099    3853
Boundary for River Rch & Prof#=Lacy 098,Reach-1,1
Up Type=0
Dn Type=3
Dn Slope=0.005
Boundary for River Rch & Prof#=Lacy 098,Reach-1,2
Up Type=0
Dn Type=3
Dn Slope=0.005
Boundary for River Rch & Prof#=Lacy 098,Reach-1,3
Up Type=0
Dn Type=3
Dn Slope=0.005
Boundary for River Rch & Prof#=Lacy 098,Reach-1,4
Up Type=0
Dn Type=3
Dn Slope=0.005
Boundary for River Rch & Prof#=Lacy 098,Reach-1,5
Up Type=0
Dn Type=3
Dn Slope=0.005
Boundary for River Rch & Prof#=Lacy 098,Reach-1,6
Up Type=0
Dn Type=3
Dn Slope=0.005
Boundary for River Rch & Prof#=Lacy 098,Reach-1,7
Up Type=0
Dn Type=3
Dn Slope=0.005

--- Lacy 098.g01 (geometry) ---

Geom Title=Existing Conditions

River Reach=Lacy 098,Reach-1
Reach XY= 30
      2745626.00      6860261.00      2745570.77      6860405.55
      2745229.53      6860562.45      2745168.15      6861217.19
      2744928.44      6861405.52      2744781.44      6861416.19
      2744595.43      6861640.91      2744614.89      6861771.05
      2744383.91      6862004.85      2744320.96      6862255.92
      2744031.26      6862416.48      2743879.45      6862612.25
      2743922.91      6863003.32      2743805.48      6863030.48
      2743659.50      6863278.05      2743286.47      6863601.18
      2743222.81      6863952.65      2742779.42      6864403.21
      2741762.08      6863961.68      2741237.14      6863909.15
      2741129.42      6863768.77      2740927.17      6863857.88
      2740915.13      6863750.76      2740779.44      6863668.20
      2740516.00      6863850.05      2740270.82      6863415.93
      2740039.49      6863474.71      2739839.64      6863024.44
      2739445.17      6862931.42      2739426.00      6862711.00

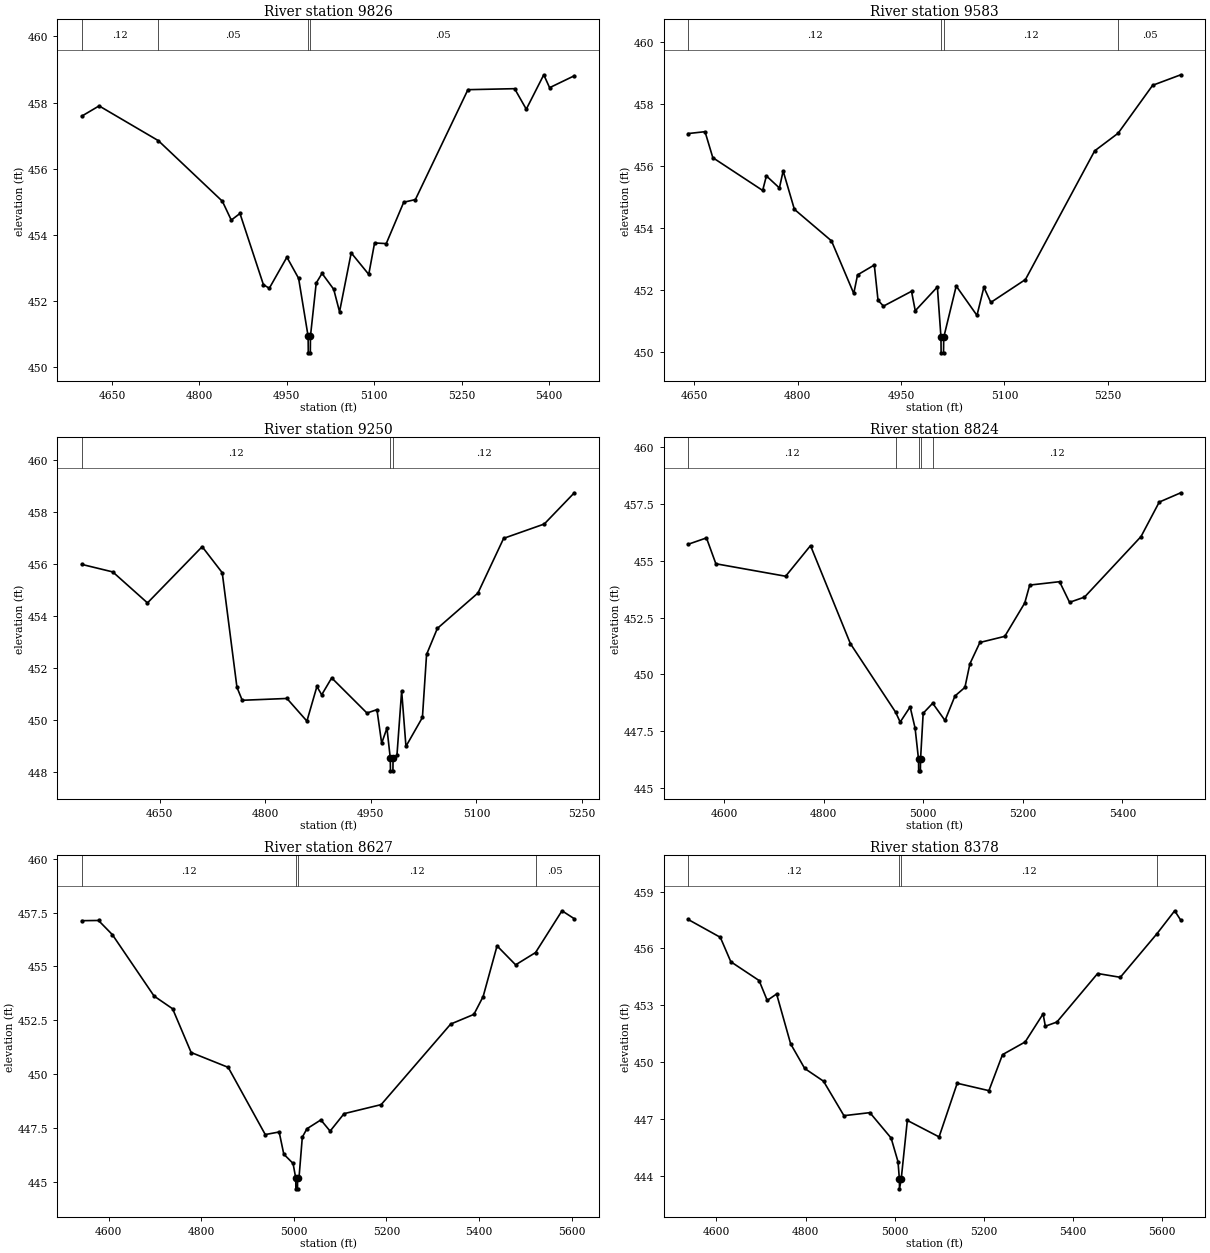
Type RM Length L Ch R = 1,9826,243,243,243
BEGIN DESCRIPTION:
Lacy 098 1754
END DESCRIPTION:
XS GIS Cut Line= 3
      2744826.42      6860805.47      2745217.33      6860760.29
      2745668.33      6860778.90
#Sta/Elev= 30
  4598.3  457.59  4628.1  457.90  4729.7  456.85  4839.5  455.02  4854.8  454.45
  4869.7  454.65  4909.9  452.50  4920.0  452.39  4950.2  453.33  4970.3  452.69
  4986.6  450.94  4986.9  450.44  4990.4  450.44  4990.6  450.94  5000.5  452.55
  5010.5  452.84  5030.5  452.36  5040.5  451.68  5060.5  453.46  5090.6  452.81
  5100.6  453.76  5120.6  453.74  5150.6  454.99  5170.6  455.07  5260.7  458.39
  5340.8  458.42  5360.8  457.80  5390.8  458.84  5400.8  458.45  5443.2  458.81
#Mann=4,-1,0
  4598.3    0.12       0  4729.7    0.05       0  4986.6    0.05       0
  4990.6    0.05       0
Bank Sta=4986.6,4990.6
Exp/Cntr=0.3,0.1

Type RM Length L Ch R = 1,9583,333,333,333
BEGIN DESCRIPTION:
Lacy 098 1756
END DESCRIPTION:
XS GIS Cut Line= 3
      2744842.85      6860855.21      2745176.64      6860987.91
      2745530.41      6861019.77
#Sta/Elev= 30
  4641.3  457.05  4665.7  457.11  4677.0  456.27  4749.3  455.21  4754.7  455.68
  4773.6  455.29  4779.0  455.84  4795.3  454.60  4849.1  453.58  4881.4  451.88
  4886.9  452.48  4911.2  452.80  4916.6  451.66  4924.5  451.47  4965.2  451.95
  4970.6  451.32  5002.7  452.09  5007.9  450.46  5008.1  449.96  5011.6  449.96
  5011.9  450.46  5030.0  452.12  5060.1  451.17  5070.1  452.08  5080.2  451.59
  5130.4  452.33  5230.8  456.49  5264.8  457.06  5314.9  458.61  5355.7  458.95
#Mann=4,-1,0
  4641.3    0.12       0  5007.9    0.07       0  5011.9    0.12       0
  5264.8    0.05       0
Bank Sta=5007.9,5011.9
Exp/Cntr=0.3,0.1

Type RM Length L Ch R = 1,9250,426,426,426
BEGIN DESCRIPTION:
Lacy 098 1753
END DESCRIPTION:
XS GIS Cut Line= 3
      2744808.10      6860927.10      2745119.11      6861274.87
      2745316.53      6861399.10
#Sta/Elev= 30
  4539.3  455.98  4583.4  455.69  4632.7  454.50  4710.4  456.66  4738.9  455.66
  4759.8  451.26  4767.3  450.76  4830.8  450.83  4859.2  449.96  4873.4  451.29
  4880.2  450.97  4894.4  451.62  4944.5  450.27  4958.7  450.40  4965.4  449.11
  4972.9  449.69  4977.6  448.55  4977.9  448.05  4981.4  448.05  4981.6  448.55
  4987.1  448.64  4993.8  451.12  4999.9  448.99  5023.3  450.10  5029.2  452.52
  5044.5  453.52  5102.2  454.88  5138.7  456.98  5196.4  457.53  5239.1  458.73
#Mann=3,-1,0
  4539.3    0.12       0  4977.6    0.07       0  4981.6    0.12       0
Bank Sta=4977.6,4981.6
Exp/Cntr=0.3,0.1

Type RM Length L Ch R = 1,8824,197,197,197
BEGIN DESCRIPTION:
Lacy 098 1752
END DESCRIPTION:
XS GIS Cut Line= 3
      2744300.46      6861434.49      2744773.41      6861456.22
      2745289.30      6861432.22
#Sta/Elev= 30
  4527.5  455.73  4564.2  456.01  4583.1  454.87  4723.3  454.32  4773.3  455.67
  4853.4  451.35  4944.2  448.33  4953.5  447.89  4973.5  448.56  4983.5  447.62
  4990.4  446.24  4990.6  445.74  4994.1  445.74  4994.4  446.24  4999.7  448.28
  5018.8  448.72  5043.6  447.96  5063.6  449.04  5083.6  449.42  5093.6  450.46
  5113.7  451.40  5163.7  451.67  5203.8  453.14  5213.8  453.93  5273.8  454.08
  5293.9  453.17  5323.9  453.40  5437.5  456.07  5474.1  457.59  5517.4  458.00
#Mann=5,-1,0
  4527.5    0.12       0  4944.2    0.05       0  4990.4    0.03       0
  4994.4    0.05       0  5018.8    0.12       0
Bank Sta=4990.4,4994.4
Exp/Cntr=0.3,0.1

Type RM Length L Ch R = 1,8627,249,249,249
BEGIN DESCRIPTION:
Lacy 098 1750
END DESCRIPTION:
XS GIS Cut Line= 3
      2744179.84      6861595.26      2744646.67      6861598.65
      2745242.61      6861571.48
#Sta/Elev= 30
  4542.1  457.12  4578.3  457.13  4608.3  456.47  4698.3  453.62  4738.3  453.03
  4778.3  451.00  4858.3  450.31  4938.3  447.19  4968.3  447.31  4978.3  446.28
  4998.3  445.85  5004.1  445.17  5004.4  444.67  5007.9  444.67  5008.1  445.17
  5011.1  445.17  5018.3  447.07  5028.3  447.46  5058.3  447.87  5078.3  447.35
  5108.4  448.16  5188.5  448.58  5338.6  452.32  5388.7  452.77  5408.7  453.60
  5438.7  455.95  5478.8  455.07  5521.8  455.64  5578.9  457.58  5605.5  457.21
#Mann=4,-1,0
  4542.1    0.12       0  5004.1    0.07       0  5008.1    0.12       0
  5521.8    0.05       0
Bank Sta=5004.1,5008.1
Exp/Cntr=0.3,0.1

Type RM Length L Ch R = 1,8378,260,260,260
BEGIN DESCRIPTION:
Lacy 098 1751
END DESCRIPTION:
XS GIS Cut Line= 3
      2744147.55      6861656.83      2744580.20      6861799.68
      2745219.46      6861679.93
#Sta/Elev= 30
  4536.6  457.53  4608.7  456.59  4632.3  455.30  4695.8  454.31  4714.0  453.26
  4735.1  453.60  4766.6  450.97  4798.2  449.67  4840.4  449.00  4886.3  447.18
  4944.5  447.34  4992.2  446.00  5007.7  444.75  5010.8  443.82  5011.0  443.32
  5014.8  443.82  5028.6  446.93  5099.9  446.06  5140.6  448.89  5211.8  448.50
  5242.3  450.40  5293.2  451.07  5333.4  452.55  5338.5  451.90  5364.4  452.12
  5455.9  454.68  5506.8  454.48  5589.1  456.78  5628.9  457.99  5642.6  457.49
#Mann=4,-1,0
  4536.6    0.12       0  5010.8    0.07       0  5014.8    0.12       0
  5589.1    0.05       0
Bank Sta=5010.8,5014.8
Exp/Cntr=0.3,0.1

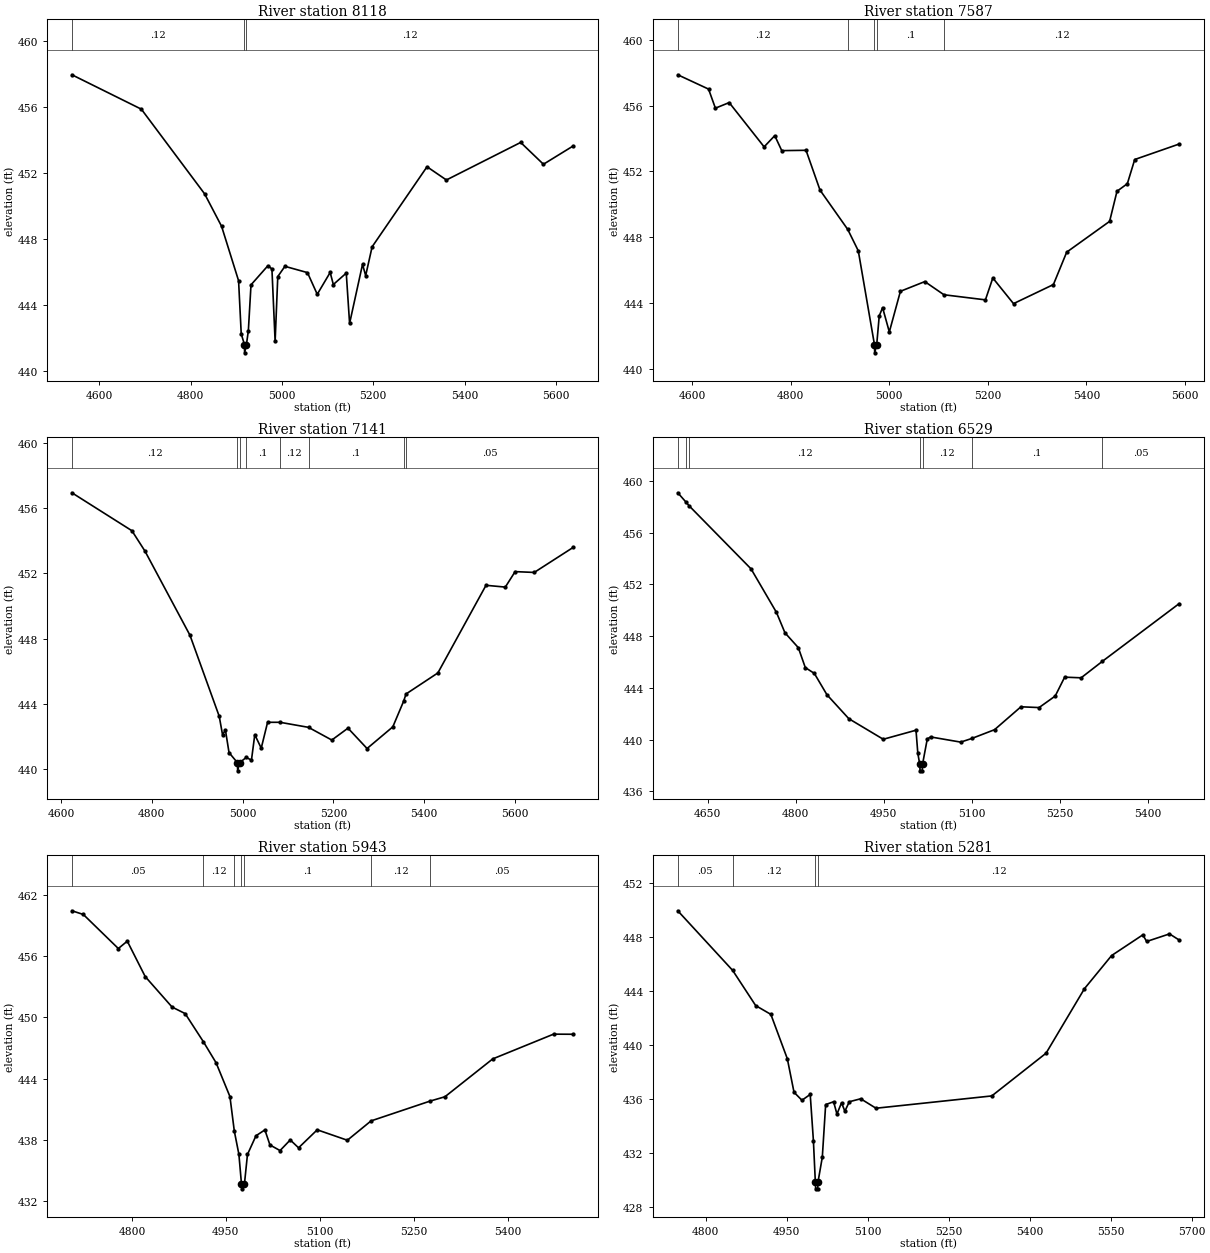
Type RM Length L Ch R = 1,8118,531,531,531
BEGIN DESCRIPTION:
Lacy 098 1747
END DESCRIPTION:
XS GIS Cut Line= 3
      2744008.80      6861749.62      2744404.04      6861982.49
      2744844.41      6862445.05
#Sta/Elev= 30
  4540.3  457.93  4692.3  455.85  4830.8  450.73  4867.9  448.77  4905.1  445.48
  4910.9  442.27  4917.9  441.62  4918.3  441.12  4922.3  441.62  4926.5  442.46
  4932.3  445.23  4969.4  446.39  4978.1  446.19  4985.1  441.81  4990.9  445.73
  5006.5  446.35  5055.9  445.97  5077.3  444.66  5105.6  445.98  5112.5  445.25
  5140.8  445.94  5148.1  442.90  5176.4  446.47  5183.3  445.79  5197.4  447.53
  5317.6  452.37  5360.0  451.57  5522.6  453.84  5572.4  452.52  5637.7  453.63
#Mann=3,-1,0
  4540.3    0.12       0  4917.9    0.07       0  4922.3    0.12       0
Bank Sta=4917.9,4922.3
Exp/Cntr=0.3,0.1

Type RM Length L Ch R = 1,7587,446,446,446
BEGIN DESCRIPTION:
Lacy 098 1748
END DESCRIPTION:
XS GIS Cut Line= 3
      2743809.59      6862069.58      2744122.05      6862355.00
      2744615.91      6862686.15
#Sta/Elev= 30
  4570.5  457.87  4633.0  457.00  4646.9  455.84  4674.9  456.18  4745.8  453.49
  4767.4  454.17  4781.6  453.26  4830.9  453.28  4859.3  450.86  4915.6  448.47
  4937.0  447.17  4969.8  441.47  4970.3  440.97  4974.4  441.47  4979.5  443.21
  4986.3  443.72  5000.0  442.24  5022.5  444.71  5072.0  445.30  5110.9  444.50
  5195.1  444.19  5210.1  445.52  5252.1  443.96  5333.1  445.12  5360.1  447.09
  5447.2  448.96  5462.2  450.79  5483.2  451.25  5498.2  452.72  5588.3  453.66
#Mann=5,-1,0
  4570.5    0.12       0  4915.6     0.1       0  4969.8    0.07       0
  4974.4     0.1       0  5110.9    0.12       0
Bank Sta=4969.8,4974.4
Exp/Cntr=0.3,0.1

Type RM Length L Ch R = 1,7141,612,612,612
BEGIN DESCRIPTION:
Lacy 098 1749
END DESCRIPTION:
XS GIS Cut Line= 3
      2743585.23      6862425.27      2743872.49      6862660.75
      2744408.89      6863159.37
#Sta/Elev= 30
  4624.2  456.95  4756.3  454.62  4785.0  453.37  4884.0  448.21  4948.5  443.23
  4955.8  442.10  4962.2  442.38  4970.1  441.00  4988.6  440.38  4989.1  439.88
  4993.3  440.38  5007.9  440.70  5019.5  440.54  5026.8  442.10  5041.0  441.27
  5055.0  442.86  5082.4  442.86  5145.1  442.55  5196.4  441.77  5232.0  442.50
  5274.0  441.25  5330.7  442.58  5354.3  444.14  5359.9  444.60  5429.9  445.89
  5535.9  451.27  5578.4  451.16  5600.0  452.11  5642.1  452.06  5728.0  453.60
#Mann=8,-1,0
  4624.2    0.12       0  4988.6    0.07       0  4993.3    0.12       0
  5007.9     0.1       0  5082.4    0.12       0  5145.1     0.1       0
  5354.3    0.12       0  5359.9    0.05       0
Bank Sta=4988.6,4993.3
Exp/Cntr=0.3,0.1

Type RM Length L Ch R = 1,6529,586,586,586
BEGIN DESCRIPTION:
Lacy 098 1746
END DESCRIPTION:
XS GIS Cut Line= 3
      2743398.08      6862939.92      2743747.35      6863143.09
      2744142.48      6863359.55
#Sta/Elev= 30
  4598.9  459.08  4613.3  458.34  4618.3  458.07  4723.8  453.20  4767.2  449.83
  4781.6  448.26  4804.4  447.11  4816.3  445.57  4831.7  445.12  4853.2  443.47
  4890.5  441.62  4949.2  440.03  5005.0  440.73  5008.1  438.95  5011.4  438.09
  5011.9  437.59  5015.6  437.59  5016.1  438.09  5024.2  440.05  5029.9  440.21
  5081.2  439.81  5100.0  440.09  5138.9  440.77  5183.9  442.54  5214.8  442.48
  5242.3  443.37  5258.4  444.83  5286.5  444.78  5322.9  446.06  5453.5  450.51
#Mann=7,-1,0
  4598.9    0.12       0  4613.3    0.05       0  4618.3    0.12       0
  5011.4    0.07       0  5016.1    0.12       0  5100.0     0.1       0
  5322.9    0.05       0
Bank Sta=5011.4,5016.1
Exp/Cntr=0.3,0.1

Type RM Length L Ch R = 1,5943,662,662,662
BEGIN DESCRIPTION:
Lacy 098 1745
END DESCRIPTION:
XS GIS Cut Line= 3
      2743131.58      6863340.53      2743361.80      6863534.34
      2743825.27      6863720.77
#Sta/Elev= 30
  4704.2  460.41  4722.4  460.05  4778.3  456.72  4792.6  457.44  4821.2  453.98
  4864.1  451.00  4885.0  450.36  4914.1  447.61  4934.4  445.55  4956.5  442.25
  4963.5  438.87  4970.8  436.61  4974.9  433.73  4975.5  433.23  4979.7  433.73
  4984.5  436.59  4998.1  438.42  5012.3  438.99  5020.4  437.52  5036.5  436.97
  5052.8  438.01  5066.1  437.24  5095.9  439.00  5144.0  437.98  5181.8  439.87
  5276.2  441.81  5299.8  442.23  5376.1  445.93  5473.2  448.35  5504.7  448.34
#Mann=7,-1,0
  4704.2    0.05       0  4914.1    0.12       0  4963.5     0.1       0
  4974.9    0.07       0  4979.7     0.1       0  5181.8    0.12       0
  5276.2    0.05       0
Bank Sta=4974.9,4979.7
Exp/Cntr=0.3,0.1

Type RM Length L Ch R = 1,5281,280,280,280
BEGIN DESCRIPTION:
Lacy 098 1734
END DESCRIPTION:
XS GIS Cut Line= 3
      2742969.51      6863869.12      2743107.46      6864086.76
      2743650.39      6864480.75
#Sta/Elev= 30
  4748.3  449.93  4850.0  445.52  4892.6  442.92  4920.7  442.27  4951.2  438.99
  4963.6  436.51  4978.3  435.92  4993.6  436.35  4999.5  432.94  5003.1  429.87
  5003.7  429.37  5007.4  429.37  5008.0  429.87  5016.0  431.71  5022.2  435.60
  5036.9  435.81  5043.1  434.90  5051.6  435.73  5057.8  435.11  5066.0  435.81
  5087.1  436.03  5115.4  435.33  5329.9  436.24  5430.4  439.40  5501.5  444.17
  5551.8  446.62  5609.6  448.15  5616.7  447.66  5659.0  448.22  5676.8  447.77
#Mann=4,-1,0
  4748.3    0.05       0  4850.0    0.12       0  5003.1    0.07       0
  5008.0    0.12       0
Bank Sta=5003.1,5008
Exp/Cntr=0.3,0.1

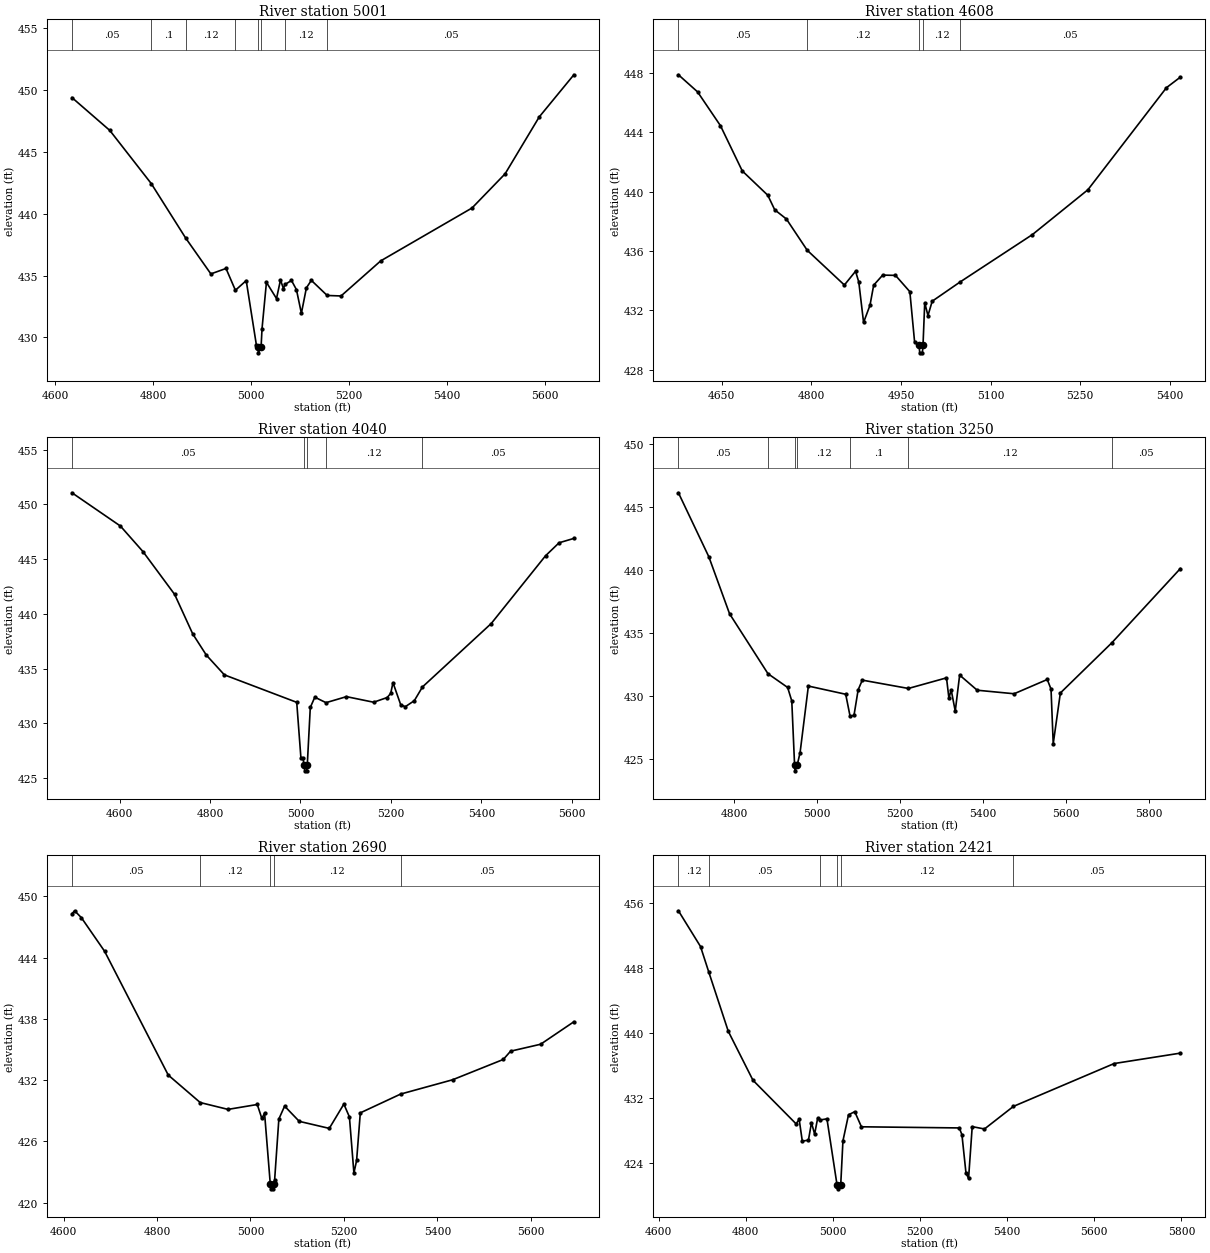
Type RM Length L Ch R = 1,5001,393,393,393
BEGIN DESCRIPTION:
Lacy 098 1733
END DESCRIPTION:
XS GIS Cut Line= 3
      2742815.85      6863926.07      2742921.57      6864339.92
      2742828.54      6864930.80
#Sta/Elev= 30
  4633.8  449.36  4711.1  446.71  4795.8  442.42  4866.0  438.03  4917.6  435.13
  4948.5  435.57  4967.7  433.81  4989.8  434.59  5010.5  429.41  5013.7  429.26
  5014.7  428.76  5020.2  429.26  5022.1  430.71  5031.1  434.45  5051.7  433.14
  5059.8  434.64  5065.9  433.94  5069.1  434.28  5082.3  434.60  5092.4  433.86
  5102.5  431.95  5112.7  434.00  5122.8  434.61  5155.2  433.39  5183.5  433.35
  5264.5  436.18  5451.1  440.45  5518.7  443.21  5588.4  447.80  5659.1  451.20
#Mann=8,-1,0
  4633.8    0.05       0  4795.8     0.1       0  4866.0    0.12       0
  4967.7     0.1       0  5013.7    0.07       0  5020.2     0.1       0
  5069.1    0.12       0  5155.2    0.05       0
Bank Sta=5013.7,5020.2
Exp/Cntr=0.3,0.1

Type RM Length L Ch R = 1,4608,568,568,568
BEGIN DESCRIPTION:
Lacy 098 41
END DESCRIPTION:
XS GIS Cut Line= 3
      2742725.99      6863961.03      2742576.00      6864361.00
      2742475.99      6864761.03
#Sta/Elev= 30
  4577.9  447.87  4609.9  446.72  4648.2  444.44  4684.7  441.39  4727.4  439.75
  4739.0  438.77  4758.5  438.15  4793.4  436.04  4855.5  433.70  4874.2  434.63
  4879.6  433.90  4887.6  431.18  4898.3  432.33  4904.5  433.69  4919.6  434.37
  4941.0  434.35  4965.0  433.25  4973.0  429.84  4980.5  429.63  4981.5  429.13
  4985.9  429.13  4987.0  429.63  4989.9  432.51  4995.3  431.64  5002.4  432.61
  5049.2  433.91  5170.0  437.10  5262.8  440.12  5394.2  447.00  5417.4  447.71
#Mann=5,-1,0
  4577.9    0.05       0  4793.4    0.12       0  4980.5    0.07       0
  4987.0    0.12       0  5049.2    0.05       0
Bank Sta=4980.5,4987
Exp/Cntr=0.3,0.1

Type RM Length L Ch R = 1,4040,790,790,790
BEGIN DESCRIPTION:
Lacy 098 1732
END DESCRIPTION:
XS GIS Cut Line= 3
      2742102.38      6863603.85      2742097.52      6864114.58
      2742077.70      6864713.70
#Sta/Elev= 30
  4494.5  451.06  4601.7  448.02  4651.7  445.68  4721.7  441.77  4761.7  438.16
  4791.7  436.23  4831.7  434.42  4991.7  431.91  5001.0  426.81  5005.2  426.81
  5008.4  426.15  5009.4  425.65  5013.9  425.65  5015.0  426.15  5021.7  431.44
  5031.7  432.38  5056.5  431.88  5101.7  432.43  5161.8  431.92  5191.8  432.35
  5199.6  432.73  5204.6  433.71  5221.8  431.68  5231.8  431.51  5251.8  432.06
  5269.9  433.32  5421.9  439.11  5542.0  445.30  5572.0  446.49  5604.7  446.89
#Mann=5,-1,0
  4494.5    0.05       0  5008.4    0.04       0  5015.0    0.05       0
  5056.5    0.12       0  5269.9    0.05       0
Bank Sta=5008.4,5015
Exp/Cntr=0.3,0.1

Type RM Length L Ch R = 1,3250,560,560,560
BEGIN DESCRIPTION:
Lacy 098 1708
END DESCRIPTION:
XS GIS Cut Line= 4
      2741369.89      6863577.69      2741368.26      6863923.12
      2741371.24      6864167.37      2741172.25      6864754.89
#Sta/Elev= 30
  4665.8  446.10  4739.1  441.03  4789.1  436.51  4881.7  431.76  4929.1  430.67
  4939.1  429.60  4945.8  424.56  4946.9  424.06  4952.5  424.56  4959.1  425.50
  4979.1  430.78  5069.1  430.13  5079.7  428.38  5089.1  428.46  5099.1  430.48
  5109.1  431.25  5220.2  430.59  5312.1  431.43  5318.0  429.80  5323.3  430.49
  5333.2  428.79  5343.8  431.65  5386.1  430.45  5475.1  430.17  5555.0  431.30
  5564.1  430.54  5569.4  426.21  5586.6  430.23  5710.7  434.21  5875.8  440.09
#Mann=7,-1,0
  4665.8    0.05       0  4881.7    0.12       0  4945.8    0.07       0
  4952.5    0.12       0  5079.7     0.1       0  5220.2    0.12       0
  5710.7    0.05       0
Bank Sta=4945.8,4952.5
Exp/Cntr=0.3,0.1

Type RM Length L Ch R = 1,2690,269,269,269
BEGIN DESCRIPTION:
Lacy 098 1706
END DESCRIPTION:
XS GIS Cut Line= 3
      2741152.58      6863549.09      2740916.44      6863847.40
      2740563.07      6864444.27
#Sta/Elev= 30
  4618.0  448.30  4623.7  448.59  4638.1  447.92  4687.8  444.63  4824.1  432.50
  4892.5  429.81  4952.0  429.14  5014.6  429.62  5024.4  428.25  5030.2  428.77
  5042.4  421.86  5043.5  421.36  5048.3  421.36  5049.4  421.86  5051.7  422.20
  5060.8  428.20  5073.1  429.46  5104.4  427.97  5168.7  427.28  5199.9  429.66
  5211.8  428.40  5221.4  422.91  5227.2  424.14  5235.1  428.80  5321.4  430.64
  5432.6  432.04  5541.1  434.03  5556.7  434.84  5621.0  435.52  5692.1  437.72
#Mann=5,-1,0
  4618.0    0.05       0  4892.5    0.12       0  5042.4    0.07       0
  5049.4    0.12       0  5321.4    0.05       0
Bank Sta=5042.4,5049.4
Exp/Cntr=0.3,0.1

Type RM Length L Ch R = 1,2421,787,787,787
BEGIN DESCRIPTION:
Lacy 098 1705
END DESCRIPTION:
XS GIS Cut Line= 3
      2741051.82      6863434.97      2740792.57      6863685.99
      2740370.24      6864354.85
#Sta/Elev= 30
  4645.5  455.02  4696.2  450.62  4715.1  447.49  4760.0  440.17  4816.6  434.15
  4915.6  428.78  4922.6  429.34  4929.8  426.66  4943.9  426.77  4950.9  428.93
  4958.1  427.52  4965.0  429.46  4970.6  429.26  4986.4  429.40  5009.5  421.28
  5010.8  420.78  5018.0  421.28  5023.1  426.69  5035.9  429.90  5050.2  430.28
  5065.5  428.42  5290.2  428.28  5296.2  427.44  5305.5  422.71  5311.4  422.06
  5319.8  428.44  5347.9  428.15  5414.3  430.93  5645.6  436.21  5797.4  437.49
#Mann=6,-1,0
  4645.5    0.12       0  4715.1    0.05       0  4970.6    0.12       0
  5009.5    0.07       0  5018.0    0.12       0  5414.3    0.05       0
Bank Sta=5009.5,5018
Exp/Cntr=0.3,0.1

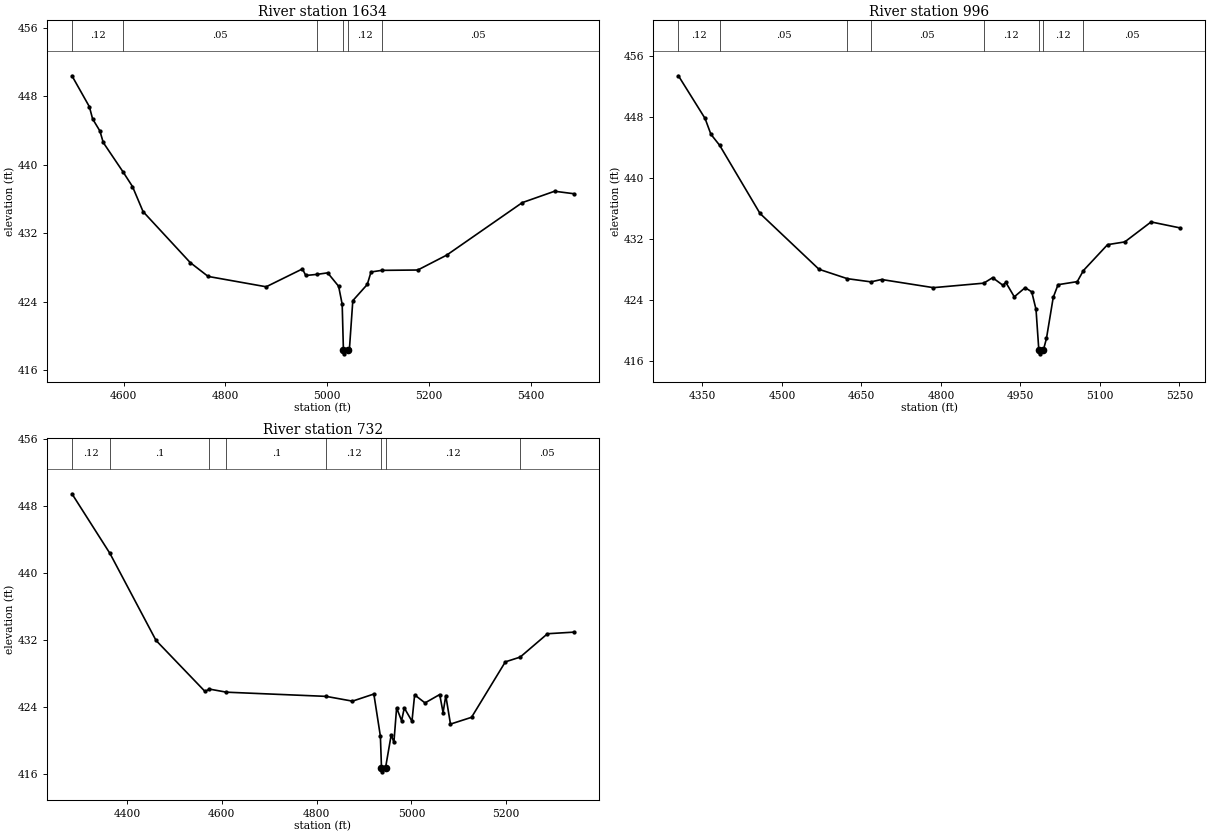
Type RM Length L Ch R = 1,1634,638,638,638
BEGIN DESCRIPTION:
Lacy 098 1704
END DESCRIPTION:
XS GIS Cut Line= 3
      2740682.79      6863210.59      2740289.84      6863528.53
      2739934.19      6863852.57
#Sta/Elev= 30
  4498.3  450.40  4532.5  446.79  4538.9  445.36  4553.3  443.94  4559.8  442.60
  4599.0  439.14  4617.3  437.45  4638.1  434.52  4730.8  428.56  4766.0  426.94
  4880.1  425.73  4951.4  427.82  4957.9  427.05  4980.0  427.18  5001.0  427.36
  5022.5  425.79  5029.5  423.69  5031.9  418.39  5033.2  417.89  5040.5  418.39
  5043.7  418.43  5050.4  424.11  5078.8  426.00  5086.2  427.46  5107.3  427.65
  5178.1  427.69  5234.9  429.43  5383.5  435.57  5447.0  436.90  5484.9  436.61
#Mann=6,-1,0
  4498.3    0.12       0  4599.0    0.05       0  4980.0    0.12       0
  5031.9    0.07       0  5040.5    0.12       0  5107.3    0.05       0
Bank Sta=5031.9,5040.5
Exp/Cntr=0.3,0.1

Type RM Length L Ch R = 1,996,264,264,264
BEGIN DESCRIPTION:
Lacy 098 1703
END DESCRIPTION:
XS GIS Cut Line= 3
      2740605.10      6863143.80      2739932.15      6863291.42
      2739704.59      6863413.31
#Sta/Elev= 30
  4304.7  453.39  4355.0  447.79  4366.0  445.72  4382.6  444.26  4458.7  435.33
  4570.0  428.01  4623.4  426.78  4668.0  426.36  4688.0  426.67  4785.9  425.60
  4880.9  426.19  4897.6  426.91  4917.3  425.90  4922.4  426.30  4938.5  424.40
  4959.0  425.60  4971.4  425.05  4979.5  422.75  4984.8  417.42  4986.1  416.92
  4993.4  417.42  4999.2  418.94  5012.0  424.33  5021.1  425.99  5057.3  426.39
  5069.0  427.85  5114.5  431.24  5147.0  431.60  5196.6  434.22  5251.8  433.43
#Mann=8,-1,0
  4304.7    0.12       0  4382.6    0.05       0  4623.4    0.12       0
  4668.0    0.05       0  4880.9    0.12       0  4984.8    0.07       0
  4993.4    0.12       0  5069.0    0.05       0
Bank Sta=4984.8,4993.4
Exp/Cntr=0.3,0.1

Type RM Length L Ch R = 1,732,0,0,0
BEGIN DESCRIPTION:
Lacy 098 1707
END DESCRIPTION:
XS GIS Cut Line= 3
      2740535.68      6863030.58      2739901.14      6862978.80
      2739700.55      6863349.90
#Sta/Elev= 30
  4284.0  449.48  4364.1  442.36  4461.3  431.97  4564.6  425.88  4573.9  426.16
  4609.9  425.79  4820.1  425.29  4875.6  424.72  4920.7  425.57  4934.5  420.53
  4936.8  416.78  4938.0  416.28  4945.4  416.78  4957.3  420.69  4963.0  419.81
  4968.7  423.92  4979.2  422.39  4984.9  423.91  5001.1  422.32  5006.7  425.47
  5028.6  424.51  5059.6  425.51  5066.7  423.35  5072.4  425.38  5082.3  421.98
  5126.7  422.79  5198.0  429.41  5229.3  429.98  5286.9  432.77  5342.5  432.96
#Mann=8,-1,0
  4284.0    0.12       0  4364.1     0.1       0  4573.9    0.12       0
  4609.9     0.1       0  4820.1    0.12       0  4936.8    0.07       0
  4945.4    0.12       0  5229.3    0.05       0
Bank Sta=4936.8,4945.4
Exp/Cntr=0.3,0.1

Chan Stop Cuts=-1