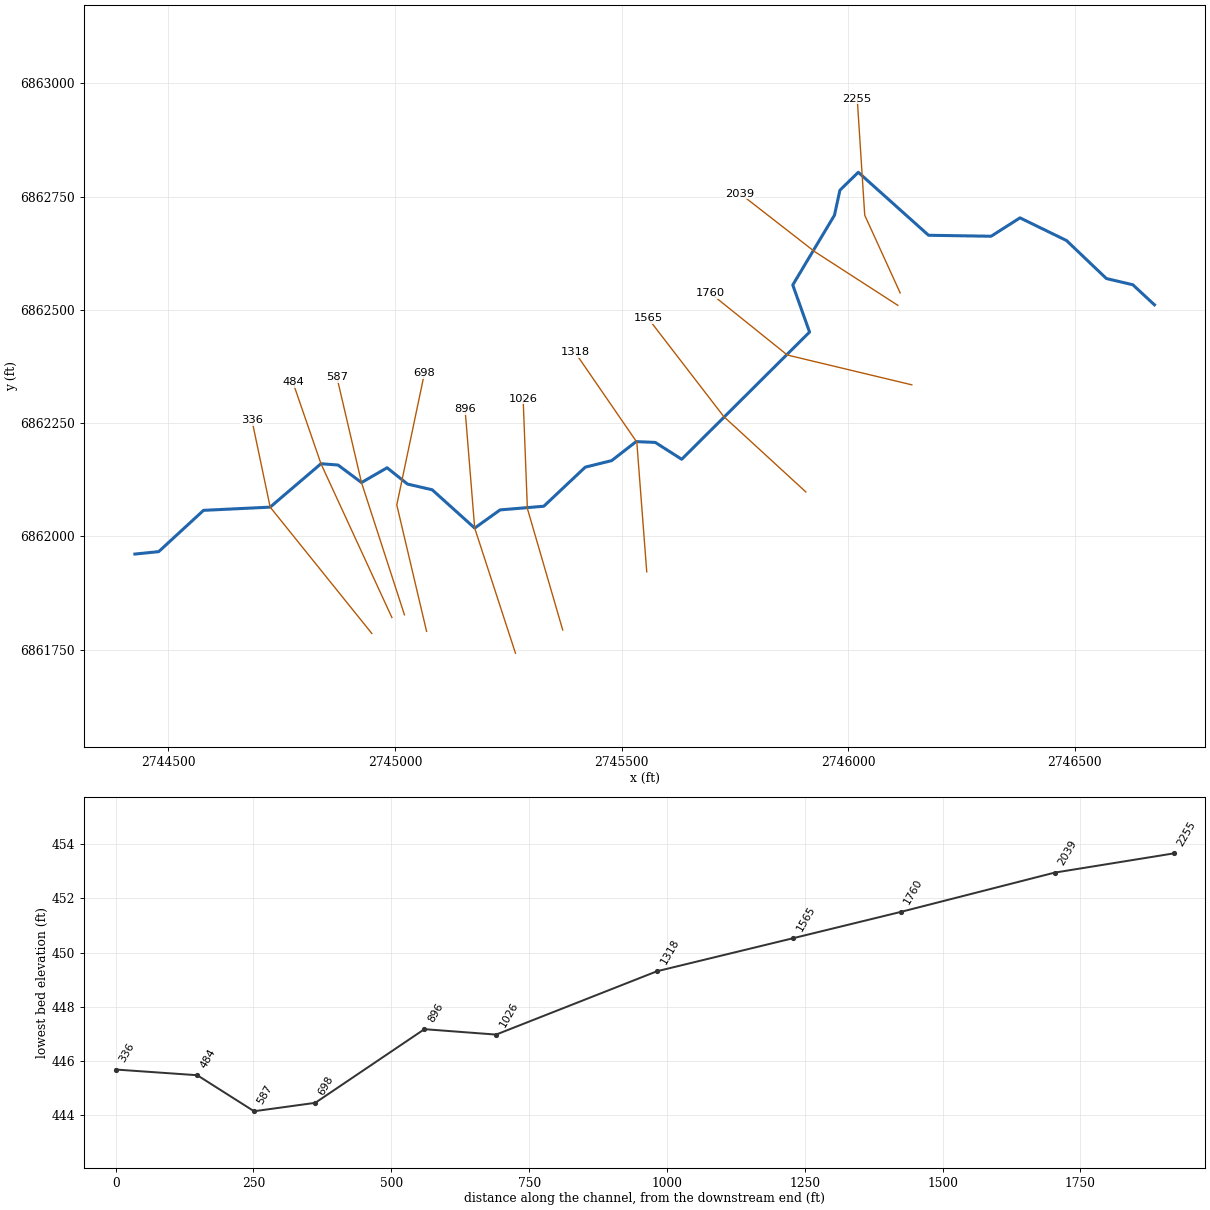
--- Lacy 099.prj (project) ---

Proj Title=Lacy 099 Base Level Engineering
Current Plan=p01
Default Exp/Contr=0.3,0.1
English Units
Geom File=g01
Flow File=f01
Plan File=p01
BEGIN DESCRIPTION:
Lacy 099
END DESCRIPTION:

--- Lacy 099.p01 (plan) ---

Plan Title=Multiple Run
Short Identifier=Multiple
Geom File=g01
Flow File=f01
Subcritical Flow
K Sum by GR= 0
Std Step Tol= 0.01
Critical Tol= 0.01
Num of Std Step Trials= 20
Max Error Tol= 0.3
Flow Tol Ratio= 0.001
Split Flow NTrial= 30
Split Flow Tol= 0.02
Split Flow Ratio= 0.02
Log Output Level= 0
Friction Slope Method= 1
Unsteady Friction Slope Method= 2
Unsteady Bridges Friction Slope Method= 1
Parabolic Critical Depth
Global Vel Dist=  1 , 1 , 1
Global Log Level= 0
CheckData=True
Encroach Param= -1, 0, 0, 0
BEGIN DESCRIPTION:
Multiple Run
END DESCRIPTION:

--- Lacy 099.f01 (steady flow) ---

Flow Title=Multiple
Number of Profiles=7
Profile Names=10-year,25-year,50-year,1pct_min,100-year,1pct_plu,500-year
River Rch & RM= Lacy 099,Reach-1,2255
     287     368     431     252     502    1002     681
Boundary for River Rch & Prof#=Lacy 099,Reach-1,1
Up Type=0
Dn Type=3
Dn Slope=0.005
Boundary for River Rch & Prof#=Lacy 099,Reach-1,2
Up Type=0
Dn Type=3
Dn Slope=0.005
Boundary for River Rch & Prof#=Lacy 099,Reach-1,3
Up Type=0
Dn Type=3
Dn Slope=0.005
Boundary for River Rch & Prof#=Lacy 099,Reach-1,4
Up Type=0
Dn Type=3
Dn Slope=0.005
Boundary for River Rch & Prof#=Lacy 099,Reach-1,5
Up Type=0
Dn Type=3
Dn Slope=0.005
Boundary for River Rch & Prof#=Lacy 099,Reach-1,6
Up Type=0
Dn Type=3
Dn Slope=0.005
Boundary for River Rch & Prof#=Lacy 099,Reach-1,7
Up Type=0
Dn Type=3
Dn Slope=0.005

--- Lacy 099.g01 (geometry) ---

Geom Title=Existing Conditions

River Reach=Lacy 099,Reach-1
Reach XY= 30
      2746676.00      6862511.00      2746628.35      6862555.30
      2746569.92      6862569.07      2746482.04      6862652.86
      2746379.32      6862702.96      2746315.56      6862662.37
      2746177.47      6862664.53      2746022.42      6862803.52
      2745981.83      6862763.87      2745969.90      6862708.87
      2745877.84      6862554.87      2745914.89      6862450.95
      2745632.73      6862170.15      2745574.37      6862207.39
      2745532.12      6862209.16      2745478.19      6862167.18
      2745419.95      6862152.84      2745328.42      6862066.53
      2745231.89      6862058.44      2745175.90      6862018.32
      2745082.05      6862102.84      2745027.65      6862115.44
      2744982.55      6862151.42      2744926.08      6862118.83
      2744874.35      6862157.44      2744836.64      6862160.35
      2744724.53      6862064.56      2744577.47      6862057.46
      2744478.51      6861966.33      2744426.00      6861961.00

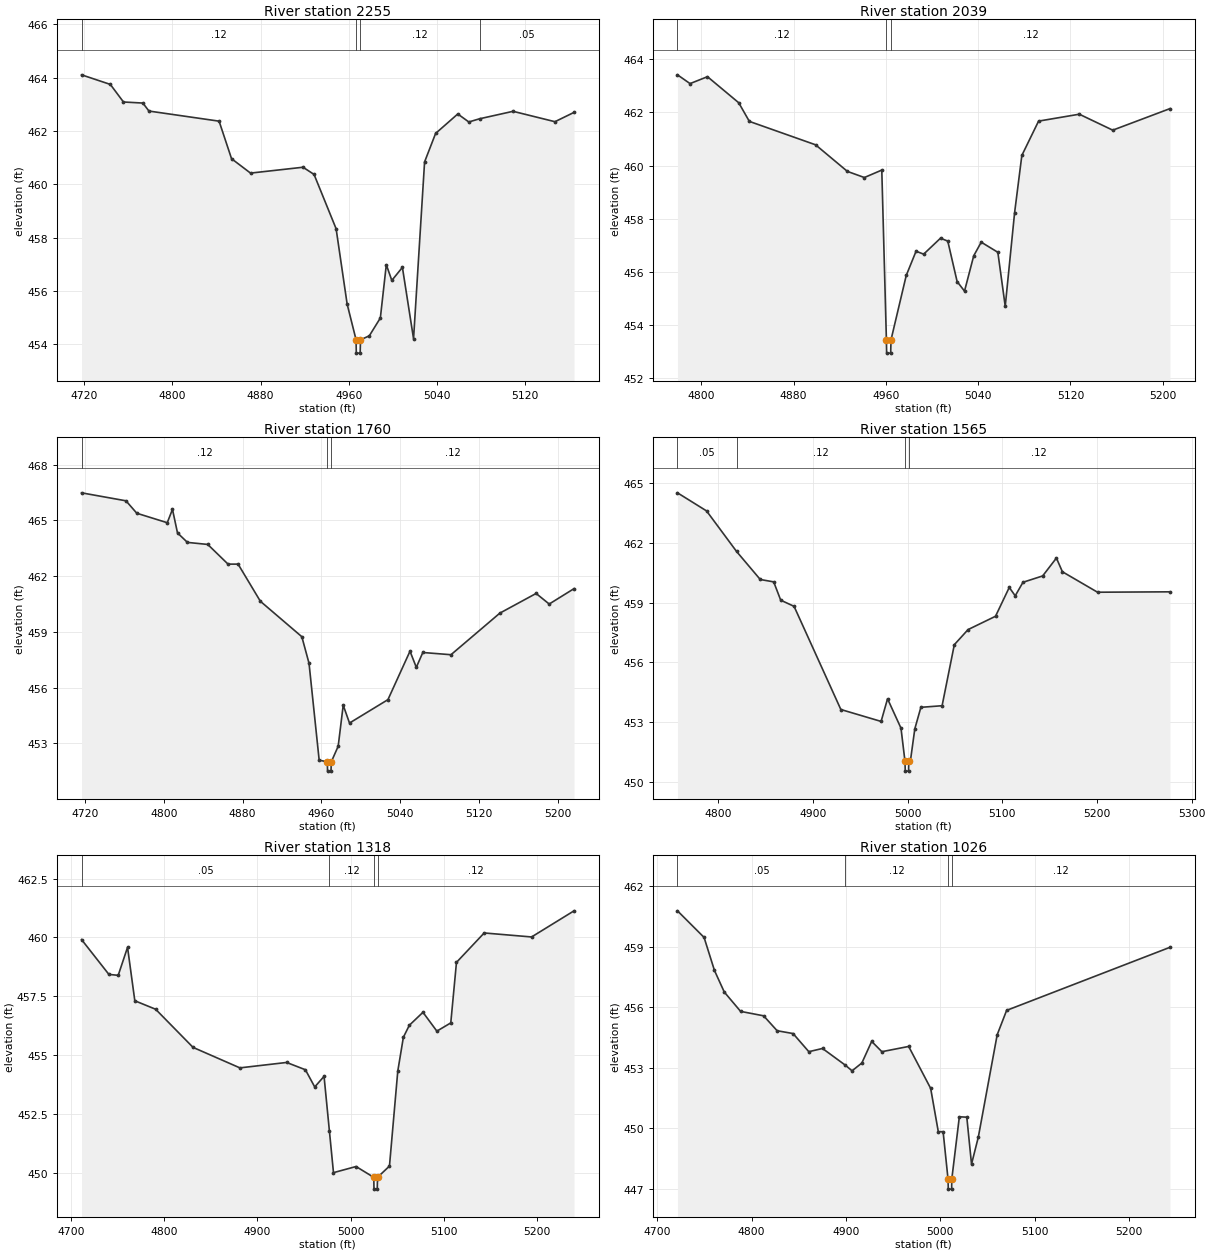
Type RM Length L Ch R = 1,2255,216,216,216
BEGIN DESCRIPTION:
Lacy 099 1762
END DESCRIPTION:
XS GIS Cut Line= 3
      2746114.87      6862537.25      2746036.67      6862708.78
      2746020.08      6862966.23
#Sta/Elev= 30
  4717.7  464.11  4743.8  463.75  4755.7  463.09  4773.3  463.05  4778.8  462.75
  4842.4  462.37  4853.7  460.96  4870.9  460.42  4918.5  460.64  4928.5  460.37
  4948.5  458.33  4958.5  455.50  4966.6  454.16  4966.8  453.66  4970.3  453.66
  4970.6  454.16  4978.6  454.31  4988.6  454.98  4994.0  456.98  4999.0  456.39
  5008.6  456.88  5018.7  454.20  5028.7  460.84  5038.7  461.91  5058.8  462.64
  5068.8  462.34  5078.6  462.46  5108.9  462.74  5146.9  462.35  5164.2  462.70
#Mann=4,-1,0
  4717.7    0.12       0  4966.6    0.07       0  4970.6    0.12       0
  5078.6    0.05       0
Bank Sta=4966.6,4970.6
Exp/Cntr=0.3,0.1

Type RM Length L Ch R = 1,2039,279,279,279
BEGIN DESCRIPTION:
Lacy 099 1761
END DESCRIPTION:
XS GIS Cut Line= 3
      2746109.73      6862509.85      2745926.34      6862628.31
      2745761.72      6862756.39
#Sta/Elev= 30
  4779.4  463.41  4790.3  463.08  4805.4  463.34  4832.5  462.36  4841.7  461.66
  4899.1  460.78  4926.7  459.78  4941.4  459.55  4956.5  459.83  4960.5  453.45
  4960.7  452.95  4964.2  452.95  4964.5  453.45  4977.7  455.87  4986.2  456.78
  4992.8  456.67  5007.4  457.27  5013.7  457.16  5021.8  455.64  5028.2  455.28
  5036.2  456.61  5042.7  457.12  5057.1  456.74  5063.5  454.71  5071.6  458.22
  5077.9  460.38  5092.4  461.67  5127.7  461.93  5156.7  461.33  5206.3  462.14
#Mann=3,-1,0
  4779.4    0.12       0  4960.5    0.07       0  4964.5    0.12       0
Bank Sta=4960.5,4964.5
Exp/Cntr=0.3,0.1

Type RM Length L Ch R = 1,1760,195,195,195
BEGIN DESCRIPTION:
Lacy 099 1760
END DESCRIPTION:
XS GIS Cut Line= 3
      2746140.57      6862334.47      2745865.84      6862400.23
      2745696.36      6862536.41
#Sta/Elev= 30
  4716.6  466.49  4761.7  466.06  4772.7  465.39  4803.6  464.88  4808.9  465.60
  4814.0  464.33  4824.1  463.82  4844.7  463.71  4865.3  462.65  4875.5  462.65
  4898.1  460.65  4940.2  458.74  4947.5  457.31  4957.8  452.09  4966.1  452.00
  4966.3  451.50  4969.8  451.50  4970.1  452.00  4977.1  452.84  4982.2  455.05
  4988.6  454.09  5027.6  455.35  5050.0  457.96  5056.4  457.09  5063.0  457.89
  5091.6  457.77  5141.2  460.01  5178.0  461.07  5191.3  460.50  5216.5  461.33
#Mann=3,-1,0
  4716.6    0.12       0  4966.1    0.07       0  4970.1    0.12       0
Bank Sta=4966.1,4970.1
Exp/Cntr=0.3,0.1

Type RM Length L Ch R = 1,1565,247,247,247
BEGIN DESCRIPTION:
Lacy 099 1759
END DESCRIPTION:
XS GIS Cut Line= 3
      2745906.69      6862098.10      2745725.59      6862264.44
      2745558.34      6862481.60
#Sta/Elev= 30
  4757.1  464.53  4787.8  463.62  4819.5  461.58  4844.5  460.17  4858.7  460.05
  4866.1  459.13  4880.2  458.82  4929.6  453.63  4972.1  453.03  4978.9  454.17
  4993.1  452.69  4997.3  451.03  4997.6  450.53  5001.1  450.53  5001.3  451.03
  5003.0  451.03  5007.7  452.66  5014.1  453.74  5036.5  453.82  5049.4  456.89
  5063.9  457.65  5092.9  458.32  5107.4  459.77  5113.7  459.35  5121.9  460.03
  5142.7  460.35  5157.2  461.25  5163.5  460.56  5200.6  459.53  5277.1  459.55
#Mann=4,-1,0
  4757.1    0.05       0  4819.5    0.12       0  4997.3    0.07       0
  5001.3    0.12       0
Bank Sta=4997.3,5001.3
Exp/Cntr=0.3,0.1

Type RM Length L Ch R = 1,1318,292,292,292
BEGIN DESCRIPTION:
Lacy 099 1758
END DESCRIPTION:
XS GIS Cut Line= 3
      2745555.57      6861921.83      2745533.66      6862207.96
      2745397.19      6862406.39
#Sta/Elev= 30
  4711.5  459.91  4740.8  458.43  4750.8  458.39  4760.8  459.58  4768.6  457.31
  4790.9  456.95  4831.0  455.33  4881.2  454.46  4931.3  454.69  4951.4  454.38
  4961.4  453.65  4971.4  454.10  4977.1  451.79  4981.5  450.01  5005.7  450.27
  5024.7  449.81  5024.9  449.31  5028.4  449.31  5028.7  449.81  5041.5  450.29
  5050.4  454.32  5056.4  455.76  5062.8  456.27  5077.4  456.82  5092.3  456.02
  5107.2  456.37  5113.3  458.94  5143.0  460.19  5193.8  460.02  5239.3  461.13
#Mann=4,-1,0
  4711.5    0.05       0  4977.1    0.12       0  5024.7    0.07       0
  5028.7    0.12       0
Bank Sta=5024.7,5028.7
Exp/Cntr=0.3,0.1

Type RM Length L Ch R = 1,1026,130,130,130
BEGIN DESCRIPTION:
Lacy 099 1757
END DESCRIPTION:
XS GIS Cut Line= 3
      2745370.15      6861793.38      2745292.16      6862061.59
      2745282.77      6862303.99
#Sta/Elev= 30
  4721.5  460.78  4749.7  459.46  4760.7  457.82  4771.1  456.75  4788.4  455.79
  4812.8  455.57  4827.1  454.83  4844.0  454.69  4860.7  453.79  4875.2  453.95
  4899.4  453.12  4906.5  452.84  4916.9  453.23  4927.3  454.30  4938.1  453.79
  4966.5  454.05  4989.8  451.97  4997.9  449.82  5003.0  449.82  5008.2  447.47
  5008.5  446.97  5012.0  446.97  5012.2  447.47  5020.2  450.56  5028.1  450.54
  5033.1  448.21  5040.3  449.55  5060.3  454.63  5070.3  455.84  5243.4  458.97
#Mann=4,-1,0
  4721.5    0.05       0  4899.4    0.12       0  5008.2    0.07       0
  5012.2    0.12       0
Bank Sta=5008.2,5012.2
Exp/Cntr=0.3,0.1

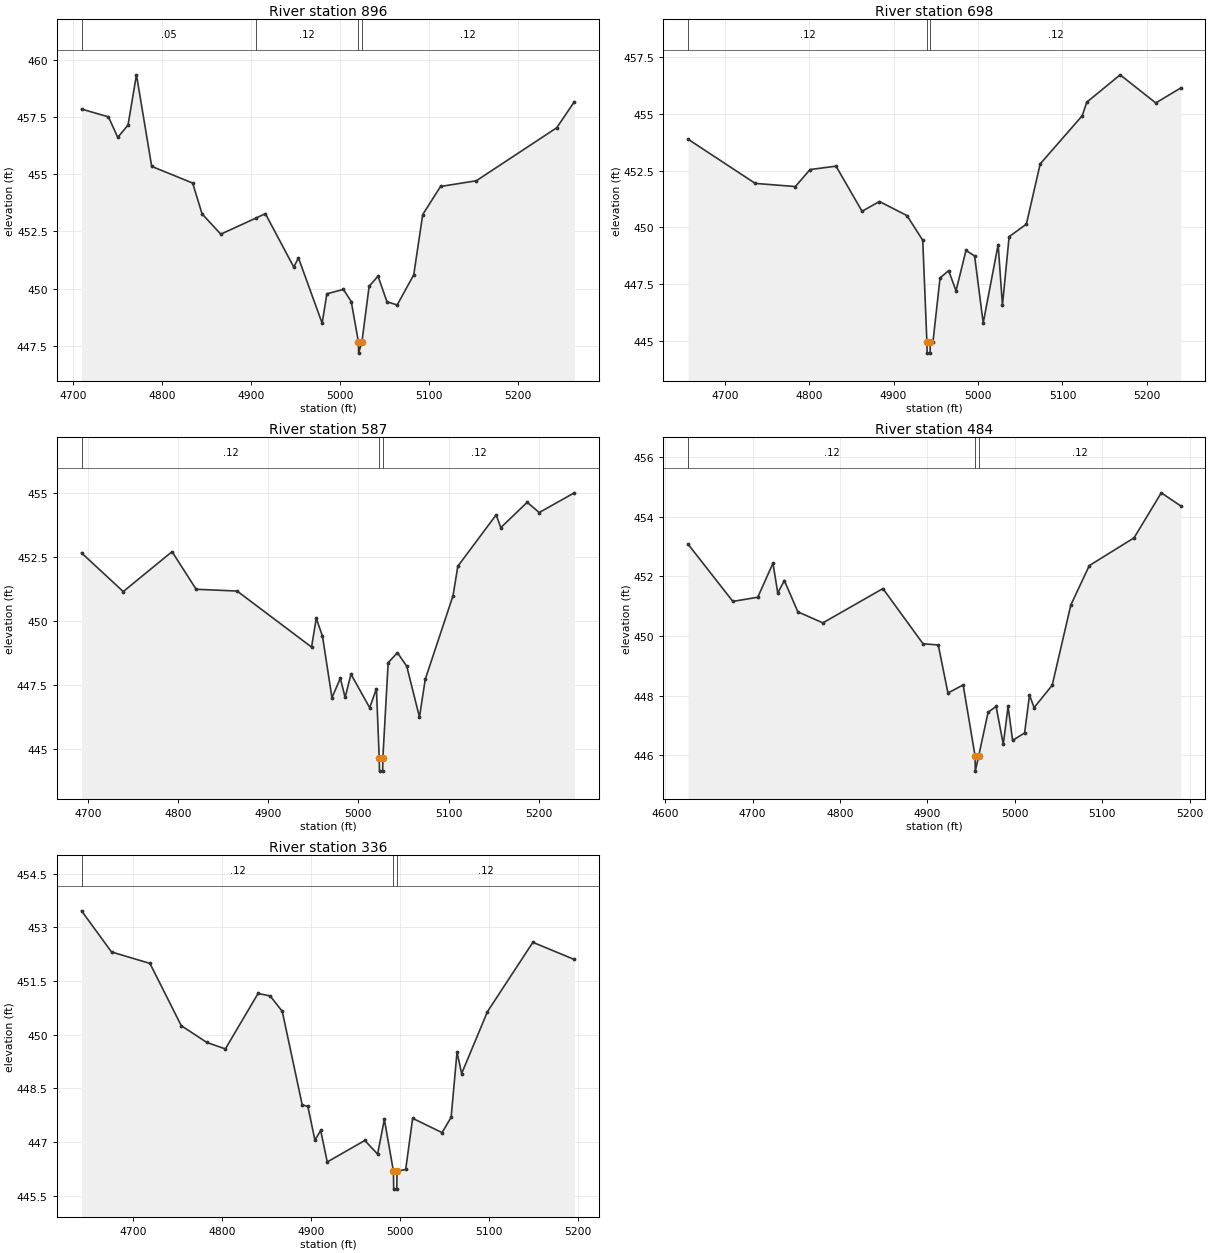
Type RM Length L Ch R = 1,896,198,198,198
BEGIN DESCRIPTION:
Lacy 099 1769
END DESCRIPTION:
XS GIS Cut Line= 3
      2745265.84      6861742.31      2745175.90      6862018.32
      2745154.61      6862280.76
#Sta/Elev= 30
  4709.7  457.86  4739.9  457.52  4750.4  456.62  4761.9  457.16  4771.4  459.36
  4788.5  455.35  4834.5  454.62  4845.1  453.27  4866.1  452.38  4905.3  453.08
  4916.2  453.28  4948.1  450.94  4953.4  451.34  4980.0  448.48  4985.3  449.77
  5003.9  449.96  5012.7  449.43  5020.7  447.67  5021.0  447.17  5024.7  447.67
  5032.8  450.10  5042.8  450.54  5052.8  449.42  5064.3  449.28  5082.9  450.60
  5093.0  453.24  5113.0  454.47  5153.2  454.72  5243.5  457.04  5263.3  458.18
#Mann=4,-1,0
  4709.7    0.05       0  4905.3    0.12       0  5020.7    0.07       0
  5024.7    0.12       0
Bank Sta=5020.7,5024.7
Exp/Cntr=0.3,0.1

Type RM Length L Ch R = 1,698,111,111,111
BEGIN DESCRIPTION:
Lacy 099 1768
END DESCRIPTION:
XS GIS Cut Line= 3
      2745069.69      6861790.37      2745003.97      6862069.45
      2745064.98      6862360.00
#Sta/Elev= 30
  4656.5  453.89  4736.1  451.94  4783.6  451.80  4801.0  452.55  4831.8  452.70
  4862.6  450.71  4883.2  451.14  4915.8  450.52  4934.5  449.43  4939.4  444.95
  4939.7  444.45  4943.2  444.45  4943.4  444.95  4946.6  444.95  4955.0  447.77
  4965.2  448.09  4973.9  447.20  4985.7  448.98  4995.9  448.74  5006.1  445.78
  5023.8  449.24  5028.9  446.56  5036.8  449.59  5057.2  450.14  5073.6  452.80
  5123.5  454.93  5128.7  455.52  5168.3  456.73  5210.5  455.49  5240.1  456.15
#Mann=3,-1,0
  4656.5    0.12       0  4939.4    0.07       0  4943.4    0.12       0
Bank Sta=4939.4,4943.4
Exp/Cntr=0.3,0.1

Type RM Length L Ch R = 1,587,103,103,103
BEGIN DESCRIPTION:
Lacy 099 1767
END DESCRIPTION:
XS GIS Cut Line= 3
      2745020.82      6861827.02      2744926.08      6862118.83
      2744871.66      6862351.86
#Sta/Elev= 30
  4693.2  452.67  4739.4  451.16  4793.5  452.72  4820.2  451.25  4865.6  451.18
  4948.1  448.99  4953.3  450.11  4960.2  449.42  4970.7  447.01  4980.0  447.77
  4985.3  447.02  4991.8  447.93  5012.5  446.62  5020.0  447.36  5023.1  444.64
  5023.4  444.14  5026.9  444.14  5027.1  444.64  5033.0  448.38  5043.3  448.77
  5053.6  448.24  5067.7  446.25  5074.1  447.73  5104.9  451.00  5110.2  452.15
  5152.7  454.16  5157.8  453.66  5187.1  454.65  5200.4  454.25  5239.3  455.02
#Mann=3,-1,0
  4693.2    0.12       0  5023.1    0.07       0  5027.1    0.12       0
Bank Sta=5023.1,5027.1
Exp/Cntr=0.3,0.1

Type RM Length L Ch R = 1,484,148,148,148
BEGIN DESCRIPTION:
Lacy 099 1766
END DESCRIPTION:
XS GIS Cut Line= 3
      2744993.19      6861820.91      2744836.64      6862160.35
      2744774.72      6862339.97
#Sta/Elev= 30
  4626.2  453.08  4677.5  451.16  4706.0  451.30  4723.4  452.44  4728.9  451.44
  4736.4  451.86  4751.9  450.81  4780.5  450.44  4849.2  451.59  4895.1  449.74
  4912.5  449.70  4923.6  448.09  4941.0  448.36  4954.7  445.97  4954.9  445.47
  4958.7  445.97  4969.5  447.44  4978.7  447.64  4986.9  446.37  4992.4  447.64
  4997.6  446.50  5011.3  446.75  5016.9  448.02  5022.2  447.60  5042.9  448.35
  5064.2  451.04  5085.3  452.36  5136.5  453.29  5167.7  454.80  5190.0  454.36
#Mann=3,-1,0
  4626.2    0.12       0  4954.7    0.07       0  4958.7    0.12       0
Bank Sta=4954.7,4958.7
Exp/Cntr=0.3,0.1

Type RM Length L Ch R = 1,336,0,0,0
BEGIN DESCRIPTION:
Lacy 099 1765
END DESCRIPTION:
XS GIS Cut Line= 3
      2744948.90      6861785.72      2744724.53      6862064.56
      2744684.26      6862256.58
#Sta/Elev= 30
  4642.1  453.46  4675.8  452.31  4719.0  451.99  4754.2  450.25  4783.0  449.78
  4803.8  449.60  4840.6  451.15  4854.2  451.08  4867.8  450.65  4890.2  448.04
  4896.6  447.99  4904.5  447.05  4911.0  447.32  4918.4  446.44  4960.6  447.04
  4975.0  446.66  4982.6  447.63  4992.8  446.18  4993.1  445.68  4996.6  445.68
  4996.8  446.18  5006.6  446.23  5014.4  447.66  5047.5  447.26  5057.7  447.69
  5064.3  449.51  5069.5  448.91  5098.5  450.64  5149.6  452.58  5196.2  452.10
#Mann=3,-1,0
  4642.1    0.12       0  4992.8    0.07       0  4996.8    0.12       0
Bank Sta=4992.8,4996.8
Exp/Cntr=0.3,0.1

Chan Stop Cuts=-1