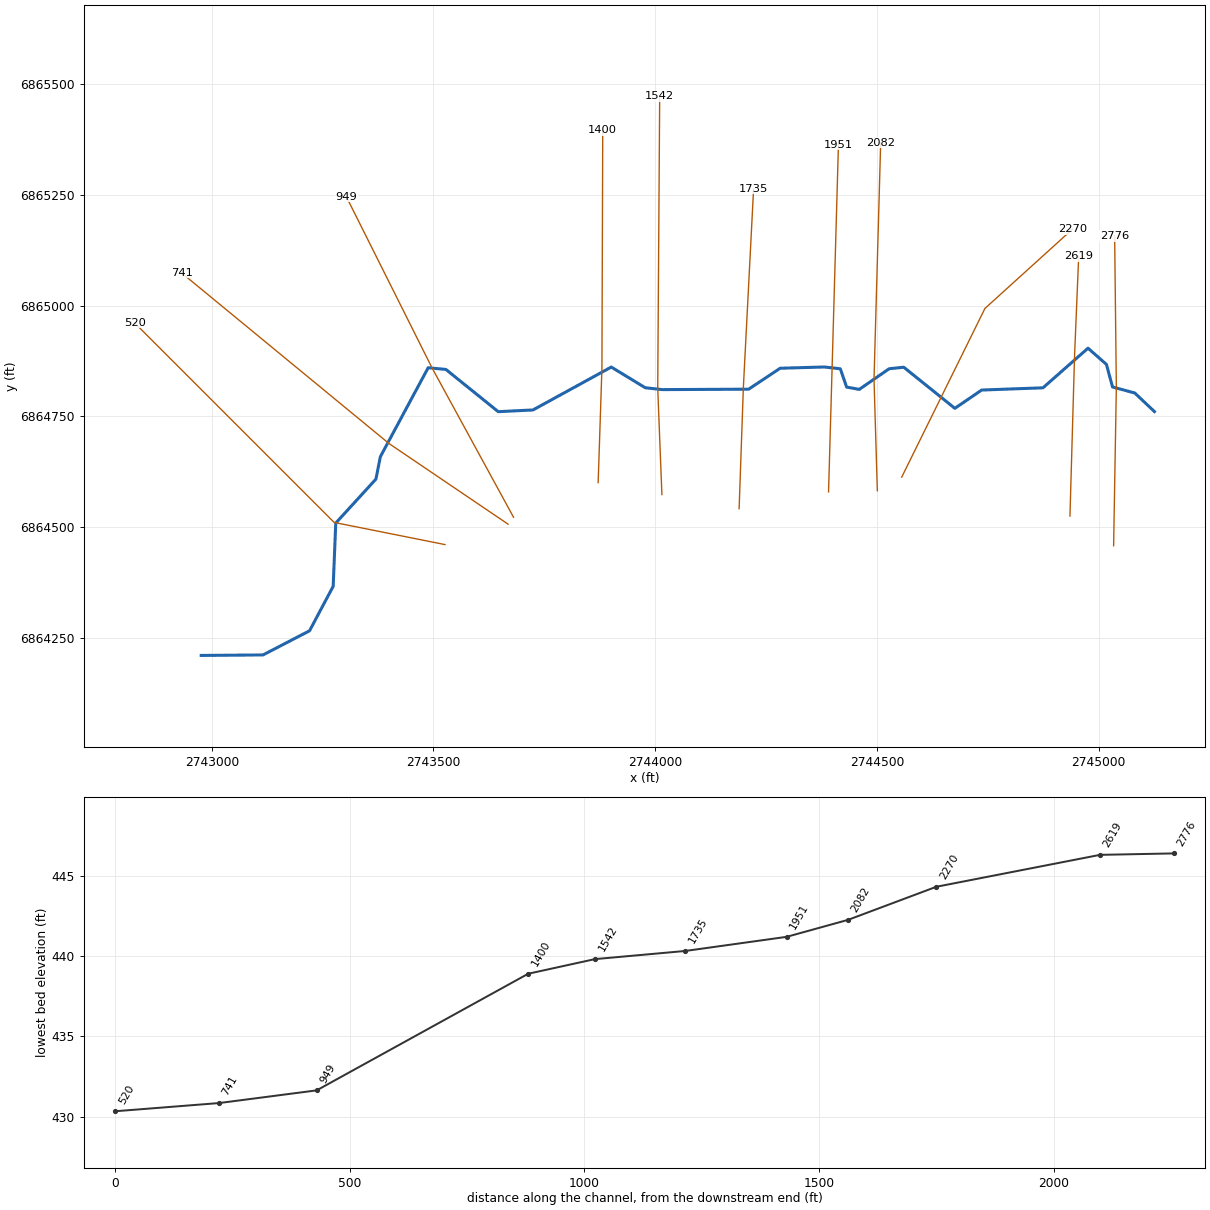
--- Lacy 100.prj (project) ---

Proj Title=Lacy 100 Base Level Engineering
Current Plan=p01
Default Exp/Contr=0.3,0.1
English Units
Geom File=g01
Flow File=f01
Plan File=p01
BEGIN DESCRIPTION:
Lacy 100
END DESCRIPTION:

--- Lacy 100.p01 (plan) ---

Plan Title=Multiple Run
Short Identifier=Multiple
Geom File=g01
Flow File=f01
Subcritical Flow
K Sum by GR= 0
Std Step Tol= 0.01
Critical Tol= 0.01
Num of Std Step Trials= 20
Max Error Tol= 0.3
Flow Tol Ratio= 0.001
Split Flow NTrial= 30
Split Flow Tol= 0.02
Split Flow Ratio= 0.02
Log Output Level= 0
Friction Slope Method= 1
Unsteady Friction Slope Method= 2
Unsteady Bridges Friction Slope Method= 1
Parabolic Critical Depth
Global Vel Dist=  1 , 1 , 1
Global Log Level= 0
CheckData=True
Encroach Param= -1, 0, 0, 0
BEGIN DESCRIPTION:
Multiple Run
END DESCRIPTION:

--- Lacy 100.f01 (steady flow) ---

Flow Title=Multiple
Number of Profiles=7
Profile Names=10-year,25-year,50-year,1pct_min,100-year,1pct_plu,500-year
River Rch & RM= Lacy 100,Reach-1,2776
     439     581     695     414     826    1648    1167
Boundary for River Rch & Prof#=Lacy 100,Reach-1,1
Up Type=0
Dn Type=3
Dn Slope=0.005
Boundary for River Rch & Prof#=Lacy 100,Reach-1,2
Up Type=0
Dn Type=3
Dn Slope=0.005
Boundary for River Rch & Prof#=Lacy 100,Reach-1,3
Up Type=0
Dn Type=3
Dn Slope=0.005
Boundary for River Rch & Prof#=Lacy 100,Reach-1,4
Up Type=0
Dn Type=3
Dn Slope=0.005
Boundary for River Rch & Prof#=Lacy 100,Reach-1,5
Up Type=0
Dn Type=3
Dn Slope=0.005
Boundary for River Rch & Prof#=Lacy 100,Reach-1,6
Up Type=0
Dn Type=3
Dn Slope=0.005
Boundary for River Rch & Prof#=Lacy 100,Reach-1,7
Up Type=0
Dn Type=3
Dn Slope=0.005

--- Lacy 100.g01 (geometry) ---

Geom Title=Existing Conditions

River Reach=Lacy 100,Reach-1
Reach XY= 30
      2745126.00      6864761.00      2745081.70      6864802.89
      2745031.51      6864816.51      2745017.73      6864867.43
      2744976.21      6864903.98      2744874.53      6864814.57
      2744736.44      6864809.60      2744675.90      6864768.33
      2744560.66      6864861.03      2744527.71      6864857.62
      2744460.30      6864811.05      2744431.79      6864816.22
      2744417.56      6864857.48      2744381.52      6864861.59
      2744281.95      6864858.75      2744210.78      6864811.52
      2744015.81      6864810.55      2743977.55      6864814.81
      2743901.00      6864861.41      2743724.41      6864764.67
      2743646.05      6864760.79      2743527.95      6864856.06
      2743488.01      6864859.88      2743380.19      6864659.26
      2743370.15      6864608.71      2743279.55      6864509.53
      2743273.76      6864366.91      2743220.42      6864266.58
      2743115.54      6864212.14      2742976.00      6864211.00

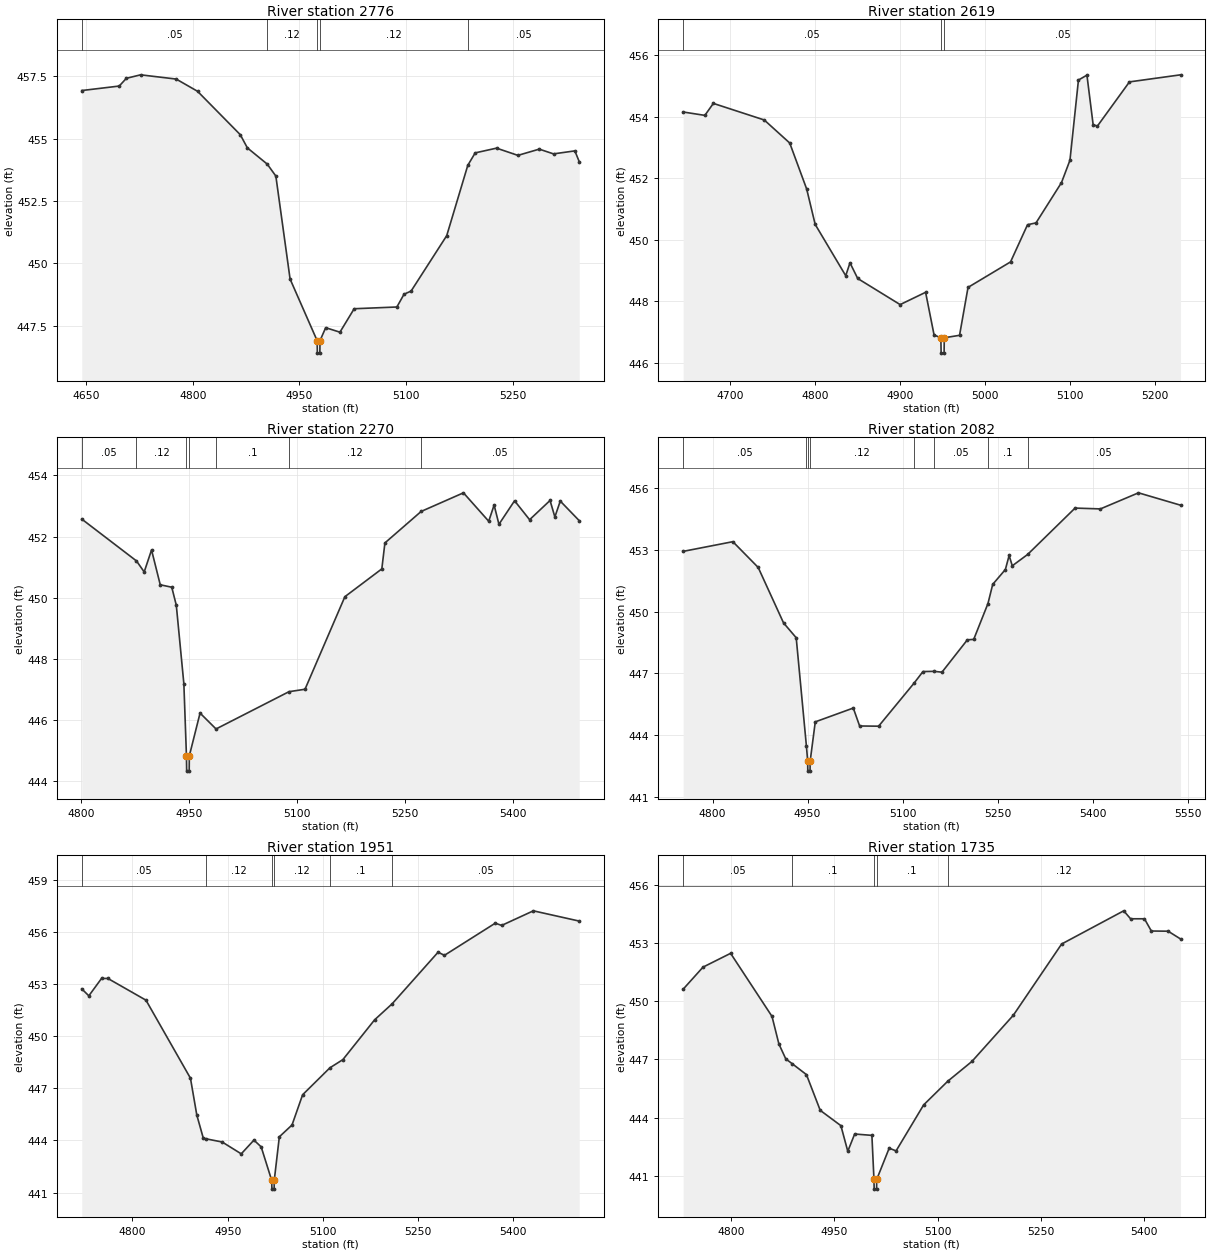
Type RM Length L Ch R = 1,2776,157,157,157
BEGIN DESCRIPTION:
Lacy 100 1743
END DESCRIPTION:
XS GIS Cut Line= 3
      2745033.97      6864458.43      2745040.09      6864815.37
      2745036.29      6865157.06
#Sta/Elev= 30
  4644.2  456.93  4696.8  457.11  4706.8  457.42  4726.8  457.56  4776.8  457.39
  4806.8  456.90  4866.8  455.16  4876.8  454.63  4904.7  453.98  4916.8  453.50
  4936.8  449.37  4974.8  446.90  4975.1  446.40  4978.6  446.40  4978.8  446.90
  4986.8  447.42  5006.8  447.24  5026.8  448.18  5086.8  448.25  5096.8  448.76
  5106.8  448.89  5156.8  451.11  5186.4  453.93  5196.8  454.43  5226.8  454.62
  5256.8  454.33  5286.8  454.58  5306.8  454.39  5336.8  454.51  5342.9  454.08
#Mann=5,-1,0
  4644.2    0.05       0  4904.7    0.12       0  4974.8    0.07       0
  4978.8    0.12       0  5186.4    0.05       0
Bank Sta=4974.8,4978.8
Exp/Cntr=0.3,0.1

Type RM Length L Ch R = 1,2619,349,349,349
BEGIN DESCRIPTION:
Lacy 100 1744
END DESCRIPTION:
XS GIS Cut Line= 3
      2744935.48      6864525.41      2744945.88      6864887.57
      2744955.19      6865111.17
#Sta/Elev= 30
  4644.4  454.16  4670.0  454.05  4680.0  454.44  4740.0  453.90  4770.0  453.15
  4790.0  451.65  4800.0  450.50  4836.0  448.83  4841.0  449.25  4850.1  448.74
  4900.1  447.89  4930.1  448.29  4940.1  446.90  4948.1  446.81  4948.4  446.31
  4951.9  446.31  4952.1  446.81  4970.1  446.89  4980.1  448.45  5030.2  449.28
  5050.2  450.49  5060.2  450.55  5090.2  451.86  5100.2  452.59  5110.2  455.20
  5120.2  455.36  5127.5  453.75  5132.5  453.70  5170.3  455.14  5230.5  455.37
#Mann=3,-1,0
  4644.4    0.05       0  4948.1    0.03       0  4952.1    0.05       0
Bank Sta=4948.1,4952.1
Exp/Cntr=0.3,0.1

Type RM Length L Ch R = 1,2270,188,188,188
BEGIN DESCRIPTION:
Lacy 100 1742
END DESCRIPTION:
XS GIS Cut Line= 3
      2744556.07      6864613.23      2744743.69      6864993.56
      2744941.48      6865172.78
#Sta/Elev= 30
  4800.6  452.57  4876.6  451.20  4887.3  450.84  4897.5  451.56  4909.6  450.42
  4925.6  450.34  4931.9  449.75  4942.4  447.18  4946.0  444.82  4946.3  444.32
  4949.8  444.32  4950.0  444.82  4964.9  446.22  4987.1  445.70  5088.4  446.92
  5110.7  447.00  5166.1  450.03  5217.4  450.94  5221.7  451.79  5272.0  452.82
  5330.8  453.43  5365.9  452.50  5373.4  453.03  5380.1  452.40  5401.8  453.17
  5422.7  452.55  5451.1  453.18  5457.8  452.64  5465.3  453.16  5491.6  452.52
#Mann=7,-1,0
  4800.6    0.05       0  4876.6    0.12       0  4946.0    0.07       0
  4950.0    0.12       0  4987.1     0.1       0  5088.4    0.12       0
  5272.0    0.05       0
Bank Sta=4946,4950
Exp/Cntr=0.3,0.1

Type RM Length L Ch R = 1,2082,131,131,131
BEGIN DESCRIPTION:
Lacy 100 1741
END DESCRIPTION:
XS GIS Cut Line= 3
      2744501.04      6864582.54      2744493.56      6864833.44
      2744508.58      6865367.41
#Sta/Elev= 30
  4753.5  452.92  4832.0  453.39  4872.0  452.14  4912.0  449.45  4932.0  448.73
  4948.1  443.48  4950.1  442.76  4950.3  442.26  4953.8  442.26  4954.1  442.76
  4962.1  444.65  5022.1  445.32  5032.1  444.45  5062.1  444.44  5118.1  446.53
  5132.1  447.09  5149.8  447.10  5162.1  447.06  5202.2  448.63  5212.2  448.65
  5234.7  450.39  5242.2  451.32  5262.2  452.04  5268.1  452.72  5273.1  452.22
  5297.3  452.77  5372.2  455.02  5412.2  454.98  5472.3  455.76  5538.7  455.16
#Mann=8,-1,0
  4753.5    0.05       0  4948.1    0.12       0  4950.1    0.07       0
  4954.1    0.12       0  5118.1     0.1       0  5149.8    0.05       0
  5234.7     0.1       0  5297.3    0.05       0
Bank Sta=4950.1,4954.1
Exp/Cntr=0.3,0.1

Type RM Length L Ch R = 1,1951,216,216,216
BEGIN DESCRIPTION:
Lacy 100 1739
END DESCRIPTION:
XS GIS Cut Line= 3
      2744391.00      6864579.91      2744399.00      6864858.88
      2744413.34      6865363.19
#Sta/Elev= 30
  4720.2  452.72  4731.3  452.32  4751.3  453.32  4761.3  453.32  4821.3  452.07
  4891.4  447.58  4901.4  445.46  4911.4  444.16  4915.1  444.10  4941.4  443.91
  4971.4  443.23  4991.4  444.02  5002.8  443.63  5019.4  441.70  5019.7  441.20
  5023.2  441.20  5023.4  441.70  5031.4  444.21  5051.4  444.89  5068.1  446.63
  5111.1  448.18  5131.5  448.65  5181.5  450.94  5209.1  451.86  5281.5  454.83
  5291.5  454.65  5371.6  456.50  5381.6  456.37  5431.6  457.21  5503.8  456.62
#Mann=6,-1,0
  4720.2    0.05       0  4915.1    0.12       0  5019.4    0.07       0
  5023.4    0.12       0  5111.1     0.1       0  5209.1    0.05       0
Bank Sta=5019.4,5023.4
Exp/Cntr=0.3,0.1

Type RM Length L Ch R = 1,1735,193,193,193
BEGIN DESCRIPTION:
Lacy 100 1740
END DESCRIPTION:
XS GIS Cut Line= 3
      2744189.32      6864542.13      2744198.91      6864815.99
      2744221.96      6865263.37
#Sta/Elev= 30
  4730.5  450.62  4759.4  451.76  4799.4  452.47  4859.5  449.22  4869.5  447.80
  4879.5  447.03  4888.9  446.78  4909.5  446.22  4929.5  444.38  4959.5  443.59
  4969.5  442.27  4979.5  443.16  5004.5  443.09  5007.5  440.82  5007.8  440.32
  5011.3  440.32  5011.5  440.82  5029.6  442.43  5039.6  442.29  5079.6  444.66
  5114.6  445.88  5149.7  446.90  5209.8  449.28  5279.9  452.95  5370.0  454.66
  5380.0  454.25  5400.1  454.25  5410.1  453.62  5434.5  453.61  5452.5  453.21
#Mann=5,-1,0
  4730.5    0.05       0  4888.9     0.1       0  5007.5    0.07       0
  5011.5     0.1       0  5114.6    0.12       0
Bank Sta=5007.5,5011.5
Exp/Cntr=0.3,0.1

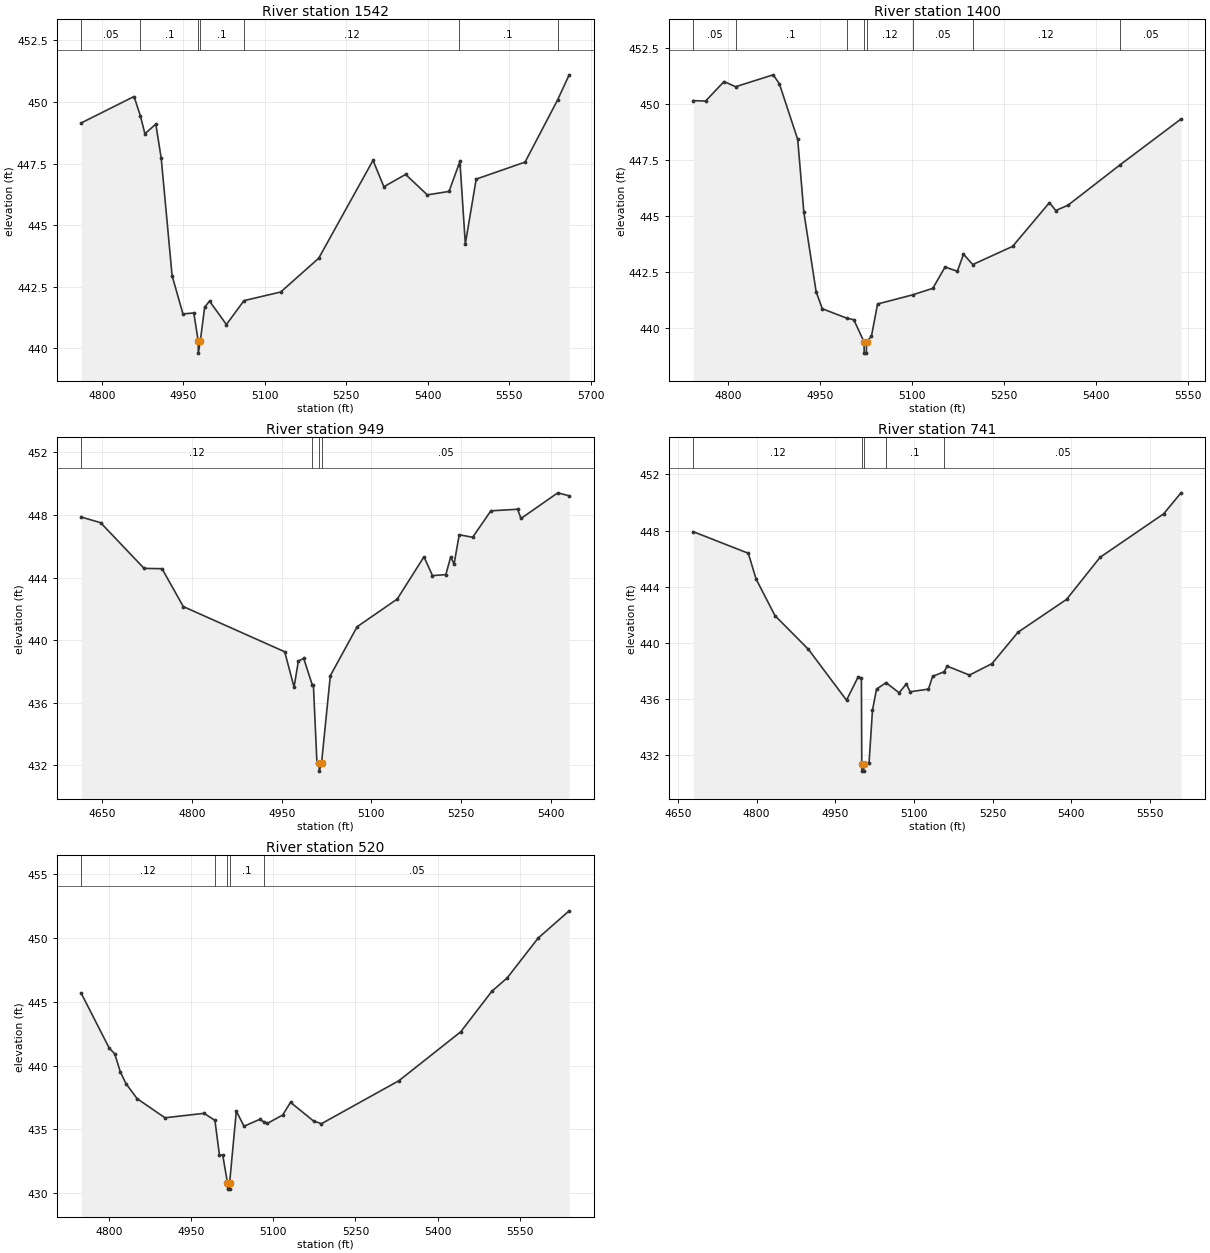
Type RM Length L Ch R = 1,1542,142,142,142
BEGIN DESCRIPTION:
Lacy 100 1738
END DESCRIPTION:
XS GIS Cut Line= 3
      2744015.15      6864573.95      2744005.73      6864813.96
      2744010.16      6865472.15
#Sta/Elev= 30
  4762.1  449.15  4859.2  450.22  4871.1  449.42  4879.2  448.71  4899.3  449.10
  4909.3  447.71  4929.3  442.95  4949.3  441.40  4969.3  441.44  4977.3  440.31
  4977.6  439.81  4981.3  440.31  4989.3  441.68  4998.3  441.92  5029.3  440.97
  5061.7  441.94  5129.3  442.29  5199.3  443.66  5299.3  447.63  5319.3  446.56
  5359.3  447.06  5399.3  446.23  5439.3  446.37  5457.3  447.46  5459.3  447.60
  5469.3  444.24  5489.3  446.87  5579.3  447.56  5639.2  450.08  5660.5  451.10
#Mann=7,-1,0
  4762.1    0.05       0  4871.1     0.1       0  4977.3    0.07       0
  4981.3     0.1       0  5061.7    0.12       0  5457.3     0.1       0
  5639.2    0.05       0
Bank Sta=4977.3,4981.3
Exp/Cntr=0.3,0.1

Type RM Length L Ch R = 1,1400,451,451,451
BEGIN DESCRIPTION:
Lacy 100 1737
END DESCRIPTION:
XS GIS Cut Line= 3
      2743871.38      6864600.78      2743879.88      6864858.57
      2743881.71      6865395.43
#Sta/Elev= 30
  4743.7  450.16  4763.9  450.14  4794.0  451.01  4812.8  450.78  4874.0  451.31
  4884.0  450.92  4914.0  448.43  4924.0  445.19  4944.0  441.64  4954.0  440.88
  4993.9  440.46  5005.4  440.39  5022.1  439.40  5022.3  438.90  5025.8  438.90
  5026.1  439.40  5034.1  439.65  5044.1  441.09  5101.3  441.50  5134.1  441.79
  5154.1  442.74  5174.1  442.55  5184.1  443.31  5199.2  442.85  5264.1  443.66
  5324.1  445.61  5334.4  445.26  5354.1  445.49  5438.9  447.29  5538.5  449.34
#Mann=8,-1,0
  4743.7    0.05       0  4812.8     0.1       0  4993.9    0.12       0
  5022.1    0.07       0  5026.1    0.12       0  5101.3    0.05       0
  5199.2    0.12       0  5438.9    0.05       0
Bank Sta=5022.1,5026.1
Exp/Cntr=0.3,0.1

Type RM Length L Ch R = 1,949,208,208,208
BEGIN DESCRIPTION:
Lacy 100 1736
END DESCRIPTION:
XS GIS Cut Line= 3
      2743680.56      6864522.61      2743496.33      6864860.22
      2743303.61      6865245.27
#Sta/Elev= 30
  4615.2  447.87  4647.5  447.51  4720.1  444.59  4750.1  444.57  4785.6  442.15
  4955.1  439.26  4970.7  437.00  4977.9  438.66  4986.8  438.84  5001.1  437.15
  5003.0  437.15  5009.0  432.13  5012.6  432.13  5012.8  431.63  5016.6  432.13
  5031.3  437.73  5076.1  440.86  5143.1  442.63  5187.8  445.33  5202.0  444.13
  5224.3  444.19  5232.5  445.33  5238.1  444.87  5246.7  446.74  5269.1  446.58
  5299.6  448.27  5344.3  448.37  5349.9  447.78  5411.4  449.42  5430.4  449.23
#Mann=4,-1,0
  4615.2    0.12       0  5001.1    0.05       0  5012.6    0.07       0
  5016.6    0.05       0
Bank Sta=5012.6,5016.6
Exp/Cntr=0.3,0.1

Type RM Length L Ch R = 1,741,221,221,221
BEGIN DESCRIPTION:
Lacy 100 1735
END DESCRIPTION:
XS GIS Cut Line= 3
      2743668.08      6864507.15      2743399.50      6864689.05
      2742931.57      6865073.99
#Sta/Elev= 30
  4679.2  447.92  4784.3  446.38  4799.2  444.54  4835.2  441.93  4899.1  439.52
  4971.6  435.90  4993.9  437.57  5000.0  437.49  5000.7  431.34  5000.9  430.84
  5004.4  430.84  5004.7  431.34  5014.6  431.44  5021.1  435.18  5028.9  436.69
  5046.9  437.15  5071.9  436.43  5085.8  437.06  5092.8  436.50  5127.9  436.69
  5135.8  437.60  5157.8  437.93  5163.5  438.33  5206.1  437.69  5249.1  438.51
  5298.7  440.75  5391.2  443.09  5455.1  446.09  5576.3  449.19  5609.5  450.69
#Mann=5,-1,0
  4679.2    0.12       0  5000.7    0.07       0  5004.7    0.12       0
  5046.9     0.1       0  5157.8    0.05       0
Bank Sta=5000.7,5004.7
Exp/Cntr=0.3,0.1

Type RM Length L Ch R = 1,520,0,0,0
BEGIN DESCRIPTION:
Lacy 100 56
END DESCRIPTION:
XS GIS Cut Line= 3
      2743525.96      6864461.01      2743276.00      6864511.00
      2742826.00      6864961.00
#Sta/Elev= 30
  4749.2  445.64  4800.1  441.37  4810.3  440.91  4820.5  439.50  4830.7  438.59
  4851.1  437.41  4902.1  435.91  4973.5  436.26  4993.3  435.71  5001.6  432.99
  5007.6  432.99  5016.2  430.83  5016.5  430.33  5020.0  430.33  5020.2  430.83
  5032.4  436.43  5046.5  435.25  5074.8  435.78  5082.9  435.60  5089.0  435.47
  5117.2  436.13  5131.4  437.12  5173.8  435.65  5188.0  435.45  5329.4  438.81
  5442.5  442.64  5499.1  445.80  5527.4  446.86  5583.9  449.97  5640.5  452.10
#Mann=5,-1,0
  4749.2    0.12       0  4993.3     0.1       0  5016.2    0.07       0
  5020.2     0.1       0  5082.9    0.05       0
Bank Sta=5016.2,5020.2
Exp/Cntr=0.3,0.1

Chan Stop Cuts=-1