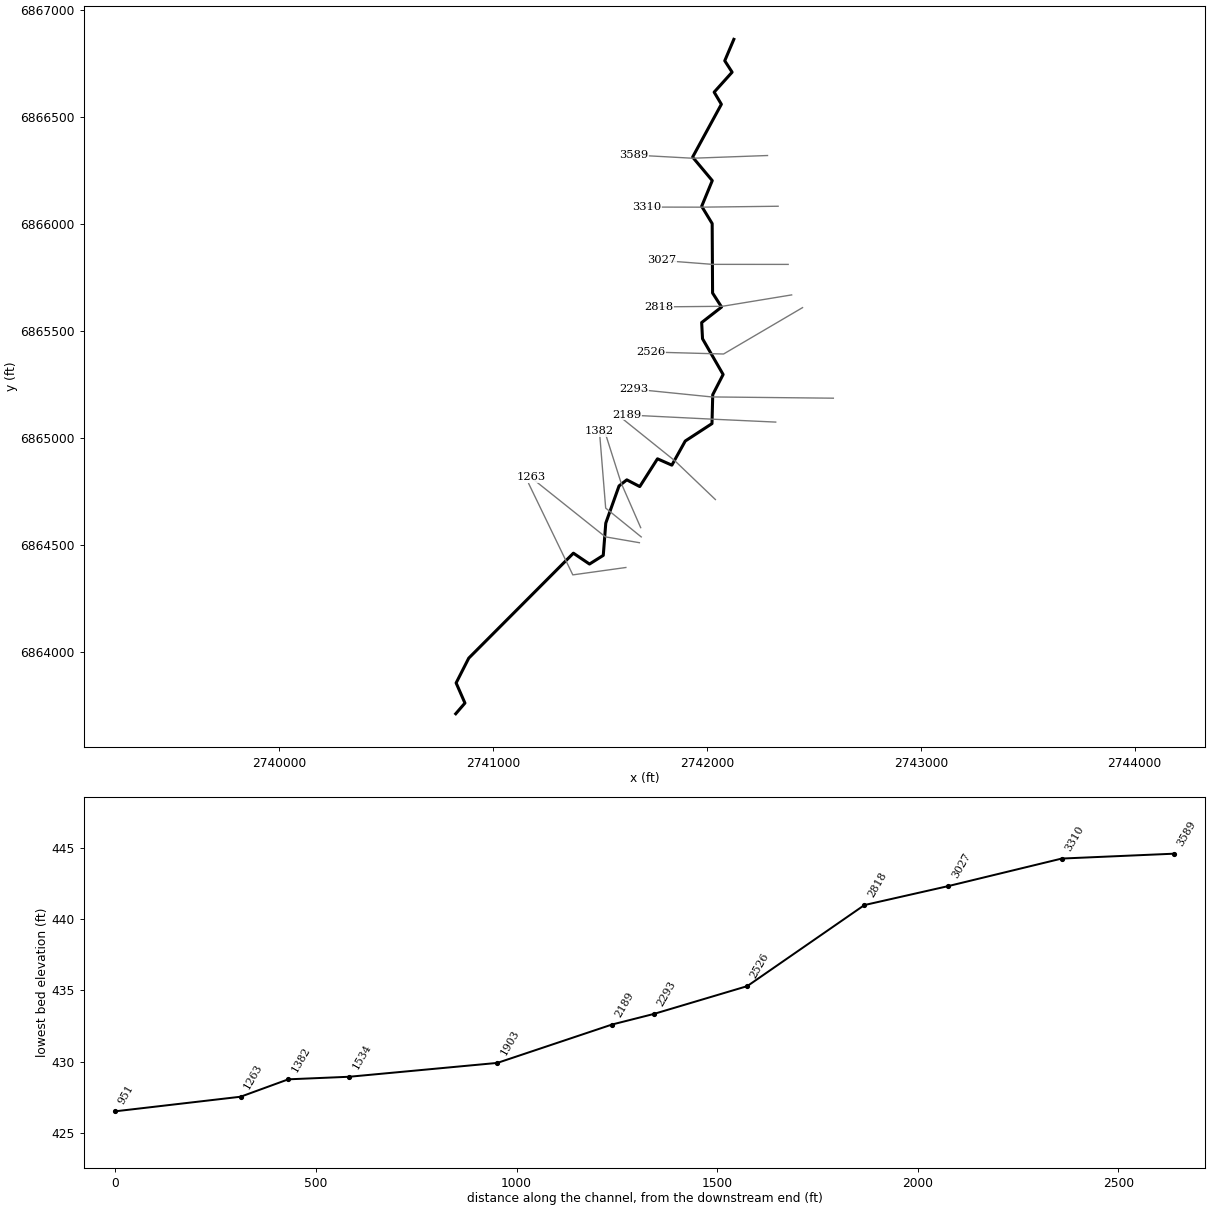
--- Lacy 101.prj (project) ---

Proj Title=Lacy 101 Base Level Engineering
Current Plan=p01
Default Exp/Contr=0.3,0.1
English Units
Geom File=g01
Flow File=f01
Plan File=p01
BEGIN DESCRIPTION:
Lacy 101
END DESCRIPTION:

--- Lacy 101.p01 (plan) ---

Plan Title=Multiple Run
Short Identifier=Multiple
Geom File=g01
Flow File=f01
Subcritical Flow
K Sum by GR= 0
Std Step Tol= 0.01
Critical Tol= 0.01
Num of Std Step Trials= 20
Max Error Tol= 0.3
Flow Tol Ratio= 0.001
Split Flow NTrial= 30
Split Flow Tol= 0.02
Split Flow Ratio= 0.02
Log Output Level= 0
Friction Slope Method= 1
Unsteady Friction Slope Method= 2
Unsteady Bridges Friction Slope Method= 1
Parabolic Critical Depth
Global Vel Dist=  1 , 1 , 1
Global Log Level= 0
CheckData=True
Encroach Param= -1, 0, 0, 0
BEGIN DESCRIPTION:
Multiple Run
END DESCRIPTION:

--- Lacy 101.f01 (steady flow) ---

Flow Title=Multiple
Number of Profiles=7
Profile Names=10-year,25-year,50-year,1pct_min,100-year,1pct_plu,500-year
River Rch & RM= Lacy 101,Reach-1,3589
     246     311     362     210     418     834     558
River Rch & RM= Lacy 101,Reach-1,1263
     335     434     511     300     599    1194     822
Boundary for River Rch & Prof#=Lacy 101,Reach-1,1
Up Type=0
Dn Type=3
Dn Slope=0.005
Boundary for River Rch & Prof#=Lacy 101,Reach-1,2
Up Type=0
Dn Type=3
Dn Slope=0.005
Boundary for River Rch & Prof#=Lacy 101,Reach-1,3
Up Type=0
Dn Type=3
Dn Slope=0.005
Boundary for River Rch & Prof#=Lacy 101,Reach-1,4
Up Type=0
Dn Type=3
Dn Slope=0.005
Boundary for River Rch & Prof#=Lacy 101,Reach-1,5
Up Type=0
Dn Type=3
Dn Slope=0.005
Boundary for River Rch & Prof#=Lacy 101,Reach-1,6
Up Type=0
Dn Type=3
Dn Slope=0.005
Boundary for River Rch & Prof#=Lacy 101,Reach-1,7
Up Type=0
Dn Type=3
Dn Slope=0.005

--- Lacy 101.g01 (geometry) ---

Geom Title=Existing Conditions

River Reach=Lacy 101,Reach-1
Reach XY= 30
      2742126.00      6866861.00      2742083.58      6866760.93
      2742118.00      6866707.66      2742034.02      6866614.34
      2742067.75      6866557.77      2741933.30      6866310.92
      2742025.23      6866201.22      2741975.73      6866081.18
      2742024.76      6866000.50      2742026.67      6865676.15
      2742068.74      6865610.70      2741975.65      6865538.25
      2741979.64      6865462.66      2742075.92      6865295.61
      2742027.41      6865201.34      2742023.90      6865066.26
      2741898.87      6864984.82      2741836.31      6864872.12
      2741769.06      6864901.81      2741686.31      6864772.12
      2741625.77      6864803.53      2741589.40      6864775.09
      2741527.39      6864601.33      2741515.67      6864450.77
      2741451.21      6864410.23      2741376.00      6864461.00
      2740886.76      6863970.68      2740827.82      6863854.88
      2740869.05      6863760.88      2740826.00      6863711.00

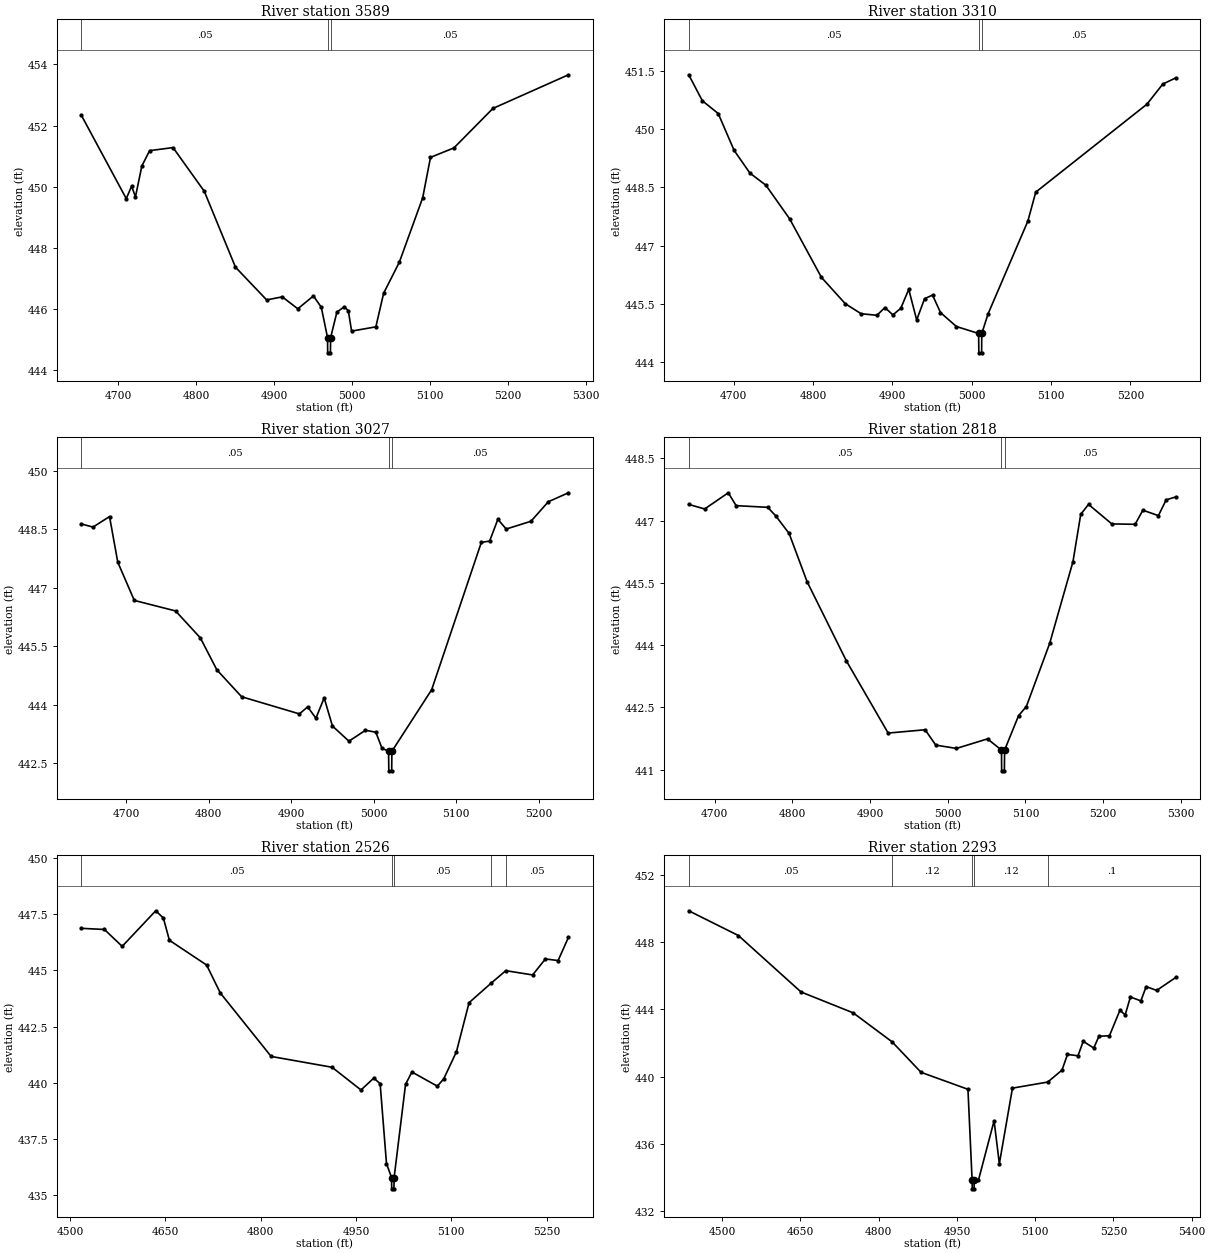
Type RM Length L Ch R = 1,3589,279,279,279
BEGIN DESCRIPTION:
Lacy 101 1726
END DESCRIPTION:
XS GIS Cut Line= 3
      2742283.45      6866318.39      2741933.26      6866305.70
      2741659.29      6866320.68
#Sta/Elev= 30
  4652.7  452.33  4710.2  449.61  4717.0  450.02  4722.0  449.67  4730.2  450.68
  4740.2  451.18  4770.2  451.28  4810.3  449.85  4850.3  447.37  4890.3  446.30
  4910.3  446.40  4930.3  446.01  4950.3  446.43  4960.4  446.06  4968.4  445.07
  4968.6  444.57  4972.1  444.57  4972.4  445.07  4980.4  445.90  4990.1  446.08
  4995.1  445.94  4999.3  445.28  5030.4  445.42  5040.4  446.52  5060.5  447.53
  5090.5  449.64  5100.5  450.96  5130.6  451.27  5180.6  452.56  5277.5  453.66
#Mann=3,-1,0
  4652.7    0.05       0  4968.4    0.04       0  4972.4    0.05       0
Bank Sta=4968.4,4972.4
Exp/Cntr=0.3,0.1

Type RM Length L Ch R = 1,3310,283,283,283
BEGIN DESCRIPTION:
Lacy 101 1727
END DESCRIPTION:
XS GIS Cut Line= 3
      2742333.10      6866081.46      2741971.74      6866077.15
      2741719.73      6866077.60
#Sta/Elev= 30
  4643.6  451.41  4660.7  450.74  4680.7  450.41  4700.7  449.46  4720.7  448.87
  4740.7  448.56  4770.7  447.69  4810.7  446.18  4840.7  445.50  4860.7  445.24
  4880.7  445.20  4890.7  445.40  4900.7  445.21  4910.7  445.38  4920.7  445.87
  4930.7  445.08  4940.7  445.63  4950.7  445.72  4960.7  445.27  4980.7  444.91
  5008.7  444.73  5009.0  444.23  5012.5  444.23  5012.7  444.73  5020.7  445.24
  5070.7  447.63  5080.7  448.38  5220.7  450.65  5240.7  451.17  5257.0  451.33
#Mann=3,-1,0
  4643.6    0.05       0  5008.7    0.04       0  5012.7    0.05       0
Bank Sta=5008.7,5012.7
Exp/Cntr=0.3,0.1

Type RM Length L Ch R = 1,3027,209,209,209
BEGIN DESCRIPTION:
Lacy 101 1731
END DESCRIPTION:
XS GIS Cut Line= 3
      2742379.98      6865809.82      2742025.83      6865810.02
      2741790.78      6865828.19
#Sta/Elev= 30
  4645.9  448.63  4659.9  448.55  4679.9  448.82  4689.9  447.65  4709.9  446.67
  4759.9  446.40  4789.9  445.71  4809.9  444.89  4839.9  444.20  4909.9  443.76
  4919.9  443.94  4929.9  443.65  4939.9  444.17  4949.9  443.45  4969.9  443.06
  4989.9  443.34  5002.5  443.29  5009.9  442.88  5017.9  442.80  5018.2  442.30
  5021.7  442.30  5021.9  442.80  5070.1  444.38  5130.3  448.16  5140.3  448.19
  5150.3  448.75  5160.4  448.50  5190.4  448.70  5211.4  449.20  5235.8  449.43
#Mann=3,-1,0
  4645.9    0.05       0  5017.9    0.04       0  5021.9    0.05       0
Bank Sta=5017.9,5021.9
Exp/Cntr=0.3,0.1

Type RM Length L Ch R = 1,2818,292,292,292
BEGIN DESCRIPTION:
Lacy 101 1730
END DESCRIPTION:
XS GIS Cut Line= 3
      2742396.23      6865667.34      2742072.71      6865614.15
      2741773.69      6865611.34
#Sta/Elev= 30
  4666.5  447.39  4687.0  447.28  4717.4  447.67  4727.5  447.36  4768.1  447.32
  4778.2  447.12  4795.7  446.69  4818.8  445.53  4869.4  443.62  4923.2  441.88
  4970.8  441.96  4984.5  441.59  5011.1  441.51  5051.1  441.74  5069.1  441.47
  5069.3  440.97  5072.8  440.97  5073.1  441.47  5091.1  442.30  5101.1  442.52
  5131.1  444.04  5161.1  446.01  5171.1  447.15  5181.1  447.39  5211.1  446.92
  5241.1  446.91  5251.1  447.25  5271.1  447.12  5281.1  447.50  5293.4  447.57
#Mann=3,-1,0
  4666.5    0.05       0  5069.1    0.04       0  5073.1    0.05       0
Bank Sta=5069.1,5073.1
Exp/Cntr=0.3,0.1

Type RM Length L Ch R = 1,2526,233,233,233
BEGIN DESCRIPTION:
Lacy 101 1729
END DESCRIPTION:
XS GIS Cut Line= 3
      2742447.18      6865607.93      2742078.03      6865391.31
      2741739.67      6865400.48
#Sta/Elev= 30
  4518.0  446.86  4554.1  446.81  4582.1  446.06  4634.9  447.64  4646.9  447.32
  4656.4  446.33  4715.0  445.23  4736.5  443.99  4816.6  441.17  4912.4  440.69
  4958.0  439.68  4978.1  440.21  4988.1  439.96  4998.1  436.41  5006.1  435.79
  5006.3  435.29  5009.8  435.29  5010.1  435.79  5028.1  439.93  5038.1  440.48
  5078.1  439.85  5088.1  440.17  5108.1  441.37  5128.1  443.56  5162.6  444.42
  5185.9  444.98  5228.1  444.79  5248.2  445.50  5268.2  445.43  5284.5  446.46
#Mann=5,-1,0
  4518.0    0.05       0  5006.1    0.04       0  5010.1    0.05       0
  5162.6    0.12       0  5185.9    0.05       0
Bank Sta=5006.1,5010.1
Exp/Cntr=0.3,0.1

Type RM Length L Ch R = 1,2293,104,104,104
BEGIN DESCRIPTION:
Lacy 101 1728
END DESCRIPTION:
XS GIS Cut Line= 3
      2742591.21      6865184.93      2742022.27      6865190.82
      2741659.58      6865227.43
#Sta/Elev= 30
  4435.9  449.85  4531.1  448.38  4651.1  445.03  4751.1  443.79  4826.0  442.06
  4881.1  440.26  4971.1  439.25  4979.1  433.84  4979.4  433.34  4982.9  433.34
  4983.1  433.84  4991.1  433.84  5021.2  437.38  5031.3  434.83  5056.4  439.32
  5124.0  439.68  5151.4  440.39  5161.9  441.32  5182.0  441.24  5192.1  442.10
  5212.2  441.70  5222.2  442.40  5242.3  442.43  5262.4  443.94  5272.5  443.67
  5282.5  444.73  5302.6  444.50  5312.7  445.35  5332.8  445.12  5369.4  445.89
#Mann=5,-1,0
  4435.9    0.05       0  4826.0    0.12       0  4979.1    0.07       0
  4983.1    0.12       0  5124.0     0.1       0
Bank Sta=4979.1,4983.1
Exp/Cntr=0.3,0.1

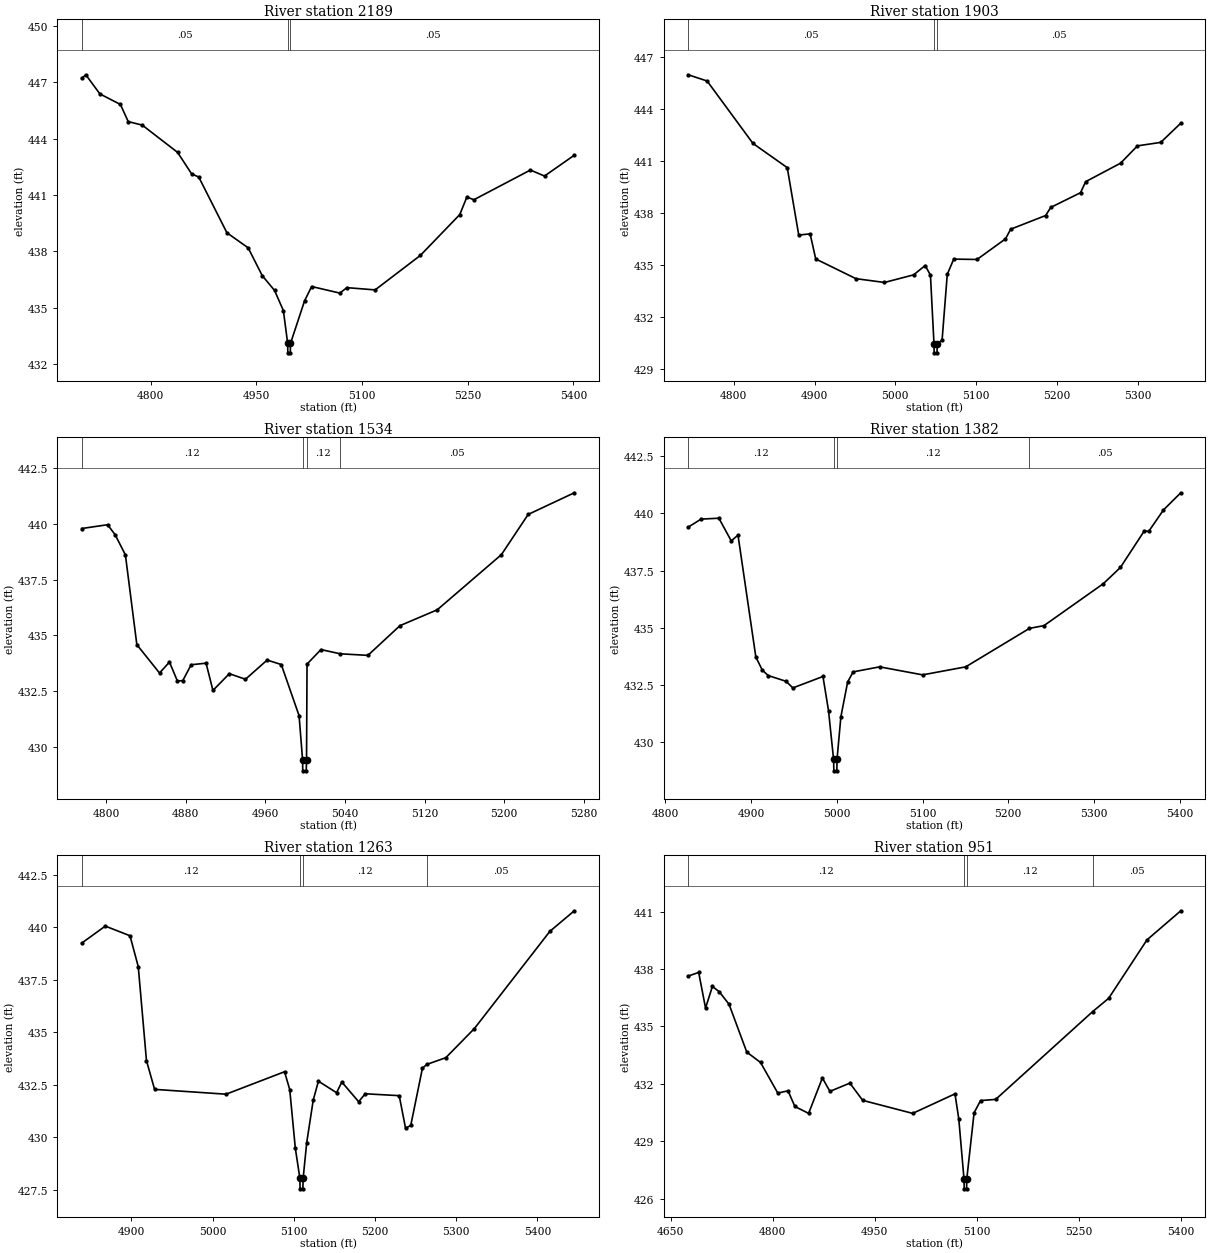
Type RM Length L Ch R = 1,2189,286,286,286
BEGIN DESCRIPTION:
Lacy 101 1711
END DESCRIPTION:
XS GIS Cut Line= 3
      2742321.82      6865073.28      2742024.93      6865086.97
      2741623.73      6865106.83
#Sta/Elev= 30
  4702.3  447.22  4708.1  447.40  4728.1  446.38  4757.2  445.82  4768.2  444.91
  4788.2  444.72  4838.3  443.27  4858.3  442.12  4868.3  441.96  4908.3  438.99
  4938.4  438.19  4958.4  436.71  4975.9  435.92  4988.4  434.85  4994.5  433.10
  4994.7  432.60  4998.2  432.60  4998.5  433.10  5018.5  435.37  5028.5  436.13
  5068.5  435.78  5078.5  436.07  5118.6  435.95  5182.9  437.79  5238.7  439.96
  5248.7  440.89  5258.8  440.75  5338.9  442.33  5358.9  442.01  5401.2  443.12
#Mann=3,-1,0
  4702.3    0.05       0  4994.5    0.05       0  4998.5    0.05       0
Bank Sta=4994.5,4998.5
Exp/Cntr=0.3,0.1

Type RM Length L Ch R = 1,1903,369,369,369
BEGIN DESCRIPTION:
Lacy 101 1712
END DESCRIPTION:
XS GIS Cut Line= 3
      2742039.77      6864711.53      2741850.49      6864892.31
      2741579.51      6865109.80
#Sta/Elev= 30
  4743.8  445.99  4767.2  445.63  4823.9  442.02  4866.3  440.62  4880.5  436.72
  4894.6  436.79  4901.5  435.34  4951.2  434.20  4986.5  433.98  5022.6  434.42
  5036.9  434.96  5043.4  434.40  5047.8  430.41  5048.0  429.91  5051.5  429.91
  5051.8  430.41  5057.8  430.65  5064.2  434.45  5072.2  435.33  5101.0  435.31
  5136.2  436.50  5142.6  437.06  5185.8  437.85  5192.2  438.32  5229.0  439.17
  5235.4  439.81  5278.6  440.88  5299.4  441.88  5328.2  442.08  5353.0  443.19
#Mann=3,-1,0
  4743.8    0.05       0  5047.8    0.05       0  5051.8    0.05       0
Bank Sta=5047.8,5051.8
Exp/Cntr=0.3,0.1

Type RM Length L Ch R = 1,1534,152,152,152
BEGIN DESCRIPTION:
Lacy 101 1710
END DESCRIPTION:
XS GIS Cut Line= 3
      2741690.59      6864580.22      2741598.98      6864789.33
      2741518.05      6865043.67
#Sta/Elev= 30
  4775.4  439.79  4801.4  439.96  4809.0  439.51  4819.3  438.61  4830.8  434.59
  4853.6  433.32  4863.6  433.81  4871.6  432.96  4877.0  432.98  4885.4  433.69
  4900.4  433.76  4907.3  432.54  4923.8  433.29  4940.0  433.04  4961.8  433.90
  4976.0  433.70  4993.9  431.41  4997.4  429.44  4997.6  428.94  5001.1  428.94
  5001.4  429.44  5001.9  433.72  5015.9  434.37  5035.3  434.18  5063.1  434.11
  5095.3  435.44  5132.8  436.15  5197.3  438.62  5224.2  440.42  5270.6  441.39
#Mann=4,-1,0
  4775.4    0.12       0  4997.4    0.07       0  5001.4    0.12       0
  5035.3    0.05       0
Bank Sta=4997.4,5001.4
Exp/Cntr=0.3,0.1

Type RM Length L Ch R = 1,1382,119,119,119
BEGIN DESCRIPTION:
Lacy 101 1714
END DESCRIPTION:
XS GIS Cut Line= 3
      2741693.12      6864536.97      2741526.92      6864671.58
      2741497.79      6865031.13
#Sta/Elev= 30
  4826.6  439.40  4841.6  439.75  4862.4  439.79  4876.8  438.80  4884.7  439.05
  4905.5  433.73  4913.0  433.16  4919.9  432.92  4940.7  432.67  4948.7  432.38
  4983.8  432.88  4990.3  431.38  4996.2  429.26  4996.5  428.76  5000.0  428.76
  5000.2  429.26  5004.7  431.12  5012.6  432.64  5019.0  433.08  5049.9  433.30
  5100.1  432.95  5150.3  433.30  5224.7  434.98  5241.6  435.10  5310.8  436.93
  5330.8  437.64  5358.7  439.24  5363.7  439.21  5381.0  440.15  5401.2  440.90
#Mann=4,-1,0
  4826.6    0.12       0  4996.2    0.07       0  5000.2    0.12       0
  5224.7    0.05       0
Bank Sta=4996.2,5000.2
Exp/Cntr=0.3,0.1

Type RM Length L Ch R = 1,1263,312,312,312
BEGIN DESCRIPTION:
Lacy 101 1713
END DESCRIPTION:
XS GIS Cut Line= 3
      2741684.55      6864509.95      2741525.36      6864537.33
      2741177.46      6864814.74
#Sta/Elev= 30
  4838.9  439.25  4867.9  440.06  4898.3  439.60  4908.5  438.13  4918.6  433.65
  4928.6  432.28  5016.6  432.05  5088.6  433.12  5095.0  432.27  5101.9  429.47
  5107.5  428.04  5107.7  427.54  5111.2  427.54  5111.5  428.04  5115.9  429.74
  5123.9  431.76  5130.3  432.67  5152.7  432.12  5159.1  432.63  5179.9  431.69
  5187.9  432.07  5229.8  431.98  5237.6  430.43  5244.0  430.56  5258.4  433.29
  5263.8  433.47  5287.2  433.79  5322.4  435.18  5415.3  439.81  5445.4  440.79
#Mann=4,-1,0
  4838.9    0.12       0  5107.5    0.07       0  5111.5    0.12       0
  5263.8    0.05       0
Bank Sta=5107.5,5111.5
Exp/Cntr=0.3,0.1

Type RM Length L Ch R = 1,951,0,0,0
BEGIN DESCRIPTION:
Lacy 101 1709
END DESCRIPTION:
XS GIS Cut Line= 3
      2741621.30      6864394.15      2741373.25      6864359.65
      2741167.08      6864785.99
#Sta/Elev= 30
  4675.8  437.63  4691.2  437.82  4701.3  435.96  4711.4  437.09  4721.5  436.81
  4735.8  436.16  4761.9  433.66  4782.1  433.12  4807.5  431.52  4822.5  431.64
  4832.6  430.82  4852.8  430.46  4873.0  432.31  4884.1  431.61  4913.4  432.04
  4932.3  431.14  5005.7  430.46  5067.9  431.48  5073.5  430.17  5081.2  427.02
  5081.5  426.52  5085.0  426.52  5085.2  427.02  5096.0  430.49  5105.5  431.13
  5127.7  431.19  5270.1  435.77  5293.8  436.47  5350.1  439.52  5399.8  441.04
#Mann=4,-1,0
  4675.8    0.12       0  5081.2    0.07       0  5085.2    0.12       0
  5270.1    0.05       0
Bank Sta=5081.2,5085.2
Exp/Cntr=0.3,0.1

Chan Stop Cuts=-1