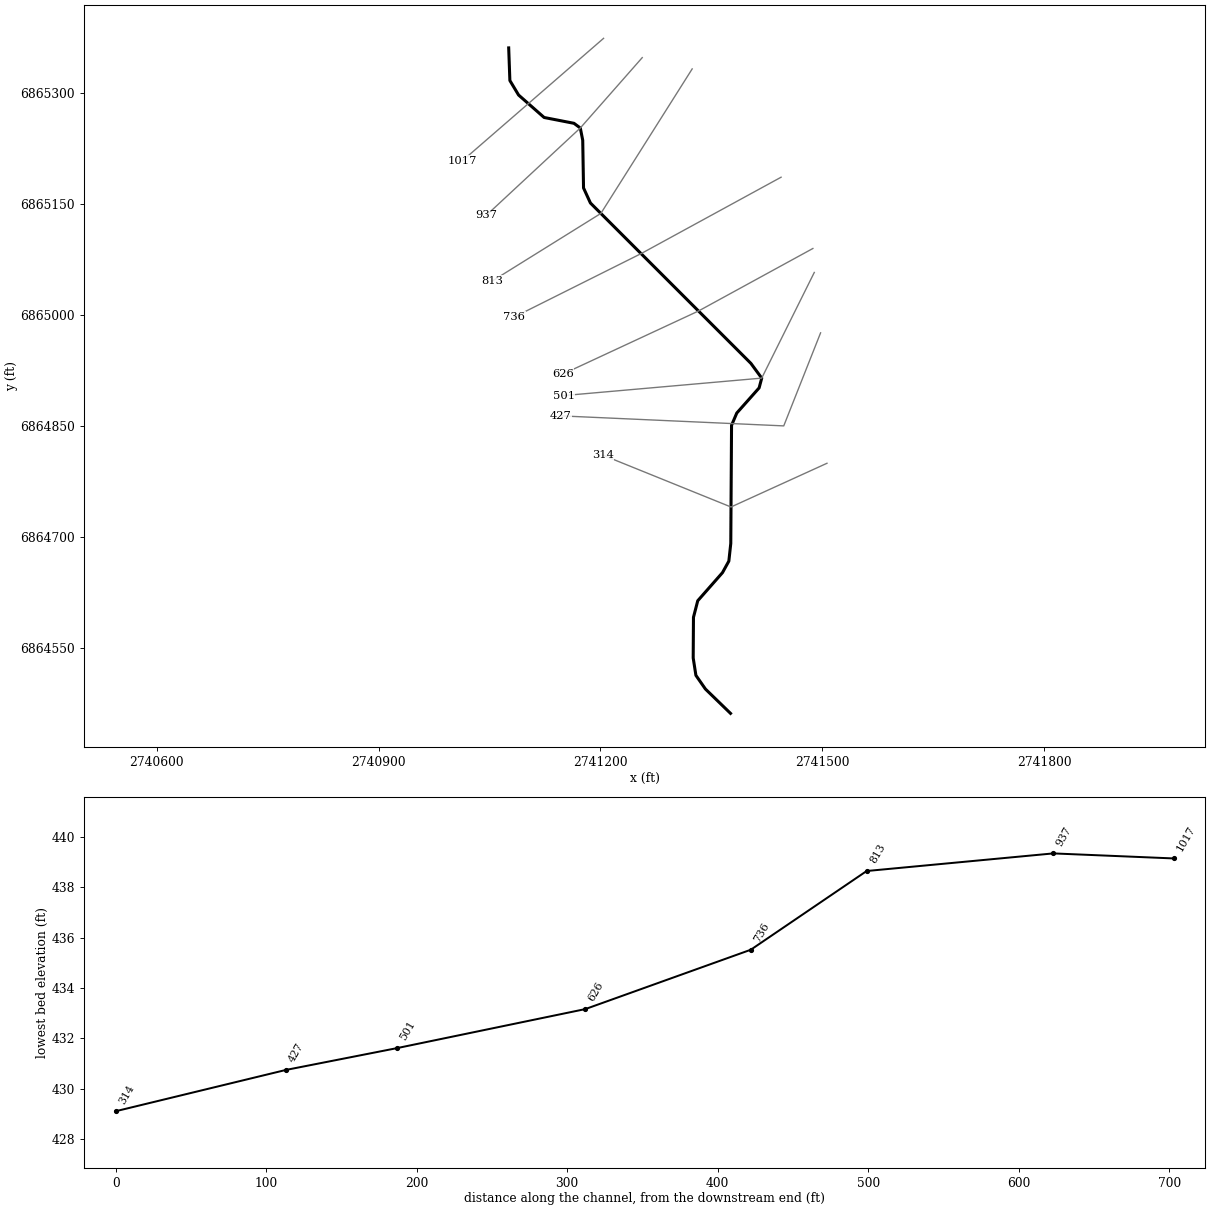
--- Lacy 102.prj (project) ---

Proj Title=Lacy 102 Base Level Engineering
Current Plan=p01
Default Exp/Contr=0.3,0.1
English Units
Geom File=g01
Flow File=f01
Plan File=p01
BEGIN DESCRIPTION:
Lacy 102
END DESCRIPTION:

--- Lacy 102.p01 (plan) ---

Plan Title=Multiple Run
Short Identifier=Multiple
Geom File=g01
Flow File=f01
Subcritical Flow
K Sum by GR= 0
Std Step Tol= 0.01
Critical Tol= 0.01
Num of Std Step Trials= 20
Max Error Tol= 0.3
Flow Tol Ratio= 0.001
Split Flow NTrial= 30
Split Flow Tol= 0.02
Split Flow Ratio= 0.02
Log Output Level= 0
Friction Slope Method= 1
Unsteady Friction Slope Method= 2
Unsteady Bridges Friction Slope Method= 1
Parabolic Critical Depth
Global Vel Dist=  1 , 1 , 1
Global Log Level= 0
CheckData=True
Encroach Param= -1, 0, 0, 0
BEGIN DESCRIPTION:
Multiple Run
END DESCRIPTION:

--- Lacy 102.f01 (steady flow) ---

Flow Title=Multiple
Number of Profiles=7
Profile Names=10-year,25-year,50-year,1pct_min,100-year,1pct_plu,500-year
River Rch & RM= Lacy 102,Reach-1,1017
     121     146     165      93     186     372     236
Boundary for River Rch & Prof#=Lacy 102,Reach-1,1
Up Type=0
Dn Type=3
Dn Slope=0.005
Boundary for River Rch & Prof#=Lacy 102,Reach-1,2
Up Type=0
Dn Type=3
Dn Slope=0.005
Boundary for River Rch & Prof#=Lacy 102,Reach-1,3
Up Type=0
Dn Type=3
Dn Slope=0.005
Boundary for River Rch & Prof#=Lacy 102,Reach-1,4
Up Type=0
Dn Type=3
Dn Slope=0.005
Boundary for River Rch & Prof#=Lacy 102,Reach-1,5
Up Type=0
Dn Type=3
Dn Slope=0.005
Boundary for River Rch & Prof#=Lacy 102,Reach-1,6
Up Type=0
Dn Type=3
Dn Slope=0.005
Boundary for River Rch & Prof#=Lacy 102,Reach-1,7
Up Type=0
Dn Type=3
Dn Slope=0.005

--- Lacy 102.g01 (geometry) ---

Geom Title=Existing Conditions

River Reach=Lacy 102,Reach-1
Reach XY= 23
      2741076.00      6865361.00      2741077.60      6865316.88
      2741089.37      6865297.26      2741123.93      6865266.89
      2741164.27      6865259.03      2741172.84      6865252.68
      2741176.12      6865236.12      2741177.21      6865171.59
      2741186.53      6865151.25      2741403.55      6864934.36
      2741418.21      6864914.42      2741414.67      6864901.16
      2741384.47      6864867.19      2741377.39      6864850.57
      2741376.35      6864690.85      2741373.74      6864666.94
      2741365.14      6864651.35      2741331.68      6864613.32
      2741325.89      6864590.92      2741325.52      6864536.00
      2741329.19      6864512.40      2741342.04      6864493.95
      2741376.00      6864461.00

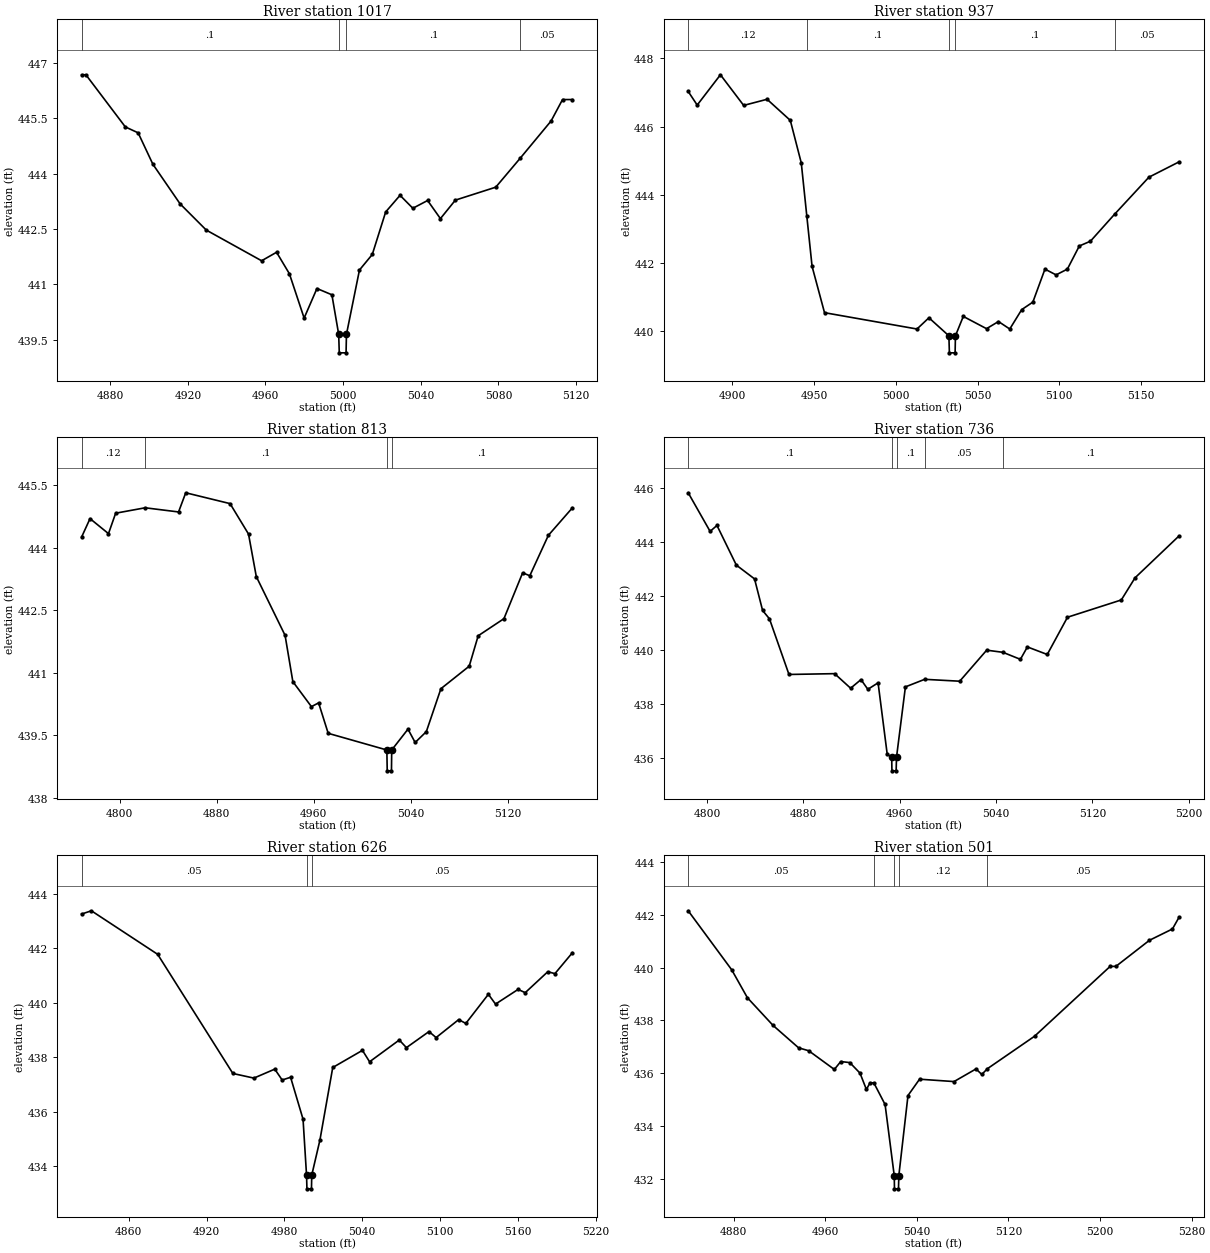
Type RM Length L Ch R = 1,1017,80,80,80
BEGIN DESCRIPTION:
Lacy 102 1722
END DESCRIPTION:
XS GIS Cut Line= 3
      2741204.31      6865373.94      2741102.57      6865285.65
      2741013.34      6865208.29
#Sta/Elev= 30
  4865.3  446.67  4867.5  446.67  4887.8  445.26  4894.4  445.10  4902.0  444.25
  4916.0  443.18  4929.5  442.47  4958.0  441.64  4965.7  441.87  4972.3  441.29
  4979.9  440.09  4986.5  440.89  4994.2  440.72  4997.7  439.65  4998.0  439.15
  5001.5  439.15  5001.7  439.65  5008.4  441.39  5015.0  441.81  5021.9  442.96
  5029.3  443.41  5035.9  443.06  5043.5  443.27  5050.1  442.78  5057.8  443.28
  5078.6  443.63  5091.3  444.42  5107.1  445.42  5113.0  446.00  5118.1  446.00
#Mann=4,-1,0
  4865.3     0.1       0  4997.7    0.07       0  5001.7     0.1       0
  5091.3    0.05       0
Bank Sta=4997.7,5001.7
Exp/Cntr=0.3,0.1

Type RM Length L Ch R = 1,937,124,124,124
BEGIN DESCRIPTION:
Lacy 102 1721
END DESCRIPTION:
XS GIS Cut Line= 3
      2741256.62      6865347.86      2741172.84      6865252.68
      2741046.05      6865134.83
#Sta/Elev= 30
  4873.2  447.03  4878.7  446.63  4892.9  447.52  4907.1  446.62  4921.4  446.80
  4935.6  446.18  4942.3  444.93  4945.7  443.36  4948.9  441.89  4956.5  440.53
  5013.0  440.05  5020.3  440.38  5032.5  439.85  5032.8  439.35  5036.3  439.35
  5036.5  439.85  5041.3  440.42  5055.5  440.06  5062.8  440.27  5069.7  440.05
  5077.0  440.62  5083.8  440.84  5091.2  441.81  5098.0  441.64  5104.9  441.81
  5112.2  442.49  5119.0  442.63  5133.7  443.42  5154.7  444.51  5173.1  444.96
#Mann=5,-1,0
  4873.2    0.12       0  4945.7     0.1       0  5032.5    0.07       0
  5036.5     0.1       0  5133.7    0.05       0
Bank Sta=5032.5,5036.5
Exp/Cntr=0.3,0.1

Type RM Length L Ch R = 1,813,77,77,77
BEGIN DESCRIPTION:
Lacy 102 1720
END DESCRIPTION:
XS GIS Cut Line= 3
      2741324.15      6865332.59      2741200.65      6865137.15
      2741053.86      6865045.79
#Sta/Elev= 30
  4768.8  444.26  4775.7  444.70  4790.9  444.34  4796.8  444.83  4821.1  444.96
  4848.6  444.86  4854.5  445.32  4891.0  445.06  4906.2  444.33  4912.6  443.31
  4936.3  441.90  4942.7  440.79  4958.0  440.19  4963.9  440.28  4971.8  439.55
  5020.1  439.15  5020.4  438.65  5023.9  438.65  5024.1  439.15  5037.5  439.65
  5043.4  439.33  5052.6  439.59  5064.6  440.62  5087.9  441.16  5095.3  441.89
  5116.5  442.30  5131.9  443.40  5137.8  443.33  5153.1  444.30  5172.9  444.96
#Mann=4,-1,0
  4768.8    0.12       0  4821.1     0.1       0  5020.1    0.07       0
  5024.1     0.1       0
Bank Sta=5020.1,5024.1
Exp/Cntr=0.3,0.1

Type RM Length L Ch R = 1,736,110,110,110
BEGIN DESCRIPTION:
Lacy 102 1716
END DESCRIPTION:
XS GIS Cut Line= 3
      2741444.38      6865186.12      2741255.25      6865082.89
      2741083.39      6864996.98
#Sta/Elev= 30
  4784.3  445.82  4802.5  444.39  4808.2  444.61  4824.3  443.14  4839.4  442.63
  4846.1  441.46  4851.8  441.15  4868.0  439.09  4905.9  439.12  4919.2  438.58
  4927.8  438.90  4933.5  438.54  4942.0  438.78  4949.6  436.13  4953.3  436.02
  4953.5  435.52  4957.0  435.52  4957.3  436.02  4964.7  438.63  4980.7  438.91
  5009.8  438.84  5032.2  439.99  5045.7  439.91  5060.2  439.65  5066.0  440.11
  5082.5  439.83  5099.3  441.21  5144.0  441.85  5155.4  442.67  5191.9  444.22
#Mann=5,-1,0
  4784.3     0.1       0  4953.3    0.05       0  4957.3     0.1       0
  4980.7    0.05       0  5045.7     0.1       0
Bank Sta=4953.3,4957.3
Exp/Cntr=0.3,0.1

Type RM Length L Ch R = 1,626,125,125,125
BEGIN DESCRIPTION:
Lacy 102 1715
END DESCRIPTION:
XS GIS Cut Line= 3
      2741487.40      6865089.73      2741332.70      6865005.17
      2741149.44      6864919.96
#Sta/Elev= 30
  4823.7  443.26  4831.2  443.38  4882.3  441.78  4940.3  437.40  4956.5  437.23
  4972.6  437.56  4978.3  437.16  4984.8  437.26  4994.4  435.72  4997.1  433.66
  4997.4  433.16  5000.9  433.16  5001.1  433.66  5007.4  434.95  5017.3  437.62
  5040.2  438.25  5045.7  437.83  5068.6  438.63  5074.1  438.35  5091.5  438.94
  5097.0  438.72  5114.4  439.38  5119.9  439.24  5137.3  440.31  5142.8  439.95
  5160.2  440.49  5165.7  440.37  5183.1  441.14  5188.6  441.07  5202.1  441.84
#Mann=3,-1,0
  4823.7    0.05       0  4997.1    0.05       0  5001.1    0.05       0
Bank Sta=4997.1,5001.1
Exp/Cntr=0.3,0.1

Type RM Length L Ch R = 1,501,74,74,74
BEGIN DESCRIPTION:
Lacy 102 1718
END DESCRIPTION:
XS GIS Cut Line= 3
      2741489.28      6865057.32      2741418.21      6864914.42
      2741150.35      6864890.79
#Sta/Elev= 30
  4840.4  442.16  4878.4  439.92  4892.1  438.86  4914.5  437.81  4936.8  436.96
  4945.6  436.85  4968.0  436.14  4973.6  436.44  4981.5  436.40  4990.4  436.00
  4996.0  435.38  4999.1  435.63  5002.5  435.63  5012.3  434.81  5020.3  432.11
  5020.5  431.61  5024.0  431.61  5024.3  432.11  5032.3  435.15  5042.4  435.77
  5072.5  435.68  5091.7  436.16  5096.7  435.95  5101.7  436.17  5142.8  437.40
  5208.8  440.05  5213.8  440.05  5243.1  441.04  5263.2  441.47  5268.9  441.91
#Mann=5,-1,0
  4840.4    0.05       0  5002.5    0.12       0  5020.3    0.04       0
  5024.3    0.12       0  5101.7    0.05       0
Bank Sta=5020.3,5024.3
Exp/Cntr=0.3,0.1

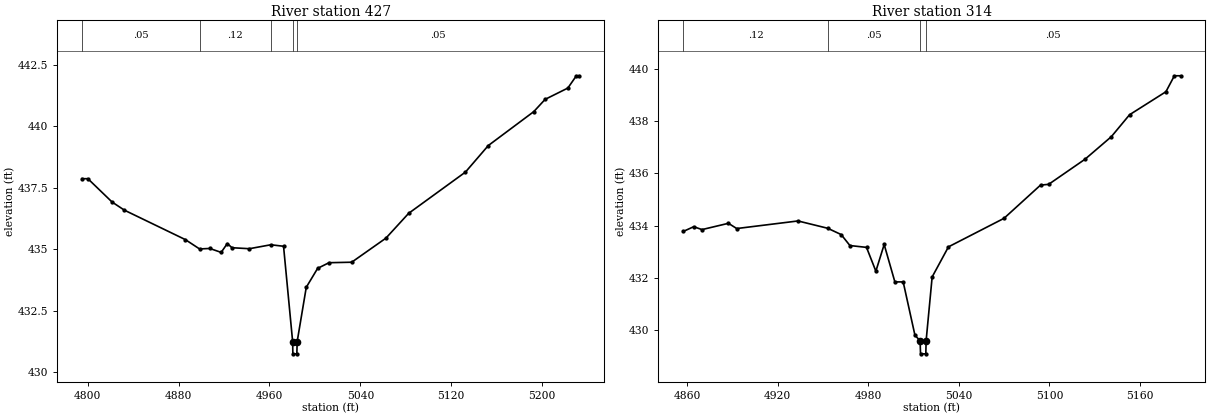
Type RM Length L Ch R = 1,427,113,113,113
BEGIN DESCRIPTION:
Lacy 102 1719
END DESCRIPTION:
XS GIS Cut Line= 3
      2741497.81      6864975.63      2741447.99      6864849.80
      2741146.03      6864863.37
#Sta/Elev= 30
  4795.0  437.87  4800.2  437.87  4821.5  436.92  4832.3  436.59  4886.0  435.39
  4898.5  435.01  4907.5  435.03  4917.5  434.87  4922.9  435.23  4927.0  435.06
  4942.3  435.02  4961.2  435.18  4972.4  435.12  4980.4  431.24  4980.6  430.74
  4984.1  430.74  4984.4  431.24  4992.4  433.45  5002.4  434.22  5012.4  434.45
  5032.4  434.47  5062.5  435.45  5082.5  436.46  5132.5  438.14  5152.6  439.22
  5192.6  440.60  5202.6  441.10  5222.6  441.56  5230.1  442.06  5232.6  442.06
#Mann=5,-1,0
  4795.0    0.05       0  4898.5    0.12       0  4961.2    0.05       0
  4980.4    0.04       0  4984.4    0.05       0
Bank Sta=4980.4,4984.4
Exp/Cntr=0.3,0.1

Type RM Length L Ch R = 1,314,0,0,0
BEGIN DESCRIPTION:
Lacy 102 1717
END DESCRIPTION:
XS GIS Cut Line= 3
      2741506.44      6864799.24      2741376.67      6864740.11
      2741203.41      6864810.19
#Sta/Elev= 30
  4857.4  433.78  4864.3  433.96  4869.8  433.85  4887.3  434.09  4892.8  433.89
  4933.4  434.18  4953.1  433.90  4962.0  433.66  4967.8  433.24  4978.8  433.17
  4985.0  432.26  4990.5  433.28  4997.6  431.85  5003.1  431.85  5010.9  429.81
  5014.3  429.60  5014.6  429.10  5018.1  429.10  5018.3  429.60  5022.3  432.04
  5033.1  433.19  5069.9  434.28  5094.1  435.55  5099.5  435.58  5123.6  436.54
  5141.0  437.40  5153.1  438.24  5177.2  439.12  5182.8  439.73  5186.9  439.73
#Mann=4,-1,0
  4857.4    0.12       0  4953.1    0.05       0  5014.3    0.04       0
  5018.3    0.05       0
Bank Sta=5014.3,5018.3
Exp/Cntr=0.3,0.1

Chan Stop Cuts=-1