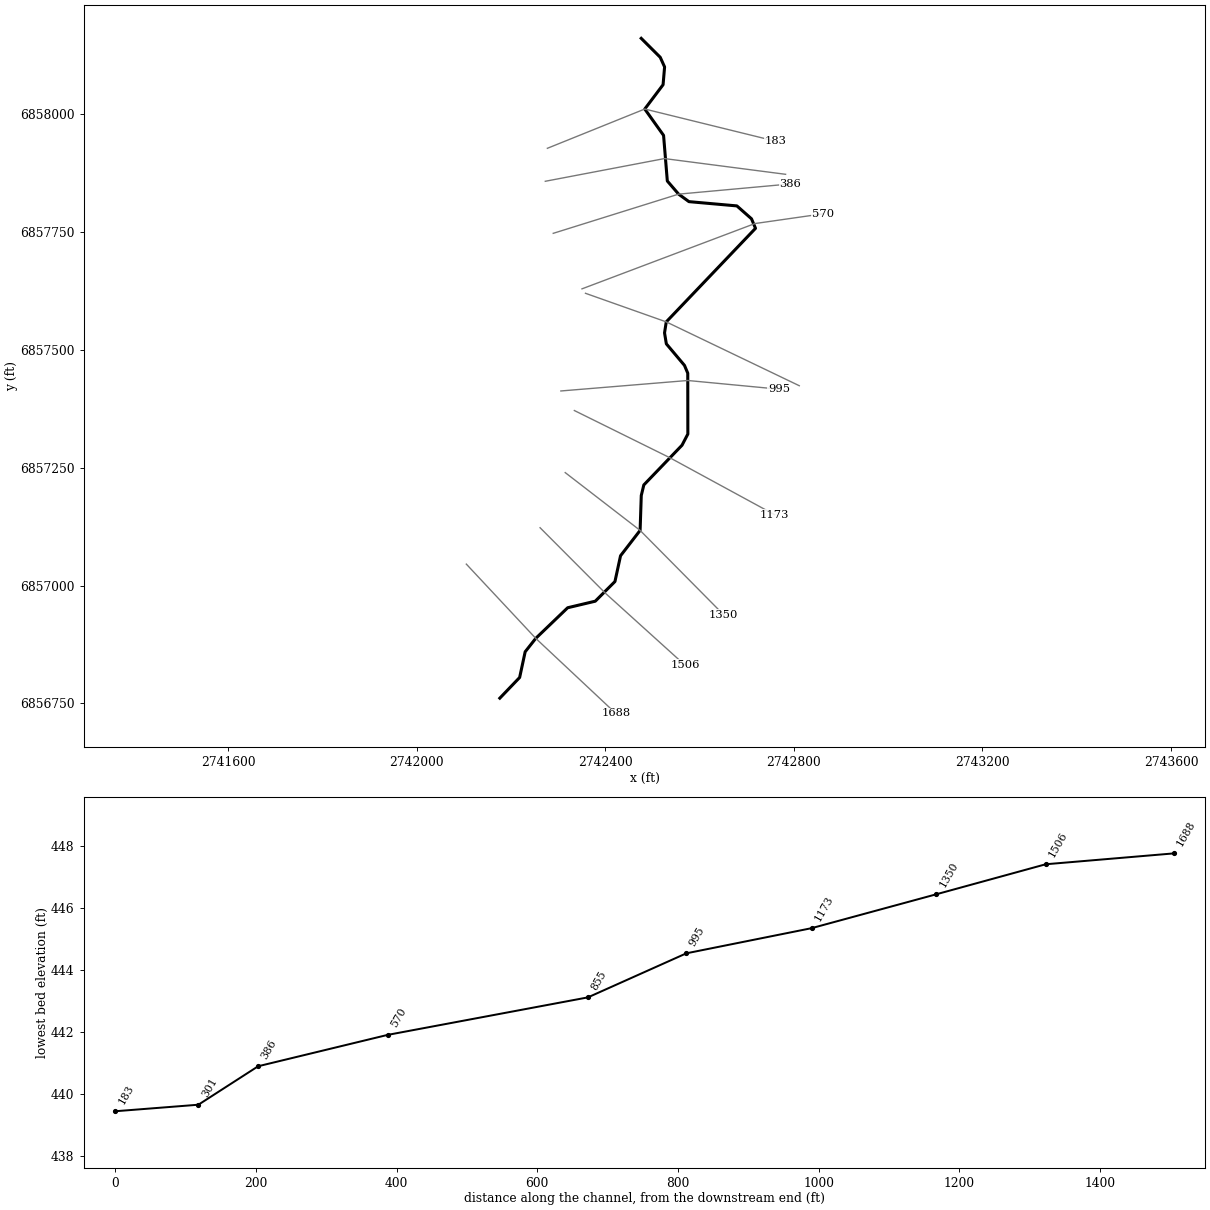
--- Lacy 104.prj (project) ---

Proj Title=Lacy 104 Base Level Engineering
Current Plan=p01
Default Exp/Contr=0.3,0.1
English Units
Geom File=g01
Flow File=f01
Plan File=p01
BEGIN DESCRIPTION:
Lacy 104
END DESCRIPTION:

--- Lacy 104.p01 (plan) ---

Plan Title=Multiple Run
Short Identifier=Multiple
Geom File=g01
Flow File=f01
Subcritical Flow
K Sum by GR= 0
Std Step Tol= 0.01
Critical Tol= 0.01
Num of Std Step Trials= 20
Max Error Tol= 0.3
Flow Tol Ratio= 0.001
Split Flow NTrial= 30
Split Flow Tol= 0.02
Split Flow Ratio= 0.02
Log Output Level= 0
Friction Slope Method= 1
Unsteady Friction Slope Method= 2
Unsteady Bridges Friction Slope Method= 1
Parabolic Critical Depth
Global Vel Dist=  1 , 1 , 1
Global Log Level= 0
CheckData=True
Encroach Param= -1, 0, 0, 0
BEGIN DESCRIPTION:
Multiple Run
END DESCRIPTION:

--- Lacy 104.f01 (steady flow) ---

Flow Title=Multiple
Number of Profiles=7
Profile Names=10-year,25-year,50-year,1pct_min,100-year,1pct_plu,500-year
River Rch & RM= Lacy 104,Reach-1,1688
     208     261     302     174     347     693     460
Boundary for River Rch & Prof#=Lacy 104,Reach-1,1
Up Type=0
Dn Type=3
Dn Slope=0.005
Boundary for River Rch & Prof#=Lacy 104,Reach-1,2
Up Type=0
Dn Type=3
Dn Slope=0.005
Boundary for River Rch & Prof#=Lacy 104,Reach-1,3
Up Type=0
Dn Type=3
Dn Slope=0.005
Boundary for River Rch & Prof#=Lacy 104,Reach-1,4
Up Type=0
Dn Type=3
Dn Slope=0.005
Boundary for River Rch & Prof#=Lacy 104,Reach-1,5
Up Type=0
Dn Type=3
Dn Slope=0.005
Boundary for River Rch & Prof#=Lacy 104,Reach-1,6
Up Type=0
Dn Type=3
Dn Slope=0.005
Boundary for River Rch & Prof#=Lacy 104,Reach-1,7
Up Type=0
Dn Type=3
Dn Slope=0.005

--- Lacy 104.g01 (geometry) ---

Geom Title=Existing Conditions

River Reach=Lacy 104,Reach-1
Reach XY= 30
      2742176.00      6856761.00      2742218.06      6856804.86
      2742229.80      6856859.43      2742252.26      6856887.89
      2742319.95      6856952.84      2742378.54      6856966.75
      2742420.27      6857008.45      2742432.15      6857063.15
      2742473.67      6857116.97      2742476.13      6857190.95
      2742481.54      6857213.42      2742562.60      6857297.70
      2742574.96      6857321.44      2742574.77      6857450.50
      2742567.81      6857467.07      2742529.34      6857512.75
      2742525.50      6857536.04      2742529.13      6857559.37
      2742718.50      6857757.87      2742710.00      6857778.12
      2742679.00      6857805.47      2742577.26      6857814.51
      2742555.36      6857830.43      2742531.40      6857858.29
      2742523.44      6857955.10      2742483.56      6858011.01
      2742522.40      6858062.58      2742525.61      6858100.32
      2742516.36      6858120.79      2742476.00      6858161.00

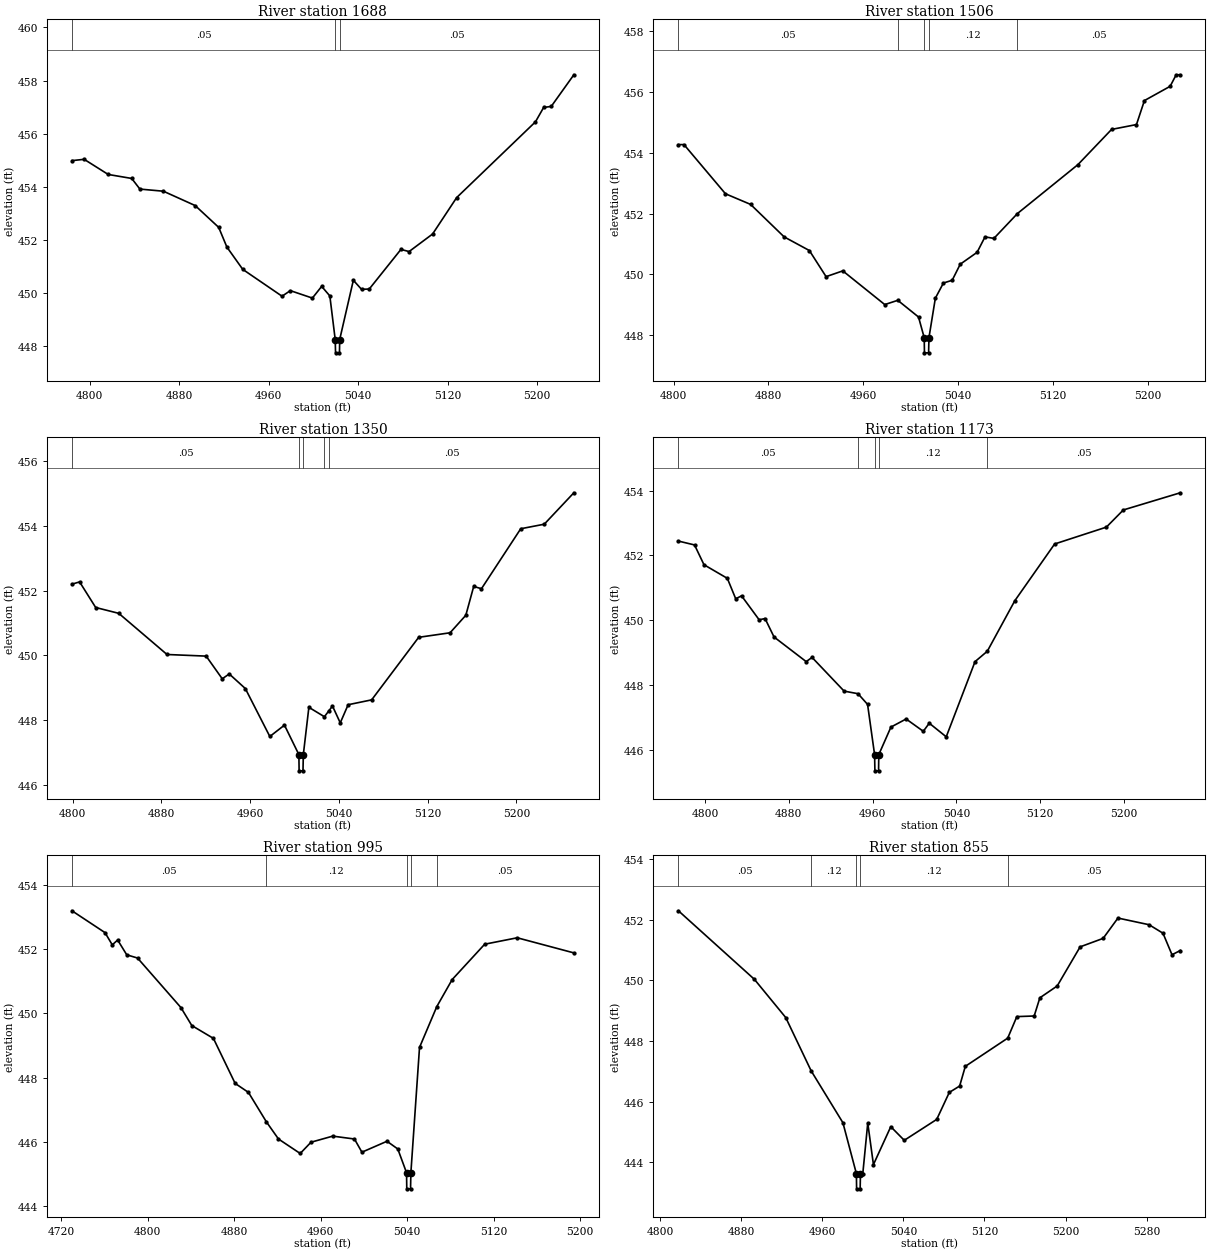
Type RM Length L Ch R = 1,1688,182,182,182
BEGIN DESCRIPTION:
Lacy 104 1794
END DESCRIPTION:
XS GIS Cut Line= 3
      2742104.93      6857045.44      2742252.26      6856887.89
      2742422.02      6856728.73
#Sta/Elev= 30
  4784.3  454.99  4795.2  455.04  4816.7  454.47  4837.7  454.32  4845.0  453.92
  4866.0  453.84  4894.4  453.30  4915.4  452.48  4922.7  451.74  4936.9  450.90
  4972.0  449.89  4979.4  450.10  4999.1  449.82  5007.4  450.26  5014.7  449.90
  5019.5  448.26  5019.8  447.76  5023.3  447.76  5023.5  448.26  5035.7  450.49
  5043.0  450.15  5049.9  450.16  5078.2  451.65  5085.5  451.57  5106.5  452.23
  5128.0  453.60  5198.4  456.45  5205.7  456.99  5212.5  457.03  5232.7  458.22
#Mann=3,-1,0
  4784.3    0.05       0  5019.5    0.04       0  5023.5    0.05       0
Bank Sta=5019.5,5023.5
Exp/Cntr=0.3,0.1

Type RM Length L Ch R = 1,1506,156,156,156
BEGIN DESCRIPTION:
Lacy 104 1795
END DESCRIPTION:
XS GIS Cut Line= 3
      2742261.42      6857122.63      2742399.84      6856983.86
      2742568.60      6856831.29
#Sta/Elev= 30
  4804.0  454.27  4808.7  454.27  4843.7  452.65  4864.9  452.30  4893.2  451.23
  4914.5  450.78  4928.6  449.92  4942.7  450.11  4978.1  449.00  4989.1  449.14
  5006.6  448.59  5011.4  447.91  5011.6  447.41  5015.1  447.41  5015.4  447.91
  5020.8  449.21  5027.6  449.71  5035.0  449.80  5041.8  450.33  5056.0  450.72
  5062.7  451.23  5070.2  451.18  5090.1  452.00  5141.1  453.61  5169.5  454.77
  5190.5  454.93  5197.2  455.72  5218.9  456.19  5224.0  456.57  5227.5  456.57
#Mann=5,-1,0
  4804.0    0.05       0  4989.1    0.12       0  5011.4    0.07       0
  5015.4    0.12       0  5090.1    0.05       0
Bank Sta=5011.4,5015.4
Exp/Cntr=0.3,0.1

Type RM Length L Ch R = 1,1350,177,177,177
BEGIN DESCRIPTION:
Lacy 104 1796
END DESCRIPTION:
XS GIS Cut Line= 3
      2742314.77      6857239.57      2742473.67      6857116.97
      2742650.83      6856938.04
#Sta/Elev= 30
  4799.3  452.20  4806.2  452.27  4820.7  451.48  4841.5  451.30  4885.0  450.03
  4920.3  449.98  4934.8  449.28  4941.1  449.43  4955.6  448.98  4977.7  447.50
  4990.9  447.85  5003.9  446.94  5004.1  446.44  5007.6  446.44  5007.9  446.94
  5012.9  448.40  5026.9  448.11  5031.1  448.30  5034.2  448.44  5041.2  447.92
  5048.3  448.48  5069.5  448.63  5111.9  450.56  5140.2  450.70  5154.4  451.24
  5161.5  452.13  5168.5  452.06  5203.9  453.91  5225.1  454.05  5251.8  455.02
#Mann=5,-1,0
  4799.3    0.05       0  5003.9    0.04       0  5007.9    0.05       0
  5026.9    0.12       0  5031.1    0.05       0
Bank Sta=5003.9,5007.9
Exp/Cntr=0.3,0.1

Type RM Length L Ch R = 1,1173,178,178,178
BEGIN DESCRIPTION:
Lacy 104 1793
END DESCRIPTION:
XS GIS Cut Line= 3
      2742334.13      6857371.31      2742536.20      6857271.44
      2742759.16      6857150.19
#Sta/Elev= 30
  4774.6  452.44  4790.0  452.32  4799.0  451.71  4821.3  451.29  4829.3  450.66
  4834.9  450.75  4851.7  450.01  4857.3  450.05  4865.9  449.48  4896.6  448.72
  4902.2  448.85  4932.8  447.81  4946.1  447.73  4955.2  447.40  4961.9  445.85
  4962.2  445.35  4965.7  445.35  4965.9  445.85  4977.5  446.70  4992.0  446.95
  5008.4  446.57  5014.1  446.82  5030.3  446.40  5057.8  448.72  5069.5  449.04
  5095.8  450.60  5133.8  452.35  5183.2  452.87  5199.4  453.40  5253.8  453.93
#Mann=5,-1,0
  4774.6    0.05       0  4946.1    0.12       0  4961.9    0.07       0
  4965.9    0.12       0  5069.5    0.05       0
Bank Sta=4961.9,4965.9
Exp/Cntr=0.3,0.1

Type RM Length L Ch R = 1,995,140,140,140
BEGIN DESCRIPTION:
Lacy 104 1792
END DESCRIPTION:
XS GIS Cut Line= 3
      2742305.51      6857412.80      2742574.80      6857435.02
      2742768.12      6857416.62
#Sta/Elev= 30
  4729.8  453.19  4760.4  452.51  4767.1  452.13  4772.1  452.28  4780.5  451.82
  4790.5  451.72  4830.6  450.18  4840.7  449.62  4860.7  449.22  4880.8  447.82
  4893.1  447.54  4909.6  446.63  4920.9  446.09  4941.0  445.64  4951.0  445.99
  4971.1  446.18  4991.2  446.09  4998.1  445.68  5021.3  446.02  5031.3  445.78
  5039.4  445.04  5039.6  444.54  5043.1  444.54  5043.4  445.04  5051.4  448.94
  5067.4  450.21  5081.6  451.05  5111.7  452.15  5141.8  452.35  5194.2  451.88
#Mann=5,-1,0
  4729.8    0.05       0  4909.6    0.12       0  5039.4    0.07       0
  5043.4    0.12       0  5067.4    0.05       0
Bank Sta=5039.4,5043.4
Exp/Cntr=0.3,0.1

Type RM Length L Ch R = 1,855,285,285,285
BEGIN DESCRIPTION:
Lacy 104 1791
END DESCRIPTION:
XS GIS Cut Line= 3
      2742357.75      6857620.04      2742529.13      6857559.37
      2742811.41      6857423.90
#Sta/Elev= 30
  4818.2  452.29  4893.1  450.03  4924.0  448.77  4949.1  447.01  4980.4  445.30
  4993.7  443.62  4993.9  443.12  4997.4  443.12  4997.7  443.62  5000.0  443.62
  5004.9  445.29  5010.5  443.92  5027.6  445.17  5040.9  444.72  5072.9  445.41
  5085.3  446.30  5095.5  446.51  5101.1  447.16  5142.9  448.09  5151.9  448.80
  5169.0  448.82  5174.6  449.42  5191.7  449.81  5214.3  451.10  5237.0  451.38
  5251.6  452.05  5282.3  451.83  5296.0  451.55  5304.9  450.84  5313.1  450.98
#Mann=5,-1,0
  4818.2    0.05       0  4949.1    0.12       0  4993.7    0.07       0
  4997.7    0.12       0  5142.9    0.05       0
Bank Sta=4993.7,4997.7
Exp/Cntr=0.3,0.1

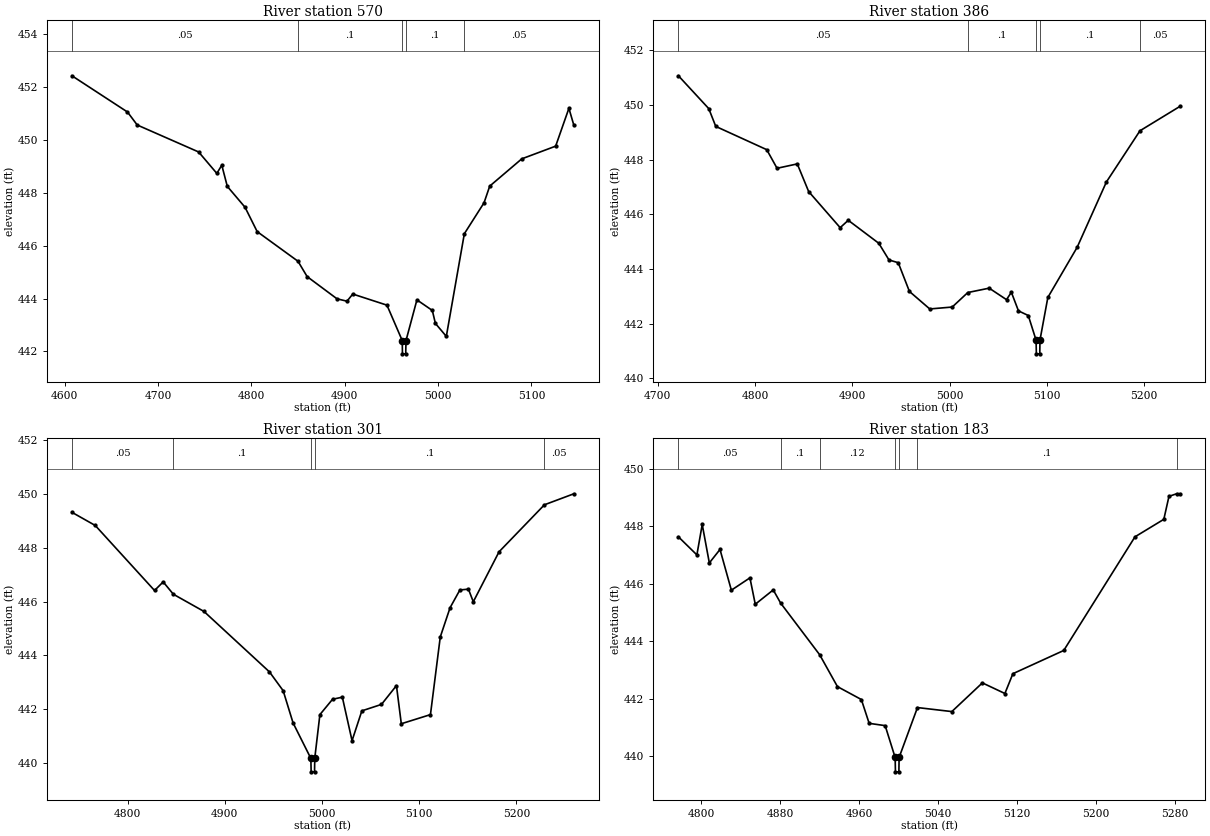
Type RM Length L Ch R = 1,570,184,184,184
BEGIN DESCRIPTION:
Lacy 104 1789
END DESCRIPTION:
XS GIS Cut Line= 3
      2742350.36      6857629.48      2742717.18      6857767.99
      2742861.21      6857788.64
#Sta/Elev= 30
  4607.9  452.42  4667.4  451.05  4677.8  450.56  4743.6  449.54  4763.1  448.73
  4768.4  449.04  4774.3  448.24  4793.3  447.45  4806.3  446.53  4850.0  445.41
  4859.8  444.83  4891.8  443.99  4902.5  443.90  4908.7  444.17  4945.3  443.75
  4961.7  442.41  4961.9  441.91  4965.4  441.91  4965.7  442.41  4977.4  443.95
  4993.9  443.55  4997.2  443.06  5008.9  442.57  5028.2  446.45  5049.3  447.62
  5055.4  448.25  5089.7  449.28  5126.0  449.76  5140.2  451.19  5145.5  450.55
#Mann=5,-1,0
  4607.9    0.05       0  4850.0     0.1       0  4961.7    0.07       0
  4965.7     0.1       0  5028.2    0.05       0
Bank Sta=4961.7,4965.7
Exp/Cntr=0.3,0.1

Type RM Length L Ch R = 1,386,85,85,85
BEGIN DESCRIPTION:
Lacy 104 1790
END DESCRIPTION:
XS GIS Cut Line= 3
      2742289.36      6857747.28      2742555.36      6857830.43
      2742791.68      6857851.99
#Sta/Elev= 30
  4721.3  451.06  4752.5  449.86  4759.7  449.21  4812.1  448.36  4822.7  447.68
  4843.5  447.84  4855.2  446.83  4887.6  445.51  4895.9  445.78  4927.3  444.94
  4937.8  444.33  4947.3  444.23  4958.8  443.18  4979.7  442.54  5002.8  442.61
  5018.8  443.14  5040.8  443.30  5058.6  442.88  5063.6  443.15  5070.9  442.47
  5081.0  442.30  5089.0  441.40  5089.3  440.90  5092.8  440.90  5093.0  441.40
  5101.1  442.96  5131.2  444.79  5161.3  447.18  5195.8  449.05  5237.3  449.95
#Mann=5,-1,0
  4721.3    0.05       0  5018.8     0.1       0  5089.0    0.04       0
  5093.0     0.1       0  5195.8    0.05       0
Bank Sta=5089,5093
Exp/Cntr=0.3,0.1

Type RM Length L Ch R = 1,301,118,118,118
BEGIN DESCRIPTION:
Lacy 104 1788
END DESCRIPTION:
XS GIS Cut Line= 3
      2742272.47      6857857.71      2742525.32      6857905.89
      2742782.36      6857872.51
#Sta/Elev= 30
  4742.6  449.32  4766.6  448.83  4827.6  446.41  4836.5  446.73  4847.0  446.27
  4878.5  445.63  4945.9  443.38  4960.0  442.68  4970.2  441.48  4988.5  440.16
  4988.8  439.66  4992.3  439.66  4992.5  440.16  4997.8  441.79  5010.8  442.36
  5020.9  442.44  5030.9  440.82  5041.0  441.93  5061.2  442.17  5076.6  442.87
  5081.6  441.45  5111.6  441.79  5121.7  444.68  5131.8  445.77  5141.9  446.43
  5150.7  446.46  5155.7  445.99  5182.2  447.85  5228.9  449.60  5259.2  450.01
#Mann=5,-1,0
  4742.6    0.05       0  4847.0     0.1       0  4988.5    0.07       0
  4992.5     0.1       0  5228.9    0.05       0
Bank Sta=4988.5,4992.5
Exp/Cntr=0.3,0.1

Type RM Length L Ch R = 1,183,0,0,0
BEGIN DESCRIPTION:
Lacy 104 1787
END DESCRIPTION:
XS GIS Cut Line= 3
      2742276.93      6857927.69      2742483.56      6858011.01
      2742760.60      6857942.85
#Sta/Elev= 30
  4777.2  447.64  4795.9  447.01  4801.3  448.07  4808.5  446.73  4819.3  447.20
  4830.8  445.78  4849.6  446.21  4855.0  445.29  4873.2  445.79  4880.7  445.33
  4920.2  443.53  4938.2  442.42  4962.4  441.97  4970.3  441.14  4986.5  441.06
  4996.6  439.95  4996.9  439.45  5000.4  439.45  5000.6  439.95  5019.2  441.69
  5054.0  441.55  5084.9  442.55  5107.7  442.18  5115.8  442.87  5167.3  443.68
  5239.4  447.64  5268.6  448.25  5273.8  449.05  5281.5  449.14  5285.3  449.14
#Mann=7,-1,0
  4777.2    0.05       0  4880.7     0.1       0  4920.2    0.12       0
  4996.6    0.07       0  5000.6    0.12       0  5019.2     0.1       0
  5281.5    0.05       0
Bank Sta=4996.6,5000.6
Exp/Cntr=0.3,0.1

Chan Stop Cuts=-1