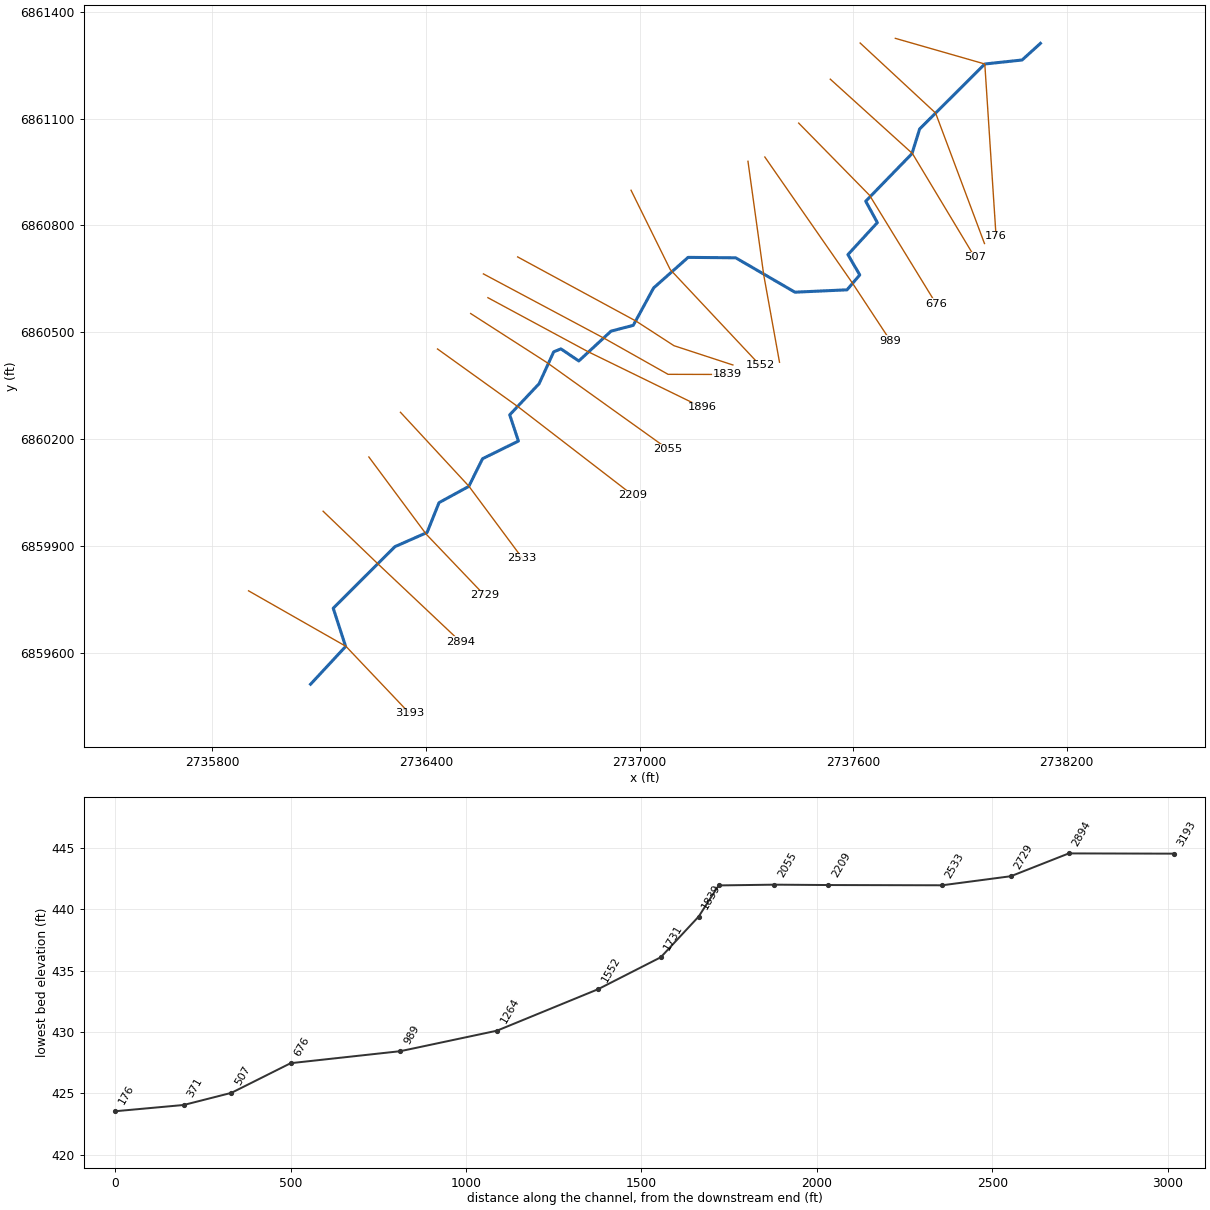
--- Lacy 106.prj (project) ---

Proj Title=Lacy 106 Base Level Engineering
Current Plan=p01
Default Exp/Contr=0.3,0.1
English Units
Geom File=g01
Flow File=f01
Plan File=p01
Y Axis Title=Elevation
X Axis Title(PF)=Main Channel Distance
X Axis Title(XS)=Station
BEGIN DESCRIPTION:
Lacy 106
END DESCRIPTION:
DSS Export Rating Curves= 0
DSS Export Rating Curve Sorted= 0
DSS Export Volume Flow Curves= 0
DXF OffsetX= 0
DXF OffsetY= 0
DXF ScaleX= 1
DXF ScaleY= 10

--- Lacy 106.p01 (plan) ---

Plan Title=Multiple Run
Short Identifier=Multiple
Geom File=g01
Flow File=f01
Subcritical Flow
K Sum by GR= 0
Std Step Tol= 0.01
Critical Tol= 0.01
Num of Std Step Trials= 20
Max Error Tol= 0.3
Flow Tol Ratio= 0.001
Split Flow NTrial= 30
Split Flow Tol= 0.02
Split Flow Ratio= 0.02
Log Output Level= 0
Friction Slope Method= 1
Unsteady Friction Slope Method= 2
Unsteady Bridges Friction Slope Method= 1
Parabolic Critical Depth
Global Vel Dist=  1 , 1 , 1
Global Log Level= 0
CheckData=True
Encroach Param= -1, 0, 0, 0
BEGIN DESCRIPTION:
Multiple Run
END DESCRIPTION:

--- Lacy 106.f01 (steady flow) ---

Flow Title=Multiple
Number of Profiles=7
Profile Names=10-year,25-year,50-year,1pct_min,100-year,1pct_plu,500-year
River Rch & RM= Lacy 106,Reach-1,3193
     426     558     662     391     780    1555    1078
Boundary for River Rch & Prof#=Lacy 106,Reach-1,1
Up Type=0
Dn Type=3
Dn Slope=0.005
Boundary for River Rch & Prof#=Lacy 106,Reach-1,2
Up Type=0
Dn Type=3
Dn Slope=0.005
Boundary for River Rch & Prof#=Lacy 106,Reach-1,3
Up Type=0
Dn Type=3
Dn Slope=0.005
Boundary for River Rch & Prof#=Lacy 106,Reach-1,4
Up Type=0
Dn Type=3
Dn Slope=0.005
Boundary for River Rch & Prof#=Lacy 106,Reach-1,5
Up Type=0
Dn Type=3
Dn Slope=0.005
Boundary for River Rch & Prof#=Lacy 106,Reach-1,6
Up Type=0
Dn Type=3
Dn Slope=0.005
Boundary for River Rch & Prof#=Lacy 106,Reach-1,7
Up Type=0
Dn Type=3
Dn Slope=0.005

--- Lacy 106.g01 (geometry) ---

Geom Title=Existing Conditions
Program Version=4.10

River Reach=Lacy 106        ,Reach-1
Reach XY= 30
        2736076.        6859511.       2736174.4      6859617.04
      2736139.54      6859724.38       2736312.8      6859897.36
      2736403.14      6859937.17      2736436.71      6860020.96
      2736520.34      6860066.66      2736559.01      6860144.42
      2736659.76      6860193.96      2736635.32      6860267.65
       2736717.8      6860354.99      2736758.96      6860444.76
      2736779.15      6860452.92      2736829.32      6860419.02
      2736919.97       6860502.8      2736982.33      6860519.04
      2737039.62      6860624.23      2737136.43      6860709.97
      2737270.07      6860708.77       2737436.5      6860612.19
      2737582.82      6860618.81      2737618.54      6860660.75
      2737585.34      6860717.66      2737667.97      6860807.67
       2737635.3      6860867.67      2737765.22      6861001.32
      2737786.78      6861070.68      2737969.82      6861253.16
      2738074.59      6861264.39        2738126.        6861311.

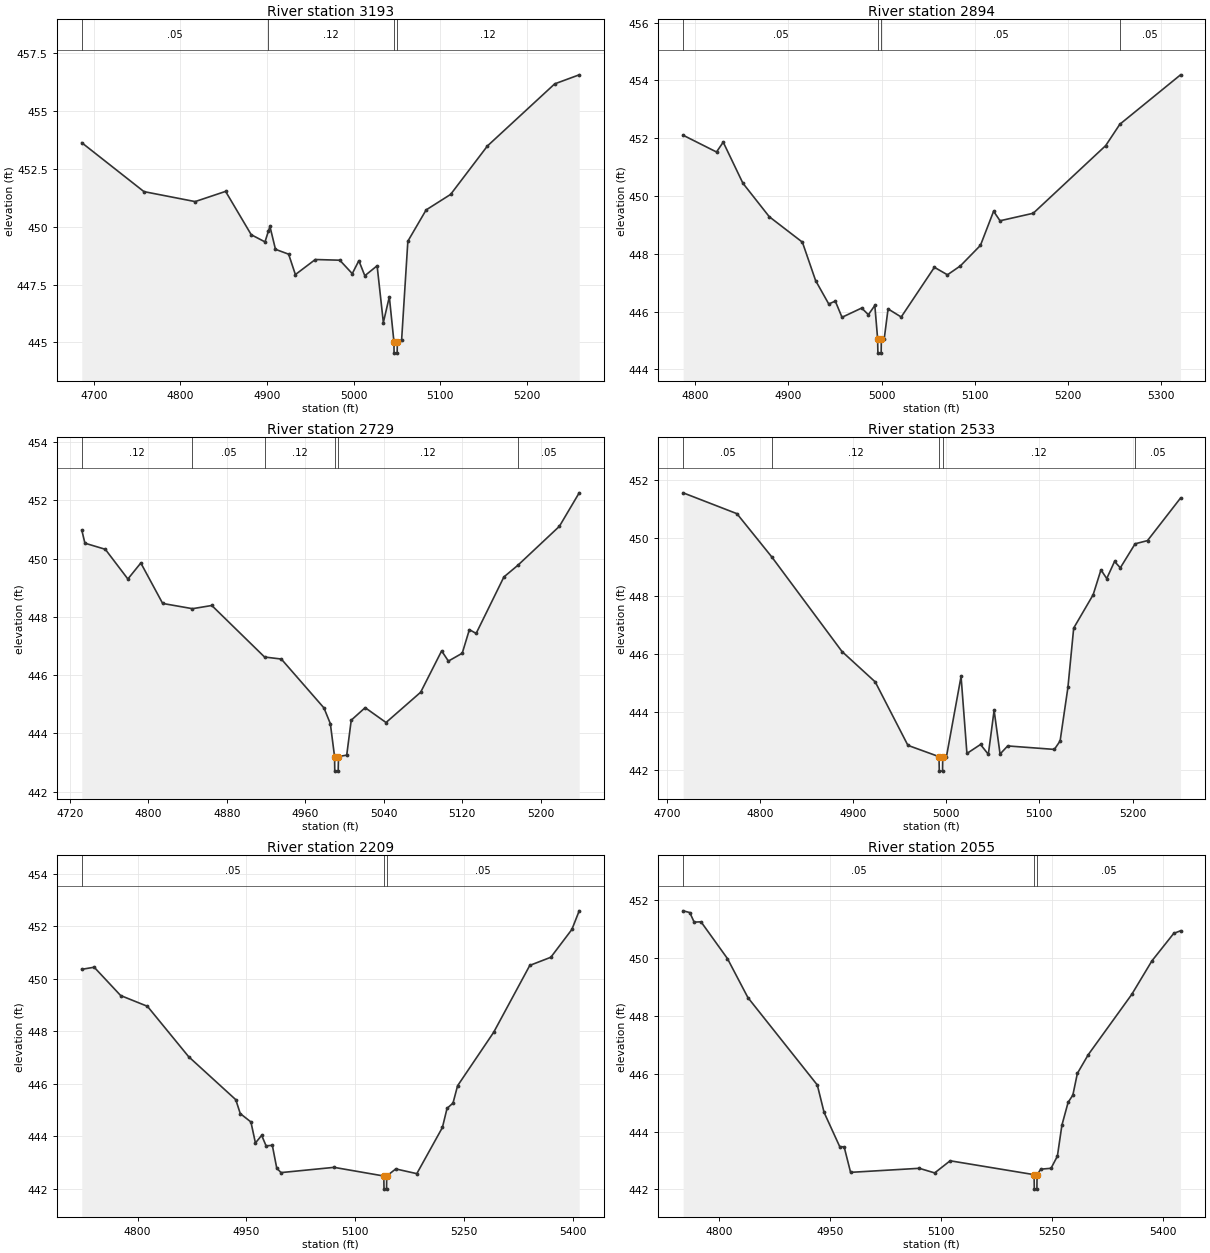
Type RM Length L Ch R = 1 ,3193    ,299,299,299
BEGIN DESCRIPTION:
Lacy 106 1683
END DESCRIPTION:
XS GIS Cut Line= 3
      2735901.69      6859773.33      2736175.16      6859617.46
      2736353.95      6859429.07
#Sta/Elev= 30
    4686  453.62  4757.8  451.51  4816.9  451.08  4852.1  451.52  4881.7  449.65
  4897.6  449.34  4901.4  449.79  4903.3  450.01  4909.7  449.02  4924.9  448.81
  4932.7  447.93  4955.7  448.58    4984  448.55  4998.4  447.97    5006  448.53
  5012.9  447.88  5027.1  448.31  5034.3  445.86  5041.2  446.97  5046.5  445.04
  5046.7  444.54  5050.2  444.54  5050.5  445.04  5055.4  445.11  5062.6  449.37
  5083.7  450.72    5112  451.39  5154.5  453.48  5232.2  456.16  5260.5  456.55
#Mann= 4 ,-1 , 0
    4686     .05       0  4901.4     .12       0  5046.5     .07       0
  5050.5     .12       0
Bank Sta=5046.5,5050.5
XS Rating Curve= 0 ,0
Exp/Cntr=0.3,0.1

Type RM Length L Ch R = 1 ,2894    ,165,165,165
BEGIN DESCRIPTION:
Lacy 106 1682
END DESCRIPTION:
XS GIS Cut Line= 3
      2736111.12      6859996.92      2736265.11      6859849.05
      2736497.87      6859629.45
#Sta/Elev= 30
    4787   452.1  4822.8  451.52    4830  451.86  4851.1  450.44  4879.4  449.28
  4914.9   448.4  4929.1  447.07  4943.2  446.26  4950.2  446.36  4957.4   445.8
  4978.5  446.12  4985.7  445.89  4992.6  446.21  4995.6  445.06  4995.9  444.56
  4999.4  444.56  4999.6  445.06  5002.7  445.06  5006.8  446.09  5020.9  445.81
  5056.5  447.53  5070.5  447.27  5084.4  447.58  5105.9  448.29    5120  449.47
  5126.9  449.14  5162.5   449.4  5240.2  451.74  5255.4  452.48  5320.5  454.19
#Mann= 4 ,-1 , 0
    4787     .05       0  4995.6     .07       0  4999.6     .05       0
  5255.4     .05       0
Bank Sta=4995.6,4999.6
XS Rating Curve= 0 ,0
Exp/Cntr=0.3,0.1

Type RM Length L Ch R = 1 ,2729    ,196,196,196
BEGIN DESCRIPTION:
Lacy 106 1681
END DESCRIPTION:
XS GIS Cut Line= 3
      2736239.66      6860149.32      2736400.78      6859932.36
      2736564.49      6859760.92
#Sta/Elev= 30
  4732.1  450.98  4735.3  450.53  4756.1  450.32  4779.1   449.3  4792.3  449.85
  4814.6  448.46    4845  448.28  4864.7  448.39  4918.5  446.62  4935.6  446.55
  4979.1  444.87  4985.6  444.33  4989.9   443.2  4990.1   442.7  4993.6   442.7
  4993.9   443.2  5002.3  443.25  5006.9  444.45  5021.1  444.88  5042.4  444.37
  5077.7  445.41  5099.1  446.83    5106  446.48  5120.1  446.75  5127.4  447.56
  5134.3  447.43  5162.6  449.37  5176.8  449.77  5219.2  451.11  5239.4  452.26
#Mann= 6 ,-1 , 0
  4732.1     .12       0    4845     .05       0  4918.5     .12       0
  4989.9     .07       0  4993.9     .12       0  5176.8     .05       0
Bank Sta=4989.9,4993.9
XS Rating Curve= 0 ,0
Exp/Cntr=0.3,0.1

Type RM Length L Ch R = 1 ,2533    ,324,324,324
BEGIN DESCRIPTION:
Lacy 106 1680
END DESCRIPTION:
XS GIS Cut Line= 3
      2736328.41      6860274.86      2736520.54      6860067.25
      2736670.51      6859865.31
#Sta/Elev= 30
  4717.2  451.57    4775  450.85  4812.6  449.35  4887.9  446.09  4923.6  445.04
  4958.7  442.85  4992.1  442.46  4992.4  441.96  4995.9  441.96  4996.1  442.46
  5000.1  442.46  5015.8  445.23  5022.1  442.57  5036.7  442.88  5045.1  442.54
  5051.3  444.06  5057.7  442.55  5065.9  442.83    5116  442.71  5122.2     443
  5130.6  444.85  5136.8   446.9  5157.7  448.05  5166.1  448.91  5172.3  448.61
  5180.7   449.2  5186.9  448.98  5202.8  449.81  5216.1  449.92  5251.6  451.39
#Mann= 5 ,-1 , 0
  4717.2     .05       0  4812.6     .12       0  4992.1     .07       0
  4996.1     .12       0  5202.8     .05       0
Bank Sta=4992.1,4996.1
XS Rating Curve= 0 ,0
Exp/Cntr=0.3,0.1

Type RM Length L Ch R = 1 ,2209    ,154,154,154
BEGIN DESCRIPTION:
Lacy 106 1678
END DESCRIPTION:
XS GIS Cut Line= 3
      2736432.48      6860452.66      2736660.26       6860289.2
      2736981.39      6860041.71
#Sta/Elev= 30
    4723  450.36  4740.1  450.44  4776.6  449.36  4813.5  448.95  4870.3  447.03
  4935.3  445.39  4941.5  444.86  4956.2  444.54  4962.4  443.74    4971  444.03
  4977.1  443.63  4985.7  443.65  4991.8  442.78  4997.7  442.61  5070.8  442.81
  5139.4  442.48  5139.7  441.98  5143.2  441.98  5143.4  442.48  5155.9  442.75
  5184.9  442.57  5220.2  444.33  5226.6  445.06  5234.8  445.26  5241.1  445.92
  5290.9  447.96  5340.7  450.51  5369.7  450.82  5398.7  451.88  5408.8  452.59
#Mann= 3 ,-1 , 0
    4723     .05       0  5139.4     .03       0  5143.4     .05       0
Bank Sta=5139.4,5143.4
XS Rating Curve= 0 ,0
Exp/Cntr=0.3,0.1

Type RM Length L Ch R = 1 ,2055    ,159,159,159
BEGIN DESCRIPTION:
Lacy 106 1679
END DESCRIPTION:
XS GIS Cut Line= 3
      2736525.59      6860552.25      2736739.88      6860414.48
      2737079.65      6860171.44
#Sta/Elev= 30
  4751.1  451.63  4760.1  451.57    4766  451.24  4775.3  451.25    4811  449.98
  4838.7  448.63  4932.5  445.61  4941.7  444.66  4962.8  443.48  4968.8  443.47
  4977.5  442.59  5070.4  442.73  5091.2  442.57  5112.1  442.99  5225.6  442.51
  5225.9  442.01  5229.4  442.01  5229.6  442.51  5234.7   442.7  5248.5  442.73
  5257.1  443.15  5263.2  444.22  5271.6  445.01    5278  445.26  5284.1  446.01
  5298.9  446.66  5357.6  448.74  5384.9   449.9  5414.4  450.85  5423.6  450.94
#Mann= 3 ,-1 , 0
  4751.1     .05       0  5225.6     .03       0  5229.6     .05       0
Bank Sta=5225.6,5229.6
XS Rating Curve= 0 ,0
Exp/Cntr=0.3,0.1

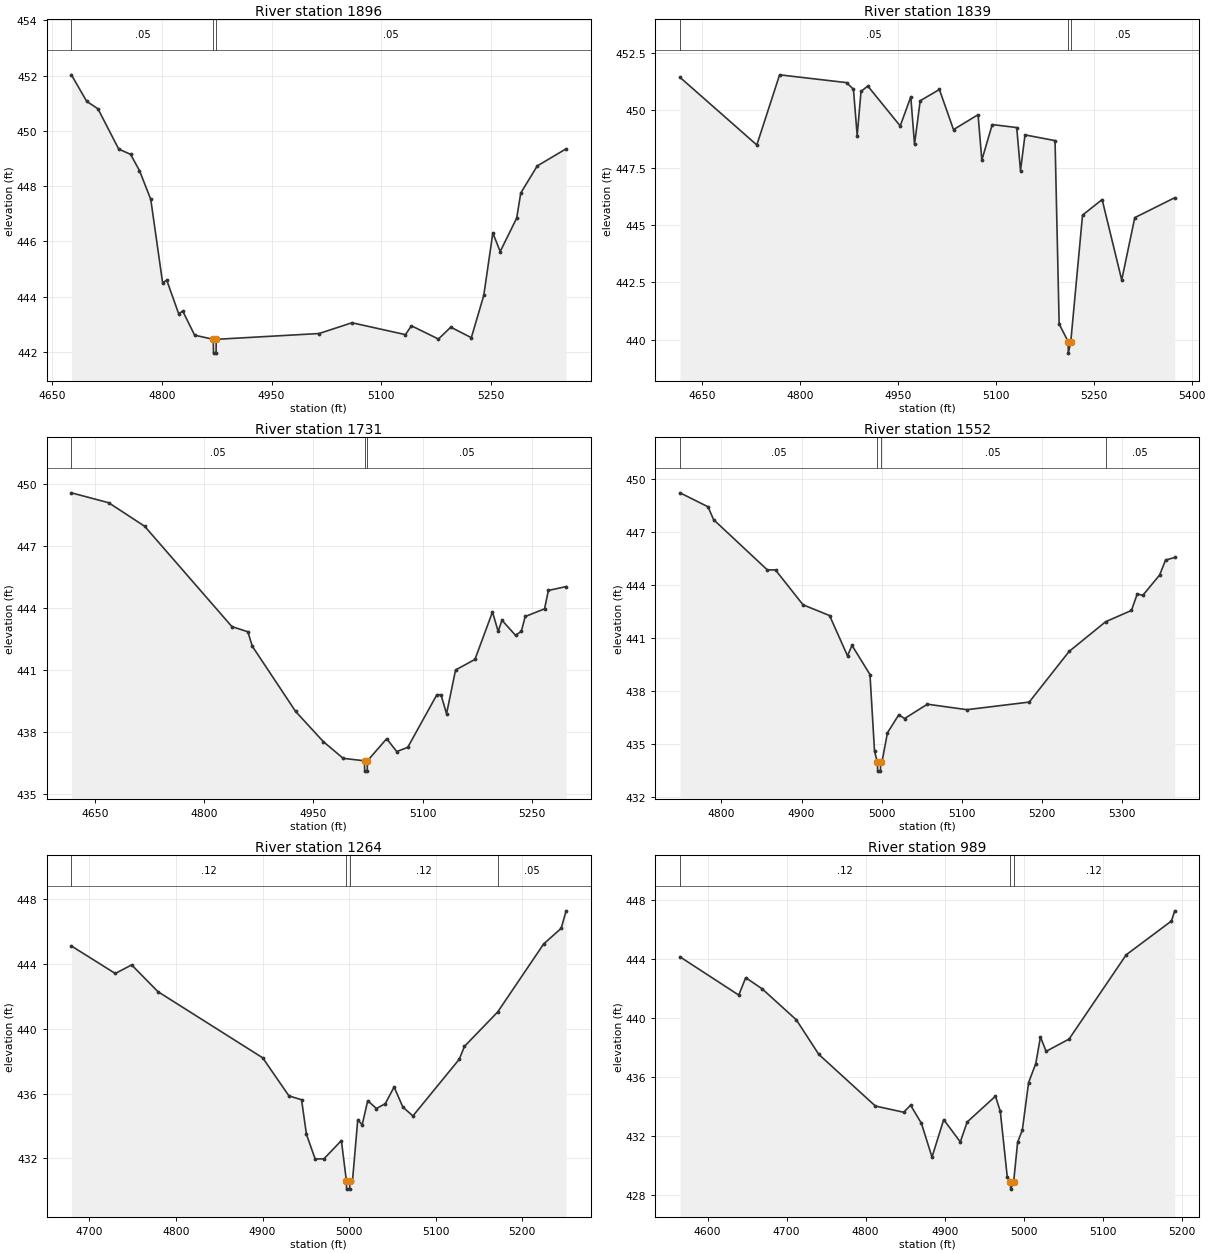
Type RM Length L Ch R = 1 ,1896    ,57,57,57
BEGIN DESCRIPTION:
Lacy 106 1673
END DESCRIPTION:
XS GIS Cut Line= 3
      2736574.08       6860596.7      2736854.77      6860445.34
        2737176.      6860288.44
#Sta/Elev= 30
  4676.3  452.03  4697.2  451.07  4712.6   450.8    4741  449.34  4757.2  449.15
  4769.4  448.56  4784.8  447.52    4801   444.5  4806.7  444.59  4822.9  443.38
  4828.6  443.47  4844.8   442.6  4870.3  442.45  4870.6  441.95  4874.1  441.95
  4874.3  442.45  5014.9  442.66  5059.9  443.05    5133  442.62  5141.2  442.94
  5178.1  442.46    5195  442.89  5223.1  442.51  5240.1  444.04  5252.5   446.3
  5262.6  445.63  5285.1  446.84  5290.7  447.75  5313.2  448.73  5352.7  449.35
#Mann= 3 ,-1 , 0
  4676.3     .05       0  4870.3     .03       0  4874.3     .05       0
Bank Sta=4870.3,4874.3
XS Rating Curve= 0 ,0
Exp/Cntr=0.3,0.1

Type RM Length L Ch R = 1 ,1839    ,108,108,108
BEGIN DESCRIPTION:
Lacy 106 1672
END DESCRIPTION:
XS GIS Cut Line= 4
      2736561.43      6860663.54      2736903.47      6860481.14
      2737080.18      6860381.42      2737247.24      6860381.05
#Sta/Elev= 30
  4616.5  451.44  4734.1  448.49    4769  451.55  4871.5  451.21  4882.1  450.92
  4887.8   448.9  4893.7  450.83  4904.1  451.06  4953.7  449.32  4969.9  450.59
  4975.6  448.52  4984.3  450.42  5013.7  450.91  5035.3  449.16  5072.9  449.81
  5078.7  447.83  5094.6  449.38  5132.1  449.25  5137.9  447.37  5144.8  448.93
  5190.8  448.68  5197.1  440.68  5210.9  439.91  5211.1  439.41  5214.9  439.91
  5232.9  445.43  5262.9  446.11  5292.9   442.6  5312.9  445.32  5374.1  446.19
#Mann= 3 ,-1 , 0
  4616.5     .05       0  5210.9     .03       0  5214.9     .05       0
Bank Sta=5210.9,5214.9
XS Rating Curve= 0 ,0
Exp/Cntr=0.3,0.1

Type RM Length L Ch R = 1 ,1731    ,179,179,179
BEGIN DESCRIPTION:
Lacy 106 1671
END DESCRIPTION:
XS GIS Cut Line= 4
      2736657.59      6860711.26      2736990.38      6860530.82
      2737096.62      6860461.91      2737262.09      6860407.74
#Sta/Elev= 30
  4617.7  449.57  4668.9  449.09  4718.3  447.95  4838.1  443.09    4860  442.84
  4866.1  442.14  4925.6  438.98  4963.6  437.52  4990.9  436.71  5020.2  436.59
  5020.4  436.09  5023.9  436.09  5024.2  436.59  5050.6  437.66  5064.4  437.04
  5079.5  437.24  5119.5  439.79  5125.2  439.79  5132.8  438.87  5145.2  440.99
  5171.8   441.5  5195.9   443.8  5203.7  442.86  5208.9   443.4  5227.5  442.67
  5235.5  442.86  5240.8  443.58  5267.4  443.95  5272.6  444.84    5297  445.03
#Mann= 3 ,-1 , 0
  4617.7     .05       0  5020.2     .04       0  5024.2     .05       0
Bank Sta=5020.2,5024.2
XS Rating Curve= 0 ,0
Exp/Cntr=0.3,0.1

Type RM Length L Ch R = 1 ,1552    ,288,288,288
BEGIN DESCRIPTION:
Lacy 106 1676
END DESCRIPTION:
XS GIS Cut Line= 3
      2736976.13      6860898.53      2737086.04      6860675.96
      2737338.36      6860407.01
#Sta/Elev= 30
  4748.4  449.24  4783.3  448.45  4790.3  447.72  4857.2  444.88  4867.5  444.87
  4901.8   442.9  4934.9  442.29  4957.3  440.01  4962.9   440.6  4985.3  438.95
    4991   434.6  4994.6  433.98  4994.9  433.48  4998.4  433.48  4998.6  433.98
  5000.2  433.98  5007.1  435.65  5021.2  436.67  5028.5  436.46  5056.9  437.27
  5106.2  436.96  5183.9  437.39  5233.7  440.26  5279.2  441.94  5311.4  442.58
  5318.7  443.52  5325.5  443.43  5346.6  444.59  5353.9  445.43  5365.4  445.58
#Mann= 4 ,-1 , 0
  4748.4     .05       0  4994.6     .04       0  4998.6     .05       0
  5279.2     .05       0
Bank Sta=4994.6,4998.6
XS Rating Curve= 0 ,0
Exp/Cntr=0.3,0.1

Type RM Length L Ch R = 1 ,1264    ,275,275,275
BEGIN DESCRIPTION:
Lacy 106 1677
END DESCRIPTION:
XS GIS Cut Line= 3
      2737304.55      6860979.91      2737348.84      6860660.55
      2737393.11      6860415.43
#Sta/Elev= 30
  4679.1  445.12  4729.8  443.42  4748.7  443.95    4779   442.3  4900.1  438.21
  4930.4  435.86    4945  435.62  4950.6  433.49  4960.7  431.96  4970.8  431.97
    4991   433.1  4996.8   430.6    4997   430.1  5000.5   430.1  5000.8   430.6
  5003.8   430.6  5009.9  434.39    5015  434.07  5021.4  435.56  5031.5  435.08
  5041.7  435.38  5051.9  436.41    5062  435.17  5073.6  434.62  5127.1  438.12
  5133.2  438.92  5171.5  441.04  5224.6  445.24  5244.9  446.21  5250.6  447.29
#Mann= 4 ,-1 , 0
  4679.1     .12       0  4996.8     .07       0  5000.8     .12       0
  5171.5     .05       0
Bank Sta=4996.8,5000.8
XS Rating Curve= 0 ,0
Exp/Cntr=0.3,0.1

Type RM Length L Ch R = 1 ,989     ,313,313,313
BEGIN DESCRIPTION:
Lacy 106 1674
END DESCRIPTION:
XS GIS Cut Line= 3
      2737351.96      6860991.87      2737599.01      6860636.19
      2737705.03      6860475.11
#Sta/Elev= 30
  4565.2  444.17  4639.5  441.58  4648.3  442.76  4669.2     442  4712.4   439.9
  4740.8  437.56  4812.4  434.06  4848.2  433.64  4856.9  434.12  4870.6  432.89
    4884   430.6  4898.8  433.14  4919.8  431.63  4928.5  432.98  4964.3  434.73
  4970.4   433.7  4979.2  429.26  4983.3  428.93  4983.5  428.43  4987.3  428.93
  4992.3   431.6  4998.3  432.44  5006.2  435.65  5015.3  436.94  5021.2  438.74
  5028.4  437.77  5057.4   438.6  5129.7  444.31  5186.9   446.6  5191.1  447.29
#Mann= 3 ,-1 , 0
  4565.2     .12       0  4983.3     .07       0  4987.3     .12       0
Bank Sta=4983.3,4987.3
XS Rating Curve= 0 ,0
Exp/Cntr=0.3,0.1

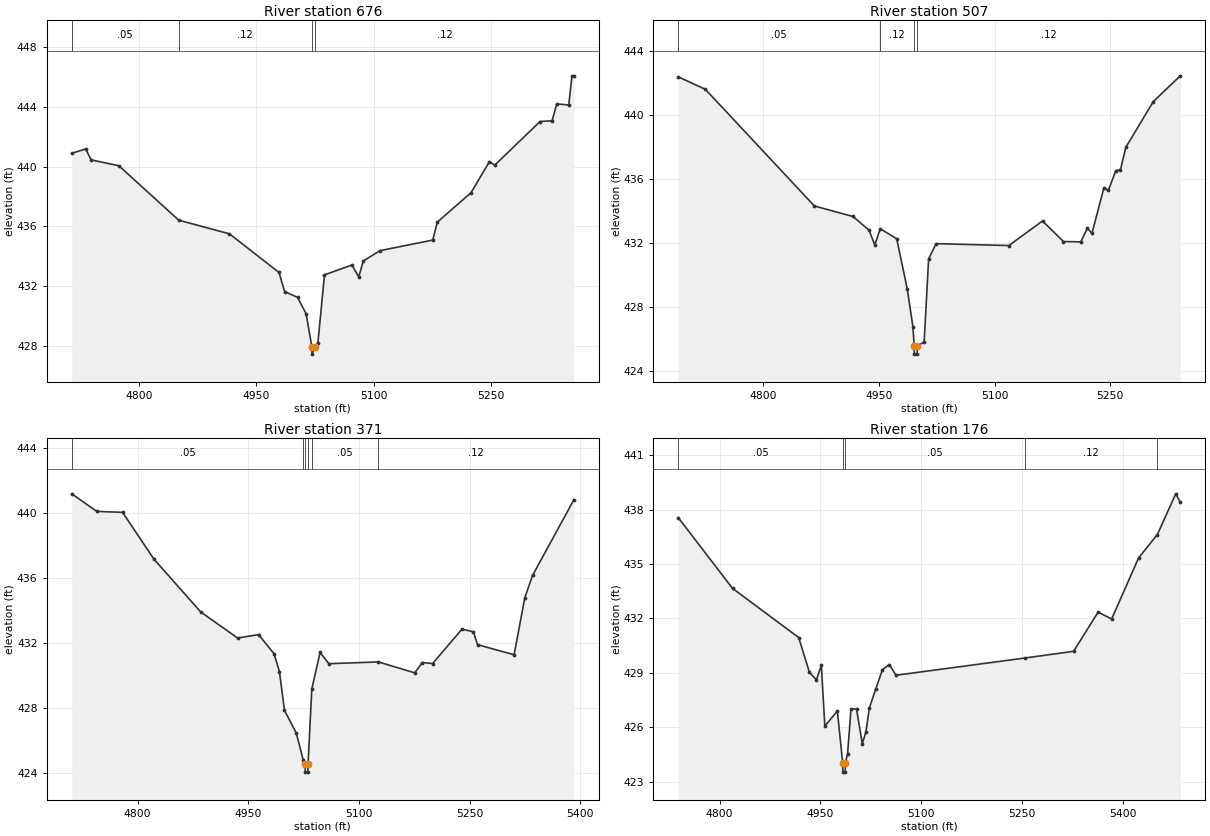
Type RM Length L Ch R = 1 ,676     ,169,169,169
BEGIN DESCRIPTION:
Lacy 106 1675
END DESCRIPTION:
XS GIS Cut Line= 3
      2737447.01      6861087.15      2737646.35      6860884.09
      2737833.46      6860578.94
#Sta/Elev= 30
  4713.8   440.9  4731.6  441.19  4738.6  440.46    4774  440.07  4850.7  436.42
  4915.5  435.51    4979  432.92  4986.2  431.64  5002.8  431.25  5013.7  430.15
    5021  427.95  5021.2  427.45    5025  427.95  5028.8  428.22  5037.2  432.76
  5072.4  433.42    5081  432.62  5086.9  433.69  5108.2  434.38  5175.7  435.09
  5181.6  436.29  5224.8  438.27  5248.3  440.34  5255.1  440.11  5313.1  443.03
  5328.5  443.08  5334.4  444.21  5349.8  444.14  5353.9  446.09  5356.3  446.09
#Mann= 4 ,-1 , 0
  4713.8     .05       0  4850.7     .12       0    5021     .07       0
    5025     .12       0
Bank Sta=5021,5025
XS Rating Curve= 0 ,0
Exp/Cntr=0.3,0.1

Type RM Length L Ch R = 1 ,507     ,136,136,136
BEGIN DESCRIPTION:
Lacy 106 1670
END DESCRIPTION:
XS GIS Cut Line= 3
      2737535.79      6861210.53      2737766.51      6861001.67
      2737941.64      6860710.38
#Sta/Elev= 30
  4689.8   442.4  4725.1  441.61  4866.3  434.31  4916.4  433.65  4937.3  432.79
  4944.7  431.86  4951.7  432.88  4973.1  432.26  4986.8  429.11  4994.1  426.76
  4995.8  425.53    4996  425.03  4999.5  425.03  4999.8  425.53  5008.7   425.8
  5014.5  430.99  5024.2  431.95  5118.5  431.83  5162.2  433.37  5189.4  432.08
  5211.8  432.06  5220.4  432.92  5226.3  432.59  5241.8  435.44  5247.6  435.28
  5257.3  436.53  5263.2  436.56  5270.2  437.98  5305.9  440.85  5340.9  442.46
#Mann= 4 ,-1 , 0
  4689.8     .05       0  4951.7     .12       0  4995.8     .07       0
  4999.8     .12       0
Bank Sta=4995.8,4999.8
XS Rating Curve= 0 ,0
Exp/Cntr=0.3,0.1

Type RM Length L Ch R = 1 ,371     ,195,195,195
BEGIN DESCRIPTION:
Lacy 106 1685
END DESCRIPTION:
XS GIS Cut Line= 3
      2737619.63       6861312.1       2737831.6      6861115.36
       2737968.9      6860748.83
#Sta/Elev= 30
  4710.8  441.16  4744.6  440.08  4779.7  440.02  4822.2  437.14  4885.7  433.89
  4935.6  432.29    4964   432.5  4984.9  431.33  4992.3  430.22  4999.1  427.85
  5015.3  426.42  5024.6  424.77  5027.1  424.54  5027.3  424.04  5030.8  424.04
  5031.1  424.54  5036.2  429.16  5047.4   431.4  5059.3  430.71  5126.3  430.82
  5175.5  430.15  5186.2  430.78    5200  430.72  5239.6  432.83  5255.2  432.68
  5260.9  431.88  5310.4  431.26    5325  434.78  5335.4  436.14  5391.4  440.79
#Mann= 6 ,-1 , 0
  4710.8     .05       0  5024.6     .12       0  5027.1     .05       0
  5031.1     .12       0  5036.2     .05       0  5126.3     .12       0
Bank Sta=5027.1,5031.1
XS Rating Curve= 0 ,0
Exp/Cntr=0.3,0.1

Type RM Length L Ch R = 1 ,176     ,0,0,0
BEGIN DESCRIPTION:
Lacy 106 1684
END DESCRIPTION:
XS GIS Cut Line= 3
      2737718.45      6861325.24      2737969.82      6861253.16
      2738001.44      6860769.09
#Sta/Elev= 30
  4738.5  437.56  4819.2  433.66  4917.6  430.95  4933.6  429.03    4944  428.62
  4951.3  429.42  4956.5  426.07  4975.2   426.9    4983  424.03  4983.3  423.53
  4986.8  423.53    4987  424.03  4990.3  424.53  4995.4  427.01  5003.6  427.01
  5012.2   425.1  5017.6  425.74  5022.7  427.06  5032.2  428.11  5042.2  429.18
  5052.3  429.46  5062.3  428.87    5254  429.82  5326.4  430.19  5362.9  432.35
    5383  431.97  5423.1  435.34  5450.9  436.62  5478.3  438.87  5485.1  438.41
#Mann= 5 ,-1 , 0
  4738.5     .05       0    4983     .04       0    4987     .05       0
    5254     .12       0  5450.9      .1       0
Bank Sta=4983,4987
XS Rating Curve= 0 ,0
Exp/Cntr=0.3,0.1

Chan Stop Cuts=-1
Use User Specified Reach Order=0
Composite Channel Slope=5