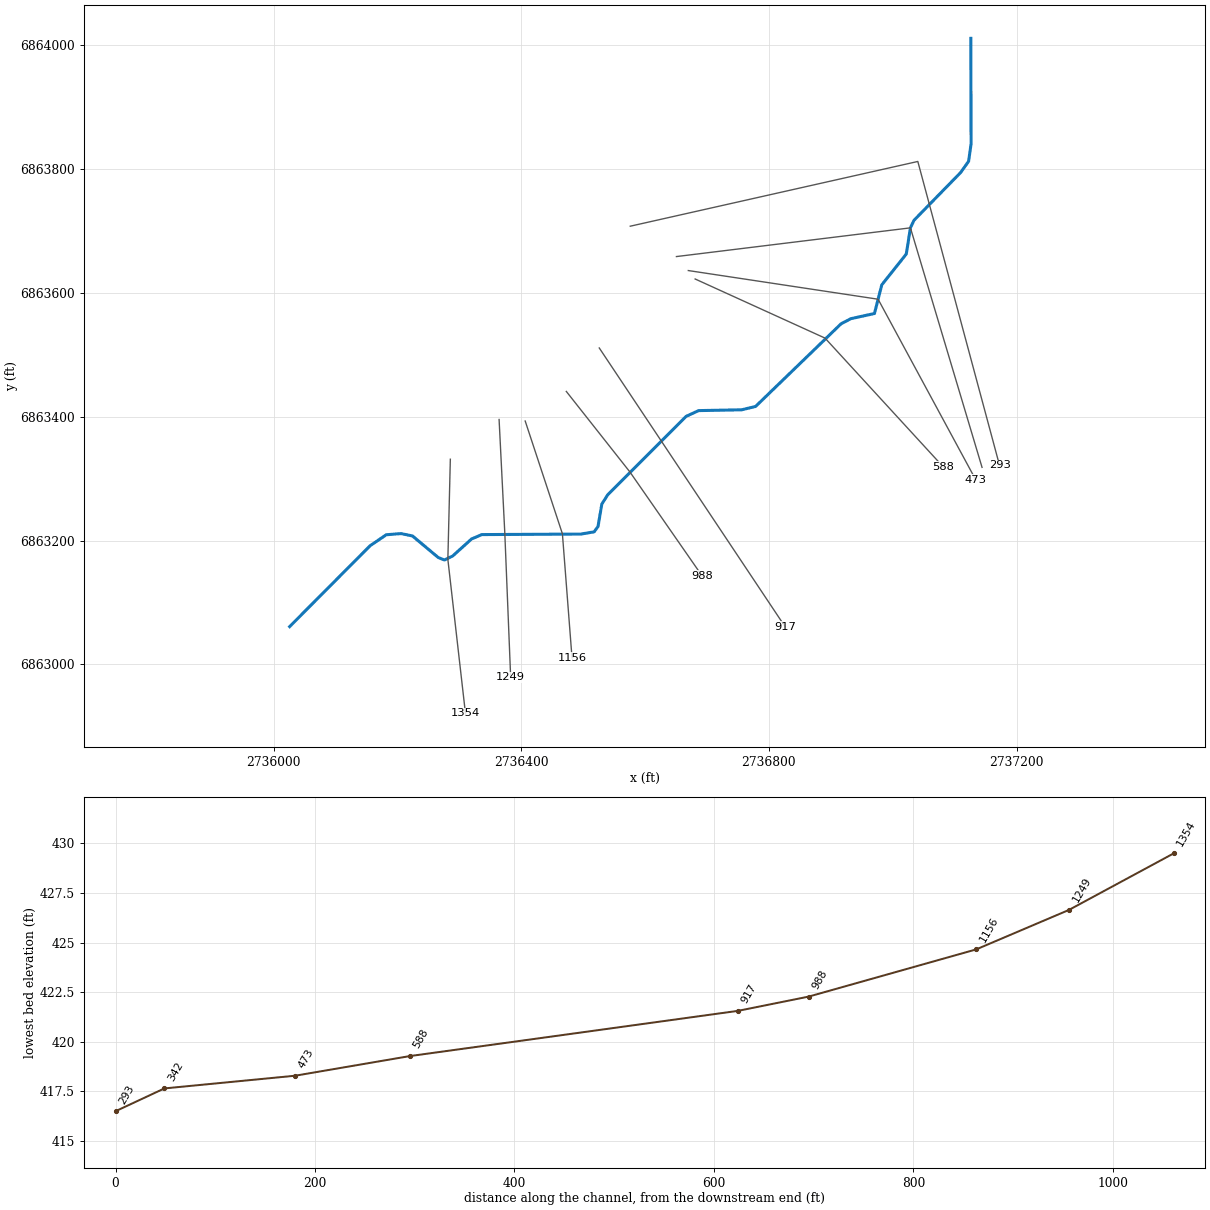
--- Lacy 107.prj (project) ---

Proj Title=Lacy 107 Base Level Engineering
Current Plan=p01
Default Exp/Contr=0.3,0.1
English Units
Geom File=g01
Flow File=f01
Plan File=p01
BEGIN DESCRIPTION:
Lacy 107
END DESCRIPTION:

--- Lacy 107.p01 (plan) ---

Plan Title=Multiple Run
Short Identifier=Multiple
Geom File=g01
Flow File=f01
Subcritical Flow
K Sum by GR= 0
Std Step Tol= 0.01
Critical Tol= 0.01
Num of Std Step Trials= 20
Max Error Tol= 0.3
Flow Tol Ratio= 0.001
Split Flow NTrial= 30
Split Flow Tol= 0.02
Split Flow Ratio= 0.02
Log Output Level= 0
Friction Slope Method= 1
Unsteady Friction Slope Method= 2
Unsteady Bridges Friction Slope Method= 1
Parabolic Critical Depth
Global Vel Dist=  1 , 1 , 1
Global Log Level= 0
CheckData=True
Encroach Param= -1, 0, 0, 0
BEGIN DESCRIPTION:
Multiple Run
END DESCRIPTION:

--- Lacy 107.f01 (steady flow) ---

Flow Title=Multiple
Number of Profiles=7
Profile Names=10-year,25-year,50-year,1pct_min,100-year,1pct_plu,500-year
River Rch & RM= Lacy 107,Reach-1,1354
     189     236     271     156     311     620     406
Boundary for River Rch & Prof#=Lacy 107,Reach-1,1
Up Type=0
Dn Type=3
Dn Slope=0.005
Boundary for River Rch & Prof#=Lacy 107,Reach-1,2
Up Type=0
Dn Type=3
Dn Slope=0.005
Boundary for River Rch & Prof#=Lacy 107,Reach-1,3
Up Type=0
Dn Type=3
Dn Slope=0.005
Boundary for River Rch & Prof#=Lacy 107,Reach-1,4
Up Type=0
Dn Type=3
Dn Slope=0.005
Boundary for River Rch & Prof#=Lacy 107,Reach-1,5
Up Type=0
Dn Type=3
Dn Slope=0.005
Boundary for River Rch & Prof#=Lacy 107,Reach-1,6
Up Type=0
Dn Type=3
Dn Slope=0.005
Boundary for River Rch & Prof#=Lacy 107,Reach-1,7
Up Type=0
Dn Type=3
Dn Slope=0.005

--- Lacy 107.g01 (geometry) ---

Geom Title=Existing Conditions

River Reach=Lacy 107,Reach-1
Reach XY= 30
      2736026.00      6863061.00      2736155.91      6863191.58
      2736182.05      6863209.35      2736205.84      6863211.25
      2736224.35      6863207.43      2736266.07      6863172.53
      2736275.99      6863168.59      2736289.20      6863174.96
      2736319.81      6863202.55      2736336.44      6863209.62
      2736496.43      6863210.46      2736517.70      6863214.07
      2736524.02      6863222.69      2736530.16      6863258.91
      2736539.74      6863273.95      2736666.21      6863400.48
      2736686.48      6863409.83      2736755.94      6863411.13
      2736778.43      6863416.52      2736916.59      6863550.11
      2736932.44      6863558.31      2736970.41      6863566.61
      2736982.24      6863612.85      2737021.82      6863662.71
      2737028.51      6863704.96      2737034.16      6863717.05
      2737109.54      6863794.25      2737122.46      6863812.47
      2737126.45      6863840.82      2737126.00      6864011.00

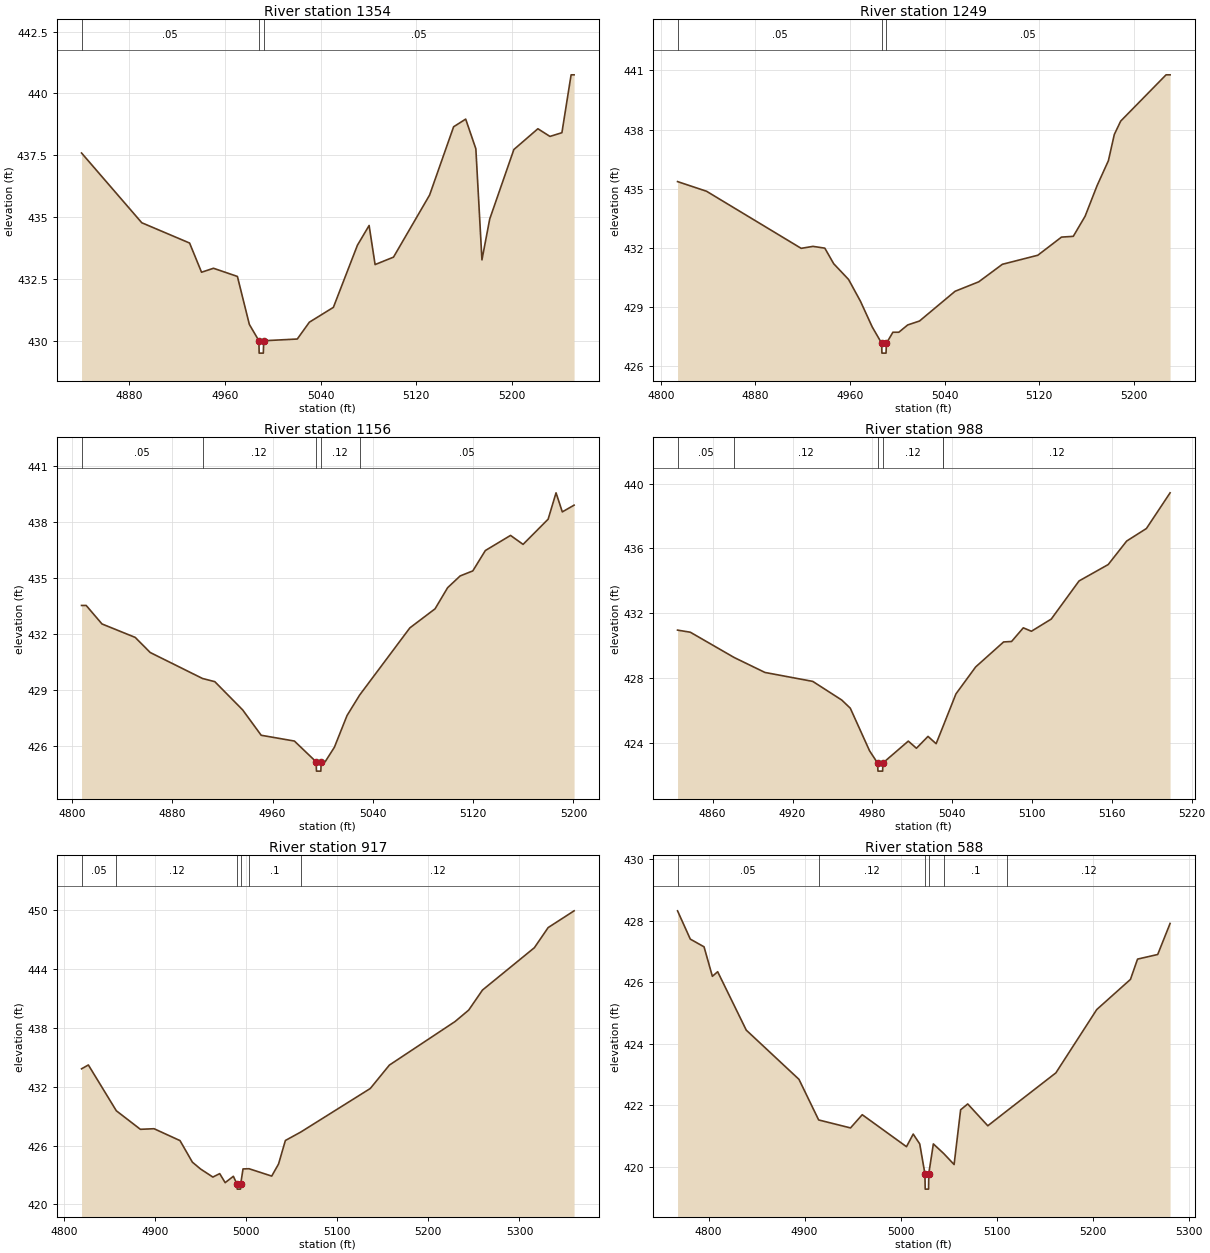
Type RM Length L Ch R = 1,1354,105,105,105
BEGIN DESCRIPTION:
Lacy 107 1661
END DESCRIPTION:
XS GIS Cut Line= 3
      2736285.52      6863331.33      2736281.52      6863169.56
      2736309.93      6862920.90
#Sta/Elev= 30
  4839.9  437.59  4890.3  434.77  4930.3  433.95  4940.3  432.77  4950.3  432.93
  4970.3  432.60  4980.3  430.66  4988.3  430.00  4988.5  429.50  4992.0  429.50
  4992.3  430.00  5020.4  430.07  5030.5  430.75  5050.6  431.35  5070.7  433.86
  5080.5  434.66  5085.5  433.08  5100.9  433.38  5131.1  435.89  5151.2  438.65
  5161.3  438.96  5169.8  437.76  5174.9  433.27  5181.4  434.92  5201.6  437.73
  5221.7  438.57  5231.8  438.26  5241.8  438.41  5249.5  440.75  5252.0  440.75
#Mann=3,-1,0
  4839.9    0.05       0  4988.3    0.04       0  4992.3    0.05       0
Bank Sta=4988.3,4992.3
Exp/Cntr=0.3,0.1

Type RM Length L Ch R = 1,1249,93,93,93
BEGIN DESCRIPTION:
Lacy 107 1660
END DESCRIPTION:
XS GIS Cut Line= 3
      2736364.25      6863395.48      2736373.52      6863210.99
      2736382.93      6862979.20
#Sta/Elev= 30
  4814.1  435.36  4838.6  434.87  4918.7  431.97  4928.7  432.07  4938.7  431.98
  4946.2  431.19  4958.8  430.39  4968.8  429.29  4978.8  427.98  4986.8  427.15
  4987.0  426.65  4990.5  426.65  4990.8  427.15  4996.3  427.71  5001.3  427.71
  5008.8  428.08  5018.8  428.28  5048.9  429.79  5068.9  430.27  5088.9  431.16
  5118.9  431.62  5138.9  432.54  5148.9  432.58  5158.9  433.60  5169.0  435.15
  5178.6  436.42  5183.6  437.75  5189.0  438.43  5227.4  440.78  5230.8  440.78
#Mann=3,-1,0
  4814.1    0.05       0  4986.8    0.04       0  4990.8    0.05       0
Bank Sta=4986.8,4990.8
Exp/Cntr=0.3,0.1

Type RM Length L Ch R = 1,1156,168,168,168
BEGIN DESCRIPTION:
Lacy 107 1659
END DESCRIPTION:
XS GIS Cut Line= 3
      2736406.39      6863393.04      2736466.50      6863210.89
      2736482.02      6863010.40
#Sta/Elev= 30
  4807.6  433.53  4811.3  433.53  4823.9  432.54  4850.4  431.82  4862.4  431.01
  4904.1  429.62  4913.9  429.45  4936.1  427.94  4950.9  426.58  4977.4  426.27
  4994.7  425.16  4995.0  424.66  4998.5  424.66  4998.7  425.16  5001.9  425.16
  5009.3  425.94  5019.4  427.64  5029.4  428.73  5069.5  432.33  5089.6  433.35
  5099.6  434.48  5109.6  435.11  5119.7  435.38  5129.7  436.47  5149.8  437.28
  5159.8  436.80  5179.8  438.15  5186.1  439.56  5191.1  438.54  5200.5  438.90
#Mann=5,-1,0
  4807.6    0.05       0  4904.1    0.12       0  4994.7    0.07       0
  4998.7    0.12       0  5029.4    0.05       0
Bank Sta=4994.7,4998.7
Exp/Cntr=0.3,0.1

Type RM Length L Ch R = 1,988,71,71,71
BEGIN DESCRIPTION:
Lacy 107 1658
END DESCRIPTION:
XS GIS Cut Line= 3
      2736472.82      6863440.76      2736575.71      6863310.46
      2736692.13      6863142.85
#Sta/Elev= 30
  4833.6  430.97  4843.2  430.84  4876.2  429.28  4899.3  428.36  4935.2  427.81
  4957.0  426.66  4963.4  426.16  4977.9  423.53  4983.9  422.78  4984.2  422.28
  4987.7  422.28  4987.9  422.78  5007.0  424.13  5013.1  423.69  5021.8  424.42
  5027.9  423.97  5033.0  425.02  5033.3  425.08  5042.8  427.04  5057.6  428.70
  5078.6  430.24  5084.6  430.27  5093.4  431.11  5099.5  430.90  5114.4  431.65
  5135.3  434.00  5157.2  435.01  5171.1  436.46  5185.9  437.23  5203.7  439.43
#Mann=6,-1,0
  4833.6    0.05       0  4876.2    0.12       0  4983.9    0.07       0
  4987.9    0.12       0  5033.0     0.1       0  5033.3    0.12       0
Bank Sta=4983.9,4987.9
Exp/Cntr=0.3,0.1

Type RM Length L Ch R = 1,917,329,329,329
BEGIN DESCRIPTION:
Lacy 107 86
END DESCRIPTION:
XS GIS Cut Line= 3
      2736526.01      6863510.98      2736626.00      6863361.00
      2736825.99      6863061.01
#Sta/Elev= 30
  4819.2  433.83  4826.7  434.22  4857.4  429.55  4883.8  427.66  4898.8  427.72
  4927.3  426.51  4940.9  424.31  4949.9  423.61  4963.4  422.79  4970.9  423.14
  4976.9  422.22  4985.9  422.87  4989.9  422.06  4990.2  421.56  4993.7  421.56
  4993.9  422.06  4996.5  423.62  5003.1  423.64  5028.0  422.89  5035.5  424.12
  5043.0  426.52  5059.9  427.38  5136.2  431.82  5157.2  434.21  5229.3  438.65
  5244.3  439.82  5259.4  441.86  5316.4  446.18  5331.5  448.23  5360.0  449.94
#Mann=6,-1,0
  4819.2    0.05       0  4857.4    0.12       0  4989.9    0.07       0
  4993.9    0.12       0  5003.1     0.1       0  5059.9    0.12       0
Bank Sta=4989.9,4993.9
Exp/Cntr=0.3,0.1

Type RM Length L Ch R = 1,588,115,115,115
BEGIN DESCRIPTION:
Lacy 107 1657
END DESCRIPTION:
XS GIS Cut Line= 3
      2736680.85      6863622.37      2736890.61      6863526.90
      2737081.74      6863318.69
#Sta/Elev= 30
  4767.7  428.33  4781.0  427.41  4795.3  427.16  4804.0  426.20  4809.5  426.35
  4839.3  424.45  4894.2  422.85  4914.7  421.53  4947.9  421.27  4960.1  421.70
  5006.2  420.66  5013.2  421.07  5020.0  420.75  5025.4  419.78  5025.7  419.28
  5029.2  419.28  5029.4  419.78  5034.2  420.75  5044.9  420.44  5055.8  420.08
  5062.6  421.86  5070.0  422.05  5090.9  421.34  5111.4  421.84  5161.8  423.06
  5204.4  425.12  5239.5  426.10  5246.9  426.76  5267.9  426.91  5280.8  427.92
#Mann=6,-1,0
  4767.7    0.05       0  4914.7    0.12       0  5025.4    0.07       0
  5029.4    0.12       0  5044.9     0.1       0  5111.4    0.12       0
Bank Sta=5025.4,5029.4
Exp/Cntr=0.3,0.1

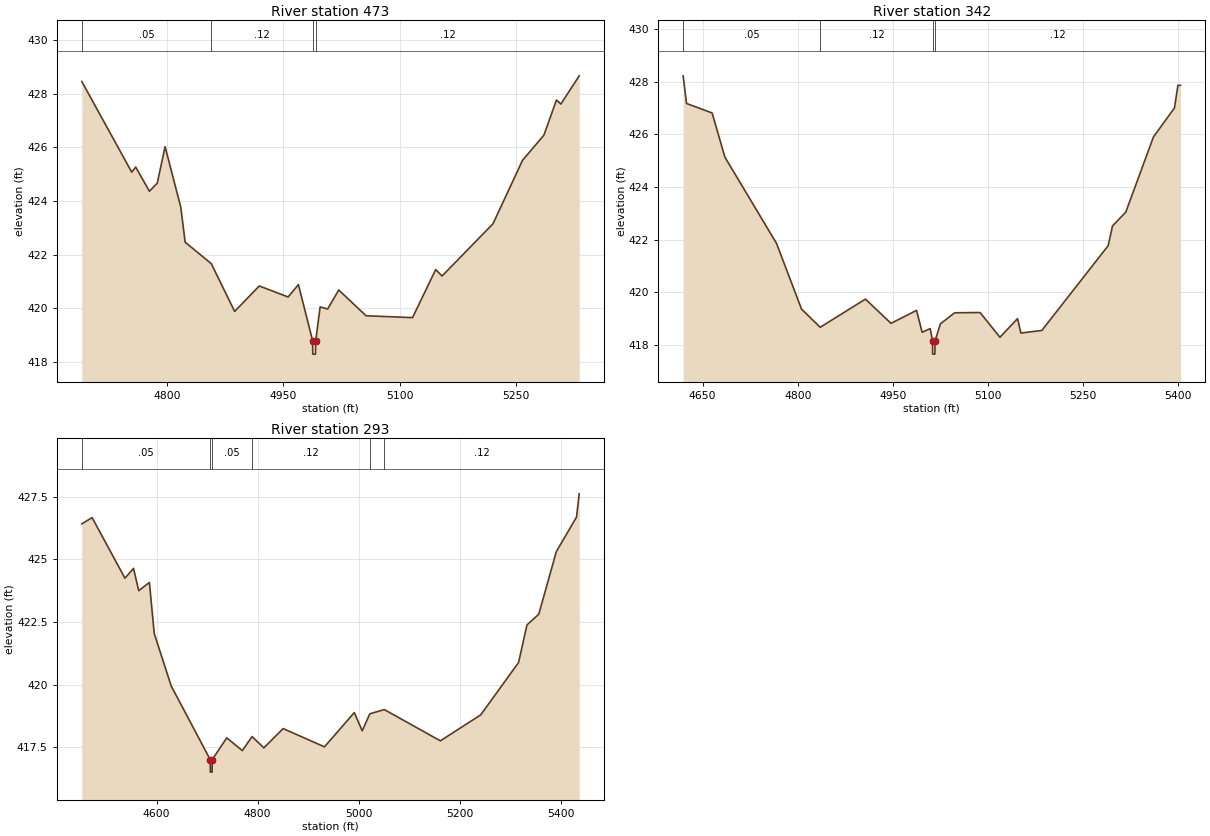
Type RM Length L Ch R = 1,473,131,131,131
BEGIN DESCRIPTION:
Lacy 107 1664
END DESCRIPTION:
XS GIS Cut Line= 3
      2736669.79      6863636.00      2736976.31      6863589.70
      2737133.88      6863298.26
#Sta/Elev= 30
  4690.0  428.45  4754.4  425.07  4759.5  425.26  4777.2  424.36  4787.3  424.66
  4797.4  426.02  4817.6  423.77  4823.3  422.46  4857.0  421.66  4887.1  419.88
  4918.8  420.83  4956.0  420.42  4969.3  420.88  4987.6  418.79  4987.8  418.29
  4991.3  418.29  4991.6  418.79  4997.3  420.05  5007.0  419.97  5021.3  420.68
  5056.5  419.72  5116.4  419.65  5146.3  421.44  5154.5  421.20  5220.2  423.15
  5258.2  425.51  5285.8  426.45  5302.0  427.76  5307.7  427.61  5331.3  428.66
#Mann=4,-1,0
  4690.0    0.05       0  4857.0    0.12       0  4987.6    0.07       0
  4991.6    0.12       0
Bank Sta=4987.6,4991.6
Exp/Cntr=0.3,0.1

Type RM Length L Ch R = 1,342,49,49,49
BEGIN DESCRIPTION:
Lacy 107 1662
END DESCRIPTION:
XS GIS Cut Line= 3
      2736650.64      6863658.59      2737028.51      6863704.96
      2737144.15      6863318.18
#Sta/Elev= 30
  4619.3  428.22  4624.7  427.17  4665.0  426.81  4685.2  425.13  4766.5  421.86
  4806.0  419.36  4835.5  418.67  4906.8  419.74  4947.1  418.82  4987.4  419.31
  4996.2  418.48  5009.0  418.62  5012.6  418.15  5012.8  417.65  5016.3  417.65
  5016.6  418.15  5025.0  418.80  5047.4  419.22  5087.6  419.23  5118.9  418.29
  5146.7  419.00  5151.9  418.45  5185.0  418.55  5289.6  421.77  5296.4  422.52
  5317.3  423.04  5361.0  425.90  5394.1  427.00  5399.6  427.86  5403.7  427.86
#Mann=4,-1,0
  4619.3    0.05       0  4835.5    0.12       0  5012.6    0.07       0
  5016.6    0.12       0
Bank Sta=5012.6,5016.6
Exp/Cntr=0.3,0.1

Type RM Length L Ch R = 1,293,0,0,0
BEGIN DESCRIPTION:
Lacy 107 1663
END DESCRIPTION:
XS GIS Cut Line= 3
      2736576.06      6863707.62      2737040.43      6863812.16
      2737172.46      6863321.19
#Sta/Elev= 30
  4452.0  426.42  4472.4  426.67  4537.4  424.25  4554.4  424.64  4564.7  423.75
  4585.8  424.08  4595.4  422.04  4629.0  419.94  4706.2  417.00  4706.4  416.50
  4709.9  416.50  4710.2  417.00  4738.9  417.87  4769.7  417.36  4789.0  417.92
  4812.4  417.47  4850.5  418.24  4932.3  417.51  4991.3  418.88  5007.0  418.15
  5022.0  418.83  5050.6  419.00  5161.7  417.75  5241.6  418.79  5316.4  420.88
  5333.0  422.38  5356.4  422.81  5391.1  425.31  5431.1  426.69  5436.4  427.62
#Mann=6,-1,0
  4452.0    0.05       0  4706.2    0.07       0  4710.2    0.05       0
  4789.0    0.12       0  5022.0    0.05       0  5050.6    0.12       0
Bank Sta=4706.2,4710.2
Exp/Cntr=0.3,0.1

Chan Stop Cuts=-1