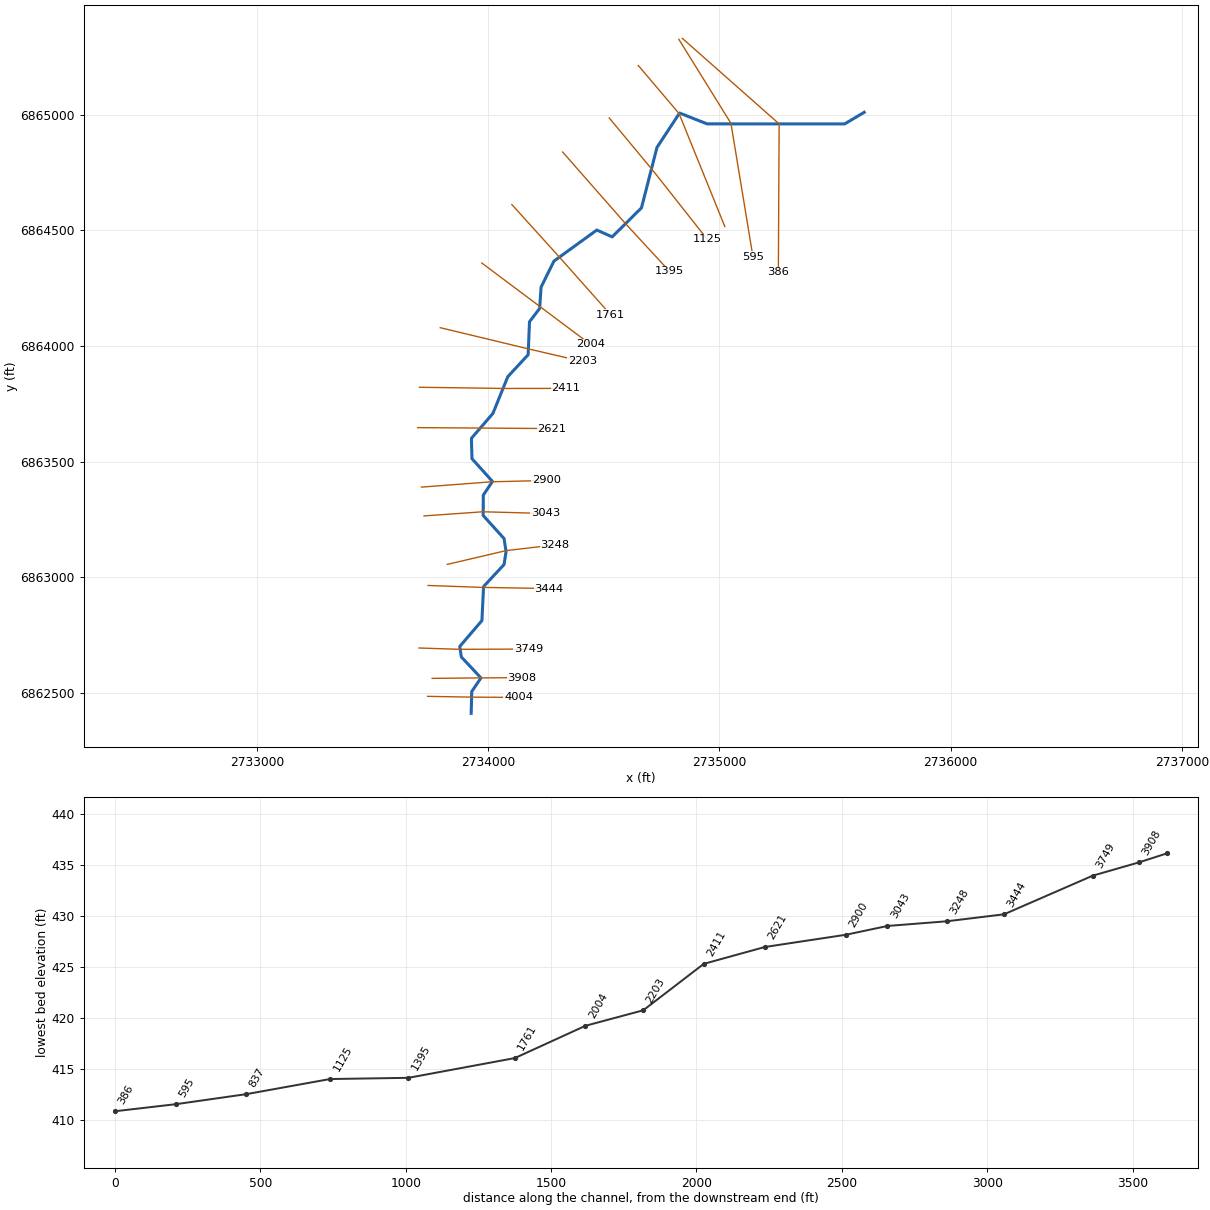
--- Lacy 108.prj (project) ---

Proj Title=Lacy 108 Base Level Engineering
Current Plan=p01
Default Exp/Contr=0.3,0.1
English Units
Geom File=g01
Flow File=f01
Plan File=p01
BEGIN DESCRIPTION:
Lacy 108
END DESCRIPTION:

--- Lacy 108.p01 (plan) ---

Plan Title=Multiple Run
Short Identifier=Multiple
Geom File=g01
Flow File=f01
Subcritical Flow
K Sum by GR= 0
Std Step Tol= 0.01
Critical Tol= 0.01
Num of Std Step Trials= 20
Max Error Tol= 0.3
Flow Tol Ratio= 0.001
Split Flow NTrial= 30
Split Flow Tol= 0.02
Split Flow Ratio= 0.02
Log Output Level= 0
Friction Slope Method= 1
Unsteady Friction Slope Method= 2
Unsteady Bridges Friction Slope Method= 1
Parabolic Critical Depth
Global Vel Dist=  1 , 1 , 1
Global Log Level= 0
CheckData=True
Encroach Param= -1, 0, 0, 0
BEGIN DESCRIPTION:
Multiple Run
END DESCRIPTION:

--- Lacy 108.f01 (steady flow) ---

Flow Title=Multiple
Number of Profiles=7
Profile Names=10-year,25-year,50-year,1pct_min,100-year,1pct_plu,500-year
River Rch & RM= Lacy 108,Reach-1,4004
     395     514     608     358     714    1424     980
Boundary for River Rch & Prof#=Lacy 108,Reach-1,1
Up Type=0
Dn Type=3
Dn Slope=0.005
Boundary for River Rch & Prof#=Lacy 108,Reach-1,2
Up Type=0
Dn Type=3
Dn Slope=0.005
Boundary for River Rch & Prof#=Lacy 108,Reach-1,3
Up Type=0
Dn Type=3
Dn Slope=0.005
Boundary for River Rch & Prof#=Lacy 108,Reach-1,4
Up Type=0
Dn Type=3
Dn Slope=0.005
Boundary for River Rch & Prof#=Lacy 108,Reach-1,5
Up Type=0
Dn Type=3
Dn Slope=0.005
Boundary for River Rch & Prof#=Lacy 108,Reach-1,6
Up Type=0
Dn Type=3
Dn Slope=0.005
Boundary for River Rch & Prof#=Lacy 108,Reach-1,7
Up Type=0
Dn Type=3
Dn Slope=0.005

--- Lacy 108.g01 (geometry) ---

Geom Title=Existing Conditions

River Reach=Lacy 108,Reach-1
Reach XY= 30
      2733926.00      6862411.00      2733928.35      6862505.23
      2733968.23      6862564.41      2733883.50      6862654.95
      2733876.56      6862700.36      2733972.44      6862812.47
      2733979.56      6862959.53      2734068.22      6863054.84
      2734076.88      6863111.00      2734068.22      6863167.16
      2733977.98      6863266.90      2733978.37      6863355.11
      2734018.19      6863414.41      2733929.48      6863512.50
      2733926.94      6863600.51      2734020.15      6863708.71
      2734084.16      6863867.05      2734172.45      6863962.47
      2734178.27      6864105.06      2734222.14      6864162.60
      2734228.33      6864255.04      2734284.02      6864367.34
      2734469.34      6864501.68      2734536.00      6864472.24
      2734662.60      6864597.69      2734729.82      6864859.42
      2734827.42      6865007.96      2734946.02      6864961.09
      2735541.17      6864960.59      2735626.00      6865011.00

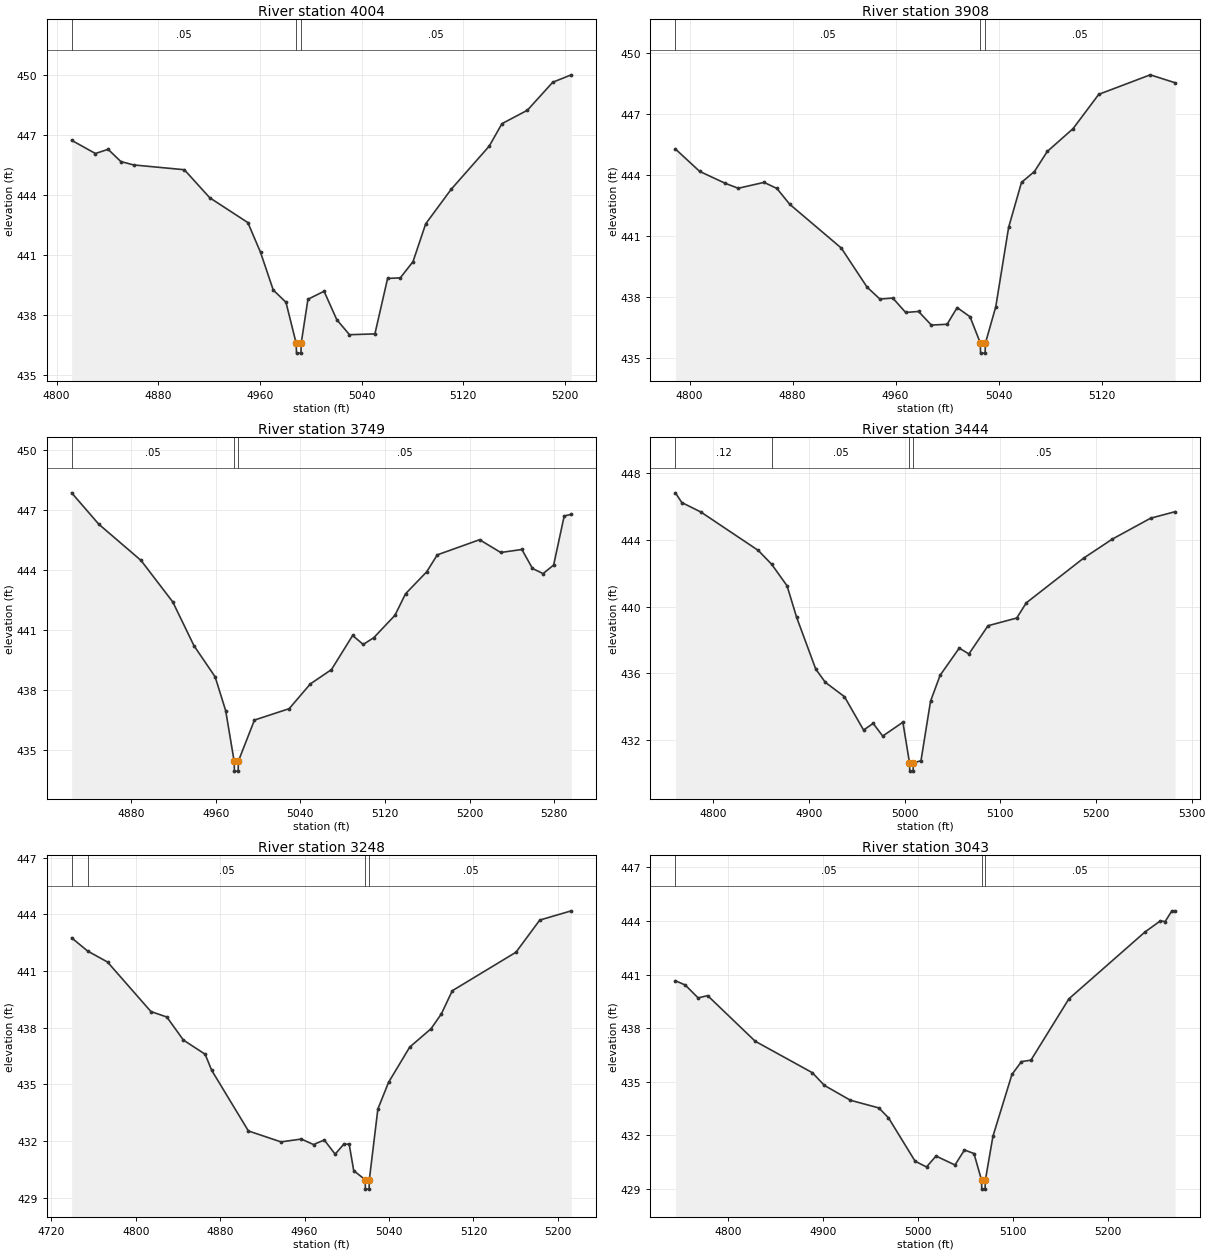
Type RM Length L Ch R = 1,4004,96,96,96
BEGIN DESCRIPTION:
Lacy 108 1638
END DESCRIPTION:
XS GIS Cut Line= 3
      2733737.30      6862484.65      2733925.47      6862481.31
      2734130.57      6862480.07
#Sta/Elev= 30
  4811.8  446.73  4830.5  446.07  4840.5  446.28  4850.5  445.67  4860.5  445.50
  4900.5  445.26  4920.5  443.86  4950.5  442.62  4960.5  441.13  4970.5  439.25
  4980.5  438.64  4988.5  436.60  4988.8  436.10  4992.3  436.10  4992.5  436.60
  4997.8  438.79  5010.5  439.19  5020.5  437.77  5030.5  437.02  5050.5  437.06
  5060.5  439.83  5070.5  439.86  5080.5  440.67  5090.5  442.56  5110.5  444.28
  5140.5  446.44  5150.5  447.56  5170.5  448.23  5190.5  449.63  5205.1  450.00
#Mann=3,-1,0
  4811.8    0.05       0  4988.5    0.04       0  4992.5    0.05       0
Bank Sta=4988.5,4992.5
Exp/Cntr=0.3,0.1

Type RM Length L Ch R = 1,3908,159,159,159
BEGIN DESCRIPTION:
Lacy 108 1637
END DESCRIPTION:
XS GIS Cut Line= 3
      2733757.24      6862562.41      2733968.23      6862564.41
      2734145.32      6862565.64
#Sta/Elev= 30
  4789.0  445.26  4807.8  444.16  4827.8  443.57  4837.8  443.33  4857.8  443.62
  4867.8  443.32  4877.8  442.54  4917.8  440.39  4937.8  438.47  4947.8  437.88
  4957.8  437.93  4967.8  437.22  4977.8  437.27  4987.8  436.60  5000.0  436.64
  5007.8  437.46  5017.8  437.01  5025.8  435.72  5026.0  435.22  5029.5  435.22
  5029.8  435.72  5037.8  437.50  5047.8  441.41  5057.8  443.62  5067.8  444.15
  5077.8  445.14  5097.8  446.26  5117.8  447.95  5157.8  448.91  5177.1  448.52
#Mann=3,-1,0
  4789.0    0.05       0  5025.8    0.04       0  5029.8    0.05       0
Bank Sta=5025.8,5029.8
Exp/Cntr=0.3,0.1

Type RM Length L Ch R = 1,3749,305,305,305
BEGIN DESCRIPTION:
Lacy 108 1636
END DESCRIPTION:
XS GIS Cut Line= 3
      2733700.46      6862693.86      2733875.29      6862688.08
      2734172.66      6862689.20
#Sta/Elev= 30
  4823.8  447.87  4849.4  446.30  4889.4  444.48  4919.4  442.40  4939.4  440.21
  4959.4  438.65  4969.4  436.95  4977.4  434.42  4977.7  433.92  4981.2  433.92
  4981.4  434.42  4996.6  436.48  5029.4  437.05  5049.4  438.29  5069.4  439.01
  5089.4  440.72  5099.4  440.27  5109.4  440.61  5129.4  441.73  5139.4  442.81
  5159.4  443.91  5169.4  444.76  5209.4  445.52  5229.4  444.88  5249.4  445.03
  5259.4  444.08  5269.4  443.82  5279.4  444.25  5289.4  446.71  5296.1  446.79
#Mann=3,-1,0
  4823.8    0.05       0  4977.4    0.04       0  4981.4    0.05       0
Bank Sta=4977.4,4981.4
Exp/Cntr=0.3,0.1

Type RM Length L Ch R = 1,3444,196,196,196
BEGIN DESCRIPTION:
Lacy 108 1635
END DESCRIPTION:
XS GIS Cut Line= 3
      2733739.41      6862964.32      2733973.12      6862955.97
      2734261.62      6862950.93
#Sta/Elev= 30
  4760.3  446.81  4766.9  446.23  4786.9  445.66  4846.9  443.36  4860.9  442.53
  4877.0  441.24  4887.0  439.35  4907.0  436.25  4917.0  435.46  4937.0  434.60
  4957.0  432.60  4967.0  433.00  4977.0  432.24  4998.1  433.07  5005.0  430.64
  5005.3  430.14  5008.8  430.14  5009.0  430.64  5017.0  430.76  5027.0  434.33
  5037.0  435.88  5057.0  437.51  5067.1  437.16  5087.1  438.85  5117.1  439.31
  5127.1  440.22  5187.1  442.90  5217.1  444.04  5257.1  445.29  5282.7  445.68
#Mann=4,-1,0
  4760.3    0.12       0  4860.9    0.05       0  5005.0    0.04       0
  5009.0    0.05       0
Bank Sta=5005,5009
Exp/Cntr=0.3,0.1

Type RM Length L Ch R = 1,3248,205,205,205
BEGIN DESCRIPTION:
Lacy 108 1634
END DESCRIPTION:
XS GIS Cut Line= 3
      2733822.87      6863055.47      2734076.89      6863115.00
      2734288.04      6863139.81
#Sta/Elev= 30
  4739.3  442.76  4754.5  442.06  4773.3  441.48  4814.4  438.86  4829.5  438.57
  4845.2  437.35  4865.8  436.60  4872.0  435.75  4906.8  432.54  4937.7  431.96
  4956.9  432.11  4968.5  431.82  4978.7  432.06  4989.0  431.31  4997.2  431.84
  5002.3  431.84  5006.6  430.44  5017.4  429.96  5017.7  429.46  5021.2  429.46
  5021.4  429.96  5029.5  433.70  5039.6  435.11  5059.7  436.98  5079.9  437.95
  5089.7  438.74  5100.0  439.96  5160.4  442.00  5182.9  443.70  5212.8  444.19
#Mann=4,-1,0
  4739.3    0.12       0  4754.5    0.05       0  5017.4    0.04       0
  5021.4    0.05       0
Bank Sta=5017.4,5021.4
Exp/Cntr=0.3,0.1

Type RM Length L Ch R = 1,3043,143,143,143
BEGIN DESCRIPTION:
Lacy 108 1633
END DESCRIPTION:
XS GIS Cut Line= 3
      2733722.18      6863265.17      2733977.15      6863283.09
      2734247.85      6863275.61
#Sta/Elev= 30
  4744.6  440.65  4755.0  440.41  4768.5  439.69  4778.5  439.82  4828.6  437.27
  4888.8  435.51  4901.5  434.80  4928.9  433.97  4958.9  433.54  4969.0  432.99
  4997.1  430.56  5009.1  430.24  5019.1  430.85  5039.1  430.35  5049.1  431.19
  5059.1  430.99  5067.1  429.50  5067.3  429.00  5070.8  429.00  5071.1  429.50
  5079.1  431.96  5099.1  435.41  5109.1  436.13  5119.1  436.21  5159.1  439.64
  5239.1  443.37  5255.5  444.00  5260.5  443.96  5267.6  444.56  5271.0  444.56
#Mann=3,-1,0
  4744.6    0.05       0  5067.1    0.04       0  5071.1    0.05       0
Bank Sta=5067.1,5071.1
Exp/Cntr=0.3,0.1

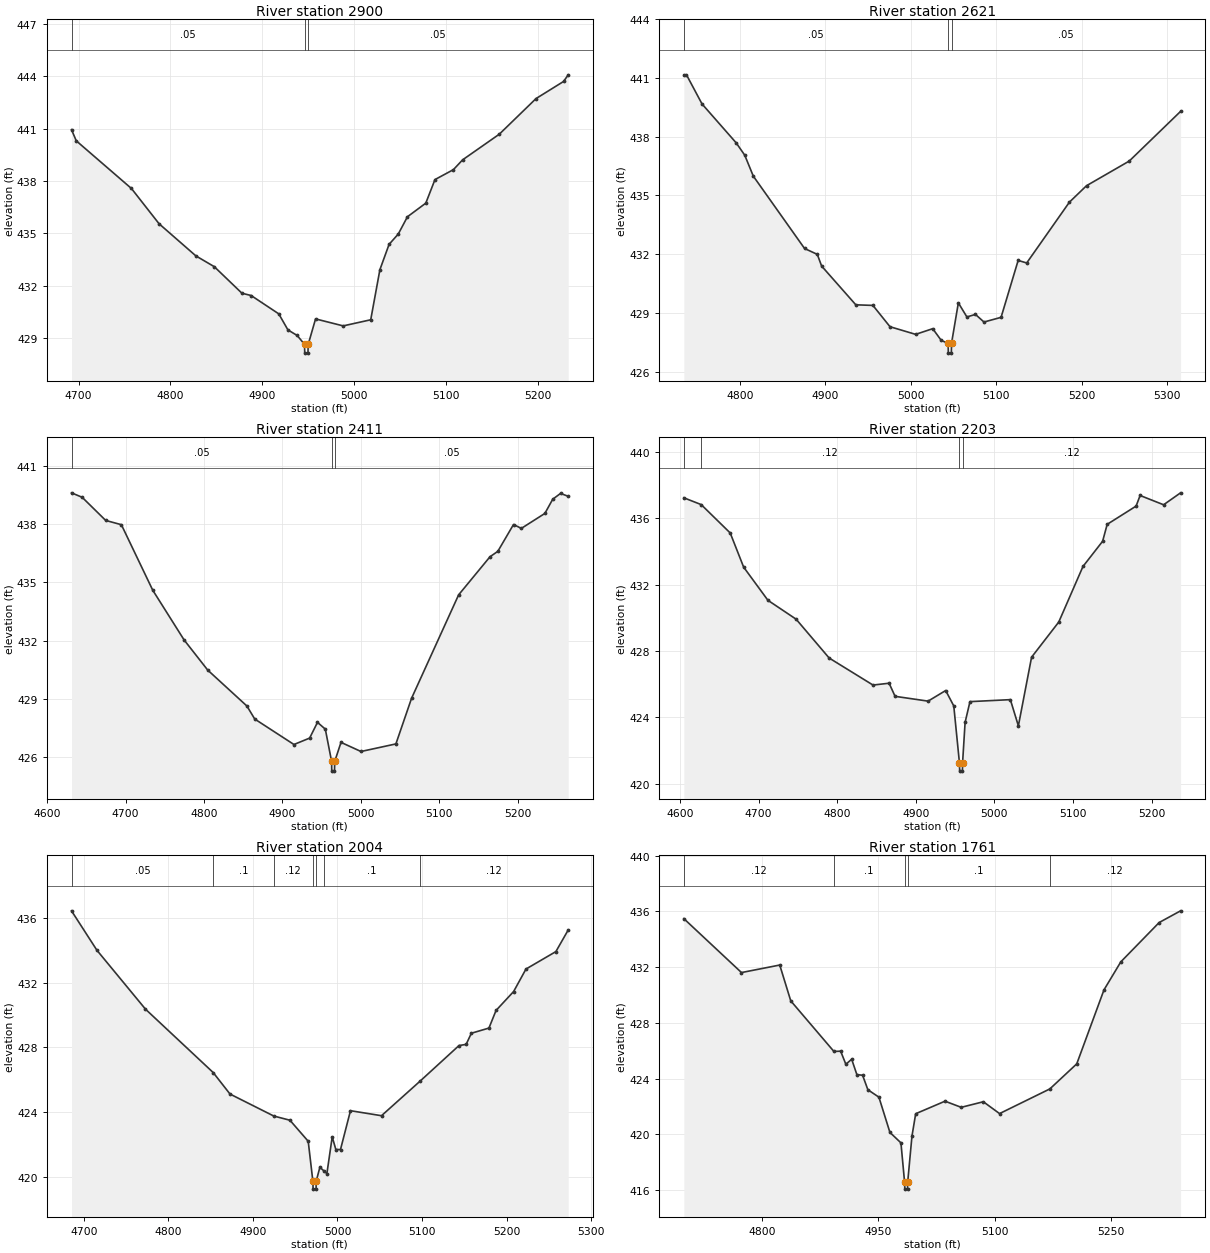
Type RM Length L Ch R = 1,2900,279,279,279
BEGIN DESCRIPTION:
Lacy 108 1632
END DESCRIPTION:
XS GIS Cut Line= 3
      2733710.85      6863389.76      2734016.09      6863412.83
      2734251.11      6863418.39
#Sta/Elev= 30
  4692.2  440.94  4697.4  440.30  4757.5  437.57  4787.6  435.55  4827.7  433.71
  4847.8  433.09  4877.9  431.57  4887.9  431.44  4918.0  430.39  4928.0  429.47
  4938.1  429.15  4946.1  428.64  4946.3  428.14  4949.8  428.14  4950.1  428.64
  4958.1  430.10  4988.2  429.70  5018.2  430.05  5028.2  432.92  5038.2  434.37
  5048.2  434.96  5058.2  435.95  5078.2  436.73  5088.2  438.08  5108.3  438.65
  5118.3  439.21  5158.3  440.68  5198.3  442.72  5228.3  443.70  5233.4  444.08
#Mann=3,-1,0
  4692.2    0.05       0  4946.1    0.05       0  4950.1    0.05       0
Bank Sta=4946.1,4950.1
Exp/Cntr=0.3,0.1

Type RM Length L Ch R = 1,2621,210,210,210
BEGIN DESCRIPTION:
Lacy 108 1626
END DESCRIPTION:
XS GIS Cut Line= 3
      2733694.70      6863647.03      2733956.83      6863645.30
      2734276.09      6863642.94
#Sta/Elev= 30
  4734.3  441.17  4737.4  441.17  4755.6  439.68  4795.6  437.69  4805.6  437.06
  4815.6  435.99  4875.6  432.29  4890.5  431.99  4895.6  431.39  4935.6  429.41
  4955.6  429.38  4975.6  428.29  5005.6  427.90  5025.6  428.19  5035.6  427.59
  5043.6  427.44  5043.9  426.94  5047.4  426.94  5047.6  427.44  5055.6  429.51
  5065.6  428.79  5075.6  428.92  5085.6  428.53  5105.6  428.77  5125.6  431.68
  5135.6  431.55  5185.6  434.66  5205.6  435.50  5255.6  436.76  5315.7  439.30
#Mann=3,-1,0
  4734.3    0.05       0  5043.6    0.05       0  5047.6    0.05       0
Bank Sta=5043.6,5047.6
Exp/Cntr=0.3,0.1

Type RM Length L Ch R = 1,2411,208,208,208
BEGIN DESCRIPTION:
Lacy 108 1627
END DESCRIPTION:
XS GIS Cut Line= 3
      2733702.37      6863821.62      2734072.07      6863816.49
      2734335.83      6863816.78
#Sta/Elev= 30
  4631.0  439.61  4644.6  439.38  4674.6  438.19  4694.6  437.97  4734.6  434.60
  4774.6  432.04  4804.7  430.49  4854.7  428.64  4864.7  427.97  4914.7  426.66
  4934.7  426.99  4944.7  427.80  4954.7  427.45  4962.7  425.79  4962.9  425.29
  4966.4  425.29  4966.7  425.79  4974.7  426.77  5000.2  426.30  5044.7  426.69
  5064.7  429.04  5124.7  434.36  5164.7  436.32  5174.7  436.60  5194.7  437.98
  5204.7  437.78  5234.7  438.55  5244.7  439.28  5254.7  439.58  5264.5  439.43
#Mann=3,-1,0
  4631.0    0.05       0  4962.7    0.05       0  4966.7    0.05       0
Bank Sta=4962.7,4966.7
Exp/Cntr=0.3,0.1

Type RM Length L Ch R = 1,2203,199,199,199
BEGIN DESCRIPTION:
Lacy 108 1631
END DESCRIPTION:
XS GIS Cut Line= 3
      2733792.01      6864079.41      2734182.32      6863985.57
      2734407.01      6863933.41
#Sta/Elev= 30
  4604.8  437.23  4626.9  436.82  4663.8  435.11  4680.9  433.05  4711.8  431.05
  4747.7  429.91  4789.7  427.57  4845.5  425.94  4866.0  426.05  4873.6  425.26
  4915.6  424.97  4938.0  425.61  4948.3  424.68  4955.5  421.25  4955.8  420.75
  4959.3  420.75  4959.5  421.25  4962.7  423.69  4968.9  424.94  5020.3  425.06
  5030.5  423.48  5047.3  427.62  5081.9  429.74  5112.7  433.09  5137.7  434.61
  5143.5  435.63  5180.3  436.73  5185.4  437.37  5215.3  436.81  5236.9  437.53
#Mann=4,-1,0
  4604.8    0.05       0  4626.9    0.12       0  4955.5    0.07       0
  4959.5    0.12       0
Bank Sta=4955.5,4959.5
Exp/Cntr=0.3,0.1

Type RM Length L Ch R = 1,2004,243,243,243
BEGIN DESCRIPTION:
Lacy 108 1630
END DESCRIPTION:
XS GIS Cut Line= 3
      2733971.89      6864359.15      2734223.30      6864170.86
      2734442.22      6864006.92
#Sta/Elev= 30
  4685.4  436.44  4715.5  434.00  4772.9  430.36  4853.0  426.44  4872.9  425.11
  4924.7  423.75  4943.8  423.49  4965.4  422.19  4970.9  419.73  4971.2  419.23
  4974.7  419.23  4974.9  419.73  4979.2  420.58  4983.7  420.37  4987.5  420.19
  4993.8  422.46  4998.1  421.68  5003.6  421.68  5015.4  424.08  5052.1  423.77
  5098.0  425.92  5143.8  428.11  5152.2  428.18  5158.4  428.87  5179.2  429.19
  5187.6  430.28  5208.4  431.45  5223.0  432.84  5258.4  433.92  5273.0  435.26
#Mann=7,-1,0
  4685.4    0.05       0  4853.0     0.1       0  4924.7    0.12       0
  4970.9    0.07       0  4974.9    0.12       0  4983.7     0.1       0
  5098.0    0.12       0
Bank Sta=4970.9,4974.9
Exp/Cntr=0.3,0.1

Type RM Length L Ch R = 1,1761,366,366,366
BEGIN DESCRIPTION:
Lacy 108 1628
END DESCRIPTION:
XS GIS Cut Line= 3
      2734101.96      6864611.98      2734303.83      6864388.80
      2734529.26      6864135.26
#Sta/Elev= 30
  4699.6  435.48  4773.9  431.61  4823.2  432.15  4837.4  429.58  4893.0  425.95
  4901.7  425.97  4908.4  425.03  4915.9  425.39  4922.6  424.29  4930.0  424.24
  4936.8  423.20  4951.0  422.67  4965.2  420.14  4979.4  419.39  4984.1  416.57
  4984.4  416.07  4987.9  416.07  4988.1  416.57  4993.6  419.87  4998.4  421.48
  5036.2  422.38  5057.1  421.94  5085.6  422.34  5106.5  421.49  5171.3  423.26
  5206.0  425.06  5241.1  430.37  5262.8  432.38  5312.2  435.20  5339.8  436.04
#Mann=5,-1,0
  4699.6    0.12       0  4893.0     0.1       0  4984.1    0.07       0
  4988.1     0.1       0  5171.3    0.12       0
Bank Sta=4984.1,4988.1
Exp/Cntr=0.3,0.1

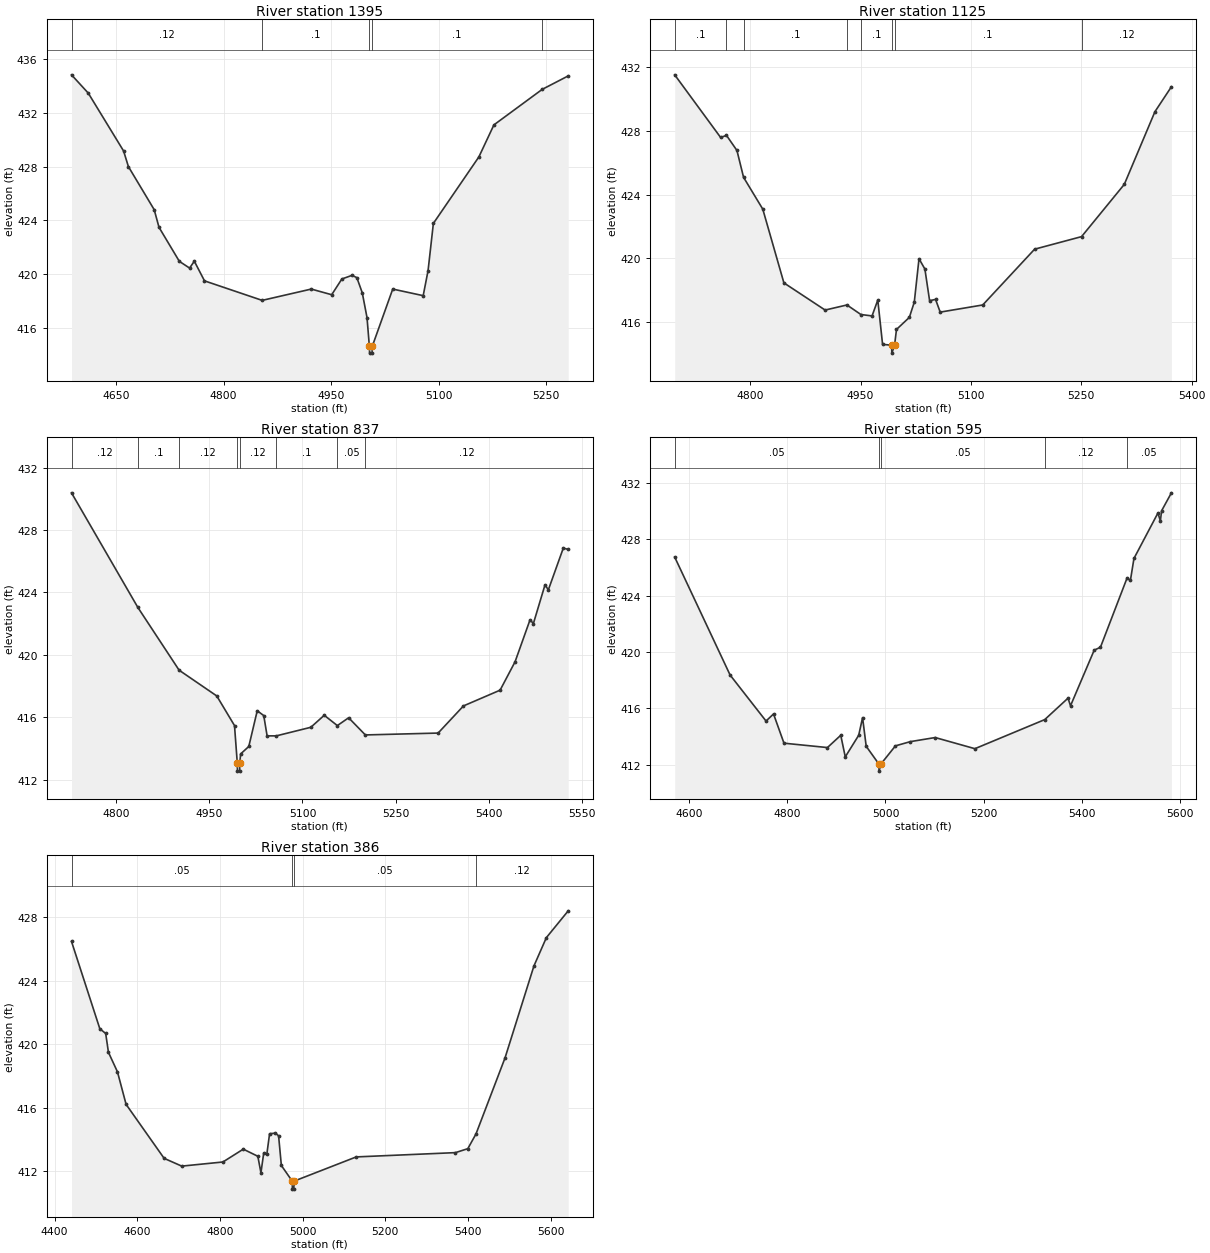
Type RM Length L Ch R = 1,1395,270,270,270
BEGIN DESCRIPTION:
Lacy 108 1629
END DESCRIPTION:
XS GIS Cut Line= 3
      2734321.71      6864839.15      2734597.99      6864524.58
      2734784.21      6864322.86
#Sta/Elev= 30
  4587.8  434.82  4611.2  433.46  4660.5  429.16  4667.2  428.00  4703.2  424.80
  4709.9  423.49  4738.3  420.96  4752.6  420.46  4759.2  420.97  4773.4  419.51
  4853.9  418.06  4922.4  418.90  4950.9  418.48  4965.1  419.65  4979.3  419.92
  4986.0  419.75  4993.6  418.62  5000.2  416.78  5003.5  414.64  5003.8  414.14
  5007.3  414.14  5007.5  414.64  5036.1  418.90  5078.6  418.41  5085.4  420.27
  5092.8  423.78  5156.3  428.72  5177.3  431.10  5244.7  433.74  5281.0  434.74
#Mann=5,-1,0
  4587.8    0.12       0  4853.9     0.1       0  5003.5    0.07       0
  5007.5     0.1       0  5244.7    0.05       0
Bank Sta=5003.5,5007.5
Exp/Cntr=0.3,0.1

Type RM Length L Ch R = 1,1125,288,288,288
BEGIN DESCRIPTION:
Lacy 108 1625
END DESCRIPTION:
XS GIS Cut Line= 3
      2734523.22      6864986.58      2734716.90      6864753.33
      2734947.27      6864461.47
#Sta/Elev= 30
  4697.5  431.53  4759.9  427.59  4767.9  427.72  4782.1  426.77  4791.1  425.08
  4817.2  423.08  4845.9  418.44  4901.9  416.73  4931.6  417.05  4950.5  416.45
  4965.7  416.36  4973.5  417.36  4980.0  414.57  4992.3  414.52  4992.6  414.02
  4996.3  414.52  4998.9  415.51  5016.4  416.27  5023.1  417.23  5029.5  419.96
  5037.5  419.31  5043.9  417.32  5052.0  417.40  5058.3  416.60  5116.1  417.05
  5186.6  420.56  5250.4  421.35  5308.5  424.64  5350.1  429.21  5372.5  430.78
#Mann=8,-1,0
  4697.5     0.1       0  4767.9    0.12       0  4791.1     0.1       0
  4931.6    0.12       0  4950.5     0.1       0  4992.3    0.07       0
  4996.3     0.1       0  5250.4    0.12       0
Bank Sta=4992.3,4996.3
Exp/Cntr=0.3,0.1

Type RM Length L Ch R = 1,837,242,242,242
BEGIN DESCRIPTION:
Lacy 108 1624
END DESCRIPTION:
XS GIS Cut Line= 3
      2734648.92      6865213.48      2734825.17      6865005.62
      2735023.21      6864516.84
#Sta/Elev= 30
  4728.1  430.38  4835.0  423.03  4901.4  419.01  4962.0  417.36  4990.6  415.46
  4995.1  413.04  4995.4  412.54  4998.9  412.54  4999.1  413.04  5000.4  413.64
  5013.6  414.12  5027.2  416.41  5037.7  416.10  5043.1  414.80  5057.9  414.80
  5113.5  415.35  5135.1  416.12  5156.2  415.46  5174.4  415.96  5201.3  414.86
  5318.5  414.98  5359.3  416.72  5418.3  417.73  5442.4  419.55  5466.5  422.24
  5471.9  422.00  5490.6  424.48  5496.0  424.16  5520.1  426.84  5528.0  426.75
#Mann=8,-1,0
  4728.1    0.12       0  4835.0     0.1       0  4901.4    0.12       0
  4995.1    0.07       0  4999.1    0.12       0  5057.9     0.1       0
  5156.2    0.05       0  5201.3    0.12       0
Bank Sta=4995.1,4999.1
Exp/Cntr=0.3,0.1

Type RM Length L Ch R = 1,595,209,209,209
BEGIN DESCRIPTION:
Lacy 108 1623
END DESCRIPTION:
XS GIS Cut Line= 4
      2734824.29      6865326.67      2735049.61      6864963.36
      2735141.80      6864404.66      2735143.89      6864385.43
#Sta/Elev= 30
  4570.1  426.73  4683.1  418.37  4756.4  415.11  4771.7  415.61  4793.0  413.54
  4881.6  413.23  4908.8  414.10  4918.0  412.57  4945.4  414.10  4953.3  415.35
  4960.7  413.32  4986.6  412.06  4986.9  411.56  4990.6  412.06  5020.3  413.35
  5050.7  413.65  5101.4  413.94  5182.4  413.15  5324.8  415.21  5372.3  416.73
  5377.4  416.19  5425.7  420.13  5438.5  420.34  5492.7  425.24  5499.6  425.08
  5506.8  426.63  5555.7  429.85  5560.7  429.29  5563.2  430.01  5583.2  431.28
#Mann=5,-1,0
  4570.1    0.05       0  4986.6    0.04       0  4990.6    0.05       0
  5324.8    0.12       0  5492.7    0.05       0
Bank Sta=4986.6,4990.6
Exp/Cntr=0.3,0.1

Type RM Length L Ch R = 1,386,0,0,0
BEGIN DESCRIPTION:
Lacy 108 1622
END DESCRIPTION:
XS GIS Cut Line= 3
      2734839.28      6865331.01      2735258.14      6864960.82
      2735254.73      6864318.14
#Sta/Elev= 30
  4441.0  426.48  4509.5  420.98  4523.7  420.68  4530.4  419.49  4552.2  418.26
  4573.1  416.21  4665.1  412.81  4707.7  412.32  4807.3  412.58  4856.6  413.39
  4891.8  412.94  4899.3  411.90  4906.0  413.14  4913.5  413.06  4920.2  414.36
  4934.4  414.40  4942.0  414.23  4948.7  412.36  4975.1  411.37  4975.4  410.87
  4978.9  410.87  4979.1  411.37  5129.8  412.90  5369.8  413.17  5399.8  413.42
  5419.6  414.35  5489.8  419.14  5559.8  424.94  5589.8  426.72  5642.7  428.41
#Mann=4,-1,0
  4441.0    0.05       0  4975.1    0.04       0  4979.1    0.05       0
  5419.6    0.12       0
Bank Sta=4975.1,4979.1
Exp/Cntr=0.3,0.1

Chan Stop Cuts=-1