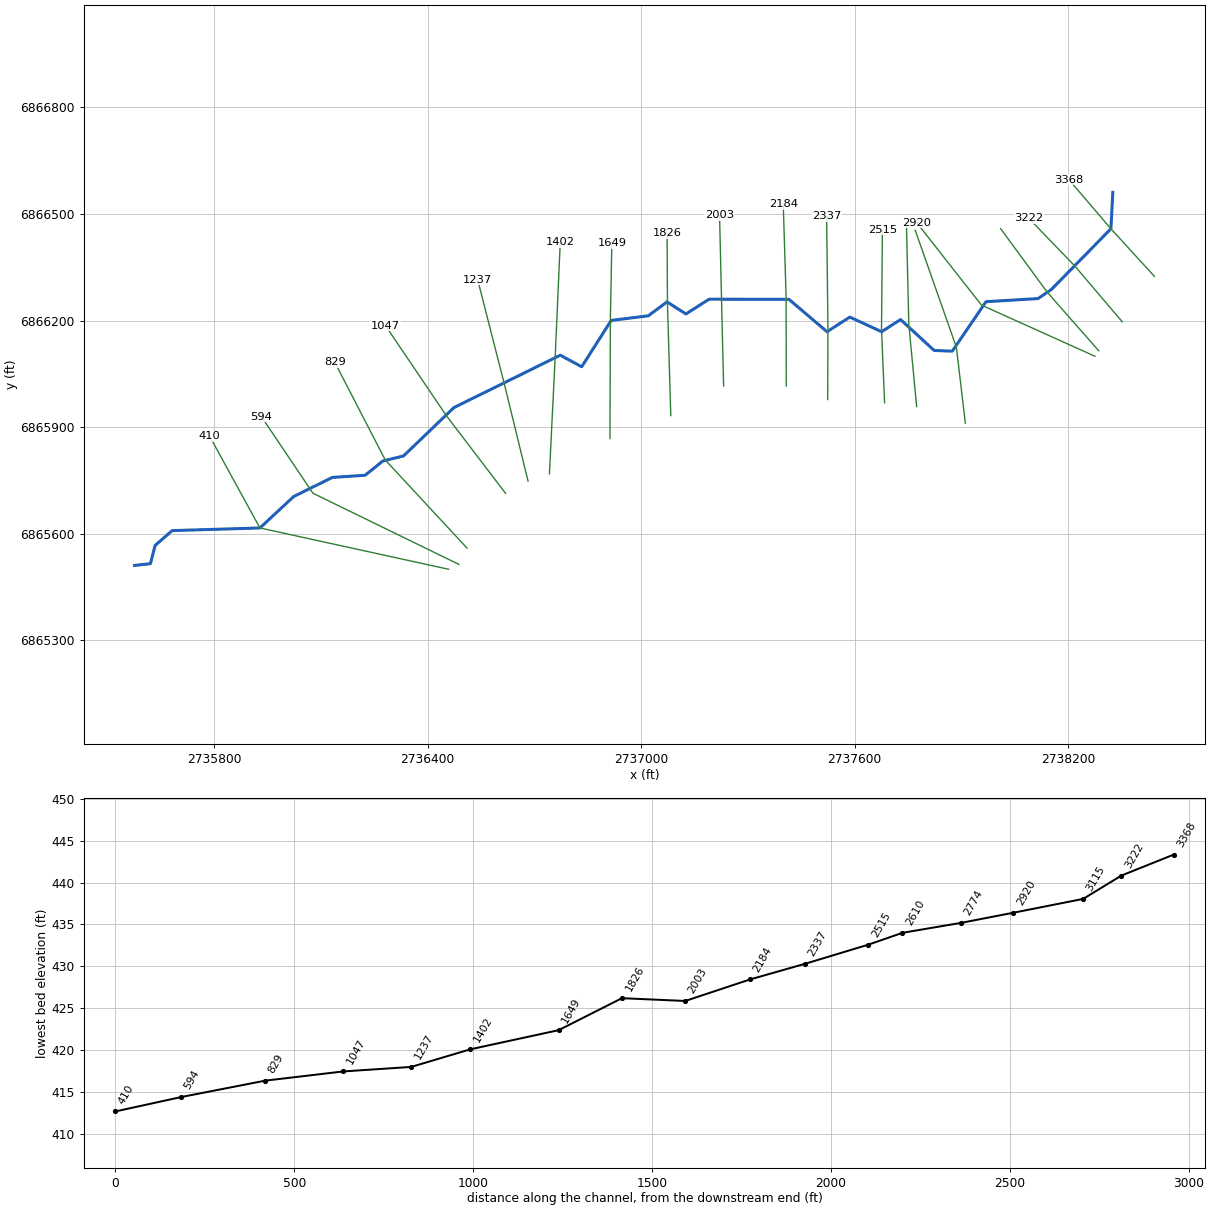
--- Lacy 109.prj (project) ---

Proj Title=Lacy 109 Base Level Engineering
Current Plan=p01
Default Exp/Contr=0.3,0.1
English Units
Geom File=g01
Flow File=f01
Plan File=p01
BEGIN DESCRIPTION:
Lacy 109
END DESCRIPTION:

--- Lacy 109.p01 (plan) ---

Plan Title=Multiple Run
Short Identifier=Multiple
Geom File=g01
Flow File=f01
Subcritical Flow
K Sum by GR= 0
Std Step Tol= 0.01
Critical Tol= 0.01
Num of Std Step Trials= 20
Max Error Tol= 0.3
Flow Tol Ratio= 0.001
Split Flow NTrial= 30
Split Flow Tol= 0.02
Split Flow Ratio= 0.02
Log Output Level= 0
Friction Slope Method= 1
Unsteady Friction Slope Method= 2
Unsteady Bridges Friction Slope Method= 1
Parabolic Critical Depth
Global Vel Dist=  1 , 1 , 1
Global Log Level= 0
CheckData=True
Encroach Param= -1, 0, 0, 0
BEGIN DESCRIPTION:
Multiple Run
END DESCRIPTION:

--- Lacy 109.f01 (steady flow) ---

Flow Title=Multiple
Number of Profiles=7
Profile Names=10-year,25-year,50-year,1pct_min,100-year,1pct_plu,500-year
River Rch & RM= Lacy 109,Reach-1,3368
     323     416     489     286     572    1141     777
Boundary for River Rch & Prof#=Lacy 109,Reach-1,1
Up Type=0
Dn Type=3
Dn Slope=0.005
Boundary for River Rch & Prof#=Lacy 109,Reach-1,2
Up Type=0
Dn Type=3
Dn Slope=0.005
Boundary for River Rch & Prof#=Lacy 109,Reach-1,3
Up Type=0
Dn Type=3
Dn Slope=0.005
Boundary for River Rch & Prof#=Lacy 109,Reach-1,4
Up Type=0
Dn Type=3
Dn Slope=0.005
Boundary for River Rch & Prof#=Lacy 109,Reach-1,5
Up Type=0
Dn Type=3
Dn Slope=0.005
Boundary for River Rch & Prof#=Lacy 109,Reach-1,6
Up Type=0
Dn Type=3
Dn Slope=0.005
Boundary for River Rch & Prof#=Lacy 109,Reach-1,7
Up Type=0
Dn Type=3
Dn Slope=0.005

--- Lacy 109.g01 (geometry) ---

Geom Title=Existing Conditions

River Reach=Lacy 109,Reach-1
Reach XY= 30
      2738326.00      6866561.00      2738320.65      6866458.50
      2738152.87      6866287.17      2738115.56      6866262.06
      2737969.53      6866253.30      2737874.57      6866114.01
      2737823.73      6866116.08      2737729.33      6866202.99
      2737676.09      6866168.84      2737586.64      6866210.01
      2737522.60      6866168.83      2737415.57      6866259.94
      2737191.16      6866260.35      2737125.90      6866218.79
      2737072.78      6866252.72      2737020.10      6866213.55
      2736915.90      6866200.61      2736832.95      6866070.18
      2736772.78      6866102.75      2736473.70      6865955.17
      2736332.06      6865819.14      2736273.83      6865804.86
      2736224.42      6865764.83      2736131.97      6865758.67
      2736023.71      6865705.15      2735928.45      6865616.47
      2735681.68      6865609.01      2735633.91      6865567.27
      2735620.65      6865515.96      2735576.00      6865511.00

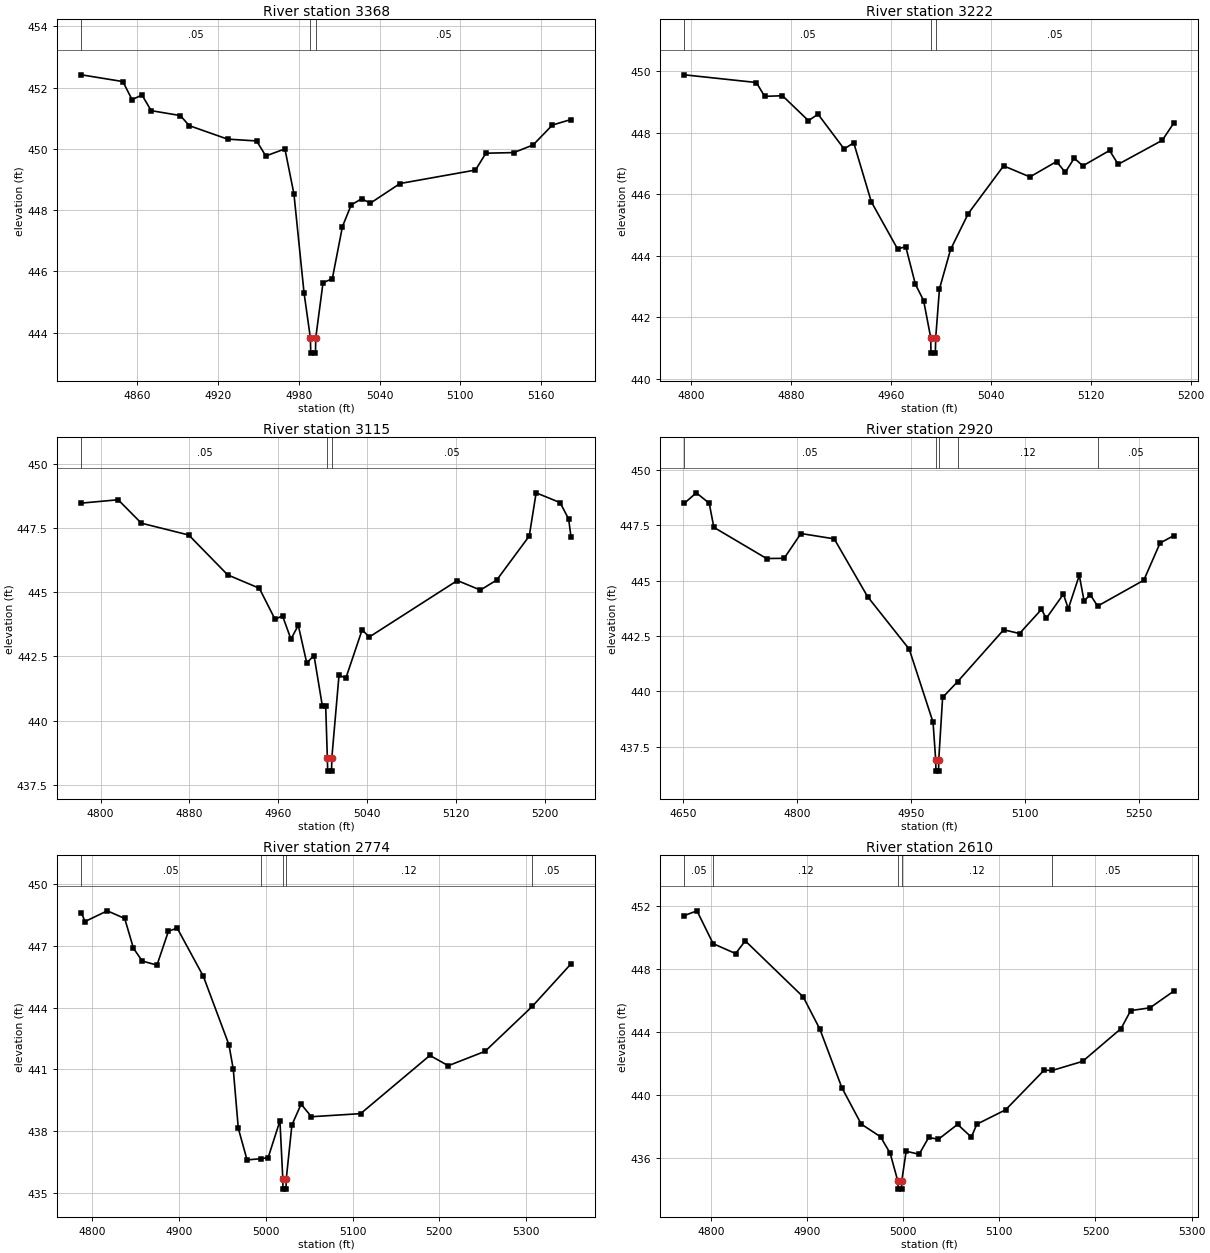
Type RM Length L Ch R = 1,3368,146,146,146
BEGIN DESCRIPTION:
Lacy 109 1656
END DESCRIPTION:
XS GIS Cut Line= 3
      2738442.94      6866324.51      2738320.65      6866458.50
      2738202.43      6866597.01
#Sta/Elev= 30
  4818.6  452.42  4849.4  452.20  4856.2  451.61  4863.6  451.76  4870.4  451.25
  4892.0  451.09  4898.7  450.76  4927.1  450.32  4948.7  450.26  4955.5  449.77
  4969.7  450.00  4976.4  448.53  4983.9  445.30  4988.6  443.83  4988.9  443.33
  4992.4  443.33  4992.6  443.83  4998.0  445.63  5004.9  445.76  5012.4  447.46
  5018.9  448.17  5026.6  448.37  5033.2  448.23  5055.2  448.87  5111.2  449.31
  5118.9  449.86  5139.7  449.88  5154.0  450.13  5168.3  450.78  5182.1  450.96
#Mann=3,-1,0
  4818.6    0.05       0  4988.6    0.04       0  4992.6    0.05       0
Bank Sta=4988.6,4992.6
Exp/Cntr=0.3,0.1

Type RM Length L Ch R = 1,3222,107,107,107
BEGIN DESCRIPTION:
Lacy 109 1655
END DESCRIPTION:
XS GIS Cut Line= 3
      2738352.40      6866196.79      2738219.31      6866353.63
      2738089.80      6866487.97
#Sta/Elev= 30
  4794.3  449.88  4852.0  449.63  4858.6  449.18  4872.9  449.20  4893.7  448.39
  4901.4  448.60  4922.3  447.47  4930.0  447.67  4944.1  445.75  4965.1  444.22
  4971.7  444.29  4979.4  443.07  4986.0  442.54  4991.7  441.33  4991.9  440.83
  4995.4  440.83  4995.7  441.33  4998.7  442.92  5007.6  444.20  5021.8  445.37
  5050.1  446.92  5071.2  446.56  5092.5  447.06  5099.5  446.71  5106.7  447.17
  5113.6  446.92  5135.0  447.42  5141.9  446.97  5177.2  447.75  5186.6  448.32
#Mann=3,-1,0
  4794.3    0.05       0  4991.7    0.04       0  4995.7    0.05       0
Bank Sta=4991.7,4995.7
Exp/Cntr=0.3,0.1

Type RM Length L Ch R = 1,3115,195,195,195
BEGIN DESCRIPTION:
Lacy 109 1654
END DESCRIPTION:
XS GIS Cut Line= 3
      2738286.42      6866115.16      2738141.22      6866280.55
      2738010.65      6866458.88
#Sta/Elev= 30
  4782.7  448.46  4815.8  448.59  4836.7  447.68  4879.4  447.22  4914.5  445.67
  4943.0  445.15  4957.2  443.94  4963.9  444.08  4971.5  443.17  4978.1  443.71
  4985.7  442.25  4992.3  442.53  4999.8  440.57  5002.8  440.57  5004.3  438.54
  5004.6  438.04  5008.1  438.04  5008.3  438.54  5014.8  441.77  5021.0  441.66
  5035.7  443.54  5041.9  443.25  5121.4  445.45  5142.2  445.08  5156.9  445.47
  5186.2  447.18  5192.4  448.86  5214.0  448.48  5221.7  447.84  5223.8  447.15
#Mann=3,-1,0
  4782.7    0.05       0  5004.3    0.04       0  5008.3    0.05       0
Bank Sta=5004.3,5008.3
Exp/Cntr=0.3,0.1

Type RM Length L Ch R = 1,2920,146,146,146
BEGIN DESCRIPTION:
Lacy 109 1650
END DESCRIPTION:
XS GIS Cut Line= 3
      2738275.78      6866099.75      2737956.77      6866243.69
      2737775.09      6866475.36
#Sta/Elev= 30
  4651.4  448.50  4667.1  448.97  4684.1  448.50  4690.2  447.41  4759.6  446.00
  4782.7  446.01  4804.8  447.13  4848.6  446.89  4892.5  444.28  4947.4  441.90
  4978.7  438.60  4982.2  436.89  4982.5  436.39  4986.0  436.39  4986.2  436.89
  4991.3  439.72  5010.9  440.43  5071.7  442.78  5092.5  442.61  5121.4  443.70
  5127.8  443.30  5150.3  444.39  5156.7  443.73  5171.2  445.24  5177.5  444.08
  5185.6  444.37  5195.3  443.85  5256.1  445.02  5277.5  446.70  5295.8  447.04
#Mann=5,-1,0
  4651.4    0.05       0  4982.2    0.04       0  4986.2    0.05       0
  5010.9    0.12       0  5195.3    0.05       0
Bank Sta=4982.2,4986.2
Exp/Cntr=0.3,0.1

Type RM Length L Ch R = 1,2774,164,164,164
BEGIN DESCRIPTION:
Lacy 109 1651
END DESCRIPTION:
XS GIS Cut Line= 3
      2737911.45      6865911.41      2737886.19      6866125.12
      2737770.54      6866454.40
#Sta/Elev= 30
  4787.5  448.61  4791.7  448.19  4817.3  448.71  4837.4  448.34  4847.5  446.89
  4857.6  446.27  4874.6  446.07  4887.8  447.72  4897.9  447.87  4928.1  445.52
  4957.5  442.20  4962.5  441.02  4968.3  438.14  4978.4  436.60  4994.4  436.66
  5002.7  436.71  5016.3  438.50  5019.6  435.68  5019.8  435.18  5023.3  435.18
  5023.6  435.68  5030.1  438.30  5040.7  439.31  5052.6  438.70  5109.3  438.85
  5189.1  441.68  5210.3  441.18  5252.7  441.88  5307.0  444.06  5351.7  446.13
#Mann=5,-1,0
  4787.5    0.05       0  4994.4    0.12       0  5019.6    0.07       0
  5023.6    0.12       0  5307.0    0.05       0
Bank Sta=5019.6,5023.6
Exp/Cntr=0.3,0.1

Type RM Length L Ch R = 1,2610,95,95,95
BEGIN DESCRIPTION:
Lacy 109 1652
END DESCRIPTION:
XS GIS Cut Line= 3
      2737774.56      6865957.96      2737752.56      6866189.05
      2737745.98      6866465.94
#Sta/Elev= 30
  4772.5  451.40  4785.6  451.70  4802.4  449.61  4825.8  448.98  4835.8  449.79
  4896.1  446.22  4913.4  444.17  4936.3  440.44  4956.4  438.13  4976.5  437.32
  4986.5  436.27  4994.5  434.49  4994.8  433.99  4998.3  433.99  4998.5  434.49
  5003.1  436.40  5016.6  436.21  5026.6  437.28  5036.6  437.16  5056.6  438.11
  5070.9  437.30  5076.6  438.12  5106.6  439.04  5146.6  441.56  5154.9  441.54
  5186.6  442.12  5226.6  444.21  5236.6  445.35  5256.7  445.53  5281.6  446.60
#Mann=5,-1,0
  4772.5    0.05       0  4802.4    0.12       0  4994.5    0.07       0
  4998.5    0.12       0  5154.9    0.05       0
Bank Sta=4994.5,4998.5
Exp/Cntr=0.3,0.1

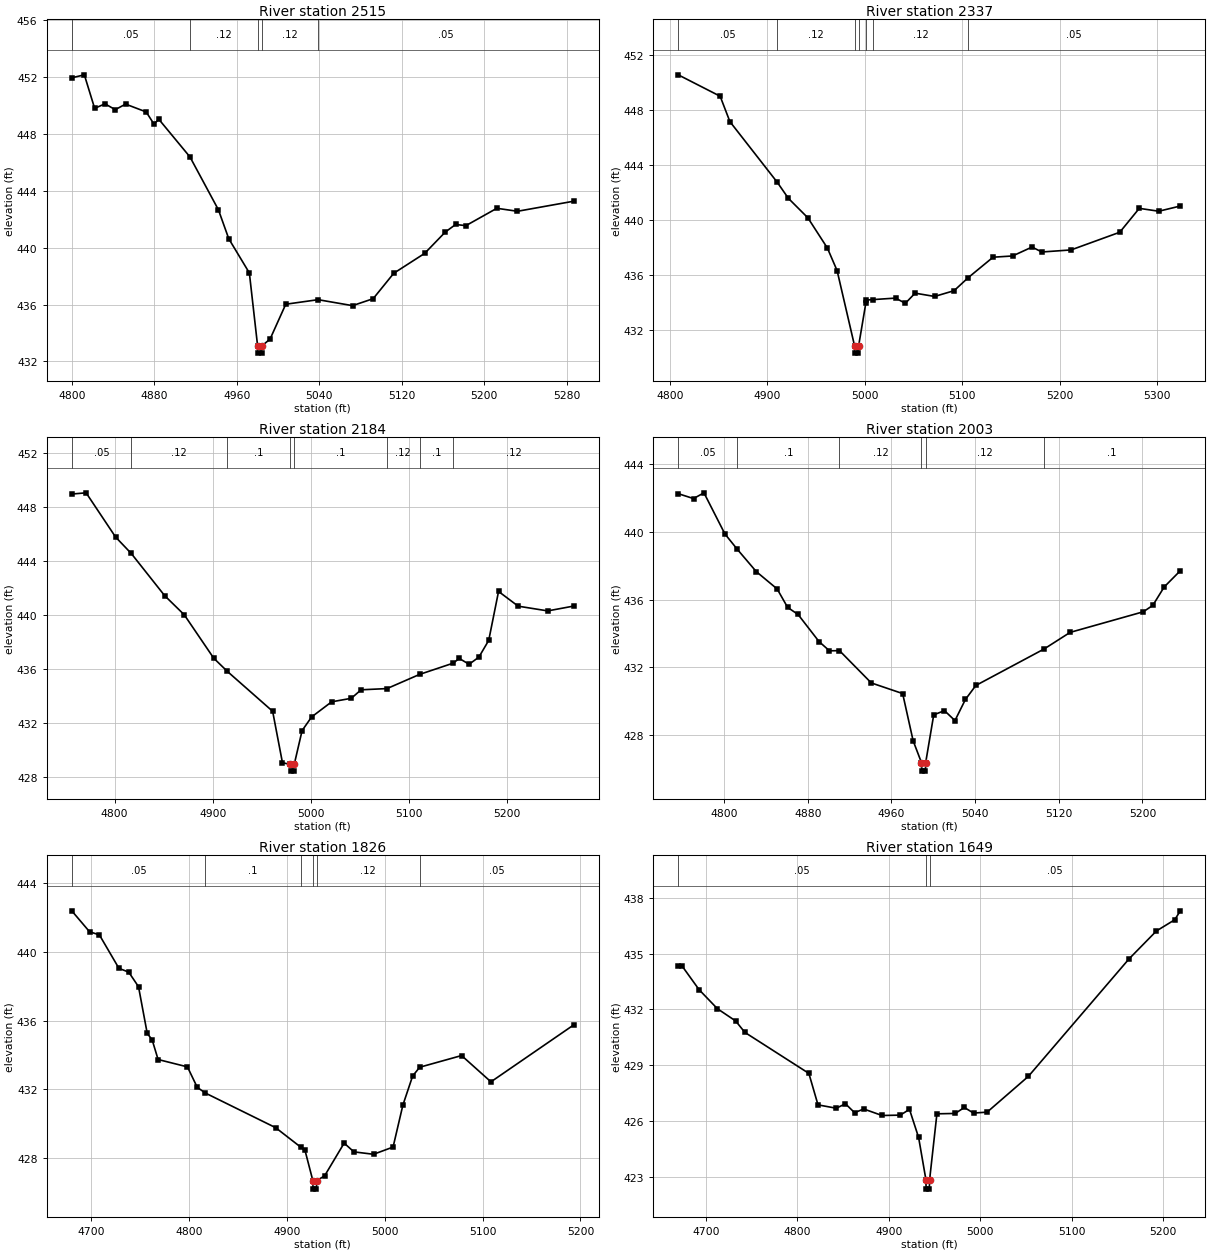
Type RM Length L Ch R = 1,2515,178,178,178
BEGIN DESCRIPTION:
Lacy 109 1649
END DESCRIPTION:
XS GIS Cut Line= 3
      2737684.39      6865968.82      2737675.79      6866176.41
      2737678.33      6866455.73
#Sta/Elev= 30
  4799.8  451.95  4812.0  452.16  4822.0  449.80  4832.0  450.12  4842.0  449.71
  4852.0  450.10  4872.0  449.55  4879.4  448.71  4884.4  449.02  4914.5  446.38
  4942.1  442.66  4952.1  440.63  4972.1  438.22  4980.1  433.08  4980.4  432.58
  4983.9  432.58  4984.1  433.08  4992.2  433.57  5007.4  436.02  5038.8  436.34
  5072.2  435.92  5092.2  436.41  5112.2  438.20  5142.2  439.60  5162.2  441.10
  5172.2  441.63  5182.2  441.55  5212.2  442.77  5232.2  442.56  5286.9  443.27
#Mann=5,-1,0
  4799.8    0.05       0  4914.5    0.12       0  4980.1    0.07       0
  4984.1    0.12       0  5038.8    0.05       0
Bank Sta=4980.1,4984.1
Exp/Cntr=0.3,0.1

Type RM Length L Ch R = 1,2337,153,153,153
BEGIN DESCRIPTION:
Lacy 109 1647
END DESCRIPTION:
XS GIS Cut Line= 3
      2737524.53      6865978.02      2737525.21      6866181.49
      2737521.48      6866493.10
#Sta/Elev= 30
  4808.5  450.56  4851.5  449.00  4861.5  447.15  4910.2  442.72  4921.5  441.56
  4941.5  440.14  4961.5  437.94  4971.5  436.29  4989.5  430.78  4989.7  430.28
  4993.2  430.28  4993.5  430.78  5000.9  433.90  5001.5  434.15  5008.2  434.18
  5031.5  434.29  5041.5  433.91  5051.5  434.65  5071.5  434.41  5091.5  434.83
  5106.0  435.78  5131.5  437.27  5151.5  437.36  5171.5  438.01  5181.5  437.65
  5211.5  437.80  5261.5  439.09  5281.5  440.83  5301.5  440.62  5323.6  441.00
#Mann=7,-1,0
  4808.5    0.05       0  4910.2    0.12       0  4989.5    0.07       0
  4993.5    0.12       0  5000.9     0.1       0  5008.2    0.12       0
  5106.0    0.05       0
Bank Sta=4989.5,4993.5
Exp/Cntr=0.3,0.1

Type RM Length L Ch R = 1,2184,181,181,181
BEGIN DESCRIPTION:
Lacy 109 1648
END DESCRIPTION:
XS GIS Cut Line= 3
      2737408.02      6866016.35      2737407.62      6866265.29
      2737399.57      6866527.63
#Sta/Elev= 30
  4756.4  448.93  4771.0  449.02  4801.0  445.75  4817.0  444.53  4851.0  441.41
  4871.0  439.99  4901.0  436.78  4914.9  435.80  4961.0  432.85  4971.0  429.04
  4979.0  428.92  4979.3  428.42  4982.8  428.42  4983.0  428.92  4991.0  431.42
  5000.7  432.43  5021.1  433.55  5041.1  433.81  5051.1  434.44  5077.5  434.53
  5110.7  435.58  5144.8  436.41  5151.1  436.76  5161.1  436.33  5171.1  436.86
  5181.1  438.10  5191.1  441.72  5211.1  440.63  5241.2  440.28  5267.8  440.64
#Mann=8,-1,0
  4756.4    0.05       0  4817.0    0.12       0  4914.9     0.1       0
  4979.0    0.07       0  4983.0     0.1       0  5077.5    0.12       0
  5110.7     0.1       0  5144.8    0.12       0
Bank Sta=4979,4983
Exp/Cntr=0.3,0.1

Type RM Length L Ch R = 1,2003,177,177,177
BEGIN DESCRIPTION:
Lacy 109 1646
END DESCRIPTION:
XS GIS Cut Line= 3
      2737231.87      6866016.45      2737225.96      6866265.30
      2737220.48      6866496.42
#Sta/Elev= 30
  4756.1  442.27  4770.7  441.98  4780.7  442.32  4800.7  439.89  4812.4  438.99
  4830.7  437.66  4850.7  436.63  4860.7  435.54  4870.7  435.12  4890.7  433.52
  4900.7  432.97  4910.3  432.98  4940.7  431.07  4970.7  430.44  4980.7  427.65
  4988.7  426.35  4989.0  425.85  4992.5  425.85  4992.7  426.35  5000.4  429.18
  5010.7  429.43  5020.7  428.84  5030.7  430.09  5040.7  430.92  5106.0  433.08
  5130.8  434.06  5200.8  435.28  5209.9  435.66  5220.8  436.75  5236.2  437.71
#Mann=6,-1,0
  4756.1    0.05       0  4812.4     0.1       0  4910.3    0.12       0
  4988.7    0.07       0  4992.7    0.12       0  5106.0     0.1       0
Bank Sta=4988.7,4992.7
Exp/Cntr=0.3,0.1

Type RM Length L Ch R = 1,1826,177,177,177
BEGIN DESCRIPTION:
Lacy 109 1645
END DESCRIPTION:
XS GIS Cut Line= 3
      2737083.39      6865932.84      2737074.01      6866250.87
      2737073.05      6866445.70
#Sta/Elev= 30
  4680.3  442.39  4698.5  441.17  4708.5  440.99  4728.5  439.04  4738.5  438.82
  4748.5  437.97  4757.4  435.25  4762.4  434.88  4768.5  433.73  4798.5  433.30
  4808.5  432.11  4816.7  431.78  4888.6  429.76  4914.6  428.61  4918.6  428.44
  4926.6  426.68  4926.8  426.18  4930.3  426.18  4930.6  426.68  4938.6  426.95
  4958.6  428.86  4968.6  428.35  4988.6  428.21  5008.6  428.63  5018.6  431.07
  5028.6  432.77  5035.8  433.28  5078.6  433.96  5108.6  432.43  5193.3  435.75
#Mann=6,-1,0
  4680.3    0.05       0  4816.7     0.1       0  4914.6    0.12       0
  4926.6    0.07       0  4930.6    0.12       0  5035.8    0.05       0
Bank Sta=4926.6,4930.6
Exp/Cntr=0.3,0.1

Type RM Length L Ch R = 1,1649,247,247,247
BEGIN DESCRIPTION:
Lacy 109 1641
END DESCRIPTION:
XS GIS Cut Line= 3
      2736912.44      6865868.24      2736913.60      6866205.94
      2736917.72      6866417.09
#Sta/Elev= 30
  4669.8  434.35  4673.7  434.35  4692.6  433.06  4712.6  432.04  4732.6  431.38
  4742.6  430.77  4812.6  428.57  4822.6  426.88  4842.6  426.70  4852.6  426.94
  4862.6  426.46  4872.6  426.66  4892.6  426.31  4912.6  426.33  4922.6  426.64
  4932.6  425.13  4940.6  422.86  4940.8  422.36  4944.3  422.36  4944.6  422.86
  4952.6  426.40  4972.6  426.42  4982.6  426.74  4992.6  426.44  5007.5  426.49
  5052.6  428.41  5162.6  434.71  5192.6  436.21  5212.6  436.81  5218.7  437.29
#Mann=3,-1,0
  4669.8    0.05       0  4940.6    0.05       0  4944.6    0.05       0
Bank Sta=4940.6,4944.6
Exp/Cntr=0.3,0.1

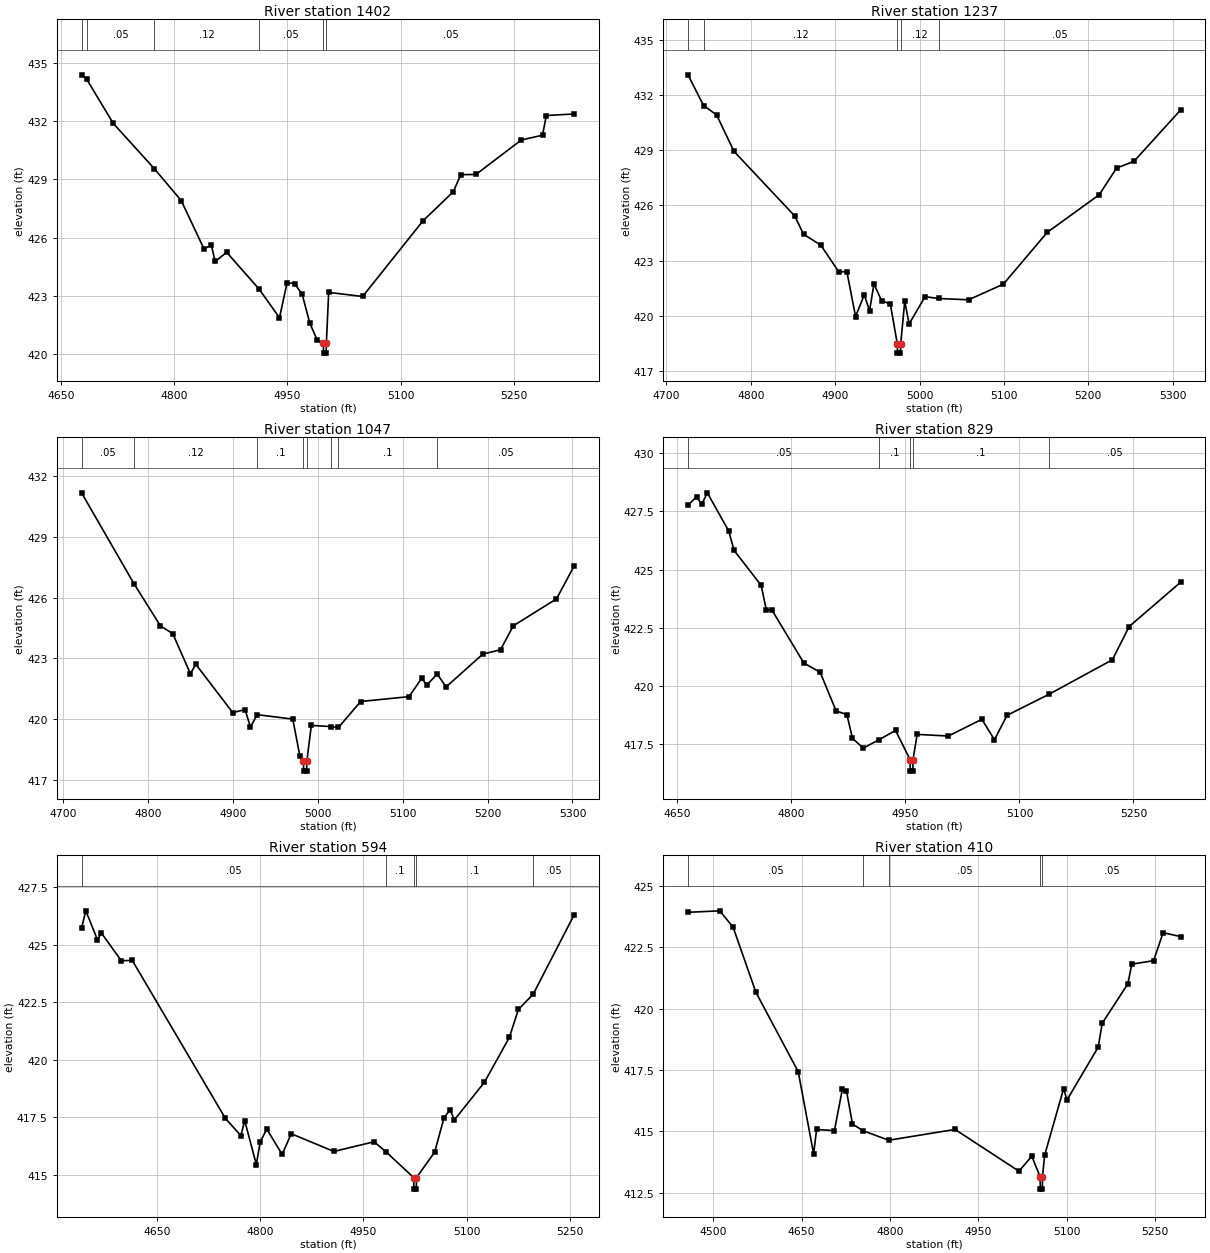
Type RM Length L Ch R = 1,1402,165,165,165
BEGIN DESCRIPTION:
Lacy 109 1642
END DESCRIPTION:
XS GIS Cut Line= 3
      2736742.31      6865768.97      2736758.40      6866096.18
      2736772.71      6866421.26
#Sta/Elev= 30
  4677.1  434.37  4683.8  434.15  4719.2  431.87  4773.7  429.54  4809.3  427.90
  4839.3  425.43  4849.1  425.61  4854.2  424.78  4869.4  425.25  4912.4  423.36
  4939.4  421.89  4949.5  423.69  4959.5  423.64  4969.5  423.09  4979.5  421.62
  4989.5  420.73  4997.5  420.57  4997.8  420.07  5001.3  420.07  5001.5  420.57
  5004.6  423.19  5049.6  422.98  5129.6  426.87  5169.7  428.36  5179.7  429.24
  5199.7  429.25  5259.8  431.02  5288.0  431.27  5293.0  432.28  5330.1  432.36
#Mann=6,-1,0
  4677.1    0.12       0  4683.8    0.05       0  4773.7    0.12       0
  4912.4    0.05       0  4997.5    0.04       0  5001.5    0.05       0
Bank Sta=4997.5,5001.5
Exp/Cntr=0.3,0.1

Type RM Length L Ch R = 1,1237,190,190,190
BEGIN DESCRIPTION:
Lacy 109 1644
END DESCRIPTION:
XS GIS Cut Line= 3
      2736682.25      6865748.04      2736617.21      6866014.90
      2736540.70      6866314.72
#Sta/Elev= 30
  4725.6  433.10  4744.0  431.43  4759.5  430.92  4780.1  428.94  4852.2  425.42
  4862.6  424.43  4883.0  423.84  4904.3  422.39  4913.9  422.40  4924.2  419.96
  4934.5  421.14  4940.8  420.28  4946.0  421.73  4955.1  420.82  4965.4  420.64
  4973.7  418.47  4973.9  417.97  4977.4  417.97  4977.7  418.47  4982.5  420.79
  4987.7  419.56  5006.6  421.04  5022.6  420.94  5058.2  420.87  5099.4  421.72
  5151.5  424.54  5213.0  426.58  5233.6  428.03  5254.3  428.40  5309.7  431.20
#Mann=5,-1,0
  4725.6    0.05       0  4744.0    0.12       0  4973.7    0.07       0
  4977.7    0.12       0  5022.6    0.05       0
Bank Sta=4973.7,4977.7
Exp/Cntr=0.3,0.1

Type RM Length L Ch R = 1,1047,218,218,218
BEGIN DESCRIPTION:
Lacy 109 1643
END DESCRIPTION:
XS GIS Cut Line= 3
      2736618.82      6865714.07      2736452.17      6865933.06
      2736281.24      6866186.28
#Sta/Elev= 30
  4721.5  431.18  4783.7  426.66  4814.4  424.61  4829.0  424.22  4849.8  422.24
  4856.1  422.71  4899.7  420.32  4914.2  420.47  4920.5  419.61  4928.5  420.22
  4970.4  420.00  4978.7  418.20  4983.0  417.93  4983.2  417.43  4986.7  417.43
  4987.0  417.93  4992.3  419.69  5015.7  419.63  5024.3  419.59  5050.4  420.87
  5107.4  421.11  5122.4  422.02  5128.4  421.68  5140.6  422.23  5151.1  421.59
  5194.3  423.21  5215.3  423.43  5230.3  424.61  5281.2  425.94  5302.2  427.58
#Mann=8,-1,0
  4721.5    0.05       0  4783.7    0.12       0  4928.5     0.1       0
  4983.0    0.07       0  4987.0     0.1       0  5015.7    0.12       0
  5024.3     0.1       0  5140.6    0.05       0
Bank Sta=4983,4987
Exp/Cntr=0.3,0.1

Type RM Length L Ch R = 1,829,235,235,235
BEGIN DESCRIPTION:
Lacy 109 1640
END DESCRIPTION:
XS GIS Cut Line= 3
      2736510.58      6865559.92      2736280.82      6865807.77
      2736138.49      6866083.66
#Sta/Elev= 30
  4663.9  427.77  4675.1  428.13  4681.9  427.81  4689.3  428.30  4717.6  426.65
  4724.4  425.83  4760.1  424.32  4766.9  423.27  4774.3  423.26  4816.3  420.98
  4837.8  420.58  4858.8  418.92  4873.0  418.76  4880.3  417.74  4894.5  417.32
  4915.7  417.69  4937.0  418.08  4956.0  416.83  4956.3  416.33  4959.8  416.33
  4960.0  416.83  4965.4  417.91  5006.5  417.84  5050.6  418.56  5067.1  417.68
  5083.7  418.73  5138.6  419.63  5222.3  421.12  5244.4  422.55  5312.3  424.46
#Mann=5,-1,0
  4663.9    0.05       0  4915.7     0.1       0  4956.0    0.07       0
  4960.0     0.1       0  5138.6    0.05       0
Bank Sta=4956,4960
Exp/Cntr=0.3,0.1

Type RM Length L Ch R = 1,594,184,184,184
BEGIN DESCRIPTION:
Lacy 109 1639
END DESCRIPTION:
XS GIS Cut Line= 3
      2736487.83      6865513.93      2736077.53      6865714.20
      2735932.98      6865929.40
#Sta/Elev= 30
  4540.5  425.73  4546.7  426.48  4563.6  425.22  4569.2  425.52  4598.2  424.31
  4614.2  424.32  4749.4  417.45  4771.9  416.70  4777.5  417.35  4794.4  415.44
  4800.0  416.43  4809.6  416.98  4831.9  415.88  4845.1  416.78  4907.1  416.01
  4965.4  416.43  4982.5  416.00  5023.0  414.87  5023.3  414.37  5026.8  414.37
  5027.0  414.87  5053.4  415.98  5067.0  417.47  5076.0  417.83  5082.0  417.38
  5125.7  419.02  5161.9  420.97  5175.1  422.19  5196.5  422.85  5256.3  426.32
#Mann=5,-1,0
  4540.5    0.05       0  4982.5     0.1       0  5023.0    0.07       0
  5027.0     0.1       0  5196.5    0.05       0
Bank Sta=5023,5027
Exp/Cntr=0.3,0.1

Type RM Length L Ch R = 1,410,0,0,0
BEGIN DESCRIPTION:
Lacy 109 1653
END DESCRIPTION:
XS GIS Cut Line= 3
      2736458.76      6865500.27      2735928.45      6865616.47
      2735787.49      6865874.02
#Sta/Elev= 30
  4457.1  423.92  4511.1  423.98  4533.7  423.31  4572.4  420.66  4644.2  417.43
  4670.3  414.09  4675.4  415.08  4705.6  415.03  4719.2  416.73  4726.1  416.65
  4736.3  415.30  4754.1  415.03  4797.7  414.64  4910.4  415.08  5018.9  413.38
  5040.7  413.99  5054.8  413.15  5055.1  412.65  5058.6  412.65  5058.8  413.15
  5062.5  414.03  5094.7  416.74  5100.4  416.28  5153.4  418.43  5160.2  419.40
  5203.8  421.01  5210.4  421.81  5247.4  421.95  5263.6  423.09  5293.6  422.93
#Mann=5,-1,0
  4457.1    0.05       0  4754.1    0.12       0  4797.7    0.05       0
  5054.8    0.04       0  5058.8    0.05       0
Bank Sta=5054.8,5058.8
Exp/Cntr=0.3,0.1

Chan Stop Cuts=-1