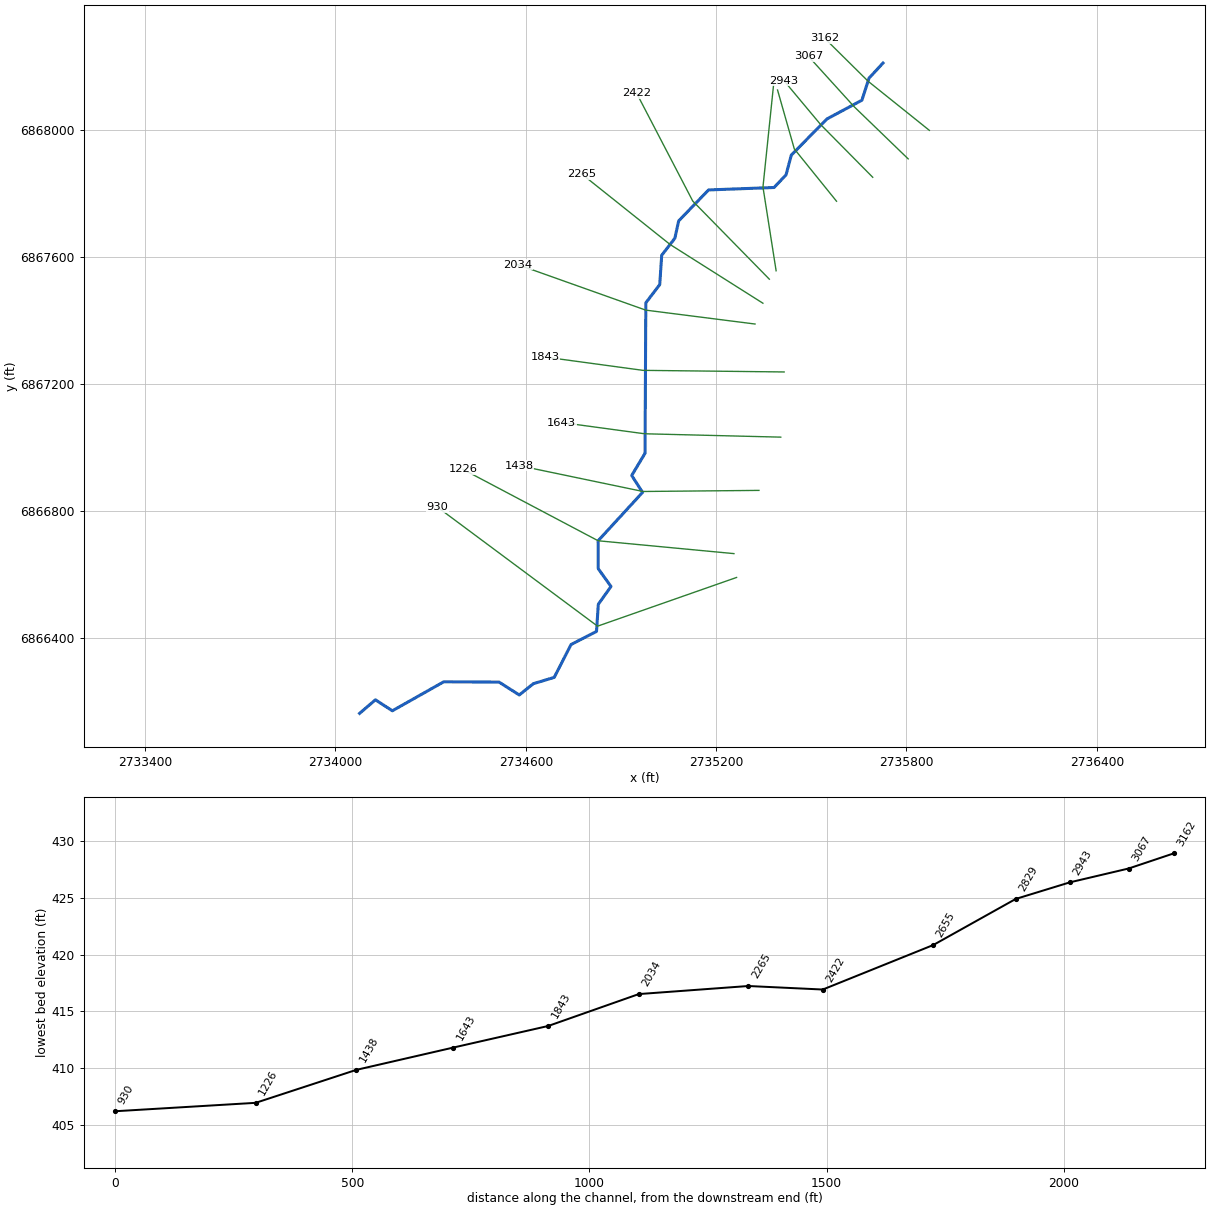
--- Lacy 110.prj (project) ---

Proj Title=Lacy 110 Base Level Engineering
Current Plan=p01
Default Exp/Contr=0.3,0.1
English Units
Geom File=g01
Flow File=f01
Plan File=p01
BEGIN DESCRIPTION:
Lacy 110
END DESCRIPTION:

--- Lacy 110.p01 (plan) ---

Plan Title=Multiple Run
Short Identifier=Multiple
Geom File=g01
Flow File=f01
Subcritical Flow
K Sum by GR= 0
Std Step Tol= 0.01
Critical Tol= 0.01
Num of Std Step Trials= 20
Max Error Tol= 0.3
Flow Tol Ratio= 0.001
Split Flow NTrial= 30
Split Flow Tol= 0.02
Split Flow Ratio= 0.02
Log Output Level= 0
Friction Slope Method= 1
Unsteady Friction Slope Method= 2
Unsteady Bridges Friction Slope Method= 1
Parabolic Critical Depth
Global Vel Dist=  1 , 1 , 1
Global Log Level= 0
CheckData=True
Encroach Param= -1, 0, 0, 0
BEGIN DESCRIPTION:
Multiple Run
END DESCRIPTION:

--- Lacy 110.f01 (steady flow) ---

Flow Title=Multiple
Number of Profiles=7
Profile Names=10-year,25-year,50-year,1pct_min,100-year,1pct_plu,500-year
River Rch & RM= Lacy 110,Reach-1,3162
     170     209     238     136     271     541     348
River Rch & RM= Lacy 110,Reach-1,2422
     346     448     528     309     617    1232     842
Boundary for River Rch & Prof#=Lacy 110,Reach-1,1
Up Type=0
Dn Type=3
Dn Slope=0.005
Boundary for River Rch & Prof#=Lacy 110,Reach-1,2
Up Type=0
Dn Type=3
Dn Slope=0.005
Boundary for River Rch & Prof#=Lacy 110,Reach-1,3
Up Type=0
Dn Type=3
Dn Slope=0.005
Boundary for River Rch & Prof#=Lacy 110,Reach-1,4
Up Type=0
Dn Type=3
Dn Slope=0.005
Boundary for River Rch & Prof#=Lacy 110,Reach-1,5
Up Type=0
Dn Type=3
Dn Slope=0.005
Boundary for River Rch & Prof#=Lacy 110,Reach-1,6
Up Type=0
Dn Type=3
Dn Slope=0.005
Boundary for River Rch & Prof#=Lacy 110,Reach-1,7
Up Type=0
Dn Type=3
Dn Slope=0.005

--- Lacy 110.g01 (geometry) ---

Geom Title=Existing Conditions

River Reach=Lacy 110,Reach-1
Reach XY= 30
      2735726.00      6868211.00      2735681.72      6868163.32
      2735659.55      6868093.91      2735549.18      6868034.70
      2735436.79      6867920.66      2735420.26      6867858.42
      2735382.48      6867818.69      2735176.00      6867811.00
      2735081.79      6867713.32      2735069.87      6867658.83
      2735028.33      6867605.04      2735022.14      6867512.60
      2734978.26      6867455.06      2734975.82      6866980.98
      2734933.81      6866910.90      2734968.01      6866857.66
      2734827.97      6866705.11      2734828.36      6866616.90
      2734868.44      6866561.00      2734828.59      6866505.02
      2734822.82      6866419.35      2734742.59      6866378.00
      2734689.56      6866274.46      2734623.74      6866254.58
      2734579.32      6866219.04      2734515.56      6866259.62
      2734341.21      6866260.49      2734179.23      6866169.12
      2734125.99      6866203.77      2734076.00      6866161.00

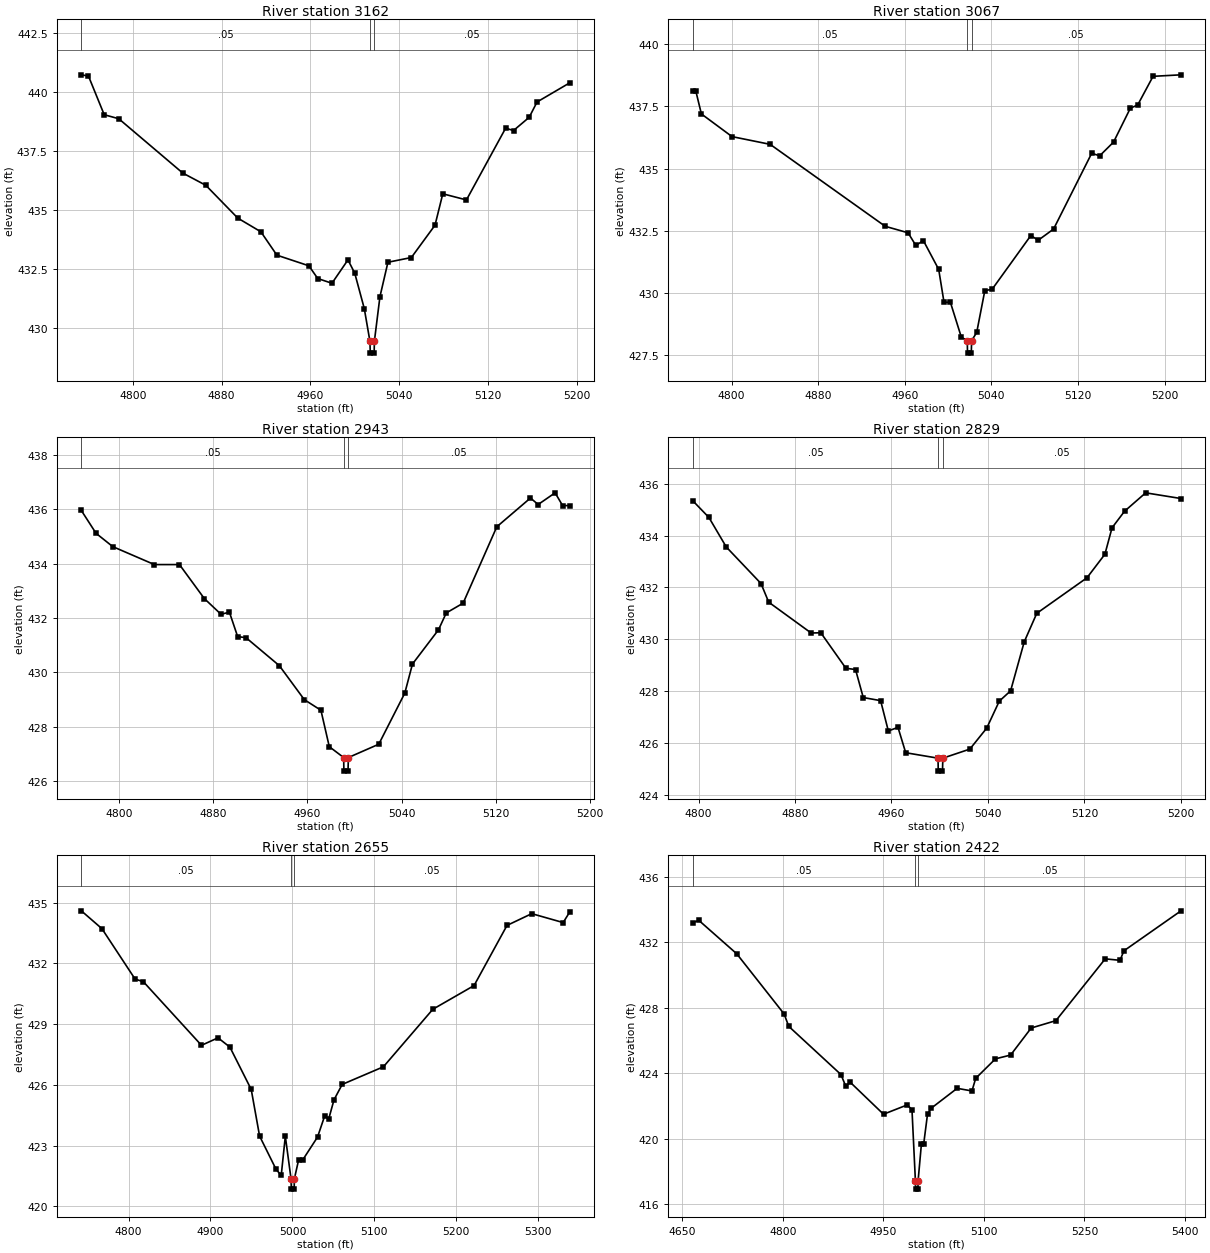
Type RM Length L Ch R = 1,3162,95,95,95
BEGIN DESCRIPTION:
Lacy 110 1595
END DESCRIPTION:
XS GIS Cut Line= 3
      2735872.10      6867998.82      2735679.09      6868153.56
      2735542.29      6868288.89
#Sta/Elev= 30
  4753.7  440.71  4760.1  440.66  4774.3  439.02  4787.4  438.85  4845.0  436.55
  4865.8  436.03  4894.6  434.64  4915.4  434.06  4929.8  433.07  4958.6  432.62
  4966.6  432.08  4979.4  431.88  4993.8  432.87  4999.9  432.31  5008.5  430.81
  5013.6  429.42  5013.9  428.92  5017.4  428.92  5017.6  429.42  5022.6  431.31
  5029.8  432.77  5050.9  432.97  5072.2  434.34  5079.2  435.67  5100.5  435.41
  5135.8  438.45  5142.9  438.35  5157.0  438.91  5164.1  439.56  5193.5  440.37
#Mann=3,-1,0
  4753.7    0.05       0  5013.6    0.04       0  5017.6    0.05       0
Bank Sta=5013.6,5017.6
Exp/Cntr=0.3,0.1

Type RM Length L Ch R = 1,3067,124,124,124
BEGIN DESCRIPTION:
Lacy 110 1594
END DESCRIPTION:
XS GIS Cut Line= 3
      2735805.26      6867908.90      2735635.50      6868072.87
      2735490.92      6868232.11
#Sta/Elev= 30
  4764.0  438.10  4767.0  438.10  4772.1  437.19  4800.4  436.28  4835.6  435.97
  4941.9  432.68  4963.0  432.42  4970.2  431.91  4977.1  432.11  4991.3  430.95
  4996.2  429.63  5002.1  429.63  5012.2  428.23  5017.7  428.09  5017.9  427.59
  5021.4  427.59  5021.7  428.09  5026.4  428.42  5033.9  430.10  5040.6  430.15
  5076.4  432.31  5083.2  432.12  5097.4  432.57  5132.6  435.61  5140.0  435.51
  5152.8  436.06  5168.3  437.42  5175.1  437.55  5189.3  438.70  5215.1  438.76
#Mann=3,-1,0
  4764.0    0.05       0  5017.7    0.04       0  5021.7    0.05       0
Bank Sta=5017.7,5021.7
Exp/Cntr=0.3,0.1

Type RM Length L Ch R = 1,2943,114,114,114
BEGIN DESCRIPTION:
Lacy 110 1593
END DESCRIPTION:
XS GIS Cut Line= 3
      2735693.58      6867850.87      2735529.68      6868016.68
      2735413.35      6868155.94
#Sta/Elev= 30
  4768.1  435.96  4780.6  435.12  4794.8  434.63  4830.1  433.97  4851.4  433.97
  4872.5  432.72  4886.7  432.14  4893.8  432.22  4900.8  431.32  4907.9  431.28
  4936.2  430.25  4957.4  429.00  4971.5  428.61  4978.6  427.27  4990.8  426.87
  4991.0  426.37  4994.5  426.37  4994.8  426.87  5020.6  427.36  5042.7  429.24
  5049.2  430.31  5071.3  431.57  5077.9  432.19  5092.2  432.55  5120.8  435.36
  5149.4  436.42  5155.9  436.18  5170.3  436.61  5176.7  436.14  5182.7  436.14
#Mann=3,-1,0
  4768.1    0.05       0  4990.8    0.04       0  4994.8    0.05       0
Bank Sta=4990.8,4994.8
Exp/Cntr=0.3,0.1

Type RM Length L Ch R = 1,2829,174,174,174
BEGIN DESCRIPTION:
Lacy 110 1592
END DESCRIPTION:
XS GIS Cut Line= 3
      2735579.45      6867775.39      2735446.36      6867940.24
      2735393.52      6868126.00
#Sta/Elev= 30
  4795.1  435.35  4808.6  434.70  4823.0  433.56  4851.8  432.15  4858.2  431.43
  4893.4  430.24  4901.4  430.25  4922.2  428.88  4930.2  428.83  4936.6  427.75
  4951.0  427.63  4957.4  426.46  4965.4  426.60  4971.8  425.62  4998.6  425.41
  4998.8  424.91  5002.3  424.91  5002.6  425.41  5025.0  425.76  5039.0  426.57
  5049.4  427.61  5058.8  428.01  5070.1  429.90  5080.5  431.00  5122.1  432.37
  5137.0  433.28  5142.9  434.30  5153.3  434.94  5170.8  435.65  5200.1  435.43
#Mann=3,-1,0
  4795.1    0.05       0  4998.6    0.04       0  5002.6    0.05       0
Bank Sta=4998.6,5002.6
Exp/Cntr=0.3,0.1

Type RM Length L Ch R = 1,2655,233,233,233
BEGIN DESCRIPTION:
Lacy 110 1588
END DESCRIPTION:
XS GIS Cut Line= 3
      2735389.03      6867556.18      2735347.55      6867820.14
      2735381.49      6868147.09
#Sta/Elev= 30
  4742.4  434.59  4767.5  433.71  4808.0  431.22  4818.1  431.09  4889.0  427.95
  4909.2  428.32  4923.7  427.86  4949.7  425.77  4959.9  423.47  4980.1  421.82
  4986.3  421.53  4991.3  423.46  4998.3  421.35  4998.6  420.85  5002.1  420.85
  5002.3  421.35  5007.5  422.29  5012.5  422.29  5030.6  423.42  5039.3  424.46
  5044.3  424.32  5050.7  425.26  5060.7  426.02  5111.0  426.89  5171.3  429.73
  5221.6  430.90  5261.8  433.87  5292.0  434.45  5330.3  434.01  5338.3  434.53
#Mann=3,-1,0
  4742.4    0.05       0  4998.3    0.04       0  5002.3    0.05       0
Bank Sta=4998.3,5002.3
Exp/Cntr=0.3,0.1

Type RM Length L Ch R = 1,2422,157,157,157
BEGIN DESCRIPTION:
Lacy 110 1587
END DESCRIPTION:
XS GIS Cut Line= 3
      2735367.65      6867529.66      2735126.22      6867775.93
      2734948.93      6868116.59
#Sta/Elev= 30
  4665.3  433.18  4674.5  433.33  4731.1  431.29  4801.8  427.62  4808.8  426.86
  4886.7  423.92  4893.7  423.22  4900.8  423.44  4950.2  421.50  4985.7  422.07
  4992.7  421.77  4997.8  417.43  4998.1  416.93  5001.6  416.93  5001.8  417.43
  5006.8  419.70  5010.2  419.70  5015.9  421.51  5021.5  421.87  5060.1  423.08
  5082.2  422.92  5087.8  423.69  5117.3  424.88  5139.9  425.11  5170.6  426.76
  5207.5  427.21  5281.1  430.98  5303.2  430.89  5309.0  431.47  5394.2  433.91
#Mann=3,-1,0
  4665.3    0.05       0  4997.8    0.04       0  5001.8    0.05       0
Bank Sta=4997.8,5001.8
Exp/Cntr=0.3,0.1

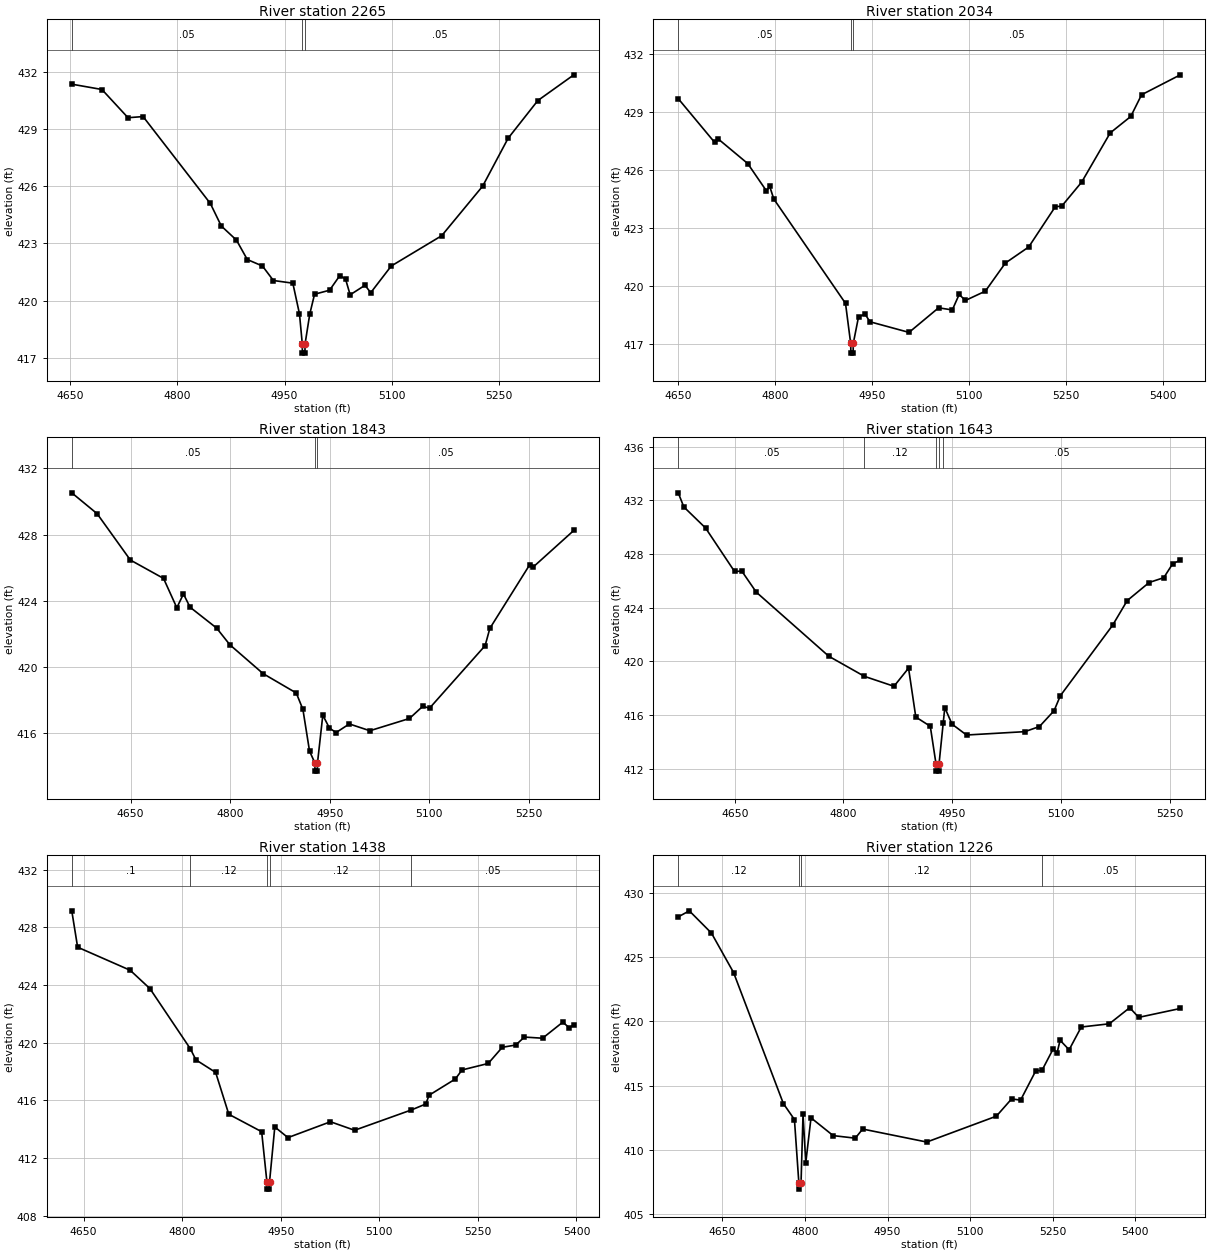
Type RM Length L Ch R = 1,2265,231,231,231
BEGIN DESCRIPTION:
Lacy 110 1591
END DESCRIPTION:
XS GIS Cut Line= 3
      2735347.38      6867453.89      2735054.60      6867639.16
      2734776.29      6867861.19
#Sta/Elev= 30
  4652.2  431.35  4694.4  431.07  4730.9  429.59  4752.0  429.65  4846.1  425.09
  4861.4  423.91  4882.6  423.17  4897.8  422.15  4919.0  421.81  4934.3  421.05
  4961.5  420.91  4970.8  419.30  4974.7  417.74  4974.9  417.24  4978.4  417.24
  4978.7  417.74  4985.2  419.29  4991.9  420.33  5012.9  420.54  5027.3  421.31
  5035.3  421.12  5041.7  420.30  5062.5  420.80  5070.5  420.41  5099.2  421.81
  5169.8  423.40  5227.1  426.00  5262.7  428.51  5304.3  430.49  5354.7  431.84
#Mann=3,-1,0
  4652.2    0.05       0  4974.7    0.04       0  4978.7    0.05       0
Bank Sta=4974.7,4978.7
Exp/Cntr=0.3,0.1

Type RM Length L Ch R = 1,2034,191,191,191
BEGIN DESCRIPTION:
Lacy 110 1590
END DESCRIPTION:
XS GIS Cut Line= 3
      2735322.50      6867388.34      2734978.03      6867432.13
      2734573.86      6867575.84
#Sta/Elev= 30
  4650.8  429.67  4707.1  427.41  4712.2  427.60  4758.2  426.32  4787.1  424.91
  4792.2  425.14  4798.5  424.49  4909.4  419.10  4917.4  417.03  4917.7  416.53
  4921.2  416.53  4921.4  417.03  4929.5  418.40  4939.6  418.55  4947.1  418.15
  5007.6  417.60  5053.3  418.87  5074.5  418.76  5085.1  419.56  5094.8  419.25
  5125.6  419.73  5156.5  421.18  5192.6  422.01  5233.7  424.09  5243.7  424.12
  5274.5  425.36  5318.6  427.90  5350.4  428.75  5367.1  429.87  5427.0  430.90
#Mann=3,-1,0
  4650.8    0.05       0  4917.4    0.04       0  4921.4    0.05       0
Bank Sta=4917.4,4921.4
Exp/Cntr=0.3,0.1

Type RM Length L Ch R = 1,1843,200,200,200
BEGIN DESCRIPTION:
Lacy 110 1589
END DESCRIPTION:
XS GIS Cut Line= 3
      2735414.25      6867237.24      2734969.31      6867242.29
      2734660.51      6867284.27
#Sta/Elev= 30
  4561.4  430.53  4599.6  429.27  4649.7  426.47  4699.7  425.36  4719.7  423.59
  4729.7  424.42  4739.7  423.62  4779.7  422.36  4799.7  421.35  4849.7  419.61
  4899.7  418.44  4909.7  417.45  4919.7  414.93  4927.7  414.22  4927.9  413.72
  4931.4  413.72  4931.7  414.22  4939.7  417.10  4949.7  416.32  4959.7  416.05
  4979.7  416.57  5010.6  416.16  5070.3  416.90  5090.4  417.64  5100.5  417.52
  5184.3  421.30  5191.4  422.34  5251.7  426.20  5256.8  426.05  5318.0  428.26
#Mann=3,-1,0
  4561.4    0.05       0  4927.7    0.04       0  4931.7    0.05       0
Bank Sta=4927.7,4931.7
Exp/Cntr=0.3,0.1

Type RM Length L Ch R = 1,1643,205,205,205
BEGIN DESCRIPTION:
Lacy 110 1586
END DESCRIPTION:
XS GIS Cut Line= 3
      2735403.66      6867031.77      2734974.04      6867042.38
      2734713.38      6867077.78
#Sta/Elev= 30
  4572.0  432.55  4579.7  431.50  4609.7  429.93  4649.7  426.69  4659.7  426.72
  4679.7  425.15  4779.7  420.38  4828.9  418.88  4869.7  418.14  4889.8  419.49
  4899.8  415.85  4919.8  415.16  4927.8  412.32  4928.0  411.82  4931.5  411.82
  4931.8  412.32  4937.7  415.44  4939.8  416.55  4949.8  415.32  4969.8  414.51
  5050.2  414.76  5070.4  415.14  5090.6  416.32  5099.3  417.44  5171.3  422.68
  5191.5  424.52  5221.8  425.87  5242.0  426.23  5254.3  427.27  5264.8  427.53
#Mann=5,-1,0
  4572.0    0.05       0  4828.9    0.12       0  4927.8    0.04       0
  4931.8    0.12       0  4937.7    0.05       0
Bank Sta=4927.8,4931.8
Exp/Cntr=0.3,0.1

Type RM Length L Ch R = 1,1438,212,212,212
BEGIN DESCRIPTION:
Lacy 110 1585
END DESCRIPTION:
XS GIS Cut Line= 3
      2735334.93      6866863.89      2734969.54      6866860.44
      2734579.43      6866941.77
#Sta/Elev= 30
  4632.1  429.14  4641.0  426.62  4721.0  425.02  4751.0  423.75  4812.5  419.58
  4821.0  418.81  4851.0  417.94  4871.0  415.04  4921.0  413.83  4929.0  410.35
  4929.3  409.85  4932.8  409.85  4933.0  410.35  4941.0  414.16  4961.0  413.42
  5025.7  414.52  5062.4  413.93  5148.9  415.34  5170.7  415.75  5175.8  416.36
  5215.6  417.48  5225.9  418.11  5265.7  418.56  5287.1  419.68  5307.6  419.84
  5320.8  420.39  5348.4  420.31  5379.1  421.42  5389.3  421.03  5396.0  421.25
#Mann=5,-1,0
  4632.1     0.1       0  4812.5    0.12       0  4929.0    0.07       0
  4933.0    0.12       0  5148.9    0.05       0
Bank Sta=4929,4933
Exp/Cntr=0.3,0.1

Type RM Length L Ch R = 1,1226,296,296,296
BEGIN DESCRIPTION:
Lacy 110 1597
END DESCRIPTION:
XS GIS Cut Line= 3
      2735256.05      6866664.60      2734827.97      6866705.11
      2734402.05      6866930.12
#Sta/Elev= 30
  4570.0  428.11  4590.1  428.58  4630.3  426.85  4670.5  423.78  4760.9  413.60
  4781.0  412.36  4789.0  407.45  4789.3  406.95  4793.0  407.45  4796.6  412.76
  4801.6  409.01  4811.1  412.49  4851.3  411.11  4891.5  410.91  4904.9  411.62
  5021.3  410.61  5147.7  412.62  5175.3  413.96  5191.7  413.87  5219.4  416.16
  5230.4  416.17  5251.0  417.86  5257.7  417.50  5263.4  418.52  5279.8  417.78
  5301.8  419.55  5352.8  419.80  5389.8  421.05  5406.2  420.30  5481.7  420.99
#Mann=4,-1,0
  4570.0    0.12       0  4789.0    0.07       0  4793.0    0.12       0
  5230.4    0.05       0
Bank Sta=4789,4793
Exp/Cntr=0.3,0.1

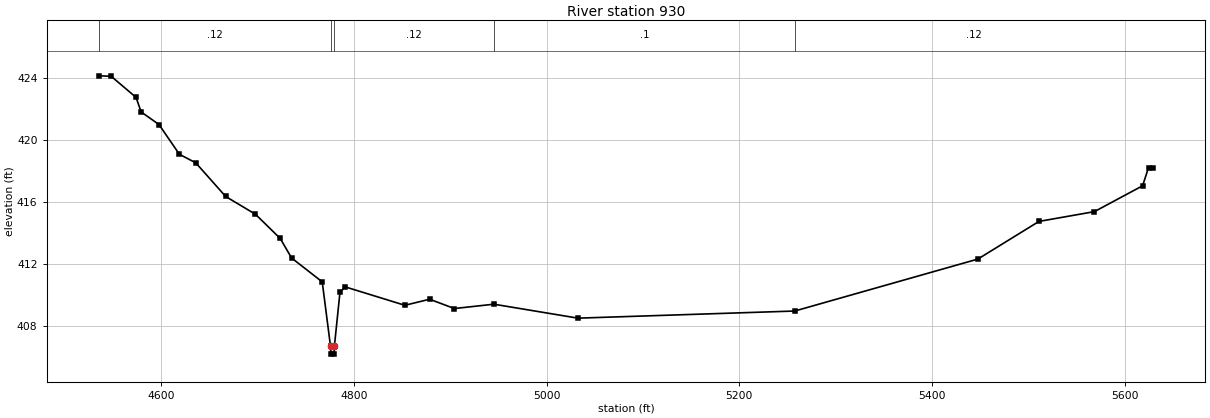
Type RM Length L Ch R = 1,930,0,0,0
BEGIN DESCRIPTION:
Lacy 110 1596
END DESCRIPTION:
XS GIS Cut Line= 3
      2735264.40      6866589.47      2734826.13      6866435.88
      2734321.20      6866811.30
#Sta/Elev= 30
  4535.6  424.16  4547.9  424.13  4573.7  422.77  4579.0  421.83  4597.5  421.02
  4618.7  419.10  4635.7  418.55  4666.7  416.38  4697.7  415.23  4723.4  413.67
  4735.2  412.41  4767.0  410.87  4775.6  406.71  4775.9  406.21  4779.4  406.21
  4779.6  406.71  4785.4  410.19  4790.7  410.55  4852.8  409.36  4878.5  409.75
  4904.2  409.15  4945.2  409.43  5032.5  408.53  5257.5  408.99  5447.6  412.34
  5511.1  414.77  5568.6  415.40  5618.7  417.07  5624.8  418.24  5629.2  418.24
#Mann=5,-1,0
  4535.6    0.12       0  4775.6    0.07       0  4779.6    0.12       0
  4945.2     0.1       0  5257.5    0.12       0
Bank Sta=4775.6,4779.6
Exp/Cntr=0.3,0.1

Chan Stop Cuts=-1