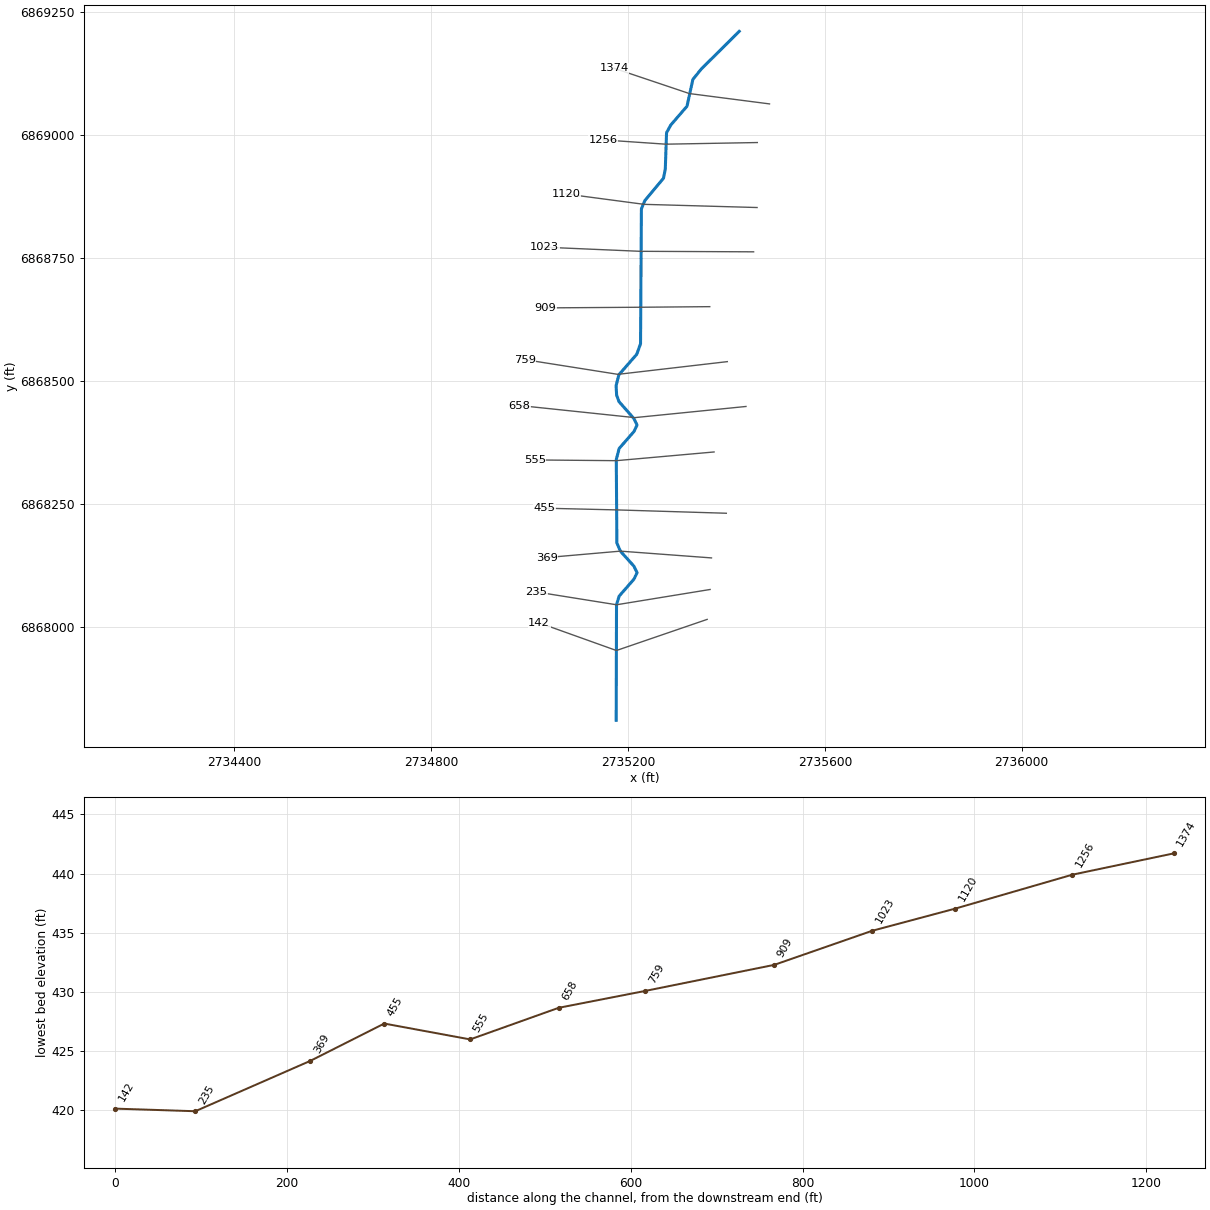
--- Lacy 111.prj (project) ---

Proj Title=Lacy 111 Base Level Engineering
Current Plan=p01
Default Exp/Contr=0.3,0.1
English Units
Geom File=g01
Flow File=f01
Plan File=p01
BEGIN DESCRIPTION:
Lacy 111
END DESCRIPTION:

--- Lacy 111.p01 (plan) ---

Plan Title=Multiple Run
Short Identifier=Multiple
Geom File=g01
Flow File=f01
Subcritical Flow
K Sum by GR= 0
Std Step Tol= 0.01
Critical Tol= 0.01
Num of Std Step Trials= 20
Max Error Tol= 0.3
Flow Tol Ratio= 0.001
Split Flow NTrial= 30
Split Flow Tol= 0.02
Split Flow Ratio= 0.02
Log Output Level= 0
Friction Slope Method= 1
Unsteady Friction Slope Method= 2
Unsteady Bridges Friction Slope Method= 1
Parabolic Critical Depth
Global Vel Dist=  1 , 1 , 1
Global Log Level= 0
CheckData=True
Encroach Param= -1, 0, 0, 0
BEGIN DESCRIPTION:
Multiple Run
END DESCRIPTION:

--- Lacy 111.f01 (steady flow) ---

Flow Title=Multiple
Number of Profiles=7
Profile Names=10-year,25-year,50-year,1pct_min,100-year,1pct_plu,500-year
River Rch & RM= Lacy 111,Reach-1,1374
     148     180     203     115     229     456     288
Boundary for River Rch & Prof#=Lacy 111,Reach-1,1
Up Type=0
Dn Type=3
Dn Slope=0.005
Boundary for River Rch & Prof#=Lacy 111,Reach-1,2
Up Type=0
Dn Type=3
Dn Slope=0.005
Boundary for River Rch & Prof#=Lacy 111,Reach-1,3
Up Type=0
Dn Type=3
Dn Slope=0.005
Boundary for River Rch & Prof#=Lacy 111,Reach-1,4
Up Type=0
Dn Type=3
Dn Slope=0.005
Boundary for River Rch & Prof#=Lacy 111,Reach-1,5
Up Type=0
Dn Type=3
Dn Slope=0.005
Boundary for River Rch & Prof#=Lacy 111,Reach-1,6
Up Type=0
Dn Type=3
Dn Slope=0.005
Boundary for River Rch & Prof#=Lacy 111,Reach-1,7
Up Type=0
Dn Type=3
Dn Slope=0.005

--- Lacy 111.g01 (geometry) ---

Geom Title=Existing Conditions

River Reach=Lacy 111,Reach-1
Reach XY= 29
      2735426.00      6869211.00      2735348.92      6869134.51
      2735331.79      6869113.32      2735319.87      6869058.83
      2735286.83      6869020.65      2735278.33      6869005.04
      2735275.76      6868931.10      2735272.14      6868912.60
      2735234.14      6868867.06      2735227.22      6868850.50
      2735225.46      6868576.21      2735217.81      6868554.92
      2735181.40      6868513.17      2735175.79      6868490.79
      2735176.93      6868471.62      2735181.65      6868458.71
      2735211.98      6868424.24      2735218.41      6868411.01
      2735212.04      6868397.80      2735182.02      6868363.45
      2735176.18      6868341.02      2735177.38      6868171.44
      2735184.45      6868154.82      2735212.05      6868124.21
      2735218.44      6868111.00      2735212.05      6868097.79
      2735182.02      6868063.45      2735176.66      6868045.84
      2735176.00      6867811.00

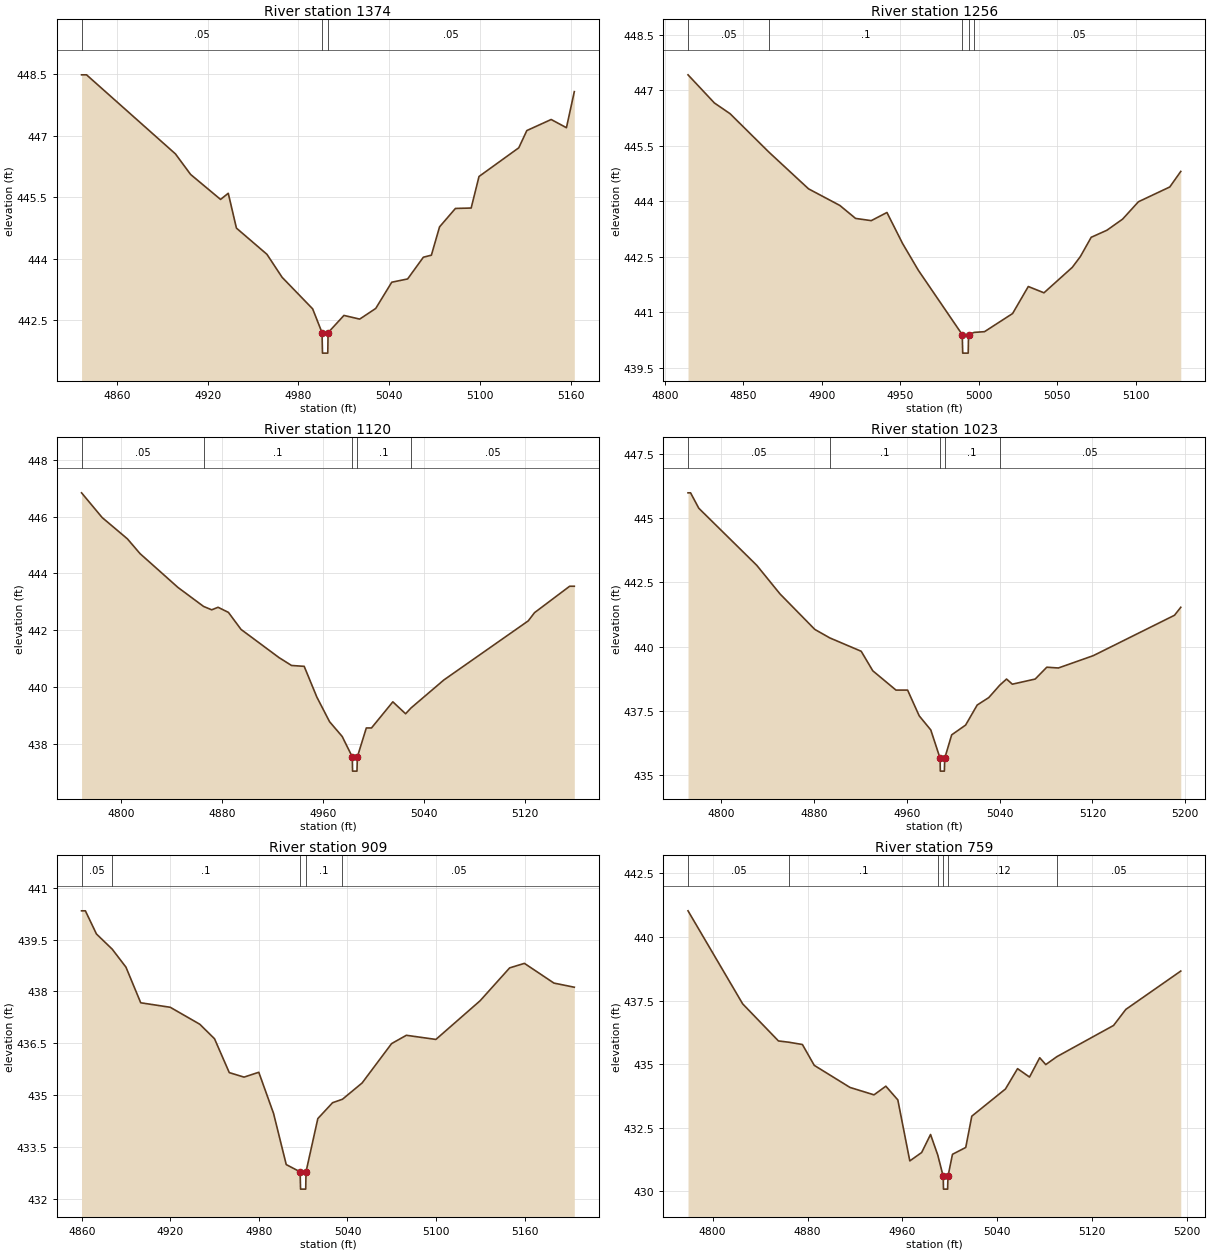
Type RM Length L Ch R = 1,1374,118,118,118
BEGIN DESCRIPTION:
Lacy 111 1602
END DESCRIPTION:
XS GIS Cut Line= 3
      2735487.55      6869063.62      2735324.67      6869084.66
      2735171.52      6869136.11
#Sta/Elev= 30
  4836.6  448.49  4839.9  448.49  4898.7  446.56  4908.7  446.06  4928.5  445.45
  4933.6  445.60  4939.0  444.75  4959.2  444.11  4969.2  443.55  4989.4  442.78
  4995.6  442.20  4995.9  441.70  4999.4  441.70  4999.6  442.20  5010.1  442.62
  5020.5  442.53  5031.1  442.79  5041.7  443.43  5052.2  443.51  5062.6  444.04
  5067.9  444.09  5073.3  444.78  5083.8  445.23  5094.2  445.24  5099.4  446.01
  5125.7  446.71  5131.0  447.13  5147.1  447.40  5157.2  447.20  5162.4  448.08
#Mann=3,-1,0
  4836.6    0.05       0  4995.6    0.04       0  4999.6    0.05       0
Bank Sta=4995.6,4999.6
Exp/Cntr=0.3,0.1

Type RM Length L Ch R = 1,1256,136,136,136
BEGIN DESCRIPTION:
Lacy 111 1603
END DESCRIPTION:
XS GIS Cut Line= 3
      2735462.79      6868985.11      2735276.65      6868981.78
      2735149.02      6868990.49
#Sta/Elev= 28
  4814.7  447.42  4831.5  446.66  4841.5  446.37  4866.3  445.33  4891.5  444.34
  4911.5  443.89  4921.5  443.54  4931.5  443.48  4941.5  443.70  4951.5  442.86
  4961.5  442.14  4989.5  440.40  4989.8  439.90  4993.3  439.90  4993.5  440.40
  4997.1  440.46  5003.7  440.48  5021.6  440.97  5031.6  441.70  5041.6  441.53
  5059.7  442.22  5064.8  442.51  5071.7  443.03  5081.7  443.22  5091.7  443.52
  5101.8  443.99  5121.8  444.39  5128.8  444.81
#Mann=5,-1,0
  4814.7    0.05       0  4866.3     0.1       0  4989.5    0.04       0
  4993.5     0.1       0  4997.1    0.05       0
Bank Sta=4989.5,4993.5
Exp/Cntr=0.3,0.1

Type RM Length L Ch R = 1,1120,97,97,97
BEGIN DESCRIPTION:
Lacy 111 1605
END DESCRIPTION:
XS GIS Cut Line= 3
      2735462.27      6868853.05      2735232.76      6868859.52
      2735073.56      6868880.64
#Sta/Elev= 30
  4768.7  446.84  4785.0  445.97  4805.0  445.22  4815.0  444.70  4845.0  443.51
  4865.3  442.84  4871.8  442.72  4876.8  442.81  4885.0  442.63  4895.0  442.03
  4925.0  441.04  4935.0  440.76  4945.0  440.73  4955.0  439.65  4965.1  438.78
  4975.1  438.26  4983.1  437.54  4983.3  437.04  4986.8  437.04  4987.1  437.54
  4994.2  438.56  4998.3  438.56  5015.2  439.48  5025.3  439.06  5029.5  439.26
  5055.6  440.25  5122.4  442.33  5127.4  442.62  5155.2  443.55  5158.9  443.55
#Mann=5,-1,0
  4768.7    0.05       0  4865.3     0.1       0  4983.1    0.07       0
  4987.1     0.1       0  5029.5    0.05       0
Bank Sta=4983.1,4987.1
Exp/Cntr=0.3,0.1

Type RM Length L Ch R = 1,1023,114,114,114
BEGIN DESCRIPTION:
Lacy 111 1604
END DESCRIPTION:
XS GIS Cut Line= 3
      2735455.26      6868763.04      2735224.93      6868764.08
      2735030.64      6868772.45
#Sta/Elev= 30
  4771.4  445.98  4773.6  445.98  4780.7  445.38  4830.7  443.16  4850.7  442.05
  4880.7  440.67  4893.6  440.34  4920.7  439.82  4930.7  439.06  4950.7  438.31
  4960.7  438.31  4970.7  437.31  4980.7  436.76  4988.7  435.66  4988.9  435.16
  4992.4  435.16  4992.7  435.66  4998.7  436.57  5010.7  436.95  5020.7  437.73
  5030.7  438.02  5040.1  438.50  5046.0  438.74  5051.0  438.54  5070.7  438.74
  5080.7  439.20  5090.7  439.17  5120.8  439.65  5190.8  441.22  5196.2  441.53
#Mann=5,-1,0
  4771.4    0.05       0  4893.6     0.1       0  4988.7    0.07       0
  4992.7     0.1       0  5040.1    0.05       0
Bank Sta=4988.7,4992.7
Exp/Cntr=0.3,0.1

Type RM Length L Ch R = 1,909,150,150,150
BEGIN DESCRIPTION:
Lacy 111 1601
END DESCRIPTION:
XS GIS Cut Line= 3
      2735366.13      6868651.61      2735223.95      6868650.41
      2735032.24      6868649.12
#Sta/Elev= 30
  4859.8  440.33  4862.4  440.33  4869.9  439.66  4880.6  439.22  4889.9  438.70
  4899.9  437.67  4919.9  437.54  4939.9  437.05  4949.9  436.63  4959.9  435.65
  4969.9  435.52  4979.9  435.66  4989.9  434.47  4998.5  432.99  5007.9  432.78
  5008.2  432.28  5011.7  432.28  5011.9  432.78  5019.9  434.32  5029.9  434.78
  5036.6  434.88  5049.9  435.35  5069.9  436.49  5079.9  436.73  5099.9  436.61
  5129.9  437.73  5149.9  438.68  5159.9  438.81  5179.9  438.24  5193.7  438.12
#Mann=5,-1,0
  4859.8    0.05       0  4880.6     0.1       0  5007.9    0.07       0
  5011.9     0.1       0  5036.6    0.05       0
Bank Sta=5007.9,5011.9
Exp/Cntr=0.3,0.1

Type RM Length L Ch R = 1,759,101,101,101
BEGIN DESCRIPTION:
Lacy 111 1600
END DESCRIPTION:
XS GIS Cut Line= 3
      2735401.81      6868539.90      2735179.48      6868514.06
      2734989.96      6868544.02
#Sta/Elev= 30
  4779.2  441.03  4825.3  437.37  4855.5  435.91  4864.3  435.86  4875.7  435.77
  4885.7  434.95  4915.9  434.08  4936.1  433.79  4946.1  434.13  4956.2  433.59
  4966.3  431.19  4976.3  431.52  4983.8  432.23  4989.9  431.42  4994.5  430.58
  4994.7  430.08  4998.2  430.08  4998.5  430.58  5002.3  431.45  5013.5  431.72
  5018.6  432.95  5047.0  434.02  5057.2  434.82  5067.3  434.49  5075.9  435.25
  5081.0  434.98  5090.3  435.29  5138.2  436.52  5148.5  437.15  5194.9  438.66
#Mann=6,-1,0
  4779.2    0.05       0  4864.3     0.1       0  4989.9    0.12       0
  4994.5    0.07       0  4998.5    0.12       0  5090.3    0.05       0
Bank Sta=4994.5,4998.5
Exp/Cntr=0.3,0.1

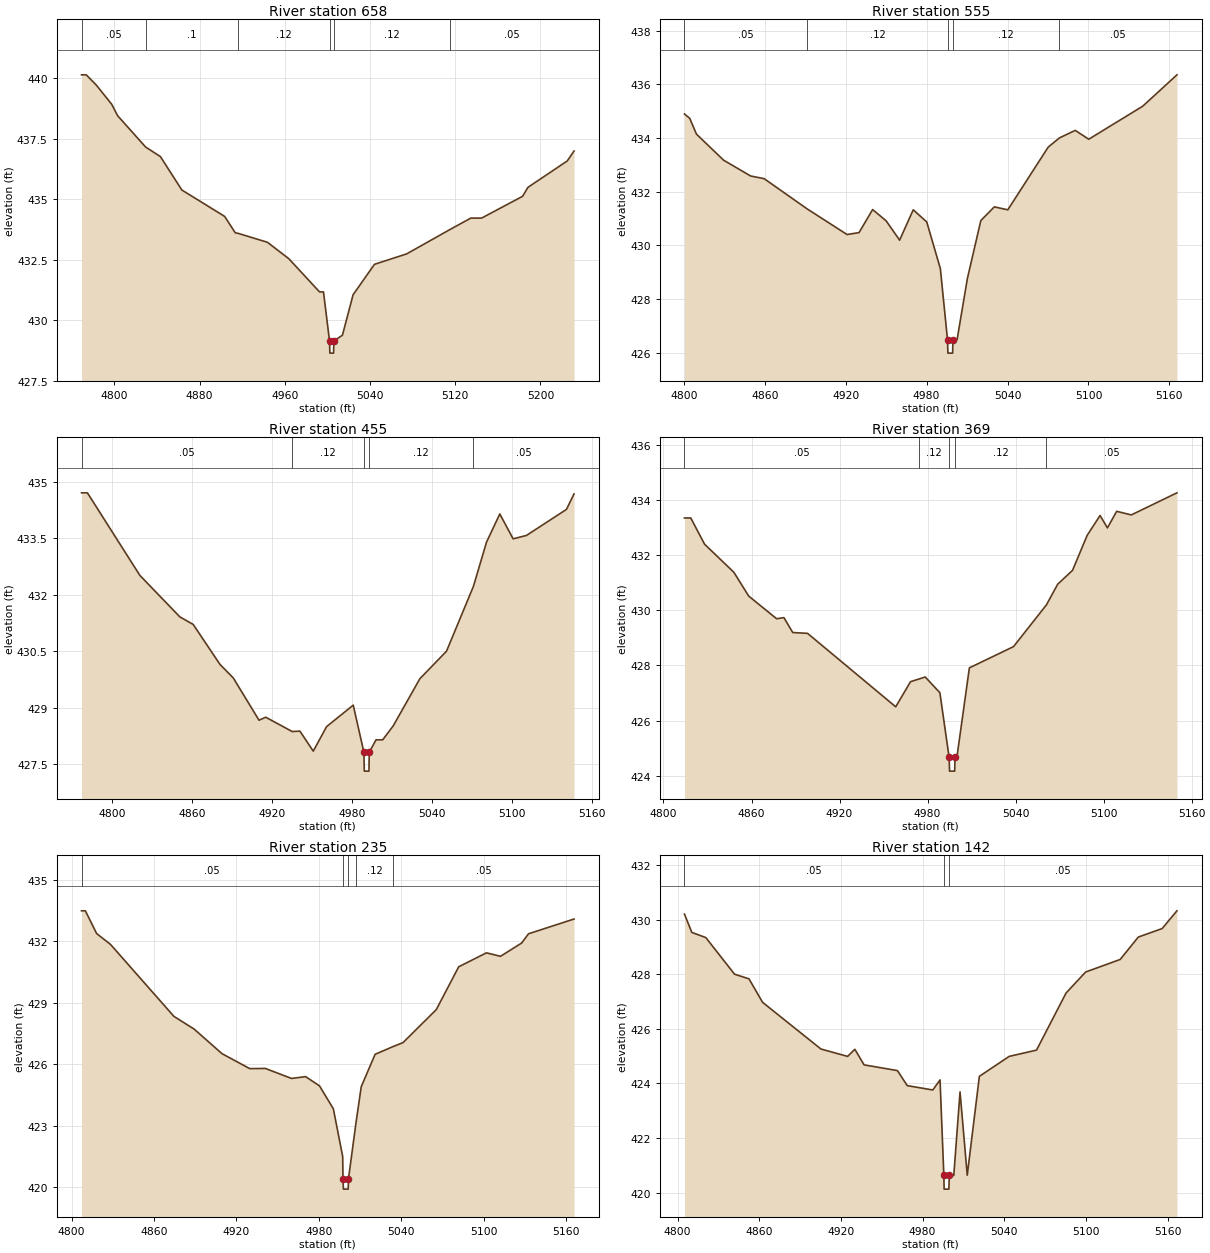
Type RM Length L Ch R = 1,658,103,103,103
BEGIN DESCRIPTION:
Lacy 111 1599
END DESCRIPTION:
XS GIS Cut Line= 3
      2735439.73      6868448.79      2735213.67      6868426.12
      2734979.65      6868450.70
#Sta/Elev= 30
  4769.1  440.15  4773.5  440.15  4782.9  439.73  4797.5  438.93  4803.0  438.46
  4829.2  437.17  4843.2  436.77  4863.3  435.39  4903.5  434.30  4913.5  433.62
  4916.1  433.60  4943.7  433.23  4963.8  432.55  4992.6  431.18  4996.3  431.18
  5002.0  429.15  5002.3  428.65  5005.8  428.65  5006.0  429.15  5014.1  429.39
  5024.1  431.06  5044.2  432.32  5074.4  432.75  5115.2  433.76  5134.7  434.23
  5144.8  434.23  5183.3  435.13  5188.3  435.50  5225.2  436.59  5231.6  437.00
#Mann=6,-1,0
  4769.1    0.05       0  4829.2     0.1       0  4916.1    0.12       0
  5002.0    0.07       0  5006.0    0.12       0  5115.2    0.05       0
Bank Sta=5002,5006
Exp/Cntr=0.3,0.1

Type RM Length L Ch R = 1,555,100,100,100
BEGIN DESCRIPTION:
Lacy 111 1598
END DESCRIPTION:
XS GIS Cut Line= 3
      2735374.91      6868356.34      2735176.29      6868338.65
      2735010.61      6868340.12
#Sta/Elev= 30
  4800.5  434.89  4804.4  434.73  4809.4  434.14  4829.5  433.17  4849.6  432.58
  4859.6  432.48  4891.6  431.35  4921.0  430.40  4929.9  430.47  4940.0  431.33
  4950.0  430.91  4960.0  430.19  4970.1  431.32  4980.1  430.87  4990.2  429.13
  4995.5  426.48  4995.8  425.98  4999.3  425.98  4999.5  426.48  5002.6  426.48
  5010.2  428.75  5020.2  430.92  5030.2  431.43  5040.2  431.32  5070.2  433.66
  5078.5  434.00  5090.2  434.28  5100.2  433.95  5140.2  435.18  5165.6  436.35
#Mann=5,-1,0
  4800.5    0.05       0  4891.6    0.12       0  4995.5    0.07       0
  4999.5    0.12       0  5078.5    0.05       0
Bank Sta=4995.5,4999.5
Exp/Cntr=0.3,0.1

Type RM Length L Ch R = 1,455,86,86,86
BEGIN DESCRIPTION:
Lacy 111 1609
END DESCRIPTION:
XS GIS Cut Line= 3
      2735399.80      6868231.81      2735176.91      6868238.61
      2735030.35      6868242.08
#Sta/Elev= 30
  4777.0  434.70  4781.4  434.70  4820.8  432.51  4850.8  431.41  4860.8  431.21
  4880.9  430.15  4890.9  429.79  4910.2  428.67  4915.2  428.75  4935.1  428.37
  4940.9  428.38  4950.9  427.85  4960.9  428.50  4980.9  429.07  4988.9  427.82
  4989.2  427.32  4992.7  427.32  4992.9  427.82  4998.0  428.15  5003.0  428.15
  5010.9  428.52  5030.9  429.77  5050.9  430.50  5071.1  432.22  5080.9  433.39
  5090.9  434.14  5100.9  433.48  5110.9  433.57  5140.9  434.26  5146.6  434.67
#Mann=5,-1,0
  4777.0    0.05       0  4935.1    0.12       0  4988.9    0.07       0
  4992.9    0.12       0  5071.1    0.05       0
Bank Sta=4988.9,4992.9
Exp/Cntr=0.3,0.1

Type RM Length L Ch R = 1,369,134,134,134
BEGIN DESCRIPTION:
Lacy 111 1608
END DESCRIPTION:
XS GIS Cut Line= 3
      2735369.64      6868141.04      2735184.45      6868154.82
      2735035.02      6868141.78
#Sta/Elev= 30
  4814.3  433.34  4818.6  433.34  4828.0  432.39  4848.0  431.37  4858.1  430.51
  4877.1  429.69  4882.1  429.73  4888.1  429.19  4898.2  429.16  4958.3  426.50
  4968.4  427.41  4974.4  427.51  4978.4  427.58  4988.4  427.01  4994.7  424.67
  4995.0  424.17  4998.5  424.17  4998.7  424.67  5000.0  424.67  5008.5  427.91
  5038.6  428.68  5061.0  430.19  5068.7  430.94  5078.8  431.44  5088.8  432.71
  5097.6  433.43  5102.6  432.98  5108.9  433.58  5118.9  433.45  5150.0  434.25
#Mann=5,-1,0
  4814.3    0.05       0  4974.4    0.12       0  4994.7    0.07       0
  4998.7    0.12       0  5061.0    0.05       0
Bank Sta=4994.7,4998.7
Exp/Cntr=0.3,0.1

Type RM Length L Ch R = 1,235,93,93,93
BEGIN DESCRIPTION:
Lacy 111 1607
END DESCRIPTION:
XS GIS Cut Line= 3
      2735366.84      6868076.90      2735176.66      6868045.84
      2735013.13      6868071.99
#Sta/Elev= 30
  4807.3  433.49  4810.1  433.49  4818.3  432.38  4828.4  431.85  4874.5  428.34
  4889.2  427.72  4909.5  426.52  4929.7  425.79  4941.0  425.80  4960.1  425.31
  4970.3  425.40  4980.4  424.95  4990.5  423.83  4997.3  421.50  4997.5  420.41
  4997.8  419.91  5001.3  419.91  5001.5  420.41  5007.0  423.16  5010.8  424.91
  5020.9  426.49  5034.1  426.87  5041.2  427.06  5065.4  428.67  5081.7  430.76
  5101.9  431.44  5112.1  431.27  5127.5  431.92  5132.5  432.37  5165.6  433.09
#Mann=5,-1,0
  4807.3    0.05       0  4997.5    0.04       0  5001.5    0.05       0
  5007.0    0.12       0  5034.1    0.05       0
Bank Sta=4997.5,5001.5
Exp/Cntr=0.3,0.1

Type RM Length L Ch R = 1,142,0,0,0
BEGIN DESCRIPTION:
Lacy 111 1606
END DESCRIPTION:
XS GIS Cut Line= 3
      2735360.85      6868016.13      2735176.40      6867952.88
      2735019.26      6868009.14
#Sta/Elev= 30
  4805.0  430.20  4810.4  429.53  4820.7  429.34  4841.8  428.00  4852.4  427.83
  4862.4  426.97  4905.3  425.26  4924.9  424.99  4930.2  425.25  4937.0  424.68
  4961.5  424.47  4968.7  423.92  4987.5  423.76  4992.8  424.13  4995.6  420.63
  4995.8  420.13  4999.3  420.13  4999.6  420.63  5002.9  420.63  5007.5  423.69
  5012.8  420.64  5021.7  424.26  5043.6  424.99  5063.7  425.22  5085.4  427.31
  5099.8  428.08  5125.2  428.54  5138.5  429.36  5156.0  429.67  5166.9  430.32
#Mann=3,-1,0
  4805.0    0.05       0  4995.6    0.04       0  4999.6    0.05       0
Bank Sta=4995.6,4999.6
Exp/Cntr=0.3,0.1

Chan Stop Cuts=-1