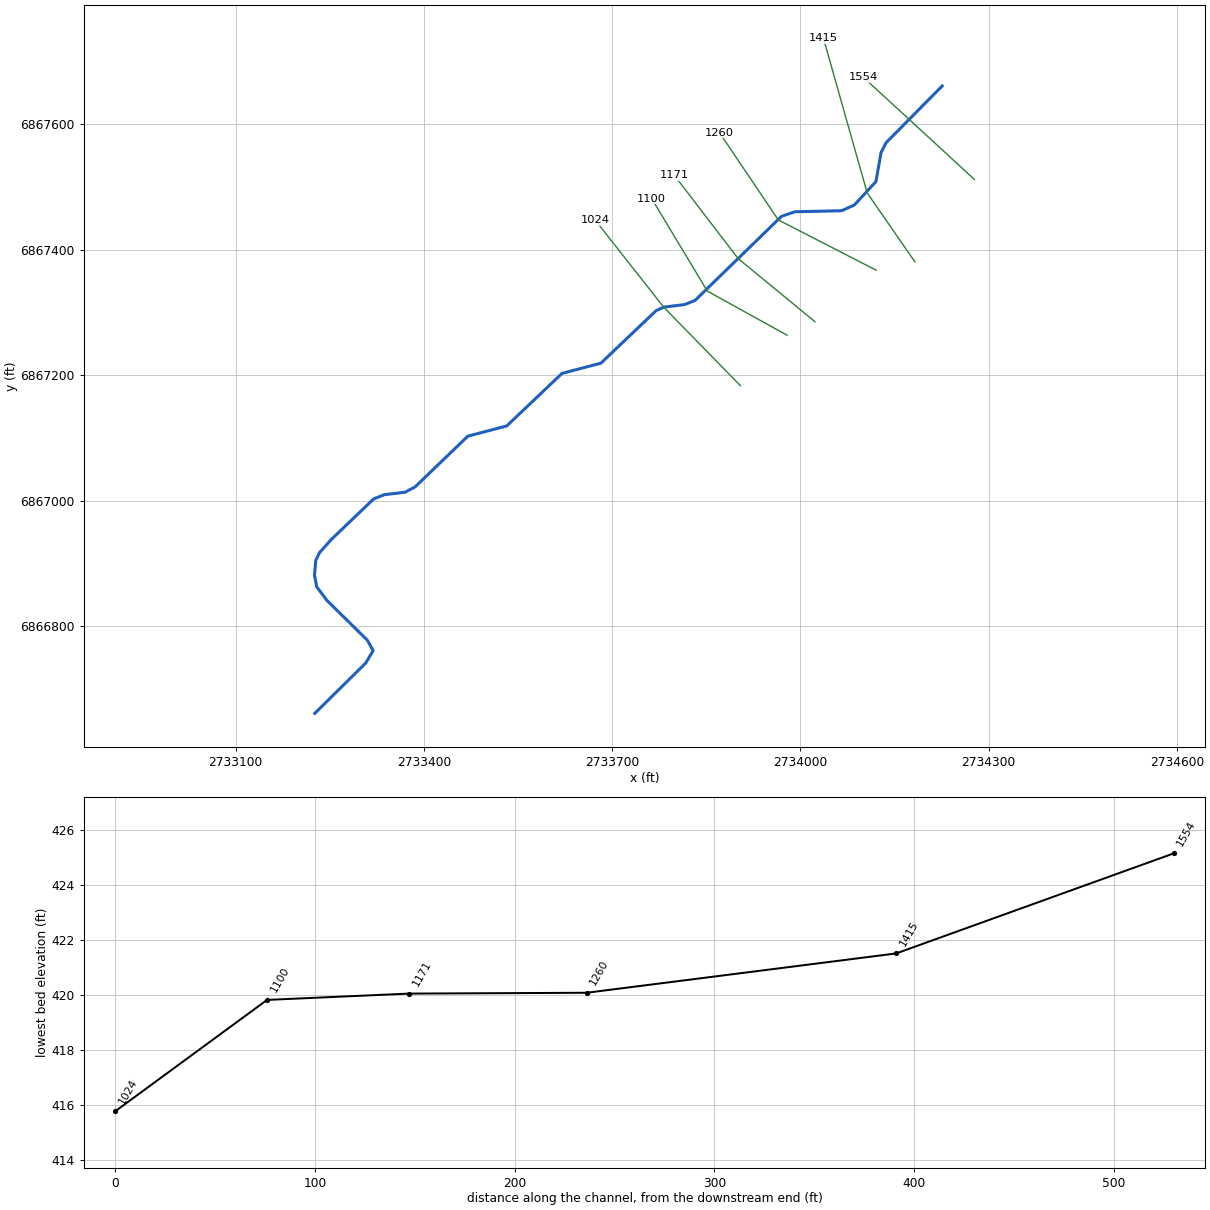
--- Lacy 112.prj (project) ---

Proj Title=Lacy 112 Base Level Engineering
Current Plan=p01
Default Exp/Contr=0.3,0.1
English Units
Geom File=g01
Flow File=f01
Plan File=p01
BEGIN DESCRIPTION:
Lacy 112
END DESCRIPTION:

--- Lacy 112.p01 (plan) ---

Plan Title=Multiple Run
Short Identifier=Multiple
Geom File=g01
Flow File=f01
Subcritical Flow
K Sum by GR= 0
Std Step Tol= 0.01
Critical Tol= 0.01
Num of Std Step Trials= 20
Max Error Tol= 0.3
Flow Tol Ratio= 0.001
Split Flow NTrial= 30
Split Flow Tol= 0.02
Split Flow Ratio= 0.02
Log Output Level= 0
Friction Slope Method= 1
Unsteady Friction Slope Method= 2
Unsteady Bridges Friction Slope Method= 1
Parabolic Critical Depth
Global Vel Dist=  1 , 1 , 1
Global Log Level= 0
CheckData=True
Encroach Param= -1, 0, 0, 0
BEGIN DESCRIPTION:
Multiple Run
END DESCRIPTION:

--- Lacy 112.f01 (steady flow) ---

Flow Title=Multiple
Number of Profiles=7
Profile Names=10-year,25-year,50-year,1pct_min,100-year,1pct_plu,500-year
River Rch & RM= Lacy 112,Reach-1,1554
      86     100     110      61     121     241     144
Boundary for River Rch & Prof#=Lacy 112,Reach-1,1
Up Type=0
Dn Type=3
Dn Slope=0.005
Boundary for River Rch & Prof#=Lacy 112,Reach-1,2
Up Type=0
Dn Type=3
Dn Slope=0.005
Boundary for River Rch & Prof#=Lacy 112,Reach-1,3
Up Type=0
Dn Type=3
Dn Slope=0.005
Boundary for River Rch & Prof#=Lacy 112,Reach-1,4
Up Type=0
Dn Type=3
Dn Slope=0.005
Boundary for River Rch & Prof#=Lacy 112,Reach-1,5
Up Type=0
Dn Type=3
Dn Slope=0.005
Boundary for River Rch & Prof#=Lacy 112,Reach-1,6
Up Type=0
Dn Type=3
Dn Slope=0.005
Boundary for River Rch & Prof#=Lacy 112,Reach-1,7
Up Type=0
Dn Type=3
Dn Slope=0.005

--- Lacy 112.g01 (geometry) ---

Geom Title=Existing Conditions

River Reach=Lacy 112,Reach-1
Reach XY= 30
      2734226.00      6867661.00      2734136.72      6867570.69
      2734128.54      6867554.91      2734120.27      6867508.42
      2734086.10      6867471.39      2734065.67      6867462.10
      2733991.22      6867460.47      2733969.83      6867453.14
      2733832.05      6867319.16      2733815.36      6867312.55
      2733782.05      6867308.46      2733769.96      6867302.82
      2733682.04      6867219.18      2733619.96      6867202.82
      2733532.04      6867119.18      2733469.96      6867102.82
      2733385.67      6867021.80      2733369.94      6867013.54
      2733336.63      6867009.46      2733319.93      6867002.85
      2733252.01      6866937.88      2733233.45      6866917.07
      2733227.58      6866904.96      2733225.53      6866881.16
      2733229.12      6866862.65      2733245.50      6866840.91
      2733309.78      6866777.65      2733319.02      6866761.00
      2733307.00      6866741.00      2733226.00      6866661.00

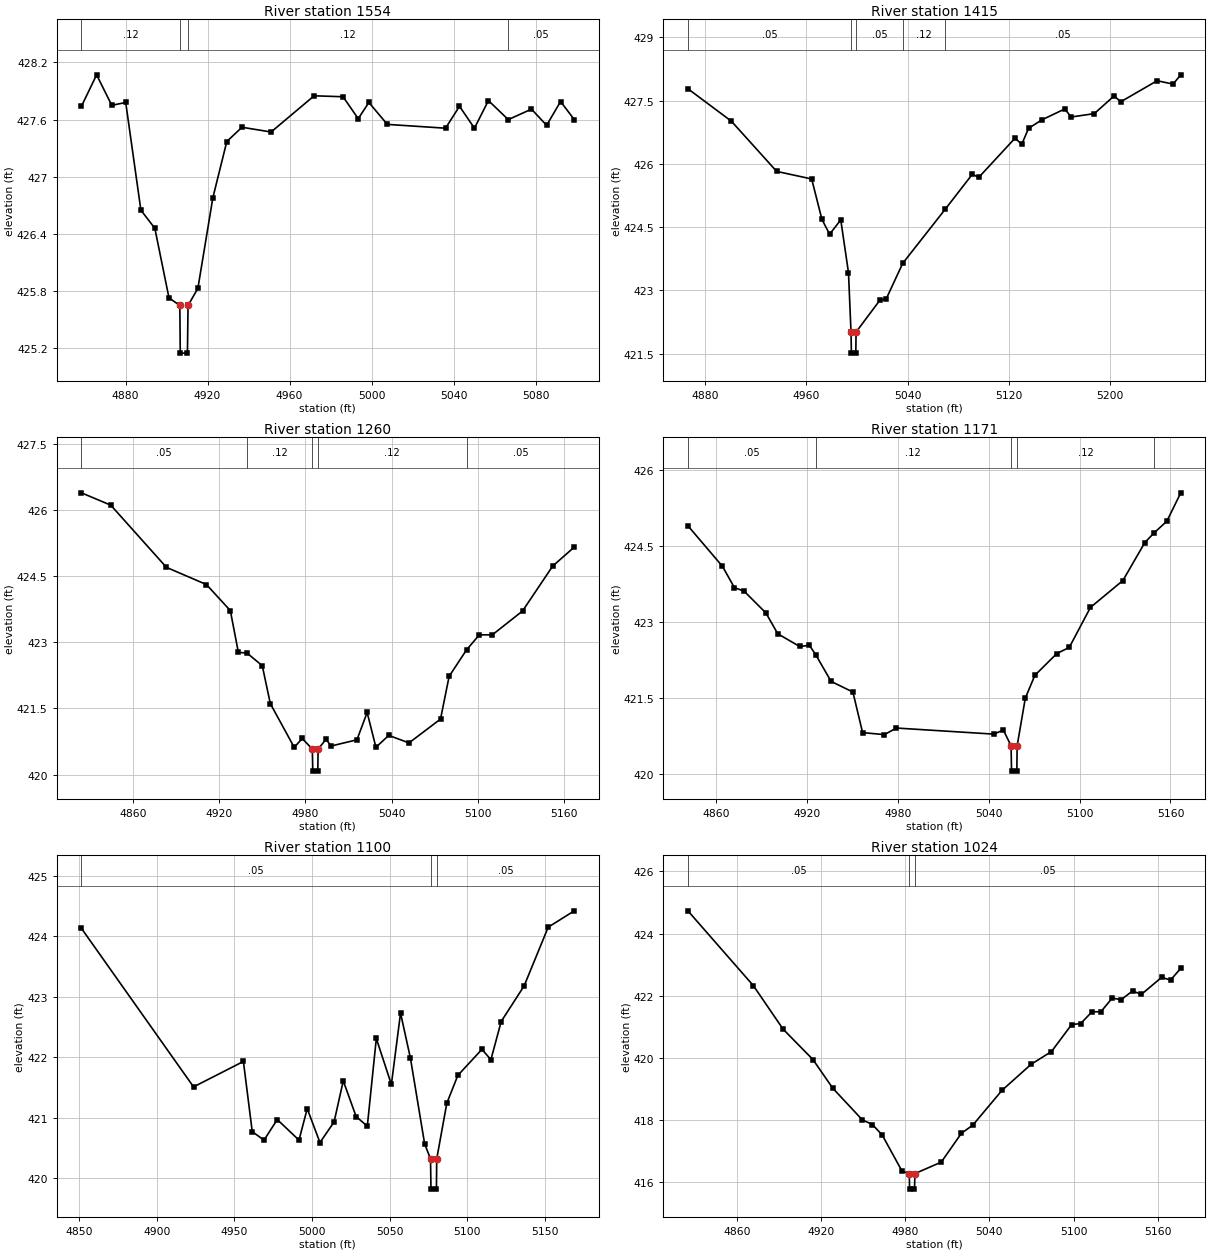
Type RM Length L Ch R = 1,1554,139,139,139
BEGIN DESCRIPTION:
Lacy 112 1584
END DESCRIPTION:
XS GIS Cut Line= 3
      2734277.38      6867511.82      2734173.31      6867607.70
      2734100.47      6867674.59
#Sta/Elev= 30
  4858.5  427.74  4865.9  428.07  4873.3  427.75  4880.1  427.78  4887.5  426.65
  4894.3  426.46  4901.2  425.73  4906.5  425.65  4906.7  425.15  4910.2  425.15
  4910.5  425.65  4915.3  425.83  4922.6  426.78  4929.4  427.37  4936.8  427.52
  4951.0  427.47  4972.0  427.85  4986.1  427.84  4993.5  427.61  4998.7  427.78
  5007.7  427.55  5036.1  427.51  5042.9  427.74  5050.2  427.51  5057.0  427.80
  5066.7  427.60  5078.0  427.71  5085.4  427.54  5092.2  427.79  5098.9  427.60
#Mann=4,-1,0
  4858.5    0.12       0  4906.5    0.07       0  4910.5    0.12       0
  5066.7    0.05       0
Bank Sta=4906.5,4910.5
Exp/Cntr=0.3,0.1

Type RM Length L Ch R = 1,1415,155,155,155
BEGIN DESCRIPTION:
Lacy 112 1583
END DESCRIPTION:
XS GIS Cut Line= 3
      2734182.51      6867380.50      2734106.41      6867490.43
      2734036.72      6867736.87
#Sta/Elev= 30
  4866.3  427.78  4900.7  427.01  4936.5  425.82  4964.2  425.64  4972.3  424.68
  4978.4  424.33  4987.2  424.67  4993.3  423.42  4995.3  422.01  4995.6  421.51
  4999.1  421.51  4999.3  422.01  5018.0  422.76  5023.2  422.80  5036.2  423.64
  5070.0  424.93  5091.2  425.75  5096.4  425.68  5125.1  426.61  5130.3  426.46
  5135.7  426.84  5146.1  427.04  5164.3  427.30  5169.5  427.11  5187.7  427.19
  5203.4  427.61  5208.6  427.47  5237.4  427.97  5250.0  427.89  5256.1  428.11
#Mann=5,-1,0
  4866.3    0.05       0  4995.3    0.04       0  4999.3    0.05       0
  5036.2    0.12       0  5070.0    0.05       0
Bank Sta=4995.3,4999.3
Exp/Cntr=0.3,0.1

Type RM Length L Ch R = 1,1260,89,89,89
BEGIN DESCRIPTION:
Lacy 112 1582
END DESCRIPTION:
XS GIS Cut Line= 3
      2734120.57      6867367.44      2733964.70      6867447.50
      2733871.20      6867586.32
#Sta/Elev= 30
  4824.3  426.39  4844.7  426.11  4883.4  424.70  4911.2  424.31  4927.8  423.72
  4933.4  422.77  4939.3  422.76  4950.0  422.47  4955.6  421.61  4972.2  420.62
  4977.8  420.82  4984.8  420.58  4985.1  420.08  4988.6  420.08  4988.8  420.58
  4994.3  420.80  4997.9  420.65  5015.8  420.79  5022.9  421.41  5029.0  420.62
  5037.9  420.89  5052.0  420.72  5073.9  421.26  5079.9  422.23  5092.0  422.83
  5100.9  423.17  5109.9  423.17  5130.9  423.71  5151.9  424.73  5166.9  425.16
#Mann=5,-1,0
  4824.3    0.05       0  4939.3    0.12       0  4984.8    0.07       0
  4988.8    0.12       0  5092.0    0.05       0
Bank Sta=4984.8,4988.8
Exp/Cntr=0.3,0.1

Type RM Length L Ch R = 1,1171,71,71,71
BEGIN DESCRIPTION:
Lacy 112 1581
END DESCRIPTION:
XS GIS Cut Line= 3
      2734023.14      6867285.27      2733900.67      6867385.89
      2733799.24      6867518.30
#Sta/Elev= 30
  4841.5  424.89  4864.3  424.09  4872.2  423.67  4878.6  423.60  4893.0  423.17
  4900.8  422.76  4915.2  422.51  4921.7  422.53  4925.8  422.35  4936.0  421.82
  4950.4  421.61  4956.8  420.81  4971.2  420.77  4979.1  420.90  5043.4  420.78
  5049.7  420.86  5054.8  420.55  5055.1  420.05  5058.6  420.05  5058.8  420.55
  5064.2  421.49  5070.5  421.94  5085.0  422.37  5093.2  422.49  5107.2  423.28
  5128.6  423.81  5143.1  424.56  5149.2  424.75  5157.6  424.98  5166.8  425.54
#Mann=5,-1,0
  4841.5    0.05       0  4925.8    0.12       0  5054.8    0.07       0
  5058.8    0.12       0  5149.2    0.05       0
Bank Sta=5054.8,5058.8
Exp/Cntr=0.3,0.1

Type RM Length L Ch R = 1,1100,76,76,76
BEGIN DESCRIPTION:
Lacy 112 3474
END DESCRIPTION:
XS GIS Cut Line= 3
      2733978.87      6867263.61      2733851.63      6867334.03
      2733762.97      6867481.39
#Sta/Elev= 30
  4851.5  424.13  4923.7  421.51  4955.8  421.93  4961.5  420.77  4969.1  420.63
  4977.6  420.97  4991.6  420.63  4996.9  421.15  5005.1  420.59  5014.2  420.93
  5020.1  421.61  5028.4  421.02  5035.6  420.86  5041.4  422.31  5051.1  421.55
  5057.0  422.73  5063.4  421.98  5072.5  420.57  5076.3  420.32  5076.6  419.82
  5080.1  419.82  5080.3  420.32  5086.8  421.24  5093.9  421.70  5109.4  422.13
  5115.2  421.96  5121.8  422.59  5136.6  423.18  5152.1  424.15  5168.9  424.42
#Mann=3,-1,0
  4851.5    0.05       0  5076.3    0.04       0  5080.3    0.05       0
Bank Sta=5076.3,5080.3
Exp/Cntr=0.3,0.1

Type RM Length L Ch R = 1,1024,0,0,0
BEGIN DESCRIPTION:
Lacy 112 1580
END DESCRIPTION:
XS GIS Cut Line= 3
      2733904.33      6867183.26      2733782.05      6867308.46
      2733672.92      6867447.18
#Sta/Elev= 30
  4825.0  424.73  4871.7  422.32  4892.9  420.92  4914.2  419.94  4928.3  419.02
  4949.4  418.00  4956.6  417.85  4963.6  417.51  4977.7  416.35  4982.9  416.27
  4983.1  415.77  4986.6  415.77  4986.9  416.27  5005.7  416.64  5020.1  417.57
  5028.2  417.83  5049.0  418.95  5069.8  419.79  5084.3  420.20  5098.7  421.07
  5105.1  421.10  5113.2  421.48  5119.5  421.48  5127.6  421.92  5134.0  421.87
  5142.1  422.15  5148.4  422.04  5162.9  422.59  5169.2  422.50  5176.5  422.88
#Mann=3,-1,0
  4825.0    0.05       0  4982.9    0.04       0  4986.9    0.05       0
Bank Sta=4982.9,4986.9
Exp/Cntr=0.3,0.1

Chan Stop Cuts=-1