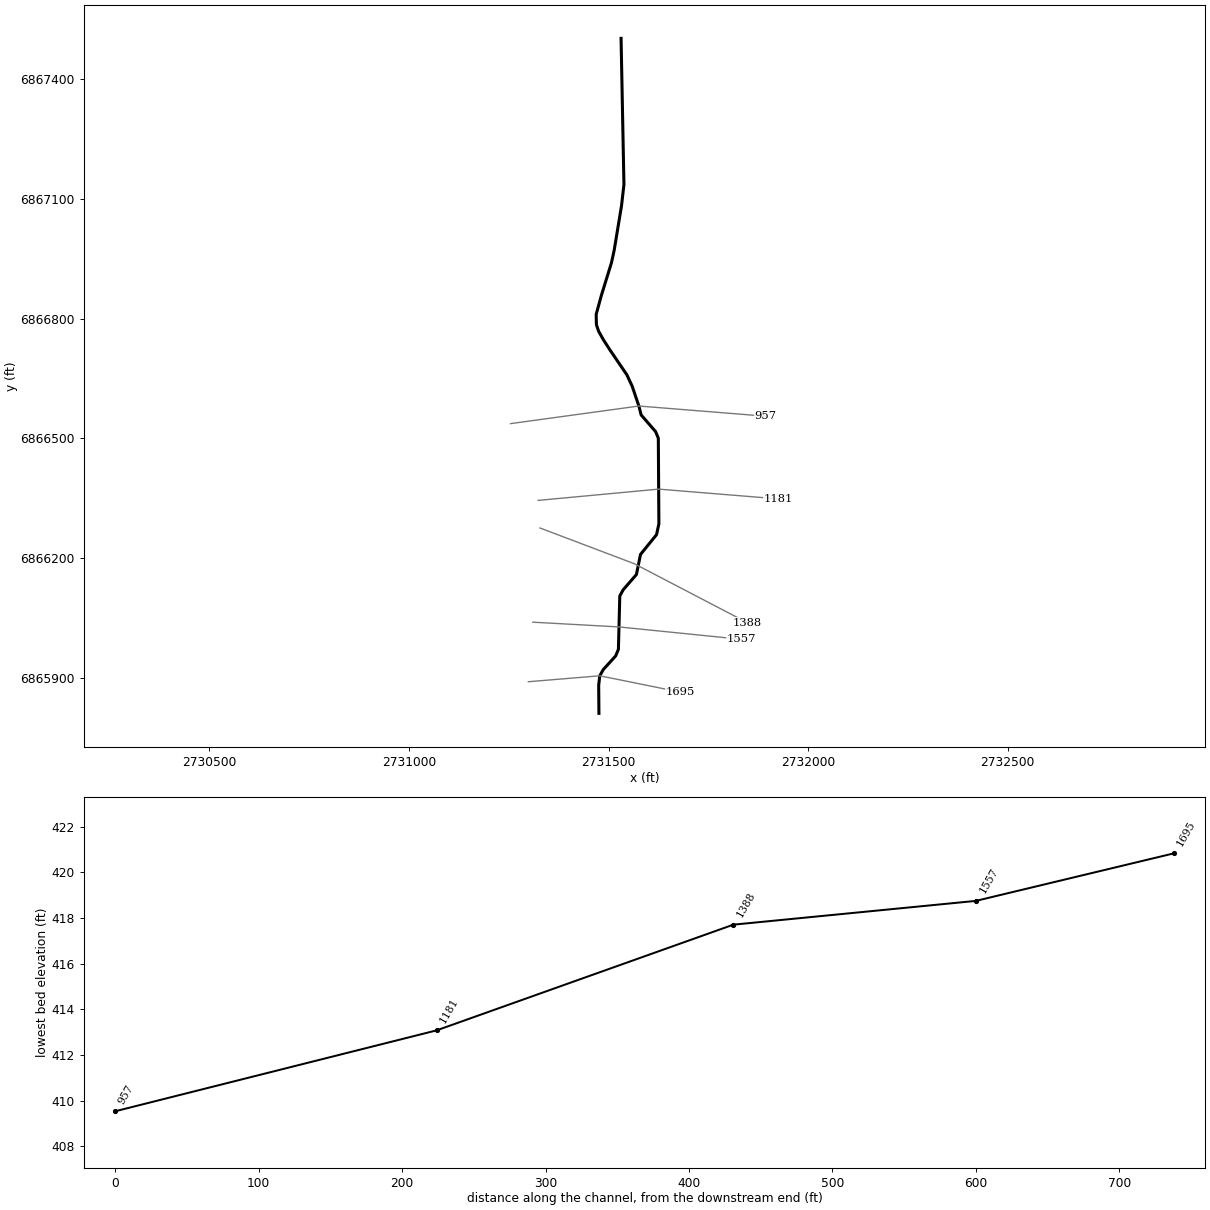
--- Lacy 113.prj (project) ---

Proj Title=Lacy 113 Base Level Engineering
Current Plan=p01
Default Exp/Contr=0.3,0.1
English Units
Geom File=g01
Flow File=f01
Plan File=p01
BEGIN DESCRIPTION:
Lacy 113
END DESCRIPTION:

--- Lacy 113.p01 (plan) ---

Plan Title=Multiple Run
Short Identifier=Multiple
Geom File=g01
Flow File=f01
Subcritical Flow
K Sum by GR= 0
Std Step Tol= 0.01
Critical Tol= 0.01
Num of Std Step Trials= 20
Max Error Tol= 0.3
Flow Tol Ratio= 0.001
Split Flow NTrial= 30
Split Flow Tol= 0.02
Split Flow Ratio= 0.02
Log Output Level= 0
Friction Slope Method= 1
Unsteady Friction Slope Method= 2
Unsteady Bridges Friction Slope Method= 1
Parabolic Critical Depth
Global Vel Dist=  1 , 1 , 1
Global Log Level= 0
CheckData=True
Encroach Param= -1, 0, 0, 0
BEGIN DESCRIPTION:
Multiple Run
END DESCRIPTION:

--- Lacy 113.f01 (steady flow) ---

Flow Title=Multiple
Number of Profiles=7
Profile Names=10-year,25-year,50-year,1pct_min,100-year,1pct_plu,500-year
River Rch & RM= Lacy 113,Reach-1,1695
     112     133     148      83     165     330     204
Boundary for River Rch & Prof#=Lacy 113,Reach-1,1
Up Type=0
Dn Type=3
Dn Slope=0.005
Boundary for River Rch & Prof#=Lacy 113,Reach-1,2
Up Type=0
Dn Type=3
Dn Slope=0.005
Boundary for River Rch & Prof#=Lacy 113,Reach-1,3
Up Type=0
Dn Type=3
Dn Slope=0.005
Boundary for River Rch & Prof#=Lacy 113,Reach-1,4
Up Type=0
Dn Type=3
Dn Slope=0.005
Boundary for River Rch & Prof#=Lacy 113,Reach-1,5
Up Type=0
Dn Type=3
Dn Slope=0.005
Boundary for River Rch & Prof#=Lacy 113,Reach-1,6
Up Type=0
Dn Type=3
Dn Slope=0.005
Boundary for River Rch & Prof#=Lacy 113,Reach-1,7
Up Type=0
Dn Type=3
Dn Slope=0.005

--- Lacy 113.g01 (geometry) ---

Geom Title=Existing Conditions

River Reach=Lacy 113,Reach-1
Reach XY= 29
      2731476.00      6865811.00      2731475.37      6865881.26
      2731478.10      6865905.13      2731486.86      6865920.65
      2731517.90      6865954.93      2731524.79      6865971.50
      2731528.25      6866105.07      2731536.80      6866120.67
      2731569.88      6866158.82      2731580.19      6866209.26
      2731620.29      6866258.65      2731626.21      6866285.91
      2731624.78      6866500.50      2731617.86      6866517.06
      2731581.75      6866558.67      2731576.07      6866581.03
      2731559.19      6866630.92      2731546.04      6866659.19
      2731504.23      6866720.55      2731486.71      6866747.84
      2731475.21      6866768.35      2731469.69      6866784.68
      2731469.08      6866810.64      2731481.92      6866857.48
      2731507.49      6866940.34      2731514.11      6866970.81
      2731532.58      6867082.72      2731538.66      6867135.90
      2731531.46      6867502.20

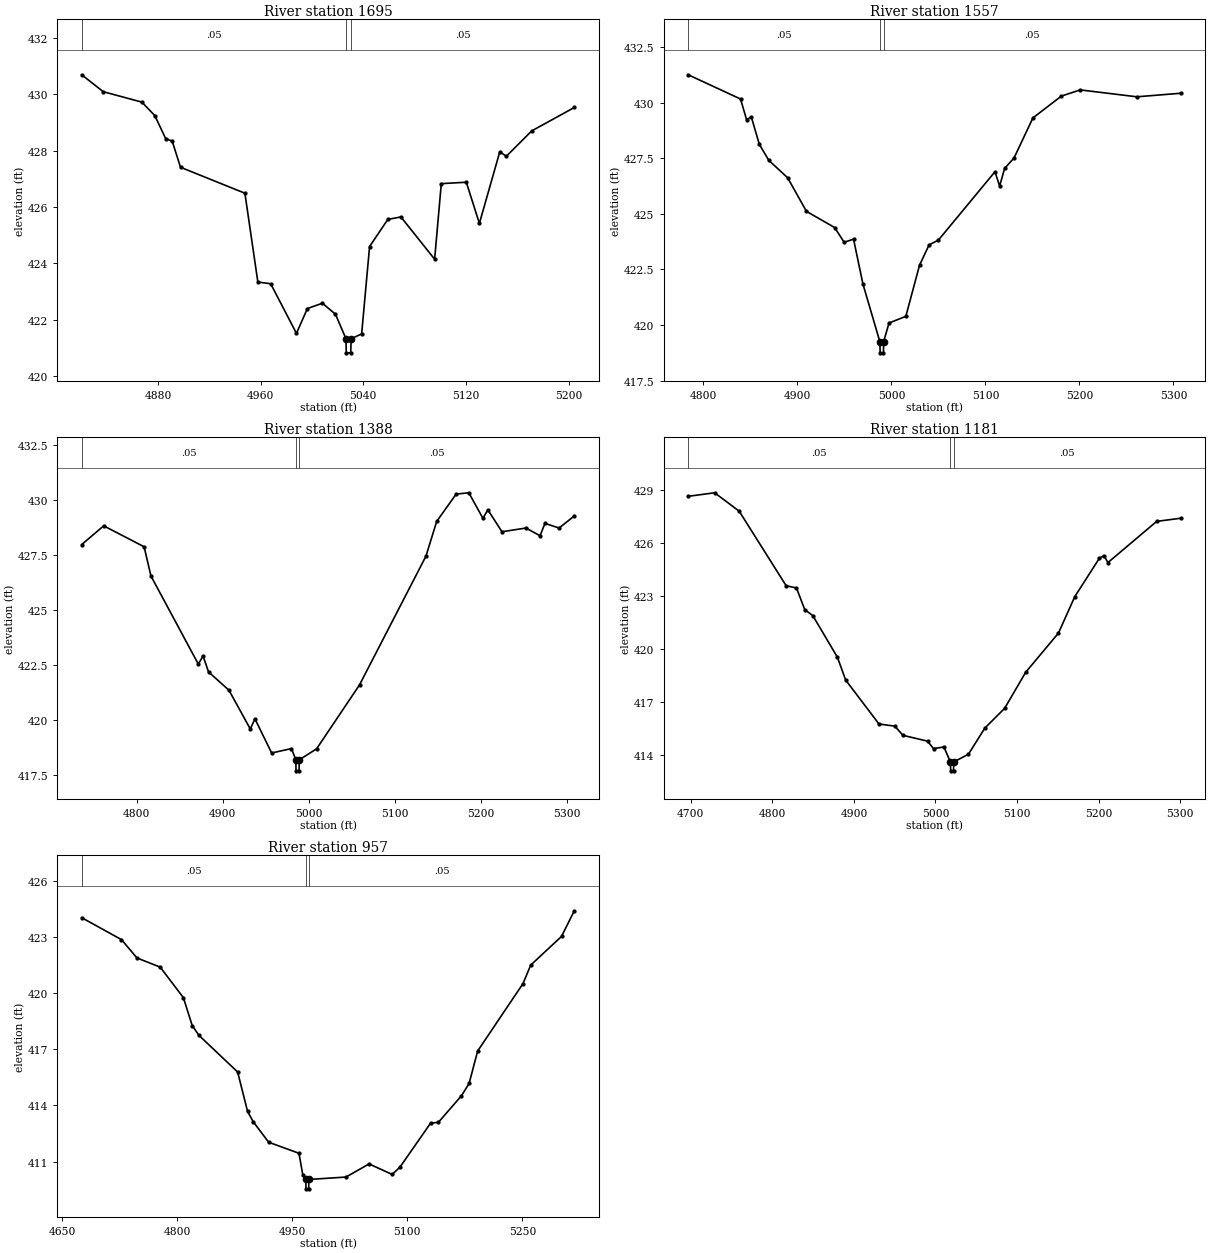
Type RM Length L Ch R = 1,1695,138,138,138
BEGIN DESCRIPTION:
Lacy 113 1574
END DESCRIPTION:
XS GIS Cut Line= 3
      2731299.22      6865890.30      2731478.10      6865905.13
      2731678.55      6865864.60
#Sta/Elev= 30
  4820.5  430.69  4837.3  430.09  4867.4  429.72  4877.5  429.24  4886.0  428.42
  4891.0  428.34  4897.5  427.41  4947.7  426.49  4957.8  423.34  4967.8  423.28
  4987.9  421.52  4996.4  422.40  5008.1  422.59  5018.3  422.20  5026.5  421.33
  5026.7  420.83  5030.2  420.83  5030.5  421.33  5038.7  421.50  5044.9  424.60
  5059.1  425.56  5069.3  425.65  5095.6  424.15  5100.8  426.83  5120.3  426.88
  5130.5  425.42  5146.4  427.96  5151.5  427.80  5171.3  428.70  5204.5  429.53
#Mann=3,-1,0
  4820.5    0.05       0  5026.5    0.05       0  5030.5    0.05       0
Bank Sta=5026.5,5030.5
Exp/Cntr=0.3,0.1

Type RM Length L Ch R = 1,1557,169,169,169
BEGIN DESCRIPTION:
Lacy 113 1573
END DESCRIPTION:
XS GIS Cut Line= 3
      2731310.37      6866039.49      2731526.24      6866027.58
      2731832.47      6865996.57
#Sta/Elev= 30
  4783.8  431.25  4839.5  430.16  4845.9  429.23  4850.9  429.36  4859.5  428.12
  4869.6  427.40  4889.6  426.62  4909.6  425.11  4939.7  424.38  4949.7  423.72
  4959.7  423.86  4969.7  421.84  4987.7  419.25  4988.0  418.75  4991.5  418.75
  4991.7  419.25  4997.4  420.09  5015.3  420.39  5029.9  422.69  5040.0  423.60
  5050.0  423.82  5110.1  426.89  5115.1  426.25  5120.4  427.04  5130.4  427.51
  5150.5  429.31  5180.7  430.29  5200.8  430.57  5261.1  430.26  5307.8  430.42
#Mann=3,-1,0
  4783.8    0.05       0  4987.7    0.05       0  4991.7    0.05       0
Bank Sta=4987.7,4991.7
Exp/Cntr=0.3,0.1

Type RM Length L Ch R = 1,1388,207,207,207
BEGIN DESCRIPTION:
Lacy 113 1572
END DESCRIPTION:
XS GIS Cut Line= 3
      2731328.32      6866275.44      2731564.33      6866186.08
      2731847.65      6866038.32
#Sta/Elev= 30
  4736.3  427.98  4761.8  428.83  4808.7  427.88  4816.7  426.55  4871.7  422.55
  4877.1  422.93  4883.5  422.20  4907.2  421.37  4932.0  419.61  4937.4  420.07
  4956.8  418.52  4979.8  418.72  4984.9  418.21  4985.1  417.71  4988.6  417.71
  4988.9  418.21  5009.0  418.71  5058.8  421.61  5135.9  427.45  5148.4  429.03
  5171.0  430.27  5185.7  430.33  5202.1  429.17  5207.8  429.56  5224.2  428.56
  5252.0  428.73  5268.4  428.38  5274.1  428.94  5290.5  428.73  5308.2  429.28
#Mann=3,-1,0
  4736.3    0.05       0  4984.9    0.05       0  4988.9    0.05       0
Bank Sta=4984.9,4988.9
Exp/Cntr=0.3,0.1

Type RM Length L Ch R = 1,1181,224,224,224
BEGIN DESCRIPTION:
Lacy 113 1571
END DESCRIPTION:
XS GIS Cut Line= 3
      2731323.75      6866344.60      2731625.63      6866372.84
      2731925.54      6866348.39
#Sta/Elev= 30
  4696.8  428.62  4729.2  428.82  4759.3  427.78  4816.9  423.56  4829.6  423.43
  4839.7  422.21  4849.7  421.86  4879.8  419.51  4889.9  418.22  4930.8  415.73
  4950.2  415.61  4960.2  415.09  4990.3  414.76  4997.7  414.34  5010.4  414.43
  5018.4  413.58  5018.7  413.08  5022.2  413.08  5022.4  413.58  5040.5  414.02
  5060.6  415.50  5084.9  416.62  5110.7  418.66  5150.9  420.88  5170.9  422.94
  5201.0  425.11  5206.6  425.26  5211.6  424.87  5271.3  427.20  5300.9  427.38
#Mann=3,-1,0
  4696.8    0.05       0  5018.4    0.05       0  5022.4    0.05       0
Bank Sta=5018.4,5022.4
Exp/Cntr=0.3,0.1

Type RM Length L Ch R = 1,957,0,0,0
BEGIN DESCRIPTION:
Lacy 113 1570
END DESCRIPTION:
XS GIS Cut Line= 3
      2731254.68      6866536.94      2731576.07      6866581.03
      2731892.65      6866555.59
#Sta/Elev= 30
  4675.6  424.02  4727.4  422.85  4747.6  421.87  4777.9  421.38  4808.1  419.75
  4819.6  418.26  4828.3  417.74  4878.8  415.78  4891.7  413.68  4899.0  413.13
  4919.2  412.03  4958.7  411.44  4963.8  410.27  4967.6  410.04  4967.9  409.54
  4971.4  409.54  4971.6  410.04  5020.0  410.17  5050.1  410.87  5080.2  410.31
  5090.2  410.69  5130.3  413.05  5140.4  413.09  5170.5  414.51  5180.5  415.17
  5191.6  416.90  5250.7  420.50  5260.8  421.49  5300.9  423.02  5317.6  424.39
#Mann=3,-1,0
  4675.6    0.05       0  4967.6    0.04       0  4971.6    0.05       0
Bank Sta=4967.6,4971.6
Exp/Cntr=0.3,0.1

Chan Stop Cuts=-1