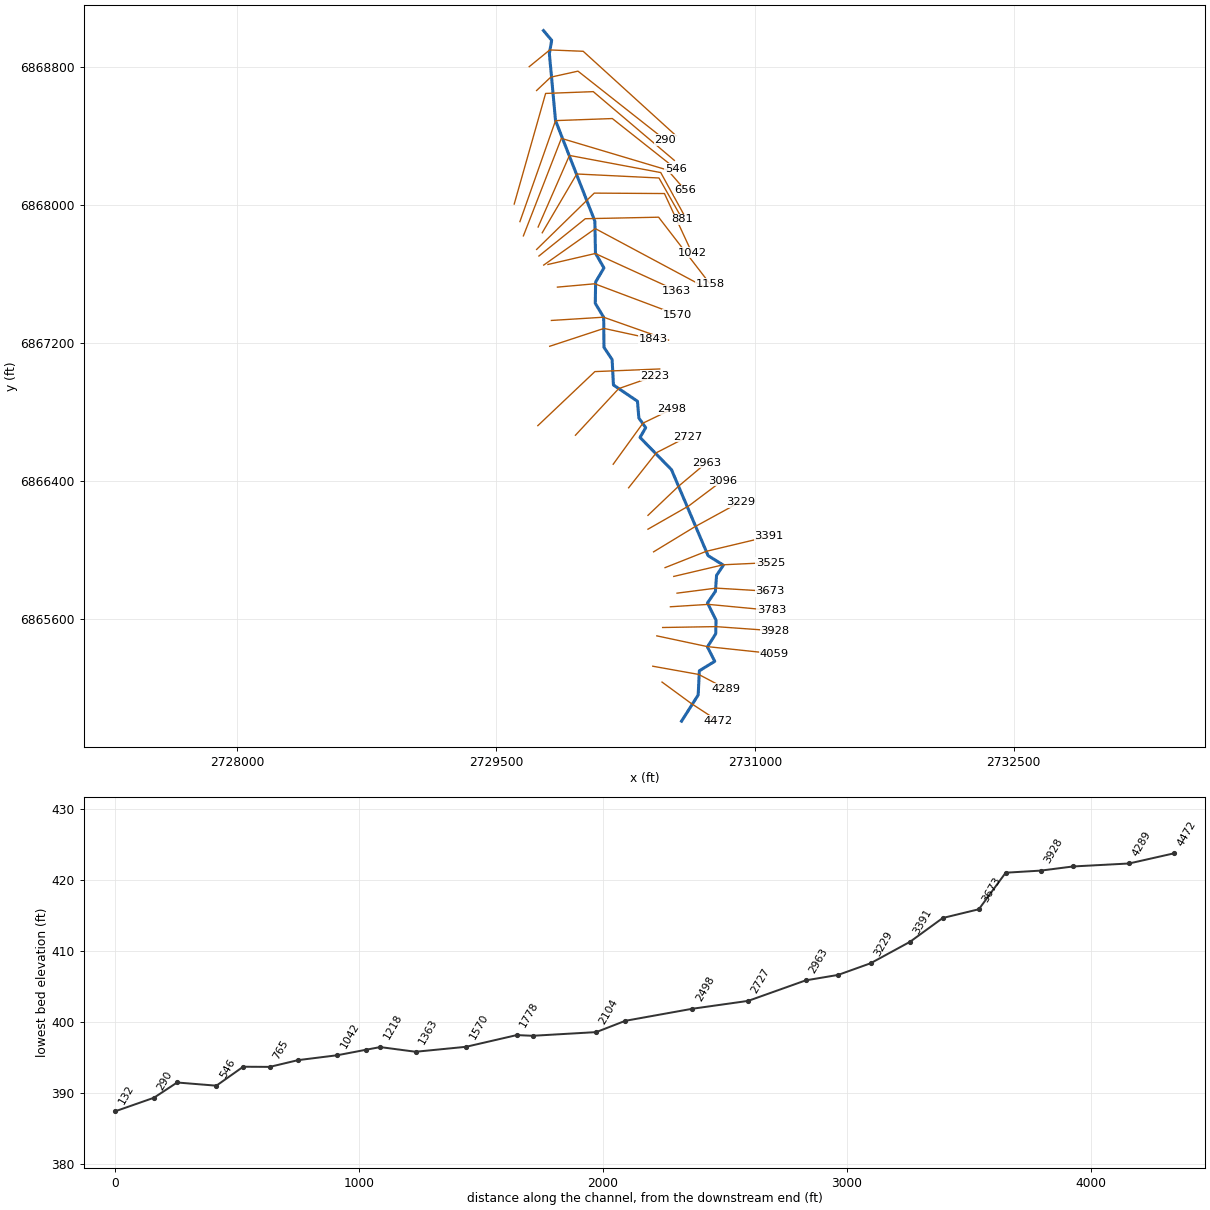
--- Lacy 114.prj (project) ---

Proj Title=Lacy 114 Base Level Engineering
Current Plan=p01
Default Exp/Contr=0.3,0.1
English Units
Geom File=g01
Flow File=f01
Plan File=p01
BEGIN DESCRIPTION:
Lacy 114
END DESCRIPTION:

--- Lacy 114.p01 (plan) ---

Plan Title=Multiple Run
Short Identifier=Multiple
Geom File=g01
Flow File=f01
Subcritical Flow
K Sum by GR= 0
Std Step Tol= 0.01
Critical Tol= 0.01
Num of Std Step Trials= 20
Max Error Tol= 0.3
Flow Tol Ratio= 0.001
Split Flow NTrial= 30
Split Flow Tol= 0.02
Split Flow Ratio= 0.02
Log Output Level= 0
Friction Slope Method= 1
Unsteady Friction Slope Method= 2
Unsteady Bridges Friction Slope Method= 1
Parabolic Critical Depth
Global Vel Dist=  1 , 1 , 1
Global Log Level= 0
CheckData=True
Encroach Param= -1, 0, 0, 0
BEGIN DESCRIPTION:
Multiple Run
END DESCRIPTION:

--- Lacy 114.f01 (steady flow) ---

Flow Title=Multiple
Number of Profiles=7
Profile Names=10-year,25-year,50-year,1pct_min,100-year,1pct_plu,500-year
River Rch & RM= Lacy 114,Reach-1,4472
     351     453     532     311     620    1237     840
Boundary for River Rch & Prof#=Lacy 114,Reach-1,1
Up Type=0
Dn Type=3
Dn Slope=0.005
Boundary for River Rch & Prof#=Lacy 114,Reach-1,2
Up Type=0
Dn Type=3
Dn Slope=0.005
Boundary for River Rch & Prof#=Lacy 114,Reach-1,3
Up Type=0
Dn Type=3
Dn Slope=0.005
Boundary for River Rch & Prof#=Lacy 114,Reach-1,4
Up Type=0
Dn Type=3
Dn Slope=0.005
Boundary for River Rch & Prof#=Lacy 114,Reach-1,5
Up Type=0
Dn Type=3
Dn Slope=0.005
Boundary for River Rch & Prof#=Lacy 114,Reach-1,6
Up Type=0
Dn Type=3
Dn Slope=0.005
Boundary for River Rch & Prof#=Lacy 114,Reach-1,7
Up Type=0
Dn Type=3
Dn Slope=0.005

--- Lacy 114.g01 (geometry) ---

Geom Title=Existing Conditions

River Reach=Lacy 114,Reach-1
Reach XY= 30
      2730576.00      6865011.00      2730672.25      6865162.56
      2730679.13      6865302.69      2730768.24      6865357.36
      2730725.80      6865440.79      2730773.81      6865516.97
      2730775.60      6865595.73      2730726.09      6865695.61
      2730772.12      6865762.59      2730778.56      6865855.12
      2730818.27      6865914.65      2730729.56      6865969.48
      2730517.86      6866467.06      2730335.30      6866654.33
      2730368.20      6866710.90      2730328.55      6866766.90
      2730320.58      6866863.67      2730181.36      6866958.30
      2730173.73      6867105.06      2730126.52      6867176.22
      2730124.78      6867350.49      2730076.05      6867431.04
      2730078.28      6867555.07      2730126.40      6867636.00
      2730077.24      6867721.50      2730073.68      6867906.90
      2729845.94      6868489.51      2729810.22      6868877.24
      2729823.44      6868954.84      2729776.00      6869011.00

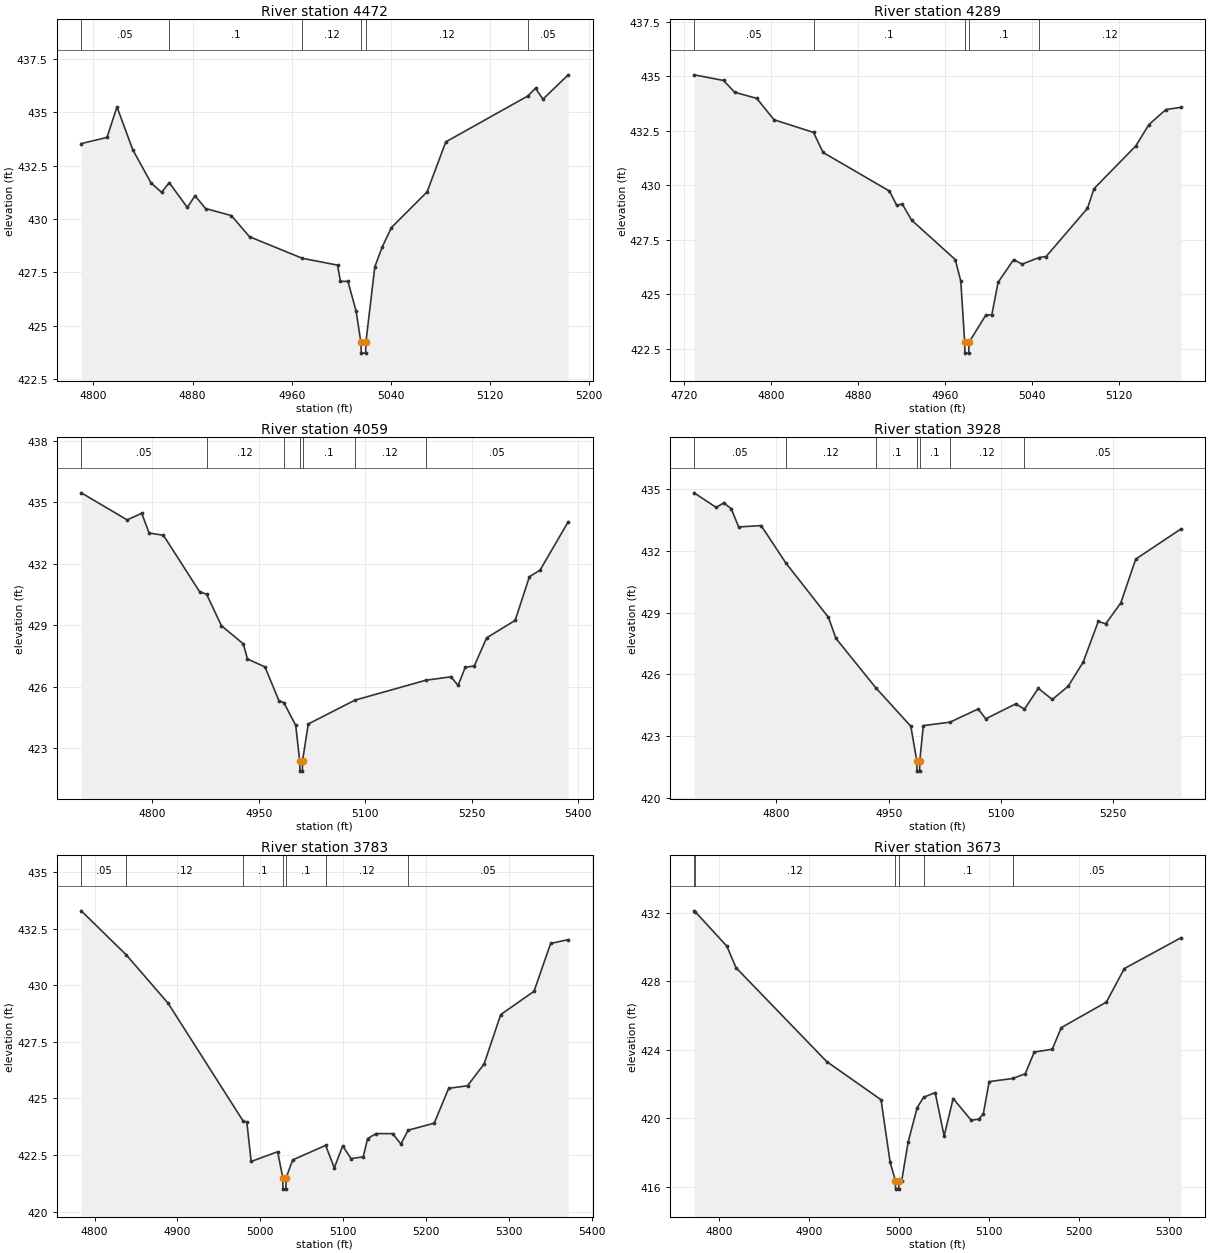
Type RM Length L Ch R = 1,4472,183,183,183
BEGIN DESCRIPTION:
Lacy 114 1543
END DESCRIPTION:
XS GIS Cut Line= 3
      2730462.81      6865237.23      2730632.03      6865113.22
      2730785.52      6865013.20
#Sta/Elev= 30
  4790.2  433.53  4811.0  433.82  4819.0  435.25  4831.8  433.24  4846.5  431.69
  4855.0  431.25  4861.2  431.70  4875.8  430.54  4882.0  431.09  4890.5  430.49
  4911.3  430.16  4926.0  429.17  4968.6  428.16  4997.0  427.84  4999.4  427.08
  5005.4  427.08  5012.0  425.69  5015.9  424.22  5016.2  423.72  5019.7  423.72
  5019.9  424.22  5027.1  427.76  5033.1  428.69  5040.5  429.60  5069.3  431.27
  5084.4  433.61  5150.6  435.76  5156.8  436.12  5162.8  435.61  5183.2  436.75
#Mann=6,-1,0
  4790.2    0.05       0  4861.2     0.1       0  4968.6    0.12       0
  5015.9    0.07       0  5019.9    0.12       0  5150.6    0.05       0
Bank Sta=5015.9,5019.9
Exp/Cntr=0.3,0.1

Type RM Length L Ch R = 1,4289,230,230,230
BEGIN DESCRIPTION:
Lacy 114 1542
END DESCRIPTION:
XS GIS Cut Line= 3
      2730409.33      6865329.03      2730675.51      6865281.42
      2730832.10      6865198.91
#Sta/Elev= 30
  4729.6  435.06  4756.7  434.80  4766.8  434.26  4787.2  433.98  4803.0  433.00
  4839.3  432.42  4848.1  431.50  4909.1  429.73  4915.7  429.08  4920.8  429.14
  4929.4  428.40  4969.5  426.59  4974.6  425.61  4978.2  422.80  4978.4  422.30
  4981.9  422.30  4982.2  422.80  4997.7  424.05  5003.1  424.05  5008.9  425.55
  5023.2  426.59  5030.9  426.38  5046.4  426.68  5053.0  426.73  5091.0  428.94
  5097.0  429.84  5135.4  431.80  5147.5  432.78  5163.1  433.47  5177.0  433.57
#Mann=5,-1,0
  4729.6    0.05       0  4839.3     0.1       0  4978.2    0.07       0
  4982.2     0.1       0  5046.4    0.12       0
Bank Sta=4978.2,4982.2
Exp/Cntr=0.3,0.1

Type RM Length L Ch R = 1,4059,131,131,131
BEGIN DESCRIPTION:
Lacy 114 1540
END DESCRIPTION:
XS GIS Cut Line= 3
      2730432.69      6865504.92      2730725.90      6865442.56
      2731110.38      6865401.82
#Sta/Elev= 30
  4699.9  435.45  4764.6  434.13  4785.1  434.45  4795.6  433.49  4815.7  433.38
  4866.9  430.62  4876.5  430.51  4897.5  428.97  4928.2  428.09  4934.2  427.35
  4958.9  426.96  4978.7  425.30  4985.5  425.22  5002.2  424.11  5007.8  422.38
  5008.1  421.88  5011.6  421.88  5011.8  422.38  5019.9  424.18  5085.6  425.34
  5185.4  426.31  5221.0  426.48  5231.1  426.06  5241.1  426.94  5253.9  427.01
  5271.3  428.38  5311.5  429.23  5331.6  431.36  5346.6  431.68  5386.3  434.04
#Mann=7,-1,0
  4699.9    0.05       0  4876.5    0.12       0  4985.5     0.1       0
  5007.8    0.07       0  5011.8     0.1       0  5085.6    0.12       0
  5185.4    0.05       0
Bank Sta=5007.8,5011.8
Exp/Cntr=0.3,0.1

Type RM Length L Ch R = 1,3928,145,145,145
BEGIN DESCRIPTION:
Lacy 114 1539
END DESCRIPTION:
XS GIS Cut Line= 3
      2730466.38      6865553.34      2730774.55      6865558.43
      2731116.46      6865534.01
#Sta/Elev= 30
  4689.9  434.82  4719.5  434.11  4729.5  434.33  4739.5  434.05  4749.5  433.16
  4779.5  433.23  4812.4  431.42  4869.5  428.77  4879.5  427.75  4933.0  425.34
  4979.6  423.48  4987.6  421.80  4987.8  421.30  4991.3  421.30  4991.6  421.80
  4996.3  423.51  5032.1  423.68  5069.7  424.32  5079.8  423.84  5119.9  424.57
  5131.5  424.31  5150.0  425.32  5168.8  424.78  5190.1  425.43  5210.1  426.60
  5230.2  428.57  5240.2  428.46  5260.2  429.46  5280.3  431.60  5340.9  433.07
#Mann=7,-1,0
  4689.9    0.05       0  4812.4    0.12       0  4933.0     0.1       0
  4987.6    0.07       0  4991.6     0.1       0  5032.1    0.12       0
  5131.5    0.05       0
Bank Sta=4987.6,4991.6
Exp/Cntr=0.3,0.1

Type RM Length L Ch R = 1,3783,110,110,110
BEGIN DESCRIPTION:
Lacy 114 1538
END DESCRIPTION:
XS GIS Cut Line= 3
      2730511.27      6865673.46      2730731.15      6865687.29
      2731097.10      6865652.62
#Sta/Elev= 30
  4783.9  433.28  4838.4  431.33  4888.8  429.20  4979.4  424.00  4983.8  423.96
  4989.0  422.22  5021.0  422.65  5027.2  421.50  5027.4  421.00  5030.9  421.00
  5031.2  421.50  5039.2  422.29  5078.9  422.93  5089.4  421.94  5099.5  422.91
  5109.5  422.35  5124.3  422.42  5129.6  423.23  5139.7  423.45  5159.8  423.45
  5169.8  422.99  5178.5  423.60  5210.0  423.91  5227.5  425.45  5250.2  425.56
  5270.2  426.52  5290.3  428.70  5330.5  429.73  5350.6  431.84  5371.8  432.01
#Mann=7,-1,0
  4783.9    0.05       0  4838.4    0.12       0  4979.4     0.1       0
  5027.2    0.07       0  5031.2     0.1       0  5078.9    0.12       0
  5178.5    0.05       0
Bank Sta=5027.2,5031.2
Exp/Cntr=0.3,0.1

Type RM Length L Ch R = 1,3673,148,148,148
BEGIN DESCRIPTION:
Lacy 114 1537
END DESCRIPTION:
XS GIS Cut Line= 3
      2730549.82      6865752.30      2730776.64      6865781.45
      2731089.00      6865762.82
#Sta/Elev= 30
  4772.2  432.10  4773.6  432.04  4808.7  430.03  4818.8  428.78  4919.6  423.30
  4980.1  421.07  4990.2  417.42  4996.0  416.35  4996.3  415.85  4999.8  415.85
  5000.0  416.35  5003.1  416.35  5010.3  418.61  5020.3  420.61  5027.4  421.21
  5040.3  421.49  5050.3  418.95  5060.3  421.14  5080.4  419.87  5088.9  419.94
  5093.9  420.26  5100.4  422.13  5126.7  422.31  5140.5  422.59  5150.5  423.85
  5170.5  424.02  5180.6  425.28  5230.7  426.77  5250.7  428.73  5313.8  430.53
#Mann=6,-1,0
  4772.2    0.05       0  4773.6    0.12       0  4996.0    0.07       0
  5000.0    0.12       0  5027.4     0.1       0  5126.7    0.05       0
Bank Sta=4996,5000
Exp/Cntr=0.3,0.1

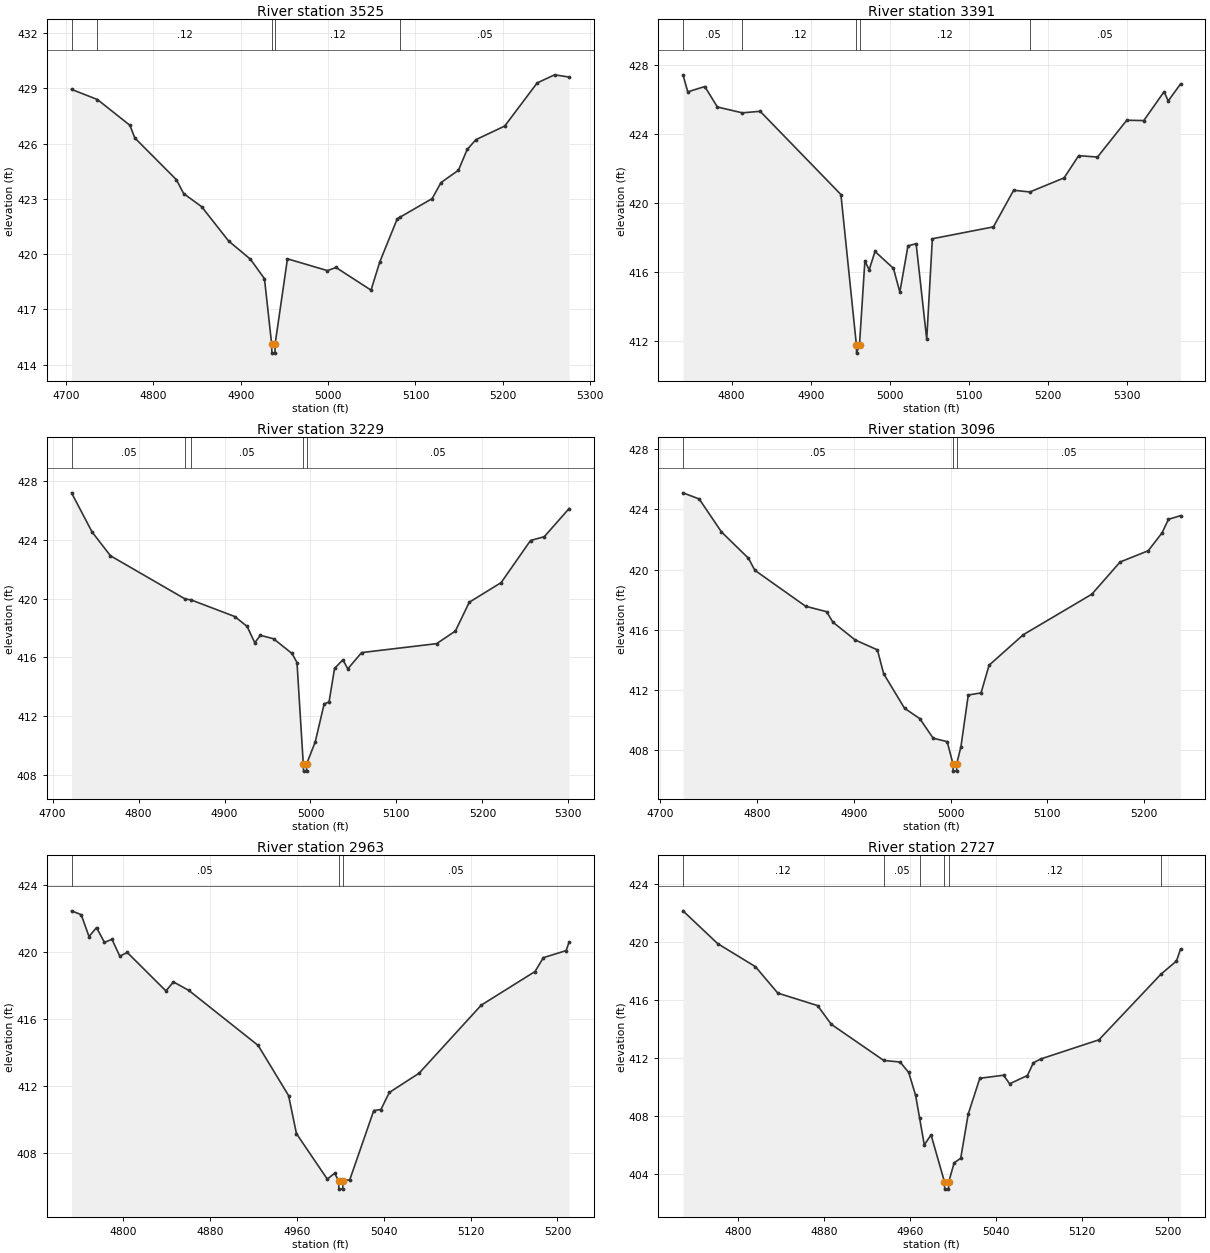
Type RM Length L Ch R = 1,3525,134,134,134
BEGIN DESCRIPTION:
Lacy 114 1536
END DESCRIPTION:
XS GIS Cut Line= 3
      2730531.00      6865849.27      2730817.50      6865916.62
      2731092.58      6865929.55
#Sta/Elev= 30
  4706.2  428.94  4735.8  428.39  4773.0  426.99  4778.7  426.30  4826.2  424.04
  4834.6  423.28  4855.2  422.57  4886.0  420.71  4911.0  419.72  4927.1  418.66
  4935.3  415.12  4935.6  414.62  4939.1  414.62  4939.3  415.12  4953.4  419.74
  4999.2  419.10  5009.0  419.27  5049.1  418.04  5059.1  419.57  5079.1  421.91
  5081.9  421.99  5119.1  423.01  5129.2  423.88  5149.2  424.55  5159.2  425.68
  5169.2  426.21  5202.2  426.95  5239.3  429.29  5259.3  429.73  5275.9  429.61
#Mann=5,-1,0
  4706.2    0.05       0  4735.8    0.12       0  4935.3    0.07       0
  4939.3    0.12       0  5081.9    0.05       0
Bank Sta=4935.3,4939.3
Exp/Cntr=0.3,0.1

Type RM Length L Ch R = 1,3391,162,162,162
BEGIN DESCRIPTION:
Lacy 114 1535
END DESCRIPTION:
XS GIS Cut Line= 3
      2730480.31      6865900.04      2730718.42      6865994.38
      2731081.25      6866080.80
#Sta/Elev= 30
  4738.5  427.45  4744.6  426.46  4766.1  426.77  4782.0  425.58  4813.5  425.24
  4836.1  425.33  4938.2  420.49  4957.7  411.77  4958.0  411.27  4961.7  411.77
  4968.5  416.63  4973.9  416.11  4981.3  417.18  5004.6  416.20  5012.7  414.82
  5023.0  417.51  5033.3  417.63  5046.7  412.07  5053.8  417.92  5131.0  418.61
  5156.6  420.74  5177.1  420.64  5220.4  421.46  5238.8  422.75  5262.6  422.67
  5299.6  424.81  5321.1  424.79  5346.8  426.47  5352.0  425.93  5367.6  426.92
#Mann=5,-1,0
  4738.5    0.05       0  4813.5    0.12       0  4957.7    0.07       0
  4961.7    0.12       0  5177.1    0.05       0
Bank Sta=4957.7,4961.7
Exp/Cntr=0.3,0.1

Type RM Length L Ch R = 1,3229,133,133,133
BEGIN DESCRIPTION:
Lacy 114 1534
END DESCRIPTION:
XS GIS Cut Line= 3
      2730413.87      6865991.54      2730650.87      6866135.67
      2730915.36      6866280.43
#Sta/Elev= 30
  4722.0  427.21  4745.9  424.54  4767.3  422.92  4854.3  419.97  4860.7  419.92
  4911.8  418.78  4926.2  418.11  4935.2  416.99  4941.7  417.50  4957.1  417.26
  4978.5  416.26  4984.3  415.64  4991.6  408.74  4991.9  408.24  4995.4  408.24
  4995.6  408.74  5005.5  410.23  5015.9  412.82  5021.6  412.96  5028.0  415.24
  5037.7  415.83  5043.4  415.21  5059.5  416.32  5146.8  416.93  5168.6  417.79
  5184.7  419.75  5221.8  421.09  5256.0  423.96  5272.0  424.22  5300.9  426.14
#Mann=5,-1,0
  4722.0    0.05       0  4854.3    0.12       0  4860.7    0.05       0
  4991.6    0.05       0  4995.6    0.05       0
Bank Sta=4991.6,4995.6
Exp/Cntr=0.3,0.1

Type RM Length L Ch R = 1,3096,133,133,133
BEGIN DESCRIPTION:
Lacy 114 1533
END DESCRIPTION:
XS GIS Cut Line= 3
      2730381.45      6866122.83      2730618.63      6866258.30
      2730811.29      6866403.35
#Sta/Elev= 30
  4723.4  425.10  4740.2  424.69  4763.2  422.50  4791.1  420.75  4797.7  419.95
  4850.2  417.56  4871.8  417.20  4878.4  416.50  4901.4  415.32  4924.4  414.66
  4930.8  413.08  4952.4  410.78  4968.2  410.09  4982.0  408.79  4996.5  408.56
  5002.4  407.10  5002.7  406.60  5006.2  406.60  5006.4  407.10  5010.7  408.22
  5018.3  411.66  5031.5  411.80  5039.8  413.64  5075.2  415.67  5146.0  418.36
  5175.2  420.50  5204.3  421.25  5218.6  422.44  5225.2  423.34  5237.7  423.58
#Mann=3,-1,0
  4723.4    0.05       0  5002.4    0.05       0  5006.4    0.05       0
Bank Sta=5002.4,5006.4
Exp/Cntr=0.3,0.1

Type RM Length L Ch R = 1,2963,236,236,236
BEGIN DESCRIPTION:
Lacy 114 1532
END DESCRIPTION:
XS GIS Cut Line= 3
      2730381.38      6866202.91      2730560.86      6866373.83
      2730721.86      6866508.90
#Sta/Elev= 30
  4752.7  422.47  4761.6  422.24  4768.8  420.93  4775.7  421.47  4783.0  420.58
  4789.9  420.77  4797.1  419.76  4804.0  419.98  4839.6  417.68  4846.5  418.22
  4860.7  417.71  4924.5  414.42  4952.5  411.42  4959.7  409.15  4988.1  406.43
  4994.9  406.78  4998.5  406.33  4998.8  405.83  5002.3  405.83  5002.5  406.33
  5008.8  406.39  5030.9  410.53  5037.5  410.59  5045.2  411.61  5072.6  412.76
  5129.8  416.83  5179.3  418.84  5187.0  419.67  5207.9  420.09  5210.7  420.60
#Mann=3,-1,0
  4752.7    0.05       0  4998.5    0.05       0  5002.5    0.05       0
Bank Sta=4998.5,5002.5
Exp/Cntr=0.3,0.1

Type RM Length L Ch R = 1,2727,229,229,229
BEGIN DESCRIPTION:
Lacy 114 1531
END DESCRIPTION:
XS GIS Cut Line= 3
      2730269.40      6866362.67      2730429.75      6866565.57
      2730611.82      6866659.09
#Sta/Elev= 30
  4748.3  422.12  4780.6  419.86  4815.8  418.27  4836.6  416.45  4873.6  415.59
  4886.4  414.30  4935.2  411.81  4950.5  411.70  4958.5  410.98  4964.9  409.41
  4968.6  407.85  4973.0  405.99  4979.3  406.68  4991.8  403.44  4992.0  402.94
  4995.5  402.94  4995.8  403.44  5000.8  404.76  5006.9  405.06  5013.9  408.11
  5024.7  410.58  5046.8  410.79  5052.5  410.20  5069.0  410.77  5074.6  411.65
  5081.4  411.91  5135.6  413.23  5193.3  417.75  5207.8  418.66  5211.6  419.48
#Mann=6,-1,0
  4748.3    0.12       0  4935.2    0.05       0  4968.6    0.12       0
  4991.8    0.07       0  4995.8    0.12       0  5193.3    0.05       0
Bank Sta=4991.8,4995.8
Exp/Cntr=0.3,0.1

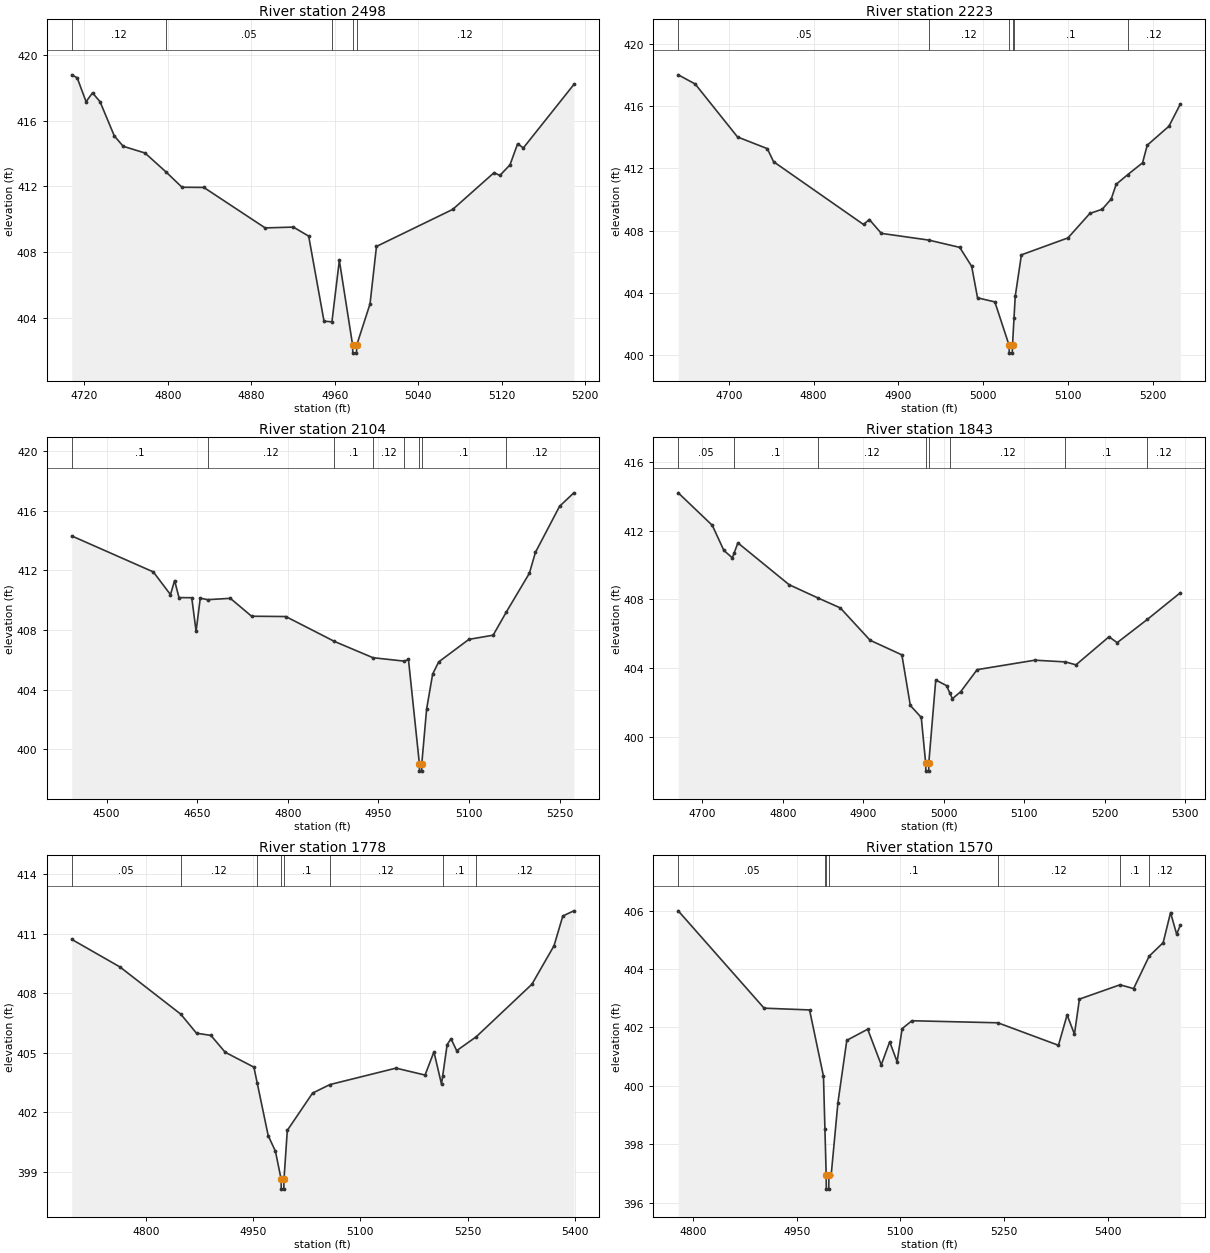
Type RM Length L Ch R = 1,2498,275,275,275
BEGIN DESCRIPTION:
Lacy 114 1530
END DESCRIPTION:
XS GIS Cut Line= 3
      2730179.92      6866499.07      2730352.32      6866736.93
      2730521.03      6866818.82
#Sta/Elev= 30
  4708.0  418.81  4713.2  418.63  4721.7  417.17  4727.9  417.71  4735.1  417.17
  4748.8  415.08  4757.3  414.45  4778.2  414.04  4798.6  412.87  4813.7  411.95
  4834.6  411.94  4893.4  409.47  4920.4  409.52  4935.1  408.97  4949.8  403.78
  4957.4  403.74  4964.5  407.49  4977.2  402.33  4977.4  401.83  4980.9  401.83
  4981.2  402.33  4993.9  404.83  5000.1  408.34  5073.2  410.60  5112.8  412.84
  5118.4  412.67  5128.1  413.32  5135.4  414.60  5140.9  414.35  5189.3  418.22
#Mann=5,-1,0
  4708.0    0.12       0  4798.6    0.05       0  4957.4    0.12       0
  4977.2    0.07       0  4981.2    0.12       0
Bank Sta=4977.2,4981.2
Exp/Cntr=0.3,0.1

Type RM Length L Ch R = 1,2223,119,119,119
BEGIN DESCRIPTION:
Lacy 114 1529
END DESCRIPTION:
XS GIS Cut Line= 3
      2729961.31      6866667.13      2730211.83      6866937.11
      2730422.86      6867010.72
#Sta/Elev= 30
  4640.4  418.00  4660.4  417.41  4710.3  414.01  4745.4  413.26  4752.8  412.42
  4858.8  408.39  4865.6  408.71  4879.8  407.82  4935.5  407.39  4972.2  406.92
  4986.3  405.70  4993.2  403.68  5013.6  403.42  5030.4  400.63  5030.6  400.13
  5034.1  400.13  5034.4  400.63  5036.2  402.40  5037.6  403.77  5044.9  406.44
  5099.8  407.53  5125.6  409.10  5140.2  409.37  5150.8  410.03  5156.6  410.97
  5170.2  411.59  5187.7  412.35  5193.2  413.48  5218.8  414.70  5232.2  416.12
#Mann=6,-1,0
  4640.4    0.05       0  4935.5    0.12       0  5030.4    0.07       0
  5034.4    0.12       0  5036.2     0.1       0  5170.2    0.12       0
Bank Sta=5030.4,5034.4
Exp/Cntr=0.3,0.1

Type RM Length L Ch R = 1,2104,261,261,261
BEGIN DESCRIPTION:
Lacy 114 1528
END DESCRIPTION:
XS GIS Cut Line= 3
      2729743.50      6866722.62      2730073.74      6867035.60
      2730449.54      6867050.94
#Sta/Elev= 30
  4442.5  414.30  4577.5  411.89  4605.9  410.37  4612.7  411.31  4620.0  410.17
  4641.1  410.16  4648.3  407.91  4655.2  410.13  4667.4  410.03  4705.0  410.12
  4740.2  408.92  4796.8  408.90  4877.4  407.23  4941.1  406.14  4993.1  405.91
  4999.8  406.03  5017.9  399.04  5018.1  398.54  5021.6  398.54  5021.9  399.04
  5029.9  402.70  5039.9  405.05  5049.9  405.86  5099.9  407.37  5140.0  407.65
  5161.8  409.20  5200.0  411.80  5210.0  413.20  5250.0  416.29  5273.6  417.19
#Mann=8,-1,0
  4442.5     0.1       0  4667.4    0.12       0  4877.4     0.1       0
  4941.1    0.12       0  4993.1     0.1       0  5017.9    0.07       0
  5021.9     0.1       0  5161.8    0.12       0
Bank Sta=5017.9,5021.9
Exp/Cntr=0.3,0.1

Type RM Length L Ch R = 1,1843,65,65,65
BEGIN DESCRIPTION:
Lacy 114 1527
END DESCRIPTION:
XS GIS Cut Line= 3
      2729812.15      6867182.33      2730126.57      6867285.79
      2730412.60      6867223.65
#Sta/Elev= 30
  4670.2  414.20  4712.5  412.31  4726.9  410.85  4737.4  410.42  4739.8  410.72
  4744.3  411.29  4807.9  408.86  4843.2  408.10  4871.5  407.51  4908.5  405.63
  4948.0  404.78  4958.5  401.84  4972.1  401.14  4977.5  398.52  4977.8  398.02
  4981.3  398.02  4981.5  398.52  4990.1  403.32  5003.5  402.99  5007.7  402.55
  5010.8  402.23  5021.1  402.64  5041.5  403.92  5113.2  404.47  5151.1  404.37
  5164.3  404.20  5205.3  405.83  5215.5  405.49  5252.9  406.84  5293.9  408.39
#Mann=8,-1,0
  4670.2    0.05       0  4739.8     0.1       0  4843.2    0.12       0
  4977.5    0.07       0  4981.5    0.12       0  5007.7    0.12       0
  5151.1     0.1       0  5252.9    0.12       0
Bank Sta=4977.5,4981.5
Exp/Cntr=0.3,0.1

Type RM Length L Ch R = 1,1778,208,208,208
BEGIN DESCRIPTION:
Lacy 114 1526
END DESCRIPTION:
XS GIS Cut Line= 3
      2729821.89      6867331.93      2730124.16      6867350.72
      2730500.49      6867218.00
#Sta/Elev= 30
  4696.5  410.71  4763.9  409.32  4848.9  406.94  4870.9  405.98  4891.0  405.87
  4911.0  405.02  4951.1  404.27  4955.8  403.46  4971.1  400.82  4981.2  400.03
  4989.2  398.62  4989.4  398.12  4992.9  398.12  4993.2  398.62  4997.8  401.08
  5033.1  402.96  5057.3  403.39  5149.8  404.22  5190.4  403.87  5202.8  405.04
  5213.4  403.41  5215.1  403.84  5221.3  405.41  5226.7  405.70  5234.6  405.10
  5261.9  405.80  5339.8  408.45  5370.7  410.39  5383.0  411.89  5398.4  412.15
#Mann=8,-1,0
  4696.5    0.05       0  4848.9    0.12       0  4955.8     0.1       0
  4989.2    0.07       0  4993.2     0.1       0  5057.3    0.12       0
  5215.1     0.1       0  5261.9    0.12       0
Bank Sta=4989.2,4993.2
Exp/Cntr=0.3,0.1

Type RM Length L Ch R = 1,1570,207,207,207
BEGIN DESCRIPTION:
Lacy 114 1544
END DESCRIPTION:
XS GIS Cut Line= 3
      2729856.95      6867524.98      2730072.78      6867544.29
      2730549.19      6867365.34
#Sta/Elev= 30
  4778.9  405.99  4903.0  402.66  4968.7  402.60  4988.8  400.33  4990.9  398.52
  4992.7  396.97  4992.9  396.47  4996.4  396.47  4996.7  396.97  5000.0  396.97
  5009.7  399.43  5022.5  401.56  5052.7  401.94  5072.3  400.72  5084.5  401.51
  5095.2  400.83  5102.5  401.96  5116.5  402.23  5240.8  402.16  5328.4  401.39
  5340.9  402.43  5351.5  401.77  5358.7  402.97  5417.4  403.46  5437.0  403.33
  5459.5  404.44  5479.7  404.90  5490.4  405.93  5499.2  405.19  5504.5  405.50
#Mann=7,-1,0
  4778.9    0.05       0  4990.9     0.1       0  4992.7    0.07       0
  4996.7     0.1       0  5240.8    0.12       0  5417.4     0.1       0
  5459.5    0.12       0
Bank Sta=4992.7,4996.7
Exp/Cntr=0.3,0.1

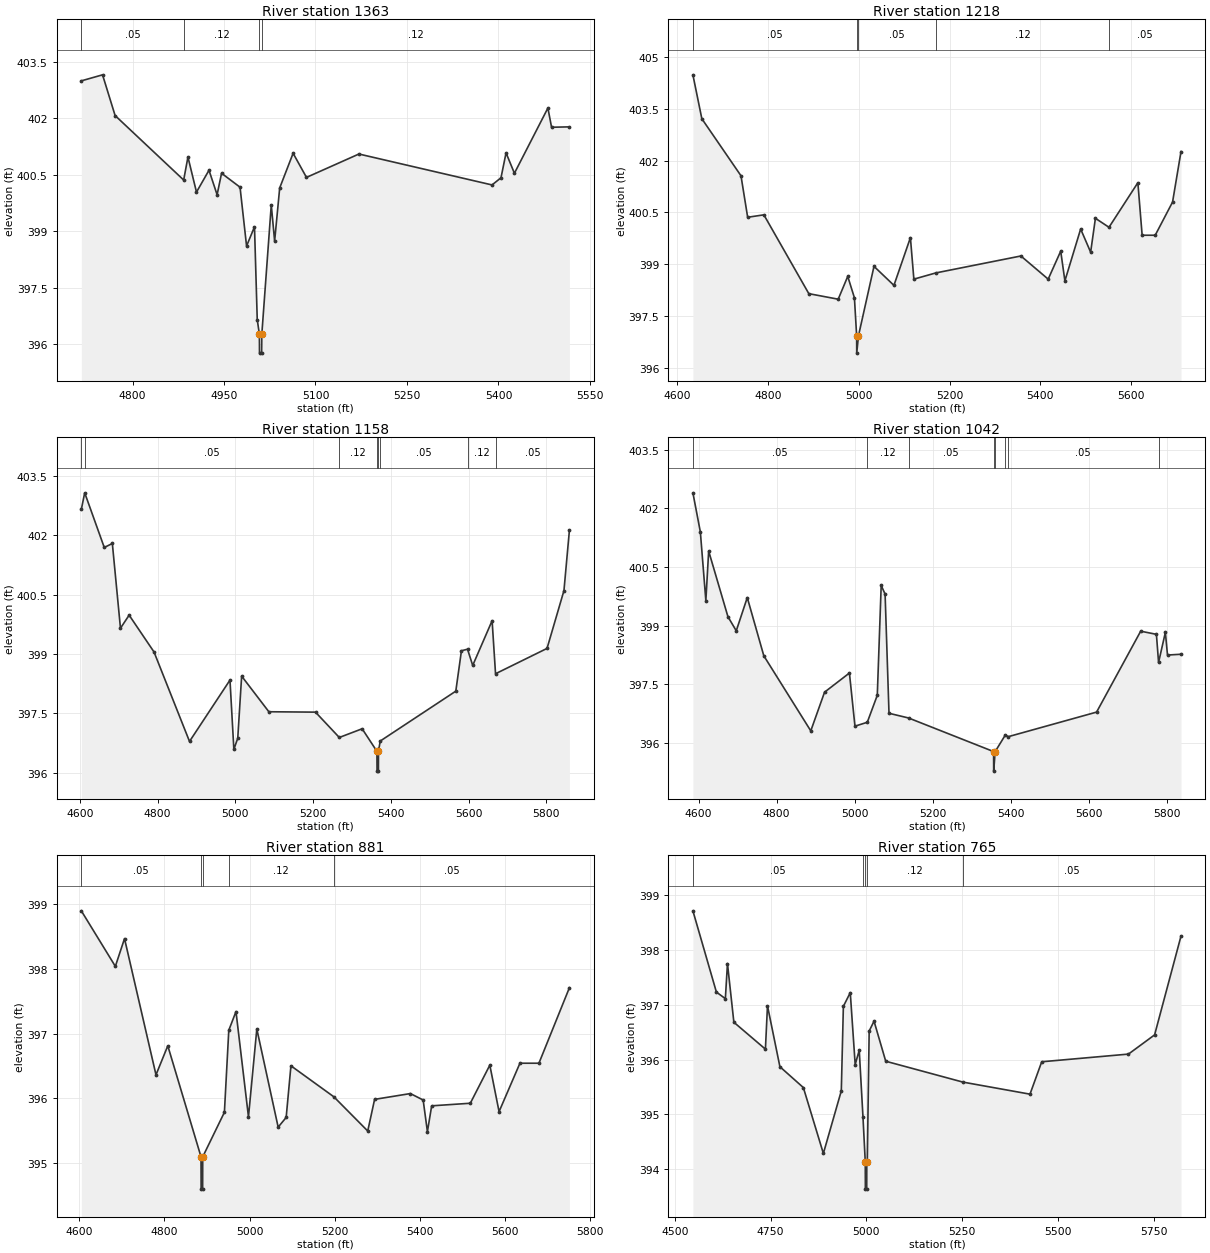
Type RM Length L Ch R = 1,1363,145,145,145
BEGIN DESCRIPTION:
Lacy 114 1545
END DESCRIPTION:
XS GIS Cut Line= 3
      2729802.08      6867656.16      2730076.00      6867719.71
      2730548.07      6867504.03
#Sta/Elev= 30
  4716.1  402.99  4750.9  403.15  4771.5  402.07  4883.9  400.36  4890.9  400.97
  4904.9  400.04  4925.4  400.62  4938.7  399.97  4946.0  400.54  4976.3  400.17
  4987.0  398.61  5000.0  399.12  5004.5  396.66  5008.0  396.27  5008.2  395.77
  5011.7  395.77  5012.0  396.27  5027.5  399.70  5033.0  398.74  5041.3  400.15
  5063.3  401.07  5085.2  400.43  5171.2  401.05  5389.4  400.23  5404.1  400.42
  5412.4  401.08  5426.1  400.54  5481.0  402.27  5487.0  401.76  5516.3  401.77
#Mann=4,-1,0
  4716.1    0.05       0  4883.9    0.12       0  5008.0    0.07       0
  5012.0    0.12       0
Bank Sta=5008,5012
Exp/Cntr=0.3,0.1

Type RM Length L Ch R = 1,1218,60,60,60
BEGIN DESCRIPTION:
Lacy 114 1546
END DESCRIPTION:
XS GIS Cut Line= 3
      2729777.52      6867652.79      2730076.19      6867863.93
      2730701.45      6867529.37
#Sta/Elev= 30
  4634.9  404.48  4654.6  403.21  4740.8  401.56  4755.5  400.36  4791.2  400.43
  4890.2  398.15  4954.9  397.99  4975.9  398.65  4990.6  398.03  4995.5  396.93
  4995.7  396.43  4999.5  396.93  5033.7  398.94  5077.6  398.39  5113.9  399.77
  5121.5  398.57  5169.9  398.75  5357.2  399.24  5417.3  398.57  5444.9  399.38
  5454.1  398.52  5488.8  400.02  5510.8  399.35  5521.3  400.33  5551.2  400.07
  5614.8  401.36  5624.2  399.84  5653.0  399.84  5691.2  400.80  5709.8  402.26
#Mann=5,-1,0
  4634.9    0.05       0  4995.5    0.04       0  4999.5    0.05       0
  5169.9    0.12       0  5551.2    0.05       0
Bank Sta=4995.5,4999.5
Exp/Cntr=0.3,0.1

Type RM Length L Ch R = 1,1158,116,116,116
BEGIN DESCRIPTION:
Lacy 114 1548
END DESCRIPTION:
XS GIS Cut Line= 4
      2729749.74      6867705.19      2730018.47      6867921.25
      2730442.99      6867930.04      2730739.70      6867544.91
#Sta/Elev= 30
  4603.7  402.65  4612.4  403.07  4662.7  401.69  4683.5  401.79  4704.4  399.65
  4726.7  399.98  4790.7  399.05  4882.0  396.79  4986.1  398.34  4996.1  396.59
  5006.1  396.87  5016.1  398.44  5086.1  397.54  5206.1  397.53  5267.3  396.89
  5326.1  397.11  5364.1  396.54  5364.4  396.04  5367.9  396.04  5368.1  396.54
  5372.6  396.80  5567.0  398.06  5581.5  399.08  5597.1  399.12  5610.5  398.71
  5660.4  399.84  5669.2  398.50  5801.7  399.14  5845.2  400.60  5859.3  402.13
#Mann=8,-1,0
  4603.7    0.12       0  4612.4    0.05       0  5267.3    0.12       0
  5364.1    0.04       0  5368.1    0.12       0  5372.6    0.05       0
  5597.1    0.12       0  5669.2    0.05       0
Bank Sta=5364.1,5368.1
Exp/Cntr=0.3,0.1

Type RM Length L Ch R = 1,1042,161,161,161
BEGIN DESCRIPTION:
Lacy 114 3449
END DESCRIPTION:
XS GIS Cut Line= 4
      2729736.54      6867743.42      2730070.16      6868069.53
      2730476.86      6868067.04      2730635.61      6867724.80
#Sta/Elev= 30
  4585.5  402.40  4604.6  401.40  4618.7  399.64  4625.9  400.91  4675.3  399.23
  4696.6  398.87  4724.8  399.72  4767.2  398.23  4887.5  396.31  4922.8  397.30
  4986.5  397.79  5000.7  396.43  5032.3  396.53  5057.9  397.22  5067.9  400.03
  5077.9  399.81  5087.9  396.76  5137.9  396.64  5355.9  395.78  5356.1  395.28
  5359.9  395.78  5386.3  396.21  5392.9  396.16  5619.7  396.79  5732.7  398.86
  5773.0  398.78  5778.5  398.06  5795.9  398.83  5801.4  398.25  5836.0  398.27
#Mann=8,-1,0
  4585.5    0.05       0  5032.3    0.12       0  5137.9    0.05       0
  5355.9    0.03       0  5359.9    0.05       0  5386.3    0.12       0
  5392.9    0.05       0  5778.5    0.12       0
Bank Sta=5355.9,5359.9
Exp/Cntr=0.3,0.1

Type RM Length L Ch R = 1,881,116,116,116
BEGIN DESCRIPTION:
Lacy 114 3460
END DESCRIPTION:
XS GIS Cut Line= 4
      2729768.89      6867839.85      2729968.87      6868180.37
      2730445.10      6868157.12      2730580.61      6867918.74
#Sta/Elev= 30
  4605.1  398.90  4685.0  398.04  4706.5  398.47  4780.4  396.36  4808.1  396.81
  4886.1  395.09  4886.4  394.59  4889.9  394.59  4890.1  395.09  4941.0  395.78
  4951.3  397.05  4968.2  397.34  4997.5  395.71  5017.1  397.07  5067.2  395.55
  5086.0  395.70  5097.2  396.50  5197.9  396.02  5277.5  395.49  5293.6  395.98
  5377.6  396.07  5407.6  395.97  5417.6  395.48  5427.6  395.88  5518.3  395.92
  5564.1  396.51  5585.8  395.79  5634.8  396.54  5679.4  396.54  5751.0  397.71
#Mann=5,-1,0
  4605.1    0.05       0  4886.1    0.07       0  4890.1    0.05       0
  4951.3    0.12       0  5197.9    0.05       0
Bank Sta=4886.1,4890.1
Exp/Cntr=0.3,0.1

Type RM Length L Ch R = 1,765,109,109,109
BEGIN DESCRIPTION:
Lacy 114 3461
END DESCRIPTION:
XS GIS Cut Line= 4
      2729745.01      6867873.07      2729926.49      6868287.80
      2730455.37      6868188.54      2730591.63      6867940.86
#Sta/Elev= 30
  4547.3  398.71  4608.6  397.23  4632.0  397.11  4637.5  397.75  4654.2  396.68
  4736.5  396.19  4741.9  396.98  4774.3  395.87  4835.5  395.49  4887.7  394.29
  4934.5  395.43  4939.9  396.97  4957.9  397.22  4970.7  395.91  4981.3  396.17
  4991.0  394.96  4997.0  394.14  4997.3  393.64  5000.8  393.64  5001.0  394.14
  5002.3  394.14  5007.2  396.52  5019.9  396.70  5050.4  395.97  5251.6  395.59
  5426.8  395.37  5457.4  395.96  5683.7  396.10  5751.9  396.45  5820.8  398.25
#Mann=5,-1,0
  4547.3    0.05       0  4991.0    0.12       0  4997.0    0.07       0
  5001.0    0.12       0  5251.6    0.05       0
Bank Sta=4997,5001
Exp/Cntr=0.3,0.1

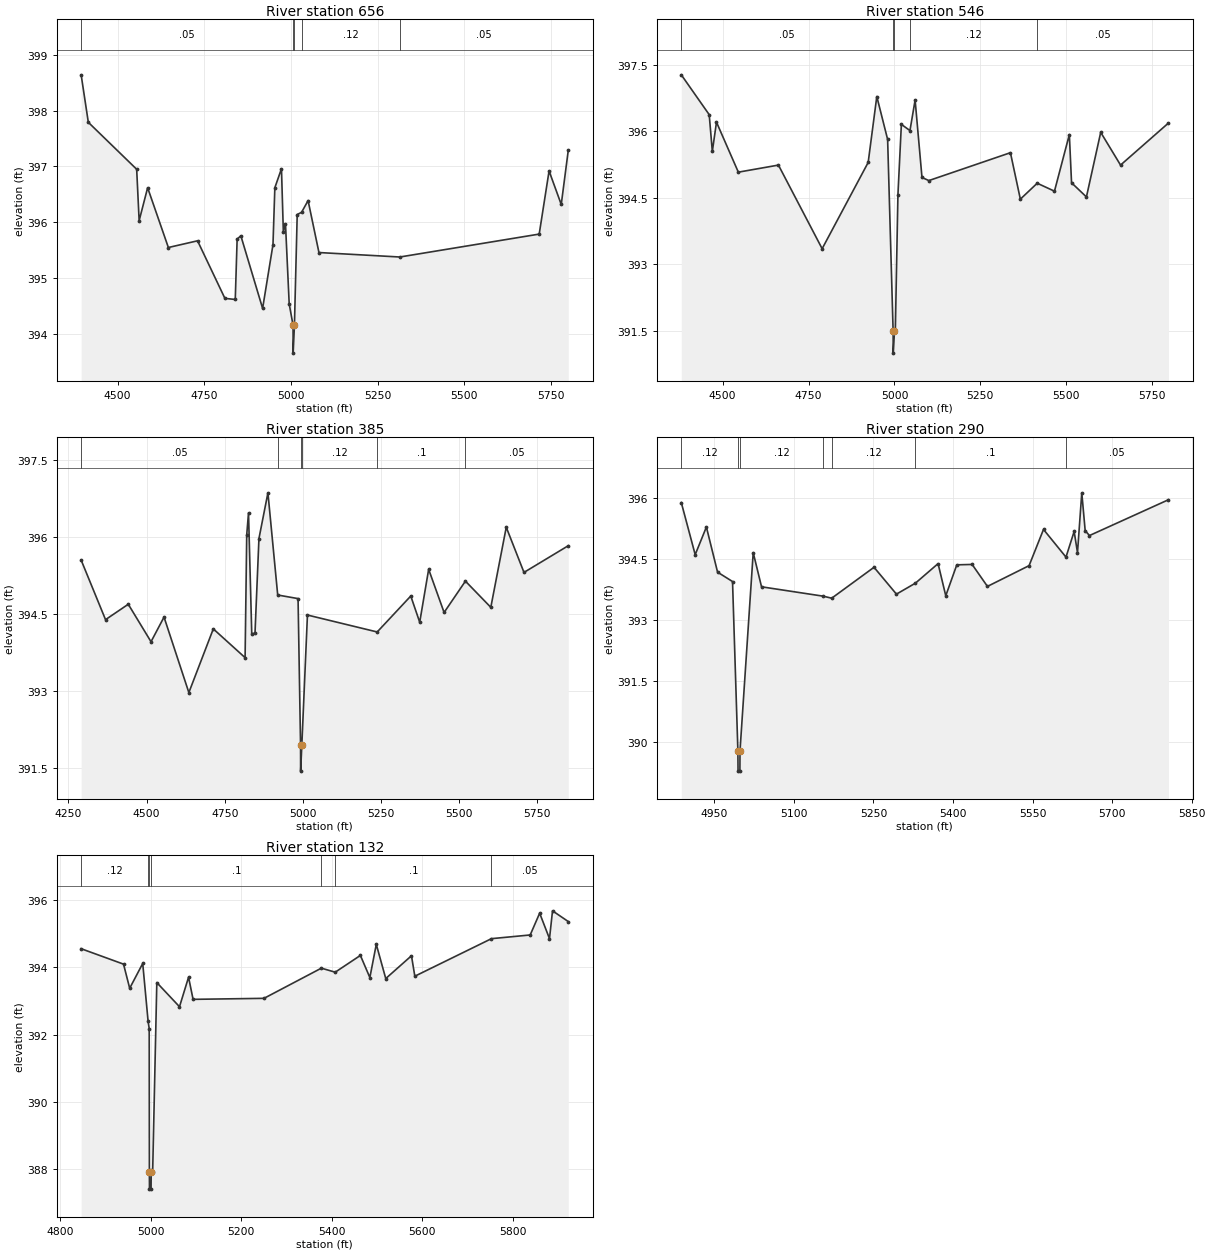
Type RM Length L Ch R = 1,656,110,110,110
BEGIN DESCRIPTION:
Lacy 114 3463
END DESCRIPTION:
XS GIS Cut Line= 4
      2729659.71      6867821.67      2729879.63      6868386.64
      2730495.74      6868202.84      2730598.15      6868085.04
#Sta/Elev= 30
  4394.7  398.64  4415.4  397.79  4554.9  396.95  4562.0  396.03  4586.5  396.62
  4646.3  395.55  4730.5  395.67  4809.4  394.64  4839.3  394.62  4844.7  395.70
  4855.4  395.76  4918.2  394.46  4948.1  395.60  4953.5  396.62  4972.6  396.96
  4978.0  395.83  4984.2  395.97  4994.9  394.54  5006.0  394.16  5006.3  393.66
  5010.0  394.16  5018.0  396.14  5030.6  396.18  5049.4  396.39  5080.7  395.46
  5314.0  395.38  5716.1  395.79  5744.6  396.92  5779.7  396.32  5800.0  397.29
#Mann=5,-1,0
  4394.7    0.05       0  5006.0    0.04       0  5010.0    0.05       0
  5030.6    0.12       0  5314.0    0.05       0
Bank Sta=5006,5010
Exp/Cntr=0.3,0.1

Type RM Length L Ch R = 1,546,161,161,161
BEGIN DESCRIPTION:
Lacy 114 3465
END DESCRIPTION:
XS GIS Cut Line= 4
      2729639.69      6867904.40      2729845.94      6868489.51
      2730175.00      6868501.45      2730541.99      6868210.83
#Sta/Elev= 30
  4379.6  397.28  4460.8  396.38  4469.9  395.55  4482.0  396.21  4545.6  395.08
  4662.3  395.24  4789.5  393.35  4923.5  395.30  4948.6  396.79  4980.1  395.82
  4996.1  391.49  4996.4  390.99  5000.1  391.49  5002.5  391.49  5010.1  394.57
  5020.1  396.16  5045.1  396.02  5060.1  396.71  5080.1  394.96  5100.1  394.89
  5337.5  395.52  5366.4  394.47  5415.5  394.83  5465.7  394.65  5509.0  395.93
  5515.4  394.84  5558.7  394.52  5600.3  395.98  5658.0  395.24  5797.4  396.19
#Mann=5,-1,0
  4379.6    0.05       0  4996.1    0.04       0  5000.1    0.05       0
  5045.1    0.12       0  5415.5    0.05       0
Bank Sta=4996.1,5000.1
Exp/Cntr=0.3,0.1

Type RM Length L Ch R = 1,385,95,95,95
BEGIN DESCRIPTION:
Lacy 114 3466
END DESCRIPTION:
XS GIS Cut Line= 4
      2729606.56      6868006.00      2729788.48      6868646.93
      2730064.55      6868657.31      2730534.08      6868259.21
#Sta/Elev= 30
  4290.7  395.55  4368.7  394.39  4441.4  394.69  4514.2  393.96  4555.8  394.44
  4635.2  392.97  4713.4  394.21  4815.1  393.65  4820.3  396.04  4826.0  396.47
  4836.4  394.11  4846.8  394.13  4859.4  395.97  4888.1  396.86  4919.4  394.87
  4984.5  394.80  4992.5  391.94  4992.7  391.44  4996.5  391.94  5014.5  394.48
  5237.6  394.15  5345.0  394.85  5373.6  394.34  5402.2  395.37  5451.6  394.53
  5519.8  395.14  5601.0  394.63  5650.4  396.19  5707.1  395.31  5848.8  395.83
#Mann=6,-1,0
  4290.7    0.05       0  4919.4    0.12       0  4992.5    0.07       0
  4996.5    0.12       0  5237.6     0.1       0  5519.8    0.05       0
Bank Sta=4992.5,4996.5
Exp/Cntr=0.3,0.1

Type RM Length L Ch R = 1,290,158,158,158
BEGIN DESCRIPTION:
Lacy 114 3469
END DESCRIPTION:
XS GIS Cut Line= 4
      2729736.31      6868663.86      2729818.01      6868741.05
      2729975.89      6868776.02      2730481.96      6868376.94
#Sta/Elev= 30
  4887.6  395.89  4913.8  394.61  4934.9  395.29  4956.0  394.18  4984.2  393.95
  4994.3  389.79  4994.6  389.29  4998.1  389.29  4998.3  389.79  5023.2  394.66
  5038.9  393.82  5155.2  393.59  5171.2  393.54  5251.0  394.30  5293.3  393.64
  5329.1  393.91  5371.8  394.39  5386.3  393.60  5407.1  394.36  5436.0  394.37
  5464.9  393.83  5543.4  394.34  5570.6  395.23  5613.0  394.55  5628.4  395.18
  5634.7  394.66  5642.8  396.13  5649.2  395.20  5657.3  395.08  5806.2  395.96
#Mann=7,-1,0
  4887.6    0.12       0  4994.3    0.07       0  4998.3    0.12       0
  5155.2     0.1       0  5171.2    0.12       0  5329.1     0.1       0
  5613.0    0.05       0
Bank Sta=4994.3,4998.3
Exp/Cntr=0.3,0.1

Type RM Length L Ch R = 1,132,0,0,0
BEGIN DESCRIPTION:
Lacy 114 3470
END DESCRIPTION:
XS GIS Cut Line= 4
      2729693.45      6868801.84      2729812.47      6868898.94
      2730006.21      6868891.03      2730545.04      6868401.06
#Sta/Elev= 30
  4846.4  394.56  4940.0  394.10  4953.6  393.38  4982.4  394.12  4994.3  392.39
  4996.7  392.18  4997.1  387.89  4997.3  387.39  5000.8  387.39  5001.1  387.89
  5004.3  387.89  5013.5  393.55  5063.6  392.83  5083.6  393.71  5093.6  393.05
  5250.2  393.08  5376.9  393.98  5407.5  393.86  5463.1  394.36  5484.0  393.70
  5498.2  394.69  5519.1  393.67  5575.9  394.35  5583.3  393.74  5752.6  394.86
  5838.1  394.97  5859.0  395.62  5880.7  394.86  5887.4  395.69  5922.2  395.37
#Mann=7,-1,0
  4846.4    0.12       0  4994.3     0.1       0  4997.1    0.07       0
  5001.1     0.1       0  5376.9    0.12       0  5407.5     0.1       0
  5752.6    0.05       0
Bank Sta=4997.1,5001.1
Exp/Cntr=0.3,0.1

Chan Stop Cuts=-1