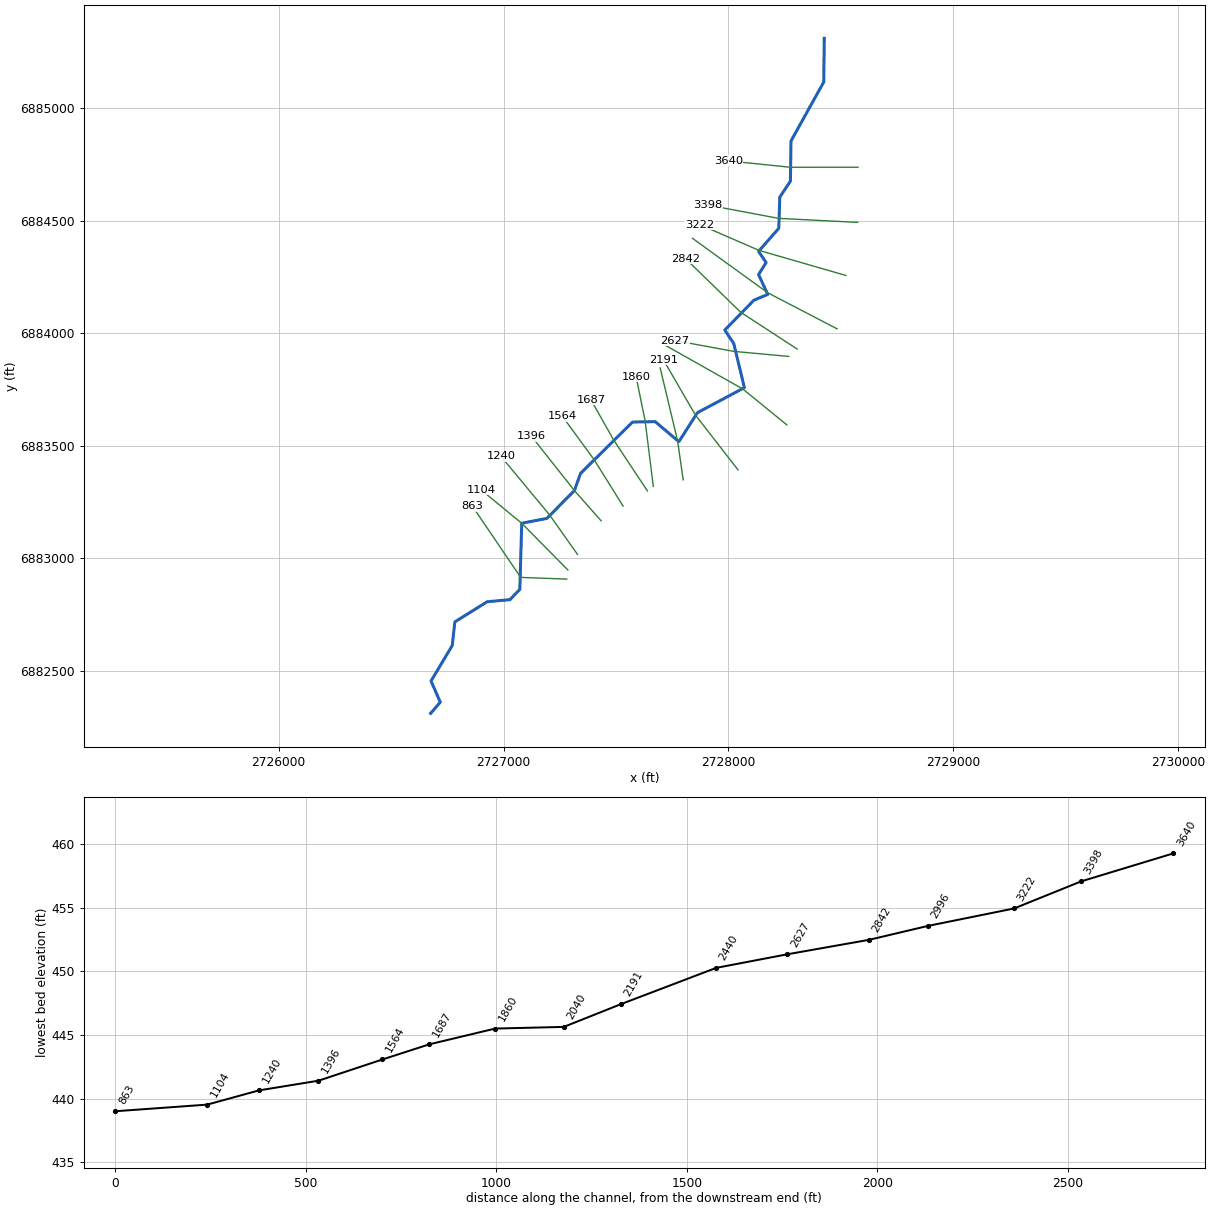
--- Lacy 116.prj (project) ---

Proj Title=Lacy 116 Base Level Engineering
Current Plan=p01
Default Exp/Contr=0.3,0.1
English Units
Geom File=g01
Flow File=f01
Plan File=p01
BEGIN DESCRIPTION:
Lacy 116
END DESCRIPTION:

--- Lacy 116.p01 (plan) ---

Plan Title=Multiple Run
Short Identifier=Multiple
Geom File=g01
Flow File=f01
Subcritical Flow
K Sum by GR= 0
Std Step Tol= 0.01
Critical Tol= 0.01
Num of Std Step Trials= 20
Max Error Tol= 0.3
Flow Tol Ratio= 0.001
Split Flow NTrial= 30
Split Flow Tol= 0.02
Split Flow Ratio= 0.02
Log Output Level= 0
Friction Slope Method= 1
Unsteady Friction Slope Method= 2
Unsteady Bridges Friction Slope Method= 1
Parabolic Critical Depth
Global Vel Dist=  1 , 1 , 1
Global Log Level= 0
CheckData=True
Encroach Param= -1, 0, 0, 0
BEGIN DESCRIPTION:
Multiple Run
END DESCRIPTION:

--- Lacy 116.f01 (steady flow) ---

Flow Title=Multiple
Number of Profiles=7
Profile Names=10-year,25-year,50-year,1pct_min,100-year,1pct_plu,500-year
River Rch & RM= Lacy 116,Reach-1,3640
     232     290     333     191     381     760     495
Boundary for River Rch & Prof#=Lacy 116,Reach-1,1
Up Type=0
Dn Type=3
Dn Slope=0.005
Boundary for River Rch & Prof#=Lacy 116,Reach-1,2
Up Type=0
Dn Type=3
Dn Slope=0.005
Boundary for River Rch & Prof#=Lacy 116,Reach-1,3
Up Type=0
Dn Type=3
Dn Slope=0.005
Boundary for River Rch & Prof#=Lacy 116,Reach-1,4
Up Type=0
Dn Type=3
Dn Slope=0.005
Boundary for River Rch & Prof#=Lacy 116,Reach-1,5
Up Type=0
Dn Type=3
Dn Slope=0.005
Boundary for River Rch & Prof#=Lacy 116,Reach-1,6
Up Type=0
Dn Type=3
Dn Slope=0.005
Boundary for River Rch & Prof#=Lacy 116,Reach-1,7
Up Type=0
Dn Type=3
Dn Slope=0.005

--- Lacy 116.g01 (geometry) ---

Geom Title=Existing Conditions

River Reach=Lacy 116,Reach-1
Reach XY= 30
      2728426.00      6885311.00      2728423.77      6885116.92
      2728278.24      6884855.07      2728275.48      6884676.22
      2728228.27      6884605.06      2728223.92      6884466.86
      2728134.00      6884364.33      2728167.44      6884314.34
      2728133.83      6884261.06      2728174.78      6884173.03
      2728113.08      6884147.27      2727983.79      6884014.42
      2728023.44      6883955.11      2728071.01      6883758.45
      2727862.43      6883647.52      2727779.58      6883518.49
      2727674.50      6883607.52      2727573.57      6883605.60
      2727342.65      6883377.67      2727315.22      6883301.32
      2727192.73      6883177.47      2727081.03      6883155.92
      2727072.56      6882862.22      2727028.71      6882816.40
      2726927.59      6882807.17      2726783.74      6882717.46
      2726772.17      6882612.59      2726677.82      6882454.88
      2726719.05      6882360.88      2726676.00      6882311.00

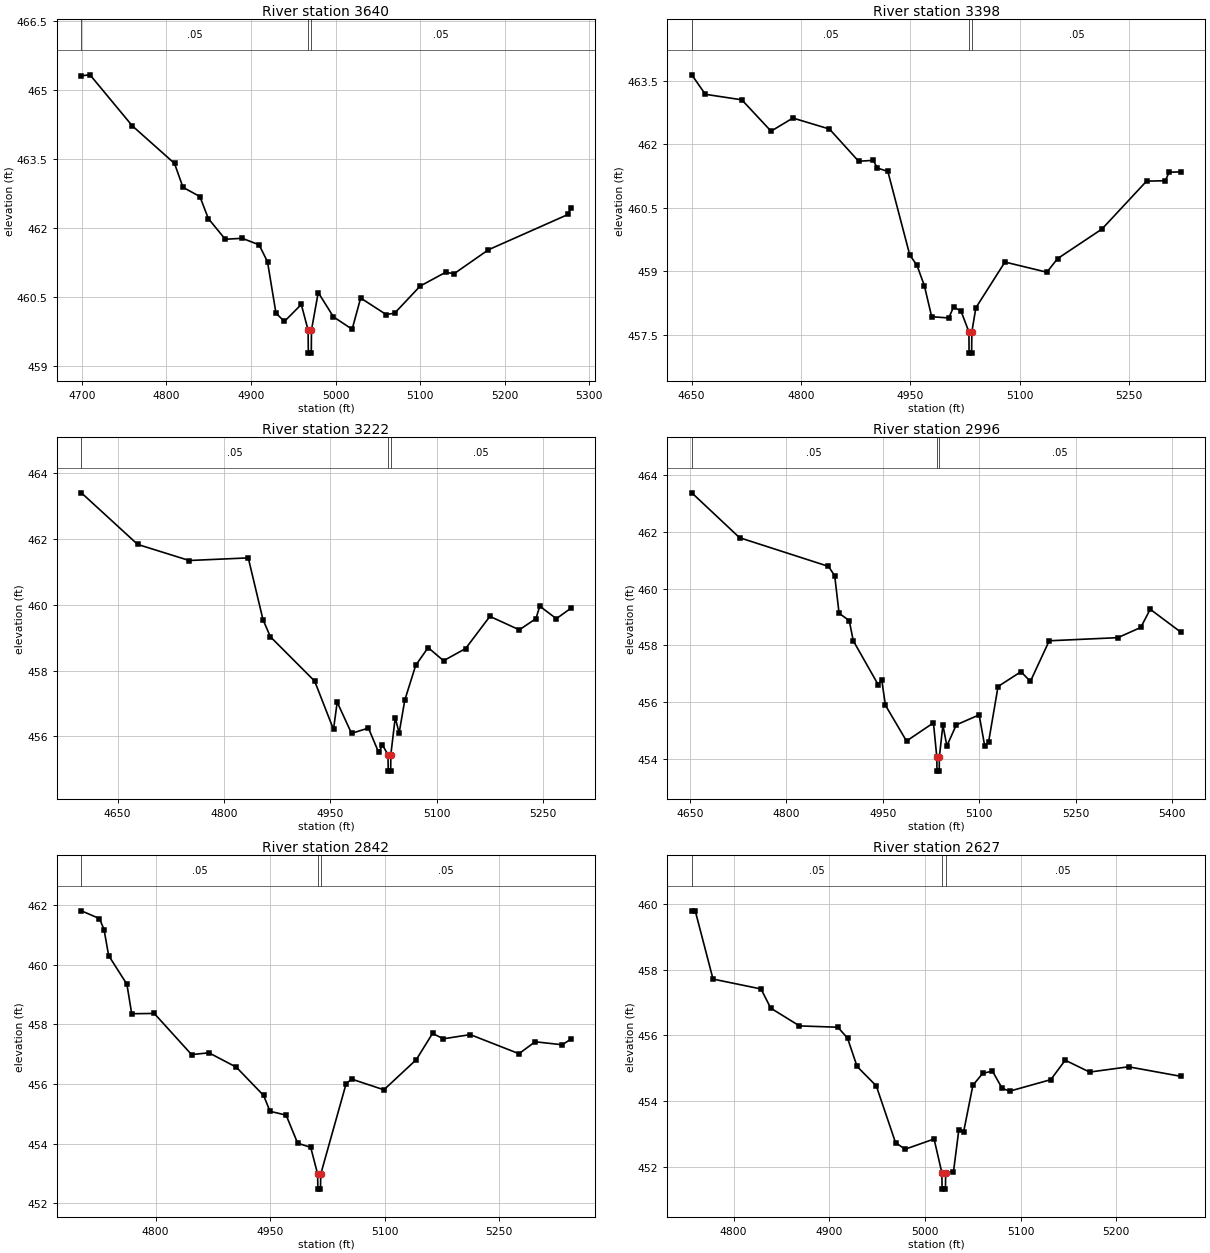
Type RM Length L Ch R = 1,3640,242,242,242
BEGIN DESCRIPTION:
Lacy 116 1495
END DESCRIPTION:
XS GIS Cut Line= 3
      2728576.24      6884738.16      2728275.08      6884738.09
      2727998.99      6884766.39
#Sta/Elev= 30
  4699.3  465.31  4709.5  465.33  4759.5  464.22  4809.5  463.40  4819.5  462.88
  4839.5  462.68  4849.5  462.20  4869.5  461.75  4889.5  461.77  4909.5  461.63
  4919.5  461.26  4929.5  460.14  4939.5  459.96  4959.5  460.33  4967.5  459.77
  4967.8  459.27  4971.3  459.27  4971.5  459.77  4979.5  460.59  4997.5  460.06
  5019.6  459.79  5029.7  460.47  5059.9  460.11  5069.9  460.14  5100.1  460.73
  5130.2  461.03  5140.3  461.00  5180.8  461.52  5275.1  462.29  5278.0  462.42
#Mann=3,-1,0
  4699.3    0.05       0  4967.5    0.04       0  4971.5    0.05       0
Bank Sta=4967.5,4971.5
Exp/Cntr=0.3,0.1

Type RM Length L Ch R = 1,3398,176,176,176
BEGIN DESCRIPTION:
Lacy 116 1498
END DESCRIPTION:
XS GIS Cut Line= 3
      2728574.55      6884492.98      2728222.56      6884510.98
      2727909.60      6884569.87
#Sta/Elev= 30
  4650.3  463.64  4668.9  463.18  4718.9  463.05  4759.0  462.31  4789.0  462.62
  4839.1  462.36  4879.1  461.60  4899.2  461.62  4904.7  461.44  4919.2  461.36
  4949.2  459.39  4959.2  459.14  4969.3  458.66  4979.3  457.93  5002.7  457.90
  5009.4  458.16  5019.6  458.06  5030.4  457.57  5030.6  457.07  5034.1  457.07
  5034.4  457.57  5039.9  458.14  5079.8  459.22  5137.3  458.98  5151.9  459.30
  5212.9  460.00  5274.0  461.13  5299.8  461.14  5304.9  461.34  5321.2  461.35
#Mann=3,-1,0
  4650.3    0.05       0  5030.4    0.04       0  5034.4    0.05       0
Bank Sta=5030.4,5034.4
Exp/Cntr=0.3,0.1

Type RM Length L Ch R = 1,3222,226,226,226
BEGIN DESCRIPTION:
Lacy 116 1497
END DESCRIPTION:
XS GIS Cut Line= 3
      2728522.26      6884257.11      2728135.41      6884368.85
      2727871.61      6884483.50
#Sta/Elev= 30
  4598.8  463.41  4678.2  461.84  4751.0  461.35  4834.3  461.43  4855.1  459.55
  4865.5  459.03  4928.0  457.68  4954.6  456.21  4959.8  457.04  4980.0  456.09
  5003.9  456.25  5018.3  455.51  5023.7  455.73  5031.5  455.44  5031.8  454.94
  5035.3  454.94  5035.5  455.44  5041.7  456.57  5047.2  456.10  5055.3  457.11
  5070.6  458.16  5088.1  458.70  5109.9  458.30  5141.0  458.67  5175.3  459.65
  5216.8  459.24  5240.2  459.58  5245.7  459.96  5269.1  459.58  5289.1  459.89
#Mann=3,-1,0
  4598.8    0.05       0  5031.5    0.04       0  5035.5    0.05       0
Bank Sta=5031.5,5035.5
Exp/Cntr=0.3,0.1

Type RM Length L Ch R = 1,2996,154,154,154
BEGIN DESCRIPTION:
Lacy 116 1496
END DESCRIPTION:
XS GIS Cut Line= 3
      2728483.27      6884019.83      2728173.95      6884180.65
      2727840.01      6884422.41
#Sta/Elev= 30
  4653.0  463.37  4727.3  461.79  4865.6  460.78  4875.3  460.45  4882.1  459.13
  4897.9  458.87  4904.2  458.16  4942.8  456.62  4948.4  456.79  4954.2  455.89
  4987.0  454.63  5028.9  455.27  5034.1  454.07  5034.4  453.57  5037.9  453.57
  5038.1  454.07  5043.6  455.19  5049.8  454.46  5064.5  455.20  5100.0  455.55
  5108.6  454.46  5114.7  454.60  5129.4  456.55  5165.0  457.07  5179.7  456.73
  5209.0  458.16  5315.8  458.27  5351.4  458.63  5366.1  459.27  5413.9  458.46
#Mann=3,-1,0
  4653.0    0.05       0  5034.1    0.04       0  5038.1    0.05       0
Bank Sta=5034.1,5038.1
Exp/Cntr=0.3,0.1

Type RM Length L Ch R = 1,2842,215,215,215
BEGIN DESCRIPTION:
Lacy 116 1494
END DESCRIPTION:
XS GIS Cut Line= 3
      2728305.93      6883929.84      2728054.35      6884093.79
      2727810.44      6884330.97
#Sta/Elev= 30
  4702.9  461.81  4726.6  461.55  4732.6  461.18  4738.6  460.31  4762.5  459.35
  4768.8  458.36  4798.3  458.37  4847.2  456.99  4869.9  457.05  4905.7  456.57
  4941.5  455.62  4949.9  455.09  4971.0  454.96  4986.1  454.02  5003.2  453.88
  5012.3  452.98  5012.5  452.48  5016.0  452.48  5016.3  452.98  5049.5  456.01
  5056.7  456.17  5099.0  455.81  5141.4  456.82  5162.7  457.70  5176.9  457.52
  5212.1  457.66  5275.9  457.02  5297.0  457.42  5332.5  457.32  5343.4  457.50
#Mann=3,-1,0
  4702.9    0.05       0  5012.3    0.04       0  5016.3    0.05       0
Bank Sta=5012.3,5016.3
Exp/Cntr=0.3,0.1

Type RM Length L Ch R = 1,2627,187,187,187
BEGIN DESCRIPTION:
Lacy 116 1492
END DESCRIPTION:
XS GIS Cut Line= 3
      2728268.11      6883897.44      2728024.31      6883919.74
      2727762.11      6883967.87
#Sta/Elev= 30
  4756.3  459.78  4759.9  459.78  4778.5  457.71  4828.7  457.41  4838.8  456.83
  4868.9  456.29  4909.0  456.25  4919.1  455.92  4929.1  455.06  4949.2  454.47
  4969.3  452.75  4979.3  452.55  5009.6  452.86  5017.7  451.84  5018.0  451.34
  5021.5  451.34  5021.7  451.84  5029.9  451.87  5035.4  453.12  5040.5  453.08
  5050.2  454.49  5060.4  454.85  5070.6  454.92  5080.7  454.40  5088.5  454.31
  5131.6  454.66  5146.7  455.25  5172.2  454.89  5212.9  455.05  5267.7  454.76
#Mann=3,-1,0
  4756.3    0.05       0  5017.7    0.04       0  5021.7    0.05       0
Bank Sta=5017.7,5021.7
Exp/Cntr=0.3,0.1

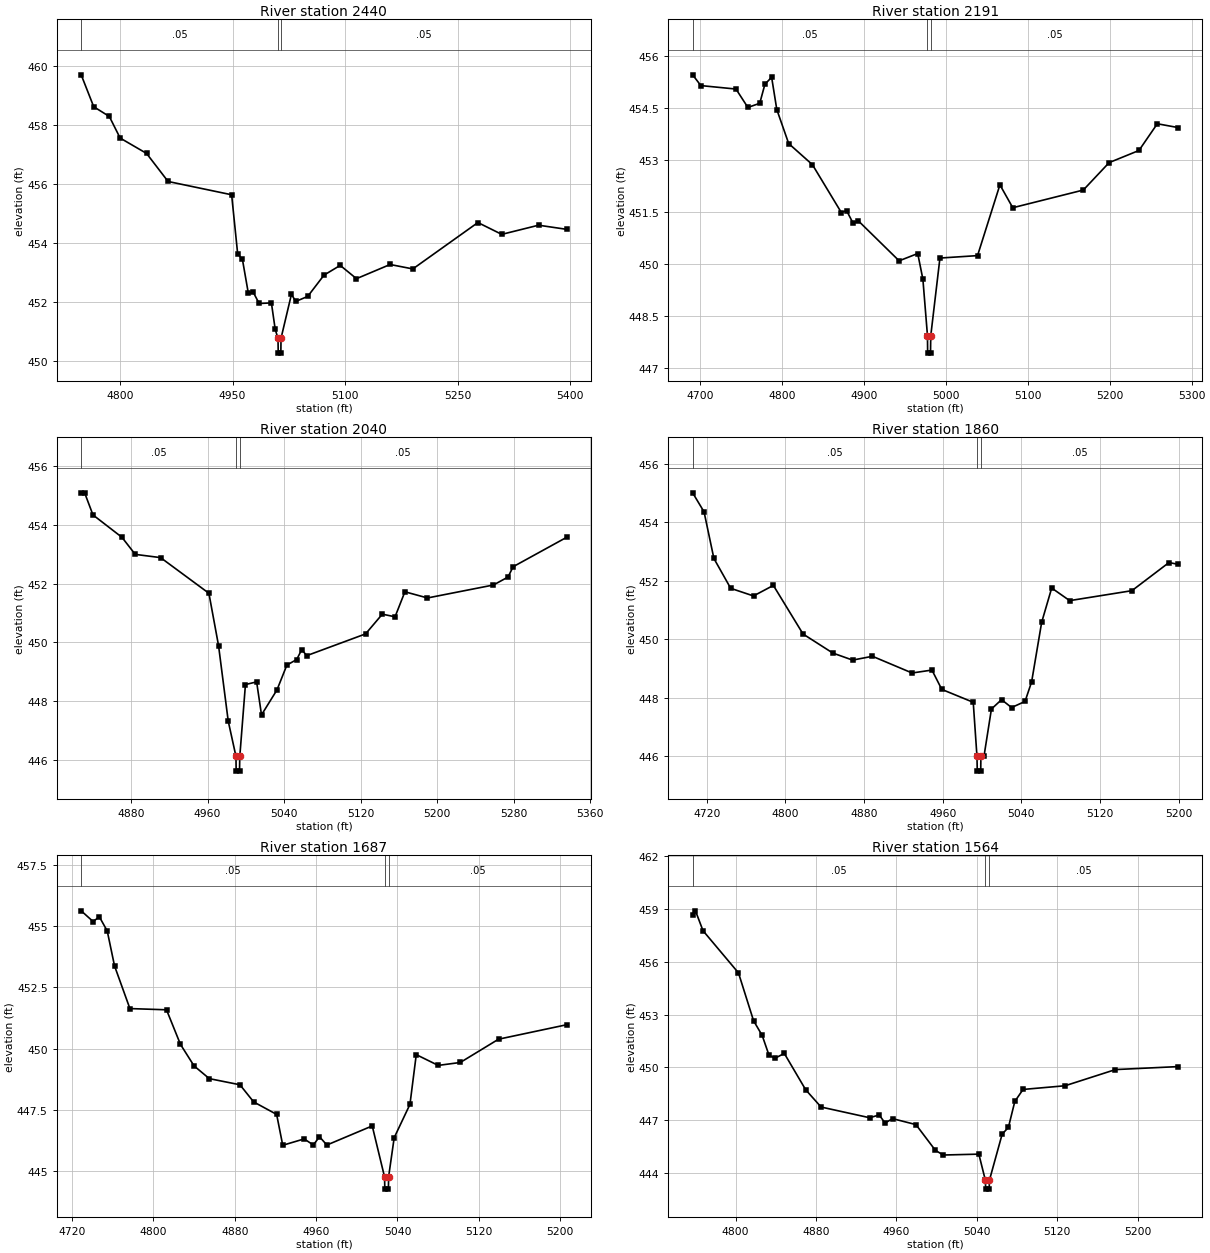
Type RM Length L Ch R = 1,2440,249,249,249
BEGIN DESCRIPTION:
Lacy 116 1493
END DESCRIPTION:
XS GIS Cut Line= 3
      2728260.43      6883592.59      2728063.84      6883752.57
      2727721.06      6883945.91
#Sta/Elev= 30
  4748.2  459.69  4764.9  458.61  4785.7  458.28  4800.1  457.55  4835.3  457.03
  4864.0  456.08  4948.7  455.63  4956.7  453.64  4963.1  453.44  4971.0  452.29
  4977.5  452.33  4985.4  451.95  5001.7  451.97  5006.8  451.07  5010.5  450.77
  5010.8  450.27  5014.3  450.27  5014.5  450.77  5028.4  452.26  5034.2  452.02
  5050.1  452.19  5071.8  452.91  5093.4  453.24  5115.1  452.79  5159.9  453.27
  5190.2  453.12  5276.9  454.69  5308.7  454.29  5357.8  454.60  5395.2  454.46
#Mann=3,-1,0
  4748.2    0.05       0  5010.5    0.04       0  5014.5    0.05       0
Bank Sta=5010.5,5014.5
Exp/Cntr=0.3,0.1

Type RM Length L Ch R = 1,2191,151,151,151
BEGIN DESCRIPTION:
Lacy 116 1491
END DESCRIPTION:
XS GIS Cut Line= 3
      2728042.62      6883393.09      2727852.93      6883637.31
      2727710.84      6883882.37
#Sta/Elev= 30
  4691.0  455.45  4701.0  455.14  4743.9  455.04  4758.4  454.51  4772.9  454.63
  4779.2  455.18  4787.4  455.38  4793.7  454.45  4808.2  453.47  4837.2  452.86
  4872.5  451.48  4878.8  451.54  4886.9  451.17  4893.3  451.24  4943.0  450.09
  4965.7  450.30  4972.0  449.56  4977.6  447.93  4977.8  447.43  4981.3  447.43
  4981.6  447.93  4992.8  450.17  5038.7  450.24  5066.0  452.28  5081.7  451.62
  5167.8  452.13  5199.3  452.92  5235.7  453.27  5258.1  454.04  5283.5  453.93
#Mann=3,-1,0
  4691.0    0.05       0  4977.6    0.04       0  4981.6    0.05       0
Bank Sta=4977.6,4981.6
Exp/Cntr=0.3,0.1

Type RM Length L Ch R = 1,2040,180,180,180
BEGIN DESCRIPTION:
Lacy 116 1490
END DESCRIPTION:
XS GIS Cut Line= 3
      2727798.87      6883348.87      2727774.05      6883521.64
      2727696.74      6883845.50
#Sta/Elev= 30
  4827.9  455.08  4831.5  455.08  4840.2  454.33  4870.5  453.57  4884.4  452.99
  4910.9  452.88  4961.4  451.67  4971.5  449.89  4981.6  447.33  4989.7  446.13
  4989.9  445.63  4993.4  445.63  4993.7  446.13  4999.6  448.57  5011.3  448.66
  5016.4  447.54  5032.6  448.39  5042.9  449.23  5053.2  449.42  5058.5  449.76
  5063.6  449.55  5125.2  450.29  5142.7  450.96  5156.0  450.87  5166.3  451.72
  5189.9  451.51  5258.8  451.95  5274.1  452.22  5279.4  452.57  5335.4  453.57
#Mann=3,-1,0
  4827.9    0.05       0  4989.7    0.04       0  4993.7    0.05       0
Bank Sta=4989.7,4993.7
Exp/Cntr=0.3,0.1

Type RM Length L Ch R = 1,1860,173,173,173
BEGIN DESCRIPTION:
Lacy 116 1506
END DESCRIPTION:
XS GIS Cut Line= 3
      2727666.05      6883319.54      2727629.55      6883611.05
      2727589.52      6883807.01
#Sta/Elev= 30
  4705.7  455.00  4717.3  454.35  4727.3  452.76  4744.4  451.74  4767.6  451.48
  4787.8  451.84  4818.0  450.18  4848.3  449.53  4868.4  449.29  4888.6  449.42
  4928.9  448.85  4949.1  448.95  4959.1  448.29  4991.1  447.85  4994.9  446.00
  4995.2  445.50  4998.7  445.50  4998.9  446.00  5002.0  446.00  5009.6  447.62
  5019.9  447.94  5030.1  447.67  5043.8  447.88  5050.5  448.55  5060.7  450.58
  5070.9  451.75  5089.2  451.32  5152.5  451.66  5190.2  452.62  5199.5  452.56
#Mann=3,-1,0
  4705.7    0.05       0  4994.9    0.04       0  4998.9    0.05       0
Bank Sta=4994.9,4998.9
Exp/Cntr=0.3,0.1

Type RM Length L Ch R = 1,1687,123,123,123
BEGIN DESCRIPTION:
Lacy 116 1507
END DESCRIPTION:
XS GIS Cut Line= 3
      2727639.80      6883299.65      2727489.99      6883525.48
      2727388.51      6883705.21
#Sta/Elev= 30
  4729.0  455.62  4740.8  455.18  4746.8  455.38  4754.6  454.80  4761.8  453.37
  4776.9  451.63  4812.9  451.58  4826.6  450.17  4840.0  449.29  4855.0  448.77
  4885.1  448.52  4898.6  447.82  4921.2  447.31  4927.2  446.05  4948.3  446.31
  4957.3  446.06  4963.3  446.40  4970.6  446.06  5015.2  446.84  5027.3  444.76
  5027.6  444.26  5031.1  444.26  5031.3  444.76  5036.8  446.36  5052.3  447.72
  5058.5  449.75  5080.1  449.31  5101.8  449.43  5139.4  450.38  5206.4  450.97
#Mann=3,-1,0
  4729.0    0.05       0  5027.3    0.04       0  5031.3    0.05       0
Bank Sta=5027.3,5031.3
Exp/Cntr=0.3,0.1

Type RM Length L Ch R = 1,1564,168,168,168
BEGIN DESCRIPTION:
Lacy 116 1505
END DESCRIPTION:
XS GIS Cut Line= 3
      2727531.63      6883232.28      2727403.00      6883438.21
      2727261.16      6883632.19
#Sta/Elev= 30
  4757.2  458.64  4760.0  458.90  4767.5  457.77  4802.8  455.37  4817.8  452.65
  4826.4  451.81  4833.1  450.70  4839.0  450.51  4848.4  450.79  4869.7  448.72
  4885.0  447.74  4933.4  447.13  4942.8  447.29  4948.7  446.83  4956.1  447.08
  4979.4  446.74  4998.7  445.28  5006.5  445.01  5042.0  445.06  5048.5  443.57
  5048.8  443.07  5052.3  443.07  5052.5  443.57  5065.2  446.20  5071.4  446.58
  5077.8  448.06  5086.0  448.74  5127.8  448.95  5177.9  449.87  5240.3  450.04
#Mann=3,-1,0
  4757.2    0.05       0  5048.5    0.04       0  5052.5    0.05       0
Bank Sta=5048.5,5052.5
Exp/Cntr=0.3,0.1

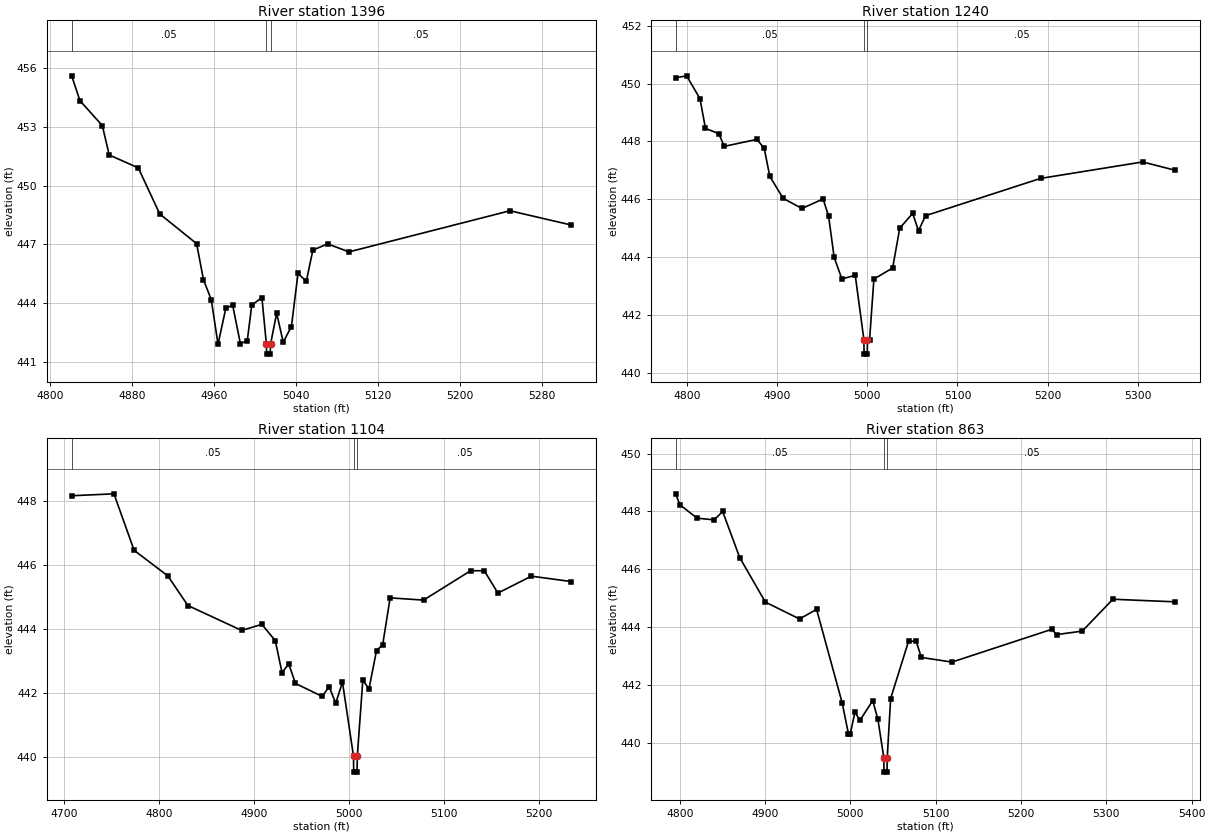
Type RM Length L Ch R = 1,1396,156,156,156
BEGIN DESCRIPTION:
Lacy 116 1504
END DESCRIPTION:
XS GIS Cut Line= 3
      2727433.78      6883166.94      2727315.22      6883301.32
      2727123.83      6883543.15
#Sta/Elev= 30
  4820.8  455.61  4828.9  454.34  4850.7  453.07  4857.4  451.57  4885.8  450.91
  4906.7  448.56  4942.7  447.04  4949.4  445.20  4957.0  444.18  4963.6  441.90
  4971.2  443.75  4977.9  443.89  4985.4  441.94  4992.1  442.08  4996.5  443.90
  5006.4  444.29  5010.8  441.90  5011.0  441.40  5014.5  441.40  5014.8  441.90
  5020.8  443.49  5027.2  442.01  5035.2  442.81  5041.6  445.52  5049.7  445.12
  5056.1  446.71  5070.5  447.03  5091.3  446.62  5248.4  448.72  5308.4  447.99
#Mann=3,-1,0
  4820.8    0.05       0  5010.8    0.04       0  5014.8    0.05       0
Bank Sta=5010.8,5014.8
Exp/Cntr=0.3,0.1

Type RM Length L Ch R = 1,1240,136,136,136
BEGIN DESCRIPTION:
Lacy 116 1503
END DESCRIPTION:
XS GIS Cut Line= 3
      2727328.99      6883017.40      2727204.70      6883193.11
      2726987.91      6883454.22
#Sta/Elev= 30
  4787.3  450.20  4799.5  450.27  4814.3  449.48  4820.4  448.45  4835.2  448.27
  4841.3  447.83  4877.5  448.07  4885.6  447.76  4891.8  446.79  4906.6  446.03
  4927.5  445.68  4950.9  446.01  4957.0  445.42  4963.2  443.99  4971.8  443.24
  4986.6  443.37  4996.2  441.14  4996.4  440.64  4999.9  440.64  5000.2  441.14
  5002.5  441.14  5007.3  443.24  5028.1  443.62  5036.0  445.00  5050.3  445.51
  5056.8  444.91  5064.6  445.43  5192.2  446.72  5305.5  447.29  5341.9  447.00
#Mann=3,-1,0
  4787.3    0.05       0  4996.2    0.04       0  5000.2    0.05       0
Bank Sta=4996.2,5000.2
Exp/Cntr=0.3,0.1

Type RM Length L Ch R = 1,1104,241,241,241
BEGIN DESCRIPTION:
Lacy 116 1501
END DESCRIPTION:
XS GIS Cut Line= 3
      2727286.07      6882948.16      2727081.03      6883155.92
      2726900.27      6883304.36
#Sta/Elev= 30
  4708.1  448.18  4752.6  448.24  4773.8  446.47  4809.2  445.67  4830.4  444.74
  4886.9  443.96  4908.2  444.15  4922.3  443.64  4929.4  442.64  4936.5  442.91
  4943.5  442.30  4971.8  441.89  4978.9  442.20  4985.9  441.68  4993.0  442.34
  5004.6  440.02  5004.8  439.52  5008.3  439.52  5008.6  440.02  5014.4  442.40
  5020.9  442.13  5028.8  443.33  5035.3  443.51  5043.1  444.98  5078.3  444.91
  5127.8  445.83  5142.2  445.83  5156.5  445.13  5191.7  445.66  5233.9  445.49
#Mann=3,-1,0
  4708.1    0.05       0  5004.6    0.04       0  5008.6    0.05       0
Bank Sta=5004.6,5008.6
Exp/Cntr=0.3,0.1

Type RM Length L Ch R = 1,863,0,0,0
BEGIN DESCRIPTION:
Lacy 116 1502
END DESCRIPTION:
XS GIS Cut Line= 3
      2727281.08      6882907.73      2727076.42      6882915.30
      2726862.61      6883230.65
#Sta/Elev= 30
  4795.2  448.61  4800.3  448.23  4820.3  447.77  4840.3  447.71  4850.3  448.00
  4870.3  446.41  4900.4  444.87  4940.4  444.29  4960.4  444.62  4990.4  441.39
  4997.7  440.33  5000.0  440.33  5005.3  441.07  5011.3  440.79  5026.2  441.47
  5032.3  440.82  5039.2  439.50  5039.4  439.00  5042.9  439.00  5043.2  439.50
  5047.2  441.54  5068.2  443.52  5077.1  443.52  5083.2  442.96  5119.1  442.80
  5235.9  443.93  5241.9  443.75  5271.8  443.87  5307.7  444.97  5381.0  444.88
#Mann=3,-1,0
  4795.2    0.05       0  5039.2    0.04       0  5043.2    0.05       0
Bank Sta=5039.2,5043.2
Exp/Cntr=0.3,0.1

Chan Stop Cuts=-1