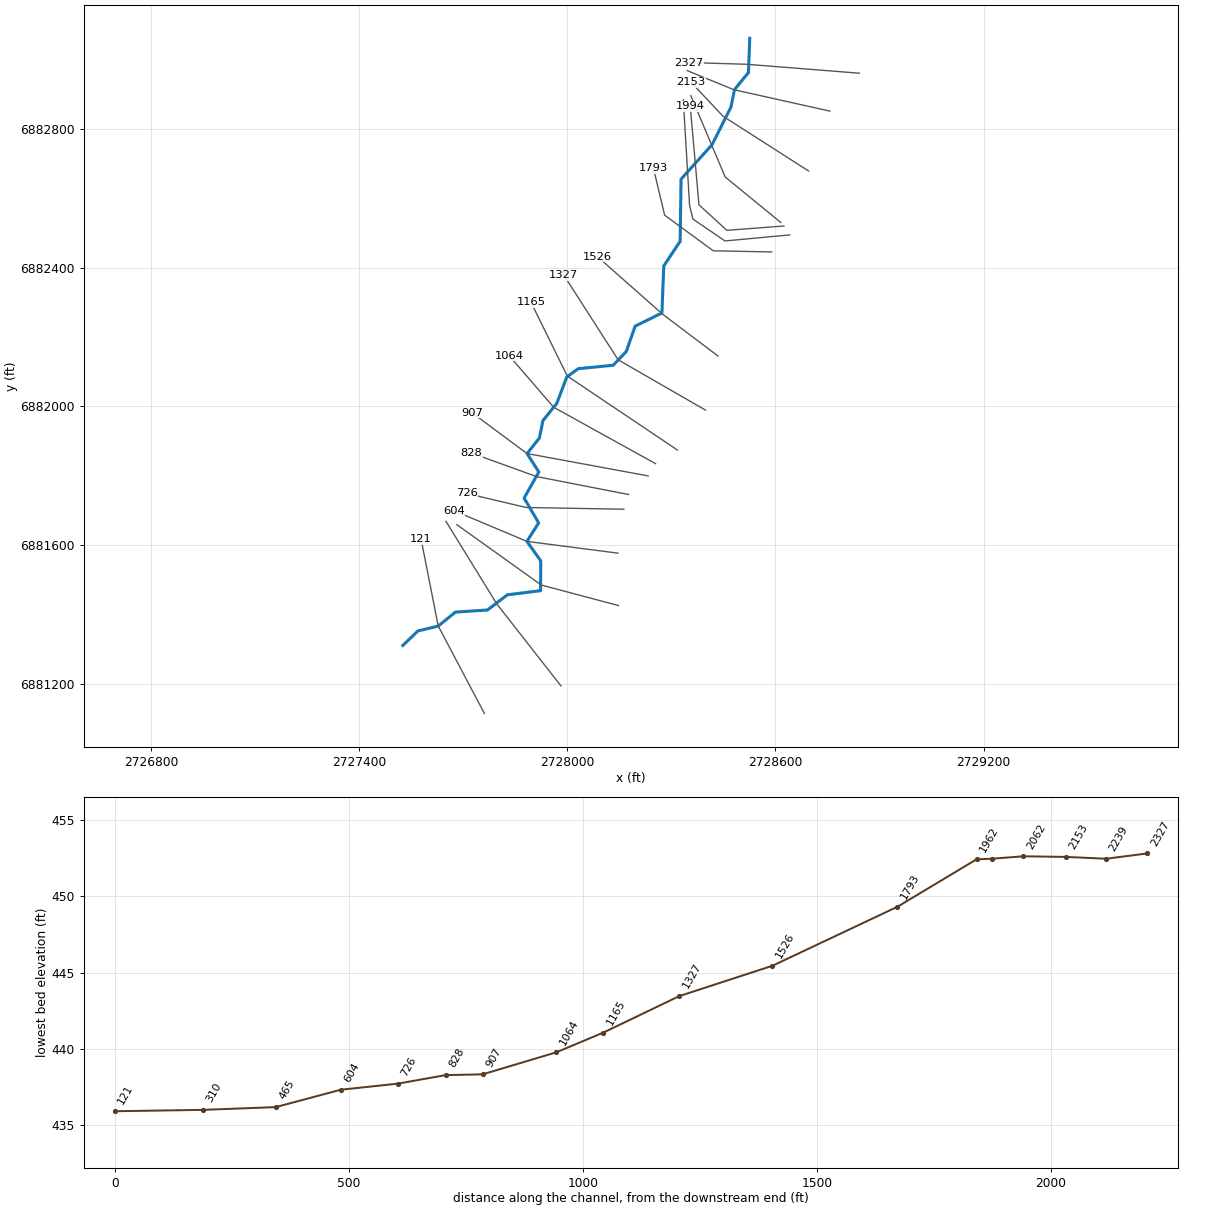
--- Lacy 117.prj (project) ---

Proj Title=Lacy 117 Base Level Engineering
Current Plan=p01
Default Exp/Contr=0.3,0.1
English Units
Geom File=g01
Flow File=f01
Plan File=p01
BEGIN DESCRIPTION:
Lacy 117
END DESCRIPTION:

--- Lacy 117.p01 (plan) ---

Plan Title=Multiple Run
Short Identifier=Multiple
Geom File=g01
Flow File=f01
Subcritical Flow
K Sum by GR= 0
Std Step Tol= 0.01
Critical Tol= 0.01
Num of Std Step Trials= 20
Max Error Tol= 0.3
Flow Tol Ratio= 0.001
Split Flow NTrial= 30
Split Flow Tol= 0.02
Split Flow Ratio= 0.02
Log Output Level= 0
Friction Slope Method= 1
Unsteady Friction Slope Method= 2
Unsteady Bridges Friction Slope Method= 1
Parabolic Critical Depth
Global Vel Dist=  1 , 1 , 1
Global Log Level= 0
CheckData=True
Encroach Param= -1, 0, 0, 0
BEGIN DESCRIPTION:
Multiple Run
END DESCRIPTION:

--- Lacy 117.f01 (steady flow) ---

Flow Title=Multiple
Number of Profiles=7
Profile Names=10-year,25-year,50-year,1pct_min,100-year,1pct_plu,500-year
River Rch & RM= Lacy 117,Reach-1,2327
     213     267     307     177     352     703     461
Boundary for River Rch & Prof#=Lacy 117,Reach-1,1
Up Type=0
Dn Type=3
Dn Slope=0.005
Boundary for River Rch & Prof#=Lacy 117,Reach-1,2
Up Type=0
Dn Type=3
Dn Slope=0.005
Boundary for River Rch & Prof#=Lacy 117,Reach-1,3
Up Type=0
Dn Type=3
Dn Slope=0.005
Boundary for River Rch & Prof#=Lacy 117,Reach-1,4
Up Type=0
Dn Type=3
Dn Slope=0.005
Boundary for River Rch & Prof#=Lacy 117,Reach-1,5
Up Type=0
Dn Type=3
Dn Slope=0.005
Boundary for River Rch & Prof#=Lacy 117,Reach-1,6
Up Type=0
Dn Type=3
Dn Slope=0.005
Boundary for River Rch & Prof#=Lacy 117,Reach-1,7
Up Type=0
Dn Type=3
Dn Slope=0.005

--- Lacy 117.g01 (geometry) ---

Geom Title=Existing Conditions

River Reach=Lacy 117,Reach-1
Reach XY= 30
      2728526.00      6883061.00      2728522.37      6882962.50
      2728482.09      6882913.19      2728471.84      6882862.72
      2728417.84      6882754.95      2728328.07      6882655.14
      2728325.48      6882476.22      2728278.28      6882405.05
      2728272.90      6882269.31      2728195.74      6882231.42
      2728170.25      6882158.45      2728132.45      6882118.75
      2728031.71      6882108.92      2727998.81      6882084.95
      2727969.88      6882008.84      2727930.13      6881959.27
      2727919.62      6881908.70      2727884.24      6881864.23
      2727918.17      6881811.08      2727875.77      6881736.00
      2727917.68      6881664.23      2727883.80      6881611.09
      2727923.69      6881555.01      2727923.16      6881469.01
      2727827.68      6881457.11      2727770.03      6881413.35
      2727677.58      6881407.18      2727628.22      6881367.03
      2727569.85      6881353.09      2727526.00      6881311.00

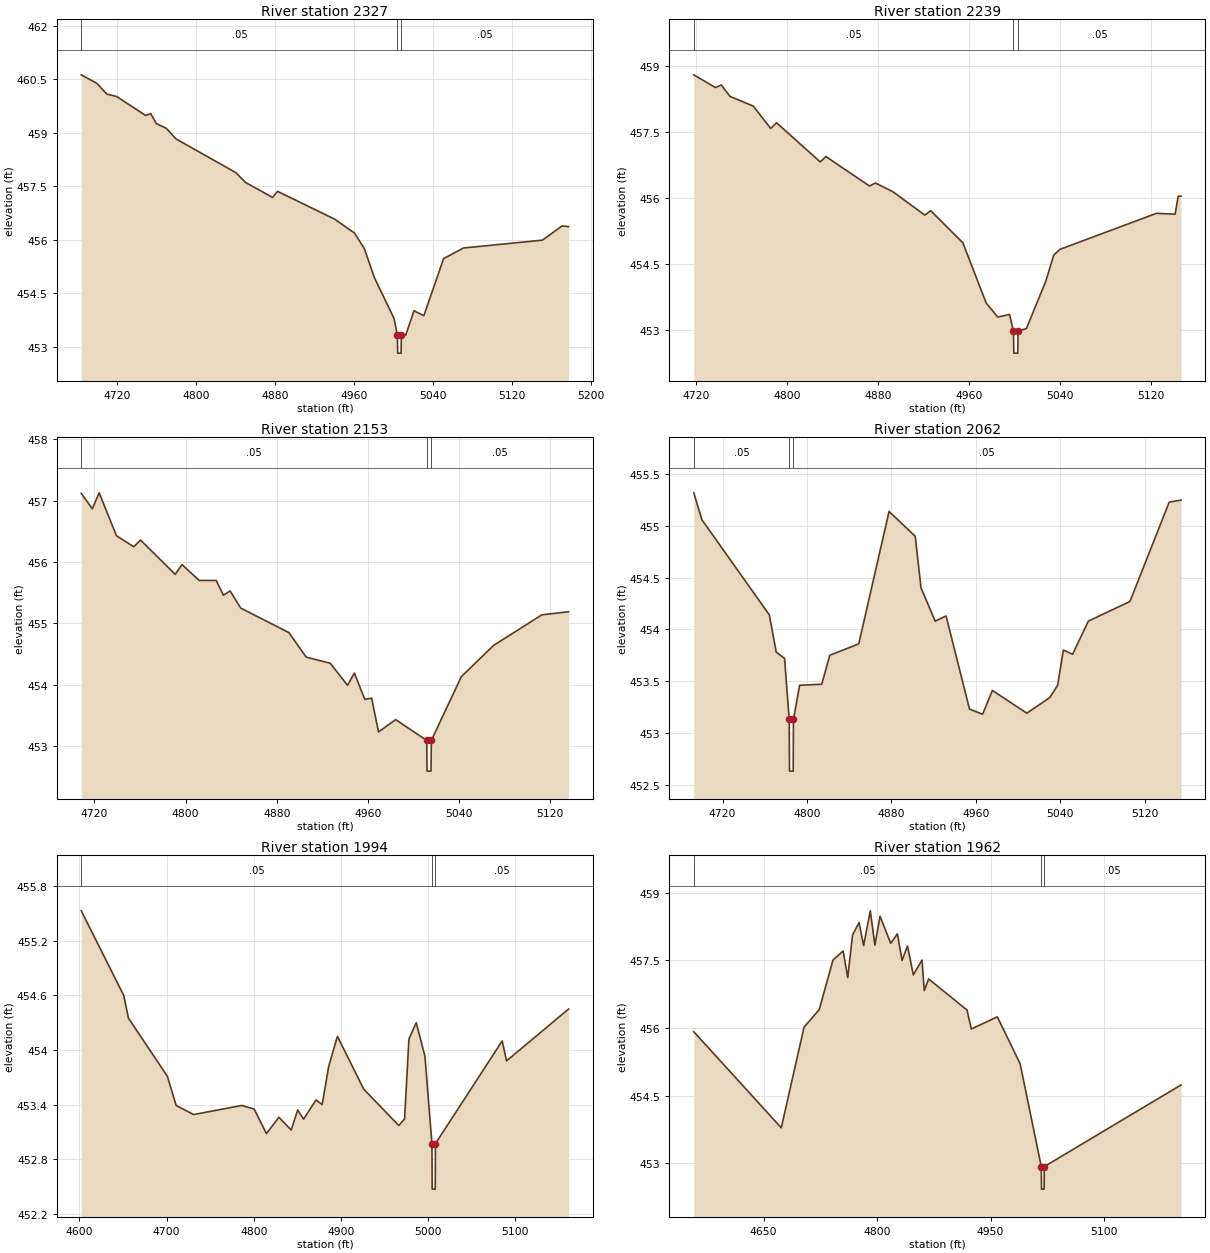
Type RM Length L Ch R = 1,2327,88,88,88
BEGIN DESCRIPTION:
Lacy 117 1466
END DESCRIPTION:
XS GIS Cut Line= 3
      2728841.74      6882960.50      2728517.60      6882986.22
      2728349.54      6882991.29
#Sta/Elev= 30
  4683.7  460.63  4699.5  460.39  4709.5  460.09  4719.6  460.02  4748.9  459.49
  4754.0  459.54  4759.7  459.26  4769.7  459.13  4779.7  458.83  4839.9  457.89
  4850.0  457.61  4877.3  457.19  4882.4  457.36  4940.2  456.58  4960.3  456.19
  4970.3  455.75  4980.4  454.94  5000.4  453.79  5003.7  453.32  5004.0  452.82
  5007.5  452.82  5007.7  453.32  5012.2  453.33  5020.5  454.01  5030.5  453.87
  5050.5  455.47  5070.5  455.77  5150.5  455.99  5170.5  456.39  5177.0  456.37
#Mann=3,-1,0
  4683.7    0.05       0  5003.7    0.04       0  5007.7    0.05       0
Bank Sta=5003.7,5007.7
Exp/Cntr=0.3,0.1

Type RM Length L Ch R = 1,2239,86,86,86
BEGIN DESCRIPTION:
Lacy 117 1472
END DESCRIPTION:
XS GIS Cut Line= 3
      2728757.01      6882851.26      2728480.10      6882912.98
      2728346.01      6882967.89
#Sta/Elev= 30
  4718.2  458.80  4737.3  458.51  4742.4  458.57  4750.0  458.31  4770.5  458.09
  4785.9  457.58  4791.0  457.71  4829.4  456.82  4834.5  456.94  4872.8  456.27
  4878.0  456.34  4893.4  456.14  4921.4  455.61  4926.6  455.71  4954.9  454.98
  4975.4  453.61  4985.6  453.29  4995.9  453.35  4999.4  452.97  4999.7  452.47
  5003.2  452.47  5003.4  452.97  5010.8  453.03  5027.9  454.11  5034.8  454.70
  5040.2  454.83  5125.2  455.65  5141.6  455.63  5144.3  456.04  5146.8  456.04
#Mann=3,-1,0
  4718.2    0.05       0  4999.4    0.04       0  5003.4    0.05       0
Bank Sta=4999.4,5003.4
Exp/Cntr=0.3,0.1

Type RM Length L Ch R = 1,2153,91,91,91
BEGIN DESCRIPTION:
Lacy 117 1471
END DESCRIPTION:
XS GIS Cut Line= 3
      2728695.84      6882678.59      2728448.69      6882836.78
      2728356.62      6882934.78
#Sta/Elev= 30
  4708.4  457.12  4718.1  456.87  4724.1  457.13  4739.3  456.43  4754.5  456.25
  4760.4  456.36  4790.9  455.80  4796.8  455.96  4812.0  455.70  4826.9  455.70
  4833.2  455.46  4839.1  455.53  4848.4  455.25  4890.7  454.85  4905.9  454.45
  4927.0  454.35  4942.2  453.99  4948.2  454.19  4957.4  453.76  4963.4  453.78
  4969.4  453.23  4984.5  453.43  5011.8  453.09  5012.0  452.59  5015.5  452.59
  5015.8  453.09  5042.1  454.13  5070.4  454.64  5112.9  455.14  5136.3  455.19
#Mann=3,-1,0
  4708.4    0.05       0  5011.8    0.04       0  5015.8    0.05       0
Bank Sta=5011.8,5015.8
Exp/Cntr=0.3,0.1

Type RM Length L Ch R = 1,2062,68,68,68
BEGIN DESCRIPTION:
Lacy 117 1470
END DESCRIPTION:
XS GIS Cut Line= 3
      2728615.76      6882530.10      2728455.27      6882661.32
      2728356.32      6882895.58
#Sta/Elev= 30
  4692.7  455.32  4700.4  455.06  4764.3  454.14  4770.8  453.78  4778.7  453.72
  4783.1  453.13  4783.4  452.63  4786.9  452.63  4787.1  453.13  4793.0  453.46
  4813.9  453.47  4821.6  453.75  4849.0  453.86  4877.7  455.14  4902.5  454.90
  4908.0  454.40  4921.4  454.08  4931.7  454.13  4953.9  453.23  4966.3  453.18
  4975.6  453.41  5008.2  453.19  5029.9  453.34  5037.4  453.46  5042.8  453.80
  5051.6  453.76  5066.5  454.08  5105.9  454.27  5143.1  455.23  5154.3  455.25
#Mann=3,-1,0
  4692.7    0.05       0  4783.1    0.04       0  4787.1    0.05       0
Bank Sta=4783.1,4787.1
Exp/Cntr=0.3,0.1

Type RM Length L Ch R = 1,1994,32,32,32
BEGIN DESCRIPTION:
Lacy 117 1468
END DESCRIPTION:
XS GIS Cut Line= 4
      2728624.53      6882520.16      2728460.11      6882507.59
      2728379.69      6882581.18      2728354.58      6882865.07
#Sta/Elev= 30
  4602.1  455.53  4650.8  454.60  4656.2  454.35  4700.9  453.71  4710.9  453.39
  4731.0  453.29  4786.2  453.39  4800.4  453.35  4814.5  453.08  4828.7  453.26
  4842.9  453.12  4850.3  453.34  4857.1  453.24  4871.3  453.45  4878.4  453.40
  4885.9  453.82  4895.9  454.15  4926.0  453.57  4966.2  453.17  4972.9  453.24
  4977.9  454.12  4986.3  454.30  4996.3  453.93  5004.3  452.97  5004.6  452.47
  5008.1  452.47  5008.3  452.97  5084.9  454.10  5089.9  453.88  5161.0  454.45
#Mann=3,-1,0
  4602.1    0.05       0  5004.3    0.04       0  5008.3    0.05       0
Bank Sta=5004.3,5008.3
Exp/Cntr=0.3,0.1

Type RM Length L Ch R = 1,1962,169,169,169
BEGIN DESCRIPTION:
Lacy 117 1467
END DESCRIPTION:
XS GIS Cut Line= 5
      2728641.17      6882494.43      2728454.68      6882476.99
      2728362.21      6882540.13      2728352.69      6882579.09
      2728334.48      6882883.46
#Sta/Elev= 30
  4557.6  455.92  4673.3  453.79  4703.4  456.02  4723.5  456.41  4741.7  457.51
  4755.1  457.71  4761.2  457.12  4767.5  458.06  4776.1  458.34  4782.2  457.83
  4791.0  458.60  4797.1  457.84  4803.9  458.48  4818.0  457.88  4826.9  458.09
  4833.0  457.50  4840.2  457.82  4847.9  457.18  4859.4  457.51  4862.4  456.83
  4868.1  457.09  4918.9  456.40  4924.6  455.98  4959.0  456.25  4989.1  455.21
  5017.1  452.93  5017.4  452.43  5020.9  452.43  5021.1  452.93  5201.9  454.74
#Mann=3,-1,0
  4557.6    0.05       0  5017.1    0.04       0  5021.1    0.05       0
Bank Sta=5017.1,5021.1
Exp/Cntr=0.3,0.1

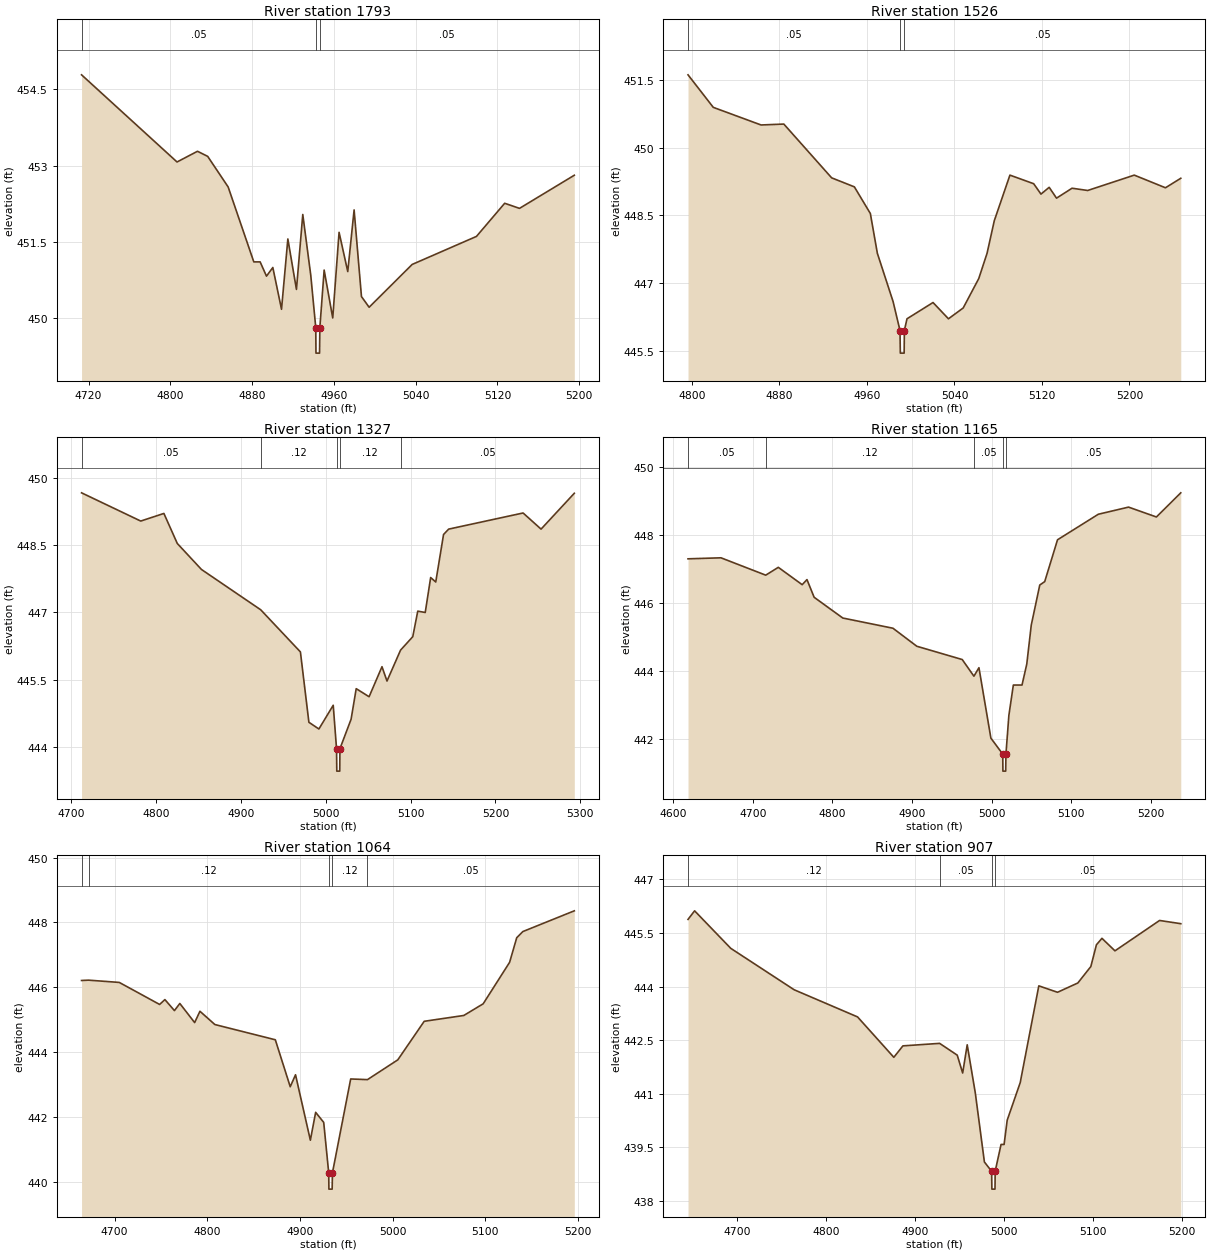
Type RM Length L Ch R = 1,1793,267,267,267
BEGIN DESCRIPTION:
Lacy 117 1469
END DESCRIPTION:
XS GIS Cut Line= 4
      2728589.40      6882445.32      2728420.92      6882448.62
      2728280.80      6882551.28      2728248.34      6882687.24
#Sta/Elev= 30
  4713.2  454.78  4806.6  453.07  4826.6  453.28  4836.6  453.18  4856.6  452.58
  4881.7  451.11  4887.9  451.11  4894.1  450.83  4900.3  451.00  4908.8  450.18
  4915.0  451.56  4923.4  450.57  4929.6  452.04  4937.4  450.85  4942.3  449.82
  4942.5  449.32  4946.0  449.32  4946.3  449.82  4950.5  450.95  4958.9  450.01
  4965.1  451.69  4973.6  450.92  4979.8  452.13  4987.0  450.43  4994.5  450.22
  5036.6  451.06  5099.5  451.61  5127.1  452.26  5141.6  452.16  5195.2  452.81
#Mann=3,-1,0
  4713.2    0.05       0  4942.3    0.04       0  4946.3    0.05       0
Bank Sta=4942.3,4946.3
Exp/Cntr=0.3,0.1

Type RM Length L Ch R = 1,1526,199,199,199
BEGIN DESCRIPTION:
Lacy 117 1473
END DESCRIPTION:
XS GIS Cut Line= 3
      2728434.14      6882145.64      2728273.95      6882266.66
      2728086.86      6882432.08
#Sta/Elev= 30
  4796.4  451.61  4819.5  450.89  4863.2  450.50  4884.0  450.52  4927.7  449.33
  4948.5  449.13  4963.1  448.54  4969.5  447.66  4983.9  446.59  4990.2  445.95
  4990.5  445.45  4994.0  445.45  4994.2  445.95  4996.6  446.21  5020.4  446.57
  5034.5  446.21  5048.0  446.45  5062.2  447.10  5069.8  447.66  5076.4  448.38
  5090.7  449.39  5112.4  449.20  5119.1  448.97  5126.6  449.12  5133.3  448.88
  5147.5  449.10  5161.8  449.05  5204.4  449.39  5232.9  449.11  5246.9  449.32
#Mann=3,-1,0
  4796.4    0.05       0  4990.2    0.04       0  4994.2    0.05       0
Bank Sta=4990.2,4994.2
Exp/Cntr=0.3,0.1

Type RM Length L Ch R = 1,1327,162,162,162
BEGIN DESCRIPTION:
Lacy 117 1474
END DESCRIPTION:
XS GIS Cut Line= 3
      2728398.53      6881989.46      2728146.72      6882134.51
      2727989.77      6882378.96
#Sta/Elev= 30
  4711.9  449.67  4781.7  449.04  4809.0  449.21  4824.8  448.54  4853.3  447.96
  4923.2  447.06  4970.0  446.12  4980.0  444.55  4991.8  444.40  5008.7  444.93
  5012.6  443.96  5012.9  443.46  5016.4  443.46  5016.6  443.96  5029.8  444.62
  5035.8  445.30  5051.0  445.12  5066.2  445.79  5072.1  445.47  5088.1  446.16
  5102.5  446.46  5108.4  447.03  5117.2  447.00  5123.6  447.78  5129.6  447.68
  5138.8  448.74  5144.8  448.86  5232.6  449.22  5253.8  448.86  5293.0  449.66
#Mann=5,-1,0
  4711.9    0.05       0  4923.2    0.12       0  5012.6    0.07       0
  5016.6    0.12       0  5088.1    0.05       0
Bank Sta=5012.6,5016.6
Exp/Cntr=0.3,0.1

Type RM Length L Ch R = 1,1165,101,101,101
BEGIN DESCRIPTION:
Lacy 117 1475
END DESCRIPTION:
XS GIS Cut Line= 3
      2728317.57      6881874.39      2728000.27      6882087.53
      2727895.71      6882299.84
#Sta/Elev= 30
  4618.7  447.31  4660.1  447.34  4716.3  446.83  4732.1  447.06  4762.1  446.55
  4768.1  446.70  4777.1  446.18  4813.1  445.57  4876.1  445.27  4906.1  444.74
  4963.1  444.35  4977.8  443.86  4984.1  444.11  4999.1  442.04  5014.0  441.57
  5014.2  441.07  5017.7  441.07  5018.0  441.57  5021.7  442.71  5027.3  443.60
  5038.2  443.60  5044.2  444.22  5049.8  445.36  5060.5  446.54  5066.7  446.64
  5082.8  447.87  5134.0  448.62  5172.0  448.83  5207.0  448.54  5237.6  449.25
#Mann=5,-1,0
  4618.7    0.05       0  4716.3    0.12       0  4977.8    0.05       0
  5014.0    0.04       0  5018.0    0.05       0
Bank Sta=5014,5018
Exp/Cntr=0.3,0.1

Type RM Length L Ch R = 1,1064,157,157,157
BEGIN DESCRIPTION:
Lacy 117 1477
END DESCRIPTION:
XS GIS Cut Line= 3
      2728254.56      6881835.17      2727960.91      6881997.66
      2727832.94      6882145.97
#Sta/Elev= 30
  4664.4  446.21  4671.9  446.22  4705.1  446.15  4748.6  445.47  4754.3  445.62
  4764.6  445.28  4770.4  445.50  4786.4  444.91  4792.1  445.26  4808.2  444.85
  4873.4  444.38  4889.5  442.93  4895.2  443.30  4911.2  441.28  4916.9  442.14
  4925.6  441.83  4931.0  440.27  4931.2  439.77  4934.7  439.77  4935.0  440.27
  4954.7  443.17  4972.8  443.15  5005.5  443.76  5034.0  444.95  5076.7  445.13
  5097.6  445.49  5126.1  446.77  5133.8  447.53  5140.4  447.72  5195.9  448.36
#Mann=5,-1,0
  4664.4    0.05       0  4671.9    0.12       0  4931.0    0.04       0
  4935.0    0.12       0  4972.8    0.05       0
Bank Sta=4931,4935
Exp/Cntr=0.3,0.1

Type RM Length L Ch R = 1,907,79,79,79
BEGIN DESCRIPTION:
Lacy 117 1476
END DESCRIPTION:
XS GIS Cut Line= 3
      2728233.25      6881799.83      2727884.24      6881864.23
      2727724.85      6881982.38
#Sta/Elev= 30
  4645.1  445.88  4652.5  446.12  4693.1  445.07  4764.3  443.91  4835.5  443.15
  4876.2  442.02  4886.4  442.34  4927.6  442.41  4947.4  442.08  4953.5  441.58
  4958.6  442.37  4967.7  441.02  4977.9  439.09  4986.0  438.83  4986.3  438.33
  4989.8  438.33  4990.0  438.83  4996.6  439.58  5000.0  439.58  5003.5  440.26
  5018.1  441.31  5039.0  444.02  5060.0  443.84  5082.8  444.10  5097.4  444.56
  5103.7  445.17  5109.9  445.35  5124.5  445.00  5174.6  445.85  5198.4  445.76
#Mann=4,-1,0
  4645.1    0.12       0  4927.6    0.05       0  4986.0    0.04       0
  4990.0    0.05       0
Bank Sta=4986,4990
Exp/Cntr=0.3,0.1

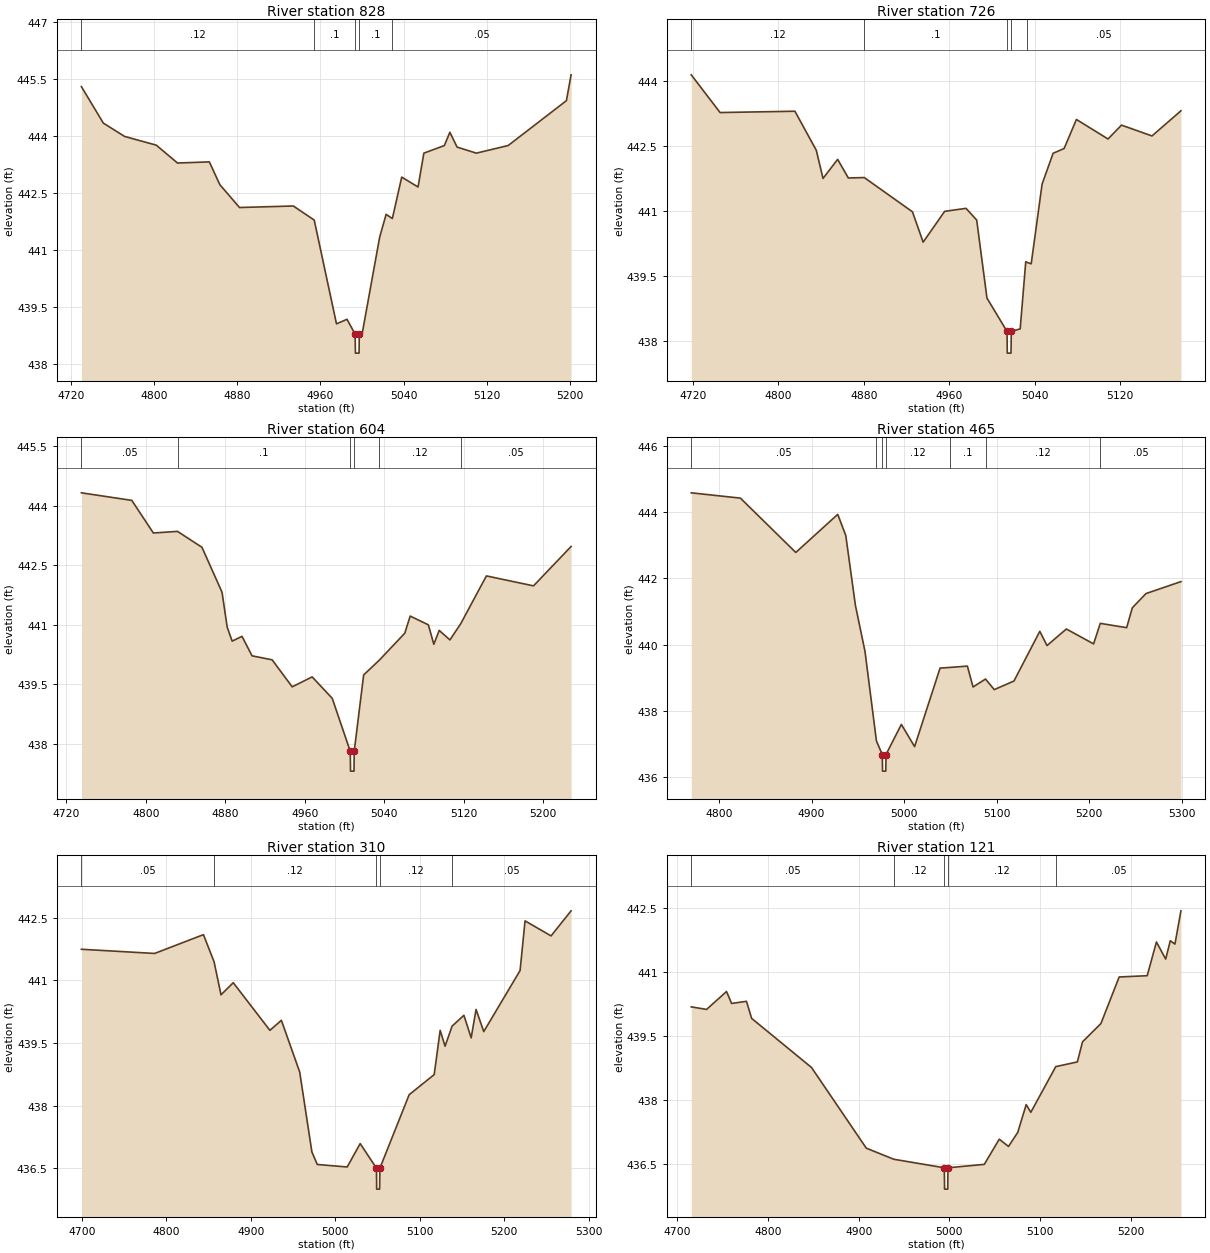
Type RM Length L Ch R = 1,828,102,102,102
BEGIN DESCRIPTION:
Lacy 117 1483
END DESCRIPTION:
XS GIS Cut Line= 3
      2728176.69      6881746.26      2727911.86      6881797.81
      2727722.93      6881866.12
#Sta/Elev= 30
  4730.2  445.29  4751.3  444.33  4771.7  443.98  4802.2  443.75  4822.6  443.28
  4853.2  443.31  4863.3  442.71  4882.2  442.11  4933.9  442.15  4954.0  441.78
  4975.4  439.05  4985.5  439.17  4993.3  438.78  4993.6  438.28  4997.1  438.28
  4997.3  438.78  5000.0  438.78  5016.9  441.33  5023.1  441.93  5029.1  441.82
  5038.1  442.91  5053.8  442.65  5059.4  443.54  5079.1  443.74  5084.4  444.09
  5091.3  443.70  5109.8  443.54  5140.4  443.74  5196.4  444.92  5200.9  445.60
#Mann=5,-1,0
  4730.2    0.12       0  4954.0     0.1       0  4993.3    0.07       0
  4997.3     0.1       0  5029.1    0.05       0
Bank Sta=4993.3,4997.3
Exp/Cntr=0.3,0.1

Type RM Length L Ch R = 1,726,122,122,122
BEGIN DESCRIPTION:
Lacy 117 1482
END DESCRIPTION:
XS GIS Cut Line= 3
      2728163.02      6881703.84      2727881.66      6881708.71
      2727709.61      6881749.44
#Sta/Elev= 30
  4718.6  444.14  4745.6  443.27  4815.6  443.30  4835.6  442.40  4841.9  441.75
  4855.6  442.19  4865.6  441.76  4880.5  441.77  4925.6  440.98  4935.6  440.28
  4955.7  440.99  4975.7  441.06  4985.7  440.79  4995.3  438.99  5014.1  438.22
  5014.3  437.72  5017.8  437.72  5018.1  438.22  5026.4  438.28  5031.6  439.83
  5033.2  439.81  5036.7  439.78  5046.9  441.62  5057.2  442.33  5067.5  442.44
  5079.0  443.11  5108.6  442.66  5121.2  442.98  5149.7  442.73  5176.8  443.31
#Mann=5,-1,0
  4718.6    0.12       0  4880.5     0.1       0  5014.1    0.07       0
  5018.1     0.1       0  5033.2    0.05       0
Bank Sta=5014.1,5018.1
Exp/Cntr=0.3,0.1

Type RM Length L Ch R = 1,604,139,139,139
BEGIN DESCRIPTION:
Lacy 117 1481
END DESCRIPTION:
XS GIS Cut Line= 3
      2728146.32      6881577.18      2727883.80      6881611.09
      2727673.69      6881699.62
#Sta/Elev= 30
  4735.3  444.32  4786.0  444.13  4807.7  443.31  4832.0  443.35  4856.6  442.95
  4876.8  441.82  4882.0  440.94  4887.0  440.59  4896.9  440.71  4907.0  440.22
  4927.2  440.12  4947.4  439.44  4967.5  439.69  4987.7  439.15  5005.8  437.82
  5006.1  437.32  5009.6  437.32  5009.8  437.82  5019.3  439.74  5035.0  440.11
  5060.7  440.79  5066.1  441.22  5084.4  441.00  5089.9  440.51  5095.3  440.86
  5106.1  440.62  5117.0  441.03  5142.8  442.23  5190.2  441.98  5228.0  442.97
#Mann=6,-1,0
  4735.3    0.05       0  4832.0     0.1       0  5005.8    0.07       0
  5009.8     0.1       0  5035.0    0.12       0  5117.0    0.05       0
Bank Sta=5005.8,5009.8
Exp/Cntr=0.3,0.1

Type RM Length L Ch R = 1,465,155,155,155
BEGIN DESCRIPTION:
Lacy 117 1480
END DESCRIPTION:
XS GIS Cut Line= 3
      2728147.34      6881426.28      2727925.15      6881485.32
      2727682.02      6881659.18
#Sta/Elev= 30
  4770.1  444.58  4823.2  444.42  4883.0  442.78  4928.3  443.93  4937.0  443.29
  4947.4  441.18  4957.7  439.80  4970.1  437.09  4976.4  436.68  4976.7  436.18
  4980.2  436.18  4980.4  436.68  4997.0  437.59  5011.3  436.92  5038.8  439.29
  5049.4  439.31  5068.3  439.35  5074.4  438.72  5087.9  438.96  5097.3  438.64
  5118.6  438.90  5146.5  440.40  5154.3  439.97  5175.2  440.47  5204.6  440.02
  5211.8  440.64  5240.3  440.51  5246.4  441.11  5261.2  441.54  5298.9  441.90
#Mann=7,-1,0
  4770.1    0.05       0  4970.1    0.12       0  4976.4    0.07       0
  4980.4    0.12       0  5049.4     0.1       0  5087.9    0.12       0
  5211.8    0.05       0
Bank Sta=4976.4,4980.4
Exp/Cntr=0.3,0.1

Type RM Length L Ch R = 1,310,189,189,189
BEGIN DESCRIPTION:
Lacy 117 1479
END DESCRIPTION:
XS GIS Cut Line= 3
      2727981.90      6881194.51      2727796.80      6881431.11
      2727650.38      6881669.07
#Sta/Elev= 30
  4699.5  441.74  4786.2  441.64  4844.0  442.09  4856.6  441.44  4864.8  440.65
  4879.3  440.94  4922.7  439.80  4936.3  440.04  4958.0  438.80  4972.4  436.89
  4978.8  436.59  5014.2  436.53  5029.6  437.09  5048.9  436.50  5049.1  436.00
  5052.6  436.00  5052.9  436.50  5087.6  438.26  5117.2  438.74  5124.3  439.80
  5130.1  439.42  5138.4  439.90  5152.4  440.16  5161.0  439.62  5166.8  440.30
  5175.9  439.77  5218.9  441.23  5224.8  442.42  5255.6  442.06  5279.3  442.66
#Mann=5,-1,0
  4699.5    0.05       0  4856.6    0.12       0  5048.9    0.07       0
  5052.9    0.12       0  5138.4    0.05       0
Bank Sta=5048.9,5052.9
Exp/Cntr=0.3,0.1

Type RM Length L Ch R = 1,121,0,0,0
BEGIN DESCRIPTION:
Lacy 117 1478
END DESCRIPTION:
XS GIS Cut Line= 3
      2727761.15      6881115.38      2727628.22      6881367.03
      2727578.75      6881617.49
#Sta/Elev= 30
  4715.4  440.18  4732.3  440.12  4754.3  440.54  4759.9  440.26  4776.3  440.31
  4782.0  439.91  4848.0  438.76  4908.4  436.87  4938.7  436.61  4994.4  436.41
  4994.7  435.91  4998.2  435.91  4998.4  436.41  5038.5  436.49  5055.0  437.08
  5065.2  436.91  5075.4  437.24  5084.7  437.89  5089.8  437.71  5117.3  438.78
  5141.1  438.89  5146.8  439.36  5167.1  439.79  5187.2  440.88  5218.1  440.91
  5228.3  441.70  5238.5  441.30  5243.6  441.73  5248.7  441.65  5255.3  442.43
#Mann=5,-1,0
  4715.4    0.05       0  4938.7    0.12       0  4994.4    0.07       0
  4998.4    0.12       0  5117.3    0.05       0
Bank Sta=4994.4,4998.4
Exp/Cntr=0.3,0.1

Chan Stop Cuts=-1