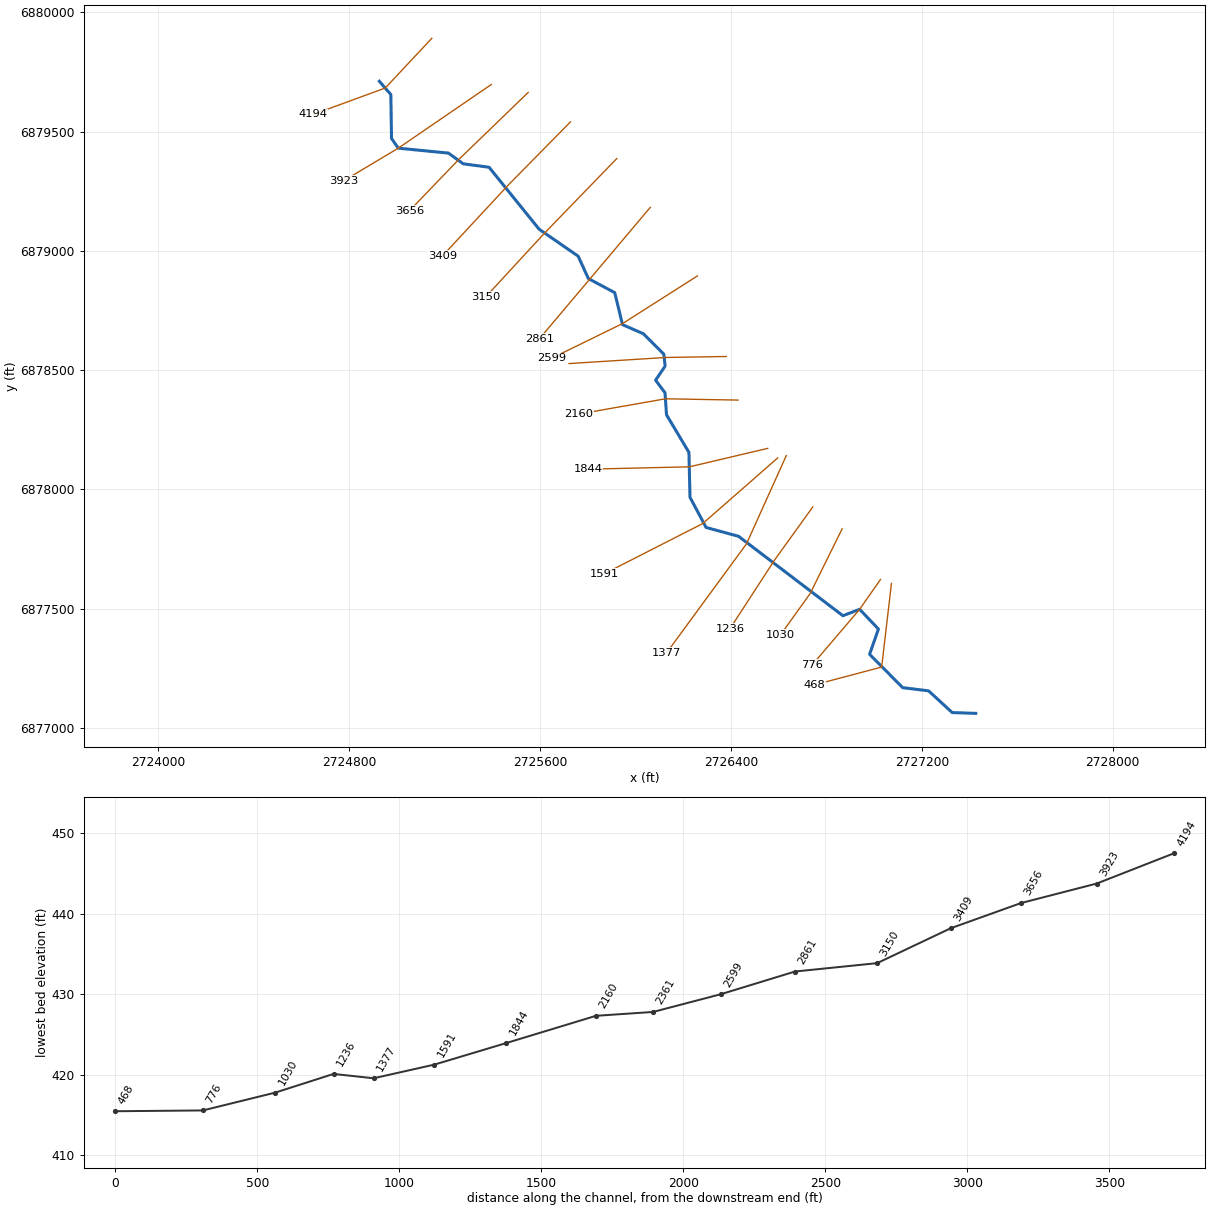
--- Lacy 119.prj (project) ---

Proj Title=Lacy 119 Base Level Engineering
Current Plan=p01
Default Exp/Contr=0.3,0.1
English Units
Geom File=g01
Flow File=f01
Plan File=p01
BEGIN DESCRIPTION:
Lacy 119
END DESCRIPTION:

--- Lacy 119.p01 (plan) ---

Plan Title=Multiple Run
Short Identifier=Multiple
Geom File=g01
Flow File=f01
Subcritical Flow
K Sum by GR= 0
Std Step Tol= 0.01
Critical Tol= 0.01
Num of Std Step Trials= 20
Max Error Tol= 0.3
Flow Tol Ratio= 0.001
Split Flow NTrial= 30
Split Flow Tol= 0.02
Split Flow Ratio= 0.02
Log Output Level= 0
Friction Slope Method= 1
Unsteady Friction Slope Method= 2
Unsteady Bridges Friction Slope Method= 1
Parabolic Critical Depth
Global Vel Dist=  1 , 1 , 1
Global Log Level= 0
CheckData=True
Encroach Param= -1, 0, 0, 0
BEGIN DESCRIPTION:
Multiple Run
END DESCRIPTION:

--- Lacy 119.f01 (steady flow) ---

Flow Title=Multiple
Number of Profiles=7
Profile Names=10-year,25-year,50-year,1pct_min,100-year,1pct_plu,500-year
River Rch & RM= Lacy 119,Reach-1,4194
     293     374     436     253     505    1008     676
Boundary for River Rch & Prof#=Lacy 119,Reach-1,1
Up Type=0
Dn Type=3
Dn Slope=0.005
Boundary for River Rch & Prof#=Lacy 119,Reach-1,2
Up Type=0
Dn Type=3
Dn Slope=0.005
Boundary for River Rch & Prof#=Lacy 119,Reach-1,3
Up Type=0
Dn Type=3
Dn Slope=0.005
Boundary for River Rch & Prof#=Lacy 119,Reach-1,4
Up Type=0
Dn Type=3
Dn Slope=0.005
Boundary for River Rch & Prof#=Lacy 119,Reach-1,5
Up Type=0
Dn Type=3
Dn Slope=0.005
Boundary for River Rch & Prof#=Lacy 119,Reach-1,6
Up Type=0
Dn Type=3
Dn Slope=0.005
Boundary for River Rch & Prof#=Lacy 119,Reach-1,7
Up Type=0
Dn Type=3
Dn Slope=0.005

--- Lacy 119.g01 (geometry) ---

Geom Title=Existing Conditions

River Reach=Lacy 119,Reach-1
Reach XY= 30
      2724926.00      6879711.00      2724974.11      6879655.22
      2724976.98      6879471.26      2725005.34      6879430.40
      2725215.50      6879409.78      2725277.60      6879364.86
      2725385.81      6879350.49      2725595.84      6879090.61
      2725759.36      6878977.70      2725802.17      6878883.86
      2725912.74      6878824.65      2725945.47      6878690.46
      2726032.05      6878652.84      2726118.51      6878567.07
      2726124.02      6878517.06      2726084.10      6878457.71
      2726123.45      6878405.11      2726129.82      6878312.59
      2726223.76      6878155.07      2726228.24      6877966.93
      2726295.58      6877840.43      2726432.16      6877803.12
      2726869.34      6877470.32      2726939.39      6877497.35
      2727018.18      6877414.44      2726981.12      6877308.71
      2727119.83      6877168.86      2727228.42      6877155.46
      2727327.41      6877064.39      2727426.00      6877061.00

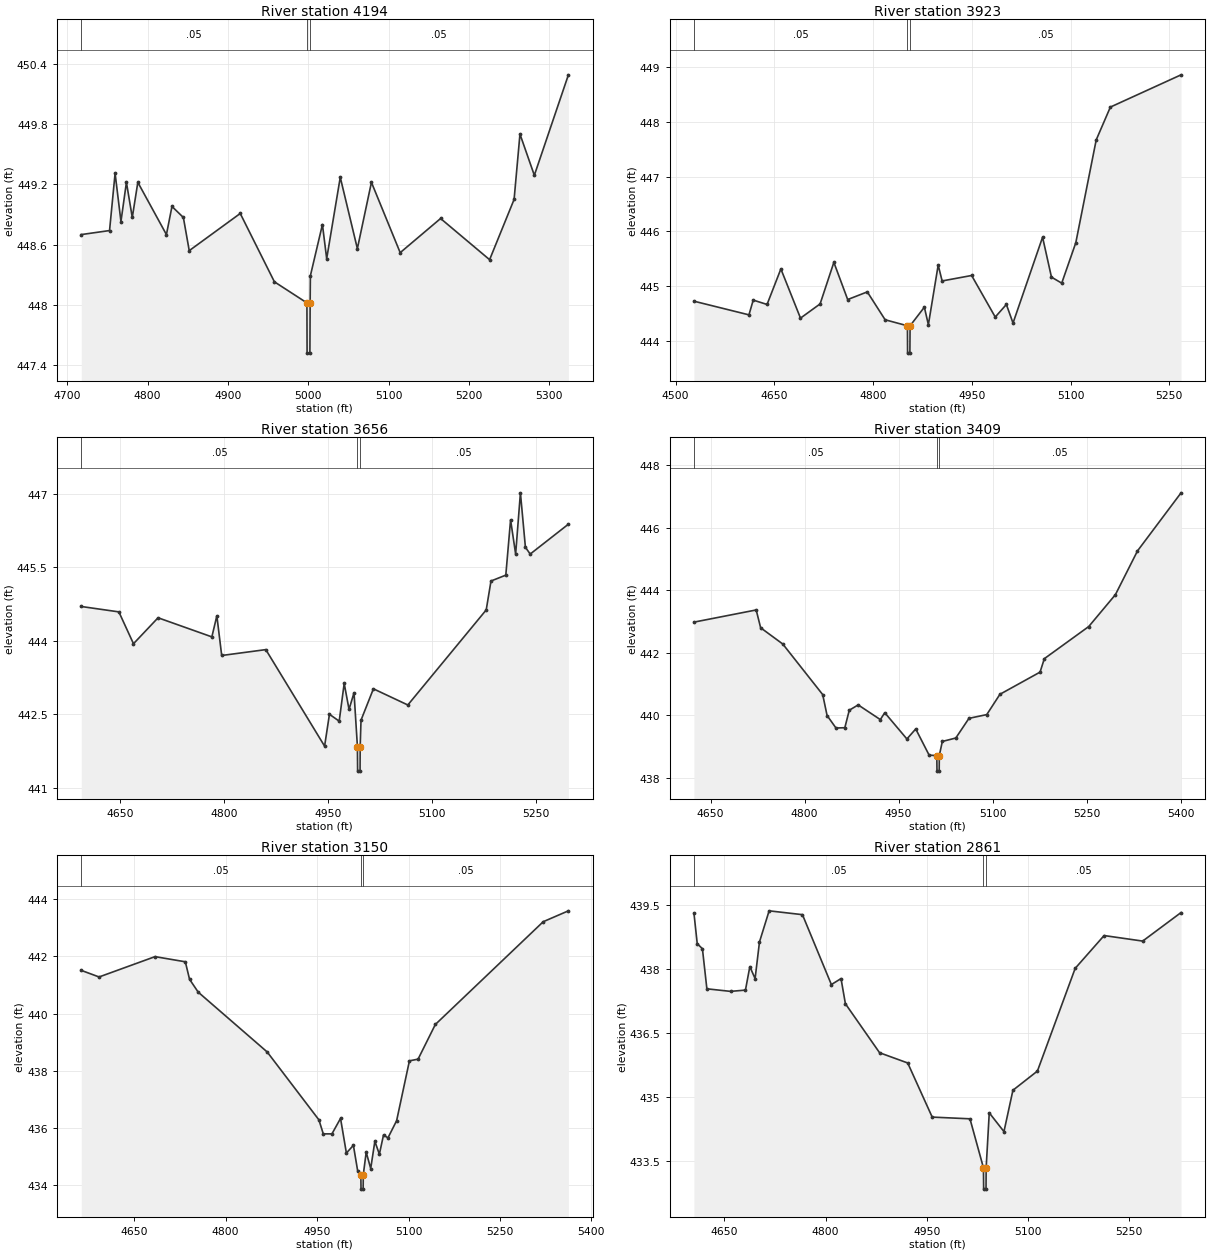
Type RM Length L Ch R = 1,4194,271,271,271
BEGIN DESCRIPTION:
Lacy 119 1449
END DESCRIPTION:
XS GIS Cut Line= 3
      2725145.86      6879890.86      2724950.81      6879682.65
      2724649.37      6879572.04
#Sta/Elev= 30
  4717.5  448.70  4752.7  448.74  4759.6  449.31  4766.9  448.83  4773.7  449.22
  4781.0  448.87  4787.9  449.22  4823.5  448.70  4830.4  448.98  4844.6  448.87
  4851.9  448.54  4915.4  448.91  4957.9  448.23  4998.4  448.02  4998.6  447.52
  5002.1  447.52  5002.4  448.02  5002.7  448.29  5017.7  448.80  5023.0  448.46
  5039.9  449.27  5061.2  448.56  5078.7  449.22  5114.5  448.52  5164.8  448.86
  5225.8  448.45  5256.3  449.05  5263.6  449.70  5281.5  449.29  5323.9  450.29
#Mann=3,-1,0
  4717.5    0.05       0  4998.4    0.04       0  5002.4    0.05       0
Bank Sta=4998.4,5002.4
Exp/Cntr=0.3,0.1

Type RM Length L Ch R = 1,3923,267,267,267
BEGIN DESCRIPTION:
Lacy 119 1448
END DESCRIPTION:
XS GIS Cut Line= 3
      2725394.99      6879697.14      2725005.34      6879430.40
      2724775.35      6879293.02
#Sta/Elev= 30
  4527.8  444.72  4611.4  444.47  4617.9  444.74  4638.9  444.66  4659.9  445.31
  4689.7  444.41  4719.5  444.67  4740.4  445.43  4761.4  444.75  4791.2  444.89
  4818.3  444.38  4852.2  444.27  4852.4  443.77  4855.9  443.77  4856.2  444.27
  4877.9  444.61  4884.0  444.29  4898.9  445.38  4904.9  445.09  4949.7  445.19
  4985.6  444.43  5002.5  444.66  5012.6  444.32  5057.5  445.89  5071.0  445.16
  5086.6  445.05  5108.0  445.79  5139.0  447.67  5160.5  448.27  5267.9  448.86
#Mann=3,-1,0
  4527.8    0.05       0  4852.2    0.04       0  4856.2    0.05       0
Bank Sta=4852.2,4856.2
Exp/Cntr=0.3,0.1

Type RM Length L Ch R = 1,3656,247,247,247
BEGIN DESCRIPTION:
Lacy 119 1447
END DESCRIPTION:
XS GIS Cut Line= 3
      2725549.84      6879663.95      2725257.57      6879381.57
      2725051.60      6879167.45
#Sta/Elev= 30
  4593.6  444.70  4647.9  444.59  4669.0  443.94  4704.5  444.47  4782.2  444.08
  4789.4  444.51  4796.4  443.70  4860.1  443.82  4945.0  441.85  4952.0  442.50
  4966.1  442.36  4973.3  443.13  4980.3  442.60  4987.5  442.94  4992.4  441.84
  4992.7  441.34  4996.2  441.34  4996.4  441.84  4997.6  442.38  5015.5  443.02
  5065.2  442.69  5178.4  444.63  5185.3  445.22  5206.7  445.34  5213.6  446.47
  5220.9  445.77  5227.8  447.02  5235.0  445.91  5241.9  445.77  5297.1  446.38
#Mann=3,-1,0
  4593.6    0.05       0  4992.4    0.04       0  4996.4    0.05       0
Bank Sta=4992.4,4996.4
Exp/Cntr=0.3,0.1

Type RM Length L Ch R = 1,3409,259,259,259
BEGIN DESCRIPTION:
Lacy 119 1442
END DESCRIPTION:
XS GIS Cut Line= 3
      2725727.01      6879540.42      2725467.22      6879276.73
      2725190.43      6878978.57
#Sta/Elev= 30
  4623.5  442.98  4722.8  443.37  4729.9  442.80  4765.2  442.28  4828.9  440.66
  4835.9  439.99  4850.1  439.59  4864.2  439.60  4871.3  440.16  4885.5  440.33
  4920.8  439.86  4927.9  440.08  4963.2  439.24  4977.3  439.56  4998.7  438.72
  5010.9  438.71  5011.2  438.21  5014.7  438.21  5014.9  438.71  5019.7  439.16
  5041.2  439.27  5062.2  439.90  5090.6  440.02  5111.6  440.67  5175.6  441.38
  5182.4  441.81  5253.3  442.84  5295.8  443.86  5331.0  445.26  5400.5  447.12
#Mann=3,-1,0
  4623.5    0.05       0  5010.9    0.04       0  5014.9    0.05       0
Bank Sta=5010.9,5014.9
Exp/Cntr=0.3,0.1

Type RM Length L Ch R = 1,3150,289,289,289
BEGIN DESCRIPTION:
Lacy 119 1441
END DESCRIPTION:
XS GIS Cut Line= 3
      2725921.35      6879386.94      2725618.67      6879074.62
      2725371.79      6878806.89
#Sta/Elev= 30
  4563.2  441.51  4592.4  441.28  4684.2  441.99  4733.9  441.81  4740.8  441.20
  4755.0  440.75  4868.2  438.66  4953.0  436.29  4960.2  435.80  4974.4  435.80
  4988.5  436.34  4998.1  435.13  5009.6  435.40  5016.6  434.51  5021.8  434.37
  5022.1  433.87  5025.6  433.87  5025.8  434.37  5030.6  435.16  5038.0  434.59
  5044.8  435.54  5052.2  435.09  5059.0  435.76  5066.3  435.66  5080.5  436.26
  5101.5  438.35  5115.7  438.41  5144.0  439.62  5321.0  443.21  5362.3  443.59
#Mann=3,-1,0
  4563.2    0.05       0  5021.8    0.04       0  5025.8    0.05       0
Bank Sta=5021.8,5025.8
Exp/Cntr=0.3,0.1

Type RM Length L Ch R = 1,2861,262,262,262
BEGIN DESCRIPTION:
Lacy 119 1440
END DESCRIPTION:
XS GIS Cut Line= 3
      2726061.86      6879182.42      2725803.08      6878875.45
      2725596.08      6878630.37
#Sta/Elev= 30
  4604.7  439.31  4609.6  438.59  4617.3  438.47  4623.9  437.53  4659.0  437.47
  4681.1  437.50  4687.6  438.05  4695.4  437.77  4701.9  438.63  4716.2  439.36
  4765.6  439.27  4808.5  437.63  4822.8  437.77  4829.3  437.18  4880.0  436.03
  4921.7  435.79  4958.0  434.52  5014.0  434.48  5034.0  433.33  5034.3  432.83
  5037.8  432.83  5038.0  433.33  5042.6  434.62  5064.4  434.18  5077.7  435.15
  5114.0  435.60  5170.0  438.01  5212.9  438.78  5270.1  438.65  5327.0  439.32
#Mann=3,-1,0
  4604.7    0.05       0  5034.0    0.04       0  5038.0    0.05       0
Bank Sta=5034,5038
Exp/Cntr=0.3,0.1

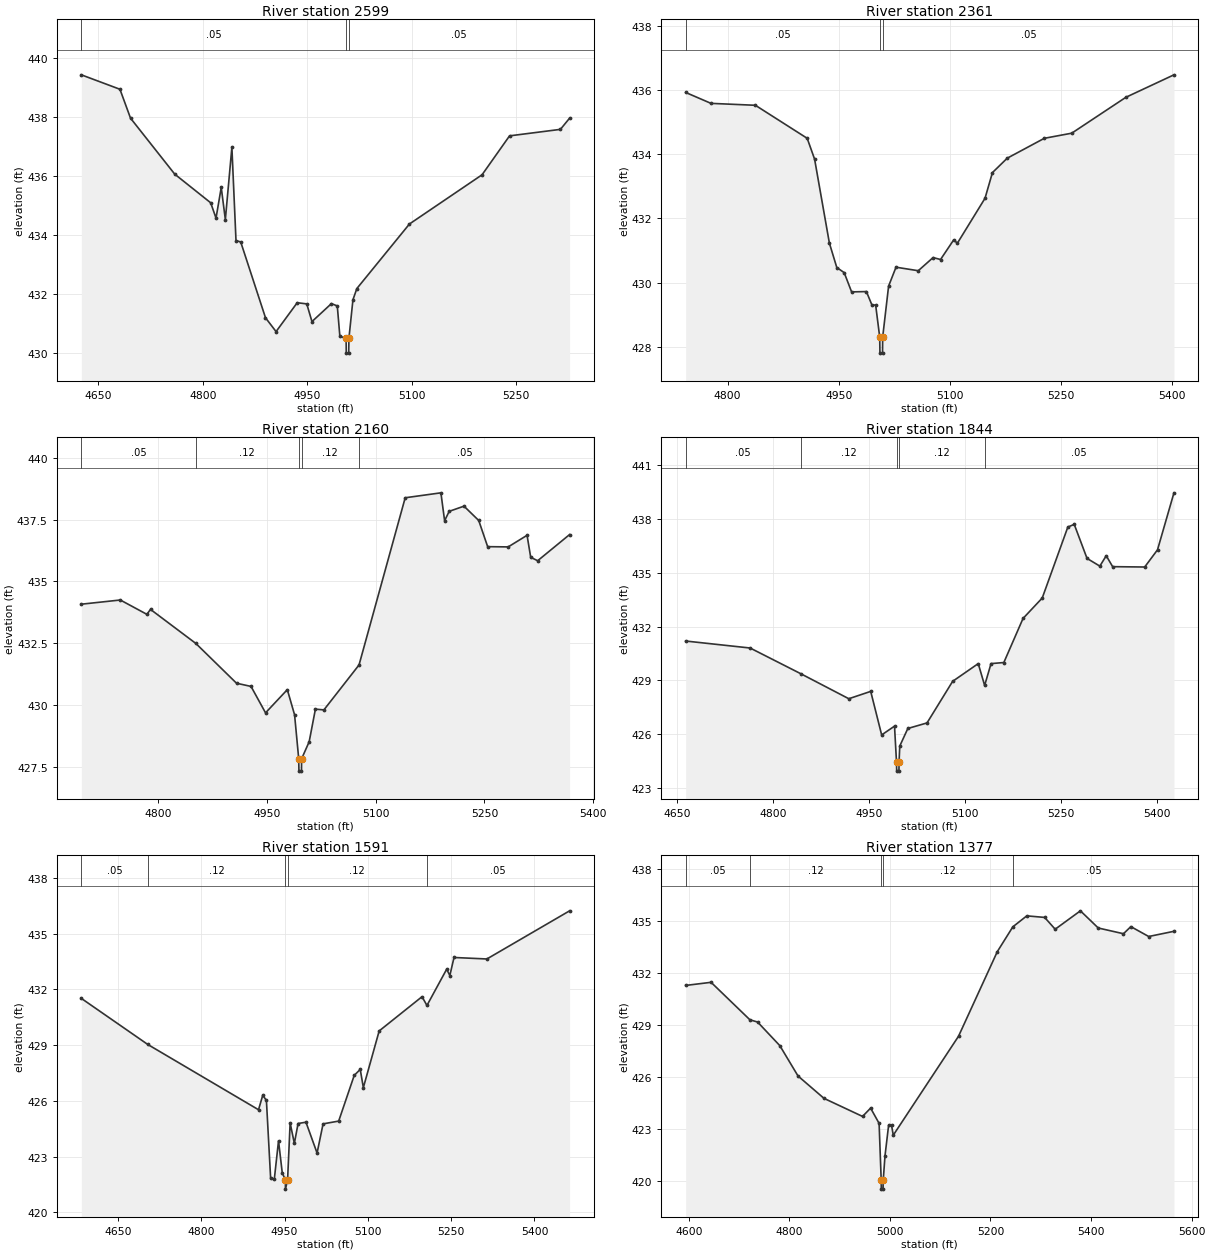
Type RM Length L Ch R = 1,2599,238,238,238
BEGIN DESCRIPTION:
Lacy 119 1439
END DESCRIPTION:
XS GIS Cut Line= 3
      2726259.35      6878894.80      2725944.87      6878694.77
      2725649.25      6878550.15
#Sta/Elev= 30
  4625.4  439.44  4680.9  438.95  4696.1  437.97  4759.7  436.07  4811.3  435.10
  4819.0  434.58  4826.5  435.62  4832.4  434.53  4841.8  436.98  4847.7  433.82
  4854.5  433.77  4890.1  431.20  4905.3  430.73  4935.7  431.71  4949.4  431.67
  4956.9  431.07  4984.9  431.68  4993.3  431.60  4997.0  430.57  5006.0  430.50
  5006.2  430.00  5009.7  430.00  5010.0  430.50  5015.8  431.81  5021.4  432.19
  5097.0  434.38  5201.4  436.05  5240.9  437.37  5314.0  437.59  5327.2  437.97
#Mann=3,-1,0
  4625.4    0.05       0  5006.0    0.04       0  5010.0    0.05       0
Bank Sta=5006,5010
Exp/Cntr=0.3,0.1

Type RM Length L Ch R = 1,2361,201,201,201
BEGIN DESCRIPTION:
Lacy 119 1435
END DESCRIPTION:
XS GIS Cut Line= 3
      2726380.15      6878557.14      2726126.04      6878552.97
      2725721.19      6878527.43
#Sta/Elev= 30
  4743.3  435.93  4777.5  435.59  4837.5  435.53  4907.5  434.50  4917.5  433.85
  4937.5  431.23  4947.5  430.47  4957.5  430.31  4967.5  429.71  4987.5  429.72
  4995.0  429.30  5000.0  429.30  5005.5  428.30  5005.8  427.80  5009.3  427.80
  5009.5  428.30  5017.5  429.89  5027.5  430.48  5057.6  430.37  5077.6  430.78
  5087.7  430.72  5105.4  431.33  5110.5  431.23  5147.8  432.63  5157.8  433.43
  5177.8  433.88  5227.9  434.50  5265.0  434.66  5338.2  435.78  5403.1  436.48
#Mann=3,-1,0
  4743.3    0.05       0  5005.5    0.05       0  5009.5    0.05       0
Bank Sta=5005.5,5009.5
Exp/Cntr=0.3,0.1

Type RM Length L Ch R = 1,2160,316,316,316
BEGIN DESCRIPTION:
Lacy 119 1434
END DESCRIPTION:
XS GIS Cut Line= 3
      2726429.74      6878374.38      2726125.55      6878379.75
      2725762.66      6878315.95
#Sta/Elev= 30
  4694.6  434.08  4748.3  434.25  4784.9  433.67  4789.9  433.87  4852.4  432.49
  4908.4  430.88  4928.4  430.75  4948.4  429.68  4978.4  430.62  4988.4  429.60
  4994.1  427.82  4994.4  427.32  4997.9  427.32  4998.1  427.82  5008.5  428.51
  5017.1  429.83  5028.8  429.80  5077.2  431.62  5140.8  438.39  5190.0  438.59
  5195.1  437.46  5201.4  437.84  5221.8  438.05  5242.1  437.47  5254.4  436.41
  5282.7  436.40  5308.7  436.87  5313.7  435.98  5323.3  435.84  5367.3  436.90
#Mann=5,-1,0
  4694.6    0.05       0  4852.4    0.12       0  4994.1    0.07       0
  4998.1    0.12       0  5077.2    0.05       0
Bank Sta=4994.1,4998.1
Exp/Cntr=0.3,0.1

Type RM Length L Ch R = 1,1844,253,253,253
BEGIN DESCRIPTION:
Lacy 119 1438
END DESCRIPTION:
XS GIS Cut Line= 3
      2726554.06      6878171.94      2726226.03      6878094.62
      2725800.27      6878084.65
#Sta/Elev= 30
  4663.1  431.19  4763.8  430.80  4842.7  429.37  4918.0  427.97  4952.2  428.38
  4969.3  425.95  4989.4  426.44  4992.5  424.43  4992.8  423.93  4996.3  423.93
  4996.5  424.43  4997.6  425.33  5010.2  426.31  5040.2  426.62  5080.2  428.94
  5120.2  429.93  5130.2  428.71  5140.2  429.93  5160.2  429.99  5190.2  432.45
  5220.2  433.59  5260.2  437.55  5270.2  437.70  5290.2  435.80  5310.2  435.37
  5320.2  435.95  5330.2  435.34  5380.3  435.32  5400.3  436.28  5426.0  439.46
#Mann=5,-1,0
  4663.1    0.05       0  4842.7    0.12       0  4992.5    0.07       0
  4996.5    0.12       0  5130.2    0.05       0
Bank Sta=4992.5,4996.5
Exp/Cntr=0.3,0.1

Type RM Length L Ch R = 1,1591,214,214,214
BEGIN DESCRIPTION:
Lacy 119 1437
END DESCRIPTION:
XS GIS Cut Line= 3
      2726595.86      6878131.86      2726281.53      6877856.64
      2725870.63      6877647.17
#Sta/Elev= 30
  4584.2  431.51  4703.9  429.03  4903.2  425.52  4910.8  426.30  4917.4  426.02
  4925.0  421.83  4931.6  421.78  4939.2  423.85  4945.9  422.13  4951.5  421.75
  4951.7  421.25  4955.5  421.75  4960.1  424.81  4967.7  423.71  4974.4  424.78
  4988.6  424.85  5008.6  423.19  5019.4  424.76  5047.5  424.91  5075.5  427.37
  5086.3  427.69  5091.9  426.71  5120.4  429.76  5197.5  431.60  5206.4  431.13
  5241.9  433.08  5247.6  432.74  5255.1  433.71  5314.3  433.63  5463.2  436.22
#Mann=5,-1,0
  4584.2    0.05       0  4703.9    0.12       0  4951.5    0.07       0
  4955.5    0.12       0  5206.4    0.05       0
Bank Sta=4951.5,4955.5
Exp/Cntr=0.3,0.1

Type RM Length L Ch R = 1,1377,141,141,141
BEGIN DESCRIPTION:
Lacy 119 1436
END DESCRIPTION:
XS GIS Cut Line= 3
      2726631.93      6878141.62      2726465.08      6877771.65
      2726131.01      6877315.94
#Sta/Elev= 30
  4593.9  431.29  4644.4  431.47  4721.6  429.31  4736.9  429.18  4781.1  427.82
  4817.3  426.07  4869.0  424.78  4945.6  423.74  4961.6  424.22  4978.5  423.34
  4982.7  420.05  4982.9  419.55  4986.4  419.55  4986.7  420.05  4990.2  421.46
  4997.4  423.23  5003.2  423.23  5006.7  422.66  5136.4  428.36  5213.6  433.24
  5244.5  434.67  5272.2  435.30  5307.7  435.21  5328.6  434.53  5378.8  435.59
  5414.3  434.60  5464.4  434.27  5479.1  434.68  5514.6  434.11  5564.8  434.41
#Mann=5,-1,0
  4593.9    0.05       0  4721.6    0.12       0  4982.7    0.07       0
  4986.7    0.12       0  5244.5    0.05       0
Bank Sta=4982.7,4986.7
Exp/Cntr=0.3,0.1

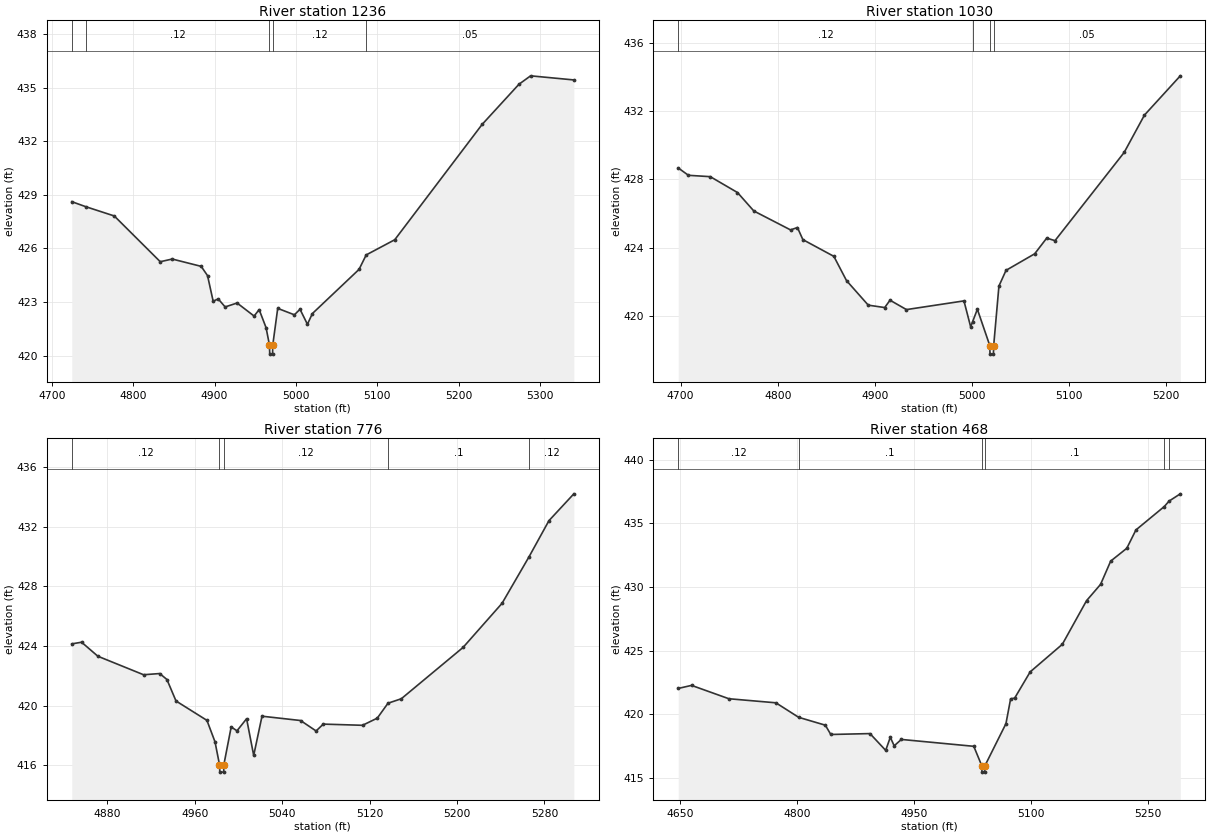
Type RM Length L Ch R = 1,1236,206,206,206
BEGIN DESCRIPTION:
Lacy 119 1446
END DESCRIPTION:
XS GIS Cut Line= 3
      2726742.90      6877926.39      2726582.05      6877702.84
      2726396.21      6877416.45
#Sta/Elev= 30
  4724.6  428.62  4741.7  428.34  4776.8  427.82  4833.3  425.26  4848.0  425.41
  4883.6  425.00  4891.4  424.48  4898.3  423.05  4904.5  423.18  4913.0  422.73
  4927.7  422.95  4948.6  422.22  4954.8  422.58  4963.3  421.57  4967.5  420.59
  4967.8  420.09  4971.3  420.09  4971.5  420.59  4977.6  422.65  4998.1  422.29
  5005.0  422.60  5014.1  421.76  5020.2  422.36  5077.5  424.83  5086.3  425.64
  5121.4  426.49  5228.7  432.94  5274.0  435.19  5288.3  435.66  5341.4  435.43
#Mann=5,-1,0
  4724.6    0.05       0  4741.7    0.12       0  4967.5    0.07       0
  4971.5    0.12       0  5086.3    0.05       0
Bank Sta=4967.5,4971.5
Exp/Cntr=0.3,0.1

Type RM Length L Ch R = 1,1030,254,254,254
BEGIN DESCRIPTION:
Lacy 119 1445
END DESCRIPTION:
XS GIS Cut Line= 3
      2726866.07      6877834.61      2726732.05      6877563.53
      2726607.17      6877389.26
#Sta/Elev= 30
  4697.6  428.67  4708.1  428.24  4730.6  428.16  4758.6  427.23  4775.4  426.15
  4813.2  425.04  4820.3  425.18  4825.9  424.47  4857.8  423.49  4870.8  422.07
  4893.2  420.63  4910.1  420.49  4915.6  420.92  4932.5  420.37  4991.7  420.88
  4998.6  419.36  5000.6  419.66  5005.5  420.39  5018.3  418.26  5018.5  417.76
  5022.0  417.76  5022.3  418.26  5027.7  421.75  5035.0  422.67  5064.5  423.64
  5076.9  424.56  5085.4  424.41  5156.6  429.58  5177.5  431.77  5214.4  434.07
#Mann=4,-1,0
  4697.6    0.12       0  5000.6    0.05       0  5018.3    0.07       0
  5022.3    0.05       0
Bank Sta=5018.3,5022.3
Exp/Cntr=0.3,0.1

Type RM Length L Ch R = 1,776,308,308,308
BEGIN DESCRIPTION:
Lacy 119 1444
END DESCRIPTION:
XS GIS Cut Line= 3
      2727026.92      6877622.35      2726939.39      6877497.35
      2726740.25      6877263.83
#Sta/Elev= 30
  4847.4  424.15  4856.4  424.26  4871.3  423.32  4913.1  422.08  4927.9  422.16
  4934.5  421.76  4942.8  420.32  4971.1  419.02  4978.5  417.58  4982.6  416.05
  4982.9  415.55  4986.4  415.55  4986.6  416.05  4993.3  418.58  4998.6  418.32
  5007.4  419.13  5013.9  416.67  5021.5  419.30  5056.8  419.01  5071.0  418.31
  5077.6  418.77  5113.5  418.69  5127.0  419.17  5136.8  420.17  5149.0  420.47
  5205.5  423.91  5241.2  426.87  5265.9  429.99  5284.1  432.41  5306.9  434.21
#Mann=5,-1,0
  4847.4    0.12       0  4982.6    0.07       0  4986.6    0.12       0
  5136.8     0.1       0  5265.9    0.12       0
Bank Sta=4982.6,4986.6
Exp/Cntr=0.3,0.1

Type RM Length L Ch R = 1,468,0,0,0
BEGIN DESCRIPTION:
Lacy 119 1443
END DESCRIPTION:
XS GIS Cut Line= 3
      2727072.68      6877605.57      2727031.76      6877255.15
      2726749.59      6877180.44
#Sta/Elev= 30
  4647.2  422.03  4664.3  422.27  4712.2  421.22  4772.6  420.90  4801.8  419.76
  4836.1  419.14  4843.1  418.41  4893.4  418.48  4913.6  417.16  4919.5  418.19
  4924.5  417.52  4933.7  418.02  5026.7  417.48  5037.0  415.95  5037.2  415.45
  5040.7  415.45  5041.0  415.95  5068.0  419.26  5074.0  421.21  5079.2  421.27
  5099.1  423.33  5140.4  425.50  5171.5  428.93  5189.5  430.21  5202.5  432.04
  5223.2  433.05  5234.9  434.49  5271.3  436.33  5277.5  436.76  5291.9  437.33
#Mann=6,-1,0
  4647.2    0.12       0  4801.8     0.1       0  5037.0    0.07       0
  5041.0     0.1       0  5271.3    0.12       0  5277.5    0.05       0
Bank Sta=5037,5041
Exp/Cntr=0.3,0.1

Chan Stop Cuts=-1