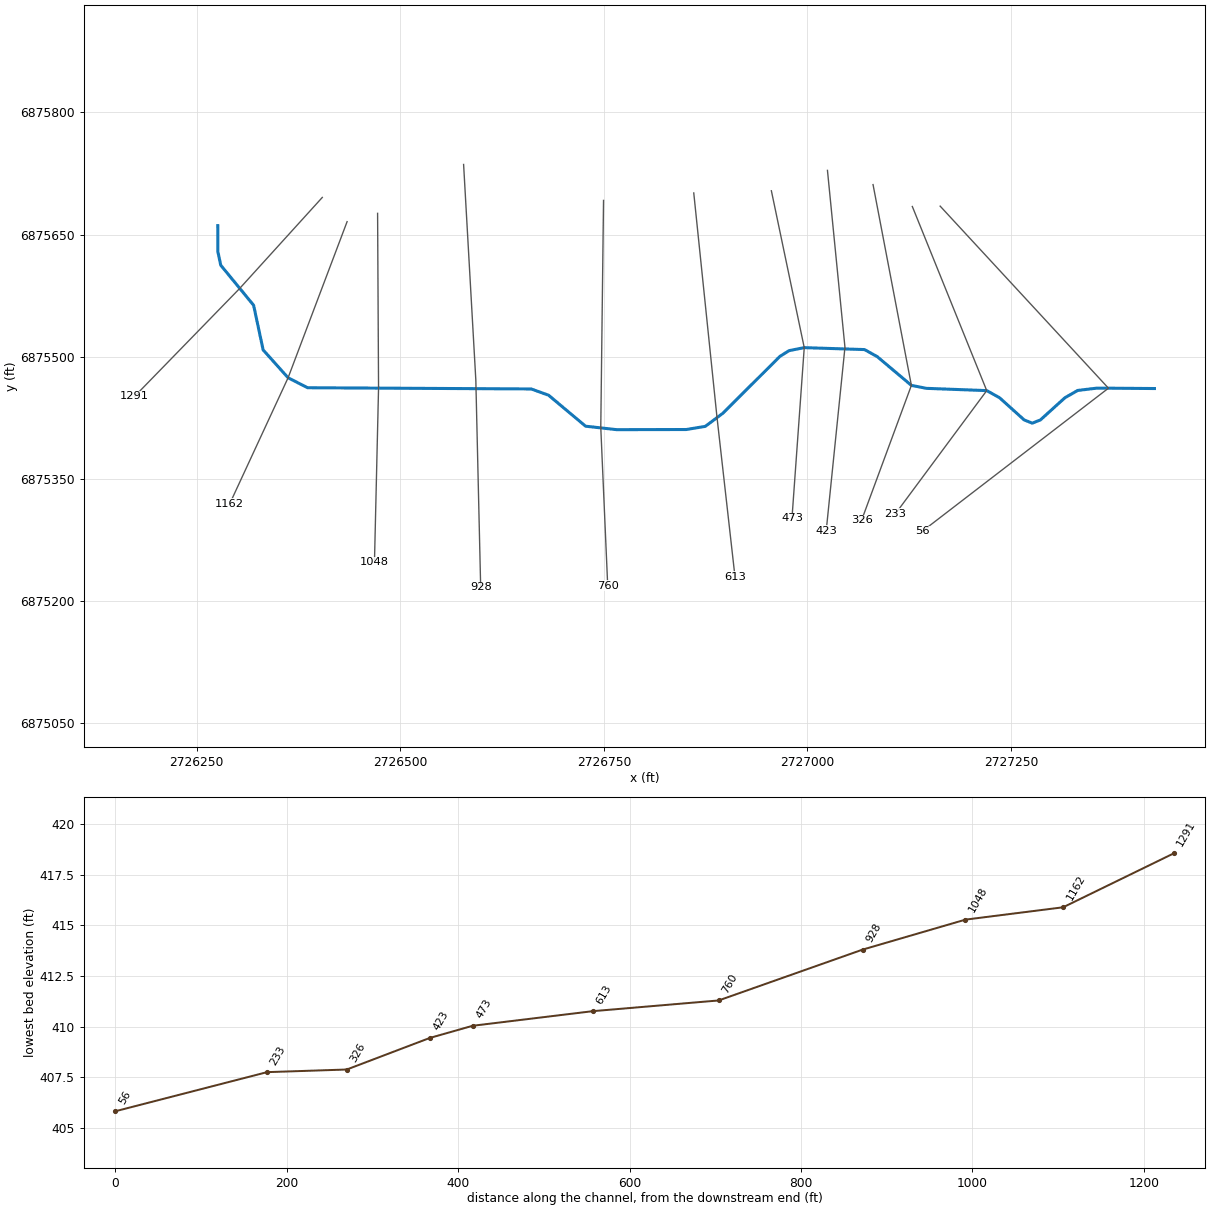
--- Lacy 120.prj (project) ---

Proj Title=Lacy 120 Base Level Engineering
Current Plan=p01
Default Exp/Contr=0.3,0.1
English Units
Geom File=g01
Flow File=f01
Plan File=p01
Y Axis Title=Elevation
X Axis Title(PF)=Main Channel Distance
X Axis Title(XS)=Station
BEGIN DESCRIPTION:
Lacy 120
END DESCRIPTION:
DSS Export Rating Curves= 0
DSS Export Rating Curve Sorted= 0
DSS Export Volume Flow Curves= 0
DXF OffsetX= 0
DXF OffsetY= 0
DXF ScaleX= 1
DXF ScaleY= 10

--- Lacy 120.p01 (plan) ---

Plan Title=Multiple Run
Short Identifier=Multiple
Geom File=g01
Flow File=f01
Subcritical Flow
K Sum by GR= 0
Std Step Tol= 0.01
Critical Tol= 0.01
Num of Std Step Trials= 20
Max Error Tol= 0.3
Flow Tol Ratio= 0.001
Split Flow NTrial= 30
Split Flow Tol= 0.02
Split Flow Ratio= 0.02
Log Output Level= 0
Friction Slope Method= 1
Unsteady Friction Slope Method= 2
Unsteady Bridges Friction Slope Method= 1
Parabolic Critical Depth
Global Vel Dist=  1 , 1 , 1
Global Log Level= 0
CheckData=True
Encroach Param= -1, 0, 0, 0
BEGIN DESCRIPTION:
Multiple Run
END DESCRIPTION:

--- Lacy 120.f01 (steady flow) ---

Flow Title=Multiple
Number of Profiles=7
Profile Names=10-year,25-year,50-year,1pct_min,100-year,1pct_plu,500-year
River Rch & RM= Lacy 120,Reach-1,1291
     162     198     224     127     253     505     320
Boundary for River Rch & Prof#=Lacy 120,Reach-1,1
Up Type=0
Dn Type=3
Dn Slope=0.005
Boundary for River Rch & Prof#=Lacy 120,Reach-1,2
Up Type=0
Dn Type=3
Dn Slope=0.005
Boundary for River Rch & Prof#=Lacy 120,Reach-1,3
Up Type=0
Dn Type=3
Dn Slope=0.005
Boundary for River Rch & Prof#=Lacy 120,Reach-1,4
Up Type=0
Dn Type=3
Dn Slope=0.005
Boundary for River Rch & Prof#=Lacy 120,Reach-1,5
Up Type=0
Dn Type=3
Dn Slope=0.005
Boundary for River Rch & Prof#=Lacy 120,Reach-1,6
Up Type=0
Dn Type=3
Dn Slope=0.005
Boundary for River Rch & Prof#=Lacy 120,Reach-1,7
Up Type=0
Dn Type=3
Dn Slope=0.005

--- Lacy 120.g01 (geometry) ---

Geom Title=Existing Conditions
Program Version=4.10

River Reach=Lacy 120        ,Reach-1
Reach XY= 30
        2726276.        6875661.       2726276.1      6875629.19
       2726279.6      6875612.49      2726320.01      6875563.21
      2726331.69       6875508.4      2726362.33      6875474.22
      2726386.28      6875461.98      2726660.78      6875460.48
      2726682.06      6875452.86      2726727.57      6875414.77
      2726765.83       6875410.5      2726851.11      6875410.68
      2726874.53      6875414.54      2726896.14      6875430.65
      2726966.22      6875500.54       2726977.5      6875507.53
      2726996.05      6875511.21      2727070.02      6875508.84
      2727085.63      6875500.19       2727127.6      6875464.86
       2727146.1      6875461.23      2727220.11      6875458.45
      2727235.78      6875449.75       2727266.1      6875422.45
      2727276.01      6875418.51      2727285.91      6875422.39
      2727316.19      6875449.74      2727331.77      6875458.66
       2727355.7      6875461.53        2727426.        6875461.

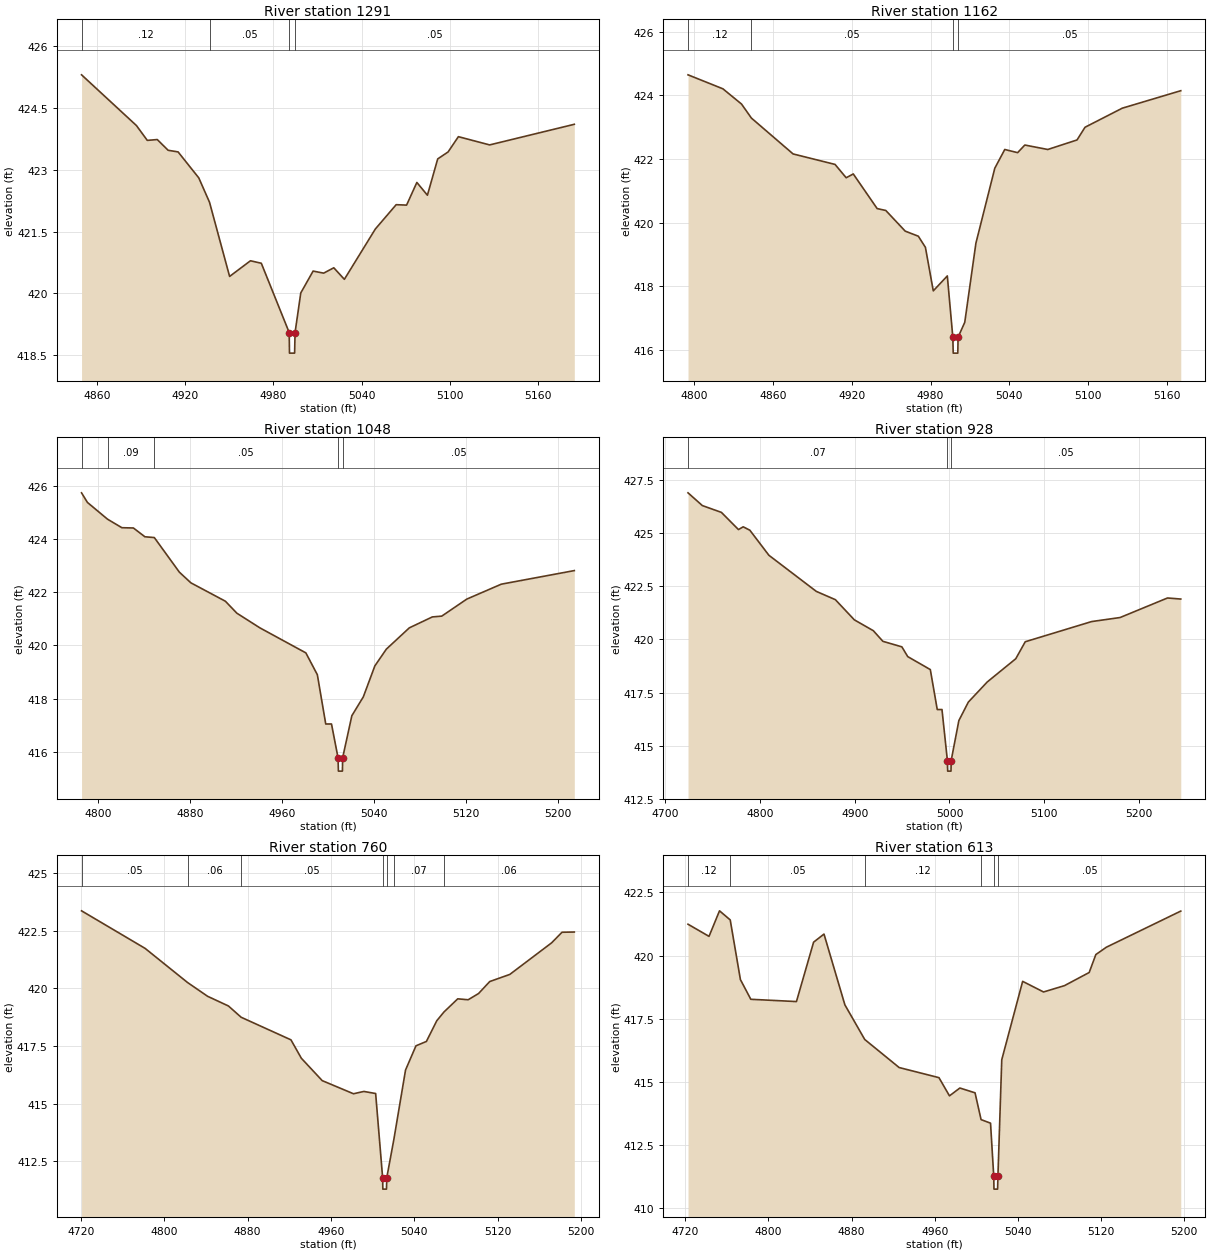
Type RM Length L Ch R = 1 ,1291    ,129,129,129
BEGIN DESCRIPTION:
Lacy 120 1419
END DESCRIPTION:
XS GIS Cut Line= 3
      2726404.33      6875695.64      2726302.98      6875583.98
      2726173.94      6875451.42
#Sta/Elev= 30
  4849.2   425.3  4886.6  424.07    4894  423.71  4900.8  423.73  4908.2  423.47
    4915  423.43  4929.1   422.8  4936.4  422.21  4950.1  420.41  4964.3  420.79
  4971.7  420.73  4990.7  419.05  4990.9  418.55  4994.4  418.55  4994.7  419.05
  4998.6  420.01    5007  420.54  5014.2  420.49  5021.1  420.62  5028.3  420.34
  5049.4  421.56  5063.6  422.15  5070.7  422.14  5077.7  422.69  5084.9  422.38
  5091.9  423.26    5099  423.43    5106   423.8  5127.3   423.6    5185   424.1
#Mann= 4 ,-1 , 0
  4849.2     .12       0  4936.4     .05       0  4990.7     .04       0
  4994.7     .05       0
Bank Sta=4990.7,4994.7
XS Rating Curve= 0 ,0
Exp/Cntr=0.3,0.1

Type RM Length L Ch R = 1 ,1162    ,114,114,114
BEGIN DESCRIPTION:
Lacy 120 1418
END DESCRIPTION:
XS GIS Cut Line= 3
      2726434.77      6875665.89      2726362.33      6875474.22
      2726290.55      6875319.24
#Sta/Elev= 30
  4795.1  424.65  4821.7  424.21  4835.9  423.73  4843.4  423.29  4875.2  422.16
  4907.2  421.83  4915.7  421.41  4921.1  421.53  4939.3  420.44  4945.9  420.38
  4960.7  419.73  4970.7  419.57  4976.1  419.22  4982.1  417.85  4992.8  418.32
    4997  416.39  4997.3  415.89  5000.8  415.89    5001  416.39  5006.1  416.86
  5014.6  419.35    5029  421.71  5036.6   422.3  5046.4   422.2  5051.9  422.44
  5069.4   422.3  5091.7   422.6  5097.8     423  5126.2   423.6  5170.8  424.15
#Mann= 4 ,-1 , 0
  4795.1     .12       0  4843.4     .05       0    4997     .04       0
    5001     .05       0
Bank Sta=4997,5001
XS Rating Curve= 0 ,0
Exp/Cntr=0.3,0.1

Type RM Length L Ch R = 1 ,1048    ,120,120,120
BEGIN DESCRIPTION:
Lacy 120 1417
END DESCRIPTION:
XS GIS Cut Line= 3
      2726472.22       6875676.1      2726473.39      6875461.51
      2726468.37      6875247.57
#Sta/Elev= 30
  4785.4  425.73  4790.5  425.37    4808  424.74  4820.5  424.42  4830.5  424.41
  4840.5  424.08  4848.7  424.05  4870.5  422.75  4880.5  422.35  4910.5  421.66
  4920.5  421.21  4940.5  420.66  4980.5  419.72  4990.5   418.9  4997.8  417.05
  5002.8  417.05  5008.5  415.78  5008.8  415.28  5012.3  415.28  5012.5  415.78
  5020.5  417.36  5030.5  418.07  5040.5  419.23  5050.5  419.86  5070.5  420.66
  5090.5  421.07  5098.7   421.1  5120.5  421.74  5150.5   422.3    5214  422.81
#Mann= 5 ,-1 , 0
  4785.4     .06       0    4808     .09       0  4848.7     .05       0
  5008.5     .05       0  5012.5     .05       0
Bank Sta=5008.5,5012.5
XS Rating Curve= 0 ,0
Exp/Cntr=0.3,0.1

Type RM Length L Ch R = 1 ,928     ,168,168,168
BEGIN DESCRIPTION:
Lacy 120 1414
END DESCRIPTION:
XS GIS Cut Line= 3
      2726577.82      6875736.12      2726592.82      6875471.49
      2726598.78      6875217.02
#Sta/Elev= 30
  4724.3   426.9  4739.4   426.3  4759.5  425.98  4777.5  425.17  4782.5   425.3
  4789.5  425.14  4809.6  423.96  4859.6  422.26  4879.7  421.87  4899.7  420.92
  4919.7  420.41  4929.8  419.91  4949.8  419.65    4956  419.19  4979.8  418.58
  4987.1   416.7  4992.1   416.7  4997.8   414.3  4998.1   413.8  5001.6   413.8
  5001.8   414.3  5009.9  416.18  5019.9  417.05  5039.9     418  5069.9  419.09
  5079.9  419.89  5149.9  420.84  5179.9  421.03  5229.9  421.95  5243.9   421.9
#Mann= 3 ,-1 , 0
  4724.3     .07       0  4997.8     .03       0  5001.8     .05       0
Bank Sta=4997.8,5001.8
XS Rating Curve= 0 ,0
Exp/Cntr=0.3,0.1

Type RM Length L Ch R = 1 ,760     ,147,147,147
BEGIN DESCRIPTION:
Lacy 120 1416
END DESCRIPTION:
XS GIS Cut Line= 3
      2726749.62      6875691.96      2726746.23      6875413.28
      2726754.74      6875219.17
#Sta/Elev= 30
  4720.7  423.37  4781.7  421.74  4822.4  420.26  4841.7  419.66  4861.7  419.24
  4873.9  418.75  4921.7  417.77  4931.7  416.97  4951.7     416  4981.7  415.43
  4991.7  415.53    5003  415.44  5009.7  411.79  5009.9  411.29  5013.4  411.29
  5013.7  411.79  5020.5  413.45  5031.7  416.46  5041.7  417.51  5051.7   417.7
  5061.7   418.6  5068.6  418.98  5081.8  419.55  5091.8  419.51  5101.8  419.78
  5112.5   420.3  5131.8  420.61  5171.9  421.98  5181.9  422.44  5193.7  422.45
#Mann= 7 ,-1 , 0
  4720.7     .05       0  4822.4     .06       0  4873.9     .05       0
  5009.7     .04       0  5013.7     .05       0  5020.5     .07       0
  5068.6     .06       0
Bank Sta=5009.7,5013.7
XS Rating Curve= 0 ,0
Exp/Cntr=0.3,0.1

Type RM Length L Ch R = 1 ,613     ,140,140,140
BEGIN DESCRIPTION:
Lacy 120 1415
END DESCRIPTION:
XS GIS Cut Line= 3
       2726860.4      6875701.13      2726888.84      6875426.47
      2726911.03      6875229.84
#Sta/Elev= 30
  4722.7  421.24  4742.9  420.76    4753  421.77  4763.3  421.41  4773.1  419.05
  4783.1  418.27    4827  418.18  4843.5  420.53  4853.5  420.85  4873.6  418.05
  4892.7  416.68  4925.8  415.57  4964.1  415.17  4974.2  414.45  4984.2  414.76
  4998.8  414.57  5004.6  413.51  5013.7  413.37  5016.8  411.26    5017  410.76
  5020.5  410.76  5020.8  411.26  5024.5  415.88  5044.6  418.98  5064.7  418.56
  5084.8  418.81  5108.6  419.33    5115  420.04  5125.1  420.33  5196.7  421.76
#Mann= 6 ,-1 , 0
  4722.7     .12       0  4763.3     .05       0  4892.7     .12       0
  5004.6     .05       0  5016.8     .07       0  5020.8     .05       0
Bank Sta=5016.8,5020.8
XS Rating Curve= 0 ,0
Exp/Cntr=0.3,0.1

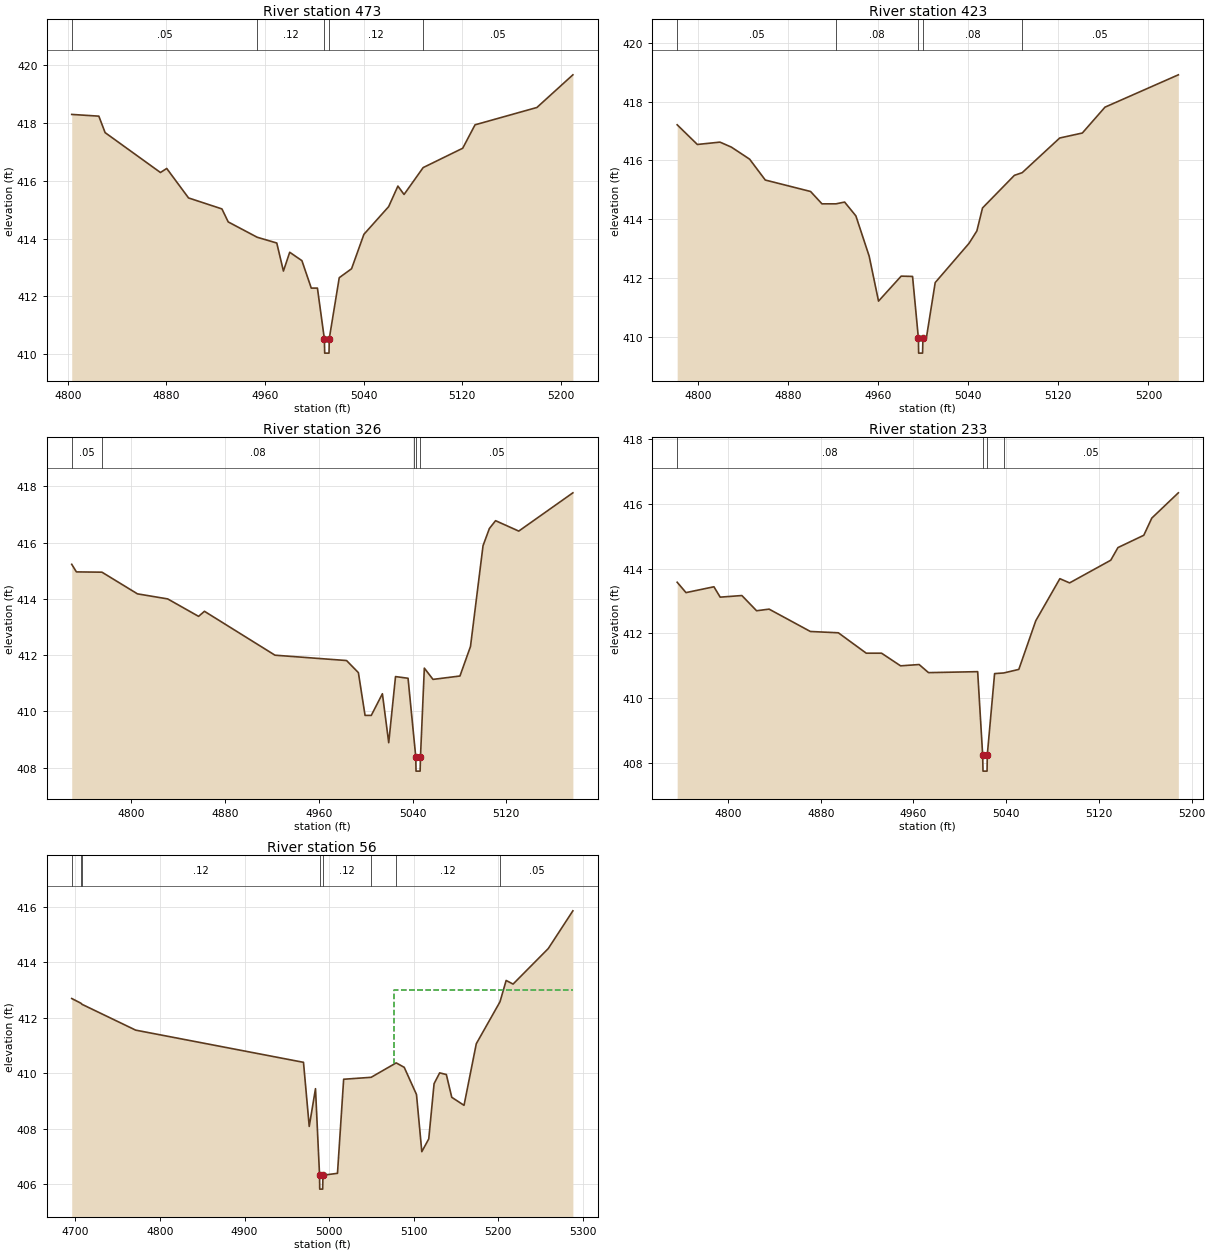
Type RM Length L Ch R = 1 ,473     ,50,50,50
BEGIN DESCRIPTION:
Lacy 120 1420
END DESCRIPTION:
XS GIS Cut Line= 3
      2726955.69      6875703.82      2726996.05      6875511.21
      2726980.99      6875301.85
#Sta/Elev= 30
  4803.2   418.3  4825.2  418.24  4830.3  417.67  4875.2  416.29  4880.3  416.43
    4898  415.41  4925.1  415.03  4930.2  414.58  4953.7  414.05  4969.6  413.85
    4975  412.88  4980.1  413.53    4990  413.24  4997.6  412.29  5002.6  412.29
  5008.2  410.54  5008.5  410.04    5012  410.04  5012.2  410.54  5020.3  412.65
  5030.3  412.96  5040.3  414.15  5060.4  415.11  5067.9  415.82  5072.9  415.53
  5088.4  416.46  5120.5  417.13  5130.5  417.94  5180.7  418.54  5209.9  419.67
#Mann= 5 ,-1 , 0
  4803.2     .05       0  4953.7     .12       0  5008.2     .07       0
  5012.2     .12       0  5088.4     .05       0
Bank Sta=5008.2,5012.2
XS Rating Curve= 0 ,0
Exp/Cntr=0.3,0.1

Type RM Length L Ch R = 1 ,423     ,97,97,97
BEGIN DESCRIPTION:
Lacy 120 1423
END DESCRIPTION:
XS GIS Cut Line= 3
      2727024.55      6875728.85      2727046.04      6875511.61
      2727023.01      6875286.28
#Sta/Elev= 30
  4781.7  417.21  4799.6  416.54  4819.7  416.62  4829.8  416.45    4846  416.04
  4859.9  415.33  4900.1  414.94  4910.2  414.52  4922.6  414.52  4930.3  414.58
  4940.3  414.11  4952.1  412.74  4960.4  411.21  4980.5  412.06  4990.6  412.05
  4995.8  409.94    4996  409.44  4999.5  409.44  4999.8  409.94  5002.8  409.94
  5010.7  411.84  5040.8  413.18  5047.7   413.6  5052.7  414.38    5081  415.49
  5087.9  415.58  5121.2  416.76  5141.3  416.93  5161.4  417.81  5226.5  418.91
#Mann= 5 ,-1 , 0
  4781.7     .05       0  4922.6     .08       0  4995.8     .07       0
  4999.8     .08       0  5087.9     .05       0
Bank Sta=4995.8,4999.8
XS Rating Curve= 0 ,0
Exp/Cntr=0.3,0.1

Type RM Length L Ch R = 1 ,326     ,93,93,93
BEGIN DESCRIPTION:
Lacy 120 1422
END DESCRIPTION:
XS GIS Cut Line= 3
      2727080.52       6875711.4       2727127.6      6875464.86
      2727066.35        6875299.
#Sta/Elev= 30
    4749  415.23    4753  414.96  4774.8  414.95  4805.1  414.18  4830.9     414
  4857.3  413.38  4862.3  413.56  4922.5     412  4983.6  411.81  4993.7  411.38
  4999.4  409.86  5004.7  409.86  5014.2  410.63  5019.6  408.89  5025.4  411.24
  5036.1  411.18  5041.4  408.93  5042.7  408.38  5042.9  407.88  5046.4  407.88
  5046.7  408.38    5050  411.54  5057.4  411.14  5080.4  411.26  5089.4  412.31
  5100.1  415.89  5105.5   416.5  5110.8  416.78  5130.6  416.41  5176.8  417.77
#Mann= 5 ,-1 , 0
    4749     .05       0  4774.8     .08       0  5041.4     .05       0
  5042.7     .07       0  5046.7     .05       0
Bank Sta=5042.7,5046.7
XS Rating Curve= 0 ,0
Exp/Cntr=0.3,0.1

Type RM Length L Ch R = 1 ,233     ,177,177,177
BEGIN DESCRIPTION:
Lacy 120 1421
END DESCRIPTION:
XS GIS Cut Line= 3
      2727128.76      6875684.49      2727220.11      6875458.45
      2727107.84      6875307.03
#Sta/Elev= 30
  4756.2  413.58  4763.8  413.26  4787.9  413.44  4793.3  413.12    4812  413.17
  4824.7   412.7  4835.5  412.75  4871.1  412.06  4895.2  412.02  4919.3  411.39
  4932.5  411.39  4948.9     411  4964.9  411.04    4973  410.79  5015.4  410.82
  5019.7  408.25    5020  407.75  5023.5  407.75  5023.7  408.25    5030  410.76
  5037.9  410.78  5050.9  410.89  5065.5  412.39  5086.3  413.69  5094.7  413.56
  5130.2  414.26  5136.4  414.65  5158.7  415.03  5165.6  415.56  5188.5  416.34
#Mann= 4 ,-1 , 0
  4756.2     .08       0  5019.7     .07       0  5023.7     .08       0
  5037.9     .05       0
Bank Sta=5019.7,5023.7
XS Rating Curve= 0 ,0
Exp/Cntr=0.3,0.1

Type RM Length L Ch R = 1 ,56      ,0,0,0
BEGIN DESCRIPTION:
Lacy 120 3480
END DESCRIPTION:
XS GIS Cut Line= 3
      2727162.92      6875684.96      2727369.55      6875461.43
      2727141.13      6875285.86
#Sta/Elev= 30
  4695.6  412.69  4706.5  412.52  4707.8  412.48  4771.2  411.55  4969.6  410.39
  4976.4  408.08  4983.8  409.44  4988.6  406.32  4988.8  405.82  4992.3  405.82
  4992.6  406.32  5009.8  406.39  5017.1  409.78  5049.6  409.85  5079.2  410.37
  5088.7  410.21  5103.2  409.23  5109.5  407.17  5117.7  407.63    5124  409.62
  5130.6  410.01  5138.5  409.95  5144.9  409.13  5159.4  408.84  5173.9  411.06
  5201.9  412.57  5209.2  413.34  5217.4  413.21    5259  414.49  5288.1  415.85
#Mann= 8 ,-1 , 0
  4695.6     .12       0  4706.5     .05       0  4707.8     .12       0
  4988.6     .07       0  4992.6     .12       0  5049.6      .1       0
  5079.2     .12       0  5201.9     .05       0
#XS Ineff= 2 , 0
       0                    5077       0     413
Permanent Ineff=
       F       F
Bank Sta=4988.6,4992.6
XS Rating Curve= 0 ,0
Exp/Cntr=0.3,0.1

Chan Stop Cuts=-1
Use User Specified Reach Order=0
Composite Channel Slope=5