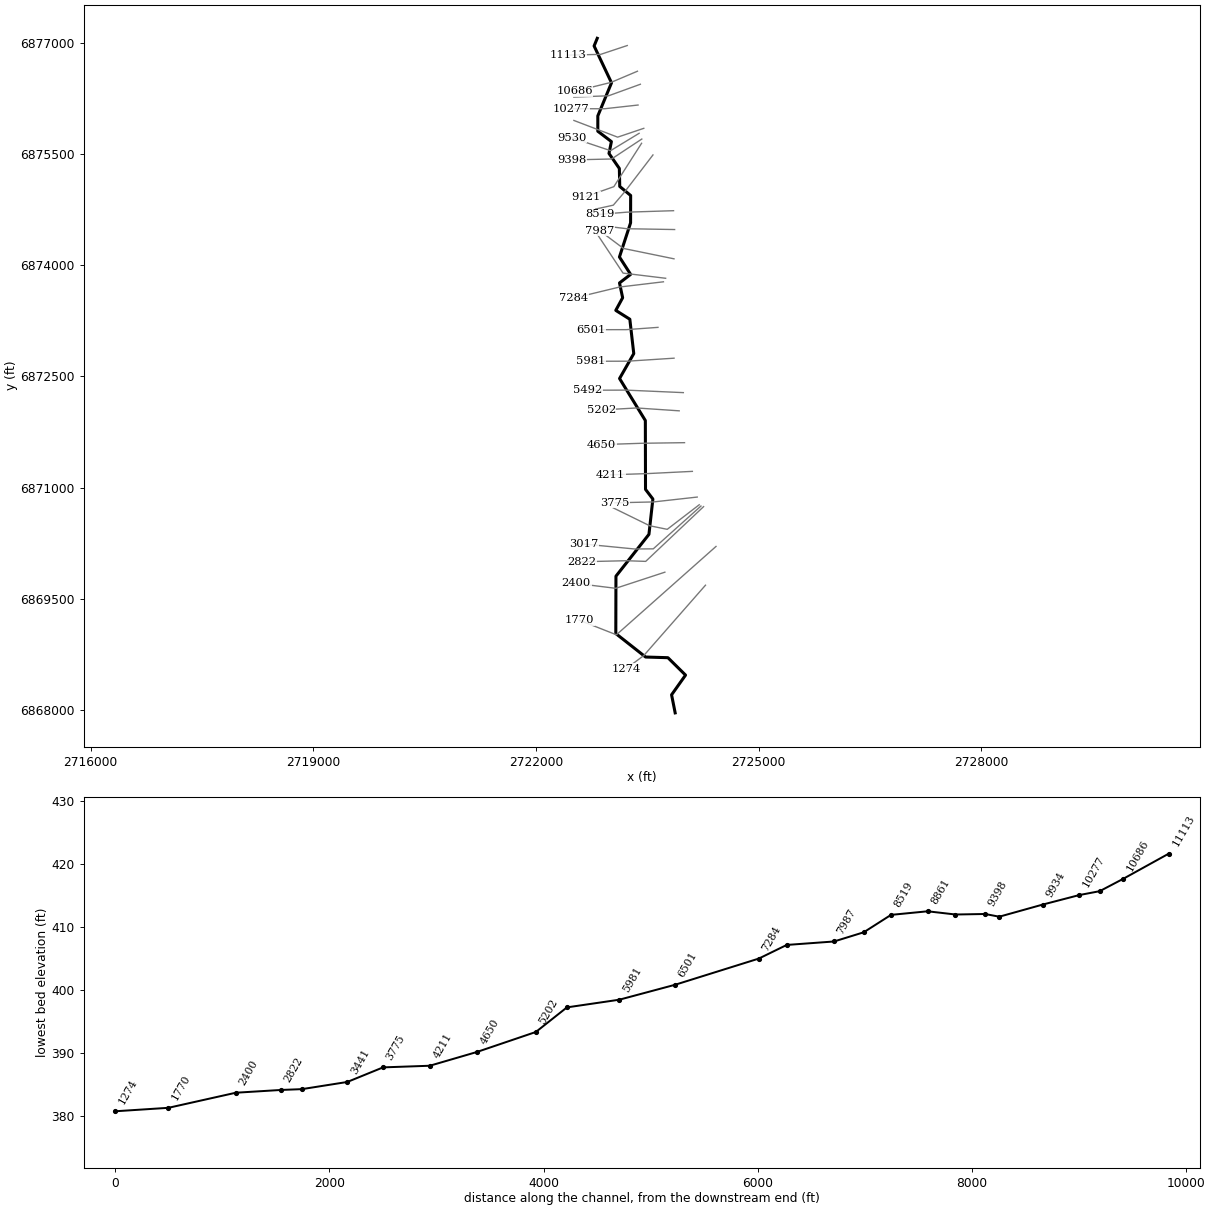
--- Lacy 121.prj (project) ---

Proj Title=Lacy 121 Base Level Engineering
Current Plan=p01
Default Exp/Contr=0.3,0.1
English Units
Geom File=g01
Flow File=f01
Plan File=p01
Y Axis Title=Elevation
X Axis Title(PF)=Main Channel Distance
X Axis Title(XS)=Station
BEGIN DESCRIPTION:
Lacy 121
END DESCRIPTION:
DSS Export Rating Curves= 0
DSS Export Rating Curve Sorted= 0
DSS Export Volume Flow Curves= 0
DXF OffsetX= 0
DXF OffsetY= 0
DXF ScaleX= 1
DXF ScaleY= 10

--- Lacy 121.p01 (plan) ---

Plan Title=Multiple Run
Short Identifier=Multiple
Geom File=g01
Flow File=f01
Subcritical Flow
K Sum by GR= 0
Std Step Tol= 0.01
Critical Tol= 0.01
Num of Std Step Trials= 20
Max Error Tol= 0.3
Flow Tol Ratio= 0.001
Split Flow NTrial= 30
Split Flow Tol= 0.02
Split Flow Ratio= 0.02
Log Output Level= 0
Friction Slope Method= 1
Unsteady Friction Slope Method= 2
Unsteady Bridges Friction Slope Method= 1
Parabolic Critical Depth
Global Vel Dist=  1 , 1 , 1
Global Log Level= 0
CheckData=True
Encroach Param= -1, 0, 0, 0
BEGIN DESCRIPTION:
Multiple Run
END DESCRIPTION:

--- Lacy 121.f01 (steady flow) ---

Flow Title=Multiple
Number of Profiles=7
Profile Names=10-year,25-year,50-year,1pct_min,100-year,1pct_plu,500-year
River Rch & RM= Lacy 121,Reach-1,11113
     446     582     689     405     808    1612    1109
River Rch & RM= Lacy 121,Reach-1,7284
     696     931    1120     668    1332    2658    1884
Boundary for River Rch & Prof#=Lacy 121,Reach-1,1
Up Type=0
Dn Type=3
Dn Slope=0.005
Boundary for River Rch & Prof#=Lacy 121,Reach-1,2
Up Type=0
Dn Type=3
Dn Slope=0.005
Boundary for River Rch & Prof#=Lacy 121,Reach-1,3
Up Type=0
Dn Type=3
Dn Slope=0.005
Boundary for River Rch & Prof#=Lacy 121,Reach-1,4
Up Type=0
Dn Type=3
Dn Slope=0.005
Boundary for River Rch & Prof#=Lacy 121,Reach-1,5
Up Type=0
Dn Type=3
Dn Slope=0.005
Boundary for River Rch & Prof#=Lacy 121,Reach-1,6
Up Type=0
Dn Type=3
Dn Slope=0.005
Boundary for River Rch & Prof#=Lacy 121,Reach-1,7
Up Type=0
Dn Type=3
Dn Slope=0.005

--- Lacy 121.g01 (geometry) ---

Geom Title=Existing Conditions
Program Version=4.10

River Reach=Lacy 121        ,Reach-1
Reach XY= 30
        2722826.        6877061.       2722783.6      6876957.62
      2723018.22       6876460.9      2722833.81      6876014.41
      2722833.69      6875807.33      2723016.72      6875667.68
      2722984.23      6875507.77      2723123.85       6875305.1
      2723129.15      6875062.64      2723276.12      6874940.74
      2723275.23      6874571.69      2723125.15      6874110.99
      2723275.87      6873876.22        2723126.        6873761.
      2723168.25      6873561.09       2723075.6      6873390.72
      2723265.06      6873271.43      2723318.17      6872807.58
       2723126.7       6872471.7      2723474.17      6871904.88
      2723476.37      6870976.17      2723575.75      6870845.78
       2723522.6      6870369.44      2723078.06      6869805.14
      2723076.05      6869031.19      2723477.46      6868714.54
      2723778.45      6868705.54      2724015.83      6868470.68
      2723827.62      6868204.97        2723876.        6867961.

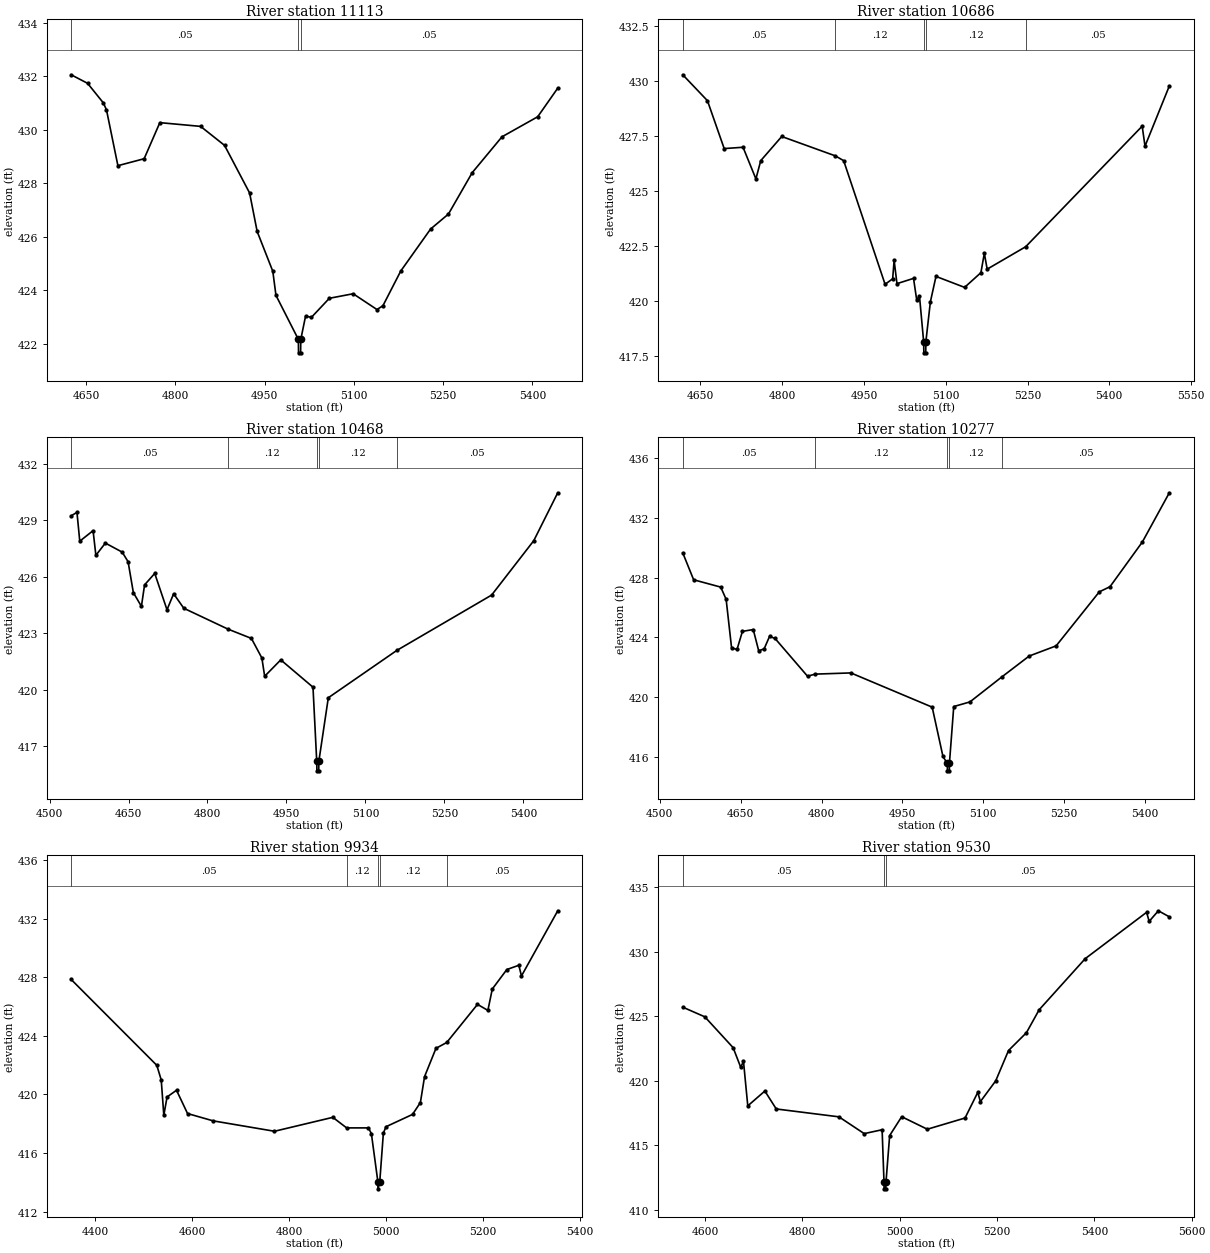
Type RM Length L Ch R = 1 ,11113   ,427,427,427
BEGIN DESCRIPTION:
Lacy 121 1390
END DESCRIPTION:
XS GIS Cut Line= 3
      2723230.49      6876963.64      2722872.32      6876844.47
      2722432.31      6876834.22
#Sta/Elev= 30
  4625.1  432.06  4652.7  431.74  4679.1  431.01  4684.4  430.75  4703.6  428.66
  4747.7  428.92  4774.1  430.27  4842.6  430.13  4882.8  429.42  4924.9  427.64
  4937.6   426.2  4963.9  424.71  4969.2  423.81  5006.9  422.16  5007.1  421.66
  5010.6  421.66  5010.9  422.16  5018.9  423.03  5028.9  422.99  5058.9   423.7
  5098.9  423.87  5138.9  423.28  5148.9  423.42  5178.9  424.72    5229  426.29
    5259  426.85    5299   428.4    5349  429.74    5409  430.49  5442.7  431.56
#Mann= 3 ,-1 , 0
  4625.1     .05       0  5006.9     .04       0  5010.9     .05       0
Bank Sta=5006.9,5010.9
XS Rating Curve= 0 ,0
Exp/Cntr=0.3,0.1

Type RM Length L Ch R = 1 ,10686   ,218,218,218
BEGIN DESCRIPTION:
Lacy 121 1391
END DESCRIPTION:
XS GIS Cut Line= 3
      2723367.75      6876617.04      2723013.19      6876466.76
      2722520.51      6876344.56
#Sta/Elev= 30
  4617.5   430.3  4662.8  429.12  4693.5  426.94  4728.1     427  4751.7  425.56
  4760.6  426.39  4799.1  427.49  4897.2  426.61  4912.7  426.39  4988.7  420.76
  5002.6  421.01  5005.3  421.85  5010.5  420.79  5040.9  421.03  5046.7  420.05
  5051.8  420.23  5059.5  418.14  5059.8  417.64  5063.3  417.64  5063.5  418.14
  5071.8  419.96  5082.1  421.12  5134.6  420.62  5164.5  421.29  5170.8  422.17
    5176  421.45  5246.6  422.47  5460.4  427.96  5465.6  427.05  5510.2  429.79
#Mann= 5 ,-1 , 0
  4617.5     .05       0  4897.2     .12       0  5059.5     .07       0
  5063.5     .12       0  5246.6     .05       0
Bank Sta=5059.5,5063.5
XS Rating Curve= 0 ,0
Exp/Cntr=0.3,0.1

Type RM Length L Ch R = 1 ,10468   ,191,191,191
BEGIN DESCRIPTION:
Lacy 121 1392
END DESCRIPTION:
XS GIS Cut Line= 3
      2723407.03       6876441.3      2722979.25      6876285.87
      2722510.54      6876268.03
#Sta/Elev= 30
  4541.1  429.23  4552.1  429.41  4557.4  427.88  4582.7  428.44    4588  427.13
    4606  427.78    4638   427.3  4649.2  426.79  4659.2  425.15  4674.5  424.42
  4680.5  425.56  4699.8  426.17  4723.1  424.24  4735.7  425.09    4755  424.32
  4839.2  423.21  4883.4  422.72  4903.3  421.68  4908.6  420.71  4939.2  421.58
  5000.4  420.13  5007.5  416.19  5007.8  415.69  5011.3  415.69  5011.5  416.19
  5029.5  419.57  5159.5  422.08  5339.7  425.02  5419.8  427.91  5465.3  430.45
#Mann= 5 ,-1 , 0
  4541.1     .05       0  4839.2     .12       0  5007.5     .07       0
  5011.5     .12       0  5159.5     .05       0
Bank Sta=5007.5,5011.5
XS Rating Curve= 0 ,0
Exp/Cntr=0.3,0.1

Type RM Length L Ch R = 1 ,10277   ,343,343,343
BEGIN DESCRIPTION:
Lacy 121 49
END DESCRIPTION:
XS GIS Cut Line= 3
      2723376.04        6876161.        2722926.        6876111.
      2722476.01        6876111.
#Sta/Elev= 30
  4542.5  429.65  4562.7  427.85    4613  427.36    4623  426.54  4633.1  423.29
  4643.2  423.19  4653.2   424.4  4673.3  424.52  4683.4   423.1  4693.5  423.23
  4703.5  424.06  4713.6  423.93    4774   421.4  4788.3  421.54  4854.4  421.62
  5005.3  419.33  5025.3  416.03  5033.3  415.57  5033.6  415.07  5037.1  415.07
  5037.3  415.57  5045.3  419.37  5075.3  419.68  5134.1  421.34  5185.3  422.75
  5235.3  423.43  5315.3  427.04  5335.3  427.39  5395.3  430.38  5445.3  433.67
#Mann= 5 ,-1 , 0
  4542.5     .05       0  4788.3     .12       0  5033.3     .07       0
  5037.3     .12       0  5134.1     .05       0
Bank Sta=5033.3,5037.3
XS Rating Curve= 0 ,0
Exp/Cntr=0.3,0.1

Type RM Length L Ch R = 1 ,9934    ,404,404,404
BEGIN DESCRIPTION:
Lacy 121 1389
END DESCRIPTION:
XS GIS Cut Line= 3
      2723453.18      6875846.65      2723100.85      6875727.61
      2722511.53      6875952.87
#Sta/Elev= 30
  4351.1  427.84  4527.6  421.98  4536.7  420.98    4542  418.57  4548.7  419.82
  4568.2  420.28  4590.9  418.69  4643.7  418.19  4770.1  417.48  4890.3  418.43
  4918.8  417.71  4963.7  417.71  4969.8  417.32  4983.1  414.05  4983.4  413.55
  4987.1  414.05  4994.5  417.35  4999.9  417.79  5054.6  418.63  5070.8  419.44
  5079.4  421.21  5102.9  423.14  5125.1  423.54  5188.5  426.14  5209.9  425.73
    5219  427.19    5249  428.52  5273.7  428.81  5279.1  428.08  5353.9  432.53
#Mann= 5 ,-1 , 0
  4351.1     .05       0  4918.8     .12       0  4983.1     .07       0
  4987.1     .12       0  5125.1     .05       0
Bank Sta=4983.1,4987.1
XS Rating Curve= 0 ,0
Exp/Cntr=0.3,0.1

Type RM Length L Ch R = 1 ,9530    ,132,132,132
BEGIN DESCRIPTION:
Lacy 121 1388
END DESCRIPTION:
XS GIS Cut Line= 3
      2723390.17      6875779.36      2723005.31      6875545.28
      2722484.66      6875720.19
#Sta/Elev= 30
  4554.4  425.71  4599.8  424.96  4657.9  422.57  4673.4  421.06  4679.2   421.5
    4688  418.06  4723.1  419.21  4746.5  417.82  4875.3  417.21  4927.2  415.91
    4964  416.21  4967.9  412.13  4968.1  411.63  4971.6  411.63  4971.9  412.13
  4979.5  415.76  5004.2  417.22  5056.9  416.25  5134.4  417.12  5160.6  419.11
  5165.9  418.39  5197.4     420  5223.7  422.35  5260.5  423.73  5286.7  425.51
  5381.3  429.47  5507.4  433.06  5512.7  432.36  5531.6  433.18  5554.1  432.71
#Mann= 3 ,-1 , 0
  4554.4     .05       0  4967.9     .04       0  4971.9     .05       0
Bank Sta=4967.9,4971.9
XS Rating Curve= 0 ,0
Exp/Cntr=0.3,0.1

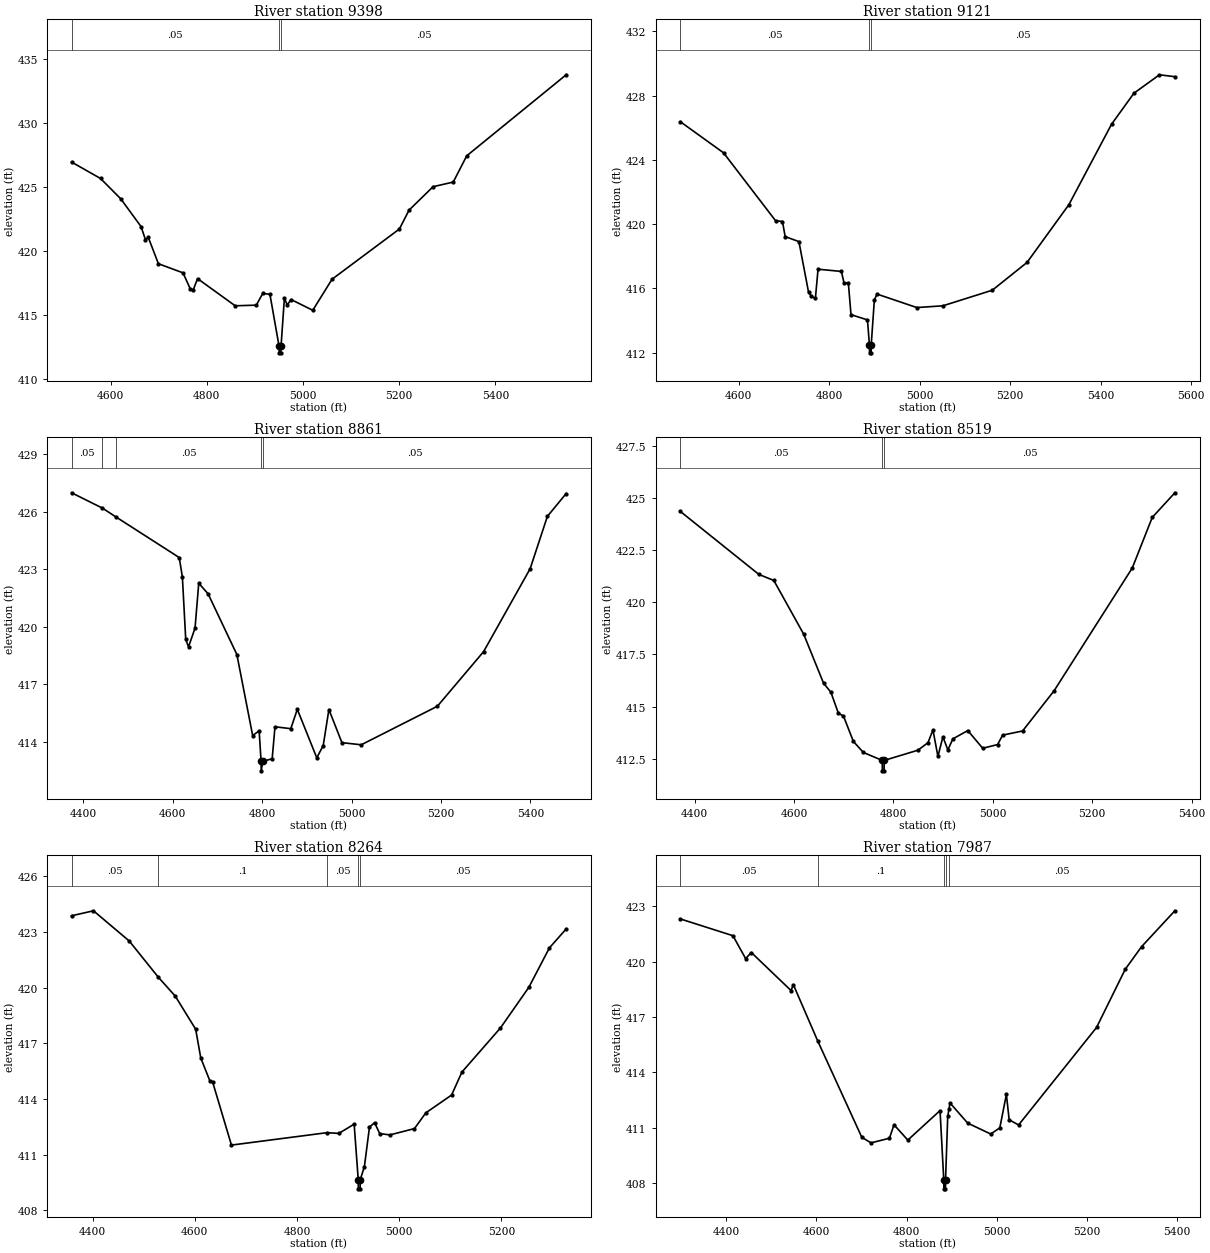
Type RM Length L Ch R = 1 ,9398    ,277,277,277
BEGIN DESCRIPTION:
Lacy 121 1376
END DESCRIPTION:
XS GIS Cut Line= 3
       2723426.5      6875702.31      2723018.94      6875433.03
      2722479.37      6875420.46
#Sta/Elev= 30
    4519  426.94  4579.2  425.66  4621.3  424.07  4663.4  421.91  4672.5  420.89
  4678.5  421.06  4699.5  419.01  4750.7   418.3  4765.8  417.04  4771.8  416.96
  4780.9  417.85  4859.1  415.73  4903.1  415.78  4916.3  416.69  4931.3  416.63
  4950.4  412.56  4950.6  412.06  4954.1  412.06  4954.4  412.56  4961.4  416.32
  4967.4  415.79  4975.1  416.22  5020.4  415.38  5060.4   417.8  5200.5  421.72
  5220.5  423.19  5270.5  425.02  5312.4  425.38  5340.5  427.43  5547.2  433.75
#Mann= 3 ,-1 , 0
    4519     .05       0  4950.4     .04       0  4954.4     .05       0
Bank Sta=4950.4,4954.4
XS Rating Curve= 0 ,0
Exp/Cntr=0.3,0.1

Type RM Length L Ch R = 1 ,9121    ,260,260,260
BEGIN DESCRIPTION:
Lacy 121 1375
END DESCRIPTION:
XS GIS Cut Line= 3
      2723423.39      6875645.03      2723049.65      6875059.68
      2722674.14      6874926.25
#Sta/Elev= 30
  4471.3  426.38  4566.9  424.44  4681.9  420.21  4697.2  420.16  4703.1  419.22
  4733.5  418.91  4754.7  415.77  4760.8   415.5  4769.9  415.37  4775.8  417.19
  4827.4  417.05  4833.4   416.3  4842.7  416.35  4848.6  414.36    4885  414.03
  4889.3  412.48  4889.6  411.98  4893.1  411.98  4893.3  412.48  4900.2  415.27
  4906.1  415.64  4994.1   414.8  5051.7  414.91  5160.8  415.88  5237.6  417.61
  5330.1  421.21  5424.4  426.22  5473.8  428.15  5530.2   429.3  5564.3  429.18
#Mann= 3 ,-1 , 0
  4471.3     .05       0  4889.3     .05       0  4893.3     .05       0
Bank Sta=4889.3,4893.3
XS Rating Curve= 0 ,0
Exp/Cntr=0.3,0.1

Type RM Length L Ch R = 1 ,8861    ,342,342,342
BEGIN DESCRIPTION:
Lacy 121 1374
END DESCRIPTION:
XS GIS Cut Line= 4
      2723576.79      6875487.62      2723192.27      6874985.08
      2723042.26      6874810.14      2722805.78      6874757.88
#Sta/Elev= 30
  4374.4     427  4443.3   426.2  4473.5  425.74    4615  423.62    4622  422.61
  4629.5  419.35  4635.8  418.96  4650.3  419.94  4658.6  422.28  4679.4  421.73
  4743.8  418.56  4779.1  414.33  4793.6  414.58  4797.9  412.99  4798.2  412.49
  4801.9  412.99  4822.7  413.12    4829  414.79  4864.3  414.69  4878.9   415.7
  4922.4  413.17  4936.8  413.81  4949.5  415.69  4978.6  413.96  5021.8  413.85
  5191.9  415.86  5295.2  418.71  5399.3  423.04  5437.8  425.77  5479.8  426.96
#Mann= 5 ,-1 , 0
  4374.4     .05       0  4443.3     .12       0  4473.5     .05       0
  4797.9     .05       0  4801.9     .05       0
Bank Sta=4797.9,4801.9
XS Rating Curve= 0 ,0
Exp/Cntr=0.3,0.1

Type RM Length L Ch R = 1 ,8519    ,255,255,255
BEGIN DESCRIPTION:
Lacy 121 1373
END DESCRIPTION:
XS GIS Cut Line= 3
      2723854.07      6874735.55      2723224.96      6874715.68
      2722860.66      6874686.44
#Sta/Elev= 30
  4371.2  424.35  4529.3  421.33  4559.4  421.04  4619.4  418.47  4659.4  416.12
  4674.1  415.69  4689.4  414.67  4699.4  414.55  4719.4  413.33  4739.5   412.8
  4777.5  412.42  4777.7  411.92  4781.2  411.92  4781.5  412.42  4849.5  412.91
  4869.5  413.27  4879.5  413.88  4889.5  412.61  4899.5  413.55  4909.5  412.92
  4919.5  413.45  4949.6  413.85  4979.6     413  5009.6  413.18  5019.6  413.63
  5059.8  413.83  5123.3  415.76  5280.5  421.64  5320.6  424.06  5366.1  425.24
#Mann= 3 ,-1 , 0
  4371.2     .05       0  4777.5     .04       0  4781.5     .05       0
Bank Sta=4777.5,4781.5
XS Rating Curve= 0 ,0
Exp/Cntr=0.3,0.1

Type RM Length L Ch R = 1 ,8264    ,277,277,277
BEGIN DESCRIPTION:
Lacy 121 1371
END DESCRIPTION:
XS GIS Cut Line= 3
      2723868.78      6874481.32      2723225.77      6874492.31
      2722903.45      6874531.55
#Sta/Elev= 30
    4359  423.88  4401.8  424.15  4471.8  422.52  4528.9  420.56  4561.8  419.55
  4601.8  417.76  4611.8  416.21  4629.8  414.96  4634.8  414.93  4671.8  411.51
  4858.9  412.18  4881.9  412.14  4911.9  412.64  4919.9  409.65  4920.1  409.15
  4923.6  409.15  4923.9  409.65  4931.9  410.34  4941.9  412.48  4951.9  412.72
  4961.9  412.13  4981.9  412.06  5029.9   412.4  5052.2  413.25  5102.6  414.21
  5122.8  415.45  5198.2  417.83  5253.7  420.02    5294  422.15  5326.8  423.17
#Mann= 5 ,-1 , 0
    4359     .05       0  4528.9      .1       0  4858.9     .05       0
  4919.9     .04       0  4923.9     .05       0
Bank Sta=4919.9,4923.9
XS Rating Curve= 0 ,0
Exp/Cntr=0.3,0.1

Type RM Length L Ch R = 1 ,7987    ,442,442,442
BEGIN DESCRIPTION:
Lacy 121 1372
END DESCRIPTION:
XS GIS Cut Line= 3
      2723860.41      6874086.28      2723179.14      6874226.26
      2722857.89      6874467.08
#Sta/Elev= 30
  4298.2  422.31    4415   421.4  4443.2  420.16  4455.8  420.49  4543.9  418.43
    4549  418.75  4602.9  415.71  4700.9  410.48  4721.3  410.18  4762.1  410.43
  4772.3  411.16  4802.9  410.33  4874.4  411.93  4882.6  408.19  4882.9  407.69
  4886.4  407.69  4886.6  408.19  4891.4  411.61  4894.1     412  4896.5  412.34
  4935.7  411.25  4986.7  410.66  5006.9  410.99  5021.5   412.8  5027.7  411.43
  5048.6  411.15  5221.5  416.43  5285.1  419.58  5321.5  420.81  5395.2  422.75
#Mann= 5 ,-1 , 0
  4298.2     .05       0  4602.9      .1       0  4882.6     .05       0
  4886.6      .1       0  4894.1     .05       0
Bank Sta=4882.6,4886.6
XS Rating Curve= 0 ,0
Exp/Cntr=0.3,0.1

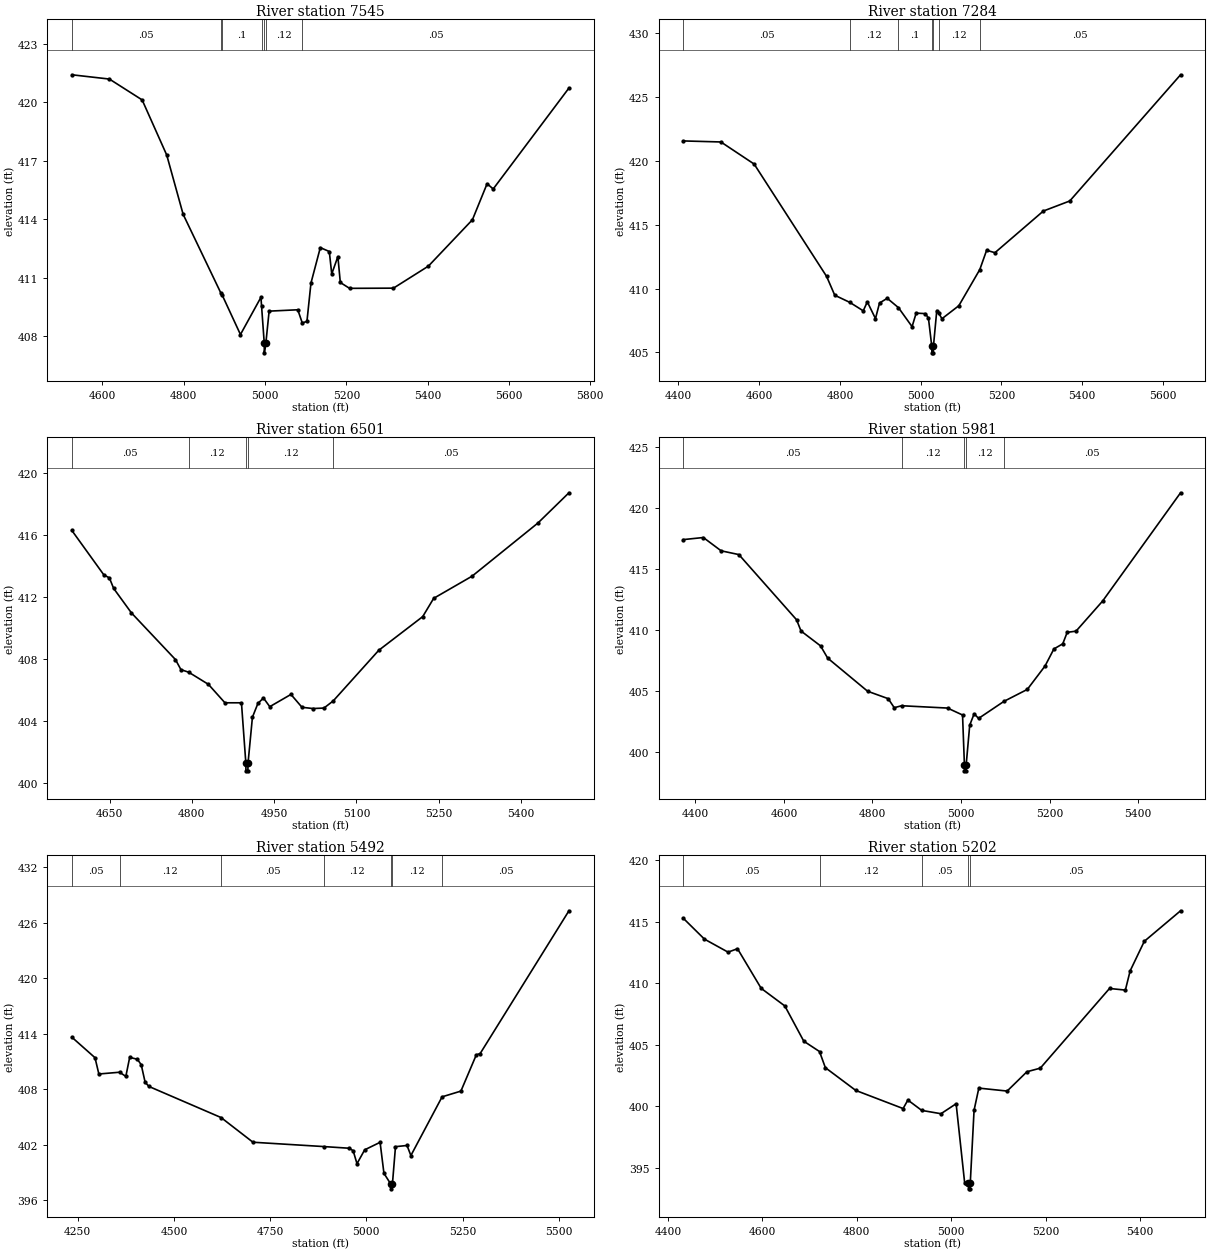
Type RM Length L Ch R = 1 ,7545    ,261,261,261
BEGIN DESCRIPTION:
Lacy 121 1370
END DESCRIPTION:
XS GIS Cut Line= 3
      2723747.69      6873823.88      2723173.68      6873893.63
      2722817.79       6874430.8
#Sta/Elev= 30
  4524.8  421.41  4617.2  421.19  4697.7  420.12  4758.2  417.29  4798.5  414.25
  4891.3  410.21  4894.9  410.09  4939.5  408.08  4989.9  409.99  4991.4  409.55
    4998  407.64  4998.2  407.14    5002  407.64    5010  409.28  5080.5  409.35
  5091.4  408.68    5103  408.75  5112.9  410.72  5135.9  412.54    5158  412.34
    5164  411.19  5179.1  412.08  5185.1  410.75  5207.8  410.45  5315.8  410.46
  5401.7  411.59    5510  413.97  5546.1  415.82  5561.1  415.55  5747.4  420.73
#Mann= 7 ,-1 , 0
  4524.8     .05       0  4891.3     .12       0  4894.9      .1       0
  4991.4     .12       0    4998     .07       0    5002     .12       0
  5091.4     .05       0
Bank Sta=4998,5002
XS Rating Curve= 0 ,0
Exp/Cntr=0.3,0.1

Type RM Length L Ch R = 1 ,7284    ,783,783,783
BEGIN DESCRIPTION:
Lacy 121 1369
END DESCRIPTION:
XS GIS Cut Line= 3
      2723717.89      6873776.43      2723125.23      6873705.47
      2722509.51      6873556.39
#Sta/Elev= 30
  4412.8  421.56  4505.5  421.48  4587.8  419.75  4767.2  410.95  4787.3  409.48
  4824.6  408.92  4857.8  408.26  4867.9  408.96  4888.1  407.65  4898.1  408.87
  4917.2  409.24  4944.9  408.51  4978.7  407.02  4988.8  408.08  5011.9  408.04
  5019.2  407.68  5027.5  405.47  5027.7  404.97  5031.2  404.97  5031.5  405.47
  5039.8  408.28    5045  408.06  5052.6  407.64  5094.4  408.66  5146.3  411.49
  5163.2     413  5183.8  412.81  5303.5  416.07    5369  416.86  5643.2  426.74
#Mann= 7 ,-1 , 0
  4412.8     .05       0  4824.6     .12       0  4944.9      .1       0
  5027.5     .07       0  5031.5      .1       0    5045     .12       0
  5146.3     .05       0
Bank Sta=5027.5,5031.5
XS Rating Curve= 0 ,0
Exp/Cntr=0.3,0.1

Type RM Length L Ch R = 1 ,6501    ,520,520,520
BEGIN DESCRIPTION:
Lacy 121 1368
END DESCRIPTION:
XS GIS Cut Line= 3
      2723644.27      6873161.68      2723217.87      6873130.95
      2722739.48      6873130.16
#Sta/Elev= 30
  4581.3  416.31  4639.7  413.44  4649.7  413.25  4657.5  412.57  4689.9  410.99
  4770.1  407.98  4780.1  407.33  4794.4  407.16  4830.2  406.38  4860.3  405.19
  4890.4  405.19  4898.4   401.3  4898.6   400.8  4902.1   400.8  4902.4   401.3
  4910.4  404.26  4920.4  405.15  4930.5   405.5    4942  404.94  4980.6  405.73
  5000.7   404.9  5020.7  404.82  5040.7  404.85  5057.6  405.31  5140.7  408.58
  5220.7  410.75  5240.7  411.93  5310.7  413.36  5430.7  416.79  5487.2  418.74
#Mann= 5 ,-1 , 0
  4581.3     .05       0  4794.4     .12       0  4898.4     .07       0
  4902.4     .12       0  5057.6     .05       0
Bank Sta=4898.4,4902.4
XS Rating Curve= 0 ,0
Exp/Cntr=0.3,0.1

Type RM Length L Ch R = 1 ,5981    ,489,489,489
BEGIN DESCRIPTION:
Lacy 121 1367
END DESCRIPTION:
XS GIS Cut Line= 3
      2723860.84      6872745.91       2723232.2      6872705.27
      2722740.06      6872704.17
#Sta/Elev= 30
  4373.3   417.4  4418.2  417.57  4458.3  416.48  4498.4  416.17  4628.7  410.82
  4638.7   409.9  4682.8  408.68  4698.8  407.68    4789  404.96  4835.5  404.35
  4849.1  403.61  4865.8  403.77  4969.4  403.58  5003.3  403.01  5007.5  398.93
  5007.7  398.43  5011.2  398.43  5011.5  398.93  5019.5  402.18  5029.5  403.11
  5039.5  402.73  5096.8  404.13  5149.5  405.11  5189.5  407.03  5209.5  408.43
  5229.5  408.85  5239.5  409.79  5259.5  409.89  5319.5  412.36  5495.4  421.24
#Mann= 5 ,-1 , 0
  4373.3     .05       0  4865.8     .12       0  5007.5     .07       0
  5011.5     .12       0  5096.8     .05       0
Bank Sta=5007.5,5011.5
XS Rating Curve= 0 ,0
Exp/Cntr=0.3,0.1

Type RM Length L Ch R = 1 ,5492    ,290,290,290
BEGIN DESCRIPTION:
Lacy 121 1366
END DESCRIPTION:
XS GIS Cut Line= 3
      2723986.18      6872281.25      2723214.87      6872315.22
      2722695.33      6872313.51
#Sta/Elev= 30
  4234.8  413.61    4295  411.39    4305  409.63  4358.9  409.82  4375.1  409.37
  4385.1  411.43  4405.1  411.22  4415.1  410.63  4425.2  408.74  4435.2  408.28
  4622.5  404.92  4705.4  402.25  4889.9  401.78  4955.7   401.6  4965.7  401.33
  4975.7  399.93  4995.7  401.43  5035.7  402.24  5045.7  398.89  5063.7  397.71
    5064  397.21  5067.7  397.71  5075.7  401.77  5105.7   401.9  5115.7  400.81
  5196.8  407.16  5245.7  407.78  5285.7   411.7  5295.7  411.84  5526.4  427.28
#Mann= 7 ,-1 , 0
  4234.8     .05       0  4358.9     .12       0  4622.5     .05       0
  4889.9     .12       0  5063.7     .07       0  5067.7     .12       0
  5196.8     .05       0
Bank Sta=5063.7,5067.7
XS Rating Curve= 0 ,0
Exp/Cntr=0.3,0.1

Type RM Length L Ch R = 1 ,5202    ,552,552,552
BEGIN DESCRIPTION:
Lacy 121 1365
END DESCRIPTION:
XS GIS Cut Line= 3
      2723930.28      6872035.77      2723356.98      6872074.35
      2722879.32      6872047.69
#Sta/Elev= 30
    4433  415.26  4477.4  413.58  4527.5  412.52  4547.5   412.8  4597.7  409.58
  4647.8  408.15  4687.9  405.29  4721.2  404.45  4733.6  403.14  4798.1  401.29
  4898.3  399.82  4908.4  400.51  4937.7  399.67  4978.5   399.4  5010.6  400.21
  5028.6  393.81  5036.6   393.8  5036.9   393.3  5040.4   393.3  5040.6   393.8
  5048.6  399.68  5058.7  401.48  5118.7  401.24  5160.6  402.81  5188.9   403.1
  5335.5  409.57  5369.1  409.44  5379.2     411  5409.2   413.4    5486  415.88
#Mann= 5 ,-1 , 0
    4433     .05       0  4721.2     .12       0  4937.7     .05       0
  5036.6     .05       0  5040.6     .05       0
Bank Sta=5036.6,5040.6
XS Rating Curve= 0 ,0
Exp/Cntr=0.3,0.1

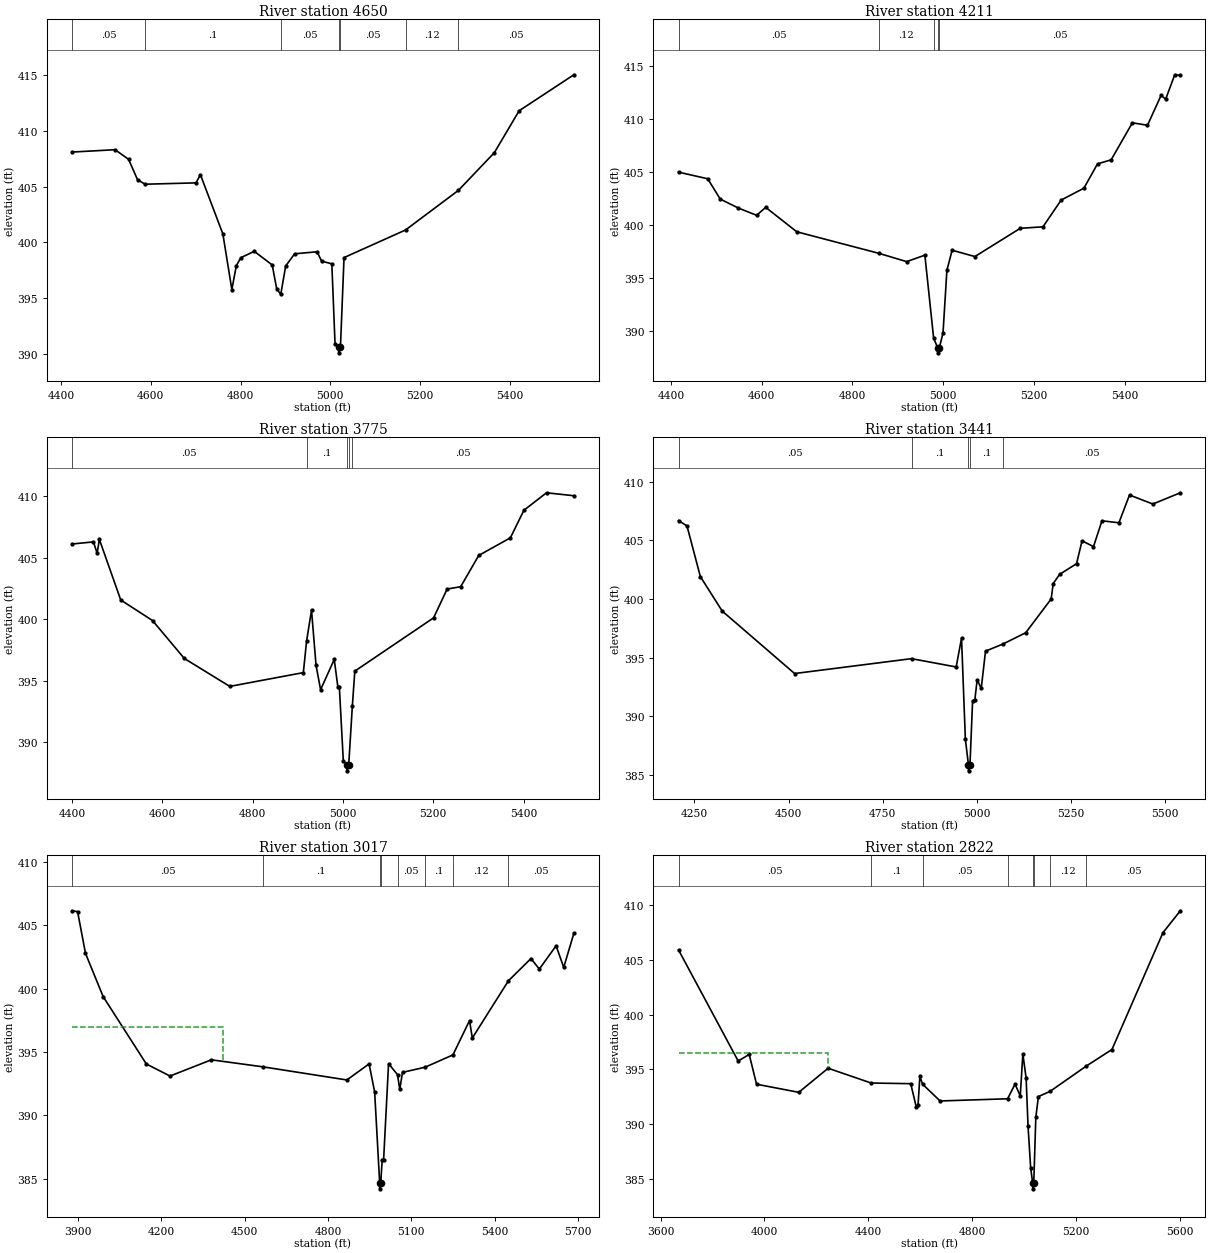
Type RM Length L Ch R = 1 ,4650    ,439,439,439
BEGIN DESCRIPTION:
Lacy 121 1364
END DESCRIPTION:
XS GIS Cut Line= 3
      2724001.93      6871606.23      2723425.32      6871597.98
      2722884.18      6871580.17
#Sta/Elev= 30
  4424.6  408.09  4520.5   408.3  4550.5  407.44  4570.5  405.61  4587.3  405.21
  4700.6  405.33  4710.6  406.06  4760.6  400.76  4780.6  395.78  4790.6  397.91
  4800.6  398.63  4830.6   399.2  4870.6  397.98  4880.6  395.83  4889.6  395.35
  4900.6  397.89  4920.6  398.98  4970.6  399.16  4980.6  398.32  5003.4  398.08
  5010.6  390.87  5018.6  390.61  5018.8  390.11  5022.6  390.61  5030.6  398.64
  5167.6  401.11  5285.5  404.66  5365.6  408.04  5420.8  411.79  5542.7  415.01
#Mann= 7 ,-1 , 0
  4424.6     .05       0  4587.3      .1       0  4889.6     .05       0
  5018.6     .05       0  5022.6     .05       0  5167.6     .12       0
  5285.5     .05       0
Bank Sta=5018.6,5022.6
XS Rating Curve= 0 ,0
Exp/Cntr=0.3,0.1

Type RM Length L Ch R = 1 ,4211    ,436,436,436
BEGIN DESCRIPTION:
Lacy 121 1363
END DESCRIPTION:
XS GIS Cut Line= 3
       2724107.8      6871219.05      2723514.09      6871189.62
      2723003.71      6871172.53
#Sta/Elev= 30
    4417  405.01  4481.3  404.38  4508.9  402.46    4549  401.61    4589  400.93
    4609  401.68  4677.4  399.37  4857.8  397.34  4919.4  396.55  4959.5  397.16
  4978.8  389.32  4987.5  388.43  4987.8  387.93  4991.5  388.43  4999.5  389.82
    5008  395.72  5019.5  397.63  5069.6  397.03  5169.6   399.7  5219.6  399.84
  5259.7  402.37  5309.7  403.49  5339.7  405.79  5369.7  406.17  5416.5  409.67
  5449.8  409.44  5479.8  412.27  5489.8   411.9  5509.8  414.21  5522.1  414.17
#Mann= 5 ,-1 , 0
    4417     .05       0  4857.8     .12       0  4978.8     .05       0
  4987.5     .04       0  4991.5     .05       0
Bank Sta=4987.5,4991.5
XS Rating Curve= 0 ,0
Exp/Cntr=0.3,0.1

Type RM Length L Ch R = 1 ,3775    ,334,334,334
BEGIN DESCRIPTION:
Lacy 121 1362
END DESCRIPTION:
XS GIS Cut Line= 3
      2724173.11      6870872.49      2723584.66      6870806.81
       2723065.4      6870794.71
#Sta/Elev= 30
  4399.9   406.1  4447.3  406.27  4455.4  405.34  4460.4  406.47  4507.7  401.55
  4578.1  399.88  4648.5   396.8  4749.2  394.53  4912.2  395.65  4919.4  398.23
  4930.3  400.72  4940.3  396.25  4950.4  394.26  4980.6  396.72  4988.8  394.45
    4992  394.45  5000.7  388.49  5008.7  388.17  5008.9  387.67  5012.7  388.17
  5020.8  392.97  5026.2  395.77  5200.7   400.1  5230.7  402.44  5260.7  402.63
  5300.7  405.17  5370.8   406.6  5400.8  408.84  5450.8  410.26  5511.4  410.02
#Mann= 5 ,-1 , 0
  4399.9     .05       0  4919.4      .1       0  5008.7     .07       0
  5012.7      .1       0  5020.8     .05       0
Bank Sta=5008.7,5012.7
XS Rating Curve= 0 ,0
Exp/Cntr=0.3,0.1

Type RM Length L Ch R = 1 ,3441    ,424,424,424
BEGIN DESCRIPTION:
Lacy 121 1361
END DESCRIPTION:
XS GIS Cut Line= 4
      2724200.27      6870768.67      2723769.11      6870437.17
      2723533.39      6870485.25      2723041.76      6870726.35
#Sta/Elev= 30
  4207.9   406.7  4230.4  406.24  4265.8  401.92  4323.8  398.98    4516  393.65
  4826.4  394.92  4944.9  394.21  4959.1  396.67  4969.3  388.05  4977.5  385.85
  4977.7  385.35  4981.5  385.85  4988.5  391.33  4994.5  391.42  5000.6  393.12
  5011.4  392.38  5022.8  395.56  5069.9  396.18  5129.5  397.13    5197  400.01
  5202.5  401.33  5219.5  402.11  5264.4  403.02    5279  404.97  5309.4  404.48
  5331.9  406.68  5376.9  406.51    5405  408.88  5466.9  408.11  5539.9  409.07
#Mann= 5 ,-1 , 0
  4207.9     .05       0  4826.4      .1       0  4977.5     .07       0
  4981.5      .1       0  5069.9     .05       0
Bank Sta=4977.5,4981.5
XS Rating Curve= 0 ,0
Exp/Cntr=0.3,0.1

Type RM Length L Ch R = 1 ,3017    ,195,195,195
BEGIN DESCRIPTION:
Lacy 121 1360
END DESCRIPTION:
XS GIS Cut Line= 4
      2724223.43      6870751.39      2723581.01      6870173.84
      2723326.47      6870172.16      2722642.37      6870239.35
#Sta/Elev= 30
  3879.1  406.15    3899  406.08  3927.4  402.79  3990.9  399.38  4146.4  394.06
  4231.6  393.11  4380.3  394.39  4565.2  393.84    4868   392.8    4948  394.07
    4968  391.85    4986  384.71  4986.2  384.21    4990  384.71  4995.2  386.52
  5000.3  386.52  5018.1  394.09  5050.3  393.22  5058.3  392.06  5068.3   393.4
    5150  393.81  5249.8  394.78  5309.5  397.49  5319.5  396.11  5449.2  400.62
  5530.5  402.38  5560.7  401.55    5621  403.39  5648.4  401.68  5684.9  404.37
#Mann= 8 ,-1 , 0
  3879.1     .05       0  4565.2      .1       0    4986     .07       0
    4990      .1       0  5050.3     .05       0    5150      .1       0
  5249.8     .12       0  5449.2     .05       0
#XS Ineff= 2 , 0
       0    4421     397               0
Permanent Ineff=
       F       F
Bank Sta=4986,4990
XS Rating Curve= 0 ,0
Exp/Cntr=0.3,0.1

Type RM Length L Ch R = 1 ,2822    ,422,422,422
BEGIN DESCRIPTION:
Lacy 121 1359
END DESCRIPTION:
XS GIS Cut Line= 4
      2724258.87      6870743.24      2723479.01      6870004.79
      2723215.68      6870013.72      2722619.13      6869999.82
#Sta/Elev= 30
  3668.8  405.91  3898.7  395.76  3941.2  396.36  3969.5  393.64  4132.2   392.9
  4245.4   395.1  4411.3  393.75  4563.8  393.69  4584.8  391.59  4592.1  391.74
    4599  394.35  4609.6  393.64    4677  392.11  4937.2  392.31  4965.9  393.65
    4986  392.57    4996  396.41  5008.6  394.19    5016  389.82    5026  386.03
    5034  384.58  5034.2  384.08    5038  384.58    5046  390.62    5056  392.51
  5101.1  392.99  5241.1  395.31  5339.4  396.81  5536.1  407.49    5603  409.49
#Mann= 8 ,-1 , 0
  3668.8     .05       0  4411.3      .1       0  4609.6     .05       0
  4937.2      .1       0    5034     .07       0    5038      .1       0
  5101.1     .12       0  5241.1     .05       0
#XS Ineff= 2 , 0
       0    4245   396.5               0
Permanent Ineff=
       F       F
Bank Sta=5034,5038
XS Rating Curve= 0 ,0
Exp/Cntr=0.3,0.1

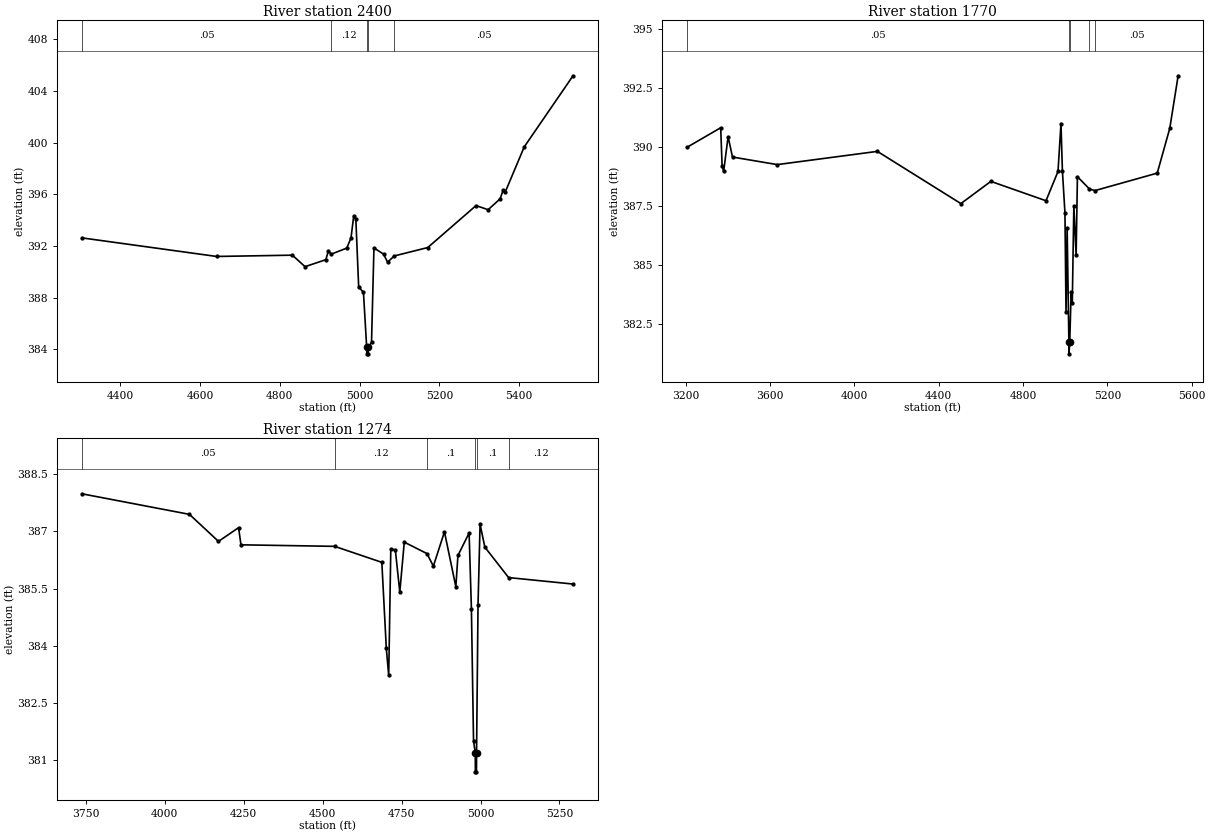
Type RM Length L Ch R = 1 ,2400    ,630,630,630
BEGIN DESCRIPTION:
Lacy 121 1358
END DESCRIPTION:
XS GIS Cut Line= 3
      2723737.19      6869859.02      2723074.64      6869641.56
       2722544.7      6869707.15
#Sta/Elev= 30
  4303.7  392.62  4641.7  391.18  4831.5  391.28  4863.3  390.39  4915.4  390.93
  4921.7   391.6  4929.1  391.36    4968  391.83  4978.5  392.62  4985.3  394.32
  4990.6  394.08  4997.7  388.83  5009.7  388.39  5017.8  384.14  5018.1  383.64
  5021.6  383.64  5021.8  384.14  5029.9  384.52    5036  391.84  5060.1  391.36
  5070.2  390.74  5086.9  391.22  5170.9  391.87  5291.9  395.12  5322.1   394.8
  5352.3  395.64  5360.1  396.34  5365.1  396.17  5412.8  399.67    5535  405.17
#Mann= 5 ,-1 , 0
  4303.7     .05       0  4929.1     .12       0  5017.8     .07       0
  5021.8     .12       0  5086.9     .05       0
Bank Sta=5017.8,5021.8
XS Rating Curve= 0 ,0
Exp/Cntr=0.3,0.1

Type RM Length L Ch R = 1 ,1770    ,496,496,496
BEGIN DESCRIPTION:
Lacy 121 1357
END DESCRIPTION:
XS GIS Cut Line= 3
      2724426.43      6870206.46      2723084.14       6869014.4
      2722585.64      6869211.08
#Sta/Elev= 30
  3204.8  389.98  3365.2  390.81  3371.8  389.21  3379.2  388.96  3400.3  390.43
  3421.2  389.57  3633.6  389.25  4108.6  389.81    4505   387.6  4647.2  388.54
  4908.9  387.72  4965.8  388.96    4980  390.99  4986.7  388.99  4998.8  387.21
  5003.9     383  5009.2  386.58  5017.5  381.74  5017.8  381.24  5021.5  381.74
  5028.2  383.87  5033.6  383.38    5041  387.51  5051.8  385.42    5058  388.74
  5114.8  388.22  5141.1  388.15  5436.8  388.89  5496.3  390.79  5535.9  393.01
#Mann= 5 ,-1 , 0
  3204.8     .05       0  5017.5     .04       0  5021.5     .05       0
  5114.8     .12       0  5141.1     .05       0
Bank Sta=5017.5,5021.5
XS Rating Curve= 0 ,0
Exp/Cntr=0.3,0.1

Type RM Length L Ch R = 1 ,1274    ,0,0,0
BEGIN DESCRIPTION:
Lacy 121 1356
END DESCRIPTION:
XS GIS Cut Line= 3
      2724284.54      6869683.63      2723452.47      6868733.86
       2723217.3      6868559.08
#Sta/Elev= 30
  3737.3  387.99  4078.2  387.45  4170.2  386.74  4233.8   387.1  4241.4  386.65
  4537.9  386.61  4687.5  386.19  4701.7  383.93  4709.3  383.22  4715.9  386.53
  4730.2  386.52  4744.4  385.41  4758.6  386.72  4830.4  386.42  4850.7  386.09
  4885.8  386.99  4921.9  385.55  4928.5  386.37  4963.9  386.96  4971.2  384.97
  4977.9   381.5  4983.5  381.19  4983.7  380.69  4987.2  380.69  4987.5  381.19
  4992.1  385.06  4998.6  387.19  5013.7  386.59    5089  385.79    5293  385.62
#Mann= 6 ,-1 , 0
  3737.3     .05       0  4537.9     .12       0  4830.4      .1       0
  4983.5     .07       0  4987.5      .1       0    5089     .12       0
Bank Sta=4983.5,4987.5
XS Rating Curve= 0 ,0
Exp/Cntr=0.3,0.1

Chan Stop Cuts=-1
Use User Specified Reach Order=0
Composite Channel Slope=5