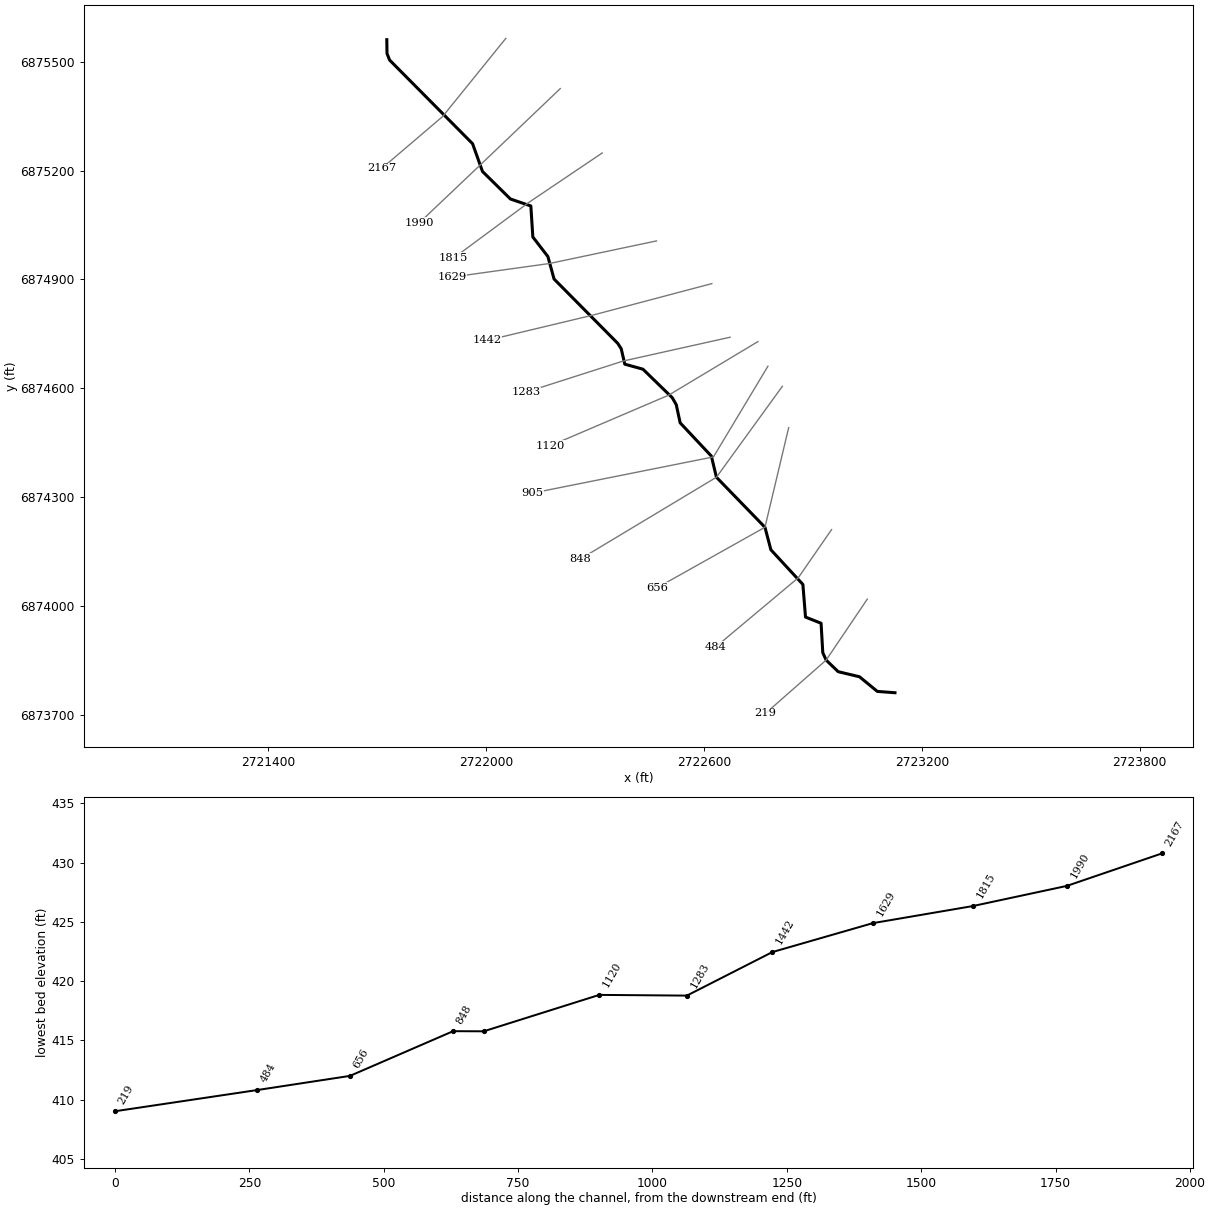
--- Lacy 122.prj (project) ---

Proj Title=Lacy 122 Base Level Engineering
Current Plan=p01
Default Exp/Contr=0.3,0.1
English Units
Geom File=g01
Flow File=f01
Plan File=p01
BEGIN DESCRIPTION:
Lacy 122
END DESCRIPTION:

--- Lacy 122.p01 (plan) ---

Plan Title=Multiple Run
Short Identifier=Multiple
Geom File=g01
Flow File=f01
Subcritical Flow
K Sum by GR= 0
Std Step Tol= 0.01
Critical Tol= 0.01
Num of Std Step Trials= 20
Max Error Tol= 0.3
Flow Tol Ratio= 0.001
Split Flow NTrial= 30
Split Flow Tol= 0.02
Split Flow Ratio= 0.02
Log Output Level= 0
Friction Slope Method= 1
Unsteady Friction Slope Method= 2
Unsteady Bridges Friction Slope Method= 1
Parabolic Critical Depth
Global Vel Dist=  1 , 1 , 1
Global Log Level= 0
CheckData=True
Encroach Param= -1, 0, 0, 0
BEGIN DESCRIPTION:
Multiple Run
END DESCRIPTION:

--- Lacy 122.f01 (steady flow) ---

Flow Title=Multiple
Number of Profiles=7
Profile Names=10-year,25-year,50-year,1pct_min,100-year,1pct_plu,500-year
River Rch & RM= Lacy 122,Reach-1,2167
     133     160     180     101     201     401     250
Boundary for River Rch & Prof#=Lacy 122,Reach-1,1
Up Type=0
Dn Type=3
Dn Slope=0.005
Boundary for River Rch & Prof#=Lacy 122,Reach-1,2
Up Type=0
Dn Type=3
Dn Slope=0.005
Boundary for River Rch & Prof#=Lacy 122,Reach-1,3
Up Type=0
Dn Type=3
Dn Slope=0.005
Boundary for River Rch & Prof#=Lacy 122,Reach-1,4
Up Type=0
Dn Type=3
Dn Slope=0.005
Boundary for River Rch & Prof#=Lacy 122,Reach-1,5
Up Type=0
Dn Type=3
Dn Slope=0.005
Boundary for River Rch & Prof#=Lacy 122,Reach-1,6
Up Type=0
Dn Type=3
Dn Slope=0.005
Boundary for River Rch & Prof#=Lacy 122,Reach-1,7
Up Type=0
Dn Type=3
Dn Slope=0.005

--- Lacy 122.g01 (geometry) ---

Geom Title=Existing Conditions

River Reach=Lacy 122,Reach-1
Reach XY= 30
      2721726.00      6875561.00      2721726.59      6875522.84
      2721733.76      6875504.79      2721962.37      6875274.21
      2721989.62      6875197.76      2722066.60      6875121.90
      2722122.83      6875102.66      2722128.37      6875017.05
      2722169.86      6874963.17      2722186.76      6874901.32
      2722362.27      6874723.98      2722371.87      6874708.99
      2722381.62      6874666.62      2722431.77      6874652.72
      2722512.38      6874574.24      2722523.47      6874554.96
      2722534.18      6874504.96      2722620.13      6874413.28
      2722634.16      6874354.95      2722767.84      6874217.05
      2722784.18      6874154.96      2722872.35      6874059.43
      2722879.55      6873969.50      2722922.44      6873952.50
      2722927.13      6873871.43      2722936.40      6873850.93
      2722969.61      6873819.00      2723028.21      6873805.01
      2723077.49      6873764.60      2723126.00      6873761.00

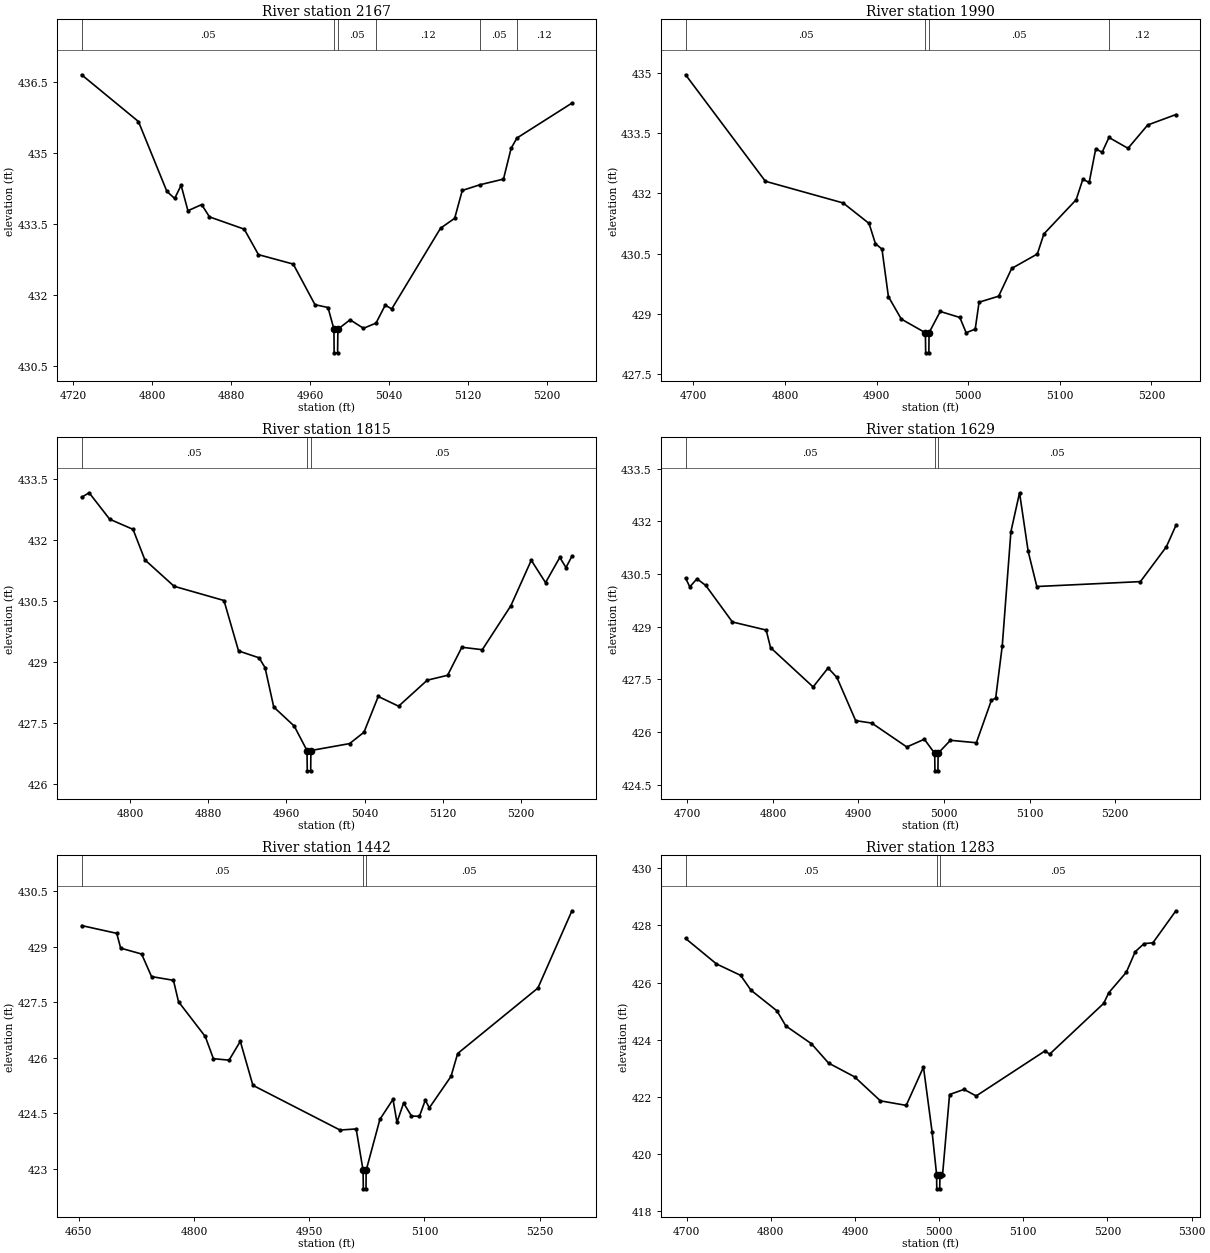
Type RM Length L Ch R = 1,2167,177,177,177
BEGIN DESCRIPTION:
Lacy 122 1385
END DESCRIPTION:
XS GIS Cut Line= 3
      2722053.95      6875564.70      2721879.92      6875349.36
      2721713.00      6875206.93
#Sta/Elev= 30
  4728.8  436.66  4786.3  435.67  4815.1  434.19  4823.0  434.04  4829.5  434.32
  4836.4  433.78  4850.3  433.91  4858.2  433.65  4893.4  433.39  4907.8  432.85
  4943.0  432.65  4965.0  431.79  4978.2  431.73  4984.2  431.27  4984.4  430.77
  4987.9  430.77  4988.2  431.27  5000.5  431.47  5014.1  431.29  5026.8  431.40
  5036.1  431.78  5042.7  431.70  5092.1  433.41  5106.4  433.62  5114.1  434.21
  5131.9  434.33  5155.8  434.45  5163.5  435.10  5169.4  435.32  5225.1  436.06
#Mann=6,-1,0
  4728.8    0.05       0  4984.2    0.04       0  4988.2    0.05       0
  5026.8    0.12       0  5131.9    0.05       0  5169.4    0.12       0
Bank Sta=4984.2,4988.2
Exp/Cntr=0.3,0.1

Type RM Length L Ch R = 1,1990,175,175,175
BEGIN DESCRIPTION:
Lacy 122 1386
END DESCRIPTION:
XS GIS Cut Line= 3
      2722203.91      6875426.17      2721977.09      6875209.61
      2721816.31      6875056.97
#Sta/Elev= 30
  4691.5  434.95  4778.6  432.30  4863.5  431.76  4891.8  431.25  4898.7  430.75
  4905.9  430.61  4912.9  429.43  4927.0  428.87  4953.3  428.53  4953.6  428.03
  4957.1  428.03  4957.3  428.53  4969.5  429.06  4990.9  428.91  4997.8  428.53
  5007.7  428.62  5011.9  429.29  5033.3  429.44  5047.5  430.13  5075.5  430.49
  5082.7  430.99  5117.9  431.84  5125.2  432.35  5132.1  432.27  5139.3  433.11
  5146.2  433.02  5153.7  433.39  5174.5  433.12  5196.0  433.70  5226.8  433.96
#Mann=4,-1,0
  4691.5    0.05       0  4953.3    0.04       0  4957.3    0.05       0
  5153.7    0.12       0
Bank Sta=4953.3,4957.3
Exp/Cntr=0.3,0.1

Type RM Length L Ch R = 1,1815,186,186,186
BEGIN DESCRIPTION:
Lacy 122 1387
END DESCRIPTION:
XS GIS Cut Line= 3
      2722319.60      6875248.78      2722117.30      6875112.43
      2721910.29      6874959.21
#Sta/Elev= 30
  4750.6  433.06  4758.3  433.17  4779.3  432.52  4803.2  432.27  4815.3  431.52
  4845.2  430.87  4896.2  430.52  4911.1  429.28  4932.1  429.11  4938.2  428.87
  4947.1  427.90  4968.1  427.43  4981.1  426.83  4981.4  426.33  4984.9  426.33
  4985.1  426.83  5024.7  427.00  5039.4  427.28  5054.0  428.16  5074.8  427.92
  5104.1  428.56  5124.9  428.68  5139.5  429.37  5160.4  429.31  5189.6  430.39
  5210.5  431.51  5225.1  430.96  5239.7  431.58  5246.0  431.33  5252.1  431.61
#Mann=3,-1,0
  4750.6    0.05       0  4981.1    0.04       0  4985.1    0.05       0
Bank Sta=4981.1,4985.1
Exp/Cntr=0.3,0.1

Type RM Length L Ch R = 1,1629,187,187,187
BEGIN DESCRIPTION:
Lacy 122 1384
END DESCRIPTION:
XS GIS Cut Line= 3
      2722469.05      6875006.33      2722174.04      6874944.04
      2721904.94      6874906.61
#Sta/Elev= 30
  4697.9  430.38  4702.8  430.13  4711.2  430.36  4721.5  430.17  4752.6  429.13
  4792.1  428.90  4797.2  428.40  4847.0  427.28  4864.5  427.82  4874.8  427.55
  4896.7  426.32  4915.6  426.25  4956.5  425.57  4977.0  425.79  4989.1  425.39
  4989.4  424.89  4992.9  424.89  4993.1  425.39  5007.5  425.76  5037.8  425.69
  5055.4  426.90  5060.4  426.96  5068.1  428.45  5078.2  431.70  5088.3  432.81
  5098.4  431.14  5108.5  430.14  5229.6  430.28  5259.9  431.27  5271.1  431.88
#Mann=3,-1,0
  4697.9    0.05       0  4989.1    0.04       0  4993.1    0.05       0
Bank Sta=4989.1,4993.1
Exp/Cntr=0.3,0.1

Type RM Length L Ch R = 1,1442,159,159,159
BEGIN DESCRIPTION:
Lacy 122 1383
END DESCRIPTION:
XS GIS Cut Line= 3
      2722621.49      6874888.66      2722291.83      6874801.32
      2722002.90      6874732.25
#Sta/Elev= 30
  4653.9  429.57  4699.6  429.36  4704.7  428.96  4732.0  428.80  4744.9  428.19
  4773.4  428.09  4780.0  427.51  4814.8  426.57  4825.4  425.97  4845.8  425.93
  4860.4  426.44  4876.8  425.25  4990.2  424.04  5011.2  424.07  5020.2  422.95
  5020.5  422.45  5024.0  422.45  5024.2  422.95  5042.1  424.33  5059.1  424.87
  5064.3  424.25  5072.9  424.77  5083.2  424.42  5093.5  424.41  5101.2  424.85
  5106.4  424.64  5134.6  425.49  5143.3  426.11  5247.7  427.88  5292.0  429.97
#Mann=3,-1,0
  4653.9    0.05       0  5020.2    0.05       0  5024.2    0.05       0
Bank Sta=5020.2,5024.2
Exp/Cntr=0.3,0.1

Type RM Length L Ch R = 1,1283,163,163,163
BEGIN DESCRIPTION:
Lacy 122 1381
END DESCRIPTION:
XS GIS Cut Line= 3
      2722671.86      6874740.90      2722376.95      6874675.15
      2722109.98      6874589.58
#Sta/Elev= 30
  4698.8  427.54  4735.5  426.65  4764.2  426.25  4776.5  425.73  4807.3  425.01
  4817.9  424.48  4848.2  423.86  4868.7  423.18  4899.5  422.70  4930.2  421.86
  4960.9  421.70  4981.4  423.04  4991.7  420.76  4997.0  419.28  4997.2  418.78
  5000.7  418.78  5001.0  419.28  5004.1  419.28  5012.4  422.08  5029.6  422.26
  5044.0  422.03  5126.0  423.61  5131.2  423.49  5195.5  425.27  5201.5  425.64
  5222.4  426.36  5233.0  427.08  5243.5  427.36  5254.0  427.39  5281.3  428.51
#Mann=3,-1,0
  4698.8    0.05       0  4997.0    0.05       0  5001.0    0.05       0
Bank Sta=4997,5001
Exp/Cntr=0.3,0.1

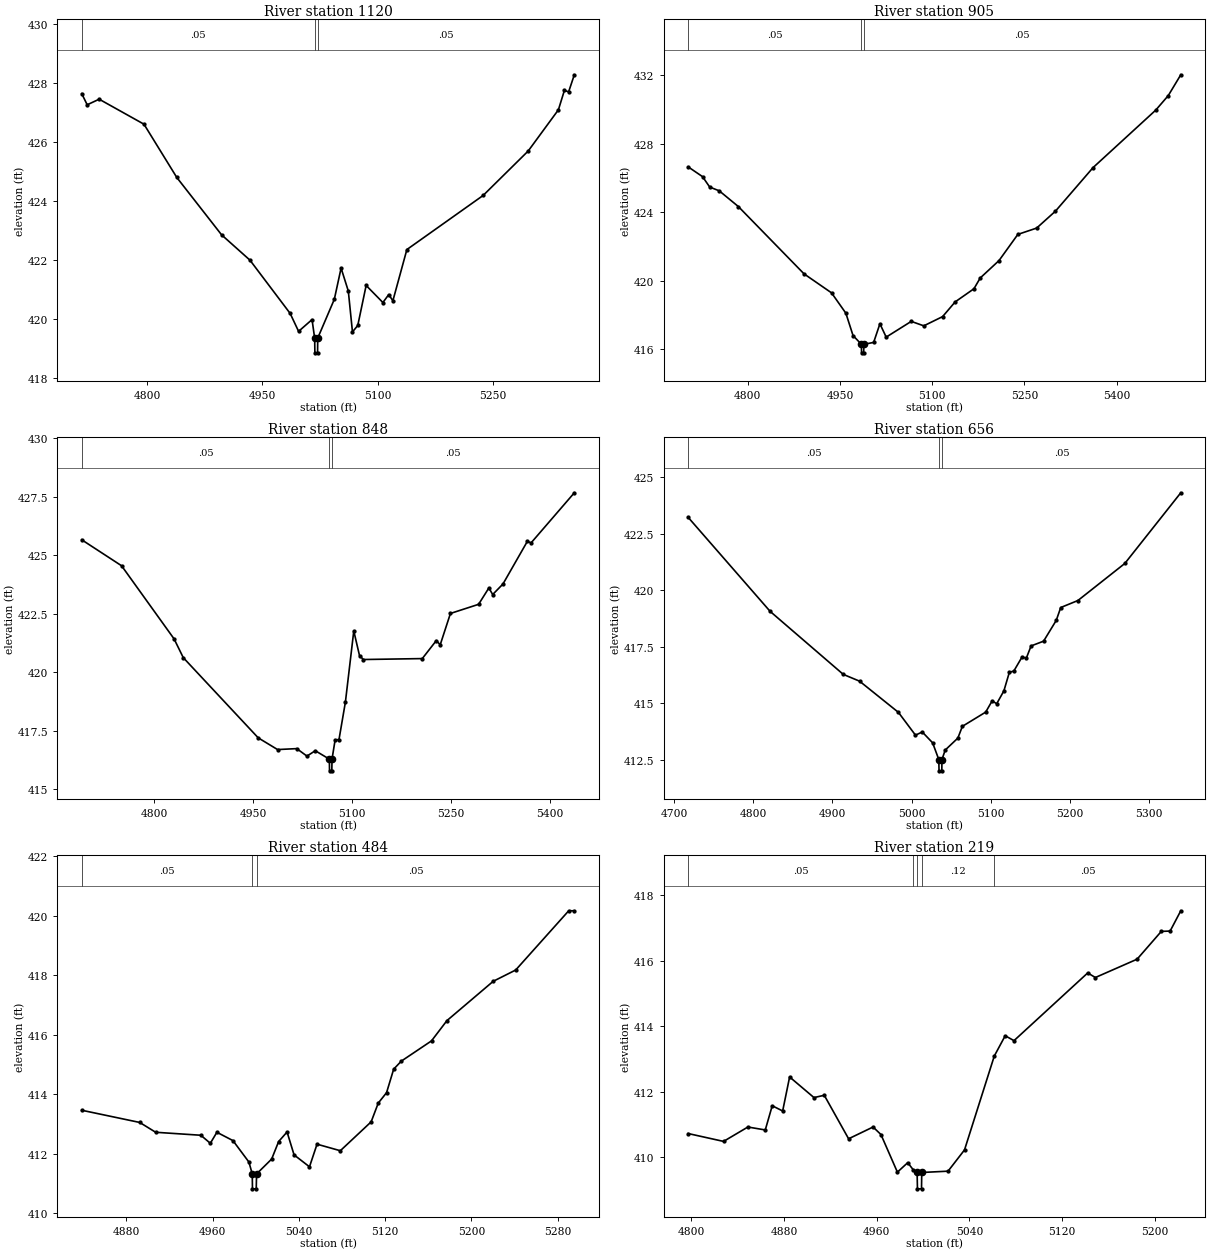
Type RM Length L Ch R = 1,1120,215,215,215
BEGIN DESCRIPTION:
Lacy 122 1382
END DESCRIPTION:
XS GIS Cut Line= 3
      2722748.47      6874728.84      2722502.41      6874581.09
      2722176.94      6874441.90
#Sta/Elev= 30
  4715.1  427.65  4722.2  427.27  4737.8  427.46  4796.1  426.61  4838.8  424.80
  4897.1  422.85  4934.0  421.99  4986.3  420.18  4997.3  419.57  5014.8  419.97
  5018.2  419.34  5018.5  418.84  5022.0  418.84  5022.2  419.34  5043.8  420.66
  5052.6  421.72  5062.0  420.94  5067.4  419.55  5074.3  419.77  5085.2  421.13
  5107.0  420.55  5114.6  420.82  5120.0  420.61  5138.2  422.35  5237.5  424.19
  5296.1  425.70  5335.4  427.10  5343.2  427.76  5348.7  427.71  5356.1  428.29
#Mann=3,-1,0
  4715.1    0.05       0  5018.2    0.04       0  5022.2    0.05       0
Bank Sta=5018.2,5022.2
Exp/Cntr=0.3,0.1

Type RM Length L Ch R = 1,905,57,57,57
BEGIN DESCRIPTION:
Lacy 122 88
END DESCRIPTION:
XS GIS Cut Line= 3
      2722775.99      6874660.99      2722626.00      6874411.00
      2722126.03      6874311.01
#Sta/Elev= 30
  4703.1  426.65  4726.4  426.08  4738.1  425.47  4753.6  425.25  4784.7  424.33
  4891.6  420.39  4936.3  419.28  4959.6  418.09  4971.3  416.78  4984.9  416.27
  4985.1  415.77  4988.6  415.77  4988.9  416.27  5004.8  416.38  5015.0  417.47
  5025.2  416.69  5066.0  417.61  5086.4  417.35  5117.0  417.89  5137.4  418.75
  5168.0  419.52  5178.2  420.15  5208.8  421.17  5239.4  422.70  5270.0  423.07
  5300.6  424.06  5361.8  426.61  5463.7  429.97  5484.1  430.82  5504.5  432.04
#Mann=3,-1,0
  4703.1    0.05       0  4984.9    0.04       0  4988.9    0.05       0
Bank Sta=4984.9,4988.9
Exp/Cntr=0.3,0.1

Type RM Length L Ch R = 1,848,192,192,192
BEGIN DESCRIPTION:
Lacy 122 1380
END DESCRIPTION:
XS GIS Cut Line= 3
      2722815.90      6874605.72      2722634.16      6874354.95
      2722259.28      6874129.60
#Sta/Elev= 30
  4690.3  425.66  4750.7  424.55  4830.4  421.42  4844.3  420.62  4958.0  417.19
  4987.3  416.69  5016.4  416.73  5031.9  416.41  5044.5  416.64  5065.9  416.28
  5066.1  415.78  5069.6  415.78  5069.9  416.28  5074.6  417.10  5080.5  417.12
  5090.2  418.72  5102.9  421.76  5111.6  420.71  5117.4  420.54  5206.8  420.58
  5228.1  421.35  5234.0  421.17  5249.5  422.51  5292.2  422.90  5307.8  423.60
  5313.6  423.32  5329.2  423.77  5366.1  425.59  5371.9  425.53  5437.4  427.67
#Mann=3,-1,0
  4690.3    0.05       0  5065.9    0.04       0  5069.9    0.05       0
Bank Sta=5065.9,5069.9
Exp/Cntr=0.3,0.1

Type RM Length L Ch R = 1,656,172,172,172
BEGIN DESCRIPTION:
Lacy 122 1379
END DESCRIPTION:
XS GIS Cut Line= 3
      2722833.21      6874491.78      2722767.84      6874217.05
      2722470.86      6874050.49
#Sta/Elev= 30
  4717.6  423.23  4821.2  419.07  4913.7  416.28  4934.3  415.98  4983.4  414.60
  5005.0  413.59  5013.6  413.73  5026.7  413.25  5034.5  412.51  5034.8  412.01
  5038.3  412.01  5038.5  412.51  5042.6  412.93  5058.6  413.46  5064.3  413.98
  5093.8  414.61  5102.0  415.11  5107.7  414.98  5116.8  415.55  5123.7  416.37
  5129.4  416.43  5139.6  417.04  5145.3  417.01  5151.2  417.54  5167.0  417.75
  5183.0  418.67  5188.7  419.24  5210.4  419.55  5269.7  421.19  5340.5  424.32
#Mann=3,-1,0
  4717.6    0.05       0  5034.5    0.04       0  5038.5    0.05       0
Bank Sta=5034.5,5038.5
Exp/Cntr=0.3,0.1

Type RM Length L Ch R = 1,484,265,265,265
BEGIN DESCRIPTION:
Lacy 122 1378
END DESCRIPTION:
XS GIS Cut Line= 3
      2722951.31      6874210.58      2722859.50      6874077.72
      2722633.00      6873887.94
#Sta/Elev= 30
  4838.5  413.46  4892.3  413.05  4907.1  412.72  4949.0  412.62  4957.8  412.35
  4963.9  412.72  4978.8  412.44  4993.6  411.72  4996.7  411.32  4996.9  410.82
  5000.4  410.82  5000.7  411.32  5014.7  411.82  5021.2  412.41  5029.0  412.73
  5035.5  411.96  5049.8  411.56  5056.8  412.32  5078.4  412.10  5107.0  413.07
  5113.6  413.70  5121.3  414.05  5127.9  414.84  5135.0  415.11  5163.0  415.79
  5177.3  416.47  5220.2  417.79  5241.1  418.17  5290.3  420.16  5295.5  420.16
#Mann=3,-1,0
  4838.5    0.05       0  4996.7    0.04       0  5000.7    0.05       0
Bank Sta=4996.7,5000.7
Exp/Cntr=0.3,0.1

Type RM Length L Ch R = 1,219,0,0,0
BEGIN DESCRIPTION:
Lacy 122 1377
END DESCRIPTION:
XS GIS Cut Line= 3
      2723049.69      6874018.89      2722936.40      6873850.93
      2722769.36      6873704.09
#Sta/Elev= 30
  4797.4  410.72  4827.9  410.48  4848.9  410.92  4863.9  410.83  4869.9  411.57
  4878.9  411.41  4884.9  412.45  4905.9  411.82  4914.8  411.89  4935.8  410.56
  4956.9  410.92  4963.7  410.69  4977.9  409.54  4986.8  409.83  4991.4  409.62
  4994.9  409.53  4995.2  409.03  4998.7  409.03  4998.9  409.53  5021.6  409.57
  5035.8  410.22  5061.5  413.09  5070.9  413.71  5078.5  413.56  5142.1  415.63
  5148.7  415.49  5184.7  416.05  5205.6  416.90  5213.2  416.91  5222.4  417.53
#Mann=5,-1,0
  4797.4    0.05       0  4991.4    0.12       0  4994.9    0.07       0
  4998.9    0.12       0  5061.5    0.05       0
Bank Sta=4994.9,4998.9
Exp/Cntr=0.3,0.1

Chan Stop Cuts=-1