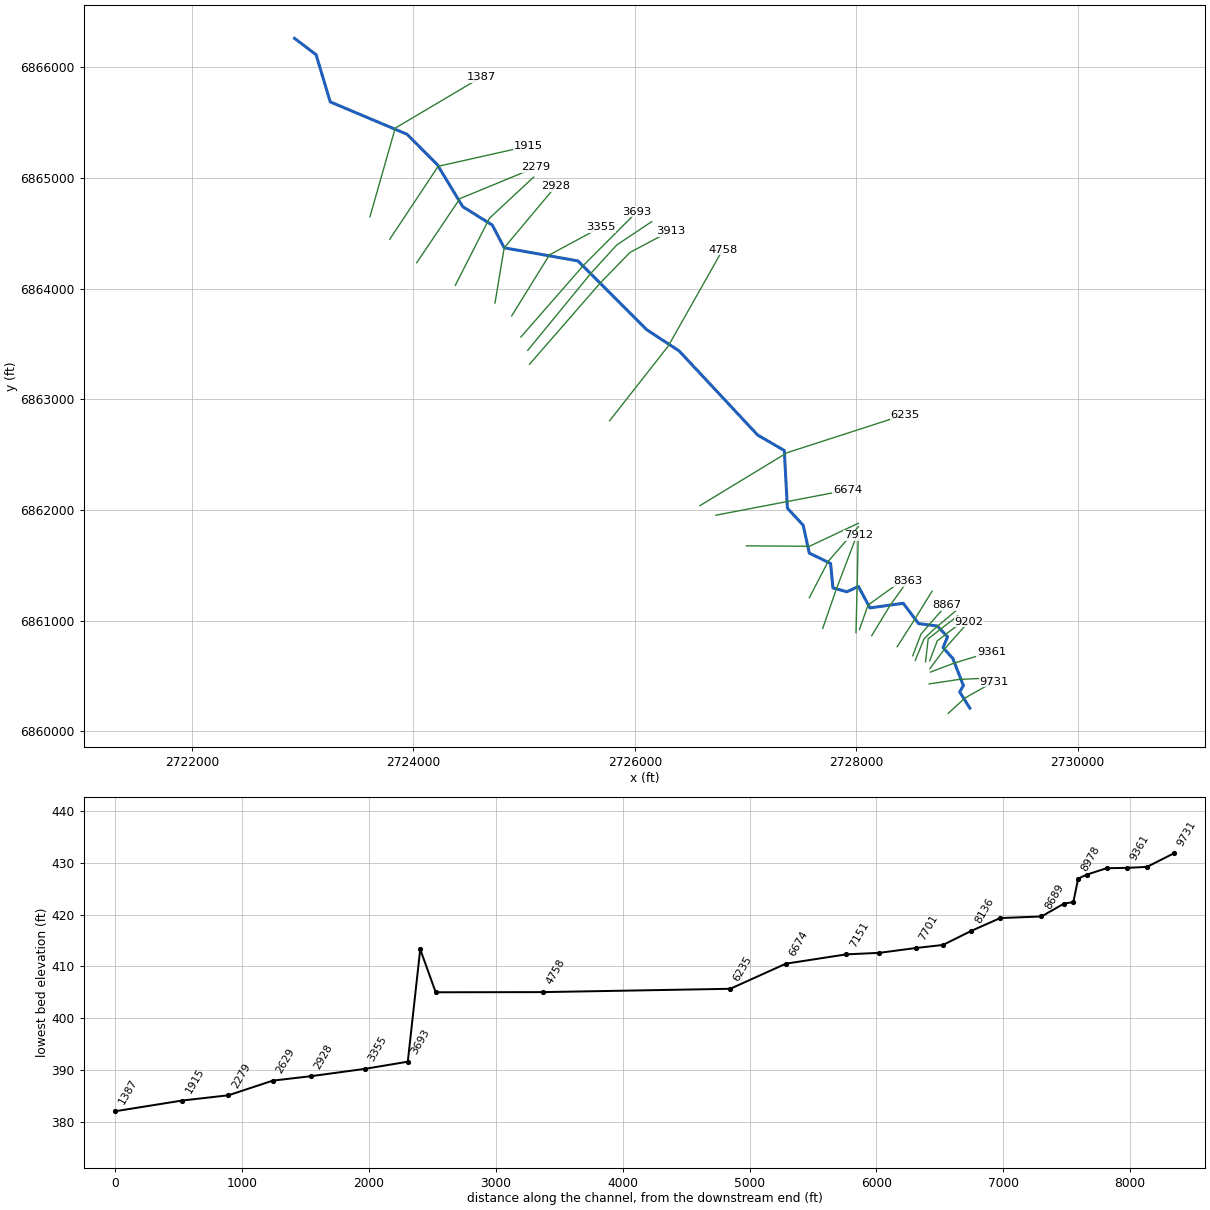
--- Lacy 123.prj (project) ---

Proj Title=Lacy 123 Base Level Engineering
Current Plan=p01
Default Exp/Contr=0.3,0.1
English Units
Geom File=g01
Flow File=f01
Plan File=p01
BEGIN DESCRIPTION:
Lacy 123
END DESCRIPTION:

--- Lacy 123.p01 (plan) ---

Plan Title=Multiple Run
Short Identifier=Multiple
Geom File=g01
Flow File=f01
Subcritical Flow
K Sum by GR= 0
Std Step Tol= 0.01
Critical Tol= 0.01
Num of Std Step Trials= 20
Max Error Tol= 0.3
Flow Tol Ratio= 0.001
Split Flow NTrial= 30
Split Flow Tol= 0.02
Split Flow Ratio= 0.02
Log Output Level= 0
Friction Slope Method= 1
Unsteady Friction Slope Method= 2
Unsteady Bridges Friction Slope Method= 1
Parabolic Critical Depth
Global Vel Dist=  1 , 1 , 1
Global Log Level= 0
CheckData=True
Encroach Param= -1, 0, 0, 0
BEGIN DESCRIPTION:
Multiple Run
END DESCRIPTION:

--- Lacy 123.f01 (steady flow) ---

Flow Title=Multiple
Number of Profiles=7
Profile Names=10-year,25-year,50-year,1pct_min,100-year,1pct_plu,500-year
River Rch & RM= Lacy 123,Reach-1,9731
     326     418     489     285     568    1134     764
River Rch & RM= Lacy 123,Reach-1,7912
     569     757     907     540    1077    2149    1517
River Rch & RM= Lacy 123,Reach-1,7151
     872    1190    1451     877    1750    3492    2544
Boundary for River Rch & Prof#=Lacy 123,Reach-1,1
Up Type=0
Dn Type=3
Dn Slope=0.005
Boundary for River Rch & Prof#=Lacy 123,Reach-1,2
Up Type=0
Dn Type=3
Dn Slope=0.005
Boundary for River Rch & Prof#=Lacy 123,Reach-1,3
Up Type=0
Dn Type=3
Dn Slope=0.005
Boundary for River Rch & Prof#=Lacy 123,Reach-1,4
Up Type=0
Dn Type=3
Dn Slope=0.005
Boundary for River Rch & Prof#=Lacy 123,Reach-1,5
Up Type=0
Dn Type=3
Dn Slope=0.005
Boundary for River Rch & Prof#=Lacy 123,Reach-1,6
Up Type=0
Dn Type=3
Dn Slope=0.005
Boundary for River Rch & Prof#=Lacy 123,Reach-1,7
Up Type=0
Dn Type=3
Dn Slope=0.005

--- Lacy 123.g01 (geometry) ---

Geom Title=Existing Conditions

River Reach=Lacy 123,Reach-1
Reach XY= 30
      2729026.00      6860211.00      2728933.98      6860357.67
      2728967.75      6860414.23      2728872.36      6860659.50
      2728783.84      6860757.60      2728824.35      6860854.96
      2728732.07      6860952.89      2728562.64      6860974.63
      2728424.57      6861157.93      2728123.29      6861116.26
      2728019.96      6861309.72      2727915.45      6861262.11
      2727789.20      6861297.25      2727768.33      6861517.52
      2727576.00      6861611.00      2727520.48      6861863.43
      2727378.06      6862016.85      2727349.97      6862538.19
      2727109.33      6862677.65      2726399.47      6863437.98
      2726109.33      6863627.65      2725485.80      6864250.52
      2724819.79      6864368.80      2724712.61      6864574.33
      2724445.62      6864740.52      2724215.22      6865120.68
      2723942.68      6865394.36      2723248.76      6865686.87
      2723120.53      6866113.45      2722926.00      6866261.00

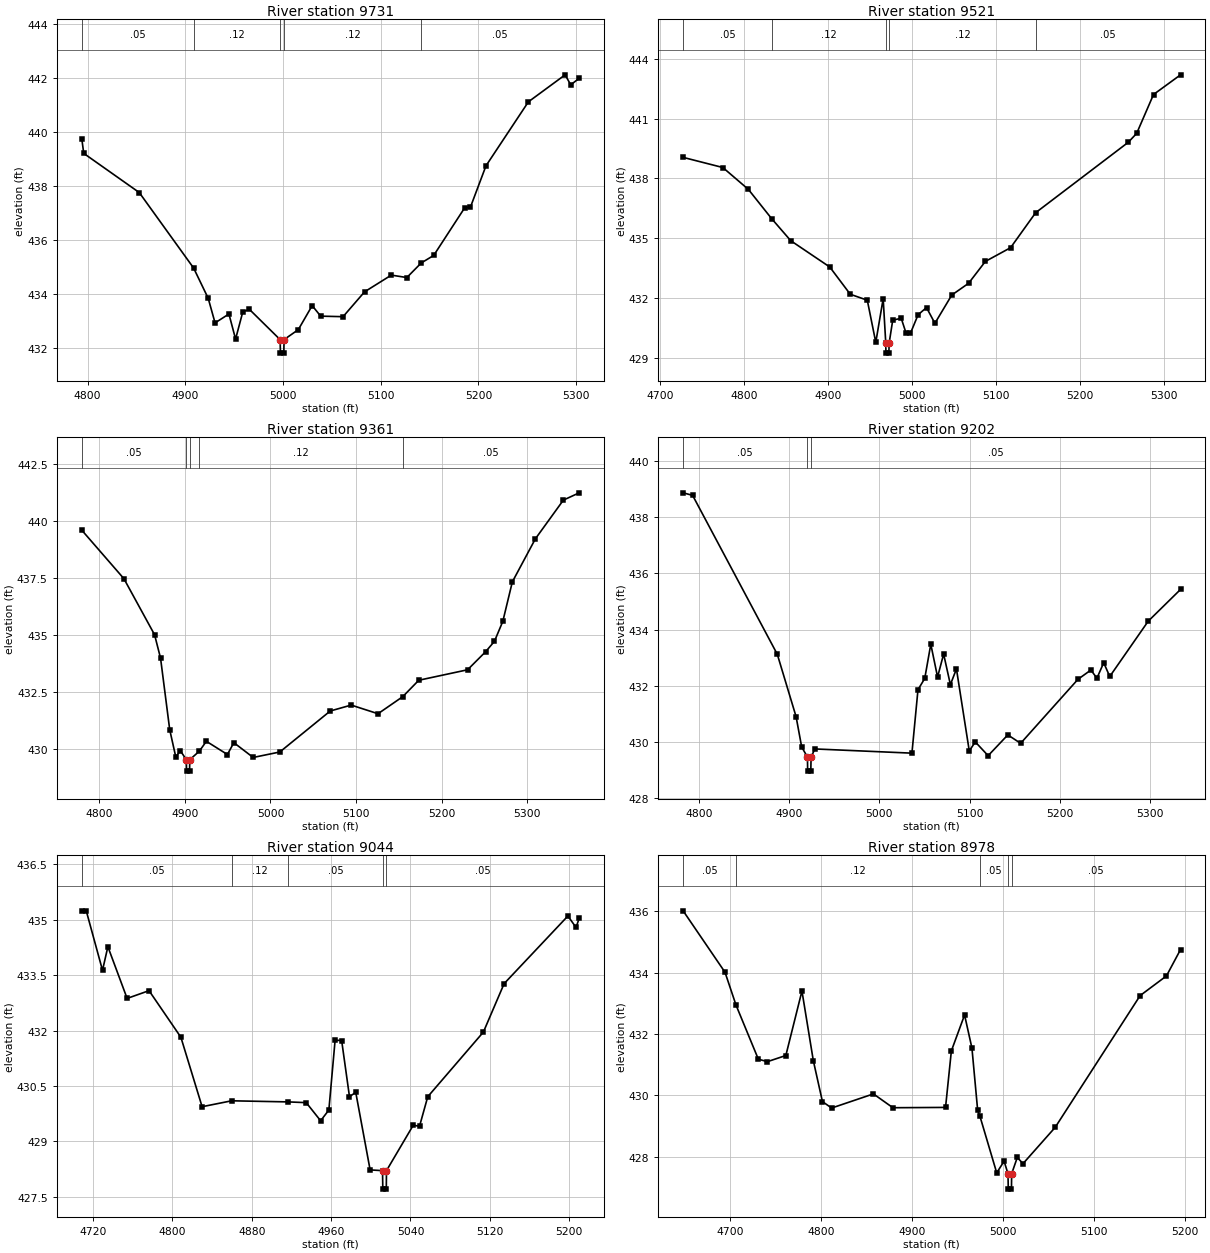
Type RM Length L Ch R = 1,9731,210,210,210
BEGIN DESCRIPTION:
Lacy 123 1337
END DESCRIPTION:
XS GIS Cut Line= 3
      2728830.66      6860163.57      2728982.43      6860302.86
      2729246.71      6860451.27
#Sta/Elev= 30
  4794.0  439.76  4796.0  439.22  4852.8  437.77  4908.5  434.97  4923.4  433.85
  4930.4  432.94  4944.6  433.27  4951.4  432.34  4958.8  433.35  4965.6  433.44
  4997.0  432.32  4997.3  431.82  5000.8  431.82  5001.0  432.32  5015.6  432.69
  5029.8  433.58  5038.5  433.19  5061.4  433.17  5083.4  434.09  5110.8  434.71
  5126.7  434.62  5141.4  435.16  5154.2  435.44  5186.0  437.21  5191.8  437.23
  5207.7  438.76  5251.1  441.13  5288.7  442.13  5294.4  441.76  5303.1  442.00
#Mann=5,-1,0
  4794.0    0.05       0  4908.5    0.12       0  4997.0    0.07       0
  5001.0    0.12       0  5141.4    0.05       0
Bank Sta=4997,5001
Exp/Cntr=0.3,0.1

Type RM Length L Ch R = 1,9521,160,160,160
BEGIN DESCRIPTION:
Lacy 123 1336
END DESCRIPTION:
XS GIS Cut Line= 3
      2728659.21      6860429.70      2728922.57      6860469.65
      2729248.13      6860485.09
#Sta/Elev= 30
  4727.3  439.06  4774.6  438.55  4805.0  437.45  4832.7  435.98  4855.5  434.87
  4901.9  433.55  4926.3  432.18  4946.6  431.88  4956.7  429.76  4965.5  431.96
  4968.6  429.72  4968.8  429.22  4972.3  429.22  4972.6  429.72  4976.9  430.88
  4987.0  430.97  4992.9  430.21  4997.9  430.21  5007.1  431.15  5017.1  431.51
  5027.1  430.72  5047.2  432.14  5067.2  432.73  5087.2  433.83  5117.2  434.52
  5147.1  436.28  5257.4  439.82  5267.4  440.27  5287.4  442.22  5319.6  443.21
#Mann=5,-1,0
  4727.3    0.05       0  4832.7    0.12       0  4968.6    0.07       0
  4972.6    0.12       0  5147.1    0.05       0
Bank Sta=4968.6,4972.6
Exp/Cntr=0.3,0.1

Type RM Length L Ch R = 1,9361,159,159,159
BEGIN DESCRIPTION:
Lacy 123 1335
END DESCRIPTION:
XS GIS Cut Line= 3
      2728669.95      6860536.46      2728881.68      6860616.76
      2729220.61      6860720.84
#Sta/Elev= 30
  4779.6  439.61  4828.8  437.48  4864.6  435.02  4871.6  433.99  4882.3  430.85
  4889.4  429.65  4894.7  429.93  4901.7  429.53  4902.0  429.03  4905.5  429.03
  4905.7  429.53  4917.0  429.91  4925.1  430.34  4949.7  429.76  4957.2  430.28
  4979.8  429.63  5010.9  429.87  5069.8  431.67  5094.3  431.93  5125.6  431.55
  5154.5  432.30  5173.2  433.02  5230.2  433.48  5251.2  434.27  5261.6  434.73
  5271.4  435.61  5282.5  437.34  5309.4  439.23  5342.1  440.93  5360.6  441.25
#Mann=5,-1,0
  4779.6    0.05       0  4901.7    0.07       0  4905.7    0.05       0
  4917.0    0.12       0  5154.5    0.05       0
Bank Sta=4901.7,4905.7
Exp/Cntr=0.3,0.1

Type RM Length L Ch R = 1,9202,158,158,158
BEGIN DESCRIPTION:
Lacy 123 1325
END DESCRIPTION:
XS GIS Cut Line= 3
      2728664.81      6860567.50      2728799.34      6860747.31
      2729016.00      6860991.35
#Sta/Elev= 30
  4782.7  438.87  4793.2  438.78  4887.0  433.12  4907.8  430.90  4914.0  429.82
  4920.4  429.46  4920.6  428.96  4924.1  428.96  4924.4  429.46  4928.6  429.75
  5036.1  429.60  5042.8  431.86  5050.3  432.26  5057.0  433.48  5064.5  432.31
  5071.2  433.13  5078.7  432.04  5085.4  432.60  5099.6  429.68  5106.3  430.00
  5120.5  429.51  5142.3  430.25  5156.5  429.95  5220.0  432.23  5234.3  432.56
  5241.0  432.27  5248.5  432.82  5255.2  432.33  5297.8  434.30  5333.6  435.43
#Mann=3,-1,0
  4782.7    0.05       0  4920.4    0.05       0  4924.4    0.05       0
Bank Sta=4920.4,4924.4
Exp/Cntr=0.3,0.1

Type RM Length L Ch R = 1,9044,66,66,66
BEGIN DESCRIPTION:
Lacy 123 1324
END DESCRIPTION:
XS GIS Cut Line= 3
      2728663.16      6860637.58      2728731.60      6860818.45
      2728976.04      6861006.02
#Sta/Elev= 30
  4708.6  435.24  4713.1  435.24  4729.5  433.63  4734.9  434.27  4754.3  432.87
  4776.4  433.08  4808.5  431.82  4829.9  429.94  4859.7  430.10  4916.8  430.07
  4934.9  430.05  4949.4  429.56  4957.7  429.85  4964.0  431.74  4970.6  431.73
  4978.5  430.21  4984.8  430.33  4999.3  428.23  5011.8  428.21  5012.1  427.71
  5015.6  427.71  5015.8  428.21  5042.8  429.44  5049.1  429.41  5057.4  430.21
  5113.5  431.96  5134.4  433.27  5198.7  435.10  5206.9  434.79  5210.1  435.04
#Mann=5,-1,0
  4708.6    0.05       0  4859.7    0.12       0  4916.8    0.05       0
  5011.8    0.05       0  5015.8    0.05       0
Bank Sta=5011.8,5015.8
Exp/Cntr=0.3,0.1

Type RM Length L Ch R = 1,8978,38,38,38
BEGIN DESCRIPTION:
Lacy 123 1323
END DESCRIPTION:
XS GIS Cut Line= 3
      2728625.94      6860628.95      2728649.68      6860837.31
      2728915.68      6861043.55
#Sta/Elev= 30
  4648.5  436.01  4694.5  434.01  4706.6  432.94  4731.1  431.18  4741.1  431.10
  4761.3  431.30  4779.0  433.40  4791.5  431.13  4801.5  429.80  4811.6  429.59
  4857.5  430.05  4878.9  429.60  4936.7  429.61  4943.1  431.45  4957.6  432.62
  4965.7  431.54  4972.0  429.51  4974.3  429.34  4992.9  427.48  5001.0  427.86
  5005.3  427.45  5005.6  426.95  5009.1  426.95  5009.3  427.45  5015.5  427.98
  5021.8  427.78  5057.1  428.96  5150.4  433.25  5179.3  433.89  5194.8  434.75
#Mann=5,-1,0
  4648.5    0.05       0  4706.6    0.12       0  4974.3    0.05       0
  5005.3    0.04       0  5009.3    0.05       0
Bank Sta=5005.3,5009.3
Exp/Cntr=0.3,0.1

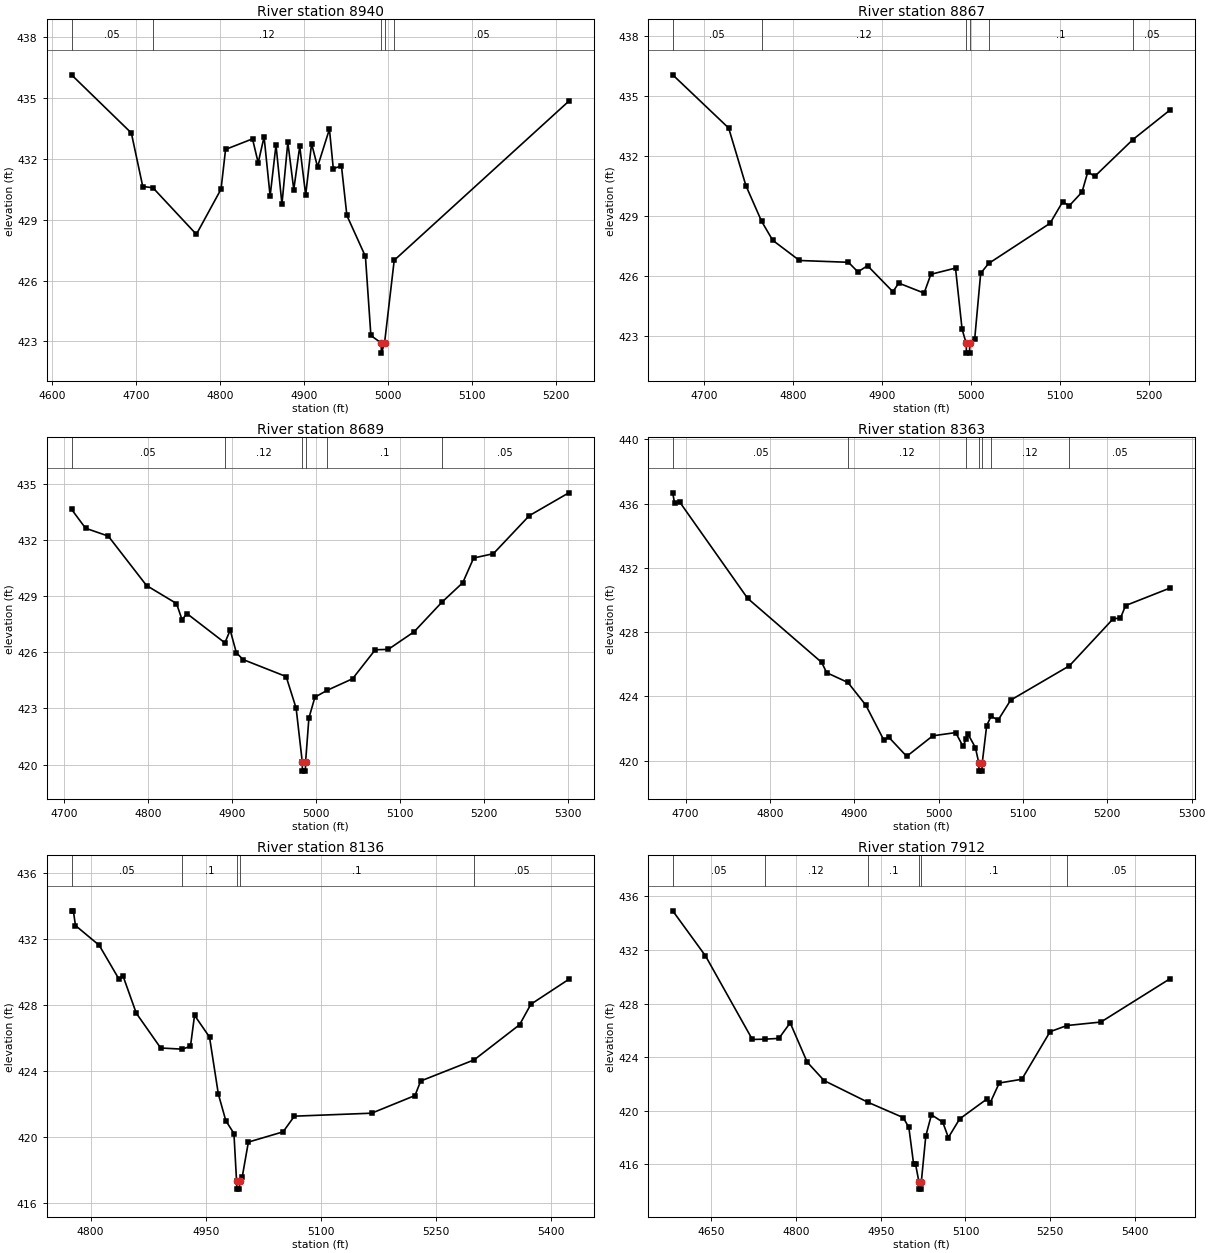
Type RM Length L Ch R = 1,8940,73,73,73
BEGIN DESCRIPTION:
Lacy 123 1321
END DESCRIPTION:
XS GIS Cut Line= 4
      2728533.14      6860642.38      2728612.26      6860836.43
      2728687.59      6860910.93      2728899.21      6861089.95
#Sta/Elev= 30
  4623.1  436.15  4694.4  433.28  4708.0  430.64  4720.1  430.58  4771.9  428.28
  4801.3  430.51  4806.7  432.47  4838.8  432.99  4845.6  431.81  4852.6  433.09
  4859.8  430.17  4866.8  432.69  4873.9  429.77  4880.9  432.82  4888.0  430.49
  4895.1  432.62  4902.2  430.22  4909.2  432.76  4916.3  431.61  4930.5  433.47
  4935.1  431.52  4944.8  431.66  4951.3  429.21  4973.4  427.19  4979.9  423.29
  4992.2  422.92  4992.4  422.42  4996.2  422.92  5007.7  427.00  5215.8  434.85
#Mann=5,-1,0
  4623.1    0.05       0  4720.1    0.12       0  4992.2    0.07       0
  4996.2    0.12       0  5007.7    0.05       0
Bank Sta=4992.2,4996.2
Exp/Cntr=0.3,0.1

Type RM Length L Ch R = 1,8867,178,178,178
BEGIN DESCRIPTION:
Lacy 123 1322
END DESCRIPTION:
XS GIS Cut Line= 3
      2728510.14      6860683.38      2728584.81      6860879.95
      2728814.30      6861142.52
#Sta/Elev= 30
  4665.1  436.05  4728.0  433.39  4747.4  430.51  4765.0  428.73  4777.5  427.78
  4807.6  426.77  4862.6  426.68  4873.3  426.20  4884.1  426.51  4912.6  425.21
  4919.2  425.64  4947.7  425.14  4955.3  426.08  4983.0  426.39  4990.4  423.33
  4995.0  422.64  4995.3  422.14  4998.8  422.14  4999.0  422.64  5004.6  422.86
  5011.3  426.13  5020.2  426.62  5089.3  428.63  5103.4  429.70  5111.0  429.51
  5125.2  430.19  5131.8  431.21  5139.4  430.97  5182.3  432.81  5224.1  434.29
#Mann=6,-1,0
  4665.1    0.05       0  4765.0    0.12       0  4995.0    0.07       0
  4999.0    0.12       0  5020.2     0.1       0  5182.3    0.05       0
Bank Sta=4995,4999
Exp/Cntr=0.3,0.1

Type RM Length L Ch R = 1,8689,326,326,326
BEGIN DESCRIPTION:
Lacy 123 1320
END DESCRIPTION:
XS GIS Cut Line= 3
      2728369.46      6860765.78      2728528.82      6861013.71
      2728684.72      6861267.64
#Sta/Elev= 30
  4708.8  433.63  4725.5  432.62  4752.6  432.20  4798.2  429.56  4833.9  428.60
  4840.5  427.74  4846.4  428.06  4891.6  426.50  4897.9  427.18  4905.2  425.98
  4913.1  425.61  4964.6  424.70  4976.5  423.01  4983.8  420.15  4984.0  419.65
  4987.5  419.65  4987.8  420.15  4991.7  422.48  4998.9  423.60  5013.7  423.97
  5043.7  424.58  5070.8  426.13  5086.3  426.15  5117.1  427.09  5150.0  428.66
  5175.1  429.71  5188.1  431.03  5211.6  431.26  5254.4  433.29  5301.5  434.51
#Mann=6,-1,0
  4708.8    0.05       0  4891.6    0.12       0  4983.8    0.07       0
  4987.8    0.12       0  5013.7     0.1       0  5150.0    0.05       0
Bank Sta=4983.8,4987.8
Exp/Cntr=0.3,0.1

Type RM Length L Ch R = 1,8363,227,227,227
BEGIN DESCRIPTION:
Lacy 123 1300
END DESCRIPTION:
XS GIS Cut Line= 3
      2728139.19      6860865.14      2728306.02      6861139.23
      2728462.40      6861357.65
#Sta/Elev= 30
  4684.8  436.67  4687.0  436.02  4692.9  436.11  4773.6  430.10  4861.4  426.11
  4867.3  425.47  4892.5  424.86  4913.7  423.45  4935.0  421.28  4940.8  421.46
  4962.2  420.26  4993.1  421.54  5020.3  421.74  5028.9  420.88  5032.6  421.33
  5035.0  421.63  5043.6  420.81  5047.7  419.84  5048.0  419.34  5051.5  419.34
  5051.7  419.84  5057.0  422.17  5062.2  422.76  5070.6  422.52  5085.4  423.76
  5155.1  425.90  5207.0  428.83  5215.6  428.87  5221.7  429.65  5274.3  430.74
#Mann=7,-1,0
  4684.8    0.05       0  4892.5    0.12       0  5032.6     0.1       0
  5047.7    0.07       0  5051.7     0.1       0  5062.2    0.12       0
  5155.1    0.05       0
Bank Sta=5047.7,5051.7
Exp/Cntr=0.3,0.1

Type RM Length L Ch R = 1,8136,224,224,224
BEGIN DESCRIPTION:
Lacy 123 1299
END DESCRIPTION:
XS GIS Cut Line= 3
      2728029.23      6860921.43      2728106.30      6861141.48
      2728442.54      6861383.78
#Sta/Elev= 30
  4775.1  433.73  4777.5  433.73  4780.2  432.84  4811.2  431.64  4836.9  429.59
  4842.2  429.78  4859.4  427.53  4891.2  425.42  4919.2  425.35  4930.0  425.52
  4935.3  427.40  4954.8  426.08  4966.3  422.63  4976.0  421.02  4986.6  420.24
  4990.0  417.37  4990.3  416.87  4993.8  416.87  4994.0  417.37  4997.3  417.58
  5005.4  419.72  5050.6  420.34  5065.3  421.29  5165.9  421.47  5222.4  422.54
  5229.8  423.42  5299.4  424.70  5358.6  426.83  5373.3  428.07  5422.7  429.58
#Mann=5,-1,0
  4775.1    0.05       0  4919.2     0.1       0  4990.0    0.07       0
  4994.0     0.1       0  5299.4    0.05       0
Bank Sta=4990,4994
Exp/Cntr=0.3,0.1

Type RM Length L Ch R = 1,7912,211,211,211
BEGIN DESCRIPTION:
Lacy 123 1297
END DESCRIPTION:
XS GIS Cut Line= 3
      2727997.61      6860893.01      2728008.09      6861322.74
      2728018.08      6861773.27
#Sta/Elev= 30
  4581.6  434.92  4639.6  431.56  4722.6  425.32  4744.2  425.34  4769.6  425.40
  4789.6  426.56  4819.7  423.63  4849.7  422.25  4927.4  420.63  4989.7  419.49
  4999.7  418.76  5008.1  416.04  5011.5  416.04  5017.7  414.65  5018.0  414.15
  5021.5  414.15  5021.7  414.65  5029.7  418.11  5039.7  419.70  5059.7  419.15
  5069.7  418.00  5089.7  419.39  5138.7  420.90  5143.7  420.59  5159.8  422.07
  5199.8  422.35  5249.8  425.90  5279.7  426.36  5339.8  426.62  5462.1  429.85
#Mann=6,-1,0
  4581.6    0.05       0  4744.2    0.12       0  4927.4     0.1       0
  5017.7    0.07       0  5021.7     0.1       0  5279.7    0.05       0
Bank Sta=5017.7,5021.7
Exp/Cntr=0.3,0.1

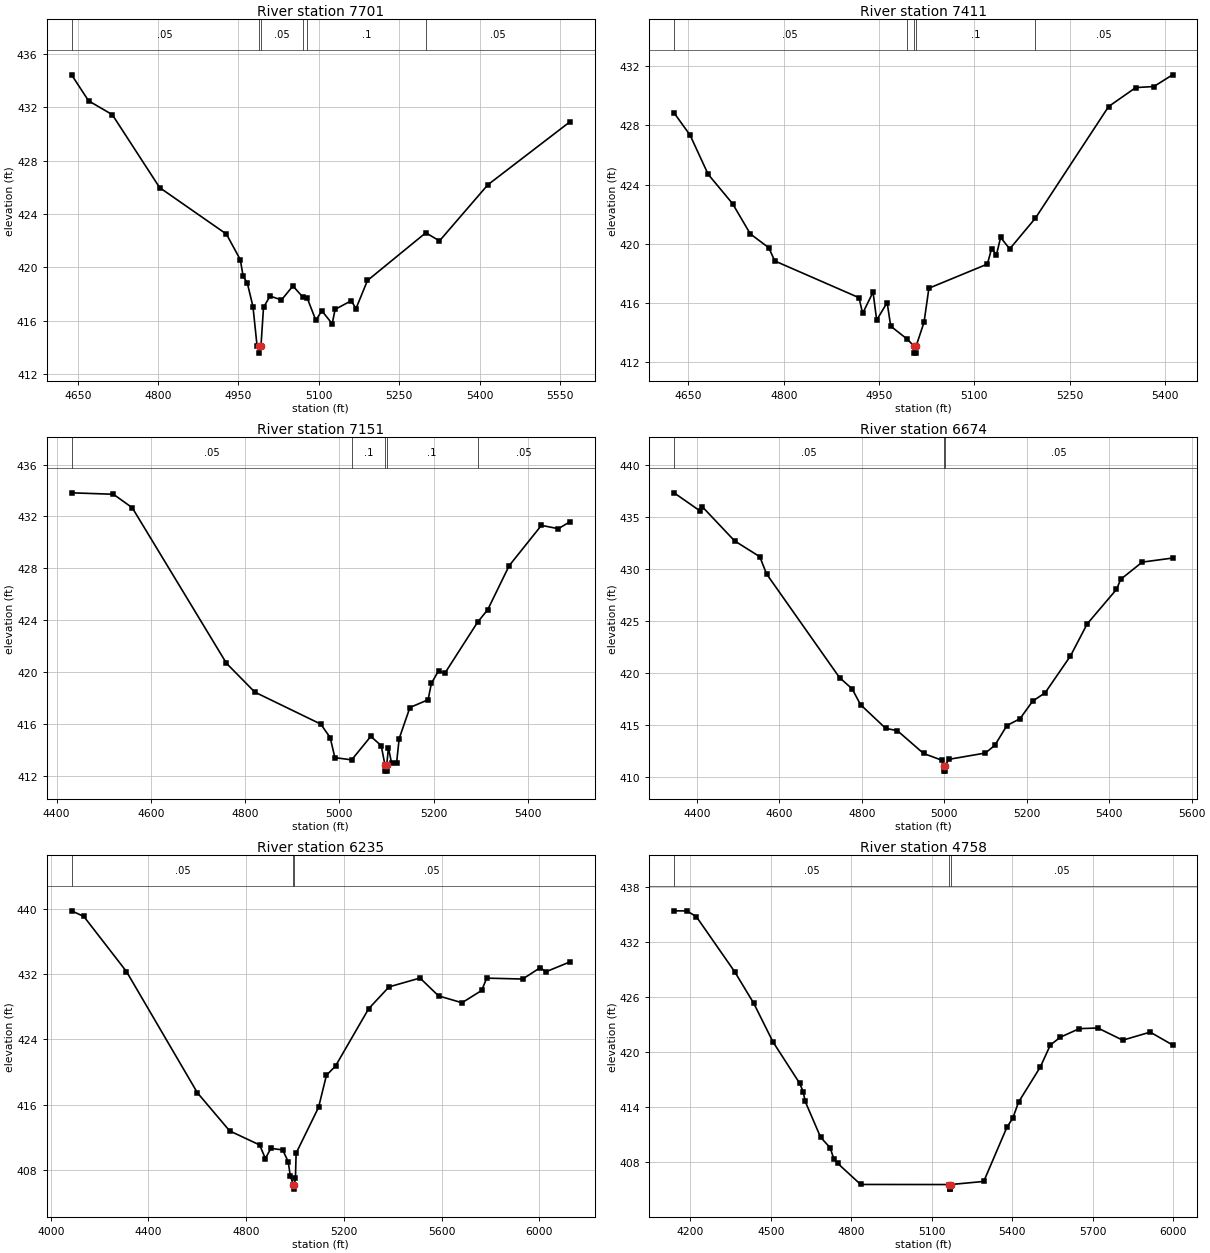
Type RM Length L Ch R = 1,7701,290,290,290
BEGIN DESCRIPTION:
Lacy 123 1298
END DESCRIPTION:
XS GIS Cut Line= 3
      2727697.23      6860931.04      2727815.46      6861273.20
      2728017.36      6861804.42
#Sta/Elev= 30
  4638.6  434.45  4670.3  432.50  4714.6  431.46  4802.9  425.99  4927.6  422.50
  4953.5  420.58  4958.8  419.33  4966.5  418.84  4977.1  417.06  4984.7  414.14
  4988.0  414.07  4988.2  413.57  4992.0  414.07  4996.8  417.00  5009.0  417.85
  5030.3  417.56  5051.7  418.61  5070.5  417.76  5078.0  417.74  5094.5  416.03
  5105.6  416.75  5125.0  415.77  5130.4  416.85  5160.5  417.50  5169.4  416.91
  5190.8  419.02  5299.7  422.60  5325.2  421.99  5415.5  426.20  5568.9  430.93
#Mann=6,-1,0
  4638.6    0.05       0  4988.0    0.05       0  4992.0    0.05       0
  5070.5    0.12       0  5078.0     0.1       0  5299.7    0.05       0
Bank Sta=4988,4992
Exp/Cntr=0.3,0.1

Type RM Length L Ch R = 1,7411,260,260,260
BEGIN DESCRIPTION:
Lacy 123 1296
END DESCRIPTION:
XS GIS Cut Line= 3
      2727576.18      6861208.67      2727747.58      6861538.30
      2728019.24      6861849.47
#Sta/Elev= 30
  4627.3  428.84  4652.5  427.34  4680.9  424.70  4719.5  422.71  4747.2  420.68
  4776.4  419.74  4785.8  418.85  4918.4  416.37  4924.1  415.31  4940.5  416.75
  4946.2  414.86  4962.7  416.04  4968.3  414.45  4993.2  413.61  5004.5  413.13
  5004.8  412.63  5008.3  412.63  5008.5  413.13  5020.8  414.72  5028.4  417.01
  5120.5  418.64  5127.1  419.69  5134.7  419.26  5141.3  420.44  5155.6  419.66
  5196.1  421.74  5311.3  429.27  5354.0  430.55  5382.5  430.62  5411.9  431.41
#Mann=5,-1,0
  4627.3    0.05       0  4993.2     0.1       0  5004.5    0.07       0
  5008.5     0.1       0  5196.1    0.05       0
Bank Sta=5004.5,5008.5
Exp/Cntr=0.3,0.1

Type RM Length L Ch R = 1,7151,477,477,477
BEGIN DESCRIPTION:
Lacy 123 1295
END DESCRIPTION:
XS GIS Cut Line= 3
      2727007.31      6861676.82      2727577.06      6861672.85
      2728018.54      6861880.64
#Sta/Elev= 30
  4432.0  433.82  4520.7  433.71  4560.7  432.67  4760.7  420.66  4820.7  418.44
  4960.7  415.97  4980.7  414.93  4990.7  413.38  5026.3  413.21  5066.9  415.02
  5089.0  414.31  5096.8  412.84  5097.1  412.34  5100.6  412.34  5100.8  412.84
  5104.3  414.13  5111.1  412.95  5121.6  412.96  5127.1  414.85  5149.9  417.25
  5188.5  417.85  5195.5  419.12  5210.6  420.08  5223.8  419.88  5293.4  423.83
  5315.0  424.80  5360.6  428.20  5429.0  431.31  5464.8  431.05  5489.7  431.59
#Mann=5,-1,0
  4432.0    0.05       0  5026.3     0.1       0  5096.8    0.05       0
  5100.8     0.1       0  5293.4    0.05       0
Bank Sta=5096.8,5100.8
Exp/Cntr=0.3,0.1

Type RM Length L Ch R = 1,6674,439,439,439
BEGIN DESCRIPTION:
Lacy 123 1293
END DESCRIPTION:
XS GIS Cut Line= 3
      2726731.86      6861953.52      2727349.33      6862071.88
      2727919.37      6862180.49
#Sta/Elev= 30
  4344.6  437.29  4407.9  435.54  4412.9  435.96  4491.4  432.67  4552.5  431.15
  4569.0  429.49  4745.9  419.53  4776.5  418.45  4796.8  416.93  4857.9  414.65
  4886.2  414.43  4949.6  412.24  4995.3  411.57  4998.5  411.04  4998.7  410.54
  5002.2  410.54  5002.5  411.04  5010.6  411.67  5099.7  412.28  5122.6  413.02
  5151.8  414.92  5183.7  415.58  5214.2  417.26  5244.8  418.08  5305.9  421.60
  5346.6  424.69  5417.7  428.01  5428.0  428.98  5480.1  430.63  5553.6  431.02
#Mann=3,-1,0
  4344.6    0.05       0  4998.5    0.04       0  5002.5    0.05       0
Bank Sta=4998.5,5002.5
Exp/Cntr=0.3,0.1

Type RM Length L Ch R = 1,6235,1477,1477,1477
BEGIN DESCRIPTION:
Lacy 123 1294
END DESCRIPTION:
XS GIS Cut Line= 3
      2726587.96      6862040.07      2727375.57      6862518.43
      2728440.49      6862862.42
#Sta/Elev= 30
  4085.4  439.72  4135.6  439.03  4310.0  432.30  4600.7  417.46  4732.5  412.81
  4855.3  411.09  4878.7  409.43  4901.1  410.67  4949.6  410.49  4972.3  409.03
  4980.6  407.32  4993.7  406.19  4993.9  405.69  4997.7  406.19  5001.9  407.09
  5004.6  410.08  5096.6  415.70  5128.7  419.61  5166.0  420.75  5301.6  427.75
  5384.9  430.42  5511.8  431.50  5587.6  429.32  5683.7  428.48  5764.0  429.98
  5785.0  431.49  5932.1  431.38  6004.0  432.77  6026.7  432.26  6126.0  433.48
#Mann=3,-1,0
  4085.4    0.05       0  4993.7    0.04       0  4997.7    0.05       0
Bank Sta=4993.7,4997.7
Exp/Cntr=0.3,0.1

Type RM Length L Ch R = 1,4758,845,845,845
BEGIN DESCRIPTION:
Lacy 123 1289
END DESCRIPTION:
XS GIS Cut Line= 3
      2725772.54      6862807.31      2726301.93      6863481.52
      2726794.78      6864353.46
#Sta/Elev= 30
  4139.6  435.45  4187.2  435.44  4222.5  434.82  4365.3  428.81  4436.7  425.35
  4508.1  421.15  4607.5  416.63  4621.1  415.70  4628.3  414.65  4686.1  410.71
  4721.4  409.58  4735.9  408.31  4750.3  407.85  4835.3  405.56  5166.4  405.55
  5166.7  405.05  5170.3  405.05  5170.7  405.55  5294.4  405.89  5381.0  411.82
  5402.7  412.80  5424.3  414.56  5505.2  418.38  5542.7  420.79  5580.3  421.65
  5651.0  422.58  5719.9  422.65  5812.7  421.32  5915.2  422.20  5998.4  420.80
#Mann=3,-1,0
  4139.6    0.05       0  5166.4    0.03       0  5170.7    0.05       0
Bank Sta=5166.4,5170.7
Exp/Cntr=0.3,0.1

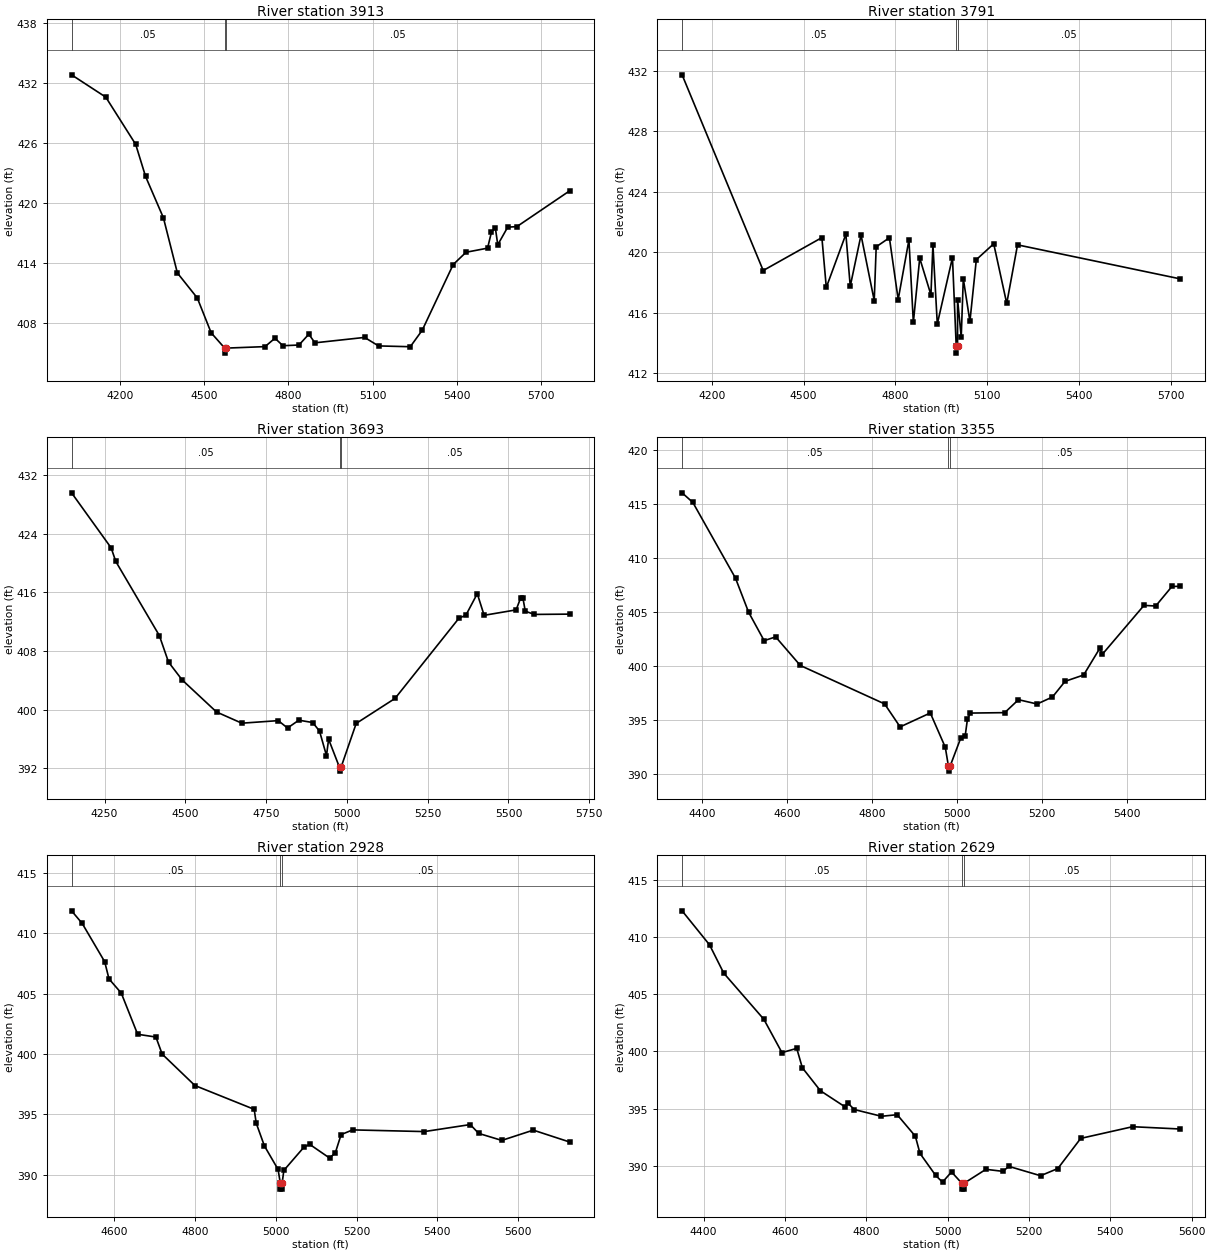
Type RM Length L Ch R = 1,3913,122,122,122
BEGIN DESCRIPTION:
Lacy 123 1285
END DESCRIPTION:
XS GIS Cut Line= 4
      2725048.49      6863316.98      2725690.45      6864054.14
      2725956.72      6864327.56      2726321.62      6864521.08
#Sta/Elev= 30
  4028.2  432.83  4150.0  430.60  4256.4  425.88  4291.5  422.68  4355.1  418.54
  4404.8  413.03  4475.7  410.53  4525.0  407.05  4573.2  405.52  4573.6  405.02
  4577.6  405.52  4716.8  405.67  4752.0  406.51  4780.4  405.76  4837.4  405.83
  4872.5  406.91  4894.4  406.05  5071.1  406.59  5120.6  405.74  5233.7  405.66
  5276.2  407.31  5386.3  413.87  5432.1  415.10  5508.7  415.51  5522.4  417.10
  5536.4  417.53  5545.0  415.85  5580.4  417.61  5612.9  417.66  5800.4  421.23
#Mann=3,-1,0
  4028.2    0.05       0  4573.2    0.05       0  4577.6    0.05       0
Bank Sta=4573.2,4577.6
Exp/Cntr=0.3,0.1

Type RM Length L Ch R = 1,3791,98,98,98
BEGIN DESCRIPTION:
Lacy 123 1284
END DESCRIPTION:
XS GIS Cut Line= 4
      2725032.26      6863442.25      2725603.77      6864139.52
      2725837.25      6864394.86      2726151.82      6864604.90
#Sta/Elev= 30
  4103.3  431.74  4368.1  418.78  4559.7  420.96  4574.1  417.66  4638.0  421.18
  4652.3  417.74  4687.5  421.13  4730.6  416.79  4737.0  420.35  4780.1  420.95
  4808.8  416.86  4843.9  420.81  4858.3  415.34  4879.1  419.60  4915.7  417.17
  4922.2  420.48  4936.5  415.24  4986.0  419.64  4998.2  413.81  4998.6  413.31
  5002.6  413.81  5002.7  416.86  5014.6  414.38  5021.4  418.24  5043.0  415.41
  5063.9  419.50  5120.7  420.55  5163.2  416.60  5198.4  420.48  5729.1  418.23
#Mann=3,-1,0
  4103.3    0.05       0  4998.2    0.04       0  5002.6    0.05       0
Bank Sta=4998.2,5002.6
Exp/Cntr=0.3,0.1

Type RM Length L Ch R = 1,3693,338,338,338
BEGIN DESCRIPTION:
Lacy 123 1283
END DESCRIPTION:
XS GIS Cut Line= 3
      2724970.80      6863563.24      2725538.54      6864212.92
      2726017.40      6864693.33
#Sta/Elev= 30
  4147.9  429.59  4270.4  422.08  4284.7  420.23  4419.5  410.12  4447.9  406.50
  4490.2  404.06  4596.5  399.69  4674.8  398.16  4787.7  398.51  4816.2  397.50
  4851.3  398.57  4894.1  398.25  4915.2  397.09  4936.8  393.74  4943.4  395.97
  4977.2  392.12  4977.7  391.62  4981.7  392.12  5028.8  398.13  5149.0  401.54
  5346.9  412.49  5368.2  412.89  5403.5  415.83  5424.7  412.88  5523.7  413.62
  5537.9  415.27  5544.9  415.20  5552.0  413.44  5580.3  413.00  5689.0  413.04
#Mann=3,-1,0
  4147.9    0.05       0  4977.2    0.04       0  4981.7    0.05       0
Bank Sta=4977.2,4981.7
Exp/Cntr=0.3,0.1

Type RM Length L Ch R = 1,3355,427,427,427
BEGIN DESCRIPTION:
Lacy 123 1286
END DESCRIPTION:
XS GIS Cut Line= 3
      2724887.68      6863754.45      2725229.40      6864305.60
      2725690.48      6864553.74
#Sta/Elev= 30
  4353.5  416.03  4378.8  415.14  4479.2  408.12  4510.0  404.97  4546.6  402.33
  4573.7  402.68  4631.8  400.03  4830.1  396.47  4866.7  394.34  4937.7  395.63
  4973.0  392.45  4980.2  390.74  4980.7  390.24  4984.7  390.74  5009.5  393.32
  5019.6  393.45  5025.2  395.07  5032.2  395.62  5112.9  395.66  5145.3  396.86
  5189.1  396.46  5225.3  397.11  5254.9  398.56  5298.7  399.15  5336.8  401.63
  5342.5  401.06  5440.7  405.60  5468.2  405.54  5506.4  407.35  5525.6  407.37
#Mann=3,-1,0
  4353.5    0.05       0  4980.2    0.04       0  4984.7    0.05       0
Bank Sta=4980.2,4984.7
Exp/Cntr=0.3,0.1

Type RM Length L Ch R = 1,2928,299,299,299
BEGIN DESCRIPTION:
Lacy 123 1305
END DESCRIPTION:
XS GIS Cut Line= 3
      2724736.78      6863869.56      2724819.79      6864368.80
      2725287.10      6864926.76
#Sta/Elev= 30
  4493.9  411.84  4520.2  410.80  4576.0  407.63  4586.6  406.21  4617.0  405.04
  4657.6  401.63  4702.9  401.40  4718.4  399.99  4799.5  397.39  4946.4  395.42
  4951.5  394.27  4971.8  392.39  5005.6  390.45  5011.1  389.32  5011.6  388.82
  5015.2  388.82  5015.7  389.32  5019.9  390.37  5069.4  392.28  5083.7  392.53
  5133.3  391.39  5147.5  391.83  5161.8  393.33  5190.4  393.72  5368.1  393.58
  5481.8  394.16  5502.7  393.43  5559.9  392.85  5638.0  393.70  5727.8  392.72
#Mann=3,-1,0
  4493.9    0.05       0  5011.1    0.04       0  5015.7    0.05       0
Bank Sta=5011.1,5015.7
Exp/Cntr=0.3,0.1

Type RM Length L Ch R = 1,2629,350,350,350
BEGIN DESCRIPTION:
Lacy 123 1304
END DESCRIPTION:
XS GIS Cut Line= 3
      2724378.40      6864029.72      2724687.11      6864636.34
      2725085.02      6865006.92
#Sta/Elev= 30
  4347.2  412.27  4414.7  409.30  4449.6  406.83  4548.2  402.80  4592.7  399.89
  4629.1  400.26  4642.8  398.57  4687.3  396.56  4748.4  395.14  4754.0  395.51
  4770.6  394.92  4837.4  394.33  4876.0  394.47  4920.7  392.59  4932.1  391.09
  4970.8  389.16  4987.5  388.58  5009.7  389.47  5035.3  388.47  5035.8  387.97
  5039.4  387.97  5039.9  388.47  5094.3  389.70  5136.3  389.52  5150.4  389.96
  5228.6  389.14  5271.1  389.77  5327.3  392.40  5454.8  393.42  5571.6  393.22
#Mann=3,-1,0
  4347.2    0.05       0  5035.3    0.04       0  5039.9    0.05       0
Bank Sta=5035.3,5039.9
Exp/Cntr=0.3,0.1

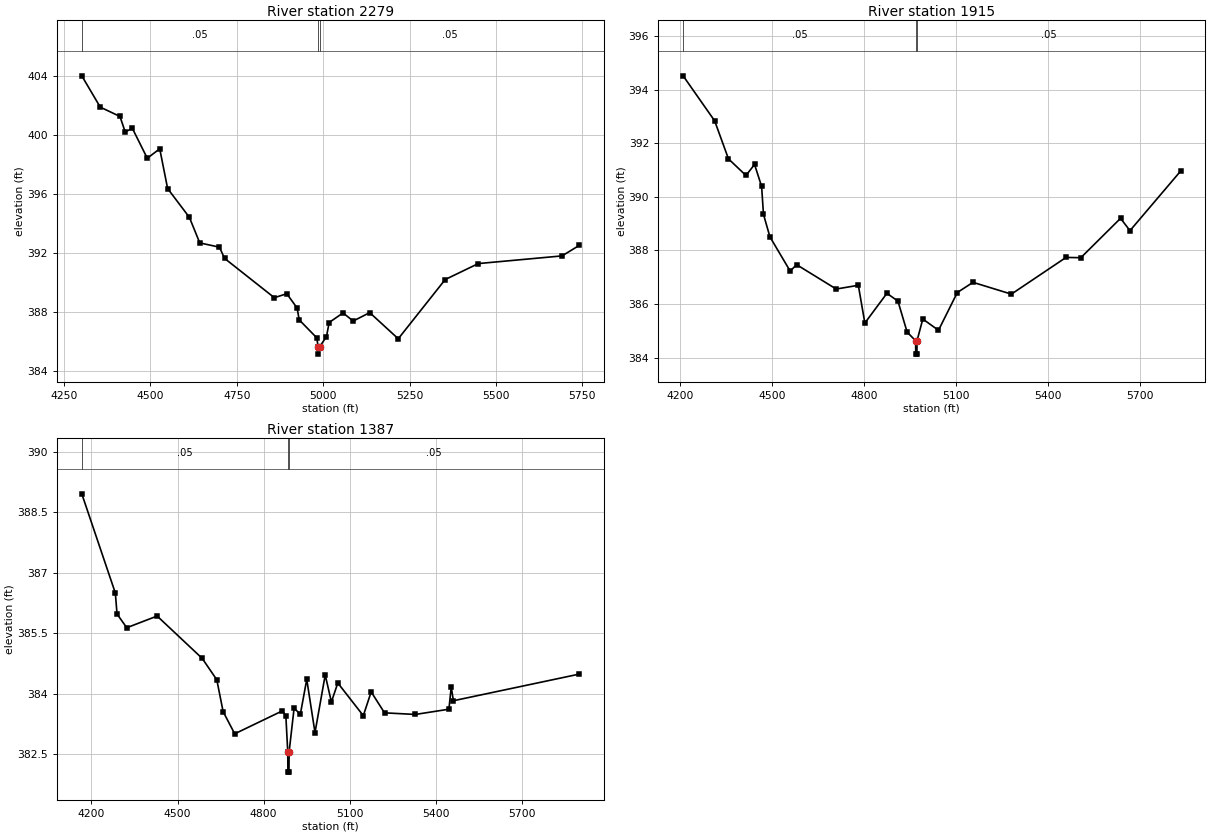
Type RM Length L Ch R = 1,2279,364,364,364
BEGIN DESCRIPTION:
Lacy 123 1303
END DESCRIPTION:
XS GIS Cut Line= 3
      2724029.61      6864233.87      2724419.89      6864813.16
      2725105.04      6865095.64
#Sta/Elev= 30
  4301.5  403.98  4355.0  401.86  4412.0  401.23  4427.0  400.19  4448.0  400.42
  4491.0  398.40  4527.1  399.04  4549.9  396.35  4612.9  394.40  4642.9  392.67
  4699.9  392.38  4714.8  391.62  4858.8  388.96  4894.8  389.23  4924.7  388.26
  4930.7  387.46  4981.7  386.24  4985.4  385.64  4985.9  385.14  4990.0  385.64
  5009.7  386.33  5017.4  387.28  5057.6  387.93  5086.9  387.38  5134.8  387.95
  5217.4  386.18  5353.3  390.19  5449.1  391.27  5691.5  391.79  5741.1  392.50
#Mann=3,-1,0
  4301.5    0.05       0  4985.4    0.04       0  4990.0    0.05       0
Bank Sta=4985.4,4990
Exp/Cntr=0.3,0.1

Type RM Length L Ch R = 1,1915,528,528,528
BEGIN DESCRIPTION:
Lacy 123 1302
END DESCRIPTION:
XS GIS Cut Line= 3
      2723786.46      6864446.71      2724223.47      6865104.95
      2725037.11      6865287.63
#Sta/Elev= 30
  4209.9  394.52  4312.8  392.84  4357.9  391.42  4415.0  390.80  4443.1  391.21
  4466.2  390.39  4472.2  389.35  4493.2  388.51  4559.4  387.23  4580.4  387.47
  4709.7  386.56  4781.9  386.70  4803.2  385.29  4875.2  386.40  4911.2  386.11
  4941.3  384.95  4969.0  384.63  4969.4  384.13  4973.1  384.13  4973.6  384.63
  4992.4  385.44  5043.6  385.02  5105.1  386.43  5156.3  386.81  5281.6  386.37
  5460.0  387.74  5508.4  387.73  5638.0  389.20  5668.8  388.74  5833.9  390.96
#Mann=3,-1,0
  4209.9    0.05       0  4969.0    0.04       0  4973.6    0.05       0
Bank Sta=4969,4973.6
Exp/Cntr=0.3,0.1

Type RM Length L Ch R = 1,1387,0,0,0
BEGIN DESCRIPTION:
Lacy 123 1301
END DESCRIPTION:
XS GIS Cut Line= 3
      2723607.12      6864648.61      2723835.65      6865450.16
      2724609.76      6865908.26
#Sta/Elev= 30
  4166.5  388.96  4283.4  386.50  4289.3  385.98  4323.2  385.64  4429.0  385.93
  4586.0  384.88  4636.9  384.35  4658.9  383.56  4699.3  383.01  4865.7  383.58
  4877.5  383.45  4884.1  382.56  4884.6  382.06  4888.3  382.06  4888.8  382.56
  4906.1  383.64  4928.1  383.50  4950.3  384.36  4979.0  383.04  5014.6  384.47
  5036.1  383.80  5058.5  384.27  5147.3  383.46  5174.7  384.05  5221.2  383.53
  5328.6  383.49  5445.6  383.62  5453.6  384.17  5461.2  383.83  5899.5  384.49
#Mann=3,-1,0
  4166.5    0.05       0  4884.1    0.04       0  4888.8    0.05       0
Bank Sta=4884.1,4888.8
Exp/Cntr=0.3,0.1

Chan Stop Cuts=-1