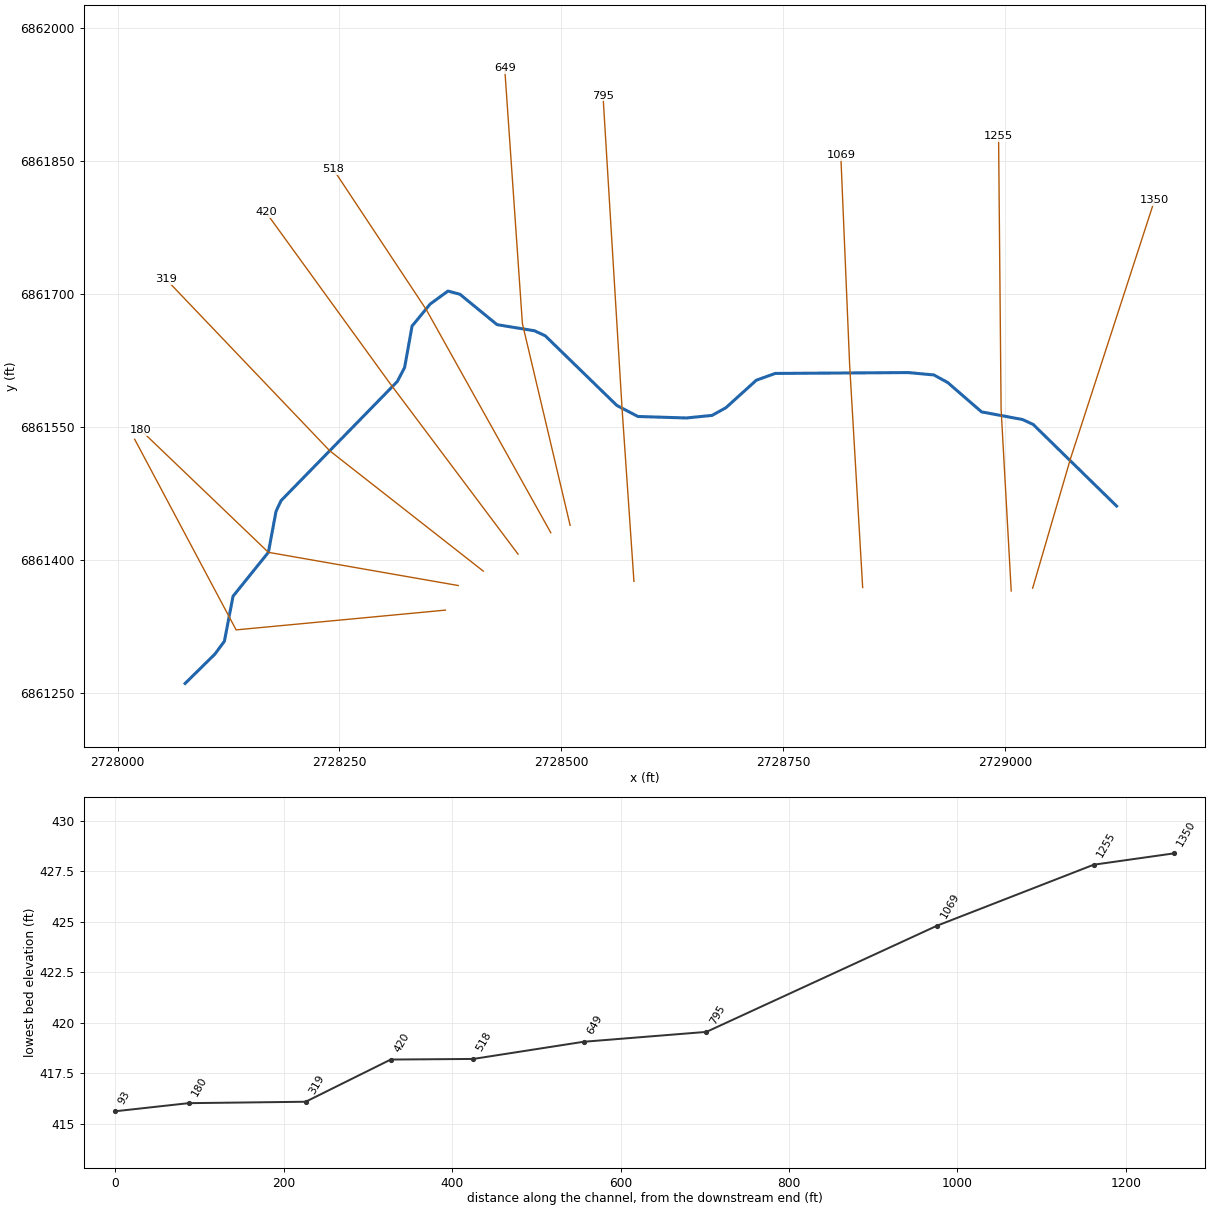
--- Lacy 124.prj (project) ---

Proj Title=Lacy 124 Base Level Engineering
Current Plan=p01
Default Exp/Contr=0.3,0.1
English Units
Geom File=g01
Flow File=f01
Plan File=p01
BEGIN DESCRIPTION:
Lacy 124
END DESCRIPTION:

--- Lacy 124.p01 (plan) ---

Plan Title=Multiple Run
Short Identifier=Multiple
Geom File=g01
Flow File=f01
Subcritical Flow
K Sum by GR= 0
Std Step Tol= 0.01
Critical Tol= 0.01
Num of Std Step Trials= 20
Max Error Tol= 0.3
Flow Tol Ratio= 0.001
Split Flow NTrial= 30
Split Flow Tol= 0.02
Split Flow Ratio= 0.02
Log Output Level= 0
Friction Slope Method= 1
Unsteady Friction Slope Method= 2
Unsteady Bridges Friction Slope Method= 1
Parabolic Critical Depth
Global Vel Dist=  1 , 1 , 1
Global Log Level= 0
CheckData=True
Encroach Param= -1, 0, 0, 0
BEGIN DESCRIPTION:
Multiple Run
END DESCRIPTION:

--- Lacy 124.f01 (steady flow) ---

Flow Title=Multiple
Number of Profiles=7
Profile Names=10-year,25-year,50-year,1pct_min,100-year,1pct_plu,500-year
River Rch & RM= Lacy 124,Reach-1,1350
     330     423     496     289     577    1151     778
Boundary for River Rch & Prof#=Lacy 124,Reach-1,1
Up Type=0
Dn Type=3
Dn Slope=0.005
Boundary for River Rch & Prof#=Lacy 124,Reach-1,2
Up Type=0
Dn Type=3
Dn Slope=0.005
Boundary for River Rch & Prof#=Lacy 124,Reach-1,3
Up Type=0
Dn Type=3
Dn Slope=0.005
Boundary for River Rch & Prof#=Lacy 124,Reach-1,4
Up Type=0
Dn Type=3
Dn Slope=0.005
Boundary for River Rch & Prof#=Lacy 124,Reach-1,5
Up Type=0
Dn Type=3
Dn Slope=0.005
Boundary for River Rch & Prof#=Lacy 124,Reach-1,6
Up Type=0
Dn Type=3
Dn Slope=0.005
Boundary for River Rch & Prof#=Lacy 124,Reach-1,7
Up Type=0
Dn Type=3
Dn Slope=0.005

--- Lacy 124.g01 (geometry) ---

Geom Title=Existing Conditions

River Reach=Lacy 124,Reach-1
Reach XY= 30
      2729126.00      6861461.00      2729032.08      6861552.91
      2729019.97      6861558.52      2728973.83      6861567.13
      2728935.67      6861600.21      2728920.07      6861608.76
      2728891.18      6861611.44      2728741.22      6861610.48
      2728719.94      6861602.85      2728685.63      6861571.81
      2728670.02      6861563.16      2728641.06      6861560.27
      2728586.48      6861561.94      2728562.71      6861574.36
      2728482.04      6861652.86      2728469.94      6861658.54
      2728427.64      6861665.47      2728385.74      6861699.78
      2728372.34      6861703.33      2728352.27      6861688.71
      2728331.85      6861663.85      2728323.46      6861617.13
      2728315.22      6861601.36      2728184.14      6861467.06
      2728178.50      6861454.97      2728169.90      6861408.81
      2728130.04      6861359.33      2728120.33      6861308.64
      2728109.59      6861294.07      2728076.00      6861261.00

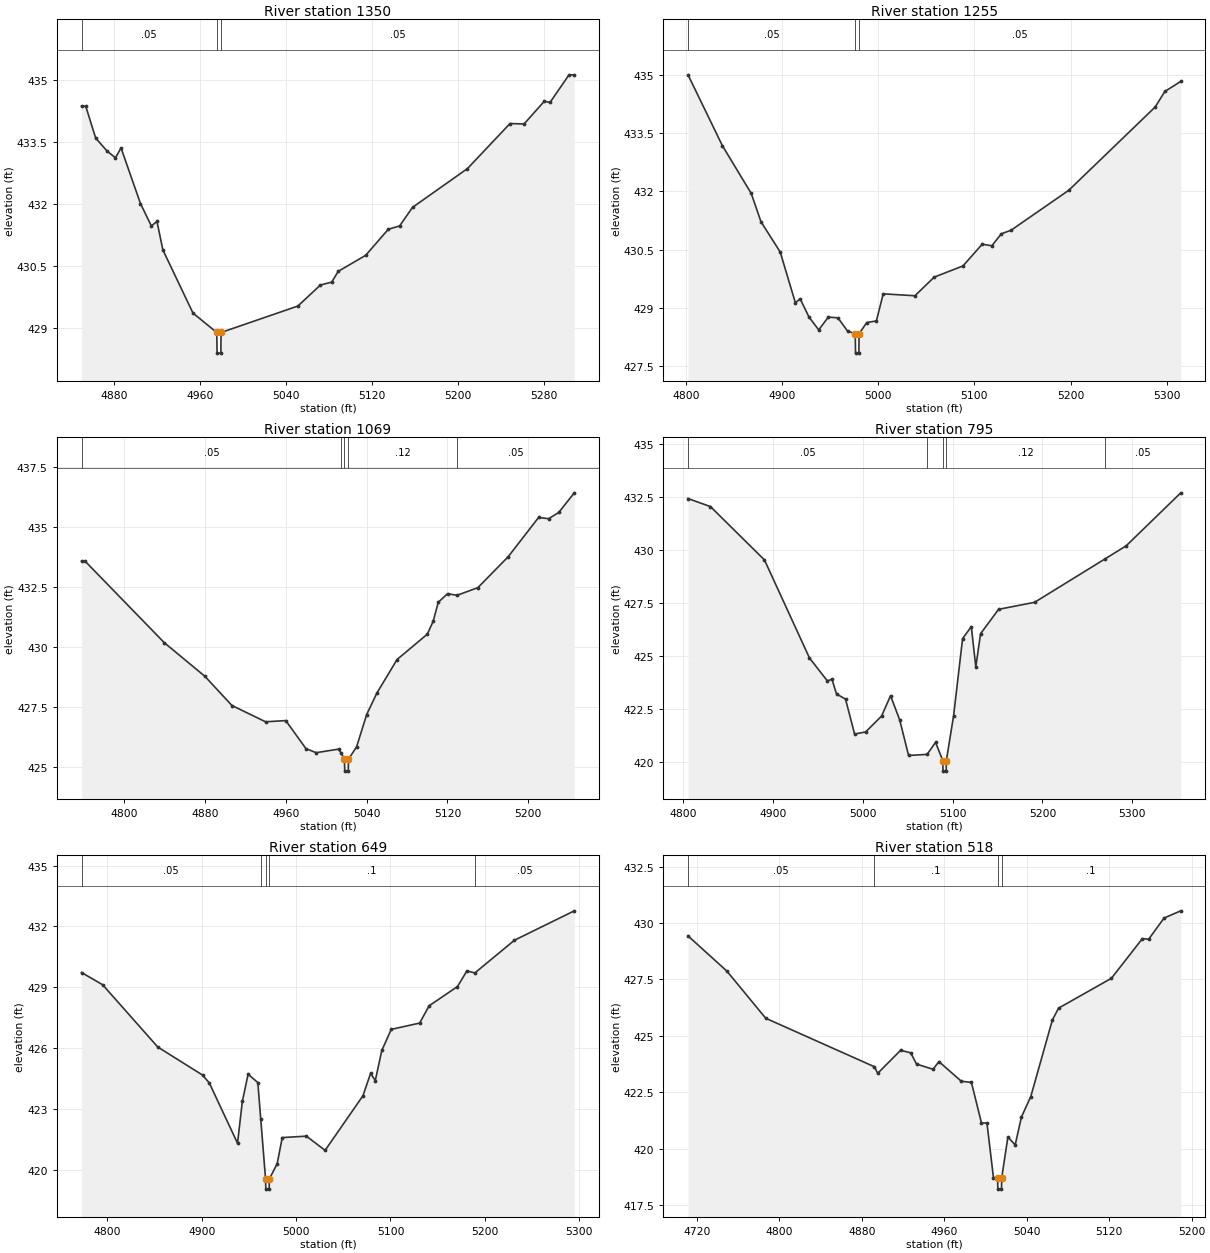
Type RM Length L Ch R = 1,1350,95,95,95
BEGIN DESCRIPTION:
Lacy 124 1331
END DESCRIPTION:
XS GIS Cut Line= 3
      2729031.41      6861368.41      2729074.21      6861514.88
      2729168.68      6861805.42
#Sta/Elev= 30
  4850.0  434.37  4853.9  434.37  4863.1  433.60  4873.5  433.29  4881.5  433.12
  4886.7  433.36  4904.8  432.01  4914.9  431.47  4920.1  431.58  4925.6  430.89
  4953.6  429.36  4975.7  428.89  4976.0  428.39  4979.5  428.39  4979.7  428.89
  5051.1  429.53  5072.1  430.04  5082.6  430.11  5088.6  430.37  5114.2  430.76
  5135.2  431.39  5145.7  431.47  5157.7  431.92  5208.8  432.86  5248.3  433.95
  5261.4  433.94  5280.2  434.49  5285.5  434.46  5303.2  435.13  5308.1  435.13
#Mann=3,-1,0
  4850.0    0.05       0  4975.7    0.04       0  4979.7    0.05       0
Bank Sta=4975.7,4979.7
Exp/Cntr=0.3,0.1

Type RM Length L Ch R = 1,1255,186,186,186
BEGIN DESCRIPTION:
Lacy 124 1330
END DESCRIPTION:
XS GIS Cut Line= 3
      2729007.25      6861365.26      2728995.84      6861570.18
      2728993.00      6861877.63
#Sta/Elev= 30
  4802.0  435.01  4837.8  433.18  4867.8  431.95  4877.9  431.22  4897.9  430.44
  4913.7  429.13  4918.7  429.23  4927.9  428.76  4938.0  428.43  4948.0  428.76
  4958.0  428.74  4968.0  428.40  4976.0  428.33  4976.3  427.83  4979.8  427.83
  4980.0  428.33  4988.0  428.62  4998.0  428.66  5005.1  429.36  5038.1  429.31
  5058.1  429.79  5088.1  430.08  5108.1  430.64  5118.1  430.60  5128.1  430.91
  5138.1  431.00  5198.1  432.03  5288.1  434.18  5298.1  434.58  5314.7  434.84
#Mann=3,-1,0
  4802.0    0.05       0  4976.0    0.04       0  4980.0    0.05       0
Bank Sta=4976,4980
Exp/Cntr=0.3,0.1

Type RM Length L Ch R = 1,1069,274,274,274
BEGIN DESCRIPTION:
Lacy 124 1329
END DESCRIPTION:
XS GIS Cut Line= 3
      2728839.80      6861369.13      2728825.08      6861620.73
      2728815.15      6861856.39
#Sta/Elev= 30
  4757.7  433.58  4761.1  433.58  4839.7  430.17  4879.8  428.77  4906.6  427.55
  4939.9  426.87  4959.9  426.92  4979.9  425.75  4990.0  425.58  5012.4  425.73
  5014.8  425.55  5018.0  425.31  5018.3  424.81  5021.8  424.81  5022.0  425.31
  5030.0  425.82  5040.0  427.17  5050.0  428.06  5070.1  429.47  5100.1  430.53
  5105.9  431.07  5110.9  431.86  5120.1  432.22  5129.4  432.15  5150.1  432.47
  5180.1  433.76  5210.2  435.40  5220.2  435.35  5230.2  435.61  5245.6  436.43
#Mann=5,-1,0
  4757.7    0.05       0  5014.8    0.12       0  5018.0    0.04       0
  5022.0    0.12       0  5129.4    0.05       0
Bank Sta=5018,5022
Exp/Cntr=0.3,0.1

Type RM Length L Ch R = 1,795,146,146,146
BEGIN DESCRIPTION:
Lacy 124 1328
END DESCRIPTION:
XS GIS Cut Line= 3
      2728581.97      6861376.08      2728568.60      6861570.55
      2728547.11      6861923.37
#Sta/Elev= 30
  4805.6  432.42  4830.6  432.04  4890.7  429.52  4940.8  424.89  4960.7  423.81
  4965.8  423.89  4970.9  423.19  4980.9  422.95  4991.0  421.30  5003.3  421.40
  5021.0  422.15  5031.0  423.11  5041.1  421.98  5051.1  420.29  5071.7  420.34
  5081.1  420.91  5089.1  420.05  5089.4  419.55  5092.9  419.55  5093.1  420.05
  5101.2  422.17  5111.2  425.81  5120.9  426.37  5125.9  424.47  5131.2  426.04
  5151.3  427.19  5191.3  427.52  5270.1  429.58  5293.3  430.19  5354.0  432.69
#Mann=5,-1,0
  4805.6    0.05       0  5071.7    0.12       0  5089.1    0.04       0
  5093.1    0.12       0  5270.1    0.05       0
Bank Sta=5089.1,5093.1
Exp/Cntr=0.3,0.1

Type RM Length L Ch R = 1,649,131,131,131
BEGIN DESCRIPTION:
Lacy 124 1327
END DESCRIPTION:
XS GIS Cut Line= 3
      2728510.03      6861439.25      2728456.24      6861666.62
      2728436.28      6861954.49
#Sta/Elev= 30
  4772.6  429.73  4794.9  429.13  4853.4  426.06  4900.8  424.68  4908.0  424.29
  4937.9  421.32  4943.0  423.38  4949.1  424.72  4959.4  424.31  4962.5  422.51
  4967.6  419.56  4967.9  419.06  4971.4  419.06  4971.6  419.56  4979.9  420.31
  4985.3  421.60  5010.9  421.67  5030.7  420.97  5070.8  423.66  5078.9  424.76
  5083.9  424.41  5090.8  425.89  5100.8  426.93  5130.9  427.24  5140.9  428.09
  5171.0  429.04  5181.0  429.81  5189.4  429.71  5231.3  431.32  5294.8  432.77
#Mann=5,-1,0
  4772.6    0.05       0  4962.5     0.1       0  4967.6    0.07       0
  4971.6     0.1       0  5189.4    0.05       0
Bank Sta=4967.6,4971.6
Exp/Cntr=0.3,0.1

Type RM Length L Ch R = 1,518,98,98,98
BEGIN DESCRIPTION:
Lacy 124 1326
END DESCRIPTION:
XS GIS Cut Line= 3
      2728488.22      6861430.95      2728347.97      6861682.26
      2728242.95      6861840.85
#Sta/Elev= 30
  4711.4  429.43  4749.1  427.87  4786.8  425.78  4892.3  423.63  4895.4  423.34
  4917.6  424.36  4927.4  424.25  4933.1  423.75  4949.1  423.52  4954.8  423.86
  4976.5  422.99  4986.3  422.94  4996.1  421.14  5001.4  421.14  5007.7  418.72
  5011.7  418.71  5012.0  418.21  5015.5  418.21  5015.7  418.71  5021.7  420.52
  5028.8  420.17  5034.8  421.40  5043.9  422.31  5064.9  425.71  5070.9  426.23
  5122.1  427.55  5152.2  429.31  5158.2  429.28  5173.2  430.22  5189.4  430.54
#Mann=4,-1,0
  4711.4    0.05       0  4892.3     0.1       0  5011.7    0.07       0
  5015.7     0.1       0
Bank Sta=5011.7,5015.7
Exp/Cntr=0.3,0.1

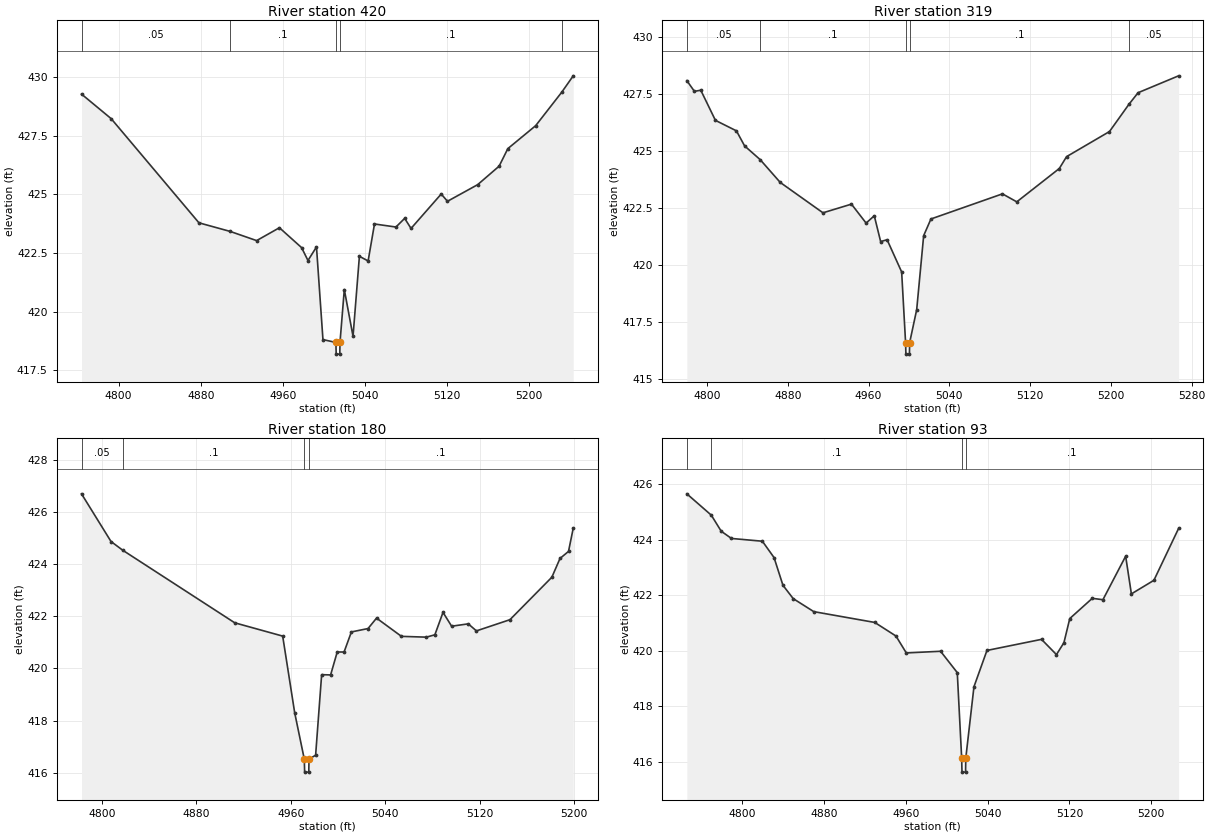
Type RM Length L Ch R = 1,420,101,101,101
BEGIN DESCRIPTION:
Lacy 124 1334
END DESCRIPTION:
XS GIS Cut Line= 3
      2728451.31      6861406.77      2728305.84      6861600.75
      2728167.04      6861792.28
#Sta/Elev= 30
  4763.9  429.29  4792.8  428.24  4878.3  423.79  4908.9  423.42  4934.5  423.03
  4956.7  423.58  4978.3  422.73  4984.5  422.18  4992.8  422.76  4999.1  418.80
  5011.7  418.68  5012.0  418.18  5015.5  418.18  5015.7  418.68  5019.9  420.94
  5028.4  418.94  5034.6  422.36  5043.1  422.16  5049.3  423.74  5070.2  423.61
  5078.7  423.98  5084.9  423.55  5114.3  425.02  5120.4  424.71  5149.8  425.42
  5170.7  426.21  5179.2  426.96  5206.3  427.94  5231.7  429.37  5242.9  430.07
#Mann=5,-1,0
  4763.9    0.05       0  4908.9     0.1       0  5011.7    0.07       0
  5015.7     0.1       0  5231.7    0.05       0
Bank Sta=5011.7,5015.7
Exp/Cntr=0.3,0.1

Type RM Length L Ch R = 1,319,139,139,139
BEGIN DESCRIPTION:
Lacy 124 1333
END DESCRIPTION:
XS GIS Cut Line= 3
      2728412.11      6861387.66      2728239.03      6861523.29
      2728054.71      6861716.47
#Sta/Elev= 30
  4780.1  428.07  4787.6  427.60  4793.9  427.65  4808.4  426.33  4829.2  425.87
  4837.3  425.21  4852.7  424.61  4872.6  423.61  4914.9  422.28  4943.1  422.66
  4957.6  421.83  4965.7  422.15  4972.0  421.02  4978.4  421.10  4992.8  419.69
  4996.7  416.59  4997.0  416.09  5000.5  416.09  5000.7  416.59  5007.7  418.04
  5014.6  421.28  5021.8  422.01  5092.6  423.11  5106.8  422.76  5148.9  424.22
  5156.1  424.74  5198.6  425.84  5217.8  427.03  5226.9  427.54  5267.0  428.28
#Mann=5,-1,0
  4780.1    0.05       0  4852.7     0.1       0  4996.7    0.07       0
  5000.7     0.1       0  5217.8    0.05       0
Bank Sta=4996.7,5000.7
Exp/Cntr=0.3,0.1

Type RM Length L Ch R = 1,180,87,87,87
BEGIN DESCRIPTION:
Lacy 124 1332
END DESCRIPTION:
XS GIS Cut Line= 3
      2728383.86      6861371.39      2728169.90      6861408.81
      2728025.98      6861546.67
#Sta/Elev= 30
  4782.8  426.70  4807.8  424.87  4817.9  424.53  4912.6  421.75  4953.2  421.24
  4963.4  418.29  4971.5  416.52  4971.8  416.02  4975.3  416.02  4975.5  416.52
  4981.1  416.67  4986.2  419.76  4993.8  419.75  4999.4  420.63  5005.2  420.63
  5011.4  421.40  5025.5  421.53  5032.7  421.93  5053.8  421.23  5074.9  421.20
  5082.1  421.29  5089.0  422.15  5096.3  421.62  5110.4  421.71  5117.3  421.44
  5145.7  421.87  5181.2  423.50  5188.1  424.22  5195.3  424.49  5199.3  425.38
#Mann=4,-1,0
  4782.8    0.05       0  4817.9     0.1       0  4971.5    0.07       0
  4975.5     0.1       0
Bank Sta=4971.5,4975.5
Exp/Cntr=0.3,0.1

Type RM Length L Ch R = 1,93,0,0,0
BEGIN DESCRIPTION:
Lacy 124 3499
END DESCRIPTION:
XS GIS Cut Line= 3
      2728369.44      6861343.67      2728133.53      6861321.39
      2728019.15      6861536.28
#Sta/Elev= 30
  4746.2  425.66  4770.1  424.89  4779.8  424.31  4789.8  424.05  4820.0  423.95
  4831.4  423.36  4840.1  422.36  4850.1  421.88  4870.2  421.41  4929.8  421.02
  4950.5  420.53  4960.6  419.92  4994.1  419.98  5010.4  419.21  5014.7  416.12
  5015.0  415.62  5018.5  415.62  5018.7  416.12  5026.7  418.70  5039.4  420.01
  5092.7  420.41  5107.3  419.86  5114.6  420.29  5120.3  421.16  5142.3  421.89
  5152.7  421.84  5174.9  423.41  5180.5  422.05  5202.5  422.54  5226.6  424.41
#Mann=4,-1,0
  4746.2    0.05       0  4770.1     0.1       0  5014.7    0.07       0
  5018.7     0.1       0
Bank Sta=5014.7,5018.7
Exp/Cntr=0.3,0.1

Chan Stop Cuts=-1