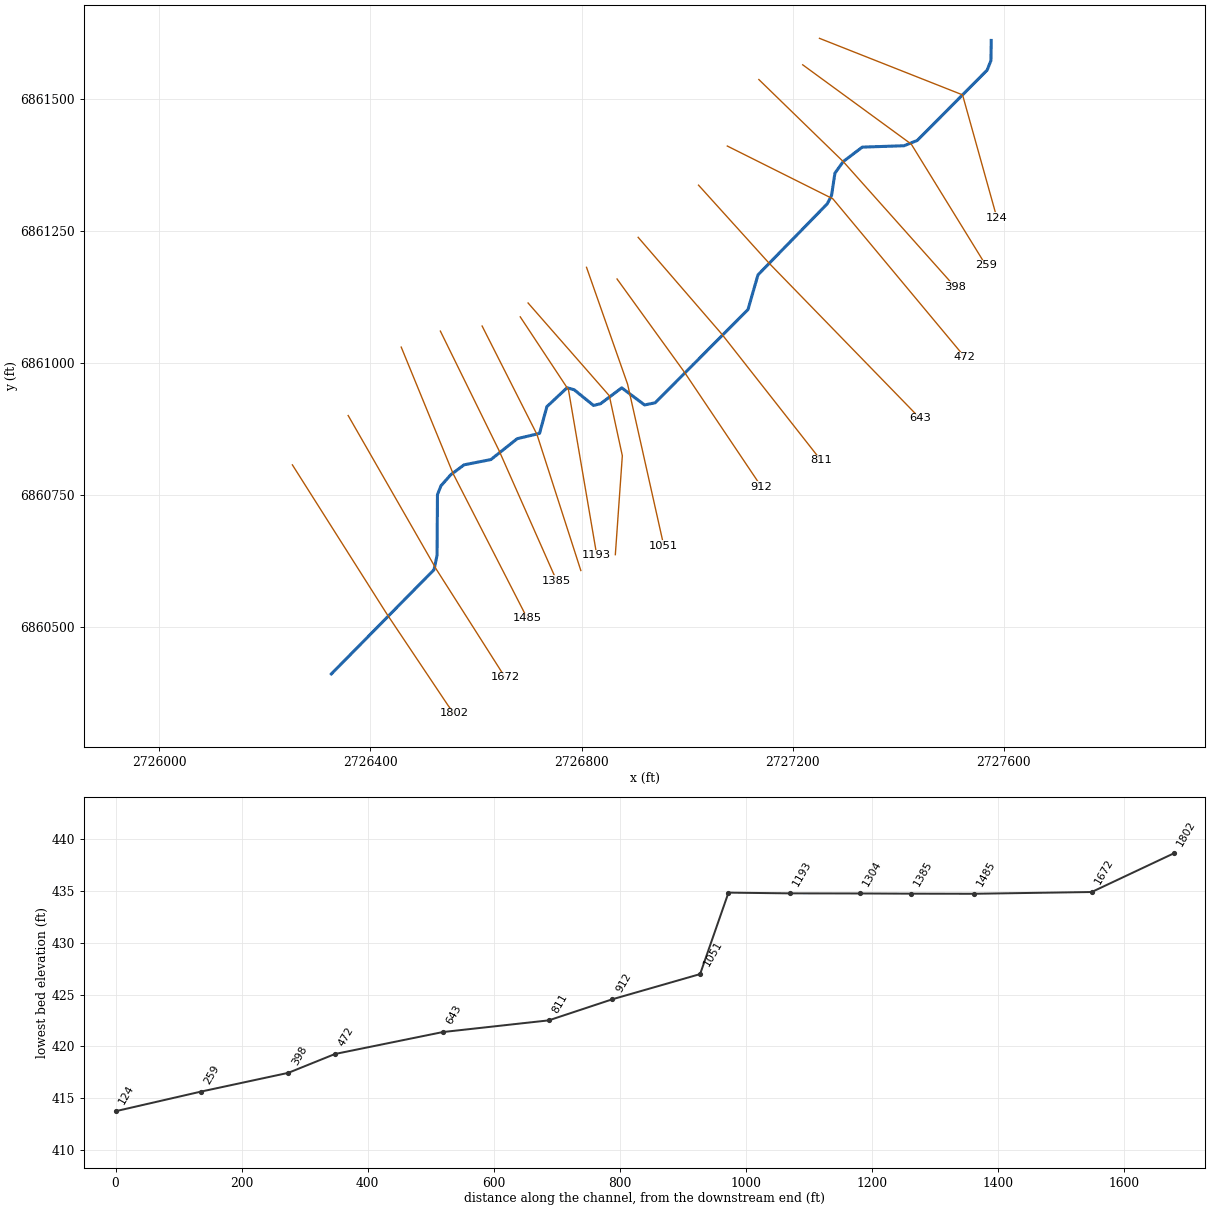
--- Lacy 125.prj (project) ---

Proj Title=Lacy 125 Base Level Engineering
Current Plan=p01
Default Exp/Contr=0.3,0.1
English Units
Geom File=g01
Flow File=f01
Plan File=p01
BEGIN DESCRIPTION:
Lacy 125
END DESCRIPTION:

--- Lacy 125.p01 (plan) ---

Plan Title=Multiple Run
Short Identifier=Multiple
Geom File=g01
Flow File=f01
Subcritical Flow
K Sum by GR= 0
Std Step Tol= 0.01
Critical Tol= 0.01
Num of Std Step Trials= 20
Max Error Tol= 0.3
Flow Tol Ratio= 0.001
Split Flow NTrial= 30
Split Flow Tol= 0.02
Split Flow Ratio= 0.02
Log Output Level= 0
Friction Slope Method= 1
Unsteady Friction Slope Method= 2
Unsteady Bridges Friction Slope Method= 1
Parabolic Critical Depth
Global Vel Dist=  1 , 1 , 1
Global Log Level= 0
CheckData=True
Encroach Param= -1, 0, 0, 0
BEGIN DESCRIPTION:
Multiple Run
END DESCRIPTION:

--- Lacy 125.f01 (steady flow) ---

Flow Title=Multiple
Number of Profiles=7
Profile Names=10-year,25-year,50-year,1pct_min,100-year,1pct_plu,500-year
River Rch & RM= Lacy 125,Reach-1,1802
     156     191     217     123     246     491     313
Boundary for River Rch & Prof#=Lacy 125,Reach-1,1
Up Type=0
Dn Type=3
Dn Slope=0.005
Boundary for River Rch & Prof#=Lacy 125,Reach-1,2
Up Type=0
Dn Type=3
Dn Slope=0.005
Boundary for River Rch & Prof#=Lacy 125,Reach-1,3
Up Type=0
Dn Type=3
Dn Slope=0.005
Boundary for River Rch & Prof#=Lacy 125,Reach-1,4
Up Type=0
Dn Type=3
Dn Slope=0.005
Boundary for River Rch & Prof#=Lacy 125,Reach-1,5
Up Type=0
Dn Type=3
Dn Slope=0.005
Boundary for River Rch & Prof#=Lacy 125,Reach-1,6
Up Type=0
Dn Type=3
Dn Slope=0.005
Boundary for River Rch & Prof#=Lacy 125,Reach-1,7
Up Type=0
Dn Type=3
Dn Slope=0.005

--- Lacy 125.g01 (geometry) ---

Geom Title=Existing Conditions

River Reach=Lacy 125,Reach-1
Reach XY= 30
      2726326.00      6860411.00      2726520.53      6860608.55
      2726526.27      6860635.89      2726527.00      6860750.71
      2726533.70      6860767.48      2726552.03      6860788.20
      2726577.39      6860807.15      2726628.20      6860817.10
      2726678.10      6860856.67      2726720.39      6860866.66
      2726734.28      6860917.38      2726772.43      6860953.08
      2726785.88      6860949.38      2726822.65      6860919.56
      2726835.99      6860922.95      2726876.00      6860952.97
      2726919.33      6860920.58      2726939.33      6860924.64
      2727115.22      6861101.32      2727134.16      6861167.05
      2727265.21      6861301.34      2727273.45      6861317.09
      2727279.88      6861359.60      2727295.59      6861381.57
      2727331.71      6861408.92      2727410.78      6861411.53
      2727435.78      6861421.52      2727568.24      6861554.79
      2727575.41      6861572.84      2727576.00      6861611.00

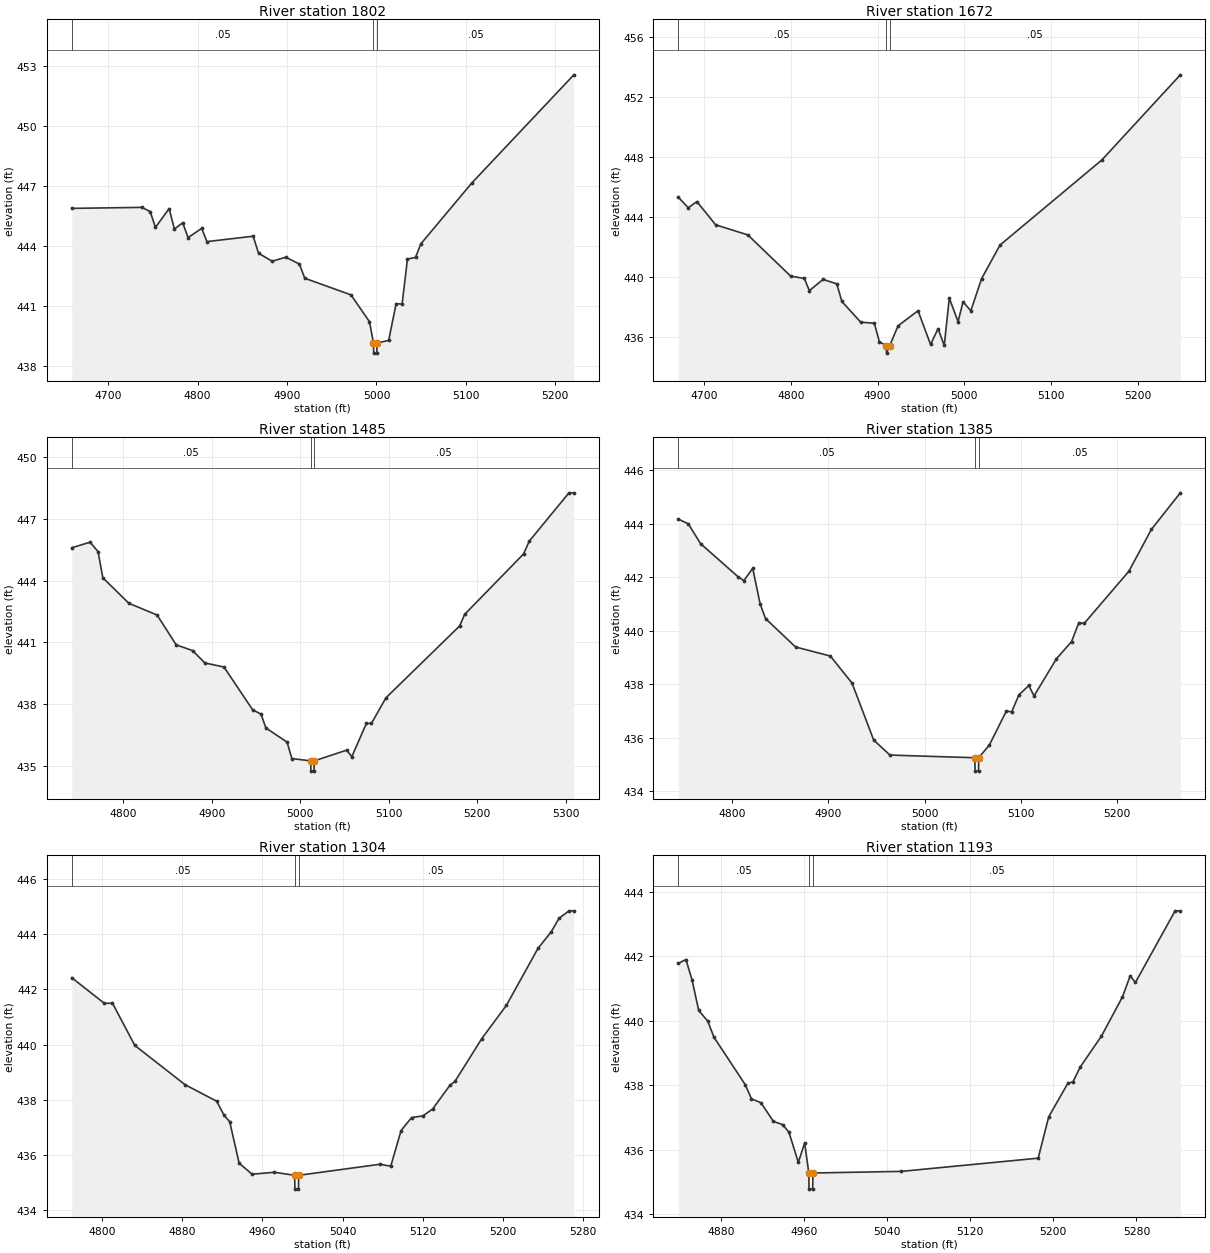
Type RM Length L Ch R = 1,1802,130,130,130
BEGIN DESCRIPTION:
Lacy 125 1312
END DESCRIPTION:
XS GIS Cut Line= 4
      2726252.18      6860807.09      2726430.52      6860525.54
      2726546.91      6860351.63      2726558.26      6860336.33
#Sta/Elev= 30
  4659.2  445.87  4737.6  445.92  4746.9  445.71  4752.8  444.92  4768.1  445.86
  4774.0  444.84  4783.3  445.15  4789.3  444.41  4804.5  444.87  4810.4  444.21
  4862.1  444.48  4868.1  443.63  4883.3  443.23  4898.6  443.43  4913.8  443.09
  4919.8  442.38  4971.5  441.55  4992.2  440.21  4996.7  439.14  4996.9  438.64
  5000.4  438.64  5000.7  439.14  5013.7  439.28  5022.0  441.11  5028.7  441.09
  5034.7  443.34  5043.7  443.42  5049.7  444.10  5106.7  447.14  5220.8  452.54
#Mann=3,-1,0
  4659.2    0.05       0  4996.7    0.04       0  5000.7    0.05       0
Bank Sta=4996.7,5000.7
Exp/Cntr=0.3,0.1

Type RM Length L Ch R = 1,1672,187,187,187
BEGIN DESCRIPTION:
Lacy 125 1319
END DESCRIPTION:
XS GIS Cut Line= 3
      2726357.88      6860900.51      2726525.48      6860608.29
      2726655.01      6860404.78
#Sta/Elev= 30
  4670.5  445.32  4682.0  444.61  4692.0  445.02  4713.6  443.47  4750.6  442.80
  4799.9  440.05  4815.7  439.89  4821.5  439.08  4837.3  439.83  4853.1  439.53
  4858.9  438.36  4880.5  436.98  4896.3  436.90  4902.1  435.67  4910.0  435.41
  4910.3  434.91  4914.0  435.41  4923.6  436.73  4946.6  437.74  4961.0  435.49
  4969.7  436.54  4976.8  435.42  4982.6  438.58  4992.7  437.01  4998.4  438.33
  5007.4  437.74  5019.8  439.88  5041.0  442.12  5158.3  447.80  5248.6  453.48
#Mann=3,-1,0
  4670.5    0.05       0  4910.0    0.04       0  4914.0    0.05       0
Bank Sta=4910,4914
Exp/Cntr=0.3,0.1

Type RM Length L Ch R = 1,1485,100,100,100
BEGIN DESCRIPTION:
Lacy 125 1318
END DESCRIPTION:
XS GIS Cut Line= 3
      2726458.35      6861030.16      2726556.45      6860790.85
      2726697.23      6860516.16
#Sta/Elev= 30
  4741.9  445.60  4762.6  445.87  4771.6  445.41  4777.0  444.14  4806.4  442.90
  4838.3  442.33  4859.9  440.88  4878.4  440.60  4892.3  440.00  4913.9  439.80
  4946.3  437.72  4955.8  437.51  4961.2  436.84  4985.2  436.15  4990.6  435.35
  5011.9  435.24  5012.1  434.74  5015.6  434.74  5015.9  435.24  5052.6  435.76
  5058.3  435.44  5074.8  437.06  5080.5  437.06  5097.0  438.31  5180.2  441.80
  5185.8  442.36  5252.4  445.30  5258.8  445.92  5303.7  448.27  5309.2  448.27
#Mann=3,-1,0
  4741.9    0.05       0  5011.9    0.04       0  5015.9    0.05       0
Bank Sta=5011.9,5015.9
Exp/Cntr=0.3,0.1

Type RM Length L Ch R = 1,1385,81,81,81
BEGIN DESCRIPTION:
Lacy 125 1317
END DESCRIPTION:
XS GIS Cut Line= 3
      2726532.52      6861060.45      2726643.52      6860834.45
      2726752.79      6860587.65
#Sta/Elev= 30
  4744.0  444.17  4754.5  443.99  4767.2  443.25  4806.6  442.00  4812.2  441.87
  4821.4  442.33  4829.1  441.00  4834.7  440.45  4865.9  439.39  4902.1  439.05
  4924.6  438.04  4947.1  435.91  4964.0  435.35  5052.2  435.25  5052.5  434.75
  5056.0  434.75  5056.2  435.25  5067.2  435.72  5085.0  437.00  5090.4  436.96
  5098.0  437.60  5108.3  437.95  5113.7  437.56  5137.0  438.95  5152.7  439.59
  5160.3  440.30  5165.8  440.27  5212.3  442.22  5235.6  443.78  5265.7  445.15
#Mann=3,-1,0
  4744.0    0.05       0  5052.2    0.04       0  5056.2    0.05       0
Bank Sta=5052.2,5056.2
Exp/Cntr=0.3,0.1

Type RM Length L Ch R = 1,1304,111,111,111
BEGIN DESCRIPTION:
Lacy 125 1316
END DESCRIPTION:
XS GIS Cut Line= 3
      2726611.60      6861070.05      2726715.48      6860864.71
      2726798.59      6860606.90
#Sta/Elev= 30
  4769.7  442.42  4802.3  441.49  4810.3  441.50  4832.6  439.97  4882.7  438.55
  4914.3  437.95  4921.7  437.44  4927.3  437.21  4936.7  435.71  4949.6  435.31
  4971.9  435.38  4992.1  435.27  4992.4  434.77  4995.9  434.77  4996.1  435.27
  5077.3  435.67  5088.0  435.60  5098.3  436.89  5108.8  437.36  5120.1  437.42
  5129.8  437.67  5146.9  438.52  5152.1  438.67  5178.9  440.22  5203.4  441.42
  5234.9  443.48  5248.3  444.09  5255.9  444.57  5265.9  444.84  5270.7  444.84
#Mann=3,-1,0
  4769.7    0.05       0  4992.1    0.04       0  4996.1    0.05       0
Bank Sta=4992.1,4996.1
Exp/Cntr=0.3,0.1

Type RM Length L Ch R = 1,1193,97,97,97
BEGIN DESCRIPTION:
Lacy 125 1315
END DESCRIPTION:
XS GIS Cut Line= 3
      2726683.82      6861087.41      2726775.17      6860949.23
      2726828.75      6860636.13
#Sta/Elev= 30
  4838.9  441.78  4846.3  441.90  4852.2  441.27  4858.6  440.32  4867.3  439.99
  4873.3  439.49  4903.4  438.02  4909.4  437.58  4918.5  437.46  4930.5  436.88
  4939.5  436.78  4945.5  436.54  4954.5  435.61  4960.6  436.21  4964.6  435.28
  4964.8  434.78  4968.3  434.78  4968.6  435.28  5053.5  435.33  5185.4  435.74
  5195.5  437.02  5213.9  438.06  5218.9  438.11  5225.9  438.57  5246.2  439.52
  5266.5  440.74  5273.9  441.39  5279.0  441.19  5317.2  443.41  5322.2  443.41
#Mann=3,-1,0
  4838.9    0.05       0  4964.6    0.05       0  4968.6    0.05       0
Bank Sta=4964.6,4968.6
Exp/Cntr=0.3,0.1

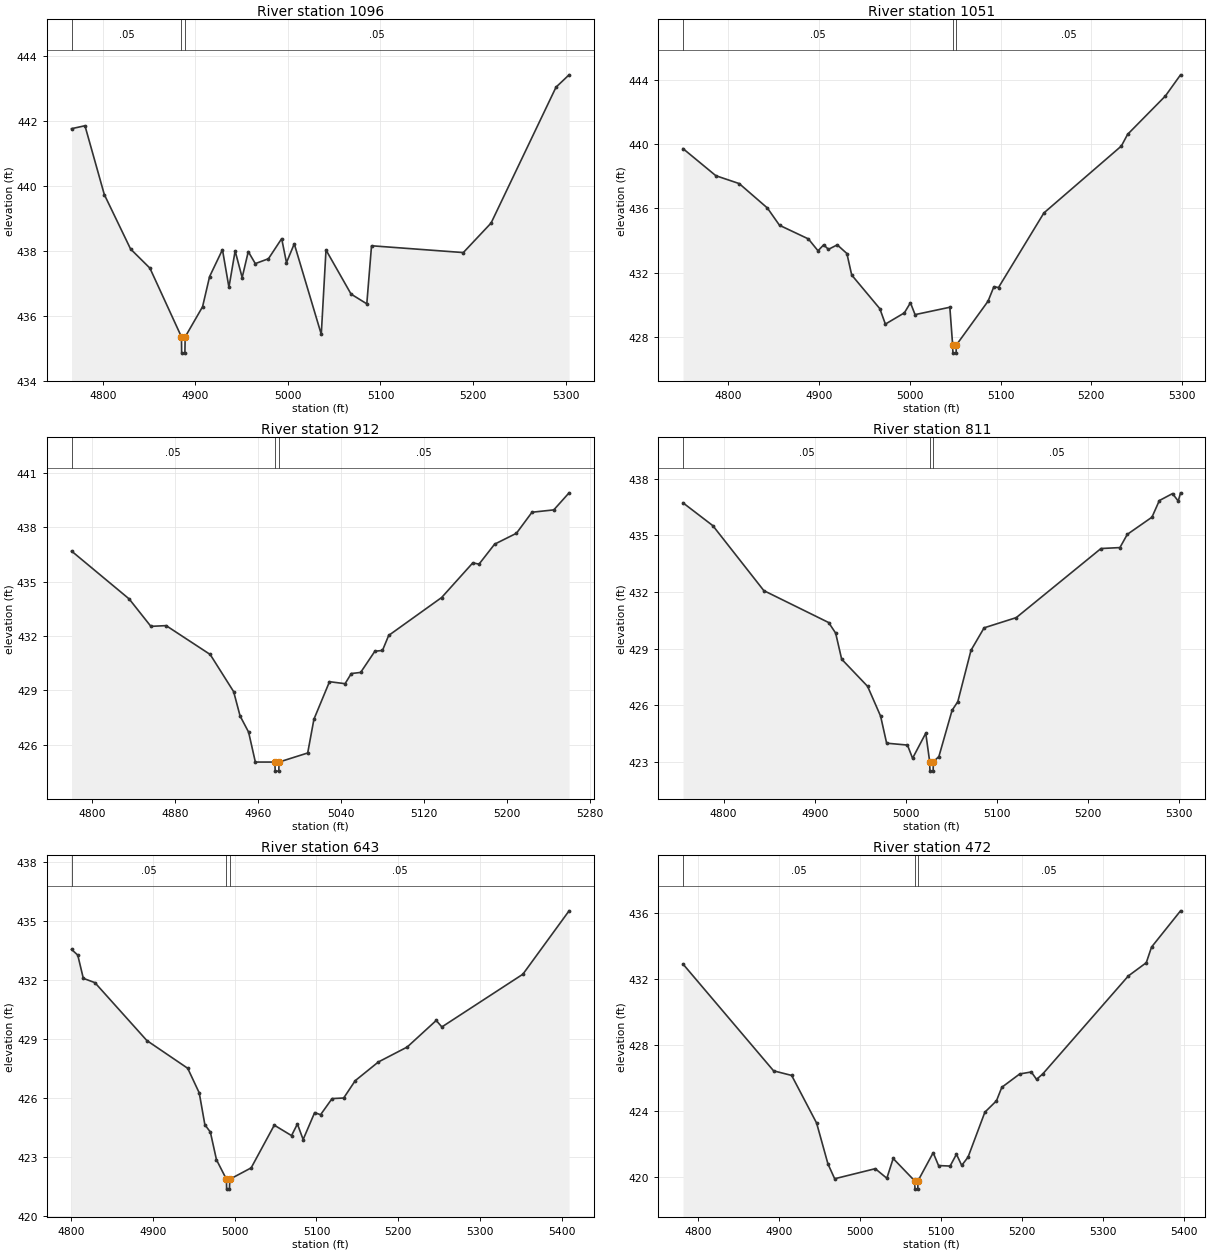
Type RM Length L Ch R = 1,1096,45,45,45
BEGIN DESCRIPTION:
Lacy 125 1313
END DESCRIPTION:
XS GIS Cut Line= 4
      2726698.65      6861113.68      2726852.50      6860938.06
      2726877.19      6860824.34      2726863.95      6860636.95
#Sta/Elev= 30
  4766.1  441.77  4780.6  441.86  4801.5  439.74  4829.9  438.06  4850.8  437.47
  4884.9  435.35  4885.1  434.85  4888.6  434.85  4888.9  435.35  4907.7  436.28
  4915.3  437.21  4929.2  438.04  4936.2  436.88  4942.9  438.00  4950.5  437.18
  4957.1  437.98  4964.7  437.61  4978.9  437.76  4993.2  438.38  4998.4  437.64
  5006.8  438.22  5036.0  435.43  5041.1  438.03  5068.2  436.67  5085.2  436.37
  5090.3  438.16  5189.5  437.95  5219.5  438.86  5289.7  443.05  5303.8  443.43
#Mann=3,-1,0
  4766.1    0.05       0  4884.9    0.05       0  4888.9    0.05       0
Bank Sta=4884.9,4888.9
Exp/Cntr=0.3,0.1

Type RM Length L Ch R = 1,1051,139,139,139
BEGIN DESCRIPTION:
Lacy 125 1314
END DESCRIPTION:
XS GIS Cut Line= 3
      2726809.36      6861181.26      2726887.23      6860959.65
      2726955.66      6860654.11
#Sta/Elev= 30
  4750.3  439.73  4786.5  438.04  4812.2  437.55  4843.2  436.03  4856.6  434.95
  4888.4  434.10  4899.0  433.36  4905.2  433.73  4910.5  433.45  4920.2  433.73
  4930.8  433.19  4936.1  431.85  4967.1  429.75  4973.2  428.79  4994.1  429.49
  5000.8  430.12  5005.9  429.38  5044.2  429.84  5047.3  427.48  5047.6  426.98
  5051.1  426.98  5051.3  427.48  5086.3  430.22  5092.7  431.12  5097.8  431.07
  5147.8  435.72  5233.1  439.89  5240.0  440.62  5281.6  443.01  5298.3  444.33
#Mann=3,-1,0
  4750.3    0.05       0  5047.3    0.05       0  5051.3    0.05       0
Bank Sta=5047.3,5051.3
Exp/Cntr=0.3,0.1

Type RM Length L Ch R = 1,912,101,101,101
BEGIN DESCRIPTION:
Lacy 125 1311
END DESCRIPTION:
XS GIS Cut Line= 3
      2726867.16      6861159.19      2726994.60      6860982.95
      2727140.48      6860765.79
#Sta/Elev= 30
  4780.5  436.68  4836.0  434.04  4856.9  432.53  4871.6  432.57  4914.0  430.98
  4936.6  428.93  4942.8  427.59  4951.0  426.70  4957.5  425.05  4976.3  425.05
  4976.6  424.55  4980.1  424.55  4980.3  425.05  5007.9  425.55  5013.9  427.41
  5028.9  429.48  5043.9  429.37  5049.9  429.93  5058.9  429.99  5072.6  431.16
  5079.9  431.20  5085.9  432.03  5136.9  434.12  5166.9  436.03  5172.9  435.96
  5187.9  437.06  5208.9  437.66  5223.9  438.82  5244.9  438.95  5259.6  439.89
#Mann=3,-1,0
  4780.5    0.05       0  4976.3    0.04       0  4980.3    0.05       0
Bank Sta=4976.3,4980.3
Exp/Cntr=0.3,0.1

Type RM Length L Ch R = 1,811,168,168,168
BEGIN DESCRIPTION:
Lacy 125 1310
END DESCRIPTION:
XS GIS Cut Line= 3
      2726907.17      6861238.04      2727065.59      6861054.75
      2727253.62      6860815.45
#Sta/Elev= 30
  4755.4  436.72  4788.2  435.51  4844.2  432.07  4915.4  430.38  4923.1  429.82
  4929.7  428.44  4958.2  427.00  4972.5  425.42  4979.1  423.99  5002.0  423.89
  5007.6  423.19  5022.1  424.52  5026.4  423.01  5026.7  422.51  5030.2  422.51
  5030.4  423.01  5036.5  423.28  5051.0  425.73  5057.3  426.19  5071.8  428.91
  5086.2  430.10  5121.5  430.64  5214.6  434.30  5235.4  434.35  5243.5  435.05
  5270.6  435.96  5278.7  436.84  5293.2  437.21  5299.5  436.81  5302.0  437.25
#Mann=3,-1,0
  4755.4    0.05       0  5026.4    0.05       0  5030.4    0.05       0
Bank Sta=5026.4,5030.4
Exp/Cntr=0.3,0.1

Type RM Length L Ch R = 1,643,171,171,171
BEGIN DESCRIPTION:
Lacy 125 1309
END DESCRIPTION:
XS GIS Cut Line= 3
      2727021.54      6861336.87      2727154.93      6861189.32
      2727440.59      6860895.65
#Sta/Elev= 30
  4800.4  433.56  4808.0  433.27  4814.8  432.09  4829.0  431.87  4892.5  428.93
  4942.5  427.52  4956.6  426.27  4963.5  424.65  4970.2  424.28  4977.7  422.87
  4989.9  421.88  4990.1  421.38  4993.6  421.38  4993.9  421.88  5020.1  422.46
  5048.4  424.63  5069.5  424.10  5076.7  424.69  5083.7  423.90  5097.8  425.27
  5105.0  425.16  5119.1  425.98  5133.3  426.01  5147.4  426.89  5175.7  427.84
  5211.0  428.60  5246.5  429.95  5253.4  429.62  5352.5  432.30  5409.0  435.52
#Mann=3,-1,0
  4800.4    0.05       0  4989.9    0.05       0  4993.9    0.05       0
Bank Sta=4989.9,4993.9
Exp/Cntr=0.3,0.1

Type RM Length L Ch R = 1,472,74,74,74
BEGIN DESCRIPTION:
Lacy 125 87
END DESCRIPTION:
XS GIS Cut Line= 3
      2727076.02      6861410.99      2727276.00      6861311.00
      2727526.00      6861011.00
#Sta/Elev= 30
  4781.5  432.92  4893.3  426.44  4915.6  426.16  4946.4  423.27  4960.4  420.79
  4968.7  419.89  5018.8  420.50  5033.1  419.92  5040.9  421.12  5067.5  419.76
  5067.8  419.26  5071.3  419.26  5071.5  419.76  5090.3  421.47  5096.9  420.69
  5111.2  420.66  5119.0  421.38  5125.5  420.70  5133.3  421.20  5154.1  423.93
  5168.4  424.62  5175.0  425.44  5197.1  426.25  5211.4  426.37  5217.9  425.92
  5225.7  426.26  5331.2  432.20  5353.3  433.00  5359.8  433.95  5395.6  436.15
#Mann=3,-1,0
  4781.5    0.05       0  5067.5    0.05       0  5071.5    0.05       0
Bank Sta=5067.5,5071.5
Exp/Cntr=0.3,0.1

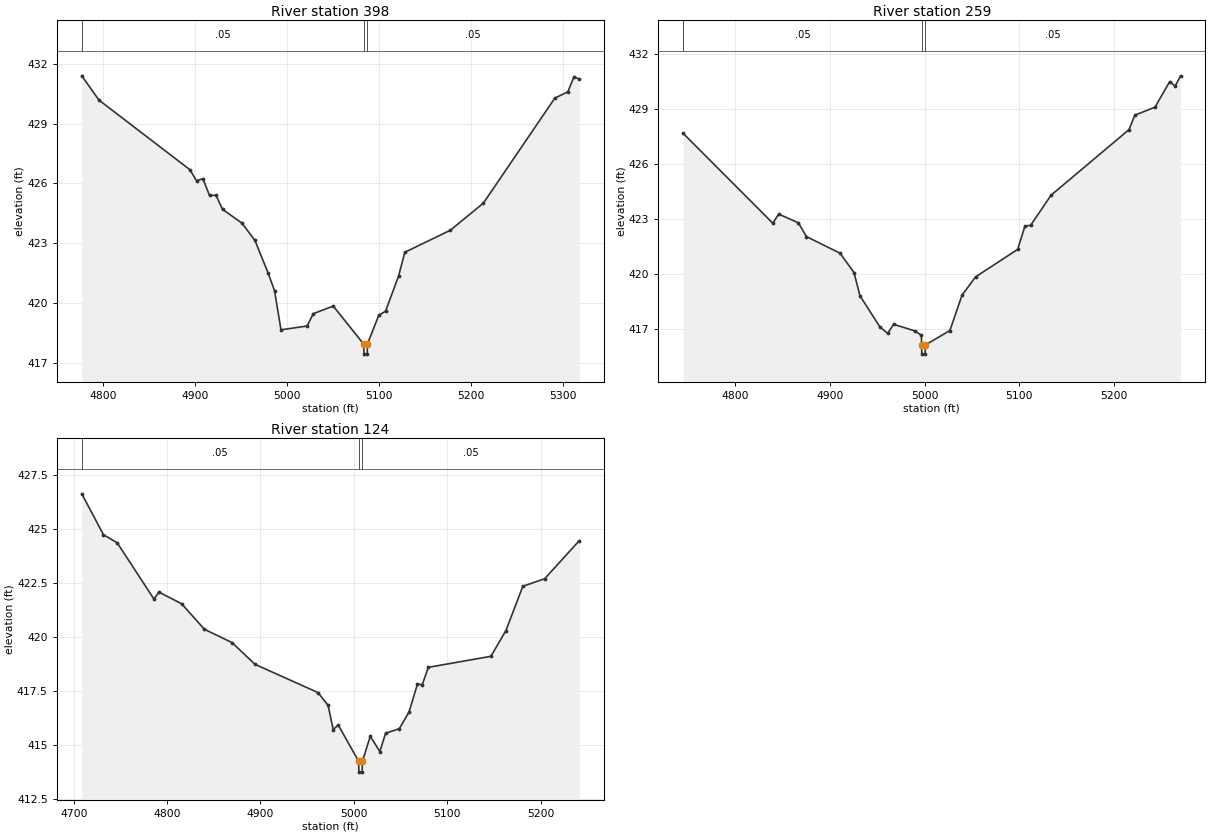
Type RM Length L Ch R = 1,398,139,139,139
BEGIN DESCRIPTION:
Lacy 125 1308
END DESCRIPTION:
XS GIS Cut Line= 3
      2727135.78      6861536.95      2727295.59      6861381.57
      2727507.08      6861144.49
#Sta/Elev= 30
  4777.1  431.40  4795.6  430.19  4894.6  426.69  4901.8  426.14  4908.7  426.24
  4915.9  425.40  4922.9  425.41  4930.1  424.70  4951.2  424.01  4965.3  423.14
  4979.5  421.52  4986.6  420.62  4993.6  418.66  5022.0  418.85  5028.7  419.47
  5050.4  419.85  5083.5  417.94  5083.8  417.44  5087.3  417.44  5087.5  417.94
  5099.8  419.38  5107.3  419.60  5121.4  421.36  5128.2  422.55  5177.5  423.65
  5213.5  425.01  5291.2  430.28  5305.4  430.60  5312.1  431.36  5317.7  431.23
#Mann=3,-1,0
  4777.1    0.05       0  5083.5    0.05       0  5087.5    0.05       0
Bank Sta=5083.5,5087.5
Exp/Cntr=0.3,0.1

Type RM Length L Ch R = 1,259,135,135,135
BEGIN DESCRIPTION:
Lacy 125 1307
END DESCRIPTION:
XS GIS Cut Line= 3
      2727218.83      6861564.86      2727424.50      6861414.61
      2727566.07      6861184.70
#Sta/Elev= 30
  4745.3  427.68  4839.9  422.77  4846.1  423.27  4866.9  422.79  4875.4  422.04
  4910.9  421.13  4925.6  420.07  4931.8  418.81  4952.7  417.12  4961.1  416.75
  4967.3  417.25  4989.5  416.89  4996.7  416.65  4996.8  416.12  4997.1  415.62
  5000.6  415.62  5000.8  416.12  5026.7  416.91  5039.5  418.84  5053.8  419.84
  5098.2  421.34  5105.9  422.62  5111.8  422.65  5133.4  424.30  5215.6  427.88
  5221.8  428.67  5243.1  429.11  5258.5  430.50  5264.4  430.26  5270.0  430.82
#Mann=3,-1,0
  4745.3    0.05       0  4996.8    0.05       0  5000.8    0.05       0
Bank Sta=4996.8,5000.8
Exp/Cntr=0.3,0.1

Type RM Length L Ch R = 1,124,0,0,0
BEGIN DESCRIPTION:
Lacy 125 1306
END DESCRIPTION:
XS GIS Cut Line= 3
      2727250.63      6861614.99      2727521.64      6861507.91
      2727586.58      6861275.40
#Sta/Elev= 30
  4708.6  426.61  4731.8  424.72  4746.6  424.34  4785.9  421.74  4791.3  422.06
  4815.6  421.52  4840.0  420.34  4869.7  419.72  4894.1  418.72  4961.7  417.41
  4972.4  416.82  4977.9  415.70  4983.3  415.91  5005.2  414.23  5005.4  413.73
  5008.9  413.73  5009.2  414.23  5017.6  415.39  5027.9  414.68  5034.0  415.53
  5048.7  415.74  5059.1  416.51  5068.1  417.80  5073.3  417.78  5079.8  418.58
  5146.8  419.09  5162.9  420.28  5181.0  422.33  5204.4  422.68  5241.4  424.44
#Mann=3,-1,0
  4708.6    0.05       0  5005.2    0.05       0  5009.2    0.05       0
Bank Sta=5005.2,5009.2
Exp/Cntr=0.3,0.1

Chan Stop Cuts=-1