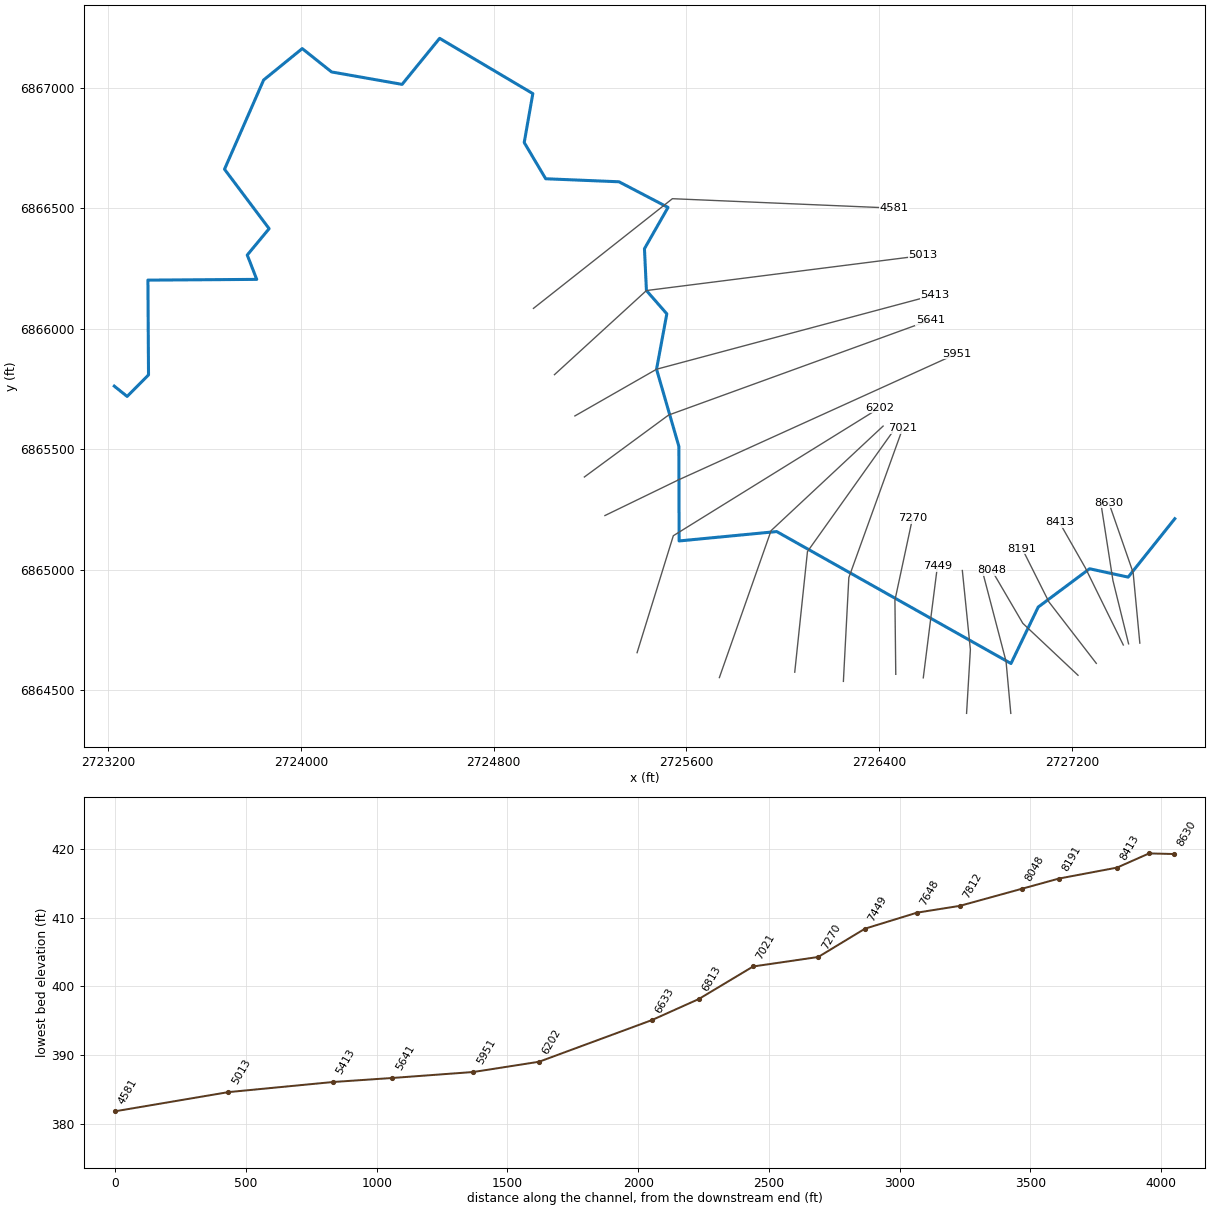
--- Lacy 126.prj (project) ---

Proj Title=Lacy 126 Base Level Engineering
Current Plan=p01
Default Exp/Contr=0.3,0.1
English Units
Geom File=g01
Flow File=f01
Plan File=p01
BEGIN DESCRIPTION:
Lacy 126
END DESCRIPTION:

--- Lacy 126.p01 (plan) ---

Plan Title=Multiple Run
Short Identifier=Multiple
Geom File=g01
Flow File=f01
Subcritical Flow
K Sum by GR= 0
Std Step Tol= 0.01
Critical Tol= 0.01
Num of Std Step Trials= 20
Max Error Tol= 0.3
Flow Tol Ratio= 0.001
Split Flow NTrial= 30
Split Flow Tol= 0.02
Split Flow Ratio= 0.02
Log Output Level= 0
Friction Slope Method= 1
Unsteady Friction Slope Method= 2
Unsteady Bridges Friction Slope Method= 1
Parabolic Critical Depth
Global Vel Dist=  1 , 1 , 1
Global Log Level= 0
CheckData=True
Encroach Param= -1, 0, 0, 0
BEGIN DESCRIPTION:
Multiple Run
END DESCRIPTION:

--- Lacy 126.f01 (steady flow) ---

Flow Title=Multiple
Number of Profiles=7
Profile Names=10-year,25-year,50-year,1pct_min,100-year,1pct_plu,500-year
River Rch & RM= Lacy 126,Reach-1,8630
     270     343     398     231     460     919     612
Boundary for River Rch & Prof#=Lacy 126,Reach-1,1
Up Type=0
Dn Type=3
Dn Slope=0.005
Boundary for River Rch & Prof#=Lacy 126,Reach-1,2
Up Type=0
Dn Type=3
Dn Slope=0.005
Boundary for River Rch & Prof#=Lacy 126,Reach-1,3
Up Type=0
Dn Type=3
Dn Slope=0.005
Boundary for River Rch & Prof#=Lacy 126,Reach-1,4
Up Type=0
Dn Type=3
Dn Slope=0.005
Boundary for River Rch & Prof#=Lacy 126,Reach-1,5
Up Type=0
Dn Type=3
Dn Slope=0.005
Boundary for River Rch & Prof#=Lacy 126,Reach-1,6
Up Type=0
Dn Type=3
Dn Slope=0.005
Boundary for River Rch & Prof#=Lacy 126,Reach-1,7
Up Type=0
Dn Type=3
Dn Slope=0.005

--- Lacy 126.g01 (geometry) ---

Geom Title=Existing Conditions

River Reach=Lacy 126,Reach-1
Reach XY= 30
      2727626.00      6865211.00      2727432.45      6864968.64
      2727272.35      6865003.27      2727059.25      6864844.36
      2726946.35      6864610.22      2725974.28      6865157.66
      2725569.48      6865118.67      2725568.41      6865510.99
      2725475.83      6865831.13      2725518.43      6866061.00
      2725433.85      6866157.59      2725425.66      6866331.20
      2725523.42      6866502.52      2725320.03      6866608.85
      2725015.89      6866621.38      2724926.79      6866771.70
      2724962.51      6866974.68      2724575.79      6867203.99
      2724420.12      6867012.96      2724127.47      6867064.56
      2724005.84      6867161.47      2723845.63      6867031.16
      2723683.32      6866660.90      2723868.39      6866414.33
      2723777.68      6866304.95      2723816.99      6866203.94
      2723365.58      6866200.82      2723368.03      6865807.64
      2723279.37      6865718.25      2723226.00      6865761.00

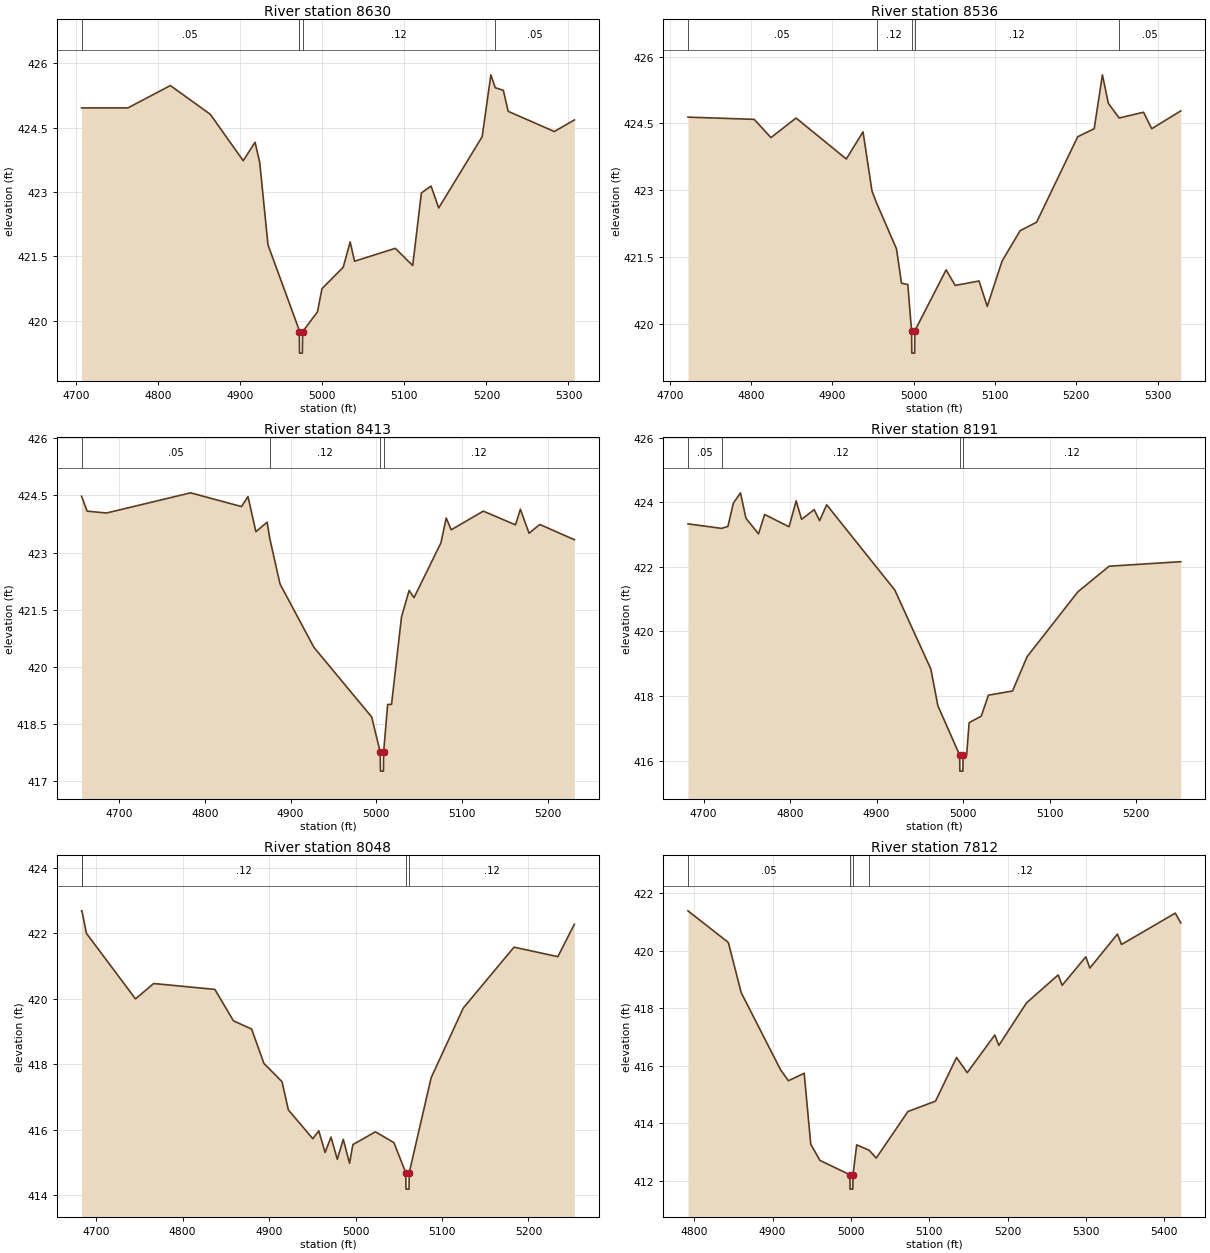
Type RM Length L Ch R = 1,8630,94,94,94
BEGIN DESCRIPTION:
Lacy 126 1355
END DESCRIPTION:
XS GIS Cut Line= 3
      2727480.89      6864694.73      2727453.19      6864987.02
      2727352.36      6865277.20
#Sta/Elev= 30
  4706.4  424.96  4762.9  424.96  4814.7  425.48  4863.4  424.81  4903.5  423.73
  4917.9  424.16  4923.6  423.69  4933.7  421.77  4971.1  419.82  4971.9  419.75
  4972.1  419.25  4975.6  419.25  4975.9  419.75  4994.0  420.21  4999.5  420.75
  5025.4  421.25  5033.9  421.84  5039.2  421.39  5088.9  421.69  5110.1  421.29
  5120.7  422.98  5132.5  423.14  5141.8  422.63  5194.8  424.29  5205.4  425.73
  5210.7  425.43  5220.6  425.37  5226.5  424.88  5282.8  424.41  5307.2  424.68
#Mann=5,-1,0
  4706.4    0.05       0  4971.1    0.12       0  4971.9    0.07       0
  4975.9    0.12       0  5210.7    0.05       0
Bank Sta=4971.9,4975.9
Exp/Cntr=0.3,0.1

Type RM Length L Ch R = 1,8536,123,123,123
BEGIN DESCRIPTION:
Lacy 126 1345
END DESCRIPTION:
XS GIS Cut Line= 3
      2727434.24      6864691.86      2727369.37      6864954.44
      2727317.60      6865286.25
#Sta/Elev= 30
  4722.3  424.64  4803.8  424.59  4824.4  424.18  4855.3  424.62  4917.1  423.70
  4937.7  424.31  4948.7  422.98  4954.4  422.71  4978.9  421.68  4985.0  420.91
  4992.8  420.88  4997.4  419.84  4997.7  419.34  5001.2  419.34  5001.4  419.84
  5039.9  421.21  5051.1  420.86  5080.4  420.96  5090.5  420.39  5108.8  421.41
  5131.0  422.09  5151.2  422.28  5201.8  424.20  5222.1  424.38  5232.2  425.59
  5239.5  424.95  5252.8  424.62  5282.8  424.75  5292.9  424.38  5328.6  424.78
#Mann=5,-1,0
  4722.3    0.05       0  4954.4    0.12       0  4997.4    0.07       0
  5001.4    0.12       0  5252.8    0.05       0
Bank Sta=4997.4,5001.4
Exp/Cntr=0.3,0.1

Type RM Length L Ch R = 1,8413,222,222,222
BEGIN DESCRIPTION:
Lacy 126 1344
END DESCRIPTION:
XS GIS Cut Line= 3
      2727412.33      6864687.03      2727254.35      6865008.02
      2727147.21      6865195.97
#Sta/Elev= 30
  4656.5  424.48  4663.0  424.09  4685.5  424.04  4783.5  424.57  4842.8  424.21
  4850.4  424.47  4859.6  423.55  4872.7  423.80  4875.7  423.38  4887.7  422.18
  4927.1  420.52  4994.5  418.69  5004.4  417.77  5004.7  417.27  5008.2  417.27
  5008.4  417.77  5013.1  419.02  5017.6  419.02  5029.2  421.31  5038.1  422.01
  5043.8  421.82  5075.2  423.26  5081.3  423.91  5087.1  423.60  5124.5  424.09
  5162.0  423.73  5167.7  424.14  5177.8  423.51  5190.3  423.74  5230.6  423.34
#Mann=4,-1,0
  4656.5    0.05       0  4875.7    0.12       0  5004.4    0.07       0
  5008.4    0.12       0
Bank Sta=5004.4,5008.4
Exp/Cntr=0.3,0.1

Type RM Length L Ch R = 1,8191,143,143,143
BEGIN DESCRIPTION:
Lacy 126 1343
END DESCRIPTION:
XS GIS Cut Line= 3
      2727300.34      6864610.82      2727103.54      6864865.95
      2726992.52      6865087.25
#Sta/Elev= 30
  4681.9  423.33  4720.7  423.19  4728.1  423.25  4734.4  423.97  4742.6  424.29
  4749.0  423.50  4763.5  423.02  4770.5  423.62  4798.8  423.24  4807.0  424.04
  4813.3  423.47  4827.8  423.77  4834.1  423.43  4842.3  423.92  4921.1  421.28
  4962.7  418.84  4970.9  417.70  4996.0  416.18  4996.3  415.68  4999.8  415.68
  5000.0  416.18  5004.1  416.18  5007.0  417.18  5021.0  417.38  5029.3  418.03
  5057.2  418.16  5074.0  419.22  5132.8  421.23  5168.9  422.02  5251.7  422.16
#Mann=4,-1,0
  4681.9    0.05       0  4720.7    0.12       0  4996.0    0.07       0
  5000.0    0.12       0
Bank Sta=4996,5000
Exp/Cntr=0.3,0.1

Type RM Length L Ch R = 1,8048,236,236,236
BEGIN DESCRIPTION:
Lacy 126 1342
END DESCRIPTION:
XS GIS Cut Line= 3
      2727224.46      6864561.38      2726995.53      6864776.83
      2726866.41      6864997.46
#Sta/Elev= 30
  4683.1  422.68  4683.5  422.68  4688.8  421.99  4745.5  419.99  4766.5  420.46
  4837.3  420.28  4858.8  419.32  4879.8  419.07  4894.0  418.02  4915.0  417.46
  4922.3  416.60  4950.6  415.72  4957.5  415.96  4964.8  415.30  4971.6  415.77
  4978.9  415.09  4985.8  415.70  4993.1  414.97  4996.9  415.54  5023.0  415.93
  5044.4  415.60  5058.1  414.68  5058.4  414.18  5061.9  414.18  5062.1  414.68
  5087.4  417.58  5124.6  419.71  5183.3  421.57  5234.0  421.28  5253.1  422.27
#Mann=4,-1,0
  4683.1    0.05       0  4683.5    0.12       0  5058.1    0.07       0
  5062.1    0.12       0
Bank Sta=5058.1,5062.1
Exp/Cntr=0.3,0.1

Type RM Length L Ch R = 1,7812,164,164,164
BEGIN DESCRIPTION:
Lacy 126 1340
END DESCRIPTION:
XS GIS Cut Line= 3
      2726945.56      6864403.31      2726925.82      6864619.34
      2726821.49      6865017.77
#Sta/Elev= 30
  4792.1  421.39  4843.6  420.29  4860.1  418.54  4910.3  415.86  4920.3  415.48
  4940.4  415.74  4948.8  413.27  4960.5  412.71  4998.7  412.21  4998.9  411.71
  5002.4  411.71  5002.7  412.21  5007.4  413.25  5023.4  413.06  5032.3  412.79
  5072.8  414.41  5108.0  414.77  5134.8  416.29  5148.4  415.76  5183.6  417.07
  5188.8  416.71  5224.1  418.19  5264.5  419.16  5269.6  418.80  5299.7  419.79
  5304.9  419.40  5340.1  420.58  5345.3  420.22  5413.9  421.31  5420.9  420.97
#Mann=4,-1,0
  4792.1    0.05       0  4998.7    0.05       0  5002.7    0.05       0
  5023.4    0.12       0
Bank Sta=4998.7,5002.7
Exp/Cntr=0.3,0.1

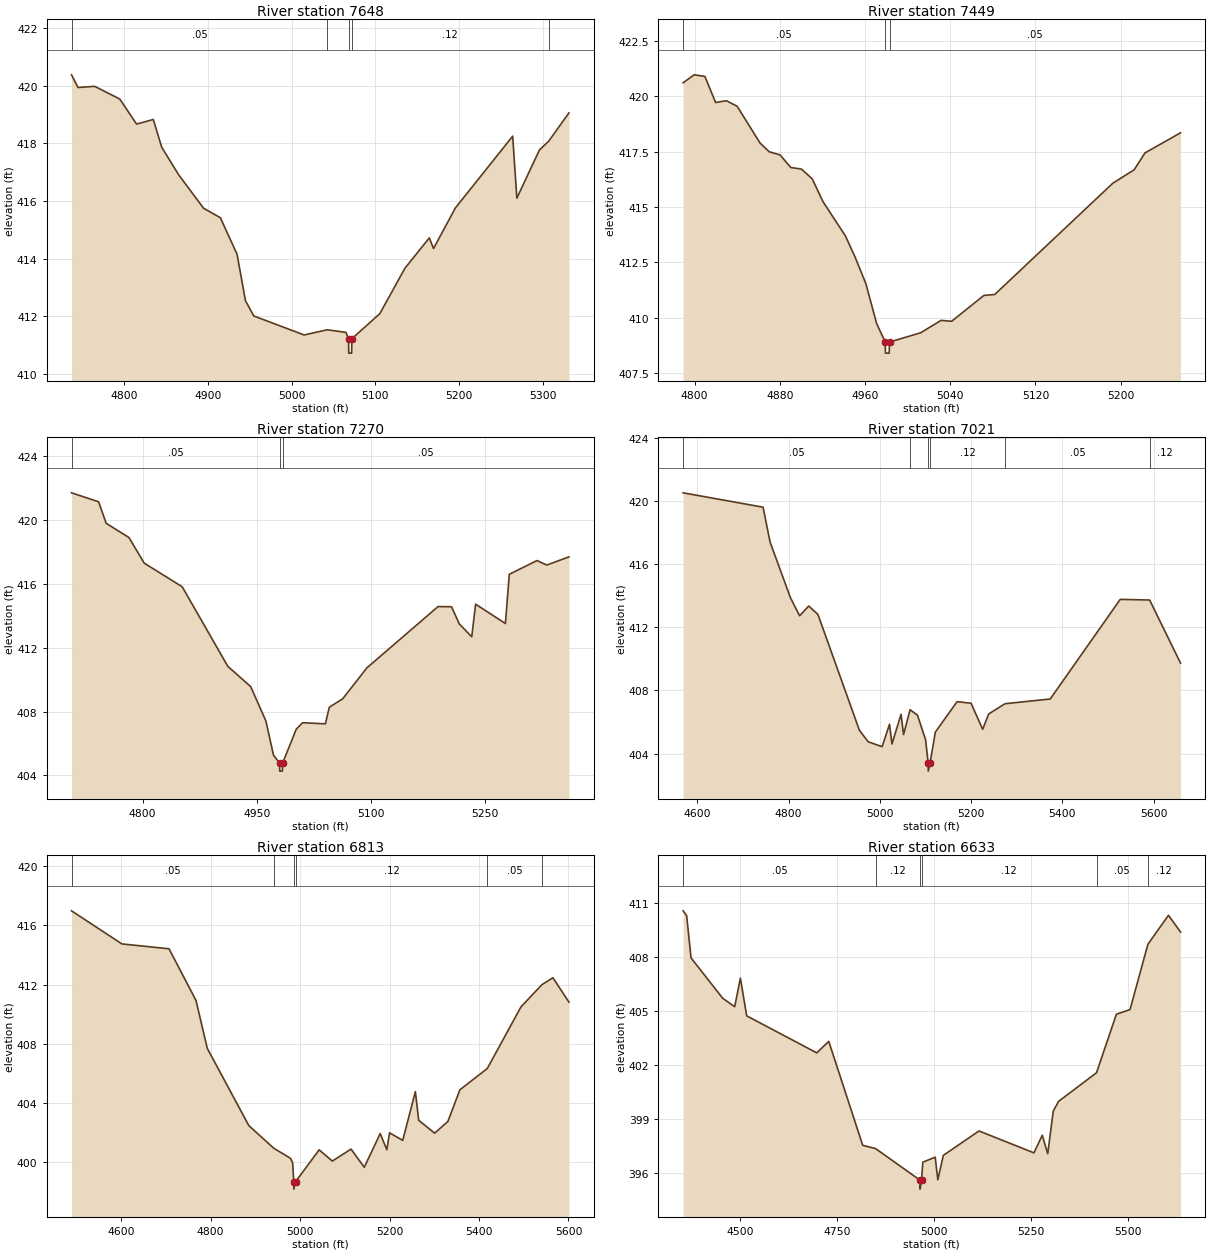
Type RM Length L Ch R = 1,7648,199,199,199
BEGIN DESCRIPTION:
Lacy 126 1341
END DESCRIPTION:
XS GIS Cut Line= 3
      2726762.06      6864403.35      2726777.89      6864667.83
      2726744.51      6864996.09
#Sta/Elev= 30
  4736.7  420.38  4744.4  419.94  4764.4  419.98  4794.4  419.54  4814.5  418.67
  4834.5  418.83  4844.5  417.87  4864.6  416.92  4894.6  415.75  4914.7  415.42
  4934.7  414.15  4944.7  412.54  4954.7  412.01  5014.9  411.35  5042.6  411.53
  5064.9  411.44  5068.0  411.22  5068.2  410.72  5071.7  410.72  5072.0  411.22
  5105.4  412.09  5135.5  413.67  5164.6  414.72  5169.6  414.35  5195.8  415.76
  5264.3  418.25  5269.3  416.10  5296.3  417.77  5307.5  418.08  5331.6  419.06
#Mann=5,-1,0
  4736.7    0.05       0  5042.6    0.12       0  5068.0    0.05       0
  5072.0    0.12       0  5307.5    0.05       0
Bank Sta=5068,5072
Exp/Cntr=0.3,0.1

Type RM Length L Ch R = 1,7449,179,179,179
BEGIN DESCRIPTION:
Lacy 126 1339
END DESCRIPTION:
XS GIS Cut Line= 3
      2726582.46      6864550.74      2726610.30      6864772.14
      2726641.16      6865014.13
#Sta/Elev= 30
  4789.2  420.61  4799.5  420.97  4809.6  420.90  4819.7  419.72  4829.8  419.80
  4839.9  419.55  4861.4  417.89  4870.1  417.49  4880.2  417.35  4890.3  416.78
  4900.3  416.71  4910.4  416.27  4920.5  415.24  4941.7  413.68  4950.7  412.73
  4960.8  411.53  4970.9  409.73  4979.0  408.89  4979.2  408.39  4982.7  408.39
  4983.0  408.89  5012.3  409.31  5031.4  409.87  5041.4  409.83  5071.7  411.00
  5081.8  411.04  5192.7  416.07  5212.8  416.68  5222.9  417.44  5256.3  418.35
#Mann=3,-1,0
  4789.2    0.05       0  4979.0    0.05       0  4983.0    0.05       0
Bank Sta=4979,4983
Exp/Cntr=0.3,0.1

Type RM Length L Ch R = 1,7270,249,249,249
BEGIN DESCRIPTION:
Lacy 126 1338
END DESCRIPTION:
XS GIS Cut Line= 3
      2726468.34      6864565.37      2726464.82      6864872.64
      2726537.61      6865212.03
#Sta/Elev= 30
  4706.4  421.69  4742.0  421.13  4752.0  419.78  4782.0  418.89  4802.0  417.29
  4852.0  415.81  4912.0  410.83  4942.1  409.56  4962.1  407.41  4972.1  405.27
  4980.1  404.77  4980.3  404.27  4983.8  404.27  4984.1  404.77  5002.1  406.90
  5010.4  407.30  5040.4  407.23  5045.5  408.27  5063.2  408.80  5094.9  410.73
  5188.6  414.57  5206.3  414.56  5216.6  413.48  5232.9  412.68  5238.0  414.72
  5277.2  413.51  5282.3  416.59  5318.8  417.45  5331.7  417.17  5360.8  417.68
#Mann=3,-1,0
  4706.4    0.05       0  4980.1    0.05       0  4984.1    0.05       0
Bank Sta=4980.1,4984.1
Exp/Cntr=0.3,0.1

Type RM Length L Ch R = 1,7021,208,208,208
BEGIN DESCRIPTION:
Lacy 126 1354
END DESCRIPTION:
XS GIS Cut Line= 3
      2726251.00      6864536.03      2726273.58      6864966.54
      2726497.29      6865586.51
#Sta/Elev= 30
  4568.9  420.52  4744.1  419.61  4759.5  417.40  4804.2  413.87  4824.2  412.73
  4844.2  413.35  4864.3  412.82  4955.1  405.49  4974.4  404.75  5005.0  404.44
  5021.3  405.86  5026.6  404.61  5046.6  406.49  5052.0  405.21  5066.4  406.78
  5082.6  406.43  5100.4  404.87  5106.0  403.39  5106.2  402.89  5110.0  403.39
  5121.7  405.36  5169.3  407.29  5200.0  407.19  5225.4  405.54  5238.6  406.51
  5274.4  407.16  5373.5  407.46  5526.9  413.77  5591.4  413.73  5659.1  409.73
#Mann=6,-1,0
  4568.9    0.05       0  5066.4    0.12       0  5106.0    0.05       0
  5110.0    0.12       0  5274.4    0.05       0  5591.4    0.12       0
Bank Sta=5106,5110
Exp/Cntr=0.3,0.1

Type RM Length L Ch R = 1,6813,180,180,180
BEGIN DESCRIPTION:
Lacy 126 1353
END DESCRIPTION:
XS GIS Cut Line= 3
      2726049.17      6864574.22      2726101.92      6865074.53
      2726454.92      6865570.81
#Sta/Elev= 30
  4489.0  416.99  4601.6  414.75  4707.0  414.42  4767.3  410.92  4792.5  407.68
  4885.4  402.45  4941.5  400.91  4978.4  400.24  4983.4  399.92  4985.8  398.65
  4986.0  398.15  4989.8  398.65  5042.6  400.81  5072.1  400.05  5113.9  400.86
  5143.5  399.63  5179.1  401.91  5193.9  400.82  5200.0  401.96  5229.5  401.45
  5257.7  404.75  5265.2  402.81  5300.9  401.94  5330.4  402.73  5357.4  404.88
  5418.4  406.31  5493.9  410.49  5540.6  411.99  5565.2  412.46  5601.1  410.81
#Mann=6,-1,0
  4489.0    0.05       0  4941.5    0.12       0  4985.8    0.07       0
  4989.8    0.12       0  5418.4    0.05       0  5540.6    0.12       0
Bank Sta=4985.8,4989.8
Exp/Cntr=0.3,0.1

Type RM Length L Ch R = 1,6633,431,431,431
BEGIN DESCRIPTION:
Lacy 126 1352
END DESCRIPTION:
XS GIS Cut Line= 3
      2725736.46      6864551.76      2725951.00      6865161.41
      2726415.78      6865595.26
#Sta/Elev= 30
  4353.7  410.58  4362.8  410.31  4374.1  407.96  4455.7  405.71  4486.6  405.24
  4501.3  406.83  4517.6  404.73  4698.1  402.67  4729.1  403.31  4816.6  397.52
  4849.7  397.34  4964.2  395.58  4964.4  395.08  4968.2  395.58  4971.5  396.58
  5003.4  396.86  5010.2  395.60  5024.4  396.96  5116.3  398.32  5257.9  397.10
  5279.4  398.08  5293.5  397.05  5307.7  399.42  5321.5  399.97  5419.2  401.56
  5470.4  404.82  5505.6  405.08  5551.7  408.72  5604.7  410.33  5635.8  409.40
#Mann=6,-1,0
  4353.7    0.05       0  4849.7    0.12       0  4964.2    0.07       0
  4968.2    0.12       0  5419.2    0.05       0  5551.7    0.12       0
Bank Sta=4964.2,4968.2
Exp/Cntr=0.3,0.1

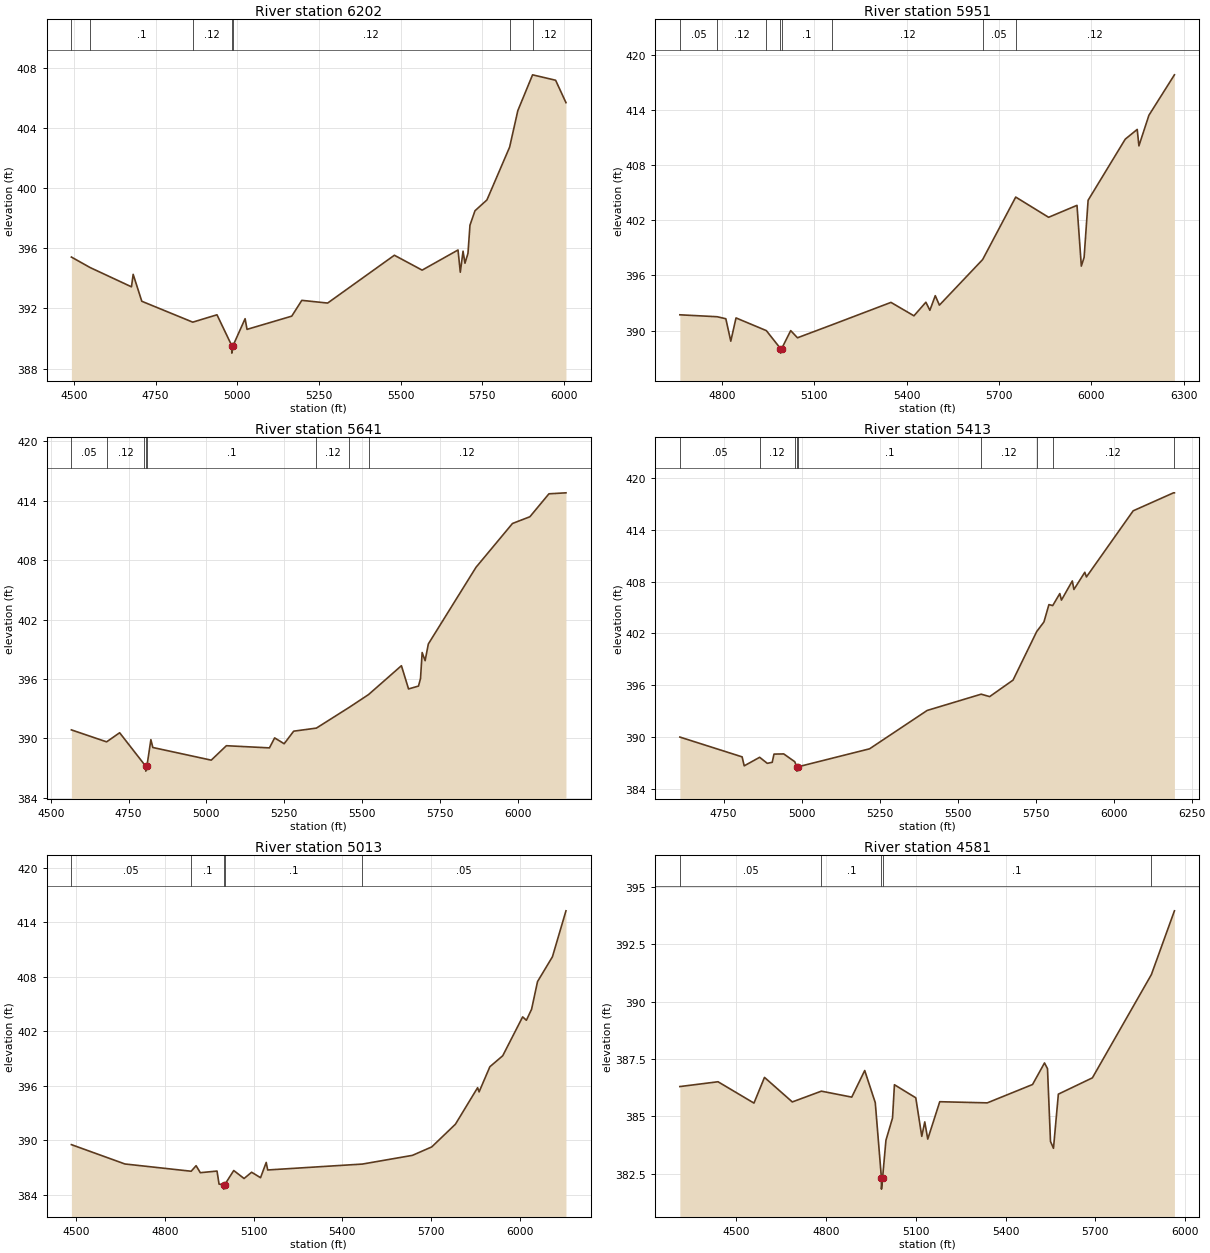
Type RM Length L Ch R = 1,6202,251,251,251
BEGIN DESCRIPTION:
Lacy 126 1349
END DESCRIPTION:
XS GIS Cut Line= 3
      2725395.04      6864655.11      2725545.40      6865140.34
      2726401.02      6865670.77
#Sta/Elev= 30
  4492.0  395.42  4549.5  394.72  4676.0  393.44  4681.2  394.27  4707.6  392.48
  4863.7  391.09  4937.9  391.58  4983.1  389.53  4983.3  389.03  4987.1  389.53
  5024.0  391.32  5029.9  390.61  5166.9  391.49  5197.7  392.54  5276.8  392.36
  5481.2  395.54  5566.2  394.55  5676.1  395.89  5683.1  394.41  5691.5  395.81
  5697.4  395.01  5706.6  395.67  5712.7  397.54  5728.1  398.50  5764.7  399.22
  5834.1  402.73  5859.3  405.16  5904.4  407.54  5975.0  407.18  6006.7  405.69
#Mann=7,-1,0
  4492.0    0.05       0  4549.5     0.1       0  4863.7    0.12       0
  4983.1    0.07       0  4987.1    0.12       0  5834.1    0.05       0
  5904.4    0.12       0
Bank Sta=4983.1,4987.1
Exp/Cntr=0.3,0.1

Type RM Length L Ch R = 1,5951,310,310,310
BEGIN DESCRIPTION:
Lacy 126 1351
END DESCRIPTION:
XS GIS Cut Line= 3
      2725261.61      6865224.04      2725564.47      6865370.93
      2726721.48      6865895.80
#Sta/Elev= 30
  4663.4  391.71  4784.6  391.50  4812.8  391.28  4828.9  388.84  4845.9  391.37
  4944.4  389.99  4990.4  388.04  4990.7  387.54  4994.4  388.04  5023.6  389.99
  5045.6  389.21  5159.3  390.64  5349.4  393.06  5424.1  391.60  5462.9  393.08
  5475.8  392.20  5493.4  393.79  5506.8  392.76  5647.3  397.72  5754.8  404.52
  5861.6  402.32  5953.9  403.62  5968.0  397.01  5977.0  397.95  5990.0  404.17
  6110.7  410.82  6149.6  411.88  6155.1  410.09  6187.6  413.42  6270.5  417.82
#Mann=8,-1,0
  4663.4    0.05       0  4784.6    0.12       0  4944.4     0.1       0
  4990.4    0.07       0  4994.4     0.1       0  5159.3    0.12       0
  5647.3    0.05       0  5754.8    0.12       0
Bank Sta=4990.4,4994.4
Exp/Cntr=0.3,0.1

Type RM Length L Ch R = 1,5641,228,228,228
BEGIN DESCRIPTION:
Lacy 126 1350
END DESCRIPTION:
XS GIS Cut Line= 3
      2725176.36      6865384.04      2725525.66      6865640.94
      2726611.22      6866035.09
#Sta/Elev= 30
  4566.4  390.84  4679.5  389.63  4721.4  390.55  4800.3  387.36  4805.0  387.17
  4805.3  386.67  4809.0  387.17  4821.7  389.85  4827.9  389.06  5015.6  387.78
  5064.2  389.24  5202.5  389.02  5219.2  390.03  5249.8  389.44  5280.4  390.71
  5353.3  391.02  5459.3  393.13  5520.8  394.41  5626.4  397.33  5649.3  394.98
  5681.2  395.27  5687.7  396.03  5693.0  398.66  5702.5  397.84  5712.9  399.53
  5866.0  407.28  5983.1  411.71  6039.0  412.39  6100.2  414.71  6154.9  414.81
#Mann=8,-1,0
  4566.4    0.05       0  4679.5    0.12       0  4800.3     0.1       0
  4805.0    0.07       0  4809.0     0.1       0  5353.3    0.12       0
  5459.3     0.1       0  5520.8    0.12       0
Bank Sta=4805,4809
Exp/Cntr=0.3,0.1

Type RM Length L Ch R = 1,5413,400,400,400
BEGIN DESCRIPTION:
Lacy 126 1348
END DESCRIPTION:
XS GIS Cut Line= 3
      2725137.03      6865637.36      2725475.83      6865831.13
      2726629.86      6866139.83
#Sta/Elev= 30
  4609.7  390.02  4809.2  387.73  4815.9  386.69  4865.4  387.68  4889.9  386.98
  4905.7  387.10  4911.4  388.05  4942.6  388.07  4977.9  387.17  4984.3  386.58
  4984.5  386.08  4988.3  386.58  5217.6  388.66  5402.3  393.10  5575.3  394.98
  5602.5  394.70  5677.5  396.61  5753.2  402.22  5776.5  403.34  5792.4  405.34
  5804.6  405.23  5827.3  406.62  5832.5  405.86  5867.4  408.08  5872.5  407.09
  5907.4  409.08  5912.6  408.54  6062.4  416.19  6191.7  418.27  6194.6  418.27
#Mann=9,-1,0
  4609.7    0.05       0  4865.4    0.12       0  4977.9     0.1       0
  4984.3    0.07       0  4988.3     0.1       0  5575.3    0.12       0
  5753.2    0.05       0  5804.6    0.12       0  6191.7    0.05       0
Bank Sta=4984.3,4988.3
Exp/Cntr=0.3,0.1

Type RM Length L Ch R = 1,5013,432,432,432
BEGIN DESCRIPTION:
Lacy 126 1347
END DESCRIPTION:
XS GIS Cut Line= 3
      2725052.30      6865808.58      2725433.85      6866157.59
      2726581.45      6866303.16
#Sta/Elev= 30
  4482.9  389.51  4664.1  387.38  4888.3  386.58  4905.0  387.19  4919.2  386.42
  4975.8  386.60  4982.7  385.16  4998.0  385.11  4998.2  384.61  5002.0  385.11
  5032.4  386.66  5067.3  385.78  5092.9  386.47  5123.1  385.87  5142.3  387.55
  5147.3  386.72  5467.9  387.37  5637.2  388.33  5702.6  389.26  5782.7  391.76
  5857.7  395.78  5862.8  395.32  5899.3  398.09  5942.8  399.30  6010.2  403.58
  6022.9  403.21  6040.4  404.42  6060.6  407.47  6111.0  410.20  6156.8  415.26
#Mann=5,-1,0
  4482.9    0.05       0  4888.3     0.1       0  4998.0    0.07       0
  5002.0     0.1       0  5467.9    0.05       0
Bank Sta=4998,5002
Exp/Cntr=0.3,0.1

Type RM Length L Ch R = 1,4581,0,0,0
BEGIN DESCRIPTION:
Lacy 126 1346
END DESCRIPTION:
XS GIS Cut Line= 3
      2724965.11      6866083.60      2725541.63      6866538.66
      2726460.02      6866499.53
#Sta/Elev= 30
  4310.7  386.30  4438.3  386.51  4558.5  385.58  4593.7  386.70  4686.7  385.63
  4783.9  386.10  4885.5  385.84  4928.8  387.00  4964.1  385.60  4984.6  382.33
  4984.8  381.83  4988.6  382.33  4999.8  383.96  5021.8  384.93  5028.2  386.38
  5099.6  385.81  5119.6  384.13  5129.6  384.76  5139.6  384.01  5179.7  385.64
  5338.7  385.59  5490.0  386.39  5530.0  387.33  5540.0  387.08  5550.0  383.91
  5560.0  383.61  5576.3  385.97  5690.1  386.68  5887.3  391.18  5964.4  393.96
#Mann=5,-1,0
  4310.7    0.05       0  4783.9     0.1       0  4984.6    0.07       0
  4988.6     0.1       0  5887.3    0.05       0
Bank Sta=4984.6,4988.6
Exp/Cntr=0.3,0.1

Chan Stop Cuts=-1