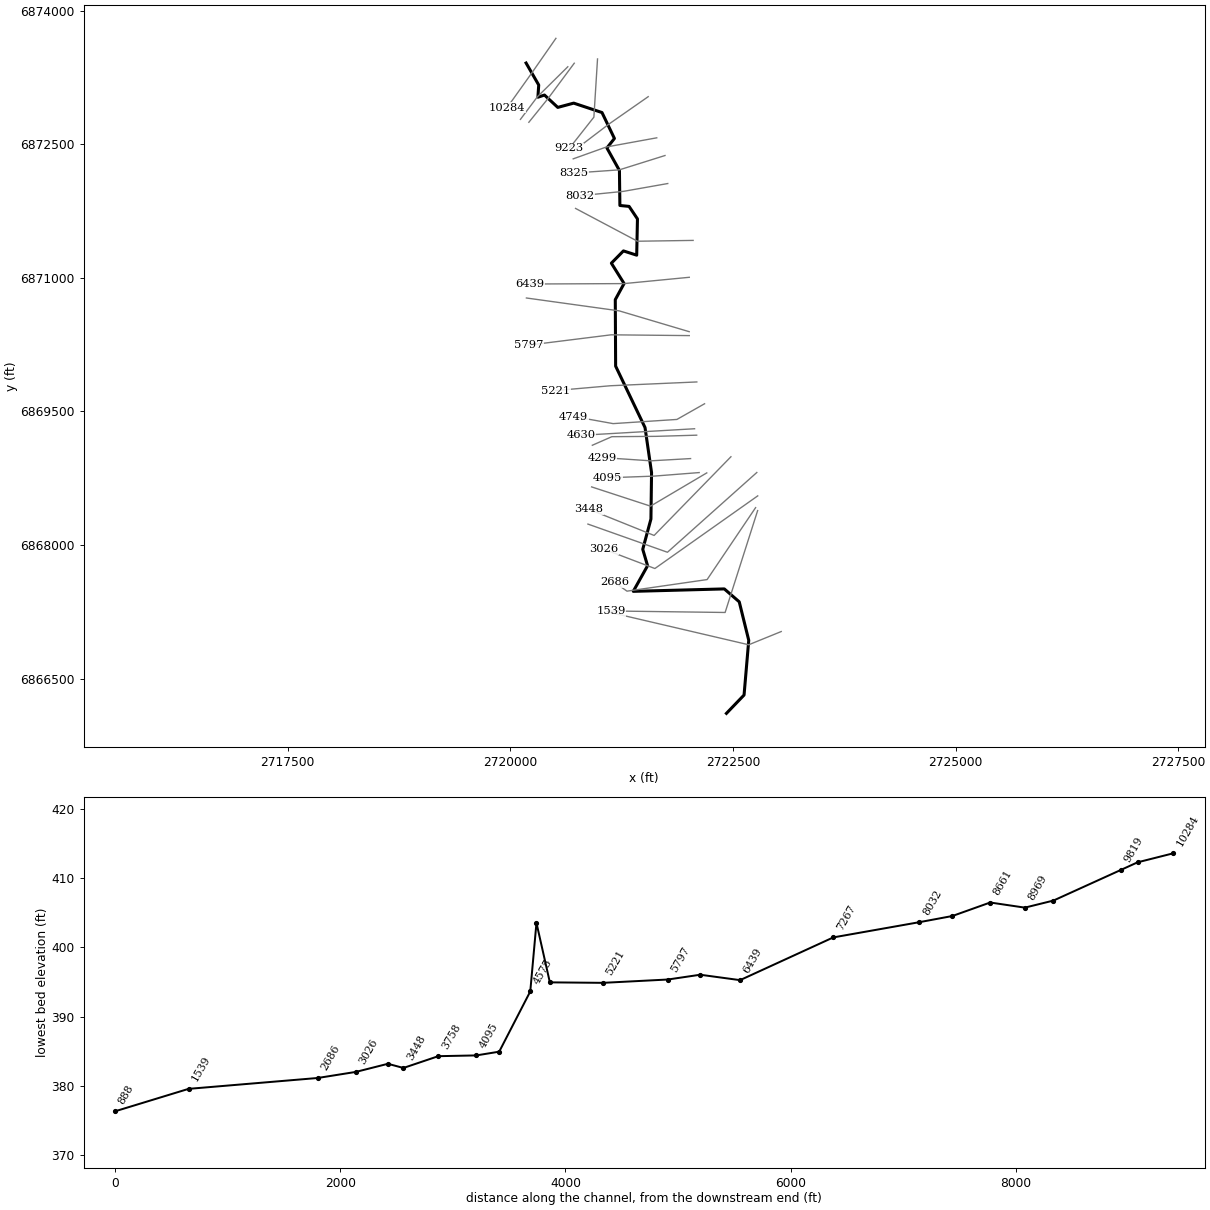
--- Lacy 127.prj (project) ---

Proj Title=Lacy 127 Base Level Engineering
Current Plan=p01
Default Exp/Contr=0.3,0.1
English Units
Geom File=g01
Flow File=f01
Plan File=p01
BEGIN DESCRIPTION:
Lacy 127
END DESCRIPTION:

--- Lacy 127.p01 (plan) ---

Plan Title=Multiple Run
Short Identifier=Multiple
Geom File=g01
Flow File=f01
Subcritical Flow
K Sum by GR= 0
Std Step Tol= 0.01
Critical Tol= 0.01
Num of Std Step Trials= 20
Max Error Tol= 0.3
Flow Tol Ratio= 0.001
Split Flow NTrial= 30
Split Flow Tol= 0.02
Split Flow Ratio= 0.02
Log Output Level= 0
Friction Slope Method= 1
Unsteady Friction Slope Method= 2
Unsteady Bridges Friction Slope Method= 1
Parabolic Critical Depth
Global Vel Dist=  1 , 1 , 1
Global Log Level= 0
CheckData=True
Encroach Param= -1, 0, 0, 0
BEGIN DESCRIPTION:
Multiple Run
END DESCRIPTION:

--- Lacy 127.f01 (steady flow) ---

Flow Title=Multiple
Number of Profiles=7
Profile Names=10-year,25-year,50-year,1pct_min,100-year,1pct_plu,500-year
River Rch & RM= Lacy 127,Reach-1,10284
     372     479     561     327     652    1301     878
River Rch & RM= Lacy 127,Reach-1,6439
     584     771     920     544    1086    2167    1511
Boundary for River Rch & Prof#=Lacy 127,Reach-1,1
Up Type=0
Dn Type=3
Dn Slope=0.005
Boundary for River Rch & Prof#=Lacy 127,Reach-1,2
Up Type=0
Dn Type=3
Dn Slope=0.005
Boundary for River Rch & Prof#=Lacy 127,Reach-1,3
Up Type=0
Dn Type=3
Dn Slope=0.005
Boundary for River Rch & Prof#=Lacy 127,Reach-1,4
Up Type=0
Dn Type=3
Dn Slope=0.005
Boundary for River Rch & Prof#=Lacy 127,Reach-1,5
Up Type=0
Dn Type=3
Dn Slope=0.005
Boundary for River Rch & Prof#=Lacy 127,Reach-1,6
Up Type=0
Dn Type=3
Dn Slope=0.005
Boundary for River Rch & Prof#=Lacy 127,Reach-1,7
Up Type=0
Dn Type=3
Dn Slope=0.005

--- Lacy 127.g01 (geometry) ---

Geom Title=Existing Conditions

River Reach=Lacy 127,Reach-1
Reach XY= 30
      2720176.00      6873411.00      2720317.93      6873164.30
      2720308.79      6873027.24      2720382.66      6873051.69
      2720531.89      6872912.96      2720710.61      6872960.91
      2721028.55      6872855.27      2721168.11      6872564.22
      2721083.64      6872457.67      2721224.36      6872204.96
      2721229.46      6871812.03      2721332.68      6871801.70
      2721426.85      6871661.01      2721418.19      6871254.15
      2721269.33      6871302.03      2721133.77      6871164.41
      2721276.50      6870936.03      2721177.80      6870754.89
      2721181.69      6870008.58      2721511.73      6869319.47
      2721585.08      6868813.82      2721578.12      6868292.40
      2721486.21      6867952.57      2721540.40      6867768.53
      2721379.76      6867480.79      2722402.20      6867508.04
      2722569.88      6867363.18      2722676.59      6866931.05
      2722623.95      6866316.84      2722426.00      6866111.00

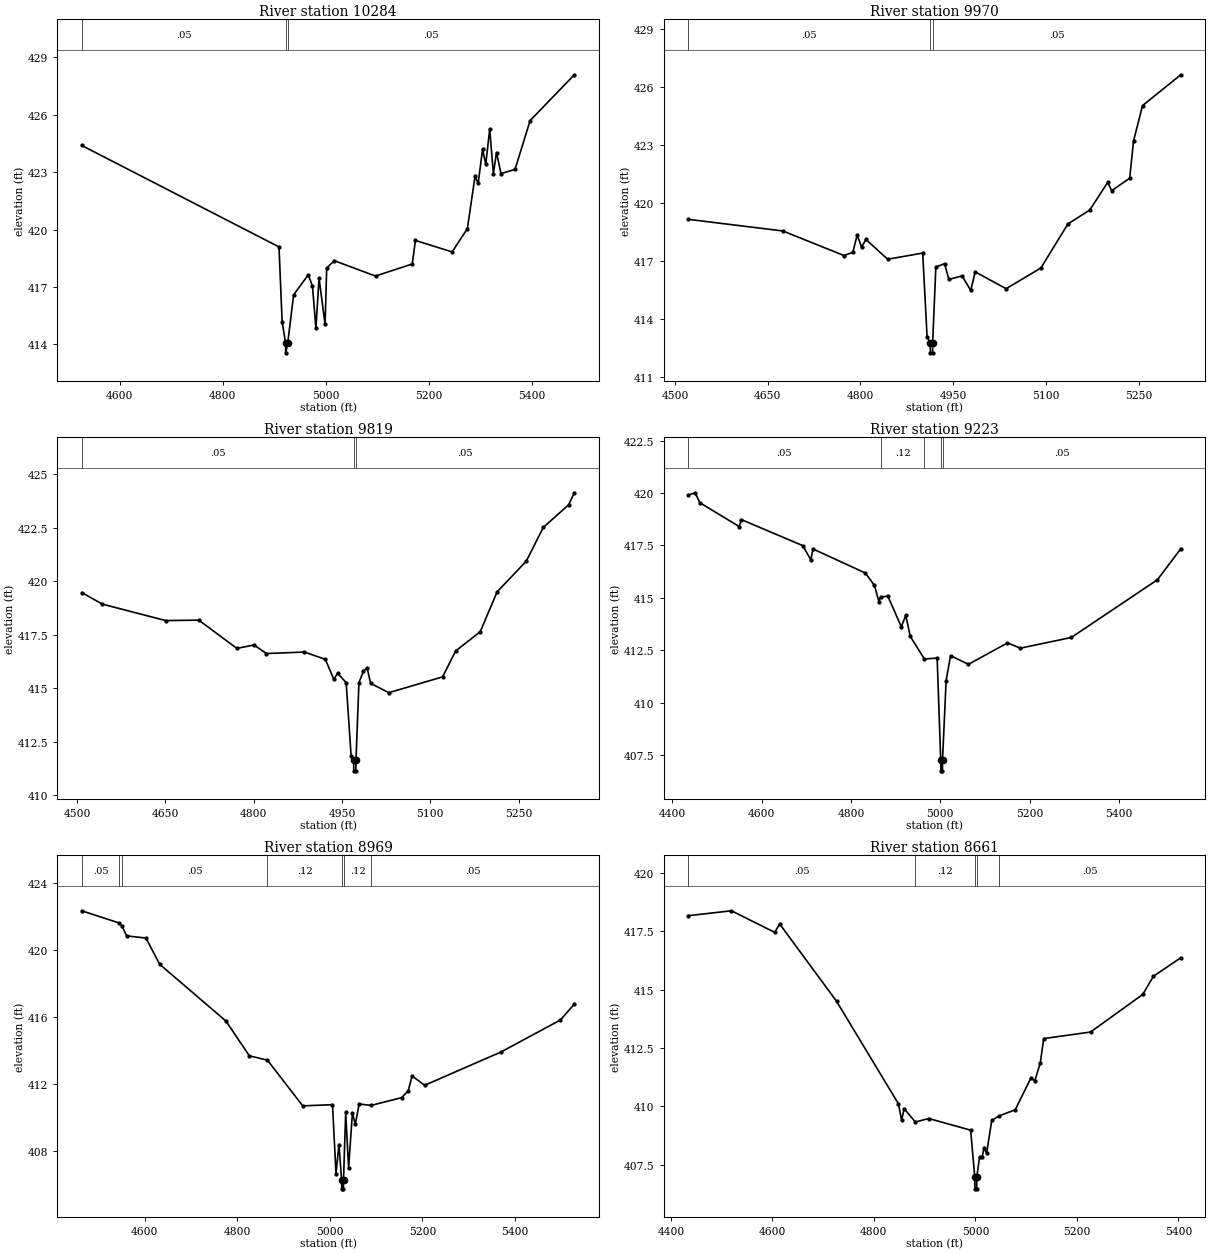
Type RM Length L Ch R = 1,10284,314,314,314
BEGIN DESCRIPTION:
Lacy 127 1276
END DESCRIPTION:
XS GIS Cut Line= 3
      2720510.98      6873688.17      2720241.13      6873300.91
      2719960.38      6872907.40
#Sta/Elev= 30
  4526.7  424.39  4909.3  419.09  4915.4  415.17  4922.2  414.06  4922.4  413.56
  4926.2  414.06  4937.7  416.59  4966.0  417.63  4974.2  417.05  4980.9  414.85
  4987.0  417.46  4998.7  415.04  5001.8  417.99  5016.6  418.37  5096.5  417.57
  5167.8  418.20  5173.9  419.43  5245.2  418.83  5274.7  420.05  5289.5  422.78
  5295.6  422.41  5304.2  424.19  5310.3  423.40  5318.0  425.24  5325.1  422.92
  5331.2  424.02  5339.9  422.92  5367.1  423.14  5396.4  425.69  5482.1  428.08
#Mann=3,-1,0
  4526.7    0.05       0  4922.2    0.04       0  4926.2    0.05       0
Bank Sta=4922.2,4926.2
Exp/Cntr=0.3,0.1

Type RM Length L Ch R = 1,9970,151,151,151
BEGIN DESCRIPTION:
Lacy 127 1282
END DESCRIPTION:
XS GIS Cut Line= 3
      2720644.58      6873369.14      2720303.14      6873032.19
      2720112.38      6872778.40
#Sta/Elev= 30
  4521.2  419.16  4674.4  418.56  4773.4  417.29  4787.6  417.46  4794.7  418.35
  4801.7  417.73  4808.8  418.12  4844.1  417.10  4900.7  417.42  4907.8  413.11
  4912.8  412.77  4913.1  412.27  4916.6  412.27  4916.8  412.77  4922.0  416.70
  4936.1  416.87  4943.1  416.06  4964.4  416.24  4978.5  415.49  4985.6  416.45
  5035.7  415.58  5092.0  416.65  5135.7  418.92  5171.1  419.64  5200.2  421.07
  5206.5  420.64  5235.7  421.28  5241.9  423.20  5256.5  425.03  5318.4  426.62
#Mann=3,-1,0
  4521.2    0.05       0  4912.8    0.04       0  4916.8    0.05       0
Bank Sta=4912.8,4916.8
Exp/Cntr=0.3,0.1

Type RM Length L Ch R = 1,9819,596,596,596
BEGIN DESCRIPTION:
Lacy 127 1281
END DESCRIPTION:
XS GIS Cut Line= 3
      2720717.04      6873408.93      2720423.90      6873014.22
      2720207.06      6872745.96
#Sta/Elev= 30
  4508.0  419.48  4542.8  418.94  4650.5  418.17  4706.8  418.19  4771.5  416.87
  4800.7  417.03  4821.5  416.63  4886.2  416.70  4921.7  416.36  4936.3  415.42
  4942.5  415.71  4957.1  415.27  4965.5  411.86  4969.8  411.65  4970.0  411.15
  4973.5  411.15  4973.8  411.65  4978.8  415.27  4986.4  415.80  4992.6  415.97
  4998.6  415.24  5029.5  414.80  5120.8  415.54  5143.1  416.75  5184.8  417.65
  5213.5  419.51  5263.1  420.95  5291.9  422.52  5335.0  423.58  5344.6  424.14
#Mann=3,-1,0
  4508.0    0.05       0  4969.8    0.04       0  4973.8    0.05       0
Bank Sta=4969.8,4973.8
Exp/Cntr=0.3,0.1

Type RM Length L Ch R = 1,9223,254,254,254
BEGIN DESCRIPTION:
Lacy 127 1280
END DESCRIPTION:
XS GIS Cut Line= 3
      2720978.32      6873456.70      2720937.41      6872803.49
      2720660.53      6872452.30
#Sta/Elev= 30
  4436.0  419.90  4451.7  420.01  4461.8  419.54  4550.0  418.40  4555.0  418.73
  4692.2  417.49  4710.2  416.81  4715.2  417.33  4832.5  416.18  4852.5  415.59
  4862.5  414.82  4866.1  415.04  4882.6  415.08  4912.6  413.62  4922.7  414.16
  4932.7  413.16  4964.4  412.08  4992.8  412.13  5000.8  407.25  5001.1  406.75
  5004.6  406.75  5004.8  407.25  5012.8  411.05  5022.8  412.24  5062.9  411.83
  5150.1  412.85  5179.0  412.60  5292.9  413.11  5485.3  415.86  5537.7  417.34
#Mann=5,-1,0
  4436.0    0.05       0  4866.1    0.12       0  4964.4    0.05       0
  5000.8    0.05       0  5004.8    0.05       0
Bank Sta=5000.8,5004.8
Exp/Cntr=0.3,0.1

Type RM Length L Ch R = 1,8969,308,308,308
BEGIN DESCRIPTION:
Lacy 127 1279
END DESCRIPTION:
XS GIS Cut Line= 3
      2721547.62      6873033.40      2721105.70      6872725.27
      2720687.49      6872407.30
#Sta/Elev= 30
  4464.1  422.35  4545.0  421.62  4551.5  421.42  4561.0  420.85  4602.8  420.72
  4632.5  419.15  4775.6  415.76  4826.2  413.68  4865.3  413.42  4941.5  410.69
  5005.8  410.76  5013.4  406.63  5019.7  408.38  5025.6  406.23  5025.8  405.73
  5029.3  405.73  5029.6  406.23  5034.3  410.31  5040.6  406.98  5048.8  410.26
  5055.1  409.59  5063.4  410.80  5089.8  410.72  5154.9  411.18  5169.5  411.59
  5177.7  412.48  5204.8  411.92  5369.1  413.90  5498.0  415.82  5528.2  416.77
#Mann=7,-1,0
  4464.1    0.05       0  4545.0    0.12       0  4551.5    0.05       0
  4865.3    0.12       0  5025.6    0.07       0  5029.6    0.12       0
  5089.8    0.05       0
Bank Sta=5025.6,5029.6
Exp/Cntr=0.3,0.1

Type RM Length L Ch R = 1,8661,336,336,336
BEGIN DESCRIPTION:
Lacy 127 1278
END DESCRIPTION:
XS GIS Cut Line= 3
      2721643.48      6872571.52      2721076.45      6872468.28
      2720705.35      6872335.48
#Sta/Elev= 30
  4434.2  418.16  4519.4  418.37  4604.4  417.45  4614.6  417.80  4726.4  414.50
  4848.4  410.11  4854.6  409.41  4859.7  409.90  4881.7  409.33  4908.0  409.48
  4990.7  408.98  4998.8  406.97  4999.1  406.47  5002.6  406.47  5002.8  406.97
  5008.2  407.83  5013.4  407.83  5016.8  408.21  5022.1  408.00  5032.3  409.40
  5047.5  409.60  5078.4  409.85  5109.1  411.20  5117.2  411.10  5127.9  411.86
  5134.6  412.90  5226.9  413.18  5329.7  414.79  5350.9  415.57  5404.7  416.36
#Mann=5,-1,0
  4434.2    0.05       0  4881.7    0.12       0  4998.8    0.07       0
  5002.8    0.12       0  5047.5    0.05       0
Bank Sta=4998.8,5002.8
Exp/Cntr=0.3,0.1

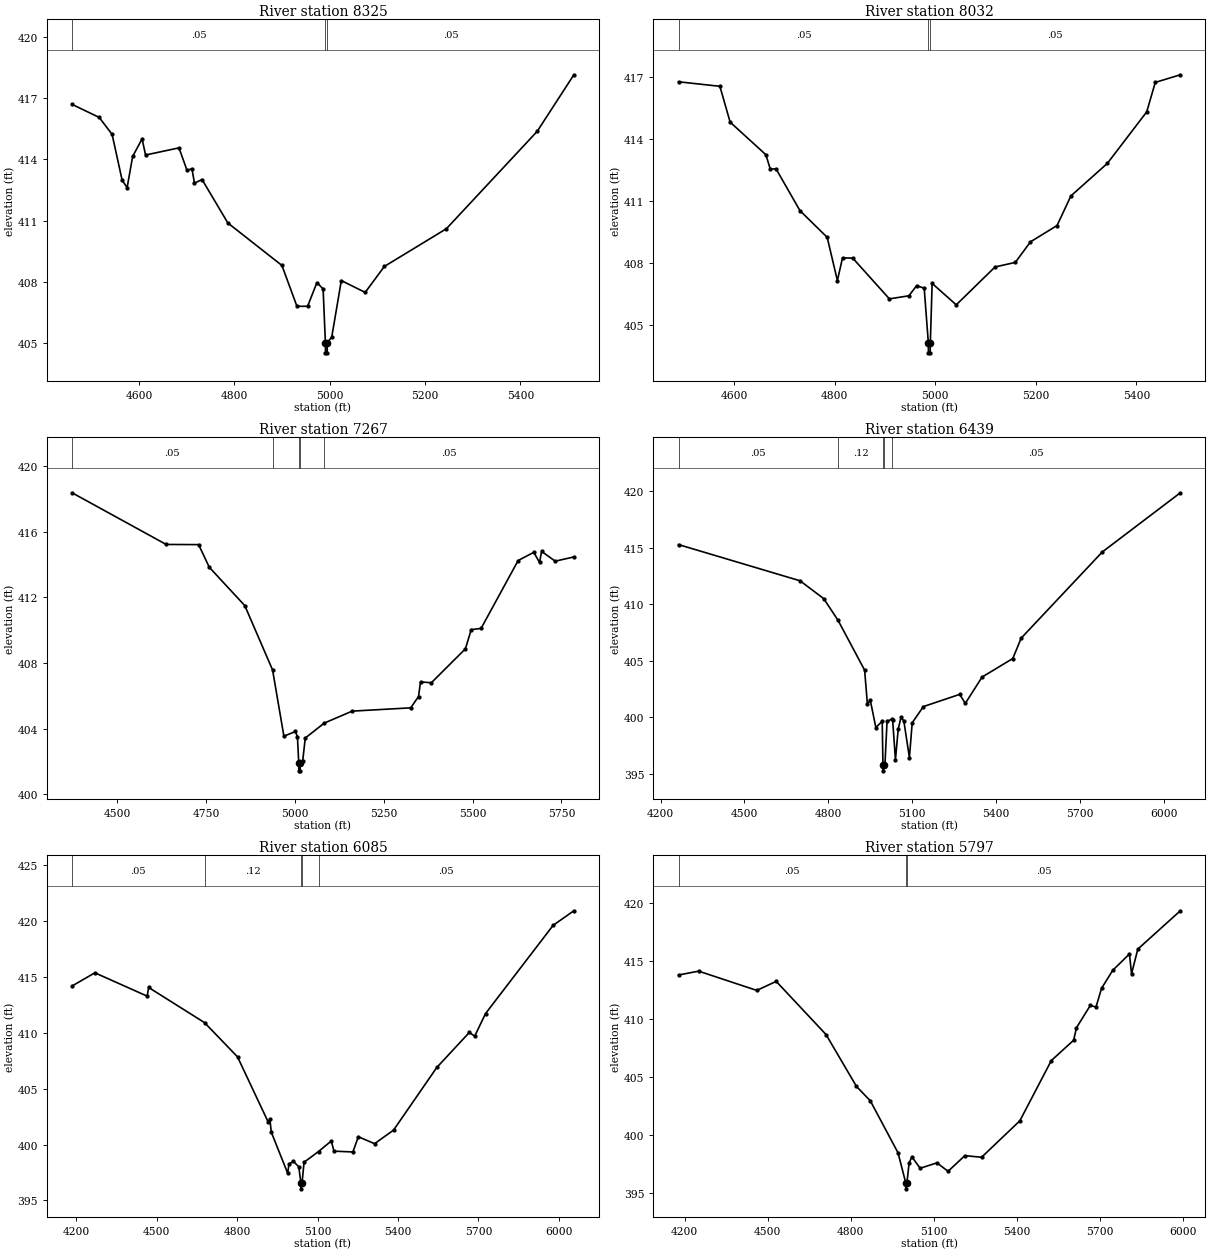
Type RM Length L Ch R = 1,8325,293,293,293
BEGIN DESCRIPTION:
Lacy 127 1277
END DESCRIPTION:
XS GIS Cut Line= 3
      2721736.17      6872372.79      2721223.30      6872211.93
      2720709.27      6872175.82
#Sta/Elev= 30
  4459.5  416.69  4516.5  416.05  4543.5  415.22  4564.5  412.98  4575.0  412.61
  4586.6  414.14  4606.4  415.00  4613.7  414.21  4683.8  414.56  4700.7  413.46
  4711.0  413.54  4716.3  412.83  4732.2  413.01  4786.4  410.88  4899.8  408.80
  4931.3  406.80  4953.7  406.80  4973.2  407.96  4986.2  407.65  4991.0  405.02
  4991.2  404.52  4994.7  404.52  4995.0  405.02  5004.3  405.29  5024.4  408.06
  5074.5  407.48  5114.6  408.75  5244.9  410.60  5435.4  415.37  5512.3  418.14
#Mann=3,-1,0
  4459.5    0.05       0  4991.0    0.04       0  4995.0    0.05       0
Bank Sta=4991,4995
Exp/Cntr=0.3,0.1

Type RM Length L Ch R = 1,8032,765,765,765
BEGIN DESCRIPTION:
Lacy 127 1275
END DESCRIPTION:
XS GIS Cut Line= 3
      2721766.99      6872058.33      2721270.01      6871970.57
      2720779.56      6871921.19
#Sta/Elev= 30
  4489.6  416.79  4571.8  416.57  4592.2  414.83  4663.2  413.25  4671.9  412.56
  4683.5  412.56  4731.1  410.53  4785.1  409.24  4805.4  407.14  4815.6  408.24
  4835.9  408.23  4908.8  406.25  4947.6  406.40  4962.9  406.89  4978.0  406.77
  4986.2  404.13  4986.4  403.63  4989.9  403.63  4990.2  404.13  4993.8  407.00
  5041.7  405.96  5118.9  407.80  5159.1  408.02  5189.3  409.02  5242.1  409.81
  5269.7  411.25  5342.2  412.83  5420.4  415.33  5437.4  416.76  5487.2  417.13
#Mann=3,-1,0
  4489.6    0.05       0  4986.2    0.04       0  4990.2    0.05       0
Bank Sta=4986.2,4990.2
Exp/Cntr=0.3,0.1

Type RM Length L Ch R = 1,7267,828,828,828
BEGIN DESCRIPTION:
Lacy 127 3460
END DESCRIPTION:
XS GIS Cut Line= 3
      2722052.05      6871420.01      2721427.05      6871410.67
      2720731.62      6871778.96
#Sta/Elev= 30
  4372.8  418.38  4637.6  415.23  4728.9  415.22  4758.9  413.84  4858.9  411.50
  4937.0  407.58  4968.9  403.54  5001.3  403.83  5007.0  403.50  5010.6  401.93
  5010.9  401.43  5014.4  401.43  5014.6  401.93  5021.7  402.02  5029.0  403.43
  5082.4  404.34  5161.0  405.07  5325.7  405.27  5347.7  405.96  5353.3  406.85
  5383.8  406.80  5479.7  408.87  5496.0  410.04  5523.7  410.11  5628.0  414.25
  5672.0  414.75  5688.3  414.13  5694.0  414.81  5732.3  414.21  5784.8  414.47
#Mann=5,-1,0
  4372.8    0.05       0  4937.0     0.1       0  5010.6    0.07       0
  5014.6     0.1       0  5082.4    0.05       0
Bank Sta=5010.6,5014.6
Exp/Cntr=0.3,0.1

Type RM Length L Ch R = 1,6439,354,354,354
BEGIN DESCRIPTION:
Lacy 127 1270
END DESCRIPTION:
XS GIS Cut Line= 3
      2722008.89      6871005.99      2721276.47      6870935.13
      2720216.42      6870930.55
#Sta/Elev= 30
  4264.0  415.26  4698.9  412.06  4783.7  410.48  4835.0  408.56  4930.0  404.16
  4940.0  401.14  4950.1  401.52  4970.2  399.09  4993.0  399.65  4995.6  395.76
  4995.8  395.26  4999.6  395.76  5002.6  395.76  5010.3  399.65  5027.8  399.82
  5030.3  399.74  5040.3  396.25  5050.3  398.97  5060.3  399.99  5070.3  399.68
  5090.3  396.43  5100.3  399.51  5140.3  400.94  5270.3  402.02  5290.3  401.22
  5350.3  403.55  5460.3  405.19  5490.3  406.99  5780.3  414.60  6059.9  419.84
#Mann=5,-1,0
  4264.0    0.05       0  4835.0    0.12       0  4995.6    0.07       0
  4999.6    0.12       0  5027.8    0.05       0
Bank Sta=4995.6,4999.6
Exp/Cntr=0.3,0.1

Type RM Length L Ch R = 1,6085,288,288,288
BEGIN DESCRIPTION:
Lacy 127 1271
END DESCRIPTION:
XS GIS Cut Line= 3
      2722007.61      6870395.52      2721221.94      6870629.07
      2720179.56      6870773.62
#Sta/Elev= 30
  4184.1  414.19  4269.2  415.37  4464.4  413.28  4469.6  414.06  4678.4  410.91
  4801.3  407.85  4916.1  402.00  4922.0  402.30  4927.2  401.12  4988.4  397.44
  4993.6  398.27  5009.7  398.50  5029.9  398.01  5038.0  396.54  5038.3  396.04
  5042.0  396.54  5049.6  398.42  5103.5  399.38  5151.1  400.32  5161.2  399.41
  5231.8  399.34  5252.0  400.70  5312.6  400.08  5383.3  401.29  5544.8  406.90
  5666.0  410.03  5686.2  409.70  5726.5  411.72  5978.9  419.62  6056.1  420.92
#Mann=5,-1,0
  4184.1    0.05       0  4678.4    0.12       0  5038.0    0.07       0
  5042.0    0.12       0  5103.5    0.05       0
Bank Sta=5038,5042
Exp/Cntr=0.3,0.1

Type RM Length L Ch R = 1,5797,576,576,576
BEGIN DESCRIPTION:
Lacy 127 1269
END DESCRIPTION:
XS GIS Cut Line= 3
      2722008.71      6870351.37      2721131.32      6870360.27
      2720203.66      6870244.48
#Sta/Elev= 30
  4178.1  413.77  4250.8  414.10  4460.8  412.44  4530.8  413.22  4710.8  408.64
  4820.8  404.17  4870.8  402.93  4970.9  398.45  4998.9  395.85  4999.1  395.35
  5002.9  395.85  5010.9  397.58  5020.9  398.11  5050.7  397.12  5111.3  397.59
  5151.6  396.86  5212.1  398.21  5272.5  398.07  5410.8  401.21  5524.5  406.40
  5605.1  408.15  5615.2  409.22  5665.6  411.16  5685.7  411.00  5705.9  412.62
  5746.2  414.17  5806.6  415.58  5814.2  413.87  5836.9  416.00  5990.4  419.30
#Mann=3,-1,0
  4178.1    0.05       0  4998.9    0.04       0  5002.9    0.05       0
Bank Sta=4998.9,5002.9
Exp/Cntr=0.3,0.1

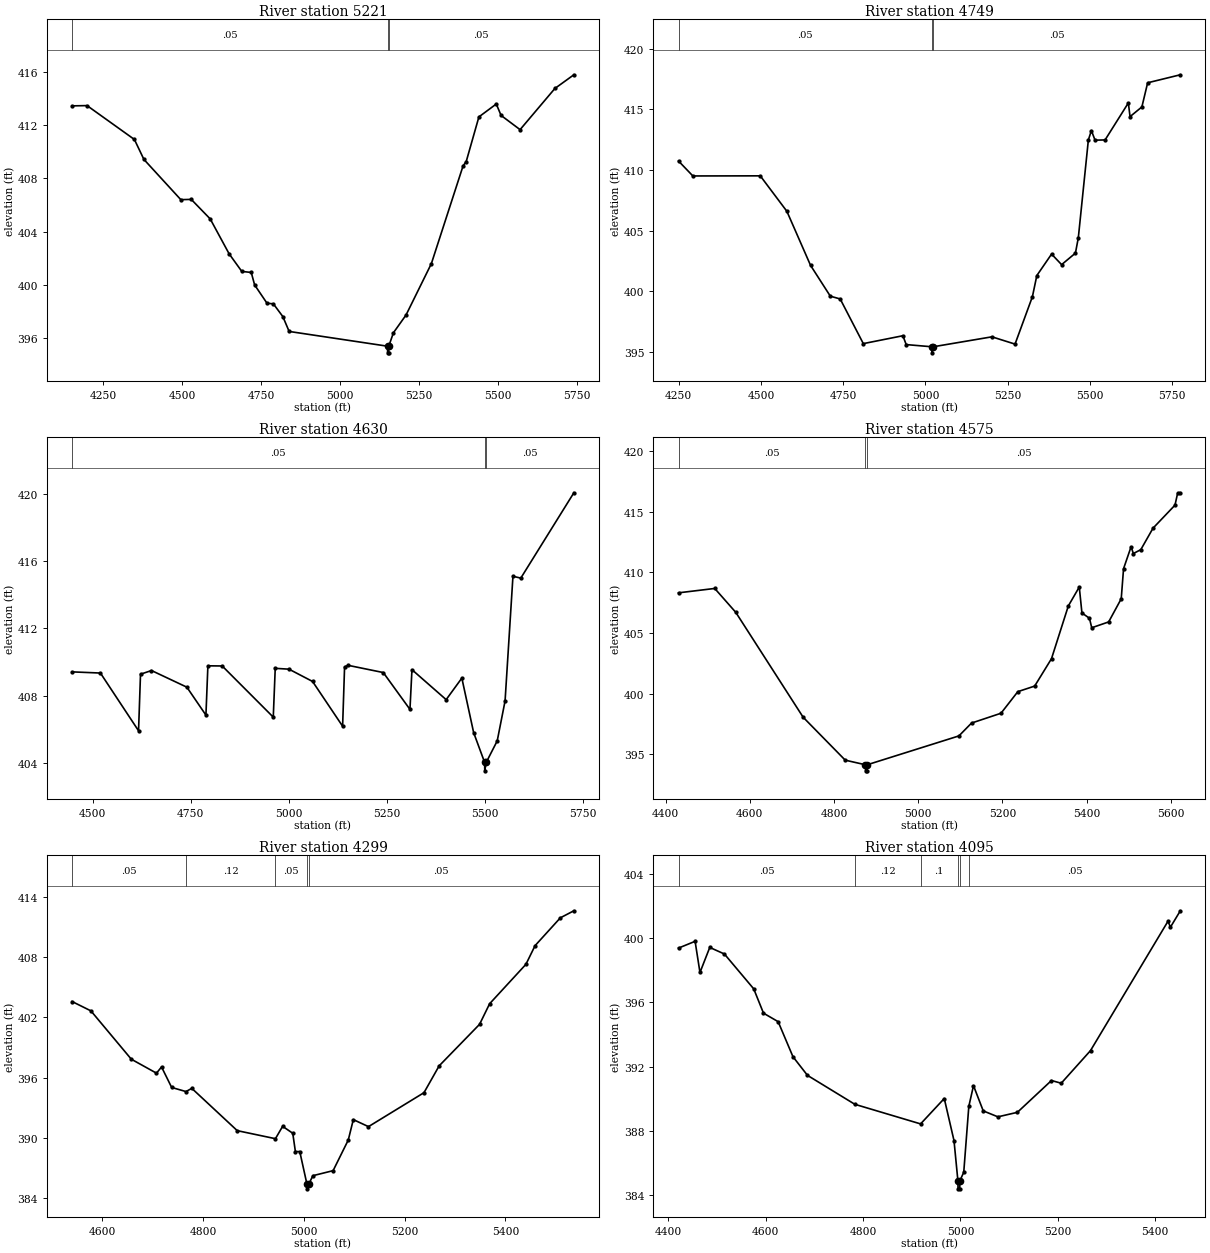
Type RM Length L Ch R = 1,5221,472,472,472
BEGIN DESCRIPTION:
Lacy 127 1268
END DESCRIPTION:
XS GIS Cut Line= 3
      2722093.43      6869831.21      2721124.06      6869788.62
      2720506.13      6869734.57
#Sta/Elev= 30
  4150.8  413.46  4198.3  413.48  4348.4  410.93  4378.5  409.43  4495.5  406.40
  4528.6  406.42  4588.7  404.95  4648.7  402.32  4688.8  401.00  4718.8  400.92
  4729.5  399.98  4768.8  398.60  4788.8  398.56  4818.9  397.60  4838.9  396.48
  5150.7  395.37  5151.0  394.87  5154.5  394.87  5154.7  395.37  5169.4  396.38
  5209.5  397.72  5289.8  401.59  5390.2  408.94  5400.2  409.27  5440.4  412.63
  5495.5  413.60  5510.7  412.74  5570.9  411.67  5681.3  414.77  5741.4  415.80
#Mann=3,-1,0
  4150.8    0.05       0  5150.7    0.03       0  5154.7    0.05       0
Bank Sta=5150.7,5154.7
Exp/Cntr=0.3,0.1

Type RM Length L Ch R = 1,4749,119,119,119
BEGIN DESCRIPTION:
Lacy 127 3438
END DESCRIPTION:
XS GIS Cut Line= 4
      2722180.54      6869586.44      2721869.85      6869410.39
      2721153.27      6869363.46      2720711.02      6869443.20
#Sta/Elev= 30
  4249.8  410.75  4293.3  409.52  4498.1  409.53  4578.9  406.61  4650.9  402.15
  4711.0  399.61  4741.0  399.38  4811.2  395.70  4931.5  396.35  4941.5  395.62
  5019.6  395.44  5019.9  394.94  5023.6  395.44  5202.0  396.26  5272.2  395.66
  5325.0  399.57  5338.4  401.31  5383.2  403.08  5413.7  402.21  5455.7  403.16
  5464.5  404.43  5495.0  412.49  5504.2  413.26  5515.3  412.47  5545.8  412.49
  5616.5  415.54  5621.6  414.41  5657.6  415.21  5675.1  417.20  5774.4  417.86
#Mann=3,-1,0
  4249.8    0.05       0  5019.6    0.03       0  5023.6    0.05       0
Bank Sta=5019.6,5023.6
Exp/Cntr=0.3,0.1

Type RM Length L Ch R = 1,4630,55,55,55
BEGIN DESCRIPTION:
Lacy 127 3436
END DESCRIPTION:
XS GIS Cut Line= 2
      2722068.19      6869305.90      2720790.92      6869232.05
#Sta/Elev= 30
  4447.6  409.41  4519.9  409.34  4617.1  405.91  4622.1  409.27  4650.1  409.49
  4740.3  408.50  4788.9  406.84  4793.9  409.77  4830.4  409.76  4960.6  406.72
  4965.6  409.62  5000.7  409.57  5060.8  408.84  5137.4  406.18  5142.4  409.70
  5151.0  409.80  5241.1  409.37  5309.1  407.18  5314.2  409.54  5401.4  407.76
  5441.4  409.04  5471.5  405.80  5499.5  404.03  5499.8  403.53  5503.5  404.03
  5531.6  405.31  5551.6  407.68  5571.7  415.09  5591.7  414.98  5727.0  420.05
#Mann=3,-1,0
  4447.6    0.05       0  5499.5    0.04       0  5503.5    0.05       0
Bank Sta=5499.5,5503.5
Exp/Cntr=0.3,0.1

Type RM Length L Ch R = 1,4575,276,276,276
BEGIN DESCRIPTION:
Lacy 127 3437
END DESCRIPTION:
XS GIS Cut Line= 4
      2722091.97      6869233.72      2721634.29      6869220.48
      2721139.01      6869216.75      2720920.06      6869120.60
#Sta/Elev= 30
  4430.5  408.31  4516.5  408.67  4566.5  406.70  4726.6  398.05  4826.6  394.51
  4874.7  394.13  4874.9  393.63  4878.4  393.63  4878.7  394.13  5096.7  396.51
  5126.7  397.57  5196.7  398.38  5236.7  400.16  5276.7  400.62  5316.7  402.88
  5356.7  407.23  5382.7  408.79  5389.0  406.65  5406.9  406.21  5412.3  405.43
  5452.5  405.91  5482.4  407.82  5487.9  410.30  5505.8  412.11  5511.2  411.55
  5528.9  411.87  5557.9  413.64  5610.1  415.54  5616.3  416.51  5622.8  416.56
#Mann=3,-1,0
  4430.5    0.05       0  4874.7    0.04       0  4878.7    0.05       0
Bank Sta=4874.7,4878.7
Exp/Cntr=0.3,0.1

Type RM Length L Ch R = 1,4299,204,204,204
BEGIN DESCRIPTION:
Lacy 127 1265
END DESCRIPTION:
XS GIS Cut Line= 3
      2722023.36      6868971.04      2721576.51      6868945.78
      2721029.22      6868982.60
#Sta/Elev= 30
  4539.8  403.57  4577.2  402.64  4657.4  397.83  4707.4  396.44  4717.4  397.06
  4737.5  395.02  4765.9  394.61  4777.5  394.93  4867.7  390.72  4943.5  389.92
  4957.8  391.15  4977.9  390.46  4983.1  388.64  4991.8  388.64  5005.9  385.43
  5006.2  384.93  5009.9  385.43  5017.9  386.24  5058.0  386.74  5088.1  389.79
  5098.1  391.82  5128.2  391.12  5238.4  394.50  5268.5  397.17  5348.7  401.30
  5368.7  403.35  5440.7  407.27  5458.9  409.13  5509.1  411.90  5535.9  412.60
#Mann=5,-1,0
  4539.8    0.05       0  4765.9    0.12       0  4943.5    0.05       0
  5005.9    0.05       0  5009.9    0.05       0
Bank Sta=5005.9,5009.9
Exp/Cntr=0.3,0.1

Type RM Length L Ch R = 1,4095,337,337,337
BEGIN DESCRIPTION:
Lacy 127 1264
END DESCRIPTION:
XS GIS Cut Line= 3
      2722119.90      6868813.98      2721611.93      6868774.16
      2721091.70      6868755.22
#Sta/Elev= 30
  4421.3  399.37  4455.3  399.79  4465.3  397.85  4485.4  399.41  4515.5  399.00
  4575.7  396.83  4595.7  395.32  4625.8  394.79  4656.2  392.61  4686.0  391.45
  4783.2  389.65  4918.2  388.43  4966.8  390.01  4986.8  387.39  4994.8  384.89
  4995.1  384.39  4998.6  384.39  4998.8  384.89  5006.8  385.42  5017.2  389.52
  5026.8  390.81  5046.8  389.24  5076.9  388.87  5116.9  389.15  5186.9  391.13
  5206.9  390.96  5267.0  392.99  5426.1  401.04  5431.1  400.67  5451.4  401.69
#Mann=6,-1,0
  4421.3    0.05       0  4783.2    0.12       0  4918.2     0.1       0
  4994.8    0.07       0  4998.8     0.1       0  5017.2    0.05       0
Bank Sta=4994.8,4998.8
Exp/Cntr=0.3,0.1

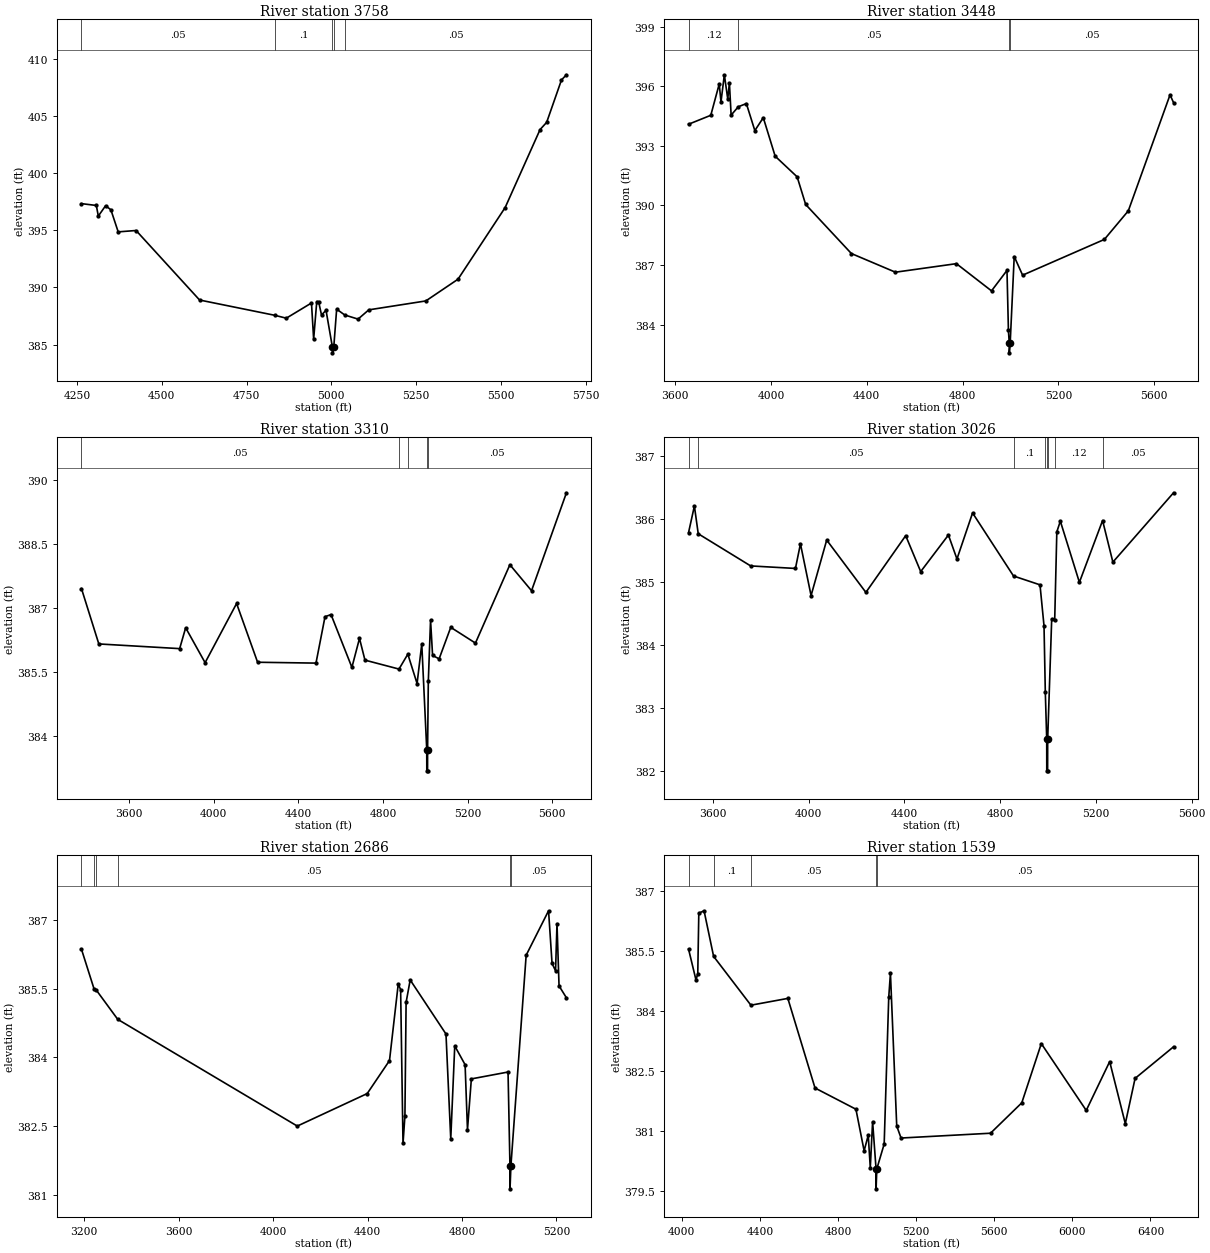
Type RM Length L Ch R = 1,3758,310,310,310
BEGIN DESCRIPTION:
Lacy 127 3459
END DESCRIPTION:
XS GIS Cut Line= 3
      2722205.26      6868810.35      2721573.25      6868437.16
      2720912.15      6868652.98
#Sta/Elev= 30
  4263.5  397.33  4307.3  397.17  4313.1  396.24  4334.6  397.15  4350.2  396.79
  4371.7  394.86  4424.4  394.98  4611.6  388.90  4833.7  387.56  4867.2  387.31
  4941.4  388.64  4947.8  385.48  4957.0  388.77  4962.8  388.71  4971.0  387.59
  4984.3  388.00  5003.1  384.78  5003.3  384.28  5007.1  384.78  5015.6  388.10
  5039.5  387.59  5078.7  387.23  5110.3  388.04  5278.5  388.82  5373.3  390.72
  5512.3  396.99  5615.2  403.81  5634.6  404.44  5678.3  408.15  5692.9  408.60
#Mann=5,-1,0
  4263.5    0.05       0  4833.7     0.1       0  5003.1    0.07       0
  5007.1     0.1       0  5039.5    0.05       0
Bank Sta=5003.1,5007.1
Exp/Cntr=0.3,0.1

Type RM Length L Ch R = 1,3448,138,138,138
BEGIN DESCRIPTION:
Lacy 127 3458
END DESCRIPTION:
XS GIS Cut Line= 3
      2722476.58      6868991.67      2721613.93      6868108.21
      2720880.77      6868402.78
#Sta/Elev= 30
  3656.0  394.09  3748.8  394.54  3784.1  396.12  3791.3  395.21  3805.4  396.58
  3819.6  395.36  3826.5  396.17  3833.7  394.55  3863.7  394.97  3897.3  395.13
  3932.7  393.77  3968.0  394.42  4017.6  392.48  4109.4  391.44  4144.9  390.05
  4335.8  387.58  4519.7  386.64  4774.3  387.07  4920.9  385.70  4985.5  386.73
  4991.5  383.71  4994.9  383.08  4995.2  382.58  4998.9  383.08  5015.7  387.43
  5050.7  386.49  5392.1  388.29  5492.1  389.73  5666.3  395.57  5680.9  395.18
#Mann=4,-1,0
  3656.0    0.12       0  3863.7    0.05       0  4994.9    0.04       0
  4998.9    0.05       0
Bank Sta=4994.9,4998.9
Exp/Cntr=0.3,0.1

Type RM Length L Ch R = 1,3310,284,284,284
BEGIN DESCRIPTION:
Lacy 127 3457
END DESCRIPTION:
XS GIS Cut Line= 3
      2722767.28      6868814.93      2721763.63      6867919.46
      2720870.46      6868235.83
#Sta/Elev= 30
  3374.3  387.46  3456.3  386.16  3838.4  386.05  3866.8  386.54  3958.7  385.72
  4107.6  387.11  4206.9  385.73  4482.9  385.71  4525.6  386.80  4554.0  386.85
  4652.7  385.61  4688.6  386.29  4714.4  385.78  4875.3  385.57  4917.1  385.92
  4960.8  385.23  4983.0  386.16  5006.5  383.68  5006.8  383.18  5010.3  383.18
  5010.5  383.68  5013.9  385.28  5024.5  386.72  5034.1  385.89  5065.0  385.81
  5120.0  386.55  5236.7  386.18  5399.5  388.02  5501.9  387.41  5666.9  389.71
#Mann=5,-1,0
  3374.3    0.05       0  4875.3     0.1       0  4917.1    0.05       0
  5006.5    0.04       0  5010.5    0.05       0
Bank Sta=5006.5,5010.5
Exp/Cntr=0.3,0.1

Type RM Length L Ch R = 1,3026,340,340,340
BEGIN DESCRIPTION:
Lacy 127 3456
END DESCRIPTION:
XS GIS Cut Line= 3
      2722777.48      6868552.34      2721622.56      6867736.95
      2721050.18      6867954.53
#Sta/Elev= 30
  3498.2  385.79  3522.5  386.21  3538.6  385.77  3757.6  385.26  3944.7  385.22
  3965.6  385.61  4010.0  384.79  4075.3  385.67  4239.0  384.84  4405.3  385.74
  4468.0  385.17  4583.8  385.75  4619.5  385.37  4684.7  386.10  4855.8  385.10
  4966.4  384.96  4983.2  384.31  4988.6  383.26  4994.5  382.51  4994.7  382.01
  4998.2  382.01  4998.5  382.51  5015.3  384.42  5027.9  384.41  5036.7  385.80
  5051.4  385.97  5131.0  385.00  5227.9  385.98  5270.9  385.32  5524.3  386.42
#Mann=8,-1,0
  3498.2    0.12       0  3538.6    0.05       0  4855.8     0.1       0
  4988.6    0.05       0  4994.5    0.04       0  4998.5    0.05       0
  5027.9    0.12       0  5227.9    0.05       0
Bank Sta=4994.5,4998.5
Exp/Cntr=0.3,0.1

Type RM Length L Ch R = 1,2686,1147,1147,1147
BEGIN DESCRIPTION:
Lacy 127 3455
END DESCRIPTION:
XS GIS Cut Line= 4
      2722753.74      6868420.47      2722208.91      6867612.91
      2721309.21      6867482.88      2721170.71      6867580.76
#Sta/Elev= 30
  3189.3  386.36  3242.8  385.49  3251.8  385.47  3342.8  384.83  4102.8  382.50
  4398.8  383.21  4493.1  383.93  4530.1  385.60  4540.2  385.48  4550.3  382.12
  4558.4  382.72  4563.4  385.20  4580.7  385.69  4732.2  384.51  4752.4  382.22
  4769.3  384.25  4813.1  383.84  4823.2  382.42  4839.6  383.53  4994.9  383.68
  5003.0  381.63  5003.3  381.13  5007.0  381.63  5071.6  386.23  5166.4  387.20
  5181.2  386.05  5196.0  385.89  5202.1  386.92  5210.8  385.56  5242.1  385.30
#Mann=6,-1,0
  3189.3    0.12       0  3242.8    0.05       0  3251.8     0.1       0
  3342.8    0.05       0  5003.0    0.04       0  5007.0    0.05       0
Bank Sta=5003,5007
Exp/Cntr=0.3,0.1

Type RM Length L Ch R = 1,1539,651,651,651
BEGIN DESCRIPTION:
Lacy 127 3454
END DESCRIPTION:
XS GIS Cut Line= 3
      2722776.52      6868387.19      2722411.26      6867243.56
      2721129.12      6867260.43
#Sta/Elev= 30
  4035.2  385.55  4073.2  384.78  4082.3  384.94  4087.6  386.45  4114.5  386.51
  4163.4  385.37  4354.4  384.15  4543.4  384.32  4682.6  382.08  4892.0  381.55
  4934.0  380.51  4955.0  380.90  4965.5  380.09  4977.4  381.24  4995.0  380.06
  4995.2  379.56  4999.0  380.06  5036.6  380.68  5060.0  384.35  5068.7  384.95
  5100.9  381.13  5123.0  380.83  5581.0  380.95  5741.1  381.71  5841.1  383.19
  6071.1  381.52  6191.1  382.74  6271.1  381.19  6321.1  382.32  6518.0  383.11
#Mann=5,-1,0
  4035.2    0.12       0  4163.4     0.1       0  4354.4    0.05       0
  4995.0    0.05       0  4999.0    0.05       0
Bank Sta=4995,4999
Exp/Cntr=0.3,0.1

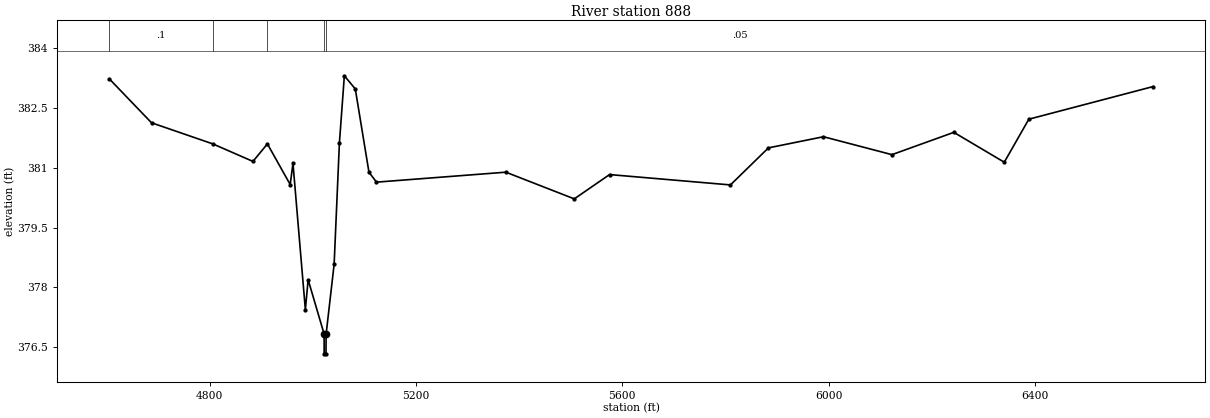
Type RM Length L Ch R = 1,888,0,0,0
BEGIN DESCRIPTION:
Lacy 127 3453
END DESCRIPTION:
XS GIS Cut Line= 3
      2723041.56      6867029.65      2722676.09      6866881.10
      2721089.48      6867251.61
#Sta/Elev= 30
  4605.5  383.23  4687.1  382.13  4806.0  381.60  4883.8  381.16  4911.8  381.60
  4956.0  380.58  4961.4  381.11  4985.4  377.44  4990.8  378.19  5021.7  376.83
  5021.9  376.33  5025.4  376.33  5025.7  376.83  5041.2  378.58  5051.4  381.62
  5061.0  383.31  5082.2  382.98  5108.7  380.89  5123.3  380.64  5374.1  380.89
  5506.8  380.22  5575.2  380.83  5809.6  380.57  5883.2  381.50  5990.0  381.78
  6122.7  381.33  6242.7  381.89  6340.5  381.14  6388.1  382.22  6629.3  383.04
#Mann=5,-1,0
  4605.5     0.1       0  4806.0    0.12       0  4911.8    0.05       0
  5021.7    0.05       0  5025.7    0.05       0
Bank Sta=5021.7,5025.7
Exp/Cntr=0.3,0.1

Chan Stop Cuts=-1