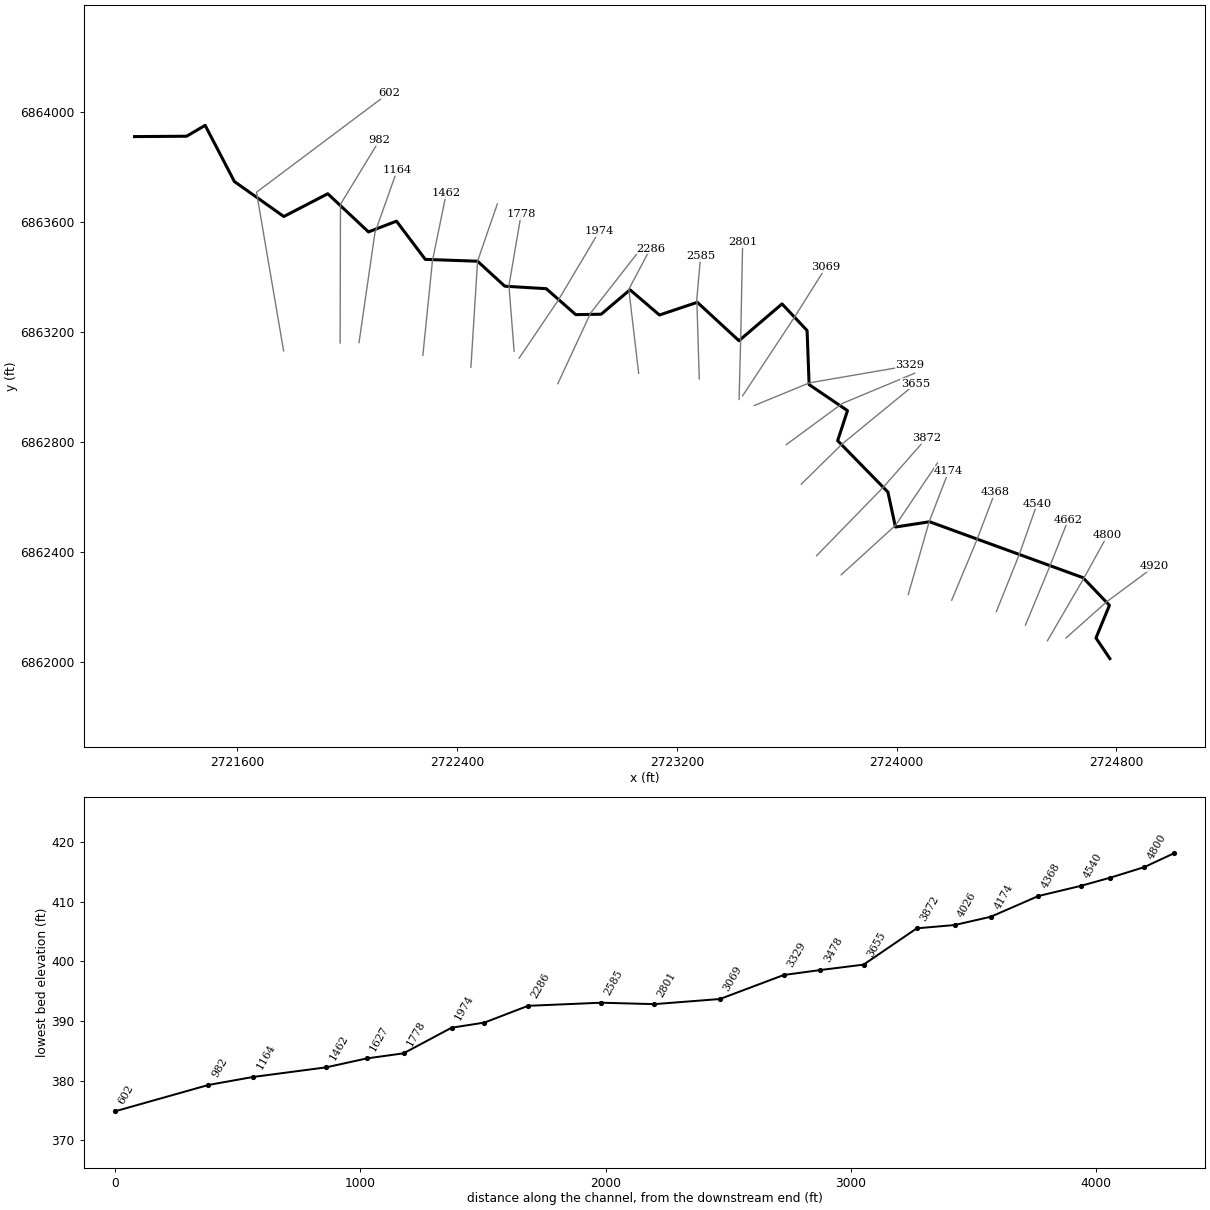
--- Lacy 128.prj (project) ---

Proj Title=Lacy 128 Base Level Engineering
Current Plan=p01
Default Exp/Contr=0.3,0.1
English Units
Geom File=g01
Flow File=f01
Plan File=p01
Y Axis Title=Elevation
X Axis Title(PF)=Main Channel Distance
X Axis Title(XS)=Station
BEGIN DESCRIPTION:
Lacy 128
END DESCRIPTION:
DSS Export Rating Curves= 0
DSS Export Rating Curve Sorted= 0
DSS Export Volume Flow Curves= 0
DXF OffsetX= 0
DXF OffsetY= 0
DXF ScaleX= 1
DXF ScaleY= 10

--- Lacy 128.p01 (plan) ---

Plan Title=Multiple Run
Short Identifier=Multiple
Geom File=g01
Flow File=f01
Subcritical Flow
K Sum by GR= 0
Std Step Tol= 0.01
Critical Tol= 0.01
Num of Std Step Trials= 20
Max Error Tol= 0.3
Flow Tol Ratio= 0.001
Split Flow NTrial= 30
Split Flow Tol= 0.02
Split Flow Ratio= 0.02
Log Output Level= 0
Friction Slope Method= 1
Unsteady Friction Slope Method= 2
Unsteady Bridges Friction Slope Method= 1
Parabolic Critical Depth
Global Vel Dist=  1 , 1 , 1
Global Log Level= 0
CheckData=True
Encroach Param= -1, 0, 0, 0
BEGIN DESCRIPTION:
Multiple Run
END DESCRIPTION:

--- Lacy 128.f01 (steady flow) ---

Flow Title=Multiple
Number of Profiles=7
Profile Names=10-year,25-year,50-year,1pct_min,100-year,1pct_plu,500-year
River Rch & RM= Lacy 128,Reach-1,4920
     300     385     450     262     523    1043     703
Boundary for River Rch & Prof#=Lacy 128,Reach-1,1
Up Type=0
Dn Type=3
Dn Slope=0.005
Boundary for River Rch & Prof#=Lacy 128,Reach-1,2
Up Type=0
Dn Type=3
Dn Slope=0.005
Boundary for River Rch & Prof#=Lacy 128,Reach-1,3
Up Type=0
Dn Type=3
Dn Slope=0.005
Boundary for River Rch & Prof#=Lacy 128,Reach-1,4
Up Type=0
Dn Type=3
Dn Slope=0.005
Boundary for River Rch & Prof#=Lacy 128,Reach-1,5
Up Type=0
Dn Type=3
Dn Slope=0.005
Boundary for River Rch & Prof#=Lacy 128,Reach-1,6
Up Type=0
Dn Type=3
Dn Slope=0.005
Boundary for River Rch & Prof#=Lacy 128,Reach-1,7
Up Type=0
Dn Type=3
Dn Slope=0.005

--- Lacy 128.g01 (geometry) ---

Geom Title=Existing Conditions
Program Version=4.10

River Reach=Lacy 128        ,Reach-1
Reach XY= 30
        2724776.        6862011.       2724725.4      6862086.06
      2724774.39      6862204.98      2724678.44      6862305.48
      2724119.86      6862509.14      2723995.61      6862489.91
      2723968.14      6862617.17      2723785.15      6862804.27
      2723820.99      6862913.54      2723681.36       6863008.3
      2723673.94      6863205.17      2723582.69      6863302.05
        2723426.      6863168.07      2723274.37      6863307.87
      2723136.62      6863261.62      2723029.33      6863353.39
       2722924.5      6863264.48       2722831.9      6863262.97
      2722724.53      6863357.44      2722573.56      6863366.48
      2722474.53      6863457.45       2722284.3      6863464.07
      2722179.42      6863603.18      2722077.45       6863564.1
      2721929.34        6863703.      2721769.28      6863620.13
      2721589.47      6863747.43      2721483.02      6863951.99
      2721415.58      6863912.39        2721226.        6863911.

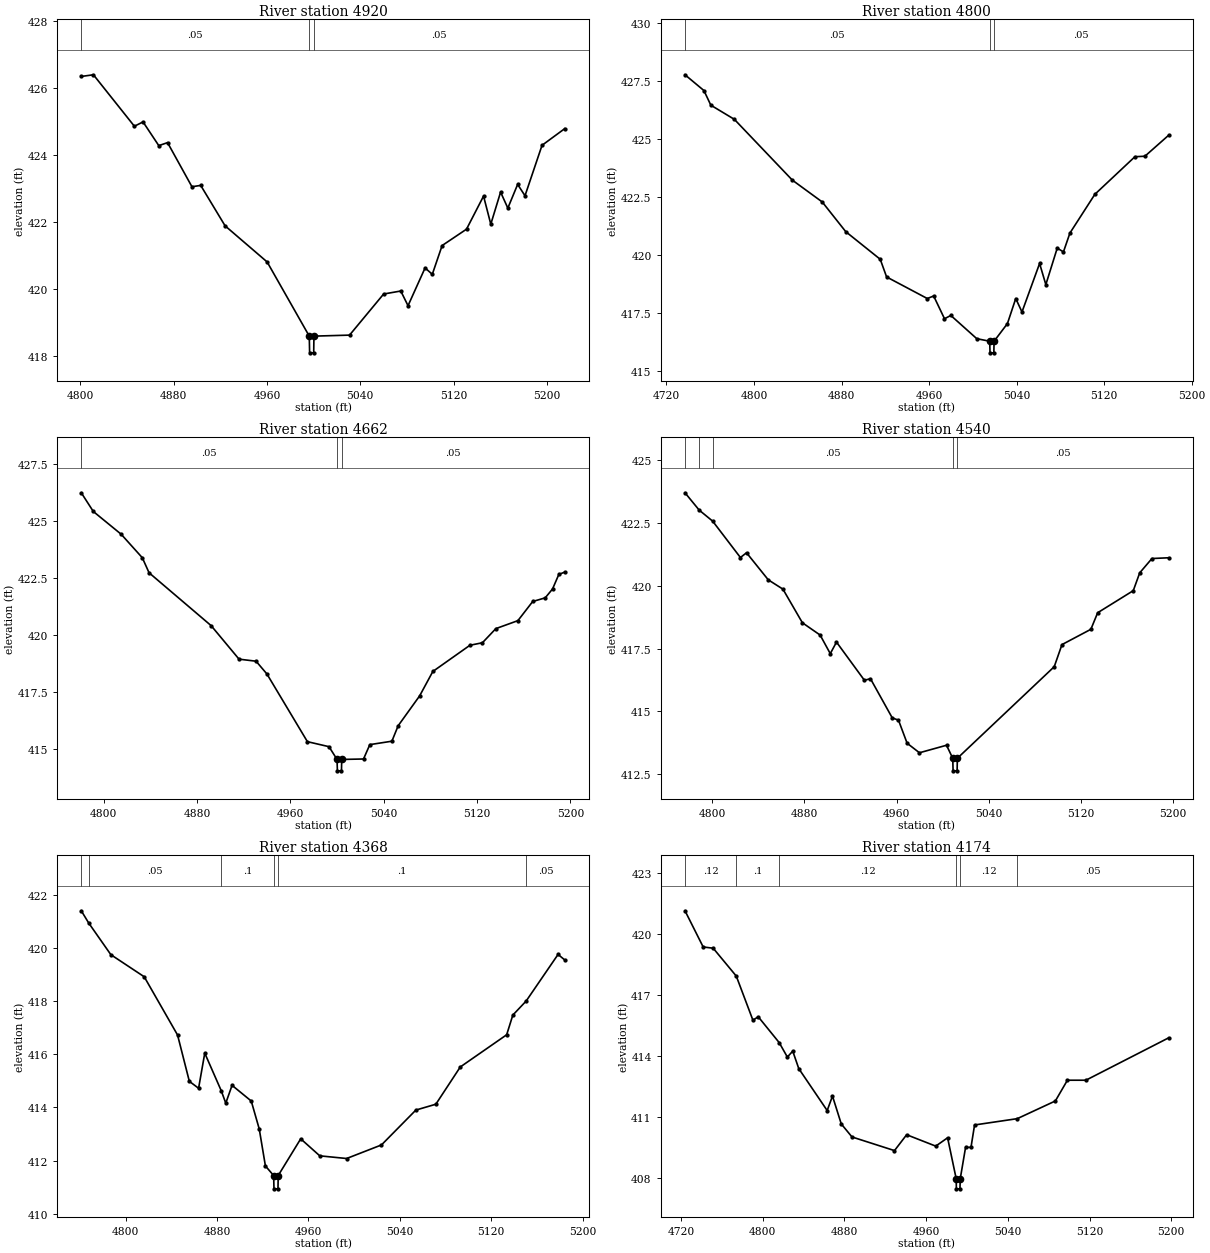
Type RM Length L Ch R = 1 ,4920    ,120,120,120
BEGIN DESCRIPTION:
Lacy 128 1245
END DESCRIPTION:
XS GIS Cut Line= 3
      2724616.47      6862086.26      2724763.91      6862217.44
      2724938.15      6862346.54
#Sta/Elev= 30
    4801  426.35  4811.4   426.4  4846.5  424.86  4853.9  424.99  4867.4  424.28
  4874.9  424.37  4895.8  423.05  4903.3  423.09  4924.2  421.88  4960.2   420.8
  4996.3  418.58  4996.6  418.08  5000.1  418.08  5000.3  418.58  5030.8  418.61
    5060  419.84  5074.7  419.93  5080.9  419.49  5095.5  420.62  5101.7  420.43
  5110.1  421.29    5131  421.78  5145.6  422.77  5151.8  421.93  5160.2  422.89
  5166.4  422.41  5174.8  423.12  5181.1  422.78  5195.7  424.29  5215.2  424.79
#Mann= 3 ,-1 , 0
    4801     .05       0  4996.3     .04       0  5000.3     .05       0
Bank Sta=4996.3,5000.3
XS Rating Curve= 0 ,0
Exp/Cntr=0.3,0.1

Type RM Length L Ch R = 1 ,4800    ,138,138,138
BEGIN DESCRIPTION:
Lacy 128 1246
END DESCRIPTION:
XS GIS Cut Line= 3
      2724548.83      6862076.05      2724682.92      6862306.47
      2724767.41      6862459.96
#Sta/Elev= 30
    4737  427.76  4754.3  427.08  4760.6  426.45  4782.1  425.84  4835.1  423.22
  4862.4  422.28  4883.9     421  4915.4  419.81  4921.2  419.05  4958.4  418.12
  4964.2  418.23  4974.1  417.25  4979.9  417.39  5003.6  416.39  5015.4  416.28
  5015.7  415.78  5019.2  415.78  5019.4  416.28  5031.6  417.04  5039.2  418.12
  5044.9  417.54    5061  419.63  5066.7  418.72  5077.1  420.29  5082.8  420.13
  5088.7  420.94  5111.5  422.61  5148.1  424.23  5157.2  424.25  5178.8  425.15
#Mann= 3 ,-1 , 0
    4737     .05       0  5015.4     .04       0  5019.4     .05       0
Bank Sta=5015.4,5019.4
XS Rating Curve= 0 ,0
Exp/Cntr=0.3,0.1

Type RM Length L Ch R = 1 ,4662    ,122,122,122
BEGIN DESCRIPTION:
Lacy 128 1244
END DESCRIPTION:
XS GIS Cut Line= 3
      2724468.61      6862132.65      2724553.73      6862338.09
      2724624.52      6862516.59
#Sta/Elev= 30
  4780.8  426.22  4791.1   425.4    4815   424.4  4833.1  423.37  4838.9  422.71
  4892.1  420.39    4916  418.92  4930.6  418.83  4939.9  418.27  4974.6   415.3
  4993.1  415.08    5000  414.52  5000.3  414.02  5003.8  414.02    5004  414.52
  5022.7  414.54  5028.1  415.17    5047  415.32  5052.4     416  5070.8  417.31
  5082.1  418.38  5113.9  419.53  5124.6  419.64  5136.1  420.26    5155  420.61
  5167.7  421.45  5178.4  421.61  5184.7     422  5190.1  422.64  5195.2  422.74
#Mann= 3 ,-1 , 0
  4780.8     .05       0    5000     .04       0    5004     .05       0
Bank Sta=5000,5004
XS Rating Curve= 0 ,0
Exp/Cntr=0.3,0.1

Type RM Length L Ch R = 1 ,4540    ,172,172,172
BEGIN DESCRIPTION:
Lacy 128 1243
END DESCRIPTION:
XS GIS Cut Line= 3
      2724362.84      6862182.09      2724446.09       6862389.7
      2724511.26      6862574.57
#Sta/Elev= 30
  4776.4  423.71  4788.7  423.02  4800.4  422.58  4824.5  421.13  4829.8  421.32
  4848.7  420.24  4861.4  419.87  4878.3  418.53  4893.7  418.04  4902.5   417.3
  4907.9  417.76  4932.1  416.24  4937.4   416.3  4956.3  414.74  4961.7  414.65
  4969.2  413.73  4979.9  413.35  5003.4  413.65  5008.8  413.13  5009.1  412.63
  5012.6  412.63  5012.8  413.13  5096.9  416.78  5103.6  417.66  5128.7  418.27
  5134.6  418.93  5165.5  419.81  5171.1  420.52  5181.7  421.09  5196.1  421.12
#Mann= 5 ,-1 , 0
  4776.4     .05       0  4788.7      .1       0  4800.4     .05       0
  5008.8     .04       0  5012.8     .05       0
Bank Sta=5008.8,5012.8
XS Rating Curve= 0 ,0
Exp/Cntr=0.3,0.1

Type RM Length L Ch R = 1 ,4368    ,194,194,194
BEGIN DESCRIPTION:
Lacy 128 1242
END DESCRIPTION:
XS GIS Cut Line= 3
      2724200.37      6862223.73      2724290.76      6862440.19
      2724357.98      6862616.54
#Sta/Elev= 30
  4761.2  421.39  4767.7  420.93  4787.1  419.74  4816.3  418.91  4845.5  416.72
  4855.8  414.98  4863.9  414.72  4869.3  416.04  4883.7  414.63  4887.7  414.16
  4893.2  414.83    4910  414.24    4917  413.19  4922.4   411.8  4929.6  411.44
  4929.9  410.94  4933.4  410.94  4933.6  411.44  4953.3  412.82    4970  412.18
  4993.5  412.08    5024  412.59  5054.1   413.9  5071.6  414.12    5093  415.52
  5133.6  416.73    5139  417.47  5150.7     418  5178.6  419.75  5184.5  419.54
#Mann= 6 ,-1 , 0
  4761.2      .1       0  4767.7     .05       0  4883.7      .1       0
  4929.6     .07       0  4933.6      .1       0  5150.7     .05       0
Bank Sta=4929.6,4933.6
XS Rating Curve= 0 ,0
Exp/Cntr=0.3,0.1

Type RM Length L Ch R = 1 ,4174    ,148,148,148
BEGIN DESCRIPTION:
Lacy 128 1241
END DESCRIPTION:
XS GIS Cut Line= 3
       2724042.1       6862243.9      2724118.47      6862509.77
      2724189.45       6862693.3
#Sta/Elev= 30
  4723.9  421.14  4741.7  419.36  4751.5   419.3  4774.1  417.93  4790.4  415.76
  4795.6  415.93  4816.1  414.66  4824.1  413.95  4829.4  414.24  4835.3  413.38
  4863.1  411.32  4868.3  412.03  4876.9  410.66  4887.4  410.02    4929  409.35
  4940.9  410.13  4969.4  409.57    4981  409.98  4989.4  407.97  4989.6  407.47
  4993.1  407.47  4993.4  407.97  4998.6  409.51  5003.9  409.51  5007.4  410.61
  5049.2  410.92  5086.5  411.79  5098.3  412.81  5116.4  412.81  5197.3  414.89
#Mann= 6 ,-1 , 0
  4723.9     .12       0  4774.1      .1       0  4816.1     .12       0
  4989.4     .07       0  4993.4     .12       0  5049.2     .05       0
Bank Sta=4989.4,4993.4
XS Rating Curve= 0 ,0
Exp/Cntr=0.3,0.1

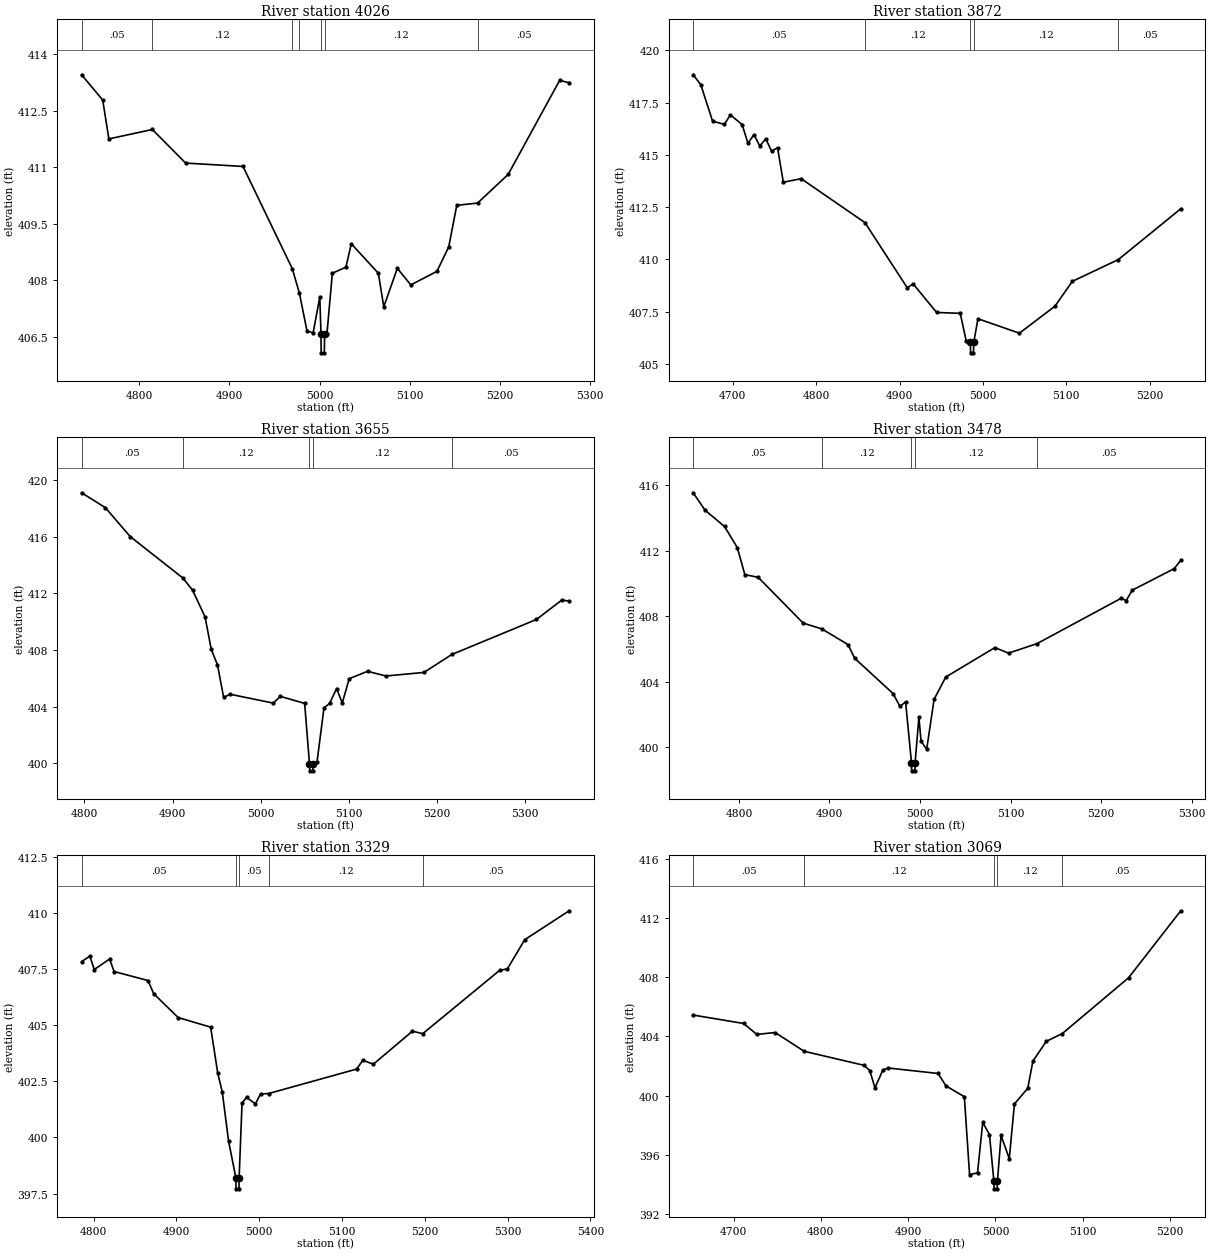
Type RM Length L Ch R = 1 ,4026    ,154,154,154
BEGIN DESCRIPTION:
Lacy 128 1240
END DESCRIPTION:
XS GIS Cut Line= 3
      2723798.16      6862316.12      2723995.84      6862496.09
      2724148.36      6862722.59
#Sta/Elev= 30
  4736.3  413.45  4759.7  412.78  4766.5  411.75  4814.7     412  4851.6  411.11
  4915.2  411.02  4969.8  408.31  4977.7  407.66  4986.1  406.66  4992.9  406.61
  5000.3  407.56  5001.6  406.58  5001.8  406.08  5005.3  406.08  5005.6  406.58
  5008.2  406.58  5014.2  408.19  5029.2  408.35  5035.2  408.97  5065.2  408.19
  5071.2   407.3  5086.2  408.32  5101.2  407.88  5130.1  408.24  5143.2  408.89
  5152.1  409.99  5175.2  410.05  5209.1  410.81  5266.1   413.3  5276.7  413.24
#Mann= 7 ,-1 , 0
  4736.3     .05       0  4814.7     .12       0  4969.8     .05       0
  4977.7     .12       0  5001.6     .07       0  5005.6     .12       0
  5175.2     .05       0
Bank Sta=5001.6,5005.6
XS Rating Curve= 0 ,0
Exp/Cntr=0.3,0.1

Type RM Length L Ch R = 1 ,3872    ,217,217,217
BEGIN DESCRIPTION:
Lacy 128 1239
END DESCRIPTION:
XS GIS Cut Line= 3
      2723708.49      6862385.49      2723952.21      6862635.78
      2724107.73      6862812.57
#Sta/Elev= 30
  4652.5  418.83  4661.6  418.36  4675.8  416.61  4689.9  416.46  4697.1  416.91
  4711.2  416.45  4718.2  415.55  4725.4  415.97  4732.4  415.42  4739.5  415.77
  4746.5  415.18  4753.7  415.34  4760.6  413.69    4782  413.86  4858.5  411.76
  4909.3  408.64  4916.3  408.83  4944.5  407.46  4972.8  407.42    4980  406.09
    4985  406.03  4985.2  405.53  4988.7  405.53    4989  406.03  4994.1  407.16
  5043.8  406.47  5086.4  407.76  5107.3  408.95  5162.4  409.99  5237.3  412.42
#Mann= 5 ,-1 , 0
  4652.5     .05       0  4858.5     .12       0    4985     .07       0
    4989     .12       0  5162.4     .05       0
Bank Sta=4985,4989
XS Rating Curve= 0 ,0
Exp/Cntr=0.3,0.1

Type RM Length L Ch R = 1 ,3655    ,177,177,177
BEGIN DESCRIPTION:
Lacy 128 1238
END DESCRIPTION:
XS GIS Cut Line= 3
      2723652.83      6862646.09      2723801.75      6862792.45
      2724068.22      6863010.79
#Sta/Elev= 30
  4796.8  419.12  4823.7  418.07    4852  416.02  4911.9  413.08  4922.7  412.23
  4936.9  410.34  4943.9  408.05    4951  406.94    4958  404.64  4965.2  404.87
  5014.4  404.24  5022.3  404.72  5049.9  404.22  5055.4  399.95  5055.7  399.45
  5059.2  399.45  5059.4  399.95  5063.9  400.05  5071.8  403.89  5078.3  404.23
  5086.1  405.27  5092.6  404.25  5100.5  405.97  5121.3  406.49  5142.1  406.16
  5185.2  406.41  5216.9  407.68    5313  410.16  5341.7  411.53  5350.1  411.46
#Mann= 5 ,-1 , 0
  4796.8     .05       0  4911.9     .12       0  5055.4     .07       0
  5059.4     .12       0  5216.9     .05       0
Bank Sta=5055.4,5059.4
XS Rating Curve= 0 ,0
Exp/Cntr=0.3,0.1

Type RM Length L Ch R = 1 ,3478    ,149,149,149
BEGIN DESCRIPTION:
Lacy 128 1237
END DESCRIPTION:
XS GIS Cut Line= 3
      2723598.13      6862789.88      2723801.99      6862939.66
      2724065.47       6863049.7
#Sta/Elev= 30
  4749.5  415.55  4762.7  414.48  4784.1  413.49  4798.2   412.2  4806.6  410.54
  4821.3  410.38  4870.9  407.58  4891.7  407.22  4920.6  406.26  4927.8  405.43
  4970.2  403.27  4977.9  402.48  4984.1  402.76  4990.6  399.04  4990.8  398.54
  4994.3  398.54  4994.6  399.04  4998.8  401.82  5001.2  400.35  5007.4  399.86
  5015.6  402.92  5028.5  404.28  5082.7  406.08  5097.8  405.74  5129.2  406.32
  5222.3   409.1  5227.7  408.95  5234.4  409.59  5280.8  410.91    5288  411.42
#Mann= 5 ,-1 , 0
  4749.5     .05       0  4891.7     .12       0  4990.6     .07       0
  4994.6     .12       0  5129.2     .05       0
Bank Sta=4990.6,4994.6
XS Rating Curve= 0 ,0
Exp/Cntr=0.3,0.1

Type RM Length L Ch R = 1 ,3329    ,260,260,260
BEGIN DESCRIPTION:
Lacy 128 1236
END DESCRIPTION:
XS GIS Cut Line= 3
      2723481.96       6862932.2      2723682.61      6863014.81
      2724048.93      6863077.91
#Sta/Elev= 30
  4785.6  407.84  4795.5  408.09  4800.9  407.49  4819.4  407.96  4824.8   407.4
  4865.7     407  4872.7  406.41  4902.1  405.35  4941.4  404.92    4950  402.86
  4955.4  402.04    4963  399.85  4971.8  398.21  4972.1  397.71  4975.6  397.71
  4975.8  398.21  4979.3  401.53  4984.7  401.79  4995.4   401.5  5001.7  401.94
  5011.4  401.96  5117.6  403.05  5125.1  403.44  5137.9  403.27    5185  404.74
  5197.5  404.63  5290.2  407.45  5299.7  407.52  5320.6  408.82  5374.3  410.11
#Mann= 5 ,-1 , 0
  4785.6     .05       0  4971.8     .05       0  4975.8     .05       0
  5011.4     .12       0  5197.5     .05       0
Bank Sta=4971.8,4975.8
XS Rating Curve= 0 ,0
Exp/Cntr=0.3,0.1

Type RM Length L Ch R = 1 ,3069    ,268,268,268
BEGIN DESCRIPTION:
Lacy 128 1235
END DESCRIPTION:
XS GIS Cut Line= 3
      2723439.28      6862967.57       2723630.7      6863257.78
      2723742.91      6863436.52
#Sta/Elev= 30
  4653.7  405.44  4711.5  404.87  4726.6  404.13  4747.6  404.26  4780.9  402.99
  4849.5  402.04    4856  401.69    4862  400.52  4871.1  401.73  4877.1  401.86
  4934.3  401.49  4943.4  400.65  4964.4  399.92  4970.4  394.65  4979.5  394.77
  4985.5  398.18  4993.2  397.36  4998.3  394.19  4998.5  393.69    5002  393.69
  5002.3  394.19  5006.5   397.3  5015.9  395.73  5021.8  399.43  5037.1  400.49
    5043  402.33  5058.3  403.66  5076.7  404.19  5152.6  407.96  5212.4  412.49
#Mann= 5 ,-1 , 0
  4653.7     .05       0  4780.9     .12       0  4998.3     .07       0
  5002.3     .12       0  5076.7     .05       0
Bank Sta=4998.3,5002.3
XS Rating Curve= 0 ,0
Exp/Cntr=0.3,0.1

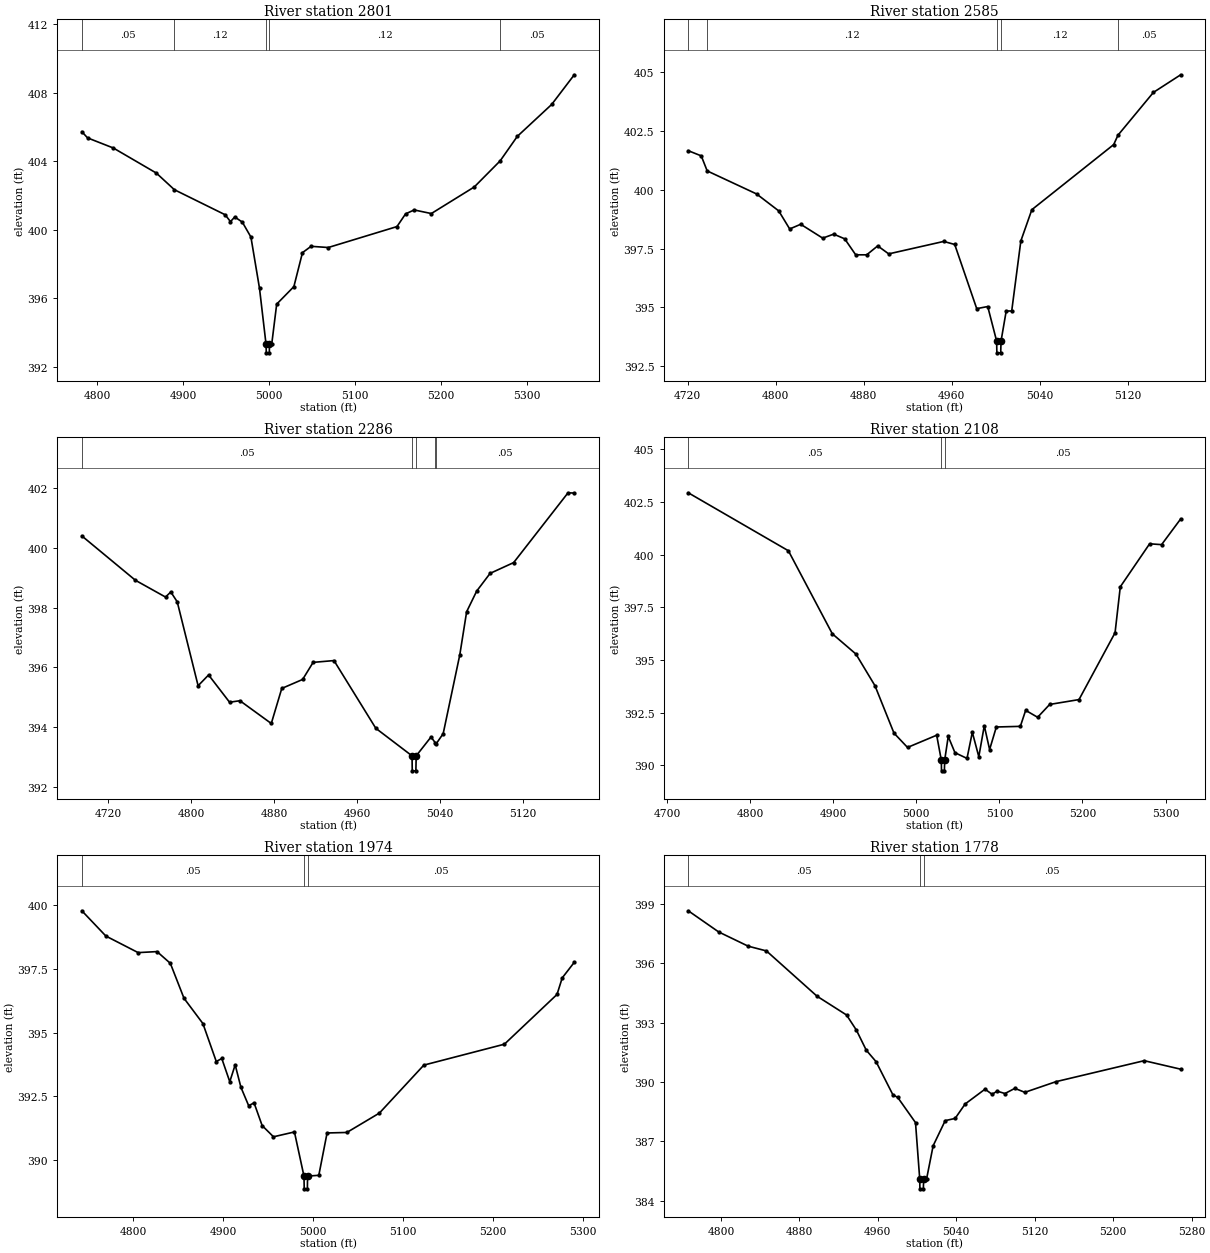
Type RM Length L Ch R = 1 ,2801    ,216,216,216
BEGIN DESCRIPTION:
Lacy 128 1234
END DESCRIPTION:
XS GIS Cut Line= 3
      2723426.38      6862954.28      2723432.24      6863175.22
      2723439.39      6863527.33
#Sta/Elev= 30
  4782.4  405.72  4789.1  405.36  4819.1  404.77  4869.1  403.31  4890.1  402.34
  4949.2  400.88  4955.4  400.48  4960.4  400.75  4969.2  400.45  4979.2  399.58
  4989.2  396.59  4996.8  393.33  4997.1  392.83  5000.6  392.83  5000.8  393.33
  5003.4  393.33  5009.2  395.67  5029.2  396.69  5039.2  398.67  5049.2  399.04
  5069.2  398.97  5149.2  400.19  5159.2  400.93  5169.2  401.16  5189.2  400.95
  5239.2   402.5  5269.3  404.02  5289.3  405.45  5329.3  407.31  5355.6  409.04
#Mann= 5 ,-1 , 0
  4782.4     .05       0  4890.1     .12       0  4996.8     .07       0
  5000.8     .12       0  5269.3     .05       0
Bank Sta=4996.8,5000.8
XS Rating Curve= 0 ,0
Exp/Cntr=0.3,0.1

Type RM Length L Ch R = 1 ,2585    ,299,299,299
BEGIN DESCRIPTION:
Lacy 128 1233
END DESCRIPTION:
XS GIS Cut Line= 3
      2723281.51      6863028.88      2723272.53      6863319.56
      2723286.51      6863475.72
#Sta/Elev= 30
  4720.6  401.67  4732.4  401.45  4737.8  400.81  4782.7  399.83  4802.8  399.11
  4812.8  398.34  4822.8  398.54  4842.8  397.95  4852.8  398.12  4862.8  397.92
  4872.8  397.24  4882.8  397.24  4892.8  397.62  4902.8  397.28  4952.8  397.81
  4962.8  397.68  4982.8  394.95  4992.8  395.04  5000.9  393.57  5001.1  393.07
  5004.6  393.07  5004.9  393.57  5009.6  394.85  5014.6  394.85  5022.9  397.83
  5032.9  399.16  5107.3  401.93  5111.2  402.33  5143.4  404.15  5168.2   404.9
#Mann= 5 ,-1 , 0
  4720.6     .05       0  4737.8     .12       0  5000.9     .07       0
  5004.9     .12       0  5111.2     .05       0
Bank Sta=5000.9,5004.9
XS Rating Curve= 0 ,0
Exp/Cntr=0.3,0.1

Type RM Length L Ch R = 1 ,2286    ,178,178,178
BEGIN DESCRIPTION:
Lacy 128 1232
END DESCRIPTION:
XS GIS Cut Line= 3
      2723060.81      6863049.71      2723025.07      6863355.36
       2723103.1      6863502.63
#Sta/Elev= 30
  4694.8  400.39  4746.4  398.91  4775.4  398.35  4780.5  398.52  4786.7  398.19
  4806.8  395.39  4816.9  395.75  4837.1  394.84  4847.1  394.89  4877.3  394.13
  4887.4   395.3  4907.5   395.6  4917.6  396.17  4937.7  396.23    4978  393.97
  5012.9  393.05  5013.1  392.55  5016.6  392.55  5016.9  393.05  5031.2  393.68
  5035.2  393.49  5036.1  393.45  5042.9  393.79  5058.9  396.42  5065.5  397.86
  5075.2  398.55  5088.1  399.14  5110.8   399.5  5163.2  401.83  5169.2  401.82
#Mann= 5 ,-1 , 0
  4694.8     .05       0  5012.9     .05       0  5016.9     .05       0
  5035.2     .12       0  5036.1     .05       0
Bank Sta=5012.9,5016.9
XS Rating Curve= 0 ,0
Exp/Cntr=0.3,0.1

Type RM Length L Ch R = 1 ,2108    ,134,134,134
BEGIN DESCRIPTION:
Lacy 128 1231
END DESCRIPTION:
XS GIS Cut Line= 3
      2722766.64      6863011.67      2722886.15        6863269.
      2723076.45      6863512.41
#Sta/Elev= 30
  4725.5  402.93    4846  400.18  4898.9  396.24  4927.3  395.28  4950.2  393.78
  4973.1  391.53  4989.4  390.85  5024.5  391.43  5030.1  390.24  5030.3  389.74
  5033.8  389.74  5034.1  390.24  5038.4  391.37  5046.5   390.6    5061  390.33
  5067.4  391.57  5075.2  390.41  5081.8  391.88  5088.2  390.75  5096.3  391.82
  5125.2  391.85  5131.6  392.61    5146  392.28  5160.5  392.89  5195.8  393.12
  5239.2  396.29  5245.5  398.47  5280.8  400.51  5295.2  400.47  5318.2  401.69
#Mann= 3 ,-1 , 0
  4725.5     .05       0  5030.1     .04       0  5034.1     .05       0
Bank Sta=5030.1,5034.1
XS Rating Curve= 0 ,0
Exp/Cntr=0.3,0.1

Type RM Length L Ch R = 1 ,1974    ,196,196,196
BEGIN DESCRIPTION:
Lacy 128 1230
END DESCRIPTION:
XS GIS Cut Line= 3
      2722625.71      6863104.44      2722768.36      6863315.61
      2722918.05      6863567.21
#Sta/Elev= 30
  4742.7  399.78  4769.4  398.79  4805.3  398.14  4826.3  398.18  4841.1  397.72
  4856.3  396.35  4877.3  395.36  4892.2  393.87  4898.3  393.99  4907.2  393.08
  4913.2  393.74  4919.6  392.86  4928.2  392.14  4934.2  392.25  4943.2  391.36
  4955.8  390.92  4979.1  391.11  4989.7  389.38    4990  388.88  4993.5  388.88
  4993.7  389.38  5006.2  389.41  5015.4  391.07  5037.4  391.09  5073.6  391.85
    5123  393.73  5212.6  394.55  5271.1   396.5  5276.9  397.15  5290.3  397.76
#Mann= 3 ,-1 , 0
  4742.7     .05       0  4989.7     .04       0  4993.7     .05       0
Bank Sta=4989.7,4993.7
XS Rating Curve= 0 ,0
Exp/Cntr=0.3,0.1

Type RM Length L Ch R = 1 ,1778    ,151,151,151
BEGIN DESCRIPTION:
Lacy 128 1229
END DESCRIPTION:
XS GIS Cut Line= 3
      2722607.52      6863130.06      2722588.76      6863368.58
      2722633.04      6863627.67
#Sta/Elev= 30
  4766.7  398.65  4797.7  397.58  4827.8  396.86  4846.4  396.62    4898  394.33
  4928.1  393.38  4938.2  392.61  4948.2   391.6  4958.2  391.02  4975.3  389.35
  4980.3  389.21  4998.4  387.94  5002.7  385.09  5002.9  384.59  5006.4  384.59
  5006.7  385.09  5009.7  385.09  5016.4  386.77  5028.7  388.04  5038.8  388.15
    5049  388.88  5069.3  389.63  5076.5  389.37  5081.6  389.53  5089.6  389.41
  5099.7  389.67  5109.9  389.47  5141.7  390.01  5231.6  391.07  5268.8  390.64
#Mann= 3 ,-1 , 0
  4766.7     .05       0  5002.7    .035       0  5006.7     .05       0
Bank Sta=5002.7,5006.7
XS Rating Curve= 0 ,0
Exp/Cntr=0.3,0.1

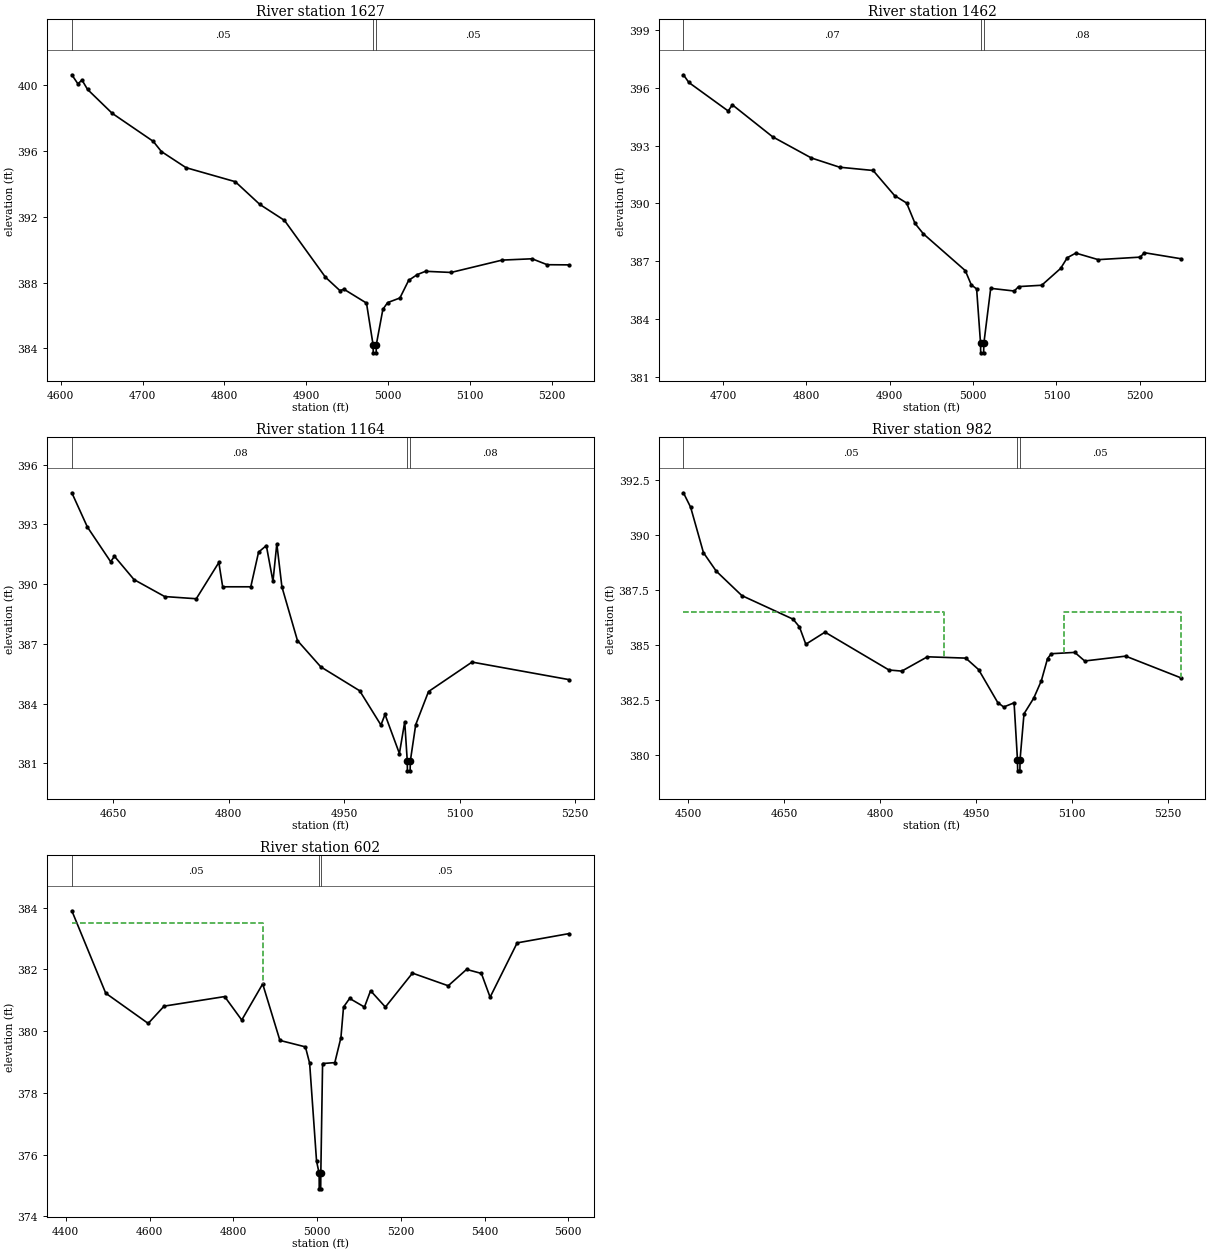
Type RM Length L Ch R = 1 ,1627    ,165,165,165
BEGIN DESCRIPTION:
Lacy 128 1251
END DESCRIPTION:
XS GIS Cut Line= 3
      2722450.33      6863071.81      2722474.53      6863457.45
      2722546.54      6863666.18
#Sta/Elev= 30
  4613.6  400.61    4621  400.06    4626  400.29  4632.8  399.72  4662.9  398.27
    4713  396.57    4723  395.95  4753.1  394.97  4813.2  394.12  4843.2  392.74
  4873.3  391.77  4923.4  388.32    4941  387.51    4946  387.59  4973.5  386.75
  4981.5  384.23  4981.8  383.73  4985.3  383.73  4985.5  384.23  4993.5  386.37
  4999.3  386.78  5014.3  387.06    5025  388.13  5035.5  388.48  5045.6  388.68
  5076.8  388.61  5139.2  389.36  5175.7  389.44  5194.2  389.08  5220.8  389.07
#Mann= 3 ,-1 , 0
  4613.6     .05       0  4981.5    .035       0  4985.5     .05       0
Bank Sta=4981.5,4985.5
XS Rating Curve= 0 ,0
Exp/Cntr=0.3,0.1

Type RM Length L Ch R = 1 ,1462    ,298,298,298
BEGIN DESCRIPTION:
Lacy 128 1250
END DESCRIPTION:
XS GIS Cut Line= 3
      2722275.38      6863114.54      2722310.45      6863460.37
      2722360.65      6863704.15
#Sta/Elev= 30
  4652.4  396.68  4658.9  396.28  4706.1   394.8  4711.1  395.12  4759.4  393.46
  4805.9  392.36  4839.8  391.88    4880  391.71  4905.7  390.41  4920.2  390.02
  4930.3  388.96  4940.3  388.42  4990.6  386.51  4997.8  385.77  5004.2  385.56
  5008.9  382.74  5009.1  382.24  5012.6  382.24  5012.9  382.74  5021.1  385.59
  5049.4  385.45  5054.5  385.68  5082.3  385.75  5104.9  386.62    5113  387.18
  5123.2  387.42  5150.1  387.08  5200.4  387.21  5205.5  387.44  5248.9  387.13
#Mann= 3 ,-1 , 0
  4652.4     .07       0  5008.9     .04       0  5012.9     .08       0
Bank Sta=5008.9,5012.9
XS Rating Curve= 0 ,0
Exp/Cntr=0.3,0.1

Type RM Length L Ch R = 1 ,1164    ,182,182,182
BEGIN DESCRIPTION:
Lacy 128 1249
END DESCRIPTION:
XS GIS Cut Line= 3
      2722043.08      6863161.04      2722100.92      6863560.57
      2722181.63      6863788.61
#Sta/Elev= 30
  4596.3  394.59  4616.5  392.87  4646.7  391.13  4651.7   391.4  4677.1  390.23
  4716.9  389.38  4757.9  389.27  4787.2  391.09  4792.2  389.87  4828.7  389.87
  4838.8  391.61  4848.9  391.94  4857.5  390.14  4862.5  392.03  4869.1  389.87
  4889.3  387.17  4919.6  385.85  4970.1  384.65  4997.7  382.93    5003  383.46
  5021.7   381.5  5028.6  383.09  5031.9  381.13  5032.1  380.63  5035.6  380.63
  5035.9  381.13  5042.9  382.95  5059.5  384.61    5116  386.09  5241.9  385.21
#Mann= 3 ,-1 , 0
  4596.3     .08       0  5031.9     .05       0  5035.9     .08       0
Bank Sta=5031.9,5035.9
XS Rating Curve= 0 ,0
Exp/Cntr=0.3,0.1

Type RM Length L Ch R = 1 ,982     ,380,380,380
BEGIN DESCRIPTION:
Lacy 128 1248
END DESCRIPTION:
XS GIS Cut Line= 3
       2721974.3      6863159.68      2721975.57      6863664.52
      2722116.98      6863897.05
#Sta/Elev= 30
  4492.5  391.92  4503.8  391.26  4523.8   389.2  4543.8  388.36  4583.8  387.25
  4663.8  386.18  4673.8  385.83  4683.8  385.04  4713.8  385.59  4813.8  383.87
  4833.8  383.82  4873.8  384.47  4933.8  384.41  4953.8  383.89  4983.8  382.39
  4993.1  382.19  5009.3  382.38  5014.6  379.79  5014.9  379.29  5018.4  379.29
  5018.6  379.79  5024.8  381.88    5040  382.59  5051.9  383.38  5061.6  384.39
  5067.4  384.61  5104.2  384.67  5119.7  384.28  5183.7   384.5  5269.5  383.52
#Mann= 3 ,-1 , 0
  4492.5     .05       0  5014.6    .035       0  5018.6     .05       0
#XS Ineff= 2 , 0
       0    4900   386.5    5088       0   386.5
Permanent Ineff=
       F       F
Bank Sta=5014.6,5018.6
XS Rating Curve= 0 ,0
Exp/Cntr=0.3,0.1

Type RM Length L Ch R = 1 ,602     ,0,0,0
BEGIN DESCRIPTION:
Lacy 128 1247
END DESCRIPTION:
XS GIS Cut Line= 3
      2721768.51      6863131.29      2721669.91      6863708.43
      2722151.12      6864069.33
#Sta/Elev= 30
  4414.5   383.9  4495.4  381.23  4596.8  380.25  4634.8  380.81  4779.4  381.12
  4820.2  380.36  4870.2  381.53  4911.3   379.7  4972.2  379.49  4982.3  378.96
  4998.8  375.79    5005  375.39  5005.2  374.89  5008.7  374.89    5009  375.39
  5013.2  378.95  5042.4  378.98    5057  379.79  5063.2  380.78  5077.8  381.06
  5113.2  380.78  5127.8  381.31  5163.2  380.78  5227.8  381.88  5313.2  381.47
    5357     382  5392.4  381.87  5413.2   381.1  5477.8  382.86  5601.5  383.16
#Mann= 3 ,-1 , 0
  4414.5     .05       0    5005    .035       0    5009     .05       0
#XS Ineff= 2 , 0
       0    4870   383.5               0
Permanent Ineff=
       F       F
Bank Sta=5005,5009
XS Rating Curve= 0 ,0
Exp/Cntr=0.3,0.1

Chan Stop Cuts=-1
Use User Specified Reach Order=0
Composite Channel Slope=5