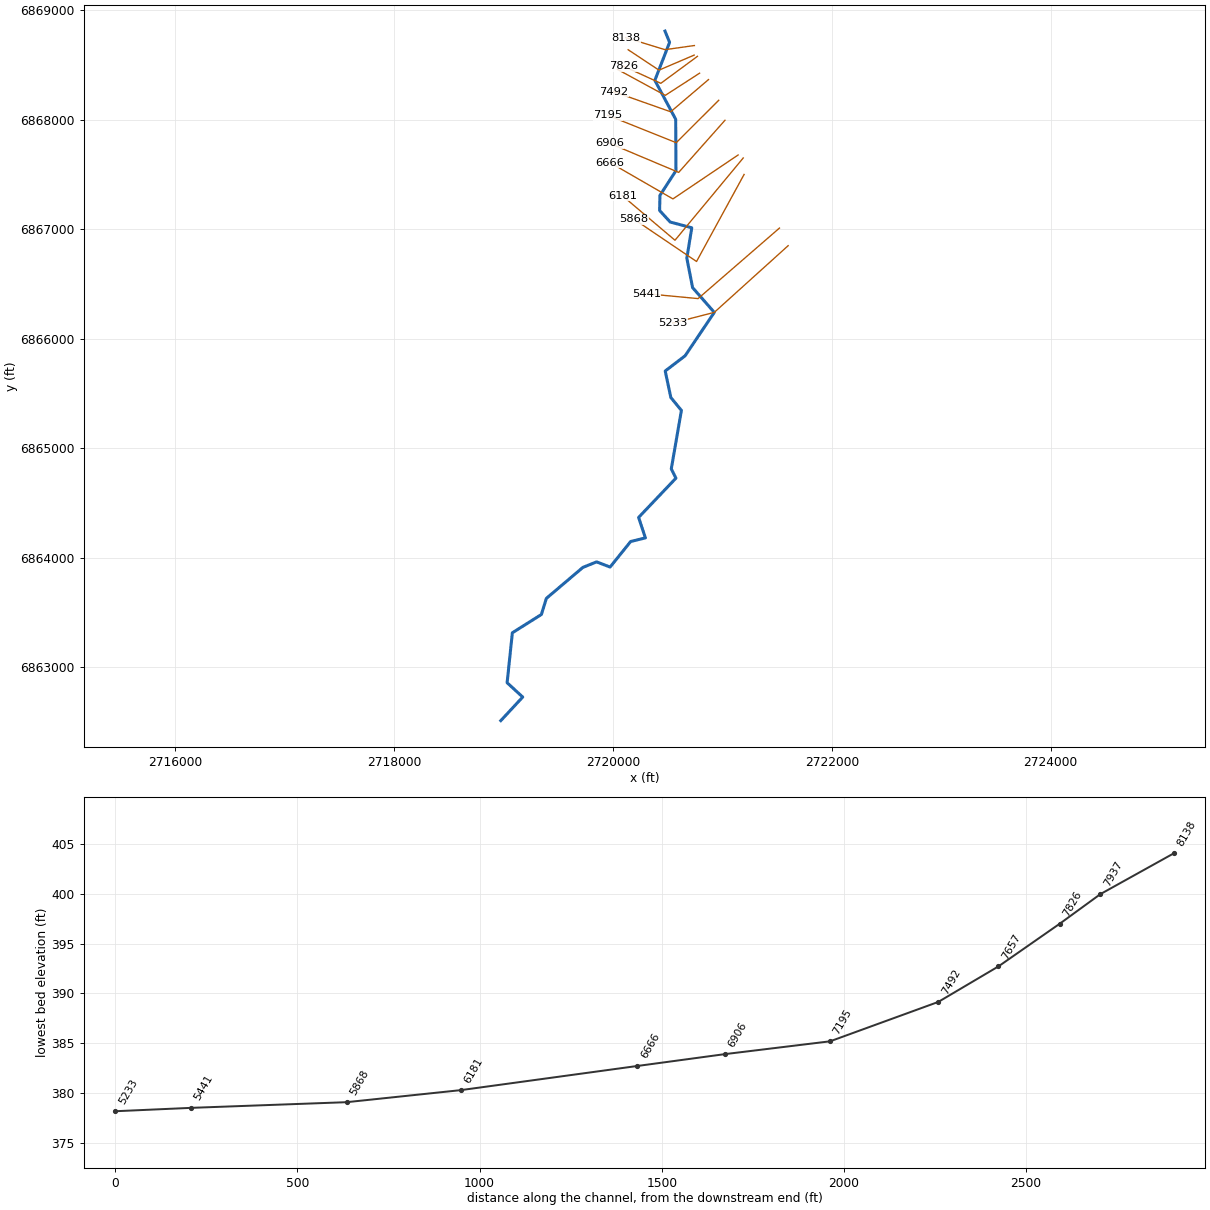
--- Lacy 129.prj (project) ---

Proj Title=Lacy 129 Base Level Engineering
Current Plan=p01
Default Exp/Contr=0.3,0.1
English Units
Geom File=g01
Flow File=f01
Plan File=p01
Y Axis Title=Elevation
X Axis Title(PF)=Main Channel Distance
X Axis Title(XS)=Station
BEGIN DESCRIPTION:
Lacy 129
END DESCRIPTION:
DSS Export Rating Curves= 0
DSS Export Rating Curve Sorted= 0
DSS Export Volume Flow Curves= 0
DXF OffsetX= 0
DXF OffsetY= 0
DXF ScaleX= 1
DXF ScaleY= 10

--- Lacy 129.p01 (plan) ---

Plan Title=Multiple Run
Short Identifier=Multiple
Geom File=g01
Flow File=f01
Subcritical Flow
K Sum by GR= 0
Std Step Tol= 0.01
Critical Tol= 0.01
Num of Std Step Trials= 20
Max Error Tol= 0.3
Flow Tol Ratio= 0.001
Split Flow NTrial= 30
Split Flow Tol= 0.02
Split Flow Ratio= 0.02
Log Output Level= 0
Friction Slope Method= 1
Unsteady Friction Slope Method= 2
Unsteady Bridges Friction Slope Method= 1
Parabolic Critical Depth
Global Vel Dist=  1 , 1 , 1
Global Log Level= 0
CheckData=True
Encroach Param= -1, 0, 0, 0
BEGIN DESCRIPTION:
Multiple Run
END DESCRIPTION:

--- Lacy 129.f01 (steady flow) ---

Flow Title=Multiple
Number of Profiles=7
Profile Names=10-year,25-year,50-year,1pct_min,100-year,1pct_plu,500-year
River Rch & RM= Lacy 129,Reach-1,8138
     239     298     343     196     392     782     509
Boundary for River Rch & Prof#=Lacy 129,Reach-1,1
Up Type=0
Dn Type=3
Dn Slope=0.005
Boundary for River Rch & Prof#=Lacy 129,Reach-1,2
Up Type=0
Dn Type=3
Dn Slope=0.005
Boundary for River Rch & Prof#=Lacy 129,Reach-1,3
Up Type=0
Dn Type=3
Dn Slope=0.005
Boundary for River Rch & Prof#=Lacy 129,Reach-1,4
Up Type=0
Dn Type=3
Dn Slope=0.005
Boundary for River Rch & Prof#=Lacy 129,Reach-1,5
Up Type=0
Dn Type=3
Dn Slope=0.005
Boundary for River Rch & Prof#=Lacy 129,Reach-1,6
Up Type=0
Dn Type=3
Dn Slope=0.005
Boundary for River Rch & Prof#=Lacy 129,Reach-1,7
Up Type=0
Dn Type=3
Dn Slope=0.005

--- Lacy 129.g01 (geometry) ---

Geom Title=Existing Conditions
Program Version=4.10

River Reach=Lacy 129        ,Reach-1
Reach XY= 30
        2720476.        6868811.      2720518.11      6868707.74
      2720383.32       6868360.9      2720573.74      6868005.06
      2720576.32      6867535.89      2720429.74      6867309.44
      2720427.03      6867171.43      2720523.54      6867066.46
      2720720.66      6867013.74       2720675.6        6866736.
      2720728.24      6866466.93      2720926.51      6866240.94
      2720659.51      6865843.95      2720477.96      6865705.12
      2720529.62       6865462.5      2720626.04      6865345.66
      2720533.59      6864810.99      2720576.04      6864726.24
      2720235.11      6864367.73       2720297.1      6864180.61
      2720162.67      6864147.61      2719974.38      6863914.13
      2719851.01      6863961.46        2719726.        6863911.
      2719392.38      6863628.09      2719346.57      6863480.58
      2719081.45      6863313.47      2719033.69      6862857.33
      2719176.13      6862726.42        2718976.        6862511.

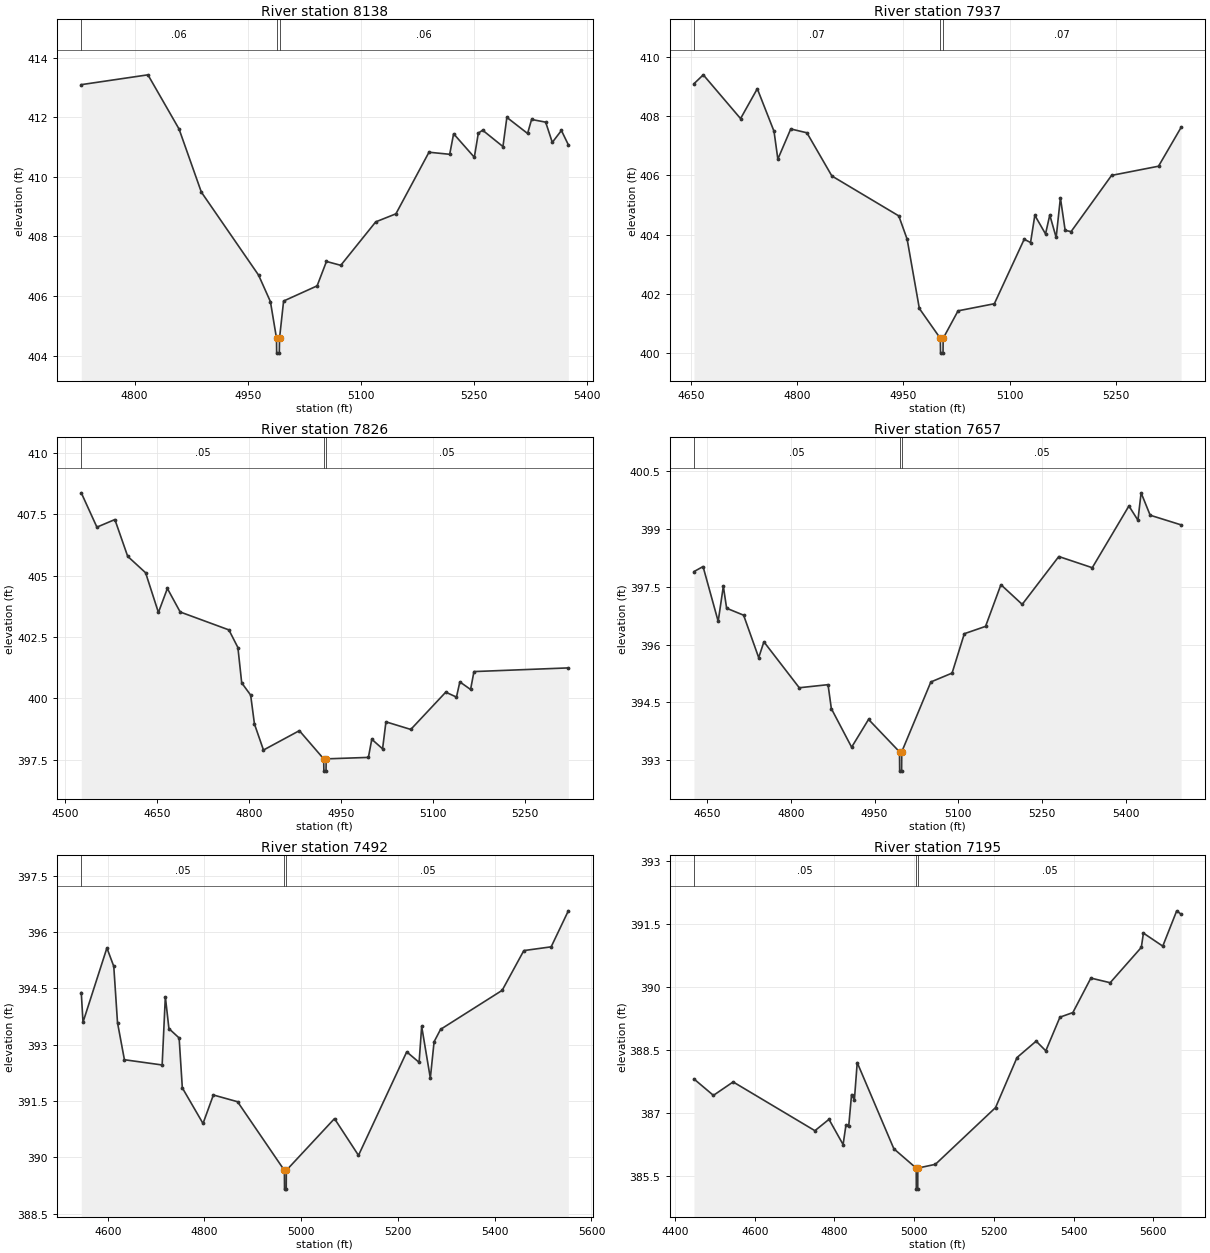
Type RM Length L Ch R = 1 ,8138    ,201,201,201
BEGIN DESCRIPTION:
Lacy 129 1218
END DESCRIPTION:
XS GIS Cut Line= 3
      2720744.56      6868679.02      2720476.35      6868640.95
       2720117.2      6868751.22
#Sta/Elev= 30
  4729.1   413.1  4817.6  413.43  4858.9  411.61  4888.5  409.49  4964.5   406.7
  4980.2  405.81  4988.3  404.58  4988.5  404.08    4992  404.08  4992.3  404.58
  4997.7  405.83  5042.2  406.34  5054.6  407.16  5073.6  407.03    5120  408.49
  5146.8  408.76  5190.7  410.83  5218.2  410.76  5223.4  411.45  5250.9  410.66
  5256.2  411.47  5261.9  411.57  5288.9  411.02  5294.1     412  5321.6  411.46
  5326.9  411.93  5345.6  411.84  5354.4  411.16  5366.5  411.56  5375.7  411.08
#Mann= 3 ,-1 , 0
  4729.1     .06       0  4988.3     .03       0  4992.3     .06       0
Bank Sta=4988.3,4992.3
XS Rating Curve= 0 ,0
Exp/Cntr=0.3,0.1

Type RM Length L Ch R = 1 ,7937    ,111,111,111
BEGIN DESCRIPTION:
Lacy 129 3444
END DESCRIPTION:
XS GIS Cut Line= 3
      2720742.46      6868591.39      2720421.12      6868453.93
      2720139.64       6868640.3
#Sta/Elev= 30
  4654.6   409.1  4667.7   409.4  4720.3  407.92  4743.9  408.93  4767.5  407.49
  4772.9  406.55  4791.1  407.57  4813.9  407.44  4849.1  405.98  4943.5  404.63
  4955.3  403.84  4972.5   401.5  5002.1  400.49  5002.4  399.99  5005.9  399.99
  5006.1  400.49  5027.1  401.42  5078.3  401.66  5120.4  403.84  5129.4  403.73
  5135.4  404.65  5150.5  404.02  5156.5  404.66  5165.5   403.9  5171.5  405.24
  5178.2  404.14  5186.6   404.1  5243.7     406  5309.9  406.31  5341.7  407.62
#Mann= 3 ,-1 , 0
  4654.6     .07       0  5002.1     .03       0  5006.1     .07       0
Bank Sta=5002.1,5006.1
XS Rating Curve= 0 ,0
Exp/Cntr=0.3,0.1

Type RM Length L Ch R = 1 ,7826    ,169,169,169
BEGIN DESCRIPTION:
Lacy 129 3446
END DESCRIPTION:
XS GIS Cut Line= 3
      2720772.73      6868580.26      2720437.93      6868333.79
      2720093.77      6868491.23
#Sta/Elev= 30
  4525.9  408.38  4551.4  406.98  4580.7  407.29  4601.6  405.79  4630.8  405.12
  4651.7   403.5  4666.3  404.48  4687.2  403.52  4766.6  402.79  4781.3  402.07
  4787.5  400.63  4802.1  400.13  4808.3  398.95    4823  397.89  4881.5  398.68
  4921.2  397.53  4921.5  397.03    4925  397.03  4925.2  397.53  4994.1  397.59
  4999.6  398.33  5017.2  397.94  5022.7  399.04  5063.2  398.73  5120.2  400.25
  5137.7  400.05  5143.2  400.67  5160.7  400.36  5166.2  401.09  5320.1  401.24
#Mann= 3 ,-1 , 0
  4525.9     .05       0  4921.2     .04       0  4925.2     .05       0
Bank Sta=4921.2,4925.2
XS Rating Curve= 0 ,0
Exp/Cntr=0.3,0.1

Type RM Length L Ch R = 1 ,7657    ,165,165,165
BEGIN DESCRIPTION:
Lacy 129 3445
END DESCRIPTION:
XS GIS Cut Line= 3
      2720792.17      6868426.38      2720478.55      6868223.66
      2720040.69      6868461.46
#Sta/Elev= 30
  4626.9  397.89  4643.1  398.02  4670.2   396.6  4679.4  397.51  4685.3  396.94
  4715.7  396.76  4742.7  395.66    4752  396.07  4815.3  394.88  4866.8  394.96
  4872.7  394.34    4909  393.34  4939.3  394.06  4994.7  393.22    4995  392.72
  4998.5  392.72  4998.7  393.22  5050.8  395.03  5088.8  395.26  5110.7  396.28
  5148.7  396.47  5176.2  397.55  5214.3  397.04  5279.8  398.28  5339.7  397.99
  5405.3  399.59  5421.4  399.22  5427.1  399.93  5443.3  399.35  5498.6   399.1
#Mann= 3 ,-1 , 0
  4626.9     .05       0  4994.7     .04       0  4998.7     .05       0
Bank Sta=4994.7,4998.7
XS Rating Curve= 0 ,0
Exp/Cntr=0.3,0.1

Type RM Length L Ch R = 1 ,7492    ,297,297,297
BEGIN DESCRIPTION:
Lacy 129 3443
END DESCRIPTION:
XS GIS Cut Line= 3
       2720873.9      6868368.13       2720528.1      6868073.56
      2720007.01      6868257.63
#Sta/Elev= 30
  4545.3  394.39  4548.9   393.6  4598.3  395.58  4612.5  395.09  4620.2  393.59
  4634.5   392.6  4712.5  392.46  4719.1  394.28  4726.5  393.43  4747.6  393.18
  4754.2  391.85    4797   390.9  4818.4  391.66  4868.4  391.48  4965.2  389.65
  4965.5  389.15    4969  389.15  4969.2  389.65  5068.8  391.03  5118.4  390.05
  5218.1  392.81  5243.7  392.53    5249  393.49  5266.9  392.11  5274.7  393.08
  5288.1  393.41  5415.4  394.45  5460.2  395.51  5516.7  395.61  5552.2  396.57
#Mann= 3 ,-1 , 0
  4545.3     .05       0  4965.2     .04       0  4969.2     .05       0
Bank Sta=4965.2,4969.2
XS Rating Curve= 0 ,0
Exp/Cntr=0.3,0.1

Type RM Length L Ch R = 1 ,7195    ,289,289,289
BEGIN DESCRIPTION:
Lacy 129 3442
END DESCRIPTION:
XS GIS Cut Line= 3
      2720967.05      6868178.86      2720578.73      6867791.14
      2719954.01      6868041.31
#Sta/Elev= 30
  4447.7  387.81  4496.4  387.42  4545.9  387.74    4751  386.58  4786.3  386.85
  4821.7  386.25  4828.8  386.71  4835.8  386.69  4842.9  387.44    4850  387.31
  4857.1   388.2    4949  386.15  5005.1  385.69  5005.4  385.19  5008.9  385.19
  5009.1  385.69  5053.2  385.78  5204.1  387.13  5257.9  388.32  5305.9  388.71
  5330.1  388.48  5365.6  389.28    5398  389.39  5443.2  390.21  5491.6   390.1
  5569.7  390.94    5575  391.28  5623.5  390.97  5658.5  391.81  5669.4  391.73
#Mann= 3 ,-1 , 0
  4447.7     .05       0  5005.1     .04       0  5009.1     .05       0
Bank Sta=5005.1,5009.1
XS Rating Curve= 0 ,0
Exp/Cntr=0.3,0.1

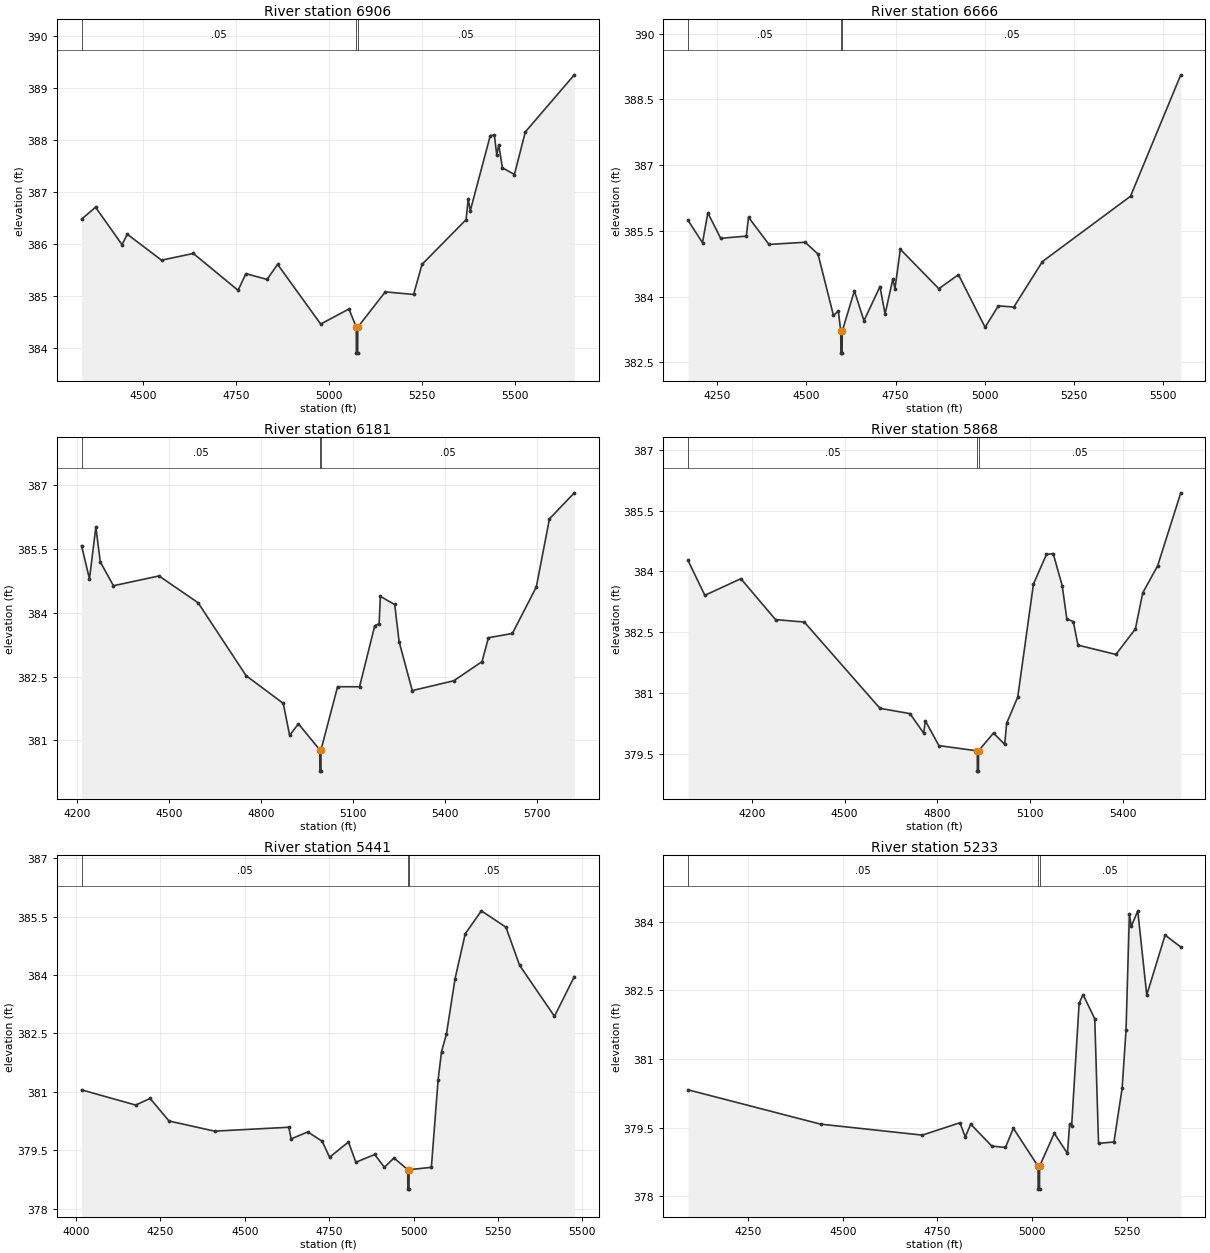
Type RM Length L Ch R = 1 ,6906    ,240,240,240
BEGIN DESCRIPTION:
Lacy 129 3447
END DESCRIPTION:
XS GIS Cut Line= 3
      2721024.13      6867996.15      2720601.06      6867519.88
      2719967.91      6867786.41
#Sta/Elev= 30
  4335.4  386.48    4373  386.71  4444.1  385.99  4458.3  386.19  4550.3  385.69
  4635.6  385.82    4756  385.11  4776.9  385.43  4833.8  385.32  4862.2  385.61
  4977.9  384.46  5053.9  384.75  5073.6   384.4  5073.8   383.9  5077.3   383.9
  5077.6   384.4  5151.5  385.08  5227.5  385.03  5250.3  385.61  5368.5  386.47
  5374.4  386.87  5379.8  386.64  5433.6  388.09  5444.5   388.1    5451  387.72
  5456.4  387.91  5466.2  387.47  5498.5  387.34  5527.7  388.16  5659.4  389.26
#Mann= 3 ,-1 , 0
  4335.4     .05       0  5073.6     .04       0  5077.6     .05       0
Bank Sta=5073.6,5077.6
XS Rating Curve= 0 ,0
Exp/Cntr=0.3,0.1

Type RM Length L Ch R = 1 ,6666    ,485,485,485
BEGIN DESCRIPTION:
Lacy 129 3439
END DESCRIPTION:
XS GIS Cut Line= 3
       2721144.2      6867679.02      2720548.59      6867277.61
      2719974.01      6867609.31
#Sta/Elev= 30
    4168  385.74  4208.6  385.23  4223.6  385.91  4259.6  385.33  4331.5  385.38
  4337.6  385.81    4395  385.19  4496.5  385.24  4532.5  384.97  4575.8  383.57
  4589.4  383.67  4596.4  383.21  4596.6  382.71  4600.1  382.71  4600.4  383.21
  4634.4  384.13  4661.4  383.45  4706.3  384.23  4720.5   383.6  4742.3   384.4
  4748.3  384.18  4763.3  385.08  4871.3  384.18  4926.3   384.5    5001   383.3
  5038.3  383.79  5081.4  383.76  5161.8   384.8  5408.8  386.29  5549.7  389.06
#Mann= 3 ,-1 , 0
    4168     .05       0  4596.4     .04       0  4600.4     .05       0
Bank Sta=4596.4,4600.4
XS Rating Curve= 0 ,0
Exp/Cntr=0.3,0.1

Type RM Length L Ch R = 1 ,6181    ,313,313,313
BEGIN DESCRIPTION:
Lacy 129 3440
END DESCRIPTION:
XS GIS Cut Line= 3
      2721190.89      6867651.73      2720567.38      6866899.92
      2720086.99      6867306.54
#Sta/Elev= 30
  4214.5  385.57  4240.3  384.79  4261.1  386.01  4275.5  385.19  4318.4  384.63
  4466.9  384.86  4594.5  384.23  4750.8  382.52  4871.9  381.87  4892.7  381.12
  4921.4  381.39    4991  380.78  4991.3  380.28  4994.8  380.28    4995  380.78
    5049  382.26  5120.6  382.26  5170.1  383.69  5184.4  383.74  5188.4  384.38
  5235.2  384.19  5249.5  383.32  5292.4  382.17  5427.6   382.4  5519.8  382.85
  5540.7  383.41  5618.7  383.51  5696.7   384.6  5739.6   386.2  5820.6  386.81
#Mann= 3 ,-1 , 0
  4214.5     .05       0    4991     .04       0    4995     .05       0
Bank Sta=4991,4995
XS Rating Curve= 0 ,0
Exp/Cntr=0.3,0.1

Type RM Length L Ch R = 1 ,5868    ,427,427,427
BEGIN DESCRIPTION:
Lacy 129 3441
END DESCRIPTION:
XS GIS Cut Line= 3
      2721198.68      6867501.06      2720764.18      6866705.97
      2720194.06       6867091.5
#Sta/Elev= 30
  3993.7  384.27  4048.2  383.41  4164.7  383.82  4276.9  382.81  4369.9  382.75
  4614.7  380.62  4711.7  380.49    4756  380.01  4761.7  380.31  4805.4   379.7
  4929.6  379.57  4929.9  379.07  4933.4  379.07  4933.6  379.57  4982.1  380.01
  5018.3  379.73  5024.6  380.25  5060.5   380.9  5111.4  383.69  5153.4  384.42
  5175.2  384.44  5204.3  383.65  5219.3  382.83  5240.3  382.76  5255.3  382.18
  5378.1  381.95  5441.1  382.58  5464.9  383.47  5513.2  384.14    5588  385.94
#Mann= 3 ,-1 , 0
  3993.7     .05       0  4929.6     .04       0  4933.6     .05       0
Bank Sta=4929.6,4933.6
XS Rating Curve= 0 ,0
Exp/Cntr=0.3,0.1

Type RM Length L Ch R = 1 ,5441    ,208,208,208
BEGIN DESCRIPTION:
Lacy 129 1227
END DESCRIPTION:
XS GIS Cut Line= 3
      2721521.88      6867011.31      2720778.42      6866366.85
      2720304.24       6866411.7
#Sta/Elev= 30
  4016.1  381.05  4176.5  380.66  4219.2  380.83  4275.3  380.25  4410.1  379.99
  4630.5  380.09  4637.1  379.79  4686.4  379.97  4729.2  379.73  4751.1  379.32
  4807.1  379.71    4829  379.19  4884.9  379.39  4913.4  379.06  4941.9   379.3
  4982.7     379  4982.9   378.5  4986.4   378.5  4986.7     379  5052.7  379.06
  5072.7  381.31  5082.8  382.03  5097.5  382.49    5123  383.91  5153.1  385.06
  5200.8  385.65  5273.6  385.23  5314.2  384.25  5417.5  382.94  5476.3  383.96
#Mann= 3 ,-1 , 0
  4016.1     .05       0  4982.7     .04       0  4986.7     .05       0
Bank Sta=4982.7,4986.7
XS Rating Curve= 0 ,0
Exp/Cntr=0.3,0.1

Type RM Length L Ch R = 1 ,5233    ,0,0,0
BEGIN DESCRIPTION:
Lacy 129 1228
END DESCRIPTION:
XS GIS Cut Line= 3
      2721601.22      6866850.24      2720926.51      6866240.94
      2720545.89       6866143.1
#Sta/Elev= 30
  4090.9  380.33    4441  379.58    4710  379.34  4809.4  379.61  4823.6   379.3
  4837.8  379.58  4893.8   379.1  4929.7  379.07  4950.6  379.49  5015.9  378.66
  5016.2  378.16  5019.7  378.16  5019.9  378.66  5058.7  379.38  5093.5  378.94
  5099.4  379.59  5104.6  379.54  5124.4  382.22  5134.8  382.41  5165.7  381.88
  5175.7  379.16  5216.4  379.19    5238  380.36  5248.3  381.63  5257.2  384.17
  5262.3   383.9  5279.3  384.24  5303.1   382.4  5351.6  383.71    5393  383.45
#Mann= 3 ,-1 , 0
  4090.9     .05       0  5015.9     .04       0  5019.9     .05       0
Bank Sta=5015.9,5019.9
XS Rating Curve= 0 ,0
Exp/Cntr=0.3,0.1

Chan Stop Cuts=-1
Use User Specified Reach Order=0
Composite Channel Slope=5