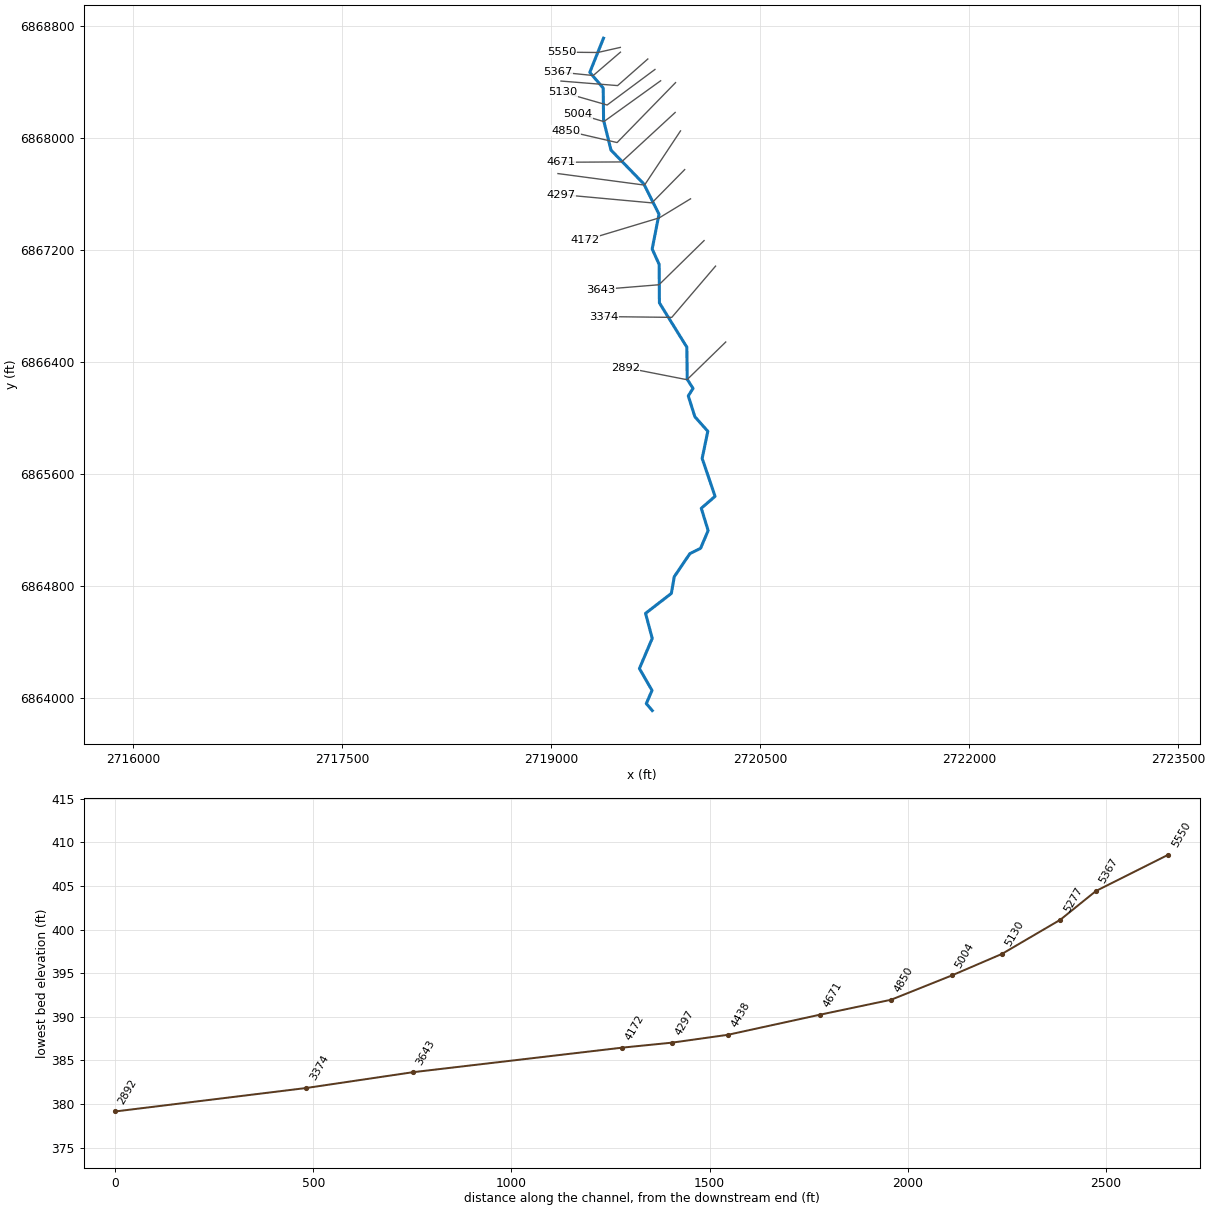
--- Lacy 130.prj (project) ---

Proj Title=Lacy 130 Base Level Engineering
Current Plan=p01
Default Exp/Contr=0.3,0.1
English Units
Geom File=g01
Flow File=f01
Plan File=p01
BEGIN DESCRIPTION:
Lacy 130
END DESCRIPTION:

--- Lacy 130.p01 (plan) ---

Plan Title=Multiple Run
Short Identifier=Multiple
Geom File=g01
Flow File=f01
Subcritical Flow
K Sum by GR= 0
Std Step Tol= 0.01
Critical Tol= 0.01
Num of Std Step Trials= 20
Max Error Tol= 0.3
Flow Tol Ratio= 0.001
Split Flow NTrial= 30
Split Flow Tol= 0.02
Split Flow Ratio= 0.02
Log Output Level= 0
Friction Slope Method= 1
Unsteady Friction Slope Method= 2
Unsteady Bridges Friction Slope Method= 1
Parabolic Critical Depth
Global Vel Dist=  1 , 1 , 1
Global Log Level= 0
CheckData=True
Encroach Param= -1, 0, 0, 0
BEGIN DESCRIPTION:
Multiple Run
END DESCRIPTION:

--- Lacy 130.f01 (steady flow) ---

Flow Title=Multiple
Number of Profiles=7
Profile Names=10-year,25-year,50-year,1pct_min,100-year,1pct_plu,500-year
River Rch & RM= Lacy 130,Reach-1,5550
     207     257     294     168     334     667     431
Boundary for River Rch & Prof#=Lacy 130,Reach-1,1
Up Type=0
Dn Type=3
Dn Slope=0.005
Boundary for River Rch & Prof#=Lacy 130,Reach-1,2
Up Type=0
Dn Type=3
Dn Slope=0.005
Boundary for River Rch & Prof#=Lacy 130,Reach-1,3
Up Type=0
Dn Type=3
Dn Slope=0.005
Boundary for River Rch & Prof#=Lacy 130,Reach-1,4
Up Type=0
Dn Type=3
Dn Slope=0.005
Boundary for River Rch & Prof#=Lacy 130,Reach-1,5
Up Type=0
Dn Type=3
Dn Slope=0.005
Boundary for River Rch & Prof#=Lacy 130,Reach-1,6
Up Type=0
Dn Type=3
Dn Slope=0.005
Boundary for River Rch & Prof#=Lacy 130,Reach-1,7
Up Type=0
Dn Type=3
Dn Slope=0.005

--- Lacy 130.g01 (geometry) ---

Geom Title=Existing Conditions

River Reach=Lacy 130,Reach-1
Reach XY= 30
      2719376.00      6868711.00      2719277.63      6868467.04
      2719373.93      6868355.14      2719376.52      6868126.22
      2719429.54      6867912.47      2719665.24      6867670.68
      2719774.16      6867454.87      2719725.22      6867205.98
      2719775.48      6867095.78      2719777.06      6866821.44
      2719973.93      6866505.14      2719976.65      6866276.16
      2720018.21      6866210.90      2719984.28      6866157.78
      2720031.54      6866008.58      2720124.34      6865904.95
      2720083.78      6865711.10      2720176.46      6865440.54
      2720077.57      6865355.14      2720126.72      6865195.93
      2720072.47      6865069.49      2719995.73      6865031.43
      2719883.88      6864867.16      2719862.74      6864747.35
      2719677.61      6864604.98      2719725.62      6864426.27
      2719633.53      6864210.99      2719724.18      6864054.88
      2719682.95      6863960.88      2719726.00      6863911.00

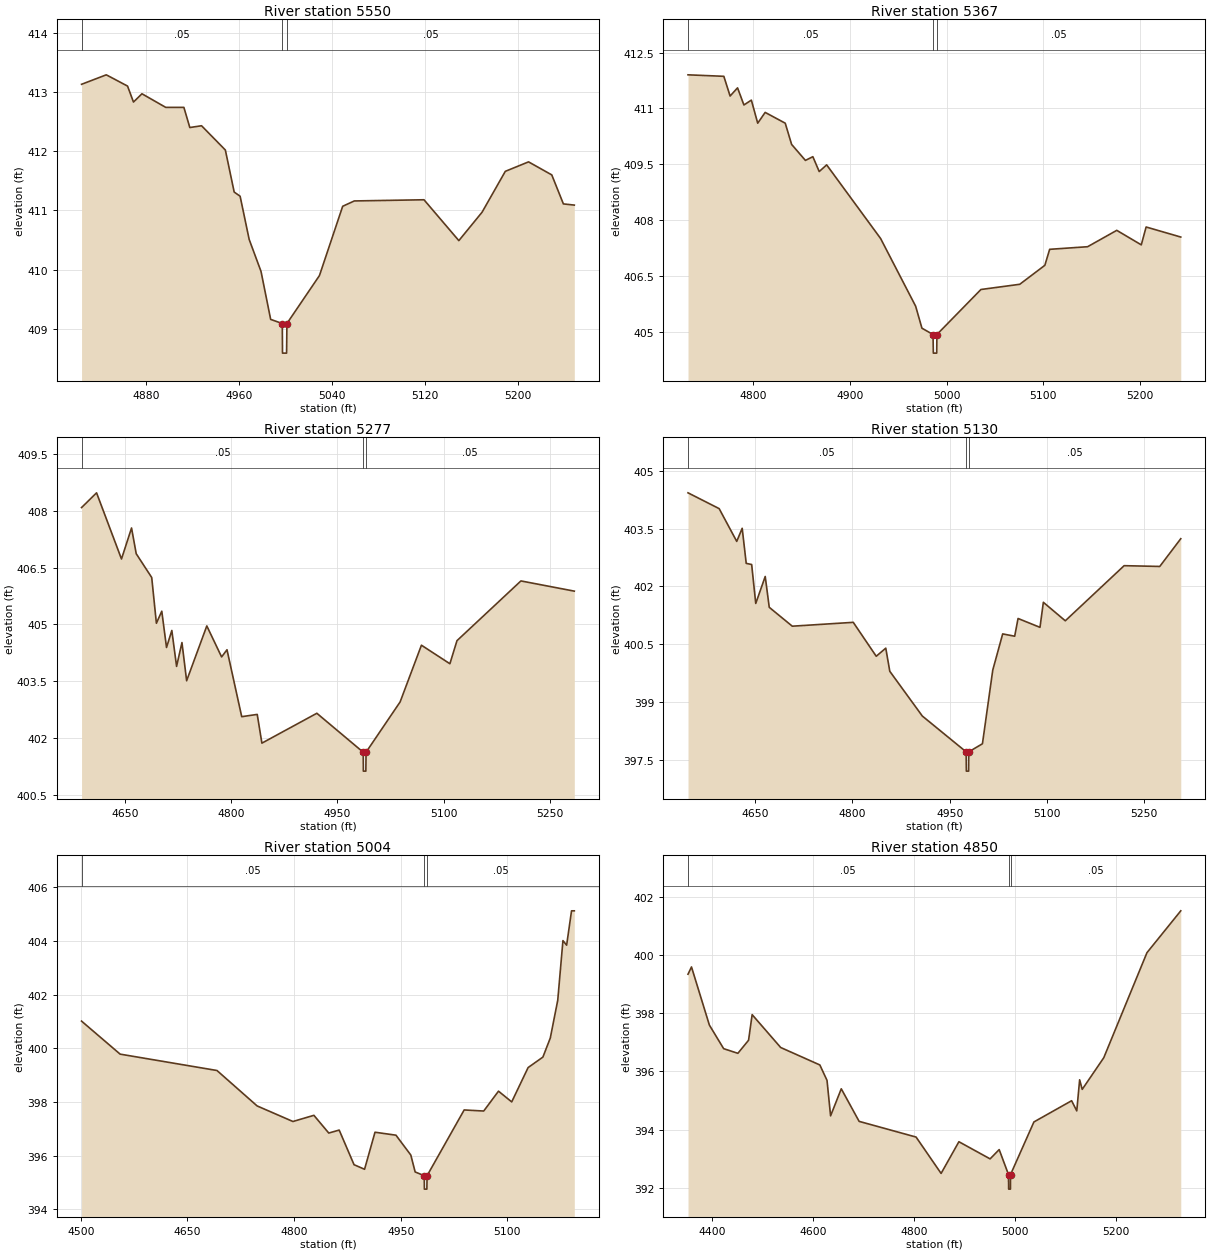
Type RM Length L Ch R = 1,5550,183,183,183
BEGIN DESCRIPTION:
Lacy 130 1217
END DESCRIPTION:
XS GIS Cut Line= 3
      2719496.76      6868645.32      2719334.79      6868608.97
      2719076.60      6868611.35
#Sta/Elev= 30
  4824.3  413.13  4845.6  413.29  4863.9  413.10  4869.0  412.83  4876.3  412.97
  4896.8  412.74  4912.4  412.74  4917.5  412.40  4927.6  412.43  4948.1  412.02
  4955.7  411.31  4960.8  411.24  4968.6  410.51  4978.8  409.97  4987.1  409.16
  4997.1  409.09  4997.3  408.59  5000.8  408.59  5001.1  409.09  5029.1  409.90
  5049.1  411.07  5059.1  411.16  5119.1  411.18  5149.1  410.49  5169.1  410.97
  5189.1  411.66  5209.1  411.82  5229.1  411.60  5239.1  411.11  5248.5  411.09
#Mann=3,-1,0
  4824.3    0.05       0  4997.1    0.03       0  5001.1    0.05       0
Bank Sta=4997.1,5001.1
Exp/Cntr=0.3,0.1

Type RM Length L Ch R = 1,5367,90,90,90
BEGIN DESCRIPTION:
Lacy 130 3447
END DESCRIPTION:
XS GIS Cut Line= 3
      2719497.57      6868611.44      2719302.23      6868444.56
      2719050.04      6868470.09
#Sta/Elev= 30
  4732.2  411.90  4769.3  411.86  4775.8  411.33  4783.5  411.55  4790.1  411.09
  4797.8  411.22  4804.4  410.60  4812.1  410.89  4832.9  410.60  4839.5  410.03
  4853.8  409.60  4861.5  409.70  4868.1  409.30  4875.8  409.48  4931.7  407.50
  4968.0  405.68  4974.5  405.09  4986.0  404.92  4986.3  404.42  4989.8  404.42
  4990.0  404.92  5035.6  406.13  5075.8  406.27  5101.8  406.78  5106.8  407.21
  5146.1  407.28  5176.3  407.72  5201.7  407.33  5206.7  407.81  5242.6  407.54
#Mann=3,-1,0
  4732.2    0.05       0  4986.0    0.04       0  4990.0    0.05       0
Bank Sta=4986,4990
Exp/Cntr=0.3,0.1

Type RM Length L Ch R = 1,5277,147,147,147
BEGIN DESCRIPTION:
Lacy 130 3449
END DESCRIPTION:
XS GIS Cut Line= 3
      2719693.96      6868562.65      2719477.20      6868372.68
      2719070.81      6868405.04
#Sta/Elev= 30
  4588.6  408.09  4609.8  408.48  4645.0  406.73  4659.2  407.55  4665.8  406.87
  4687.7  406.24  4694.3  405.03  4701.9  405.35  4708.6  404.39  4716.1  404.84
  4722.8  403.89  4730.4  404.52  4737.0  403.51  4765.5  404.96  4786.4  404.14
  4794.0  404.33  4814.8  402.56  4836.7  402.62  4843.3  401.86  4920.9  402.65
  4986.4  401.62  4986.6  401.12  4990.1  401.12  4990.4  401.62  5038.5  402.95
  5068.6  404.45  5108.8  403.96  5118.8  404.57  5209.1  406.15  5284.5  405.88
#Mann=3,-1,0
  4588.6    0.05       0  4986.4    0.04       0  4990.4    0.05       0
Bank Sta=4986.4,4990.4
Exp/Cntr=0.3,0.1

Type RM Length L Ch R = 1,5130,126,126,126
BEGIN DESCRIPTION:
Lacy 130 3448
END DESCRIPTION:
XS GIS Cut Line= 3
      2719745.14      6868487.87      2719402.03      6868234.12
      2719082.08      6868325.51
#Sta/Elev= 30
  4546.7  404.43  4594.7  404.02  4621.8  403.17  4630.2  403.51  4636.4  402.60
  4644.8  402.57  4651.1  401.56  4665.7  402.26  4671.9  401.46  4707.4  400.97
  4801.4  401.07  4836.8  400.19  4851.5  400.40  4857.7  399.80  4907.8  398.64
  4975.4  397.71  4975.7  397.21  4979.2  397.21  4979.4  397.71  5000.5  397.92
  5016.4  399.83  5031.7  400.77  5050.2  400.71  5055.4  401.17  5089.2  400.94
  5094.4  401.59  5128.2  401.11  5218.9  402.54  5273.8  402.52  5306.2  403.24
#Mann=3,-1,0
  4546.7    0.05       0  4975.4    0.04       0  4979.4    0.05       0
Bank Sta=4975.4,4979.4
Exp/Cntr=0.3,0.1

Type RM Length L Ch R = 1,5004,154,154,154
BEGIN DESCRIPTION:
Lacy 130 3451
END DESCRIPTION:
XS GIS Cut Line= 3
      2719785.87      6868407.04      2719378.70      6868115.74
      2719193.60      6868169.90
#Sta/Elev= 30
  4500.9  401.01  4555.2  399.78  4691.5  399.17  4748.0  397.85  4798.4  397.27
  4827.9  397.50  4848.8  396.84  4863.5  396.95  4884.4  395.66  4899.2  395.49
  4913.9  396.87  4943.4  396.76  4964.3  396.02  4970.4  395.39  4983.2  395.25
  4983.4  394.75  4986.9  394.75  4987.2  395.25  5039.4  397.70  5066.9  397.66
  5087.7  398.40  5106.3  398.00  5129.4  399.28  5150.2  399.67  5160.6  400.38
  5171.1  401.79  5178.4  404.01  5183.6  403.84  5190.5  405.12  5194.4  405.12
#Mann=3,-1,0
  4500.9    0.05       0  4983.2    0.04       0  4987.2    0.05       0
Bank Sta=4983.2,4987.2
Exp/Cntr=0.3,0.1

Type RM Length L Ch R = 1,4850,179,179,179
BEGIN DESCRIPTION:
Lacy 130 3452
END DESCRIPTION:
XS GIS Cut Line= 3
      2719892.94      6868393.93      2719473.54      6867965.98
      2719105.01      6868050.95
#Sta/Elev= 30
  4352.0  399.34  4358.9  399.59  4394.4  397.59  4422.7  396.78  4450.9  396.62
  4472.1  397.07  4479.2  397.95  4535.8  396.82  4613.5  396.22  4627.7  395.69
  4634.8  394.47  4656.0  395.40  4691.4  394.28  4804.4  393.74  4854.0  392.49
  4889.3  393.58  4951.2  392.99  4969.2  393.31  4987.7  392.45  4988.0  391.95
  4991.5  391.95  4991.7  392.45  5038.1  394.26  5112.9  394.99  5123.1  394.64
  5128.8  395.71  5133.9  395.38  5176.7  396.47  5262.3  400.08  5329.4  401.52
#Mann=3,-1,0
  4352.0    0.05       0  4987.7    0.04       0  4991.7    0.05       0
Bank Sta=4987.7,4991.7
Exp/Cntr=0.3,0.1

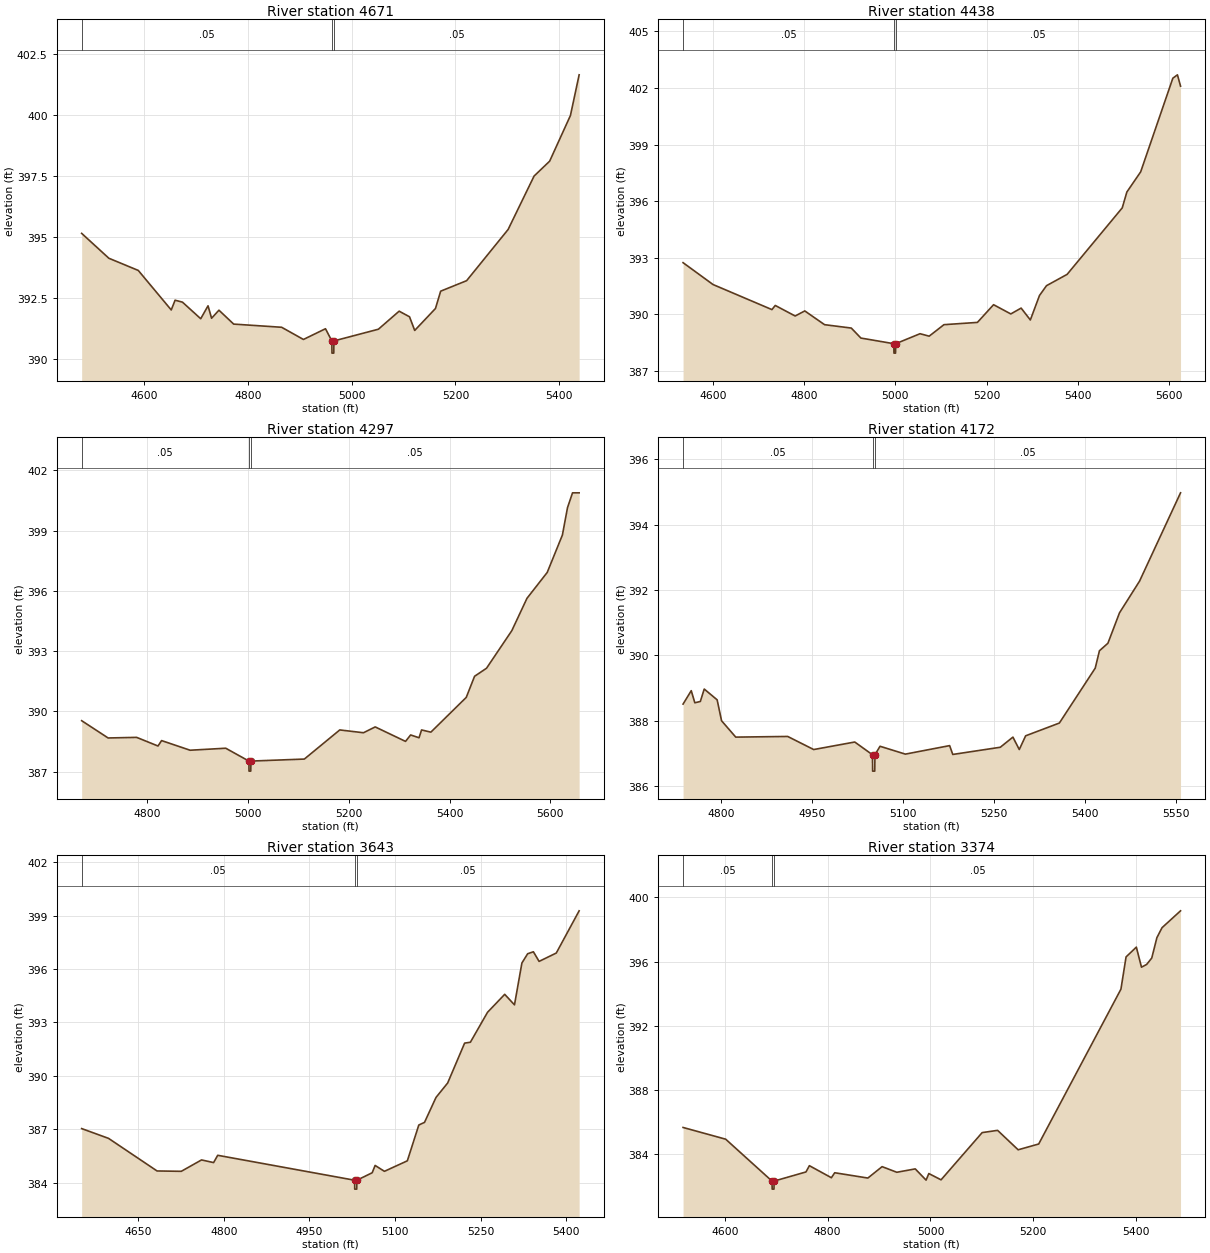
Type RM Length L Ch R = 1,4671,233,233,233
BEGIN DESCRIPTION:
Lacy 130 3450
END DESCRIPTION:
XS GIS Cut Line= 3
      2719890.20      6868180.87      2719505.37      6867827.74
      2719069.17      6867825.39
#Sta/Elev= 30
  4479.9  395.15  4532.3  394.13  4589.0  393.63  4652.5  392.01  4659.9  392.41
  4674.1  392.33  4709.3  391.65  4723.4  392.18  4730.2  391.67  4744.4  392.00
  4772.8  391.43  4865.2  391.30  4907.2  390.80  4949.7  391.24  4961.9  390.74
  4962.2  390.24  4965.7  390.24  4965.9  390.74  5051.6  391.22  5091.6  391.96
  5111.6  391.73  5121.6  391.17  5161.6  392.07  5171.6  392.78  5221.6  393.21
  5301.6  395.31  5351.6  397.50  5381.6  398.11  5421.6  399.98  5438.4  401.65
#Mann=3,-1,0
  4479.9    0.05       0  4961.9    0.04       0  4965.9    0.05       0
Bank Sta=4961.9,4965.9
Exp/Cntr=0.3,0.1

Type RM Length L Ch R = 1,4438,141,141,141
BEGIN DESCRIPTION:
Lacy 130 3454
END DESCRIPTION:
XS GIS Cut Line= 3
      2719928.47      6868049.27      2719670.30      6867662.29
      2719049.23      6867744.60
#Sta/Elev= 30
  4534.1  392.73  4599.9  391.57  4729.1  390.24  4736.4  390.46  4780.1  389.90
  4801.2  390.17  4844.6  389.44  4903.3  389.26  4924.3  388.73  4996.7  388.43
  4996.9  387.93  5000.4  387.93  5000.7  388.43  5054.1  388.96  5074.2  388.83
  5106.6  389.44  5180.0  389.56  5215.5  390.50  5253.3  390.01  5276.0  390.32
  5296.2  389.69  5316.3  390.99  5331.7  391.51  5376.9  392.11  5497.9  395.64
  5508.0  396.48  5538.3  397.55  5608.9  402.52  5619.0  402.70  5625.8  402.10
#Mann=3,-1,0
  4534.1    0.05       0  4996.7    0.04       0  5000.7    0.05       0
Bank Sta=4996.7,5000.7
Exp/Cntr=0.3,0.1

Type RM Length L Ch R = 1,4297,125,125,125
BEGIN DESCRIPTION:
Lacy 130 3453
END DESCRIPTION:
XS GIS Cut Line= 3
      2719958.40      6867772.91      2719723.15      6867535.36
      2719072.98      6867594.76
#Sta/Elev= 30
  4669.9  389.54  4722.4  388.68  4779.0  388.71  4821.4  388.28  4828.5  388.55
  4885.1  388.07  4955.8  388.17  5001.8  387.53  5002.0  387.03  5005.5  387.03
  5005.8  387.53  5111.8  387.63  5182.1  389.08  5229.2  388.94  5252.4  389.23
  5312.6  388.51  5322.7  388.83  5339.4  388.69  5344.4  389.08  5362.9  388.97
  5433.1  390.70  5449.6  391.75  5473.3  392.15  5523.5  394.02  5553.6  395.63
  5593.8  396.92  5623.9  398.78  5634.0  400.14  5644.0  400.88  5657.1  400.88
#Mann=3,-1,0
  4669.9    0.05       0  5001.8    0.04       0  5005.8    0.05       0
Bank Sta=5001.8,5005.8
Exp/Cntr=0.3,0.1

Type RM Length L Ch R = 1,4172,529,529,529
BEGIN DESCRIPTION:
Lacy 130 3445
END DESCRIPTION:
XS GIS Cut Line= 3
      2720000.35      6867564.33      2719775.52      6867428.26
      2719241.21      6867268.08
#Sta/Elev= 30
  4737.3  388.51  4750.8  388.92  4756.7  388.55  4765.8  388.59  4772.2  388.97
  4793.5  388.64  4800.8  388.00  4824.2  387.50  4909.9  387.52  4952.8  387.12
  5020.5  387.35  5049.8  386.96  5050.0  386.46  5053.5  386.46  5053.8  386.96
  5062.2  387.22  5104.0  386.98  5177.0  387.24  5182.2  386.97  5260.6  387.19
  5281.4  387.50  5291.9  387.12  5302.4  387.54  5358.0  387.93  5417.2  389.61
  5424.1  390.14  5438.1  390.37  5457.2  391.30  5490.3  392.27  5557.9  394.97
#Mann=3,-1,0
  4737.3    0.05       0  5049.8    0.04       0  5053.8    0.05       0
Bank Sta=5049.8,5053.8
Exp/Cntr=0.3,0.1

Type RM Length L Ch R = 1,3643,269,269,269
BEGIN DESCRIPTION:
Lacy 130 3444
END DESCRIPTION:
XS GIS Cut Line= 3
      2720097.58      6867266.13      2719774.28      6866950.93
      2719356.18      6866917.01
#Sta/Elev= 30
  4551.3  387.04  4598.4  386.49  4683.3  384.66  4725.7  384.64  4761.2  385.28
  4782.3  385.13  4789.5  385.54  5029.2  384.14  5029.4  383.64  5032.9  383.64
  5033.2  384.14  5060.0  384.56  5065.1  384.97  5081.4  384.64  5121.5  385.23
  5141.6  387.24  5151.6  387.39  5171.7  388.79  5192.1  389.60  5221.8  391.84
  5231.9  391.89  5261.9  393.57  5292.0  394.58  5309.1  393.99  5322.1  396.34
  5332.2  396.86  5342.2  396.97  5352.2  396.43  5382.3  396.90  5422.3  399.27
#Mann=3,-1,0
  4551.3    0.05       0  5029.2    0.04       0  5033.2    0.05       0
Bank Sta=5029.2,5033.2
Exp/Cntr=0.3,0.1

Type RM Length L Ch R = 1,3374,482,482,482
BEGIN DESCRIPTION:
Lacy 130 3446
END DESCRIPTION:
XS GIS Cut Line= 3
      2720179.85      6867083.90      2719865.93      6866718.04
      2719380.03      6866723.70
#Sta/Elev= 30
  4518.6  385.67  4601.5  384.94  4691.7  382.33  4692.0  381.83  4695.5  381.83
  4695.7  382.33  4757.8  382.90  4764.4  383.29  4807.2  382.54  4813.7  382.85
  4878.2  382.52  4905.9  383.23  4934.5  382.88  4970.4  383.09  4991.5  382.39
  4996.8  382.80  5020.6  382.41  5100.6  385.35  5130.6  385.49  5170.6  384.28
  5210.6  384.64  5370.6  394.28  5380.6  396.29  5400.6  396.90  5410.6  395.65
  5420.6  395.82  5430.6  396.22  5440.6  397.49  5450.6  398.11  5486.6  399.16
#Mann=3,-1,0
  4518.6    0.05       0  4691.7    0.04       0  4695.7    0.05       0
Bank Sta=4691.7,4695.7
Exp/Cntr=0.3,0.1

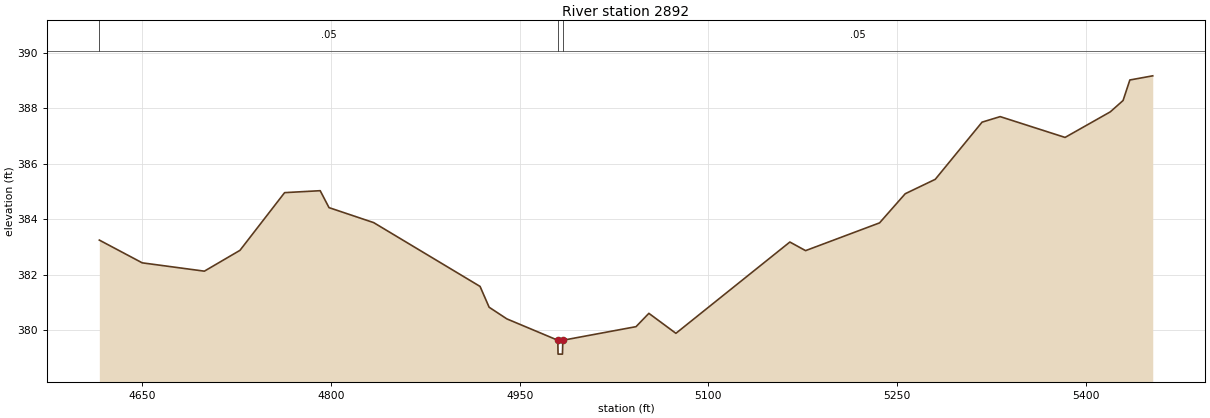
Type RM Length L Ch R = 1,2892,0,0,0
BEGIN DESCRIPTION:
Lacy 130 1209
END DESCRIPTION:
XS GIS Cut Line= 3
      2720253.00      6866542.19      2719975.15      6866273.04
      2719532.84      6866359.42
#Sta/Elev= 30
  4615.8  383.25  4649.9  382.43  4699.3  382.13  4727.6  382.88  4763.1  384.96
  4791.4  385.03  4798.4  384.42  4833.9  383.88  4918.5  381.58  4925.7  380.83
  4939.8  380.41  4980.3  379.64  4980.5  379.14  4984.0  379.14  4984.3  379.64
  5042.5  380.13  5052.7  380.61  5074.2  379.89  5164.8  383.18  5177.3  382.87
  5236.1  383.87  5256.5  384.92  5280.4  385.44  5317.6  387.50  5332.0  387.70
  5383.6  386.95  5419.5  387.87  5429.7  388.28  5435.1  389.02  5453.3  389.17
#Mann=3,-1,0
  4615.8    0.05       0  4980.3    0.04       0  4984.3    0.05       0
Bank Sta=4980.3,4984.3
Exp/Cntr=0.3,0.1

Chan Stop Cuts=-1