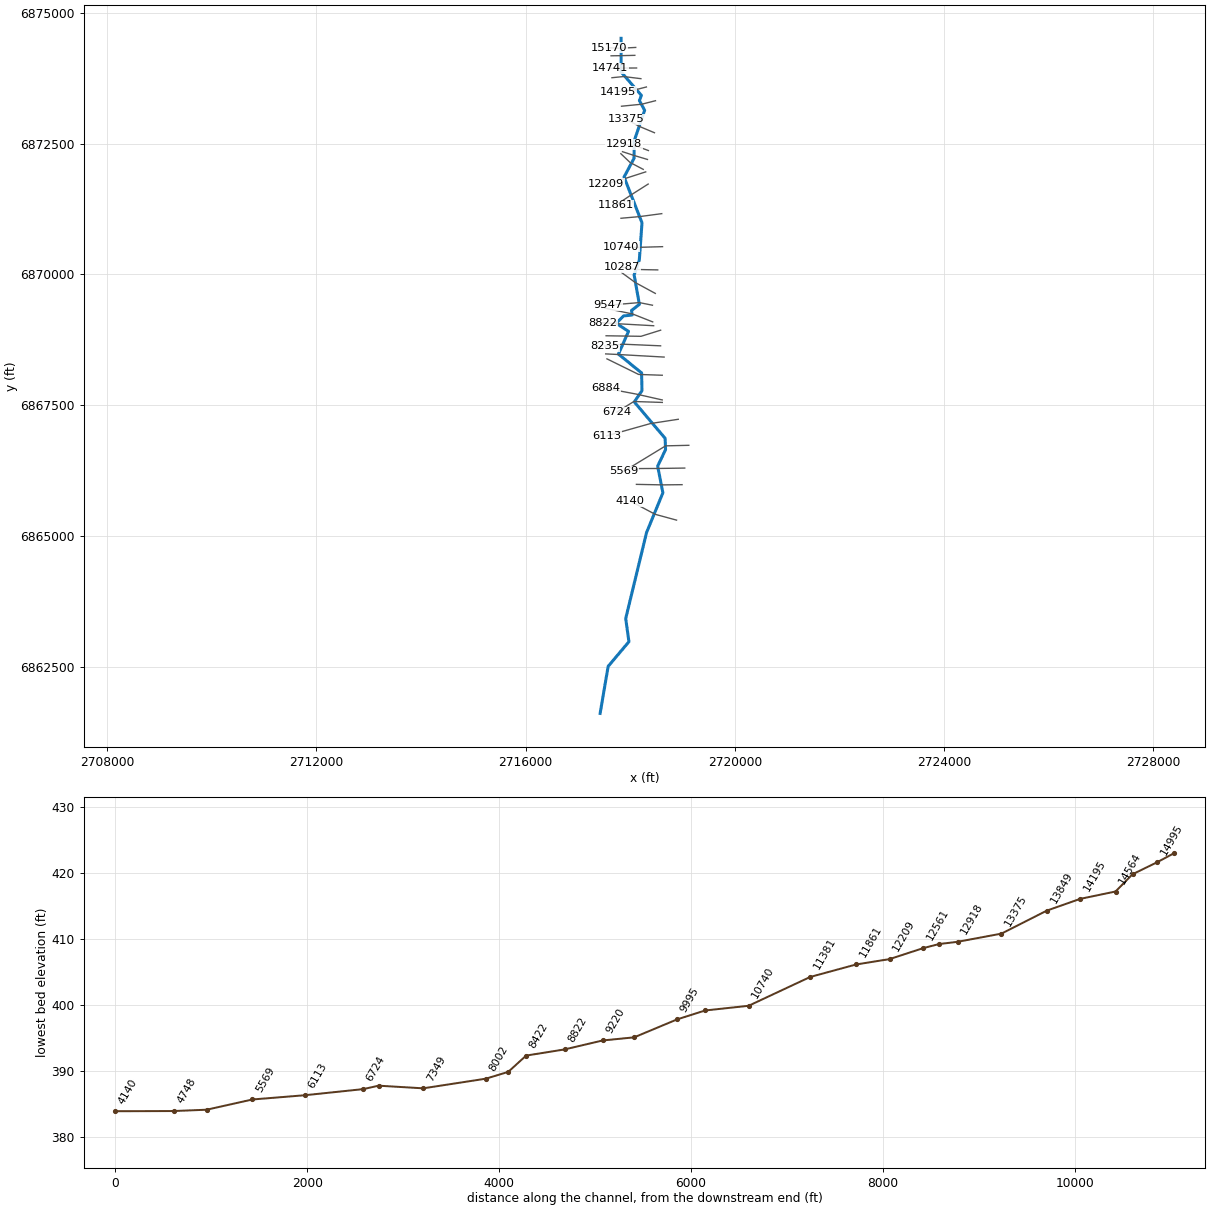
--- Lacy 131.prj (project) ---

Proj Title=Lacy 131 Base Level Engineering
Current Plan=p01
Default Exp/Contr=0.3,0.1
English Units
Geom File=g01
Flow File=f01
Plan File=p01
BEGIN DESCRIPTION:
Lacy 131
END DESCRIPTION:

--- Lacy 131.p01 (plan) ---

Plan Title=Multiple Run
Short Identifier=Multiple
Geom File=g01
Flow File=f01
Subcritical Flow
K Sum by GR= 0
Std Step Tol= 0.01
Critical Tol= 0.01
Num of Std Step Trials= 20
Max Error Tol= 0.3
Flow Tol Ratio= 0.001
Split Flow NTrial= 30
Split Flow Tol= 0.02
Split Flow Ratio= 0.02
Log Output Level= 0
Friction Slope Method= 1
Unsteady Friction Slope Method= 2
Unsteady Bridges Friction Slope Method= 1
Parabolic Critical Depth
Global Vel Dist=  1 , 1 , 1
Global Log Level= 0
CheckData=True
Encroach Param= -1, 0, 0, 0
BEGIN DESCRIPTION:
Multiple Run
END DESCRIPTION:

--- Lacy 131.f01 (steady flow) ---

Flow Title=Multiple
Number of Profiles=7
Profile Names=10-year,25-year,50-year,1pct_min,100-year,1pct_plu,500-year
River Rch & RM= Lacy 131,Reach-1,15170
     302     384     446     258     516    1029     685
River Rch & RM= Lacy 131,Reach-1,12209
     451     588     695     408     814    1625    1116
River Rch & RM= Lacy 131,Reach-1,9547
     631     841    1009     601    1199    2392    1690
River Rch & RM= Lacy 131,Reach-1,6884
     732     985    1189     711    1419    2832    2021
River Rch & RM= Lacy 131,Reach-1,6724
     858    1156    1398     837    1669    3330    2379
Boundary for River Rch & Prof#=Lacy 131,Reach-1,1
Up Type=0
Dn Type=3
Dn Slope=0.005
Boundary for River Rch & Prof#=Lacy 131,Reach-1,2
Up Type=0
Dn Type=3
Dn Slope=0.005
Boundary for River Rch & Prof#=Lacy 131,Reach-1,3
Up Type=0
Dn Type=3
Dn Slope=0.005
Boundary for River Rch & Prof#=Lacy 131,Reach-1,4
Up Type=0
Dn Type=3
Dn Slope=0.005
Boundary for River Rch & Prof#=Lacy 131,Reach-1,5
Up Type=0
Dn Type=3
Dn Slope=0.005
Boundary for River Rch & Prof#=Lacy 131,Reach-1,6
Up Type=0
Dn Type=3
Dn Slope=0.005
Boundary for River Rch & Prof#=Lacy 131,Reach-1,7
Up Type=0
Dn Type=3
Dn Slope=0.005

--- Lacy 131.g01 (geometry) ---

Geom Title=Existing Conditions

River Reach=Lacy 131,Reach-1
Reach XY= 30
      2717826.00      6874511.00      2717828.14      6873866.96
      2718214.87      6873421.04      2718176.80      6873321.70
      2718276.24      6873136.08      2718076.65      6872550.36
      2718073.93      6872216.86      2717883.51      6871861.01
      2718226.20      6870986.08      2718174.79      6870271.51
      2718075.72      6869990.82      2718176.11      6869426.21
      2718026.00      6869311.00      2718040.06      6869224.28
      2717873.55      6869205.53      2717733.58      6869064.32
      2717968.78      6868911.34      2717776.24      6868476.22
      2718218.26      6868116.99      2718225.93      6867779.46
      2718079.29      6867562.36      2718668.19      6866867.19
      2718676.46      6866650.81      2718525.59      6866336.00
      2718625.48      6865826.22      2718313.59      6865067.25
      2717914.91      6863423.67      2717976.30      6862981.16
      2717579.54      6862509.54      2717426.00      6861611.00

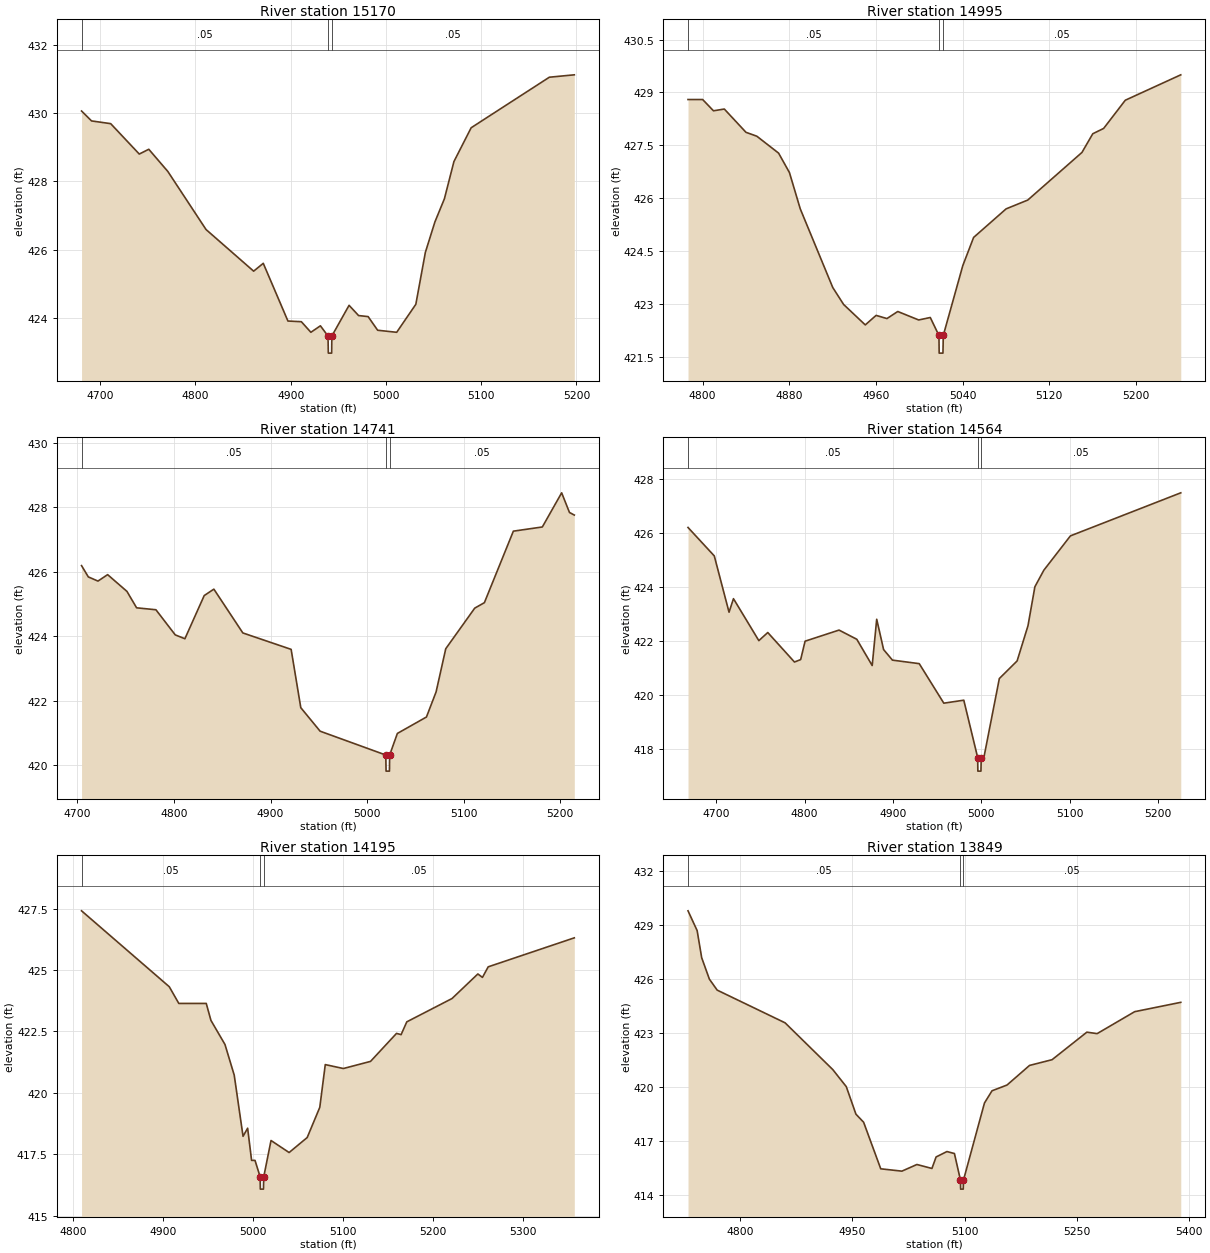
Type RM Length L Ch R = 1,15170,175,175,175
BEGIN DESCRIPTION:
Lacy 131 1206
END DESCRIPTION:
XS GIS Cut Line= 3
      2718106.52      6874337.00      2717787.32      6874320.85
      2717589.83      6874331.87
#Sta/Elev= 30
  4680.4  430.06  4690.9  429.77  4711.0  429.69  4741.0  428.80  4751.0  428.94
  4771.0  428.29  4811.1  426.59  4861.1  425.37  4871.2  425.60  4897.1  423.91
  4911.2  423.89  4921.2  423.58  4931.2  423.77  4939.2  423.47  4939.5  422.97
  4943.0  422.97  4943.2  423.47  4961.3  424.37  4971.3  424.07  4981.3  424.04
  4991.3  423.64  5011.3  423.58  5031.4  424.40  5041.4  425.92  5051.4  426.81
  5061.4  427.49  5071.4  428.58  5089.5  429.57  5171.6  431.05  5197.8  431.12
#Mann=3,-1,0
  4680.4    0.05       0  4939.2    0.04       0  4943.2    0.05       0
Bank Sta=4939.2,4943.2
Exp/Cntr=0.3,0.1

Type RM Length L Ch R = 1,14995,254,254,254
BEGIN DESCRIPTION:
Lacy 131 1205
END DESCRIPTION:
XS GIS Cut Line= 3
      2718089.53      6874185.94      2717872.43      6874180.92
      2717634.82      6874177.15
#Sta/Elev= 30
  4786.6  428.80  4800.1  428.80  4810.1  428.48  4820.1  428.53  4840.1  427.87
  4850.1  427.76  4870.2  427.28  4880.2  426.73  4890.2  425.70  4920.2  423.47
  4930.2  422.99  4950.2  422.41  4960.2  422.68  4970.2  422.59  4980.2  422.79
  4999.5  422.55  5010.2  422.62  5018.2  422.11  5018.4  421.61  5021.9  421.61
  5022.2  422.11  5040.2  424.09  5050.2  424.89  5080.2  425.70  5100.2  425.95
  5150.2  427.30  5160.2  427.83  5170.2  427.98  5190.2  428.78  5241.4  429.50
#Mann=3,-1,0
  4786.6    0.05       0  5018.2    0.04       0  5022.2    0.05       0
Bank Sta=5018.2,5022.2
Exp/Cntr=0.3,0.1

Type RM Length L Ch R = 1,14741,177,177,177
BEGIN DESCRIPTION:
Lacy 131 1203
END DESCRIPTION:
XS GIS Cut Line= 3
      2718123.02      6873944.27      2717828.05      6873942.64
      2717612.93      6873935.94
#Sta/Elev= 30
  4704.3  426.19  4711.3  425.84  4721.3  425.71  4731.3  425.91  4751.3  425.39
  4761.3  424.88  4781.3  424.82  4801.3  424.04  4811.3  423.92  4831.3  425.26
  4841.3  425.46  4871.3  424.10  4921.3  423.59  4931.3  421.78  4951.3  421.05
  5019.3  420.31  5019.6  419.81  5023.1  419.81  5023.3  420.31  5031.3  420.98
  5061.4  421.49  5071.4  422.27  5081.4  423.61  5111.4  424.87  5121.4  425.04
  5151.4  427.26  5181.4  427.39  5201.4  428.45  5209.5  427.84  5214.5  427.76
#Mann=3,-1,0
  4704.3    0.05       0  5019.3    0.04       0  5023.3    0.05       0
Bank Sta=5019.3,5023.3
Exp/Cntr=0.3,0.1

Type RM Length L Ch R = 1,14564,369,369,369
BEGIN DESCRIPTION:
Lacy 131 1204
END DESCRIPTION:
XS GIS Cut Line= 3
      2718205.49      6873740.10      2717875.82      6873780.96
      2717651.84      6873758.46
#Sta/Elev= 30
  4668.2  426.20  4697.9  425.15  4714.6  423.07  4719.6  423.57  4748.3  422.02
  4758.4  422.32  4788.6  421.23  4795.6  421.32  4800.6  422.00  4839.0  422.41
  4859.1  422.07  4876.5  421.10  4881.6  422.81  4889.4  421.69  4899.4  421.30
  4929.7  421.17  4957.5  419.71  4980.1  419.82  4995.8  417.70  4996.0  417.20
  4999.5  417.20  4999.8  417.70  5002.8  417.70  5020.3  420.62  5040.4  421.27
  5052.7  422.57  5060.5  424.01  5070.6  424.62  5100.7  425.89  5225.5  427.48
#Mann=3,-1,0
  4668.2    0.05       0  4995.8    0.04       0  4999.8    0.05       0
Bank Sta=4995.8,4999.8
Exp/Cntr=0.3,0.1

Type RM Length L Ch R = 1,14195,346,346,346
BEGIN DESCRIPTION:
Lacy 131 1202
END DESCRIPTION:
XS GIS Cut Line= 3
      2718310.47      6873581.49      2718123.68      6873533.86
      2717770.93      6873494.52
#Sta/Elev= 30
  4809.5  427.41  4907.0  424.32  4917.6  423.64  4948.1  423.64  4953.3  422.95
  4968.9  421.97  4979.2  420.72  4989.0  418.23  4994.1  418.56  4998.5  417.25
  5002.3  417.25  5008.0  416.58  5008.2  416.08  5011.7  416.08  5012.0  416.58
  5020.1  418.06  5040.2  417.57  5060.3  418.18  5074.3  419.41  5080.4  421.15
  5100.5  420.99  5130.7  421.28  5159.6  422.42  5164.7  422.37  5171.0  422.89
  5221.3  423.84  5250.0  424.84  5255.1  424.70  5261.5  425.13  5357.2  426.31
#Mann=3,-1,0
  4809.5    0.05       0  5008.0    0.04       0  5012.0    0.05       0
Bank Sta=5008,5012
Exp/Cntr=0.3,0.1

Type RM Length L Ch R = 1,13849,474,474,474
BEGIN DESCRIPTION:
Lacy 131 1201
END DESCRIPTION:
XS GIS Cut Line= 3
      2718483.77      6873318.79      2718221.20      6873252.11
      2717834.60      6873213.71
#Sta/Elev= 30
  4730.0  429.79  4742.2  428.69  4748.3  427.18  4758.6  425.99  4769.0  425.38
  4859.9  423.56  4923.7  420.96  4941.8  420.01  4954.7  418.48  4965.0  418.03
  4987.9  415.44  5016.2  415.31  5036.3  415.68  5056.4  415.46  5062.0  416.10
  5076.5  416.40  5086.5  416.29  5094.6  414.81  5094.8  414.31  5098.3  414.31
  5098.6  414.81  5126.7  419.10  5136.8  419.78  5156.9  420.10  5187.0  421.19
  5217.2  421.51  5263.7  423.04  5277.5  422.96  5327.7  424.18  5389.4  424.70
#Mann=3,-1,0
  4730.0    0.05       0  5094.6    0.04       0  5098.6    0.05       0
Bank Sta=5094.6,5098.6
Exp/Cntr=0.3,0.1

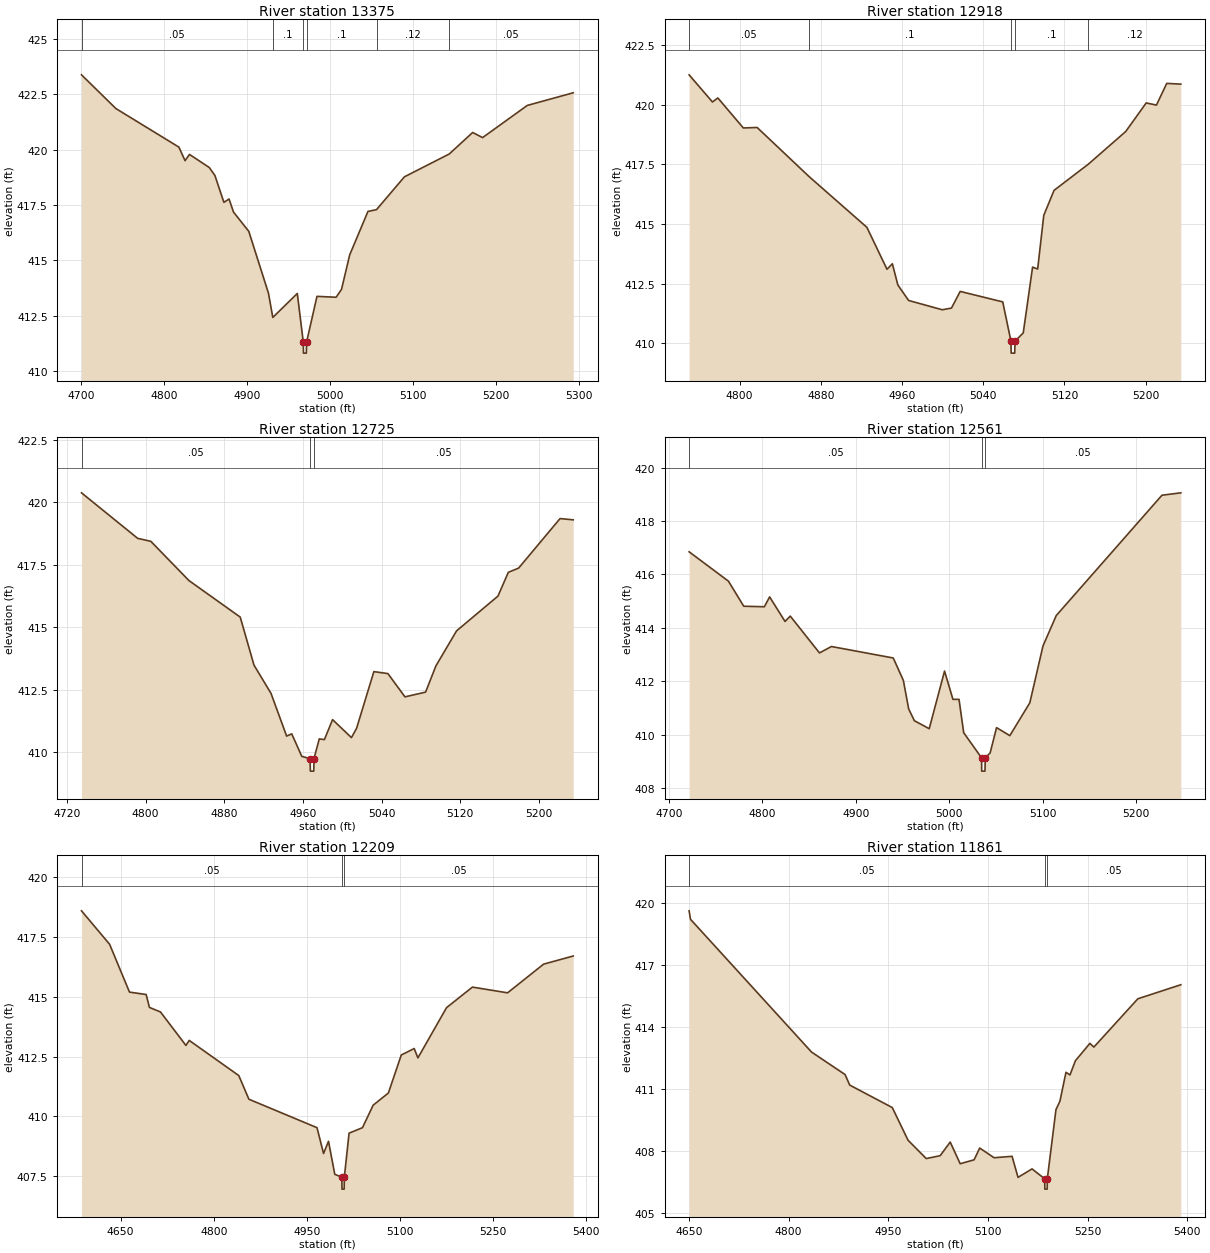
Type RM Length L Ch R = 1,13375,457,457,457
BEGIN DESCRIPTION:
Lacy 131 1200
END DESCRIPTION:
XS GIS Cut Line= 3
      2718464.19      6872707.05      2718190.06      6872821.91
      2717929.75      6872960.68
#Sta/Elev= 30
  4700.4  423.37  4741.8  421.85  4817.7  420.11  4825.1  419.50  4830.5  419.78
  4854.3  419.19  4861.1  418.83  4871.9  417.62  4878.1  417.77  4883.5  417.18
  4901.9  416.31  4925.6  413.52  4930.8  412.43  4960.3  413.51  4967.5  411.32
  4967.7  410.82  4971.2  410.82  4971.5  411.32  4984.0  413.38  5007.1  413.34
  5013.6  413.70  5023.4  415.25  5045.4  417.21  5055.7  417.29  5089.3  418.77
  5143.3  419.80  5171.5  420.77  5183.5  420.54  5237.3  421.99  5292.6  422.56
#Mann=6,-1,0
  4700.4    0.05       0  4930.8     0.1       0  4967.5    0.07       0
  4971.5     0.1       0  5055.7    0.12       0  5143.3    0.05       0
Bank Sta=4967.5,4971.5
Exp/Cntr=0.3,0.1

Type RM Length L Ch R = 1,12918,193,193,193
BEGIN DESCRIPTION:
Lacy 131 1186
END DESCRIPTION:
XS GIS Cut Line= 3
      2718348.84      6872366.66      2718114.95      6872453.04
      2717882.27      6872485.76
#Sta/Elev= 30
  4750.3  421.26  4773.3  420.12  4778.6  420.29  4803.7  419.03  4817.3  419.05
  4868.7  416.98  4925.4  414.86  4945.2  413.10  4950.5  413.33  4955.9  412.44
  4966.5  411.79  4999.6  411.40  5008.7  411.47  5017.3  412.17  5059.2  411.73
  5067.3  410.08  5067.5  409.58  5071.0  409.58  5071.3  410.08  5079.4  410.43
  5088.6  413.19  5093.6  413.11  5099.6  415.36  5109.7  416.41  5143.5  417.51
  5180.3  418.88  5200.5  420.08  5210.6  419.99  5220.7  420.90  5234.6  420.87
#Mann=5,-1,0
  4750.3    0.05       0  4868.7     0.1       0  5067.3    0.07       0
  5071.3     0.1       0  5143.5    0.12       0
Bank Sta=5067.3,5071.3
Exp/Cntr=0.3,0.1

Type RM Length L Ch R = 1,12725,164,164,164
BEGIN DESCRIPTION:
Lacy 131 1185
END DESCRIPTION:
XS GIS Cut Line= 3
      2718330.74      6872196.54      2718076.58      6872272.04
      2717853.27      6872344.81
#Sta/Elev= 30
  4734.9  420.37  4792.0  418.55  4805.4  418.43  4844.2  416.86  4896.3  415.40
  4910.3  413.48  4927.6  412.35  4943.5  410.64  4948.7  410.73  4958.9  409.83
  4967.3  409.74  4967.6  409.24  4971.1  409.24  4971.3  409.74  4976.7  410.53
  4981.9  410.50  4990.2  411.30  5009.4  410.58  5014.6  410.95  5032.2  413.22
  5046.5  413.14  5063.8  412.21  5084.8  412.40  5095.3  413.45  5116.3  414.85
  5158.4  416.24  5168.9  417.19  5179.4  417.36  5221.5  419.34  5234.9  419.29
#Mann=3,-1,0
  4734.9    0.05       0  4967.3    0.04       0  4971.3    0.05       0
Bank Sta=4967.3,4971.3
Exp/Cntr=0.3,0.1

Type RM Length L Ch R = 1,12561,352,352,352
BEGIN DESCRIPTION:
Lacy 131 1184
END DESCRIPTION:
XS GIS Cut Line= 3
      2718249.67      6872007.19      2717997.84      6872139.04
      2717822.50      6872306.19
#Sta/Elev= 30
  4721.5  416.85  4763.6  415.75  4780.0  414.81  4802.1  414.79  4807.7  415.16
  4824.2  414.24  4829.8  414.44  4861.1  413.06  4873.9  413.30  4940.1  412.87
  4950.9  412.03  4956.6  410.96  4962.7  410.52  4978.6  410.22  4995.0  412.38
  5004.0  411.32  5010.5  411.32  5015.5  410.07  5034.6  409.13  5034.8  408.63
  5038.3  408.63  5038.6  409.13  5043.8  409.31  5050.7  410.26  5064.9  409.96
  5086.3  411.19  5100.4  413.32  5114.6  414.46  5227.8  418.97  5248.0  419.06
#Mann=3,-1,0
  4721.5    0.05       0  5034.6    0.04       0  5038.6    0.05       0
Bank Sta=5034.6,5038.6
Exp/Cntr=0.3,0.1

Type RM Length L Ch R = 1,12209,348,348,348
BEGIN DESCRIPTION:
Lacy 131 1183
END DESCRIPTION:
XS GIS Cut Line= 3
      2718297.03      6871958.95      2717906.70      6871833.08
      2717540.17      6871726.27
#Sta/Elev= 30
  4587.0  418.60  4632.3  417.20  4664.3  415.20  4691.1  415.10  4696.4  414.56
  4714.2  414.37  4755.2  412.97  4760.5  413.18  4840.3  411.71  4856.6  410.72
  4966.3  409.53  4976.8  408.45  4984.8  408.96  4994.9  407.58  5006.3  407.46
  5006.5  406.96  5010.0  406.96  5010.3  407.46  5017.9  409.30  5039.5  409.53
  5056.7  410.47  5081.2  410.98  5102.0  412.57  5122.8  412.84  5128.8  412.45
  5174.9  414.55  5216.6  415.41  5273.2  415.17  5331.2  416.37  5378.9  416.71
#Mann=3,-1,0
  4587.0    0.05       0  5006.3    0.04       0  5010.3    0.05       0
Bank Sta=5006.3,5010.3
Exp/Cntr=0.3,0.1

Type RM Length L Ch R = 1,11861,480,480,480
BEGIN DESCRIPTION:
Lacy 131 1182
END DESCRIPTION:
XS GIS Cut Line= 3
      2718344.23      6871726.25      2718051.33      6871540.22
      2717723.94      6871322.23
#Sta/Elev= 30
  4650.1  419.63  4652.2  419.22  4834.4  412.79  4884.9  411.70  4891.9  411.19
  4956.0  410.10  4979.7  408.52  5007.1  407.63  5028.1  407.77  5043.2  408.43
  5058.2  407.38  5079.2  407.57  5087.6  408.14  5109.3  407.67  5136.3  407.74
  5145.3  406.72  5166.4  407.13  5185.4  406.65  5185.7  406.15  5189.2  406.15
  5189.4  406.65  5202.4  410.00  5208.4  410.41  5217.5  411.81  5223.5  411.68
  5231.7  412.37  5253.5  413.21  5259.5  413.03  5325.7  415.37  5390.4  416.05
#Mann=3,-1,0
  4650.1    0.05       0  5185.4    0.04       0  5189.4    0.05       0
Bank Sta=5185.4,5189.4
Exp/Cntr=0.3,0.1

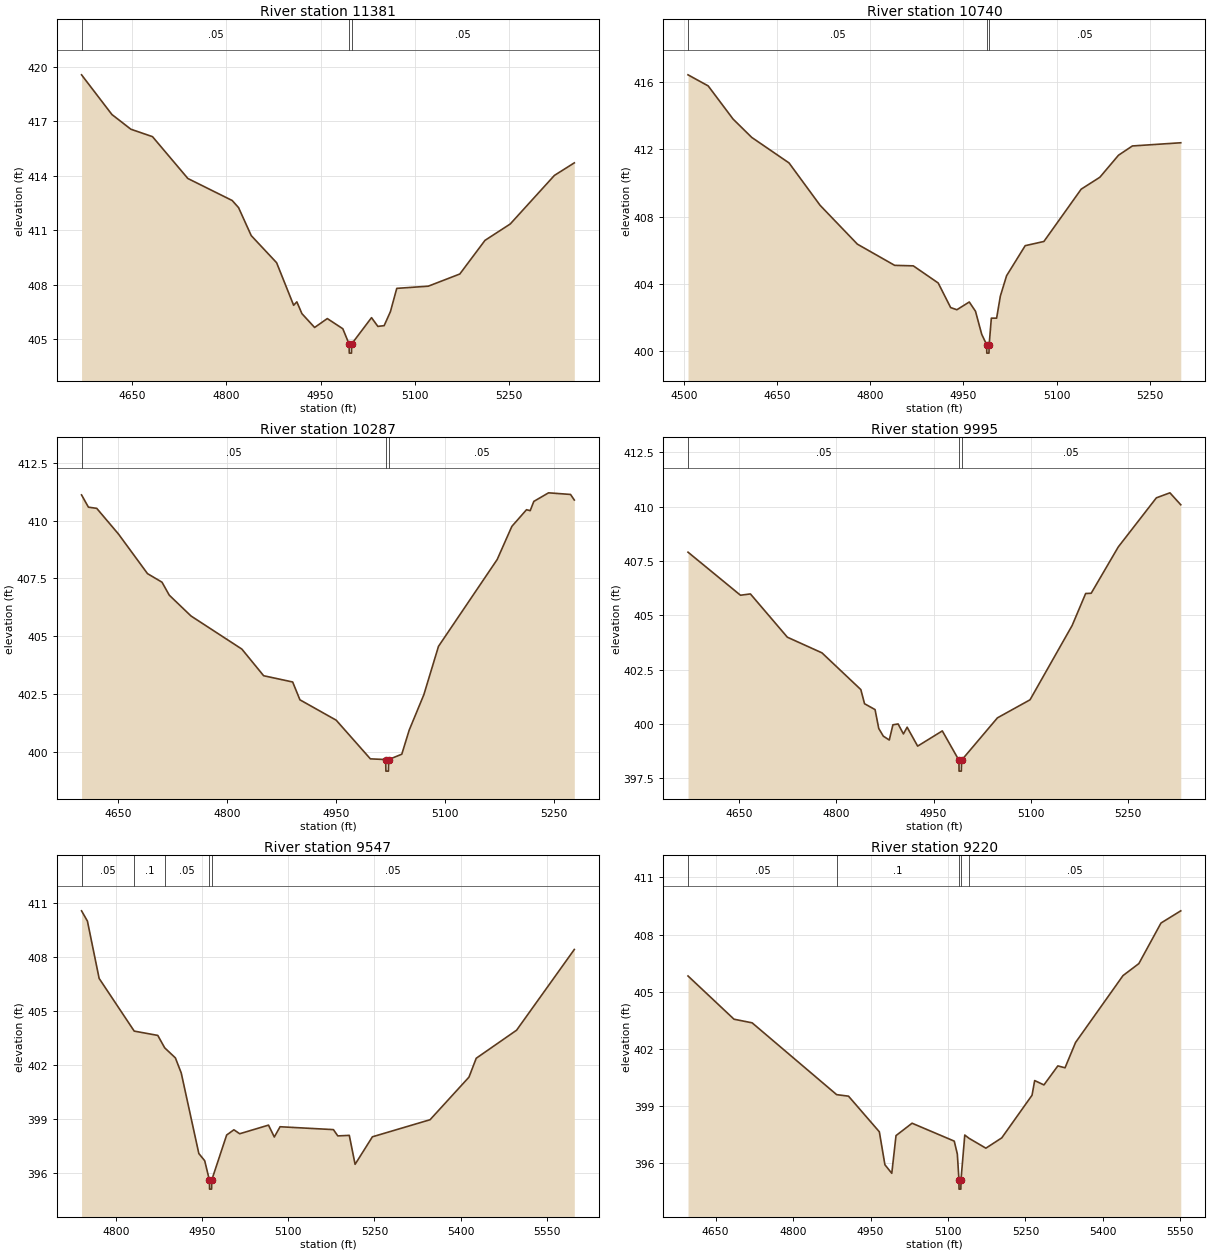
Type RM Length L Ch R = 1,11381,641,641,641
BEGIN DESCRIPTION:
Lacy 131 1181
END DESCRIPTION:
XS GIS Cut Line= 3
      2718603.85      6871160.77      2718178.10      6871104.16
      2717824.40      6871072.59
#Sta/Elev= 30
  4569.4  419.55  4617.7  417.37  4647.9  416.56  4682.4  416.15  4738.7  413.85
  4809.3  412.64  4819.4  412.25  4839.6  410.71  4880.0  409.22  4907.1  406.88
  4912.2  407.07  4920.3  406.42  4940.5  405.66  4960.7  406.15  4985.4  405.59
  4995.4  404.75  4995.7  404.25  4999.2  404.25  4999.4  404.75  5031.1  406.20
  5041.2  405.72  5051.2  405.76  5061.2  406.53  5071.3  407.81  5121.5  407.93
  5171.7  408.60  5211.8  410.45  5252.0  411.35  5322.3  414.02  5354.0  414.71
#Mann=3,-1,0
  4569.4    0.05       0  4995.4    0.04       0  4999.4    0.05       0
Bank Sta=4995.4,4999.4
Exp/Cntr=0.3,0.1

Type RM Length L Ch R = 1,10740,453,453,453
BEGIN DESCRIPTION:
Lacy 131 1180
END DESCRIPTION:
XS GIS Cut Line= 3
      2718618.49      6870529.89      2718125.67      6870515.88
      2717825.91      6870529.72
#Sta/Elev= 30
  4506.9  416.44  4539.4  415.78  4579.4  413.81  4609.4  412.72  4669.5  411.20
  4719.5  408.68  4779.5  406.37  4839.5  405.11  4869.5  405.08  4909.6  404.06
  4929.6  402.60  4939.6  402.47  4959.6  402.93  4969.6  402.38  4979.6  401.01
  4987.6  400.39  4987.8  399.89  4991.3  399.89  4991.6  400.39  4995.1  401.97
  5003.6  401.97  5009.6  403.28  5019.6  404.49  5049.6  406.28  5079.7  406.53
  5139.7  409.64  5169.8  410.35  5199.8  411.66  5222.1  412.21  5300.0  412.40
#Mann=3,-1,0
  4506.9    0.05       0  4987.6    0.04       0  4991.6    0.05       0
Bank Sta=4987.6,4991.6
Exp/Cntr=0.3,0.1

Type RM Length L Ch R = 1,10287,292,292,292
BEGIN DESCRIPTION:
Lacy 131 1167
END DESCRIPTION:
XS GIS Cut Line= 3
      2718526.91      6870085.73      2718126.82      6870093.79
      2717850.85      6870134.99
#Sta/Elev= 30
  4599.3  411.11  4608.8  410.58  4620.2  410.53  4650.2  409.42  4690.2  407.71
  4710.2  407.34  4720.2  406.78  4750.2  405.88  4820.3  404.45  4850.3  403.30
  4890.3  403.03  4900.3  402.26  4950.3  401.38  4997.4  399.71  5018.5  399.68
  5018.8  399.18  5022.3  399.18  5022.5  399.68  5040.7  399.91  5050.9  400.95
  5071.1  402.48  5091.3  404.57  5172.2  408.32  5192.4  409.75  5212.6  410.47
  5217.7  410.43  5222.7  410.83  5243.0  411.20  5273.3  411.13  5278.5  410.89
#Mann=3,-1,0
  4599.3    0.05       0  5018.5    0.04       0  5022.5    0.05       0
Bank Sta=5018.5,5022.5
Exp/Cntr=0.3,0.1

Type RM Length L Ch R = 1,9995,448,448,448
BEGIN DESCRIPTION:
Lacy 131 1166
END DESCRIPTION:
XS GIS Cut Line= 3
      2718480.45      6869636.59      2718097.74      6869844.17
      2717836.46      6870035.12
#Sta/Elev= 30
  4571.8  407.90  4652.6  405.92  4667.9  405.98  4724.8  403.99  4778.1  403.27
  4838.0  401.58  4843.7  400.93  4859.9  400.66  4865.6  399.79  4872.6  399.44
  4881.8  399.26  4887.4  399.96  4895.4  400.00  4903.6  399.54  4909.3  399.85
  4925.5  398.98  4963.5  399.68  4989.1  398.33  4989.3  397.83  4992.8  397.83
  4993.1  398.33  5048.4  400.28  5098.6  401.11  5163.5  404.53  5184.3  406.00
  5192.8  406.01  5234.5  408.14  5293.2  410.40  5314.1  410.63  5330.8  410.08
#Mann=3,-1,0
  4571.8    0.05       0  4989.1    0.04       0  4993.1    0.05       0
Bank Sta=4989.1,4993.1
Exp/Cntr=0.3,0.1

Type RM Length L Ch R = 1,9547,327,327,327
BEGIN DESCRIPTION:
Lacy 131 45
END DESCRIPTION:
XS GIS Cut Line= 3
      2718426.04      6869410.99      2718176.00      6869461.00
      2717575.98      6869411.00
#Sta/Elev= 30
  4740.5  410.59  4750.7  410.02  4771.1  406.83  4832.1  403.90  4873.1  403.66
  4885.1  402.97  4903.7  402.41  4913.9  401.57  4944.5  397.09  4954.7  396.69
  4962.9  395.61  4963.2  395.11  4966.7  395.11  4966.9  395.61  4992.9  398.12
  5005.5  398.41  5015.6  398.19  5065.7  398.67  5075.8  398.01  5085.8  398.58
  5178.6  398.42  5186.2  398.07  5206.2  398.10  5216.3  396.49  5246.4  398.02
  5346.7  398.97  5414.4  401.34  5427.0  402.39  5497.2  403.95  5597.6  408.44
#Mann=5,-1,0
  4740.5    0.05       0  4832.1     0.1       0  4885.1    0.05       0
  4962.9    0.04       0  4966.9    0.05       0
Bank Sta=4962.9,4966.9
Exp/Cntr=0.3,0.1

Type RM Length L Ch R = 1,9220,398,398,398
BEGIN DESCRIPTION:
Lacy 131 1165
END DESCRIPTION:
XS GIS Cut Line= 3
      2718430.73      6869092.07      2718047.44      6869243.39
      2717516.51      6869354.48
#Sta/Elev= 30
  4596.5  405.83  4685.6  403.56  4720.7  403.37  4884.4  399.60  4907.4  399.52
  4967.1  397.65  4977.9  395.92  4991.2  395.47  4999.4  397.45  5030.5  398.10
  5112.2  397.16  5118.2  396.48  5121.3  395.14  5121.5  394.64  5125.0  394.64
  5125.3  395.14  5132.6  397.48  5140.7  397.31  5173.5  396.79  5204.2  397.33
  5262.9  399.57  5268.0  400.34  5285.9  400.11  5312.9  401.11  5326.8  401.01
  5347.2  402.34  5439.1  405.85  5469.8  406.48  5512.7  408.61  5551.0  409.25
#Mann=5,-1,0
  4596.5    0.05       0  4884.4     0.1       0  5121.3    0.07       0
  5125.3     0.1       0  5140.7    0.05       0
Bank Sta=5121.3,5125.3
Exp/Cntr=0.3,0.1

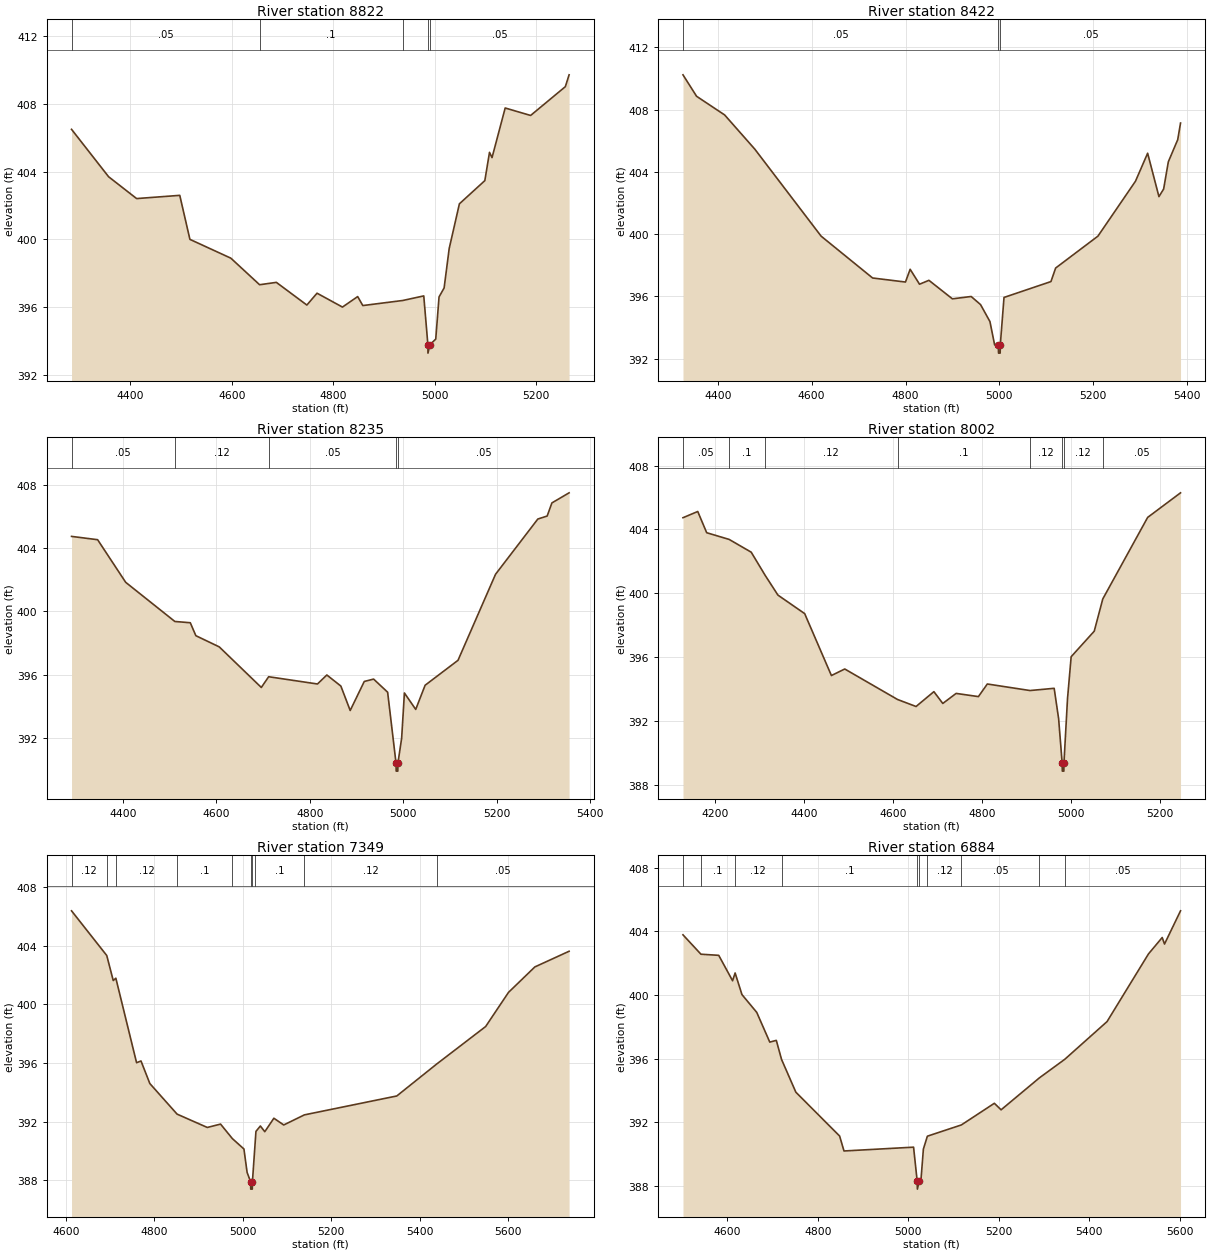
Type RM Length L Ch R = 1,8822,400,400,400
BEGIN DESCRIPTION:
Lacy 131 1164
END DESCRIPTION:
XS GIS Cut Line= 3
      2718448.88      6869018.90      2717732.48      6869058.59
      2717470.38      6869076.28
#Sta/Elev= 30
  4284.4  406.50  4357.4  403.70  4412.6  402.41  4497.6  402.60  4517.6  400.00
  4598.2  398.89  4654.9  397.32  4687.9  397.46  4748.0  396.12  4768.0  396.82
  4818.1  396.00  4848.1  396.62  4858.2  396.09  4937.0  396.39  4978.3  396.66
  4986.4  393.78  4986.6  393.28  4990.4  393.78  5001.9  394.11  5008.4  396.60
  5018.4  397.13  5028.4  399.46  5048.5  402.10  5098.6  403.47  5107.8  405.14
  5112.8  404.83  5138.7  407.76  5188.8  407.32  5257.2  409.02  5264.6  409.72
#Mann=5,-1,0
  4284.4    0.05       0  4654.9     0.1       0  4937.0    0.05       0
  4986.4    0.05       0  4990.4    0.05       0
Bank Sta=4986.4,4990.4
Exp/Cntr=0.3,0.1

Type RM Length L Ch R = 1,8422,187,187,187
BEGIN DESCRIPTION:
Lacy 131 1137
END DESCRIPTION:
XS GIS Cut Line= 3
      2718582.20      6868933.51      2718206.98      6868816.59
      2717539.98      6868827.09
#Sta/Elev= 30
  4325.8  410.24  4354.8  408.86  4414.6  407.66  4478.9  405.46  4620.1  399.87
  4729.8  397.18  4799.8  396.92  4809.8  397.74  4829.8  396.78  4849.8  397.03
  4899.8  395.84  4939.8  395.99  4959.8  395.47  4979.8  394.38  4989.8  392.88
  4997.8  392.85  4998.1  392.35  5001.6  392.35  5001.8  392.85  5009.8  395.93
  5109.8  396.95  5119.8  397.82  5209.9  399.87  5289.9  403.40  5315.8  405.20
  5339.9  402.41  5349.9  402.90  5359.9  404.65  5379.9  406.07  5385.9  407.14
#Mann=3,-1,0
  4325.8    0.05       0  4997.8    0.05       0  5001.8    0.05       0
Bank Sta=4997.8,5001.8
Exp/Cntr=0.3,0.1

Type RM Length L Ch R = 1,8235,233,233,233
BEGIN DESCRIPTION:
Lacy 131 1136
END DESCRIPTION:
XS GIS Cut Line= 3
      2718581.76      6868634.78      2717869.21      6868665.90
      2717519.38      6868631.95
#Sta/Elev= 30
  4290.2  404.75  4346.0  404.54  4406.1  401.84  4511.3  399.36  4544.3  399.28
  4556.2  398.46  4606.3  397.75  4696.3  395.18  4712.0  395.86  4816.5  395.40
  4836.5  395.97  4866.5  395.27  4886.5  393.72  4916.6  395.56  4936.6  395.71
  4966.6  394.88  4984.6  390.38  4984.9  389.88  4988.4  389.88  4988.6  390.38
  4996.6  391.97  5002.5  394.83  5026.7  393.79  5046.8  395.32  5117.2  396.90
  5197.5  402.35  5288.0  405.85  5308.0  406.04  5318.1  406.87  5354.9  407.51
#Mann=5,-1,0
  4290.2    0.05       0  4511.3    0.12       0  4712.0    0.05       0
  4984.6    0.05       0  4988.6    0.05       0
Bank Sta=4984.6,4988.6
Exp/Cntr=0.3,0.1

Type RM Length L Ch R = 1,8002,653,653,653
BEGIN DESCRIPTION:
Lacy 131 1139
END DESCRIPTION:
XS GIS Cut Line= 3
      2718649.17      6868419.87      2717774.70      6868468.89
      2717532.23      6868480.60
#Sta/Elev= 30
  4127.9  404.73  4161.1  405.12  4181.2  403.79  4231.7  403.37  4281.3  402.57
  4312.4  401.13  4341.4  399.88  4401.5  398.72  4461.6  394.84  4491.6  395.25
  4610.2  393.34  4651.9  392.90  4692.0  393.83  4712.0  393.09  4742.0  393.72
  4792.1  393.52  4812.1  394.31  4908.1  393.90  4962.4  394.04  4972.4  392.14
  4980.4  389.35  4980.7  388.85  4984.2  388.85  4984.4  389.35  4992.4  393.39
  5000.6  396.02  5052.5  397.62  5071.7  399.64  5172.6  404.75  5246.5  406.29
#Mann=8,-1,0
  4127.9    0.05       0  4231.7     0.1       0  4312.4    0.12       0
  4610.2     0.1       0  4908.1    0.12       0  4980.4    0.07       0
  4984.4    0.12       0  5071.7    0.05       0
Bank Sta=4980.4,4984.4
Exp/Cntr=0.3,0.1

Type RM Length L Ch R = 1,7349,465,465,465
BEGIN DESCRIPTION:
Lacy 131 1138
END DESCRIPTION:
XS GIS Cut Line= 3
      2718613.12      6868072.68      2718161.46      6868088.20
      2717556.47      6868385.90
#Sta/Elev= 30
  4612.3  406.39  4692.0  403.34  4706.7  401.63  4712.6  401.79  4759.5  396.02
  4769.5  396.14  4789.5  394.60  4851.2  392.51  4919.6  391.60  4949.6  391.83
  4976.3  390.84  5002.5  390.13  5009.7  388.53  5017.7  387.89  5017.9  387.39
  5021.4  387.39  5021.7  387.89  5027.4  390.34  5029.7  391.33  5039.7  391.70
  5049.7  391.31  5070.3  392.23  5092.6  391.77  5139.4  392.46  5348.5  393.75
  5438.8  395.93  5549.6  398.49  5601.3  400.82  5661.0  402.56  5738.5  403.63
#Mann=10,-1,0
  4612.3    0.12       0  4692.0     0.1       0  4712.6    0.12       0
  4851.2     0.1       0  4976.3    0.12       0  5017.7    0.07       0
  5021.7    0.12       0  5027.4     0.1       0  5139.4    0.12       0
  5438.8    0.05       0
Bank Sta=5017.7,5021.7
Exp/Cntr=0.3,0.1

Type RM Length L Ch R = 1,6884,160,160,160
BEGIN DESCRIPTION:
Lacy 131 1135
END DESCRIPTION:
XS GIS Cut Line= 3
      2718613.06      6867600.78      2718126.17      6867710.72
      2717536.44      6867822.63
#Sta/Elev= 30
  4502.0  403.79  4541.7  402.57  4581.0  402.50  4611.6  400.90  4617.2  401.39
  4632.3  400.03  4665.0  398.91  4693.8  397.04  4708.2  397.15  4719.8  395.95
  4751.4  393.89  4848.1  391.13  4857.8  390.19  5011.5  390.43  5019.5  388.29
  5019.9  387.79  5023.9  388.29  5028.1  388.46  5033.2  390.31  5042.0  391.12
  5117.2  391.83  5190.0  393.19  5204.9  392.78  5289.5  394.79  5345.7  395.96
  5439.0  398.33  5530.6  402.59  5560.9  403.62  5566.0  403.21  5601.4  405.30
#Mann=10,-1,0
  4502.0    0.12       0  4541.7     0.1       0  4617.2    0.12       0
  4719.8     0.1       0  5019.5    0.07       0  5023.9     0.1       0
  5042.0    0.12       0  5117.2    0.05       0  5289.5    0.12       0
  5345.7    0.05       0
Bank Sta=5019.5,5023.9
Exp/Cntr=0.3,0.1

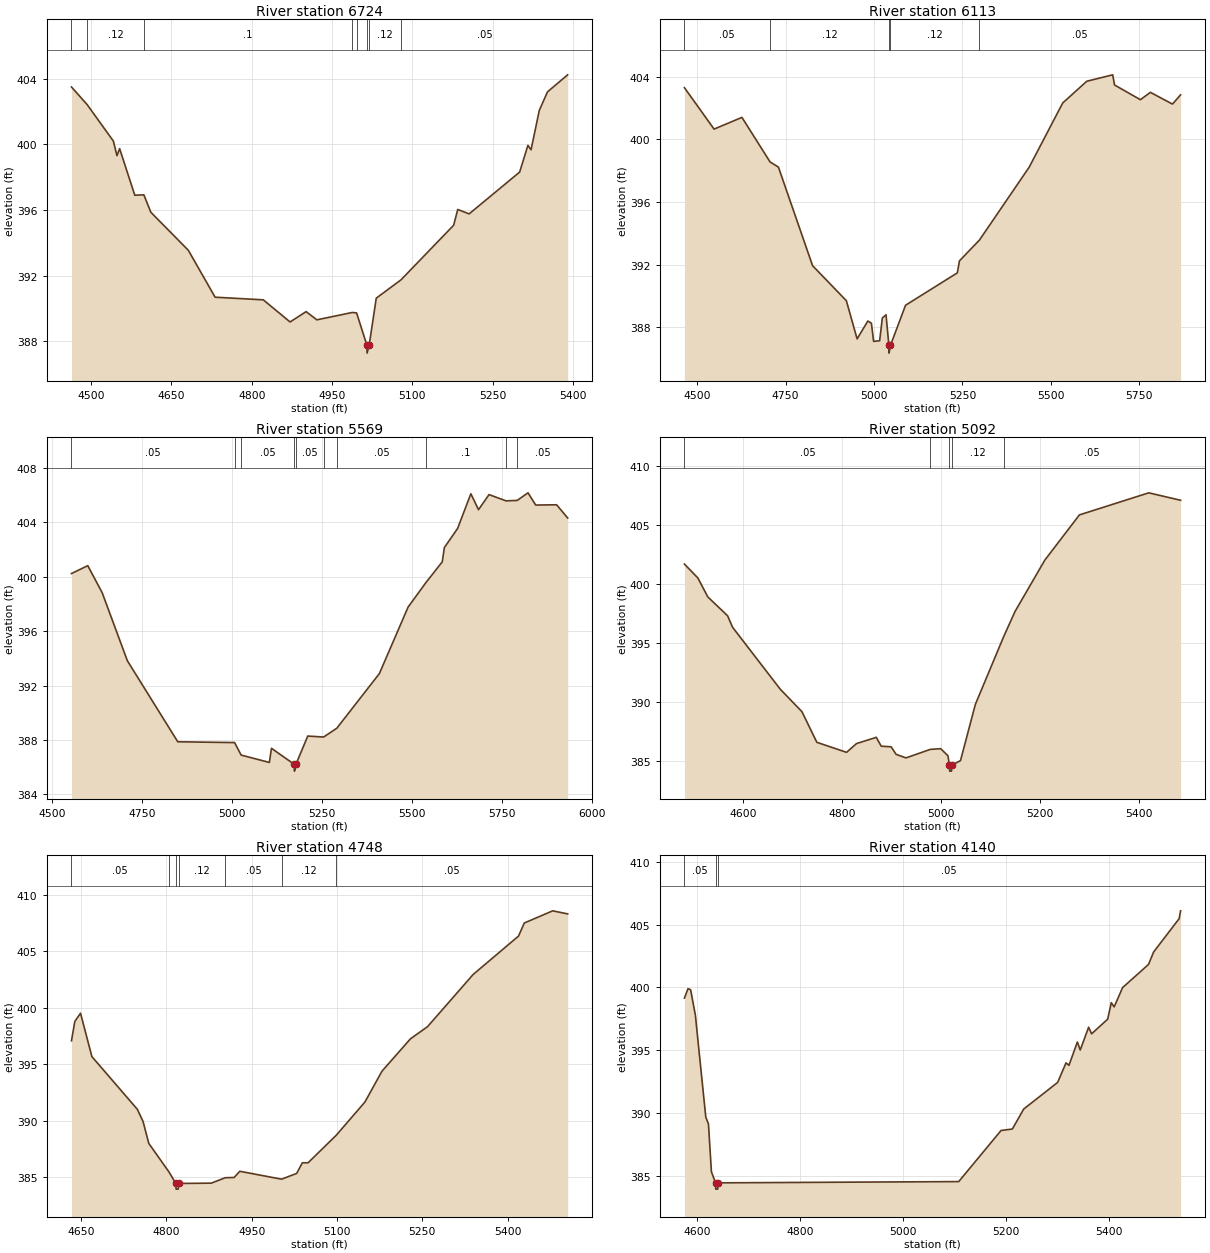
Type RM Length L Ch R = 1,6724,611,611,611
BEGIN DESCRIPTION:
Lacy 131 1134
END DESCRIPTION:
XS GIS Cut Line= 3
      2718614.24      6867553.17      2718070.69      6867570.90
      2717745.09      6867368.53
#Sta/Elev= 30
  4463.1  403.50  4492.5  402.42  4541.4  400.20  4548.1  399.31  4553.1  399.74
  4581.4  396.90  4598.4  396.92  4611.4  395.86  4681.5  393.54  4731.5  390.68
  4821.5  390.52  4871.6  389.17  4901.6  389.80  4921.6  389.30  4988.1  389.75
  4995.9  389.72  5015.0  387.77  5015.5  387.27  5019.5  387.77  5032.6  390.62
  5078.9  391.74  5177.3  395.07  5184.9  396.03  5206.2  395.76  5300.6  398.31
  5316.0  399.94  5321.9  399.67  5337.3  402.07  5352.6  403.20  5390.3  404.24
#Mann=8,-1,0
  4463.1     0.1       0  4492.5    0.12       0  4598.4     0.1       0
  4988.1    0.05       0  4995.9    0.12       0  5015.0    0.07       0
  5019.5    0.12       0  5078.9    0.05       0
Bank Sta=5015,5019.5
Exp/Cntr=0.3,0.1

Type RM Length L Ch R = 1,6113,544,544,544
BEGIN DESCRIPTION:
Lacy 131 1133
END DESCRIPTION:
XS GIS Cut Line= 3
      2718918.88      6867231.20      2718388.69      6867149.65
      2717553.77      6866914.57
#Sta/Elev= 30
  4463.5  403.31  4547.4  400.66  4626.2  401.41  4705.9  398.56  4729.5  398.23
  4826.1  391.93  4921.7  389.69  4952.1  387.25  4982.4  388.39  4992.5  388.25
  4998.8  387.09  5015.8  387.13  5023.5  388.59  5033.9  388.79  5042.0  386.84
  5042.5  386.34  5046.5  386.84  5089.1  389.40  5235.6  391.47  5241.7  392.24
  5298.3  393.57  5439.0  398.23  5533.8  402.33  5601.9  403.72  5675.2  404.13
  5680.4  403.48  5753.6  402.54  5781.9  403.01  5844.2  402.26  5867.3  402.85
#Mann=5,-1,0
  4463.5    0.05       0  4705.9    0.12       0  5042.0    0.07       0
  5046.5    0.12       0  5298.3    0.05       0
Bank Sta=5042,5046.5
Exp/Cntr=0.3,0.1

Type RM Length L Ch R = 1,5569,477,477,477
BEGIN DESCRIPTION:
Lacy 131 1132
END DESCRIPTION:
XS GIS Cut Line= 3
      2719121.26      6866733.68      2718677.45      6866723.39
      2717879.37      6866237.28
#Sta/Elev= 30
  4554.9  400.24  4600.2  400.82  4640.2  398.83  4710.2  393.82  4850.2  387.86
  5008.0  387.80  5026.3  386.88  5104.6  386.34  5110.5  387.38  5173.9  386.20
  5174.4  385.70  5178.4  386.20  5211.3  388.28  5255.4  388.21  5292.1  388.86
  5410.3  392.88  5490.0  397.77  5539.7  399.58  5584.9  401.10  5590.8  402.15
  5627.6  403.56  5664.4  406.11  5685.7  404.94  5714.8  406.05  5762.1  405.59
  5793.0  405.62  5823.2  406.18  5844.5  405.28  5902.6  405.30  5933.3  404.33
#Mann=10,-1,0
  4554.9    0.05       0  5008.0    0.12       0  5026.3    0.05       0
  5173.9    0.04       0  5178.4    0.05       0  5255.4    0.12       0
  5292.1    0.05       0  5539.7     0.1       0  5762.1    0.12       0
  5793.0    0.05       0
Bank Sta=5173.9,5178.4
Exp/Cntr=0.3,0.1

Type RM Length L Ch R = 1,5092,344,344,344
BEGIN DESCRIPTION:
Lacy 131 1131
END DESCRIPTION:
XS GIS Cut Line= 3
      2719043.23      6866298.93      2718511.32      6866290.93
      2718041.69      6866288.72
#Sta/Elev= 30
  4482.3  401.68  4509.5  400.50  4529.5  398.90  4569.5  397.30  4579.5  396.33
  4675.9  391.08  4719.6  389.18  4749.6  386.59  4809.6  385.74  4829.6  386.48
  4869.6  387.01  4879.6  386.26  4899.6  386.21  4909.6  385.57  4929.6  385.27
  4978.6  385.99  4999.6  386.05  5014.3  385.45  5017.2  384.65  5017.7  384.15
  5021.4  384.15  5021.9  384.65  5039.6  385.04  5069.6  389.80  5126.5  395.51
  5149.6  397.66  5209.6  402.00  5279.6  405.84  5419.6  407.71  5483.9  407.08
#Mann=5,-1,0
  4482.3    0.05       0  4978.6    0.12       0  5017.2    0.07       0
  5021.9    0.12       0  5126.5    0.05       0
Bank Sta=5017.2,5021.9
Exp/Cntr=0.3,0.1

Type RM Length L Ch R = 1,4748,608,608,608
BEGIN DESCRIPTION:
Lacy 131 1130
END DESCRIPTION:
XS GIS Cut Line= 3
      2718991.88      6865981.69      2718621.34      6865977.44
      2718119.70      6865987.41
#Sta/Elev= 30
  4633.2  397.08  4639.1  398.79  4649.1  399.52  4669.1  395.68  4749.1  391.01
  4759.1  389.93  4769.1  388.00  4804.6  385.47  4816.7  384.45  4817.2  383.95
  4820.9  383.95  4821.4  384.45  4879.1  384.48  4903.6  384.96  4919.1  384.98
  4929.1  385.53  5002.6  384.83  5029.1  385.34  5039.1  386.28  5049.1  386.28
  5098.9  388.73  5149.1  391.66  5179.1  394.39  5229.1  397.25  5259.2  398.33
  5339.2  402.94  5419.2  406.35  5429.2  407.50  5479.2  408.58  5505.5  408.31
#Mann=7,-1,0
  4633.2    0.05       0  4804.6    0.12       0  4816.7    0.04       0
  4821.4    0.12       0  4903.6    0.05       0  5002.6    0.12       0
  5098.9    0.05       0
Bank Sta=4816.7,4821.4
Exp/Cntr=0.3,0.1

Type RM Length L Ch R = 1,4140,311,311,311
BEGIN DESCRIPTION:
Lacy 131 1129
END DESCRIPTION:
XS GIS Cut Line= 3
      2718886.53      6865303.85      2718476.55      6865415.59
      2718001.02      6865668.64
#Sta/Elev= 30
  4575.5  399.14  4582.5  399.89  4587.6  399.80  4596.8  397.77  4617.0  389.66
  4622.2  389.11  4627.9  385.31  4635.9  384.42  4636.4  383.92  4640.1  383.92
  4640.6  384.42  5108.2  384.52  5190.4  388.59  5212.4  388.71  5234.4  390.30
  5300.3  392.42  5316.6  393.98  5322.3  393.78  5338.6  395.64  5344.2  395.00
  5360.5  396.82  5366.2  396.29  5397.5  397.46  5404.5  398.77  5410.1  398.44
  5426.4  399.97  5476.8  401.82  5486.7  402.81  5536.3  405.47  5539.1  406.09
#Mann=3,-1,0
  4575.5    0.05       0  4635.9    0.03       0  4640.6    0.05       0
Bank Sta=4635.9,4640.6
Exp/Cntr=0.3,0.1