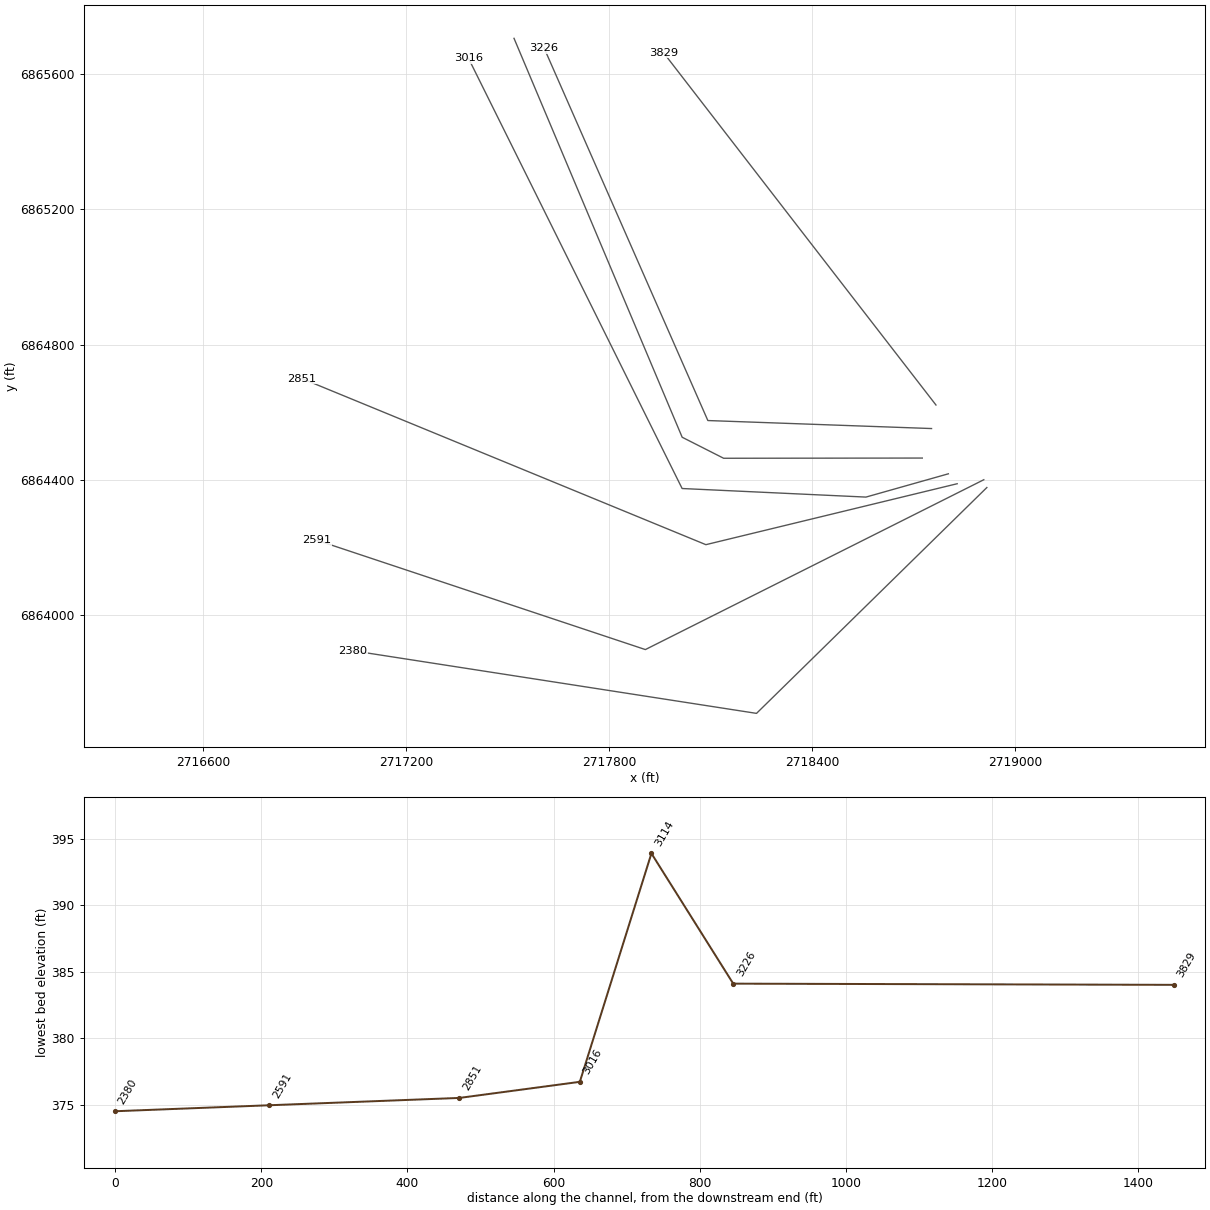
HEC-RAS study Lacy 131.prj: Lacy 131 Base Level Engineering

--- Lacy 131.g01 (geometry) --- (continued)

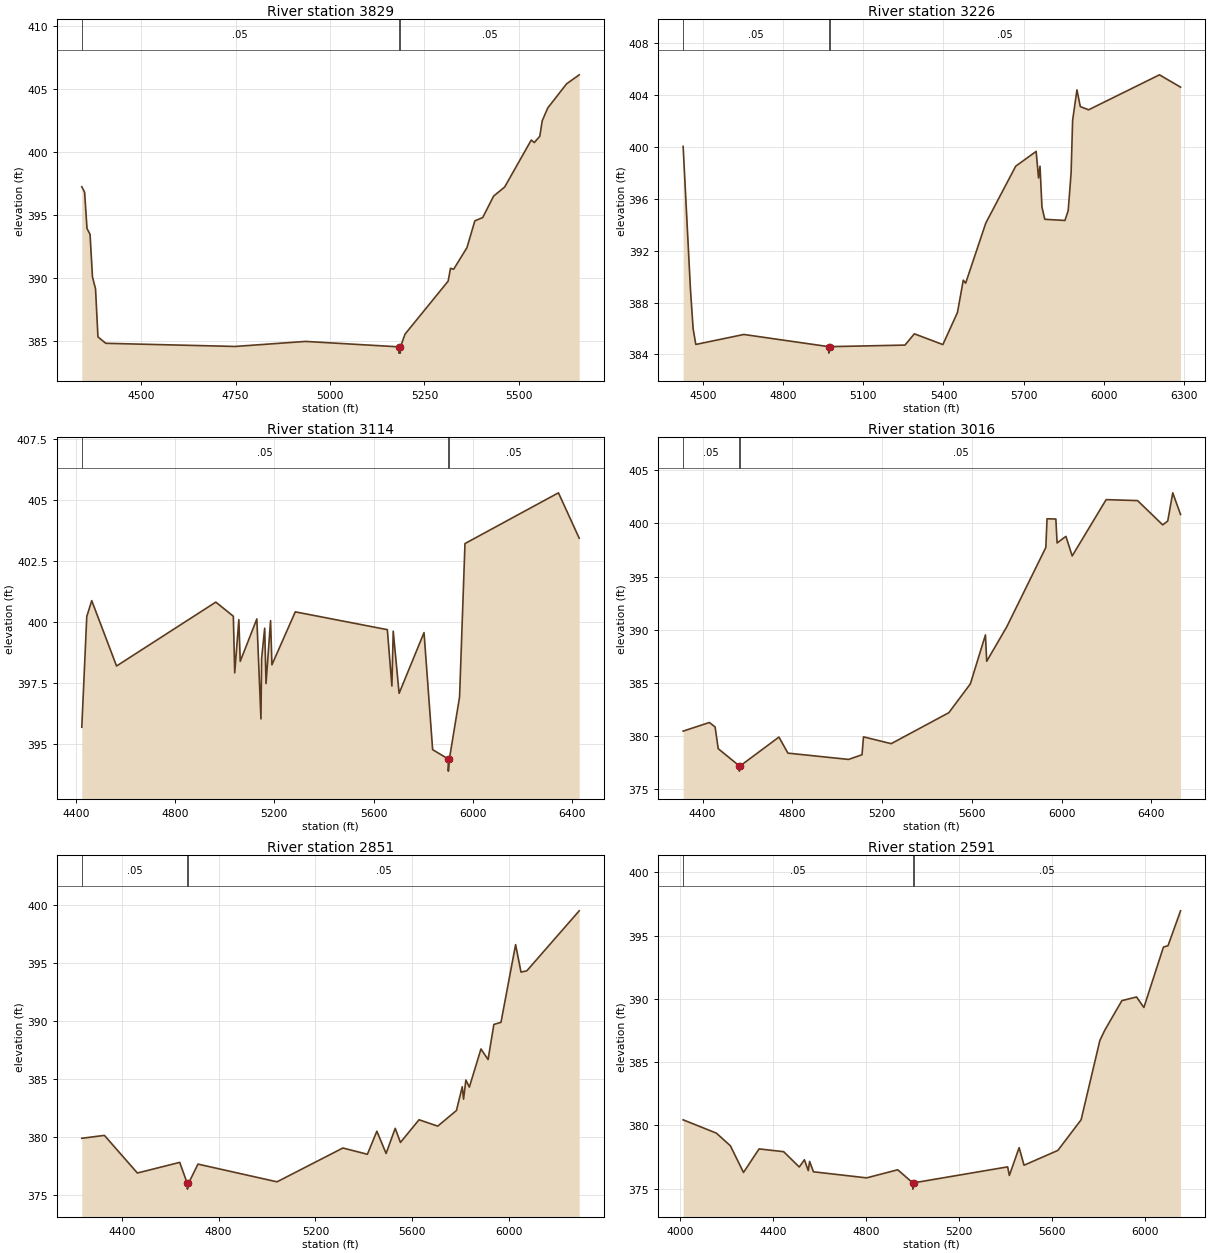
Type RM Length L Ch R = 1,3829,603,603,603
BEGIN DESCRIPTION:
Lacy 131 1128
END DESCRIPTION:
XS GIS Cut Line= 3
      2718766.52      6864621.35      2718361.72      6865144.51
      2717960.88      6865663.19
#Sta/Elev= 30
  4342.9  397.23  4350.4  396.79  4356.7  393.92  4364.8  393.44  4371.2  390.06
  4379.3  389.12  4385.7  385.30  4406.5  384.79  4748.7  384.54  4935.3  384.94
  5181.9  384.51  5182.5  384.01  5186.2  384.01  5186.7  384.51  5198.8  385.52
  5312.9  389.73  5319.2  390.75  5327.4  390.67  5362.7  392.39  5383.6  394.52
  5404.4  394.78  5433.4  396.49  5462.4  397.20  5533.0  400.94  5541.1  400.74
  5555.6  401.24  5562.0  402.47  5576.5  403.48  5626.3  405.40  5659.9  406.12
#Mann=3,-1,0
  4342.9    0.05       0  5181.9    0.03       0  5186.7    0.05       0
Bank Sta=5181.9,5186.7
Exp/Cntr=0.3,0.1

Type RM Length L Ch R = 1,3226,112,112,112
BEGIN DESCRIPTION:
Lacy 131 1122
END DESCRIPTION:
XS GIS Cut Line= 3
      2718753.46      6864551.79      2718092.31      6864575.45
      2717608.29      6865676.48
#Sta/Elev= 30
  4424.3  400.06  4451.8  389.01  4461.8  385.98  4471.8  384.77  4651.9  385.54
  4969.7  384.60  4970.3  384.10  4974.5  384.60  5255.8  384.72  5291.0  385.59
  5397.8  384.76  5452.4  387.23  5474.3  389.73  5483.2  389.50  5558.7  394.14
  5670.9  398.53  5747.4  399.67  5756.4  397.62  5761.9  398.53  5769.2  395.37
  5779.8  394.43  5855.3  394.34  5867.5  395.10  5878.4  398.01  5884.1  402.06
  5900.3  404.42  5912.9  403.13  5944.0  402.88  6209.5  405.58  6288.6  404.63
#Mann=3,-1,0
  4424.3    0.05       0  4969.7    0.04       0  4974.5    0.05       0
Bank Sta=4969.7,4974.5
Exp/Cntr=0.3,0.1

Type RM Length L Ch R = 1,3114,98,98,98
BEGIN DESCRIPTION:
Lacy 131 1121
END DESCRIPTION:
XS GIS Cut Line= 4
      2718726.14      6864464.57      2718138.93      6864463.96
      2718016.39      6864526.07      2717519.39      6865705.11
#Sta/Elev= 30
  4424.4  395.69  4444.5  400.23  4464.5  400.88  4564.5  398.20  4964.5  400.82
  5035.0  400.24  5040.6  397.92  5057.2  400.10  5062.8  398.39  5129.7  400.13
  5146.3  396.03  5148.9  398.50  5161.3  399.75  5166.7  397.48  5185.0  400.06
  5190.5  398.25  5284.6  400.42  5655.5  399.69  5673.8  397.38  5679.2  399.63
  5702.9  397.08  5803.3  399.57  5838.0  394.77  5900.7  394.39  5901.3  393.89
  5905.5  394.39  5946.5  396.93  5968.3  403.22  6344.9  405.30  6428.5  403.44
#Mann=3,-1,0
  4424.4    0.05       0  5900.7    0.04       0  5905.5    0.05       0
Bank Sta=5900.7,5905.5
Exp/Cntr=0.3,0.1

Type RM Length L Ch R = 1,3016,165,165,165
BEGIN DESCRIPTION:
Lacy 131 1124
END DESCRIPTION:
XS GIS Cut Line= 4
      2718803.16      6864418.01      2718559.57      6864349.20
      2718016.22      6864374.54      2717384.96      6865645.77
#Sta/Elev= 30
  4313.3  380.48  4430.4  381.29  4455.8  380.87  4469.6  378.83  4563.3  377.22
  4563.8  376.72  4568.1  377.22  4740.2  379.92  4780.2  378.41  5050.5  377.82
  5110.4  378.26  5117.0  379.94  5240.4  379.30  5497.2  382.21  5593.2  384.92
  5660.4  389.52  5666.0  387.04  5755.6  390.29  5929.3  397.73  5934.9  400.43
  5974.1  400.41  5979.7  398.16  6018.9  398.78  6046.9  396.94  6198.2  402.23
  6338.2  402.14  6450.2  399.86  6472.6  400.22  6495.0  402.87  6529.7  400.84
#Mann=3,-1,0
  4313.3    0.05       0  4563.3    0.04       0  4568.1    0.05       0
Bank Sta=4563.3,4568.1
Exp/Cntr=0.3,0.1

Type RM Length L Ch R = 1,2851,260,260,260
BEGIN DESCRIPTION:
Lacy 131 1125
END DESCRIPTION:
XS GIS Cut Line= 3
      2718829.21      6864388.69      2718086.47      6864208.56
      2716893.08      6864699.24
#Sta/Elev= 30
  4234.8  379.90  4328.3  380.15  4464.5  376.90  4639.4  377.82  4670.4  376.01
  4671.1  375.51  4675.5  376.01  4714.8  377.67  5041.2  376.14  5313.2  379.06
  5414.5  378.52  5453.7  380.51  5491.8  378.59  5529.4  380.76  5551.0  379.54
  5627.8  381.50  5705.1  380.95  5782.4  382.30  5806.3  384.35  5811.7  383.28
  5821.3  384.93  5835.7  384.32  5883.6  387.61  5913.0  386.70  5936.9  389.73
  5966.3  389.91  6026.7  396.62  6049.0  394.25  6073.0  394.36  6289.4  399.54
#Mann=3,-1,0
  4234.8    0.05       0  4670.4    0.04       0  4675.5    0.05       0
Bank Sta=4670.4,4675.5
Exp/Cntr=0.3,0.1

Type RM Length L Ch R = 1,2591,211,211,211
BEGIN DESCRIPTION:
Lacy 131 3449
END DESCRIPTION:
XS GIS Cut Line= 3
      2718907.89      6864400.49      2717907.62      6863898.51
      2716936.18      6864221.86
#Sta/Elev= 30
  4011.6  380.44  4154.5  379.39  4215.1  378.39  4271.7  376.28  4338.8  378.14
  4444.8  377.92  4511.9  376.71  4534.2  377.28  4550.8  376.42  4556.5  377.15
  4573.1  376.33  4802.2  375.85  4936.2  376.49  5000.7  375.46  5001.3  374.96
  5005.8  375.46  5409.8  376.72  5417.0  376.04  5459.2  378.24  5480.3  376.85
  5626.0  378.02  5726.2  380.44  5807.0  386.71  5828.1  387.52  5901.8  389.86
  5965.1  390.15  5996.7  389.32  6081.0  394.10  6100.6  394.20  6154.6  396.96
#Mann=3,-1,0
  4011.6    0.05       0  5000.7    0.04       0  5005.8    0.05       0
Bank Sta=5000.7,5005.8
Exp/Cntr=0.3,0.1

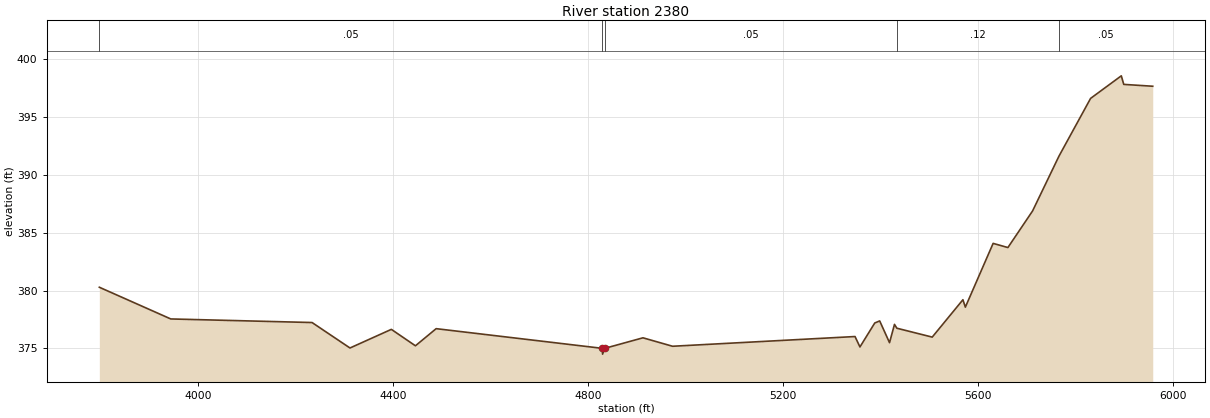
Type RM Length L Ch R = 1,2380,0,0,0
BEGIN DESCRIPTION:
Lacy 131 3450
END DESCRIPTION:
XS GIS Cut Line= 3
      2718916.89      6864377.44      2718236.13      6863709.93
      2717042.33      6863895.13
#Sta/Elev= 30
  3796.9  380.29  3943.5  377.55  4233.4  377.24  4311.2  375.04  4396.1  376.65
  4445.5  375.23  4488.0  376.71  4828.9  375.01  4829.5  374.51  4834.0  375.01
  4912.4  375.92  4973.1  375.19  5347.5  376.03  5357.6  375.13  5388.0  377.20
  5398.1  377.38  5418.3  375.50  5428.5  377.08  5433.3  376.75  5505.9  375.98
  5568.9  379.21  5573.9  378.57  5630.9  384.08  5661.2  383.72  5711.8  386.88
  5766.0  391.62  5830.9  396.61  5893.9  398.56  5898.9  397.82  5958.4  397.66
#Mann=5,-1,0
  3796.9    0.05       0  4828.9    0.04       0  4834.0    0.05       0
  5433.3    0.12       0  5766.0    0.05       0
Bank Sta=4828.9,4834
Exp/Cntr=0.3,0.1

Chan Stop Cuts=-1