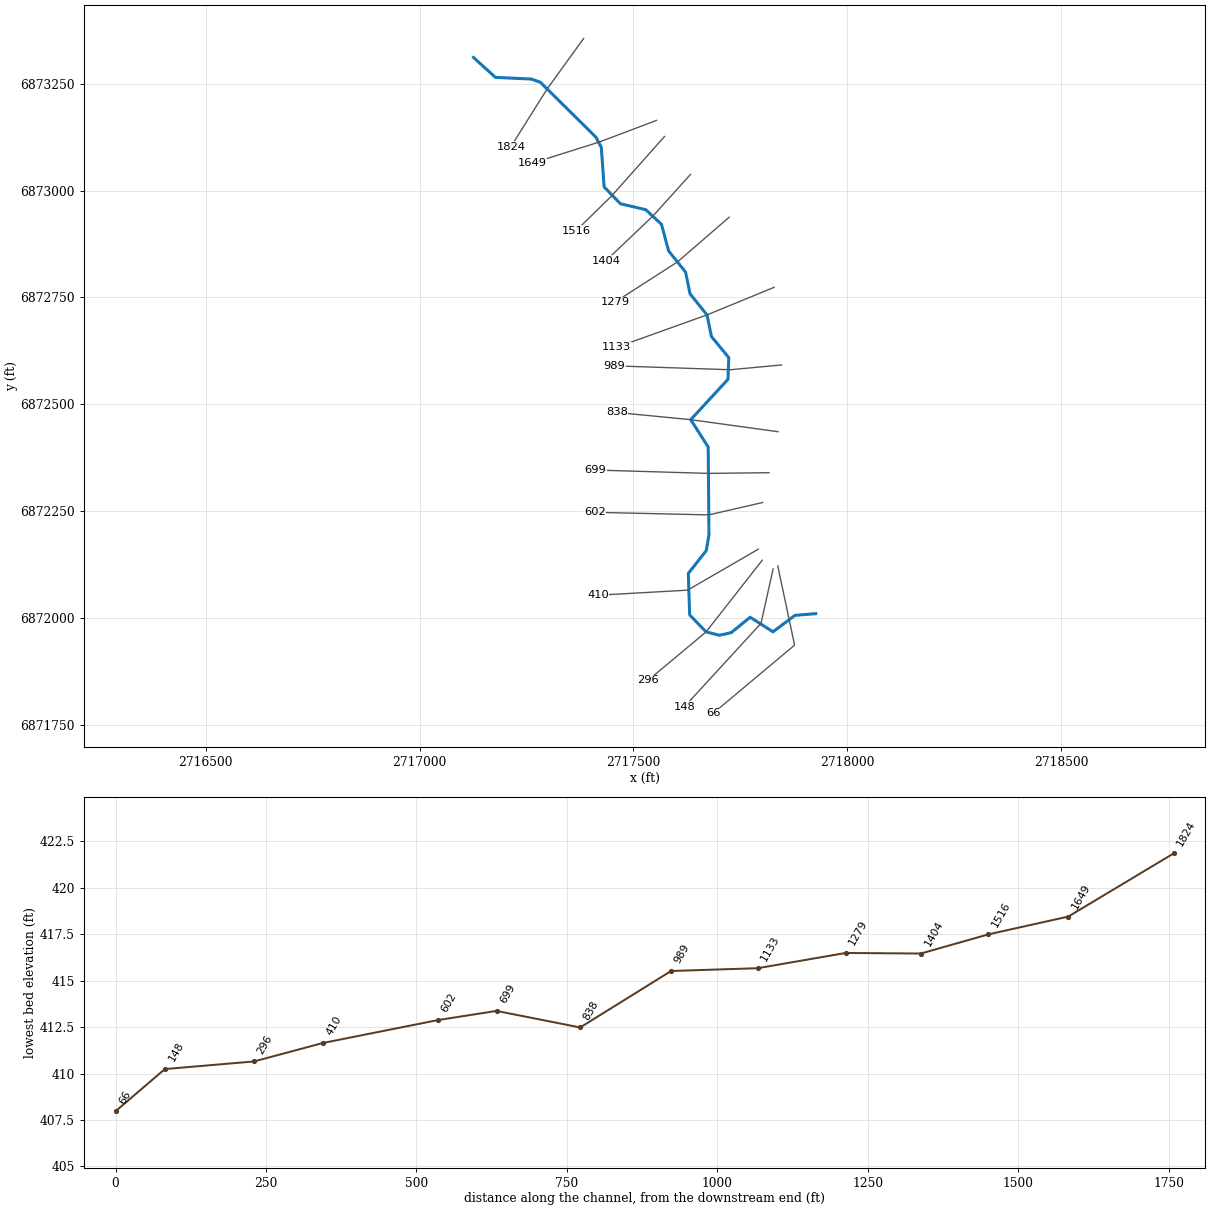
--- Lacy 132.prj (project) ---

Proj Title=Lacy 132 Base Level Engineering
Current Plan=p01
Default Exp/Contr=0.3,0.1
English Units
Geom File=g01
Flow File=f01
Plan File=p01
BEGIN DESCRIPTION:
Lacy 132
END DESCRIPTION:

--- Lacy 132.p01 (plan) ---

Plan Title=Multiple Run
Short Identifier=Multiple
Geom File=g01
Flow File=f01
Subcritical Flow
K Sum by GR= 0
Std Step Tol= 0.01
Critical Tol= 0.01
Num of Std Step Trials= 20
Max Error Tol= 0.3
Flow Tol Ratio= 0.001
Split Flow NTrial= 30
Split Flow Tol= 0.02
Split Flow Ratio= 0.02
Log Output Level= 0
Friction Slope Method= 1
Unsteady Friction Slope Method= 2
Unsteady Bridges Friction Slope Method= 1
Parabolic Critical Depth
Global Vel Dist=  1 , 1 , 1
Global Log Level= 0
CheckData=True
Encroach Param= -1, 0, 0, 0
BEGIN DESCRIPTION:
Multiple Run
END DESCRIPTION:

--- Lacy 132.f01 (steady flow) ---

Flow Title=Multiple
Number of Profiles=7
Profile Names=10-year,25-year,50-year,1pct_min,100-year,1pct_plu,500-year
River Rch & RM= Lacy 132,Reach-1,1824
     152     184     207     117     233     465     293
Boundary for River Rch & Prof#=Lacy 132,Reach-1,1
Up Type=0
Dn Type=3
Dn Slope=0.005
Boundary for River Rch & Prof#=Lacy 132,Reach-1,2
Up Type=0
Dn Type=3
Dn Slope=0.005
Boundary for River Rch & Prof#=Lacy 132,Reach-1,3
Up Type=0
Dn Type=3
Dn Slope=0.005
Boundary for River Rch & Prof#=Lacy 132,Reach-1,4
Up Type=0
Dn Type=3
Dn Slope=0.005
Boundary for River Rch & Prof#=Lacy 132,Reach-1,5
Up Type=0
Dn Type=3
Dn Slope=0.005
Boundary for River Rch & Prof#=Lacy 132,Reach-1,6
Up Type=0
Dn Type=3
Dn Slope=0.005
Boundary for River Rch & Prof#=Lacy 132,Reach-1,7
Up Type=0
Dn Type=3
Dn Slope=0.005

--- Lacy 132.g01 (geometry) ---

Geom Title=Existing Conditions

River Reach=Lacy 132,Reach-1
Reach XY= 30
      2717126.00      6873311.00      2717177.41      6873264.39
      2717260.81      6873260.53      2717282.18      6873253.16
      2717412.60      6873124.30      2717424.83      6873100.51
      2717431.42      6873008.33      2717469.64      6872969.03
      2717528.51      6872955.24      2717565.37      6872921.00
      2717582.11      6872858.84      2717621.84      6872809.28
      2717632.08      6872758.80      2717671.84      6872709.28
      2717682.16      6872658.80      2717722.69      6872609.26
      2717720.88      6872558.70      2717633.81      6872464.41
      2717674.61      6872400.57      2717676.43      6872195.82
      2717670.25      6872158.66      2717628.16      6872105.02
      2717631.30      6872008.25      2717669.62      6871968.37
      2717700.90      6871960.55      2717728.26      6871966.60
      2717772.77      6872002.70      2717825.94      6871968.57
      2717877.36      6872007.02      2717926.00      6872011.00

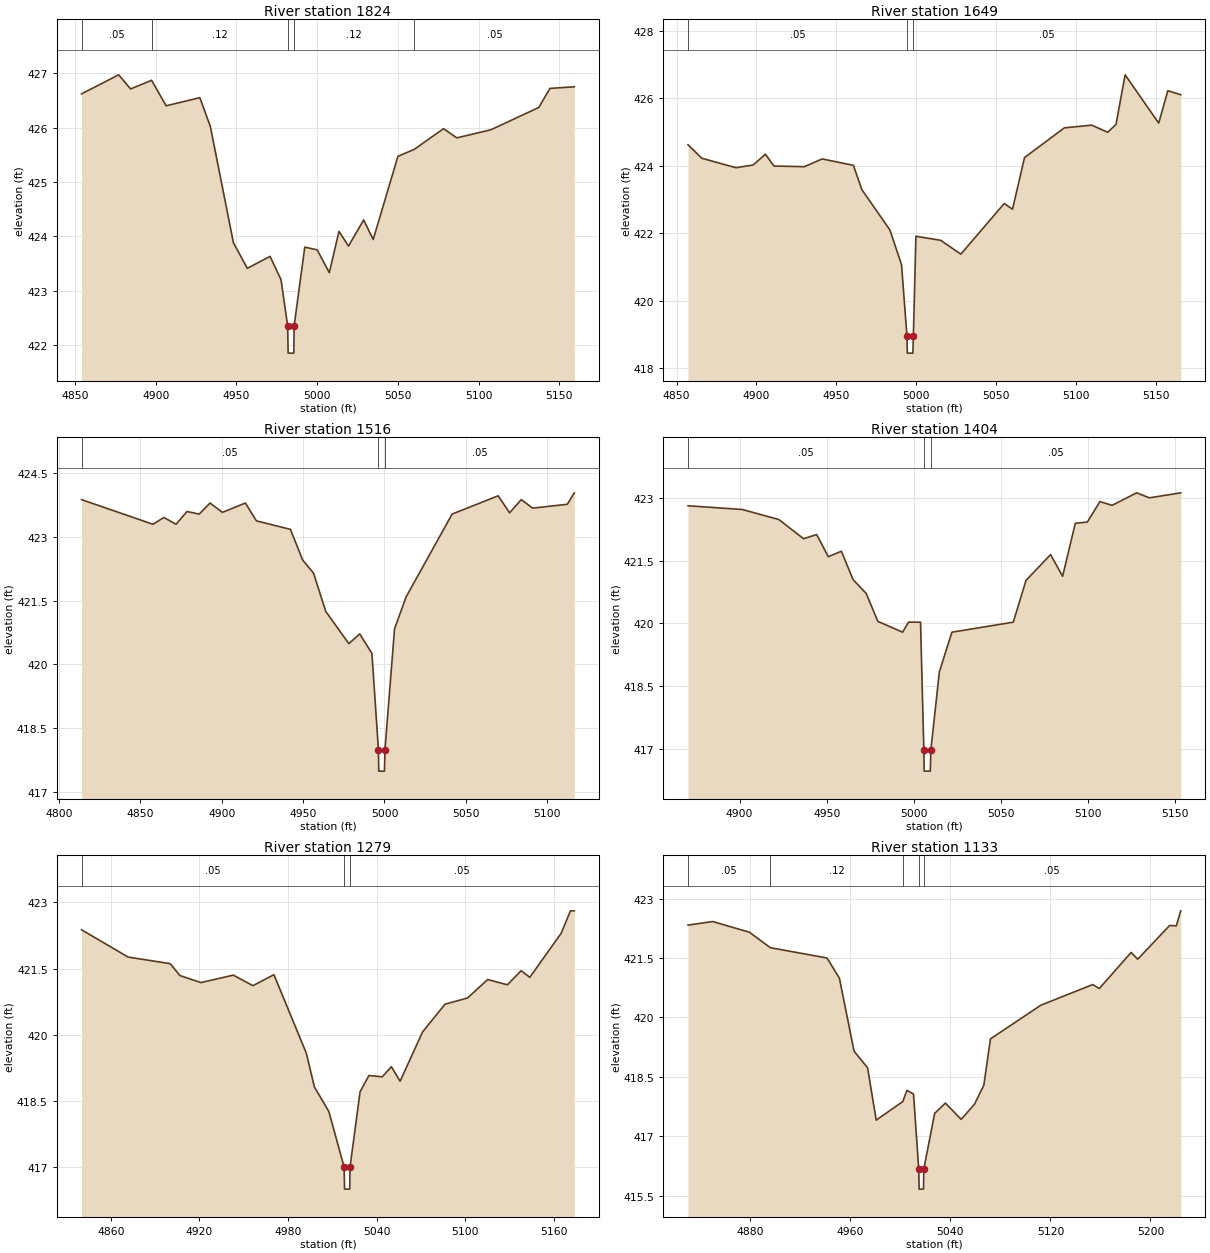
Type RM Length L Ch R = 1,1824,175,175,175
BEGIN DESCRIPTION:
Lacy 132 1198
END DESCRIPTION:
XS GIS Cut Line= 3
      2717383.73      6873355.65      2717298.19      6873237.34
      2717213.52      6873102.40
#Sta/Elev= 30
  4854.0  426.62  4877.0  426.97  4884.4  426.71  4897.4  426.87  4906.4  426.40
  4927.3  426.55  4933.8  426.02  4948.1  423.88  4956.7  423.41  4970.8  423.63
  4977.6  423.20  4981.7  422.35  4982.0  421.85  4985.5  421.85  4985.7  422.35
  4992.3  423.80  5000.0  423.75  5007.5  423.33  5013.5  424.09  5019.4  423.82
  5028.8  424.30  5034.7  423.94  5050.0  425.47  5060.2  425.60  5078.3  425.98
  5086.5  425.81  5107.7  425.96  5137.3  426.37  5144.2  426.72  5159.3  426.75
#Mann=5,-1,0
  4854.0    0.05       0  4897.4    0.12       0  4981.7    0.07       0
  4985.7    0.12       0  5060.2    0.05       0
Bank Sta=4981.7,4985.7
Exp/Cntr=0.3,0.1

Type RM Length L Ch R = 1,1649,133,133,133
BEGIN DESCRIPTION:
Lacy 132 1199
END DESCRIPTION:
XS GIS Cut Line= 3
      2717554.04      6873163.94      2717420.47      6873113.42
      2717262.84      6873063.68
#Sta/Elev= 30
  4857.2  424.62  4865.8  424.22  4887.2  423.94  4897.9  424.02  4905.6  424.34
  4910.9  423.99  4929.9  423.97  4941.1  424.20  4960.6  424.01  4965.9  423.29
  4983.4  422.10  4990.7  421.07  4994.1  418.95  4994.3  418.45  4997.8  418.45
  4998.1  418.95  4999.7  421.91  5015.2  421.79  5027.8  421.38  5054.9  422.88
  5060.1  422.71  5067.6  424.24  5092.5  425.12  5109.6  425.20  5119.6  424.99
  5124.8  425.22  5130.5  426.69  5151.5  425.26  5157.2  426.22  5165.3  426.10
#Mann=3,-1,0
  4857.2    0.05       0  4994.1    0.04       0  4998.1    0.05       0
Bank Sta=4994.1,4998.1
Exp/Cntr=0.3,0.1

Type RM Length L Ch R = 1,1516,112,112,112
BEGIN DESCRIPTION:
Lacy 132 1197
END DESCRIPTION:
XS GIS Cut Line= 3
      2717572.48      6873126.23      2717448.73      6872987.11
      2717365.33      6872905.48
#Sta/Elev= 30
  4813.8  423.88  4857.7  423.30  4864.4  423.46  4871.9  423.30  4878.6  423.60
  4886.1  423.54  4892.8  423.80  4900.4  423.58  4914.5  423.80  4921.3  423.38
  4942.2  423.18  4949.7  422.46  4956.4  422.15  4963.9  421.25  4978.1  420.49
  4984.8  420.72  4992.3  420.26  4996.3  417.99  4996.5  417.49  5000.0  417.49
  5000.3  417.99  5006.2  420.84  5013.3  421.59  5041.6  423.54  5069.9  423.97
  5076.9  423.57  5084.1  423.88  5091.1  423.68  5112.4  423.77  5116.7  424.04
#Mann=3,-1,0
  4813.8    0.05       0  4996.3    0.04       0  5000.3    0.05       0
Bank Sta=4996.3,5000.3
Exp/Cntr=0.3,0.1

Type RM Length L Ch R = 1,1404,125,125,125
BEGIN DESCRIPTION:
Lacy 132 1196
END DESCRIPTION:
XS GIS Cut Line= 3
      2717633.26      6873037.61      2717546.47      6872941.37
      2717435.59      6872835.79
#Sta/Elev= 30
  4870.4  422.82  4901.6  422.73  4922.5  422.49  4936.7  422.03  4944.2  422.13
  4950.9  421.60  4958.4  421.73  4965.1  421.05  4972.6  420.72  4979.3  420.05
  4993.5  419.79  4996.9  420.03  5003.8  420.03  5005.7  416.96  5005.9  416.46
  5009.4  416.46  5009.7  416.96  5014.6  418.84  5021.8  419.79  5057.0  420.03
  5064.3  421.03  5078.4  421.65  5085.3  421.13  5092.6  422.40  5099.5  422.43
  5106.7  422.92  5113.7  422.83  5127.8  423.13  5135.1  423.01  5153.1  423.13
#Mann=3,-1,0
  4870.4    0.05       0  5005.7    0.04       0  5009.7    0.05       0
Bank Sta=5005.7,5009.7
Exp/Cntr=0.3,0.1

Type RM Length L Ch R = 1,1279,146,146,146
BEGIN DESCRIPTION:
Lacy 132 1195
END DESCRIPTION:
XS GIS Cut Line= 3
      2717723.67      6872937.56      2717602.77      6872833.07
      2717456.68      6872739.11
#Sta/Elev= 30
  4840.2  422.38  4871.7  421.76  4900.2  421.61  4906.8  421.34  4921.0  421.18
  4942.9  421.35  4956.2  421.11  4970.4  421.36  4992.3  419.58  4997.8  418.81
  5007.6  418.25  5017.9  416.99  5018.2  416.49  5021.7  416.49  5021.9  416.99
  5028.7  418.70  5034.7  419.07  5043.7  419.04  5049.9  419.27  5055.8  418.94
  5071.0  420.06  5086.2  420.69  5101.4  420.83  5115.1  421.25  5128.4  421.13
  5137.7  421.45  5143.6  421.30  5164.8  422.30  5171.1  422.81  5173.7  422.81
#Mann=3,-1,0
  4840.2    0.05       0  5017.9    0.05       0  5021.9    0.05       0
Bank Sta=5017.9,5021.9
Exp/Cntr=0.3,0.1

Type RM Length L Ch R = 1,1133,144,144,144
BEGIN DESCRIPTION:
Lacy 132 1194
END DESCRIPTION:
XS GIS Cut Line= 3
      2717828.72      6872773.73      2717671.84      6872709.28
      2717460.79      6872633.64
#Sta/Elev= 30
  4830.4  422.33  4850.1  422.42  4879.5  422.15  4896.2  421.76  4941.5  421.50
  4951.4  420.99  4963.1  419.15  4973.9  418.73  4980.8  417.41  5002.1  417.88
  5005.3  418.16  5010.6  418.07  5014.8  416.17  5015.1  415.67  5018.6  415.67
  5018.8  416.17  5027.5  417.58  5036.1  417.84  5048.7  417.43  5059.3  417.81
  5066.8  418.29  5072.1  419.46  5112.4  420.31  5153.8  420.83  5159.1  420.73
  5184.5  421.64  5189.8  421.47  5215.3  422.32  5220.6  422.31  5224.2  422.69
#Mann=5,-1,0
  4830.4    0.05       0  4896.2    0.12       0  5002.1    0.05       0
  5014.8    0.07       0  5018.8    0.05       0
Bank Sta=5014.8,5018.8
Exp/Cntr=0.3,0.1

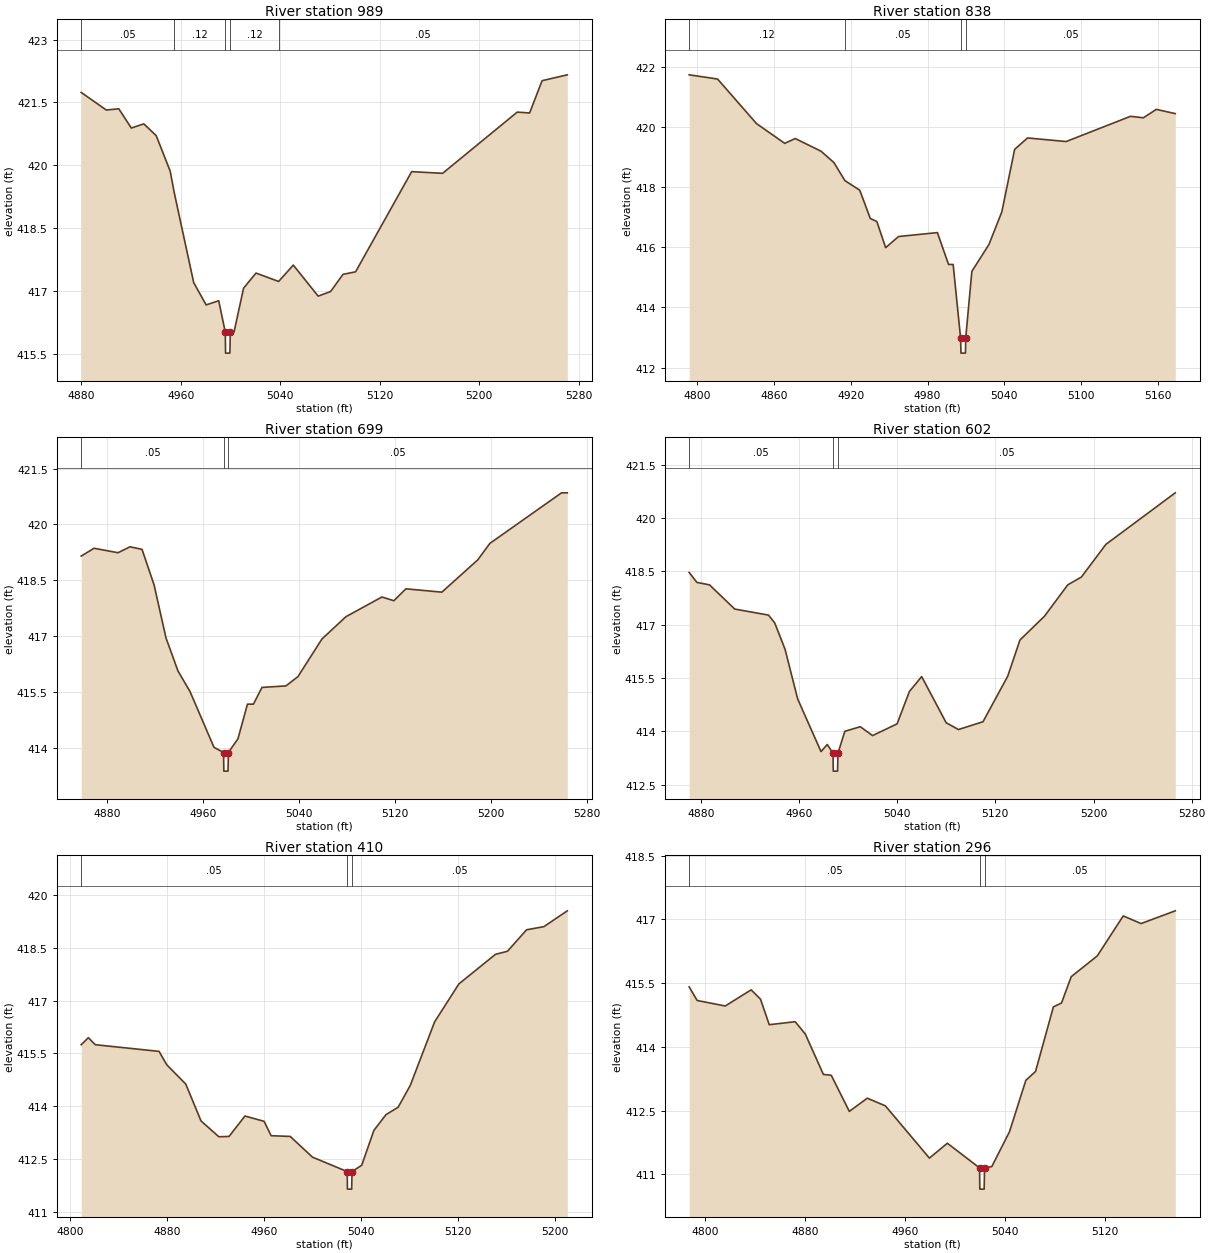
Type RM Length L Ch R = 1,989,151,151,151
BEGIN DESCRIPTION:
Lacy 132 1193
END DESCRIPTION:
XS GIS Cut Line= 3
      2717846.08      6872592.28      2717726.40      6872581.13
      2717455.75      6872590.18
#Sta/Elev= 30
  4879.8  421.74  4900.0  421.32  4910.0  421.35  4920.1  420.89  4930.1  420.99
  4940.1  420.71  4951.4  419.86  4954.4  419.38  4970.3  417.20  4980.3  416.67
  4990.4  416.77  4995.7  416.02  4995.9  415.52  4999.4  415.52  4999.7  416.02
  5002.7  416.02  5010.4  417.07  5020.4  417.43  5038.6  417.23  5050.4  417.62
  5070.4  416.88  5080.4  416.99  5090.4  417.40  5100.5  417.46  5145.6  419.85
  5170.5  419.81  5230.5  421.27  5240.5  421.25  5250.5  422.02  5270.8  422.16
#Mann=5,-1,0
  4879.8    0.05       0  4954.4    0.12       0  4995.7    0.07       0
  4999.7    0.12       0  5038.6    0.05       0
Bank Sta=4995.7,4999.7
Exp/Cntr=0.3,0.1

Type RM Length L Ch R = 1,838,139,139,139
BEGIN DESCRIPTION:
Lacy 132 1192
END DESCRIPTION:
XS GIS Cut Line= 3
      2717837.98      6872436.23      2717633.81      6872464.41
      2717461.23      6872481.20
#Sta/Elev= 30
  4793.9  421.74  4816.1  421.60  4846.4  420.12  4868.5  419.46  4876.7  419.62
  4896.8  419.20  4906.9  418.82  4915.5  418.22  4927.1  417.90  4935.3  416.96
  4940.4  416.86  4947.3  415.99  4957.4  416.36  4987.7  416.49  4996.4  415.43
  5000.0  415.43  5005.8  412.98  5006.1  412.48  5009.6  412.48  5009.8  412.98
  5014.6  415.20  5027.9  416.09  5038.0  417.18  5048.0  419.26  5058.1  419.64
  5088.2  419.52  5138.5  420.36  5148.5  420.31  5158.6  420.59  5173.4  420.45
#Mann=4,-1,0
  4793.9    0.12       0  4915.5    0.05       0  5005.8    0.05       0
  5009.8    0.05       0
Bank Sta=5005.8,5009.8
Exp/Cntr=0.3,0.1

Type RM Length L Ch R = 1,699,97,97,97
BEGIN DESCRIPTION:
Lacy 132 1191
END DESCRIPTION:
XS GIS Cut Line= 3
      2717816.65      6872340.49      2717675.16      6872338.85
      2717411.48      6872346.71
#Sta/Elev= 30
  4858.5  419.15  4869.2  419.36  4889.2  419.24  4899.2  419.40  4909.2  419.33
  4919.2  418.38  4929.2  416.95  4939.2  416.06  4949.2  415.51  4969.2  414.01
  4977.2  413.87  4977.4  413.37  4980.9  413.37  4981.2  413.87  4989.2  414.24
  4997.1  415.17  5002.1  415.17  5009.2  415.62  5029.2  415.66  5039.2  415.91
  5059.2  416.92  5079.2  417.52  5109.2  418.05  5119.2  417.95  5129.2  418.27
  5159.2  418.18  5189.2  419.05  5199.2  419.49  5259.0  420.85  5263.8  420.85
#Mann=3,-1,0
  4858.5    0.05       0  4977.2    0.05       0  4981.2    0.05       0
Bank Sta=4977.2,4981.2
Exp/Cntr=0.3,0.1

Type RM Length L Ch R = 1,602,192,192,192
BEGIN DESCRIPTION:
Lacy 132 1190
END DESCRIPTION:
XS GIS Cut Line= 3
      2717802.13      6872270.88      2717676.02      6872241.89
      2717409.49      6872247.88
#Sta/Elev= 30
  4870.6  418.47  4876.9  418.19  4887.2  418.12  4907.7  417.44  4935.2  417.27
  4940.3  417.05  4948.7  416.31  4959.0  414.91  4978.0  413.43  4983.1  413.63
  4987.8  413.38  4988.0  412.88  4991.5  412.88  4991.8  413.38  4997.4  414.00
  5010.0  414.13  5020.0  413.88  5040.0  414.21  5050.0  415.12  5060.0  415.54
  5080.0  414.24  5090.0  414.05  5110.0  414.27  5130.1  415.55  5140.1  416.57
  5160.1  417.24  5179.0  418.12  5190.1  418.34  5210.1  419.26  5266.6  420.71
#Mann=3,-1,0
  4870.6    0.05       0  4987.8    0.05       0  4991.8    0.05       0
Bank Sta=4987.8,4991.8
Exp/Cntr=0.3,0.1

Type RM Length L Ch R = 1,410,114,114,114
BEGIN DESCRIPTION:
Lacy 132 1189
END DESCRIPTION:
XS GIS Cut Line= 3
      2717791.53      6872161.56      2717626.42      6872065.94
      2717416.75      6872054.16
#Sta/Elev= 30
  4809.2  415.75  4815.1  415.95  4820.8  415.75  4873.4  415.56  4879.7  415.18
  4895.4  414.63  4908.0  413.58  4922.7  413.13  4931.1  413.14  4944.2  413.72
  4960.0  413.57  4965.8  413.16  4981.5  413.14  4999.9  412.55  5028.5  412.14
  5028.7  411.64  5032.2  411.64  5032.5  412.14  5040.5  412.32  5050.5  413.31
  5060.5  413.76  5070.5  413.97  5080.5  414.59  5100.6  416.40  5120.6  417.48
  5150.7  418.32  5160.7  418.41  5176.4  419.02  5190.7  419.11  5210.0  419.56
#Mann=3,-1,0
  4809.2    0.05       0  5028.5    0.05       0  5032.5    0.05       0
Bank Sta=5028.5,5032.5
Exp/Cntr=0.3,0.1

Type RM Length L Ch R = 1,296,148,148,148
BEGIN DESCRIPTION:
Lacy 132 1188
END DESCRIPTION:
XS GIS Cut Line= 3
      2717801.01      6872136.01      2717669.62      6871968.37
      2717533.99      6871855.10
#Sta/Elev= 30
  4787.0  415.41  4793.4  415.09  4815.9  414.96  4836.7  415.34  4844.2  415.12
  4851.2  414.52  4872.0  414.59  4880.1  414.30  4894.6  413.35  4900.9  413.33
  4915.4  412.48  4929.8  412.79  4944.3  412.61  4979.6  411.38  4994.0  411.73
  5019.8  411.15  5020.0  410.65  5023.5  410.65  5023.8  411.15  5029.6  411.18
  5043.8  412.00  5056.9  413.21  5064.7  413.42  5079.0  414.94  5085.5  415.03
  5093.3  415.65  5114.2  416.14  5135.0  417.08  5149.3  416.90  5176.7  417.20
#Mann=3,-1,0
  4787.0    0.05       0  5019.8    0.04       0  5023.8    0.05       0
Bank Sta=5019.8,5023.8
Exp/Cntr=0.3,0.1

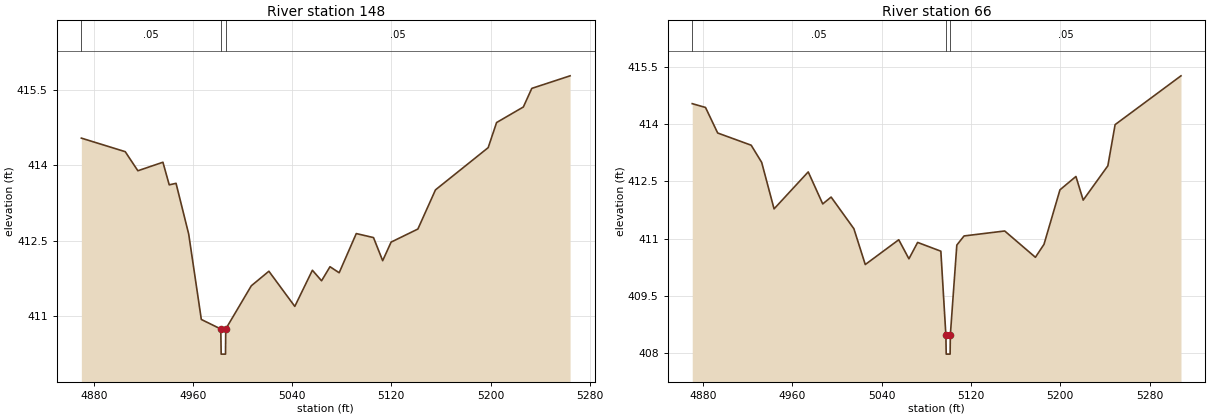
Type RM Length L Ch R = 1,148,82,82,82
BEGIN DESCRIPTION:
Lacy 132 1187
END DESCRIPTION:
XS GIS Cut Line= 3
      2717826.30      6872115.54      2717798.12      6871988.53
      2717619.47      6871793.89
#Sta/Elev= 30
  4869.9  414.54  4905.3  414.27  4915.5  413.89  4935.7  414.06  4940.8  413.61
  4946.3  413.64  4956.5  412.63  4966.7  410.93  4982.4  410.74  4982.7  410.24
  4986.2  410.24  4986.4  410.74  5007.0  411.60  5021.2  411.89  5042.1  411.19
  5056.3  411.91  5063.7  411.70  5070.5  411.98  5077.9  411.86  5091.7  412.64
  5105.6  412.56  5113.0  412.10  5119.8  412.47  5141.4  412.73  5155.6  413.51
  5198.1  414.35  5204.9  414.85  5226.5  415.16  5233.3  415.53  5264.2  415.78
#Mann=3,-1,0
  4869.9    0.05       0  4982.4    0.04       0  4986.4    0.05       0
Bank Sta=4982.4,4986.4
Exp/Cntr=0.3,0.1

Type RM Length L Ch R = 1,66,0,0,0
BEGIN DESCRIPTION:
Lacy 132 3458
END DESCRIPTION:
XS GIS Cut Line= 3
      2717837.20      6872122.67      2717876.54      6871937.48
      2717686.00      6871777.98
#Sta/Elev= 30
  4870.3  414.54  4882.2  414.44  4893.1  413.77  4923.1  413.45  4932.5  413.00
  4943.6  411.78  4974.2  412.75  4987.2  411.91  4994.7  412.09  5015.1  411.26
  5025.3  410.32  5055.3  410.97  5064.4  410.47  5072.2  410.90  5093.0  410.67
  5097.5  408.47  5097.8  407.97  5101.3  407.97  5101.5  408.47  5107.3  410.83
  5113.8  411.07  5150.2  411.20  5177.7  410.51  5185.4  410.85  5199.7  412.28
  5214.0  412.63  5220.5  412.01  5242.6  412.91  5249.1  413.99  5308.1  415.27
#Mann=3,-1,0
  4870.3    0.05       0  5097.5    0.04       0  5101.5    0.05       0
Bank Sta=5097.5,5101.5
Exp/Cntr=0.3,0.1

Chan Stop Cuts=-1