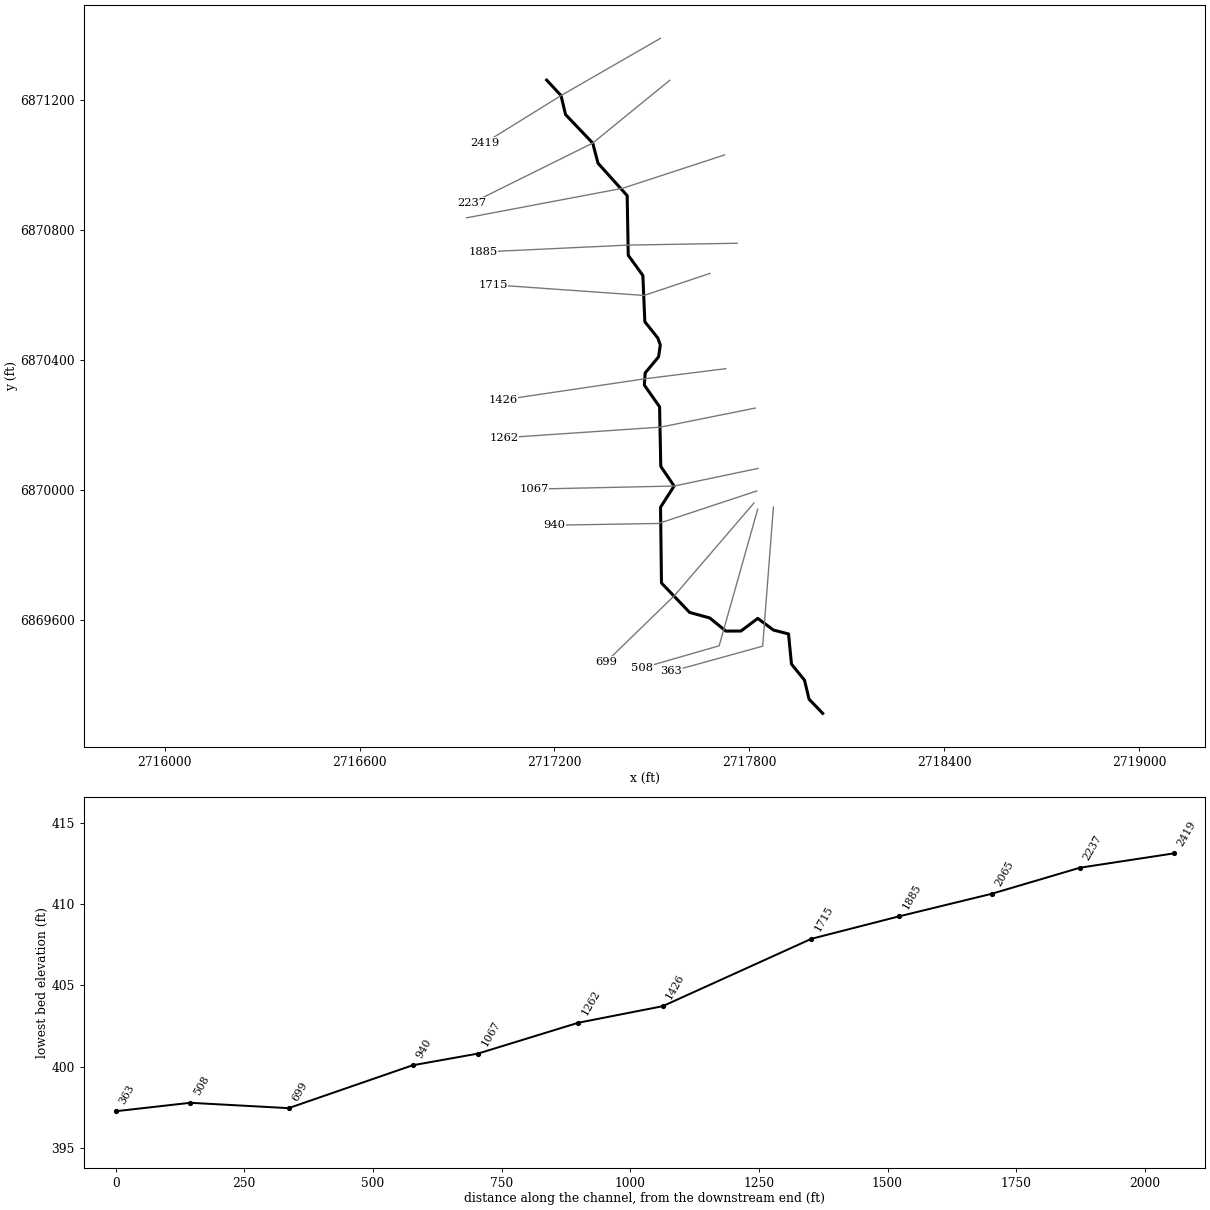
--- Lacy 133.prj (project) ---

Proj Title=Lacy 133 Base Level Engineering
Current Plan=p01
Default Exp/Contr=0.3,0.1
English Units
Geom File=g01
Flow File=f01
Plan File=p01
BEGIN DESCRIPTION:
Lacy 133
END DESCRIPTION:

--- Lacy 133.p01 (plan) ---

Plan Title=Multiple Run
Short Identifier=Multiple
Geom File=g01
Flow File=f01
Subcritical Flow
K Sum by GR= 0
Std Step Tol= 0.01
Critical Tol= 0.01
Num of Std Step Trials= 20
Max Error Tol= 0.3
Flow Tol Ratio= 0.001
Split Flow NTrial= 30
Split Flow Tol= 0.02
Split Flow Ratio= 0.02
Log Output Level= 0
Friction Slope Method= 1
Unsteady Friction Slope Method= 2
Unsteady Bridges Friction Slope Method= 1
Parabolic Critical Depth
Global Vel Dist=  1 , 1 , 1
Global Log Level= 0
CheckData=True
Encroach Param= -1, 0, 0, 0
BEGIN DESCRIPTION:
Multiple Run
END DESCRIPTION:

--- Lacy 133.f01 (steady flow) ---

Flow Title=Multiple
Number of Profiles=7
Profile Names=10-year,25-year,50-year,1pct_min,100-year,1pct_plu,500-year
River Rch & RM= Lacy 133,Reach-1,2419
     231     289     333     191     381     760     497
Boundary for River Rch & Prof#=Lacy 133,Reach-1,1
Up Type=0
Dn Type=3
Dn Slope=0.005
Boundary for River Rch & Prof#=Lacy 133,Reach-1,2
Up Type=0
Dn Type=3
Dn Slope=0.005
Boundary for River Rch & Prof#=Lacy 133,Reach-1,3
Up Type=0
Dn Type=3
Dn Slope=0.005
Boundary for River Rch & Prof#=Lacy 133,Reach-1,4
Up Type=0
Dn Type=3
Dn Slope=0.005
Boundary for River Rch & Prof#=Lacy 133,Reach-1,5
Up Type=0
Dn Type=3
Dn Slope=0.005
Boundary for River Rch & Prof#=Lacy 133,Reach-1,6
Up Type=0
Dn Type=3
Dn Slope=0.005
Boundary for River Rch & Prof#=Lacy 133,Reach-1,7
Up Type=0
Dn Type=3
Dn Slope=0.005

--- Lacy 133.g01 (geometry) ---

Geom Title=Existing Conditions

River Reach=Lacy 133,Reach-1
Reach XY= 30
      2717176.00      6871261.00      2717220.30      6871213.35
      2717234.07      6871154.92      2717317.82      6871067.04
      2717334.18      6871004.96      2717423.93      6870905.14
      2717427.22      6870721.51      2717472.21      6870659.43
      2717478.30      6870516.93      2717518.19      6870466.92
      2717525.90      6870445.60      2717520.59      6870408.80
      2717479.40      6870359.28      2717476.77      6870321.69
      2717523.71      6870255.07      2717527.38      6870071.44
      2717568.44      6870011.00      2717526.66      6869945.84
      2717529.53      6869712.45      2717616.29      6869621.75
      2717678.19      6869604.82      2717727.73      6869564.37
      2717774.36      6869564.60      2717826.03      6869603.45
      2717874.11      6869567.57      2717920.74      6869555.59
      2717929.85      6869462.65      2717969.97      6869413.22
      2717983.91      6869354.85      2718026.00      6869311.00

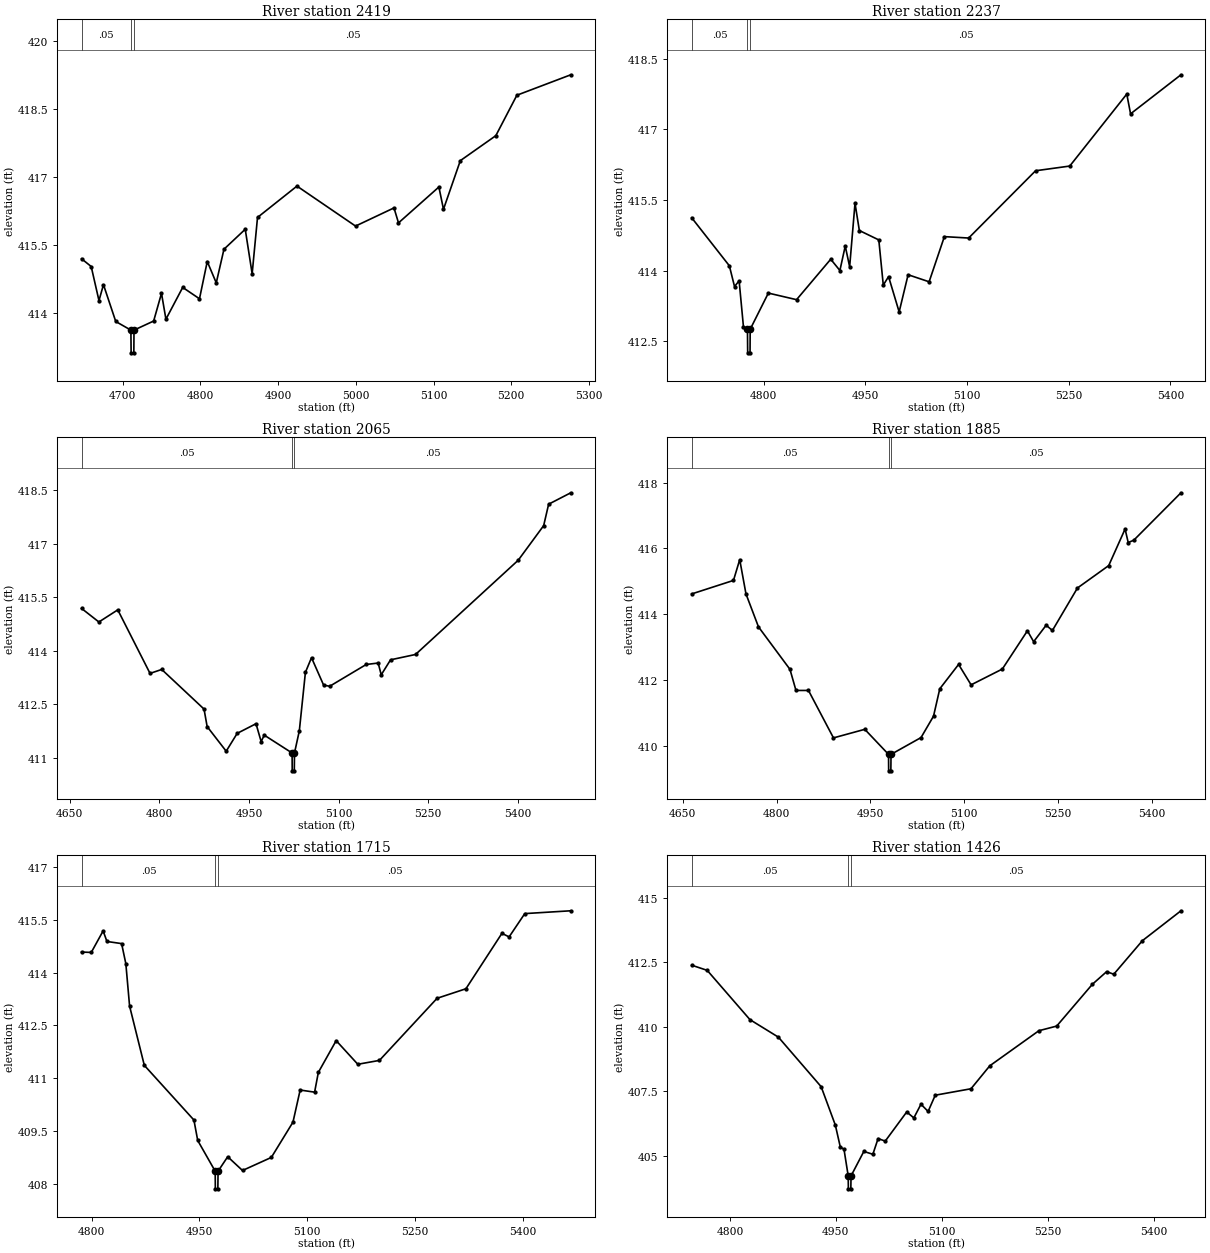
Type RM Length L Ch R = 1,2419,182,182,182
BEGIN DESCRIPTION:
Lacy 133 1171
END DESCRIPTION:
XS GIS Cut Line= 3
      2717526.30      6871389.54      2717220.30      6871213.35
      2716985.18      6871067.46
#Sta/Elev= 30
  4646.9  415.20  4659.3  415.03  4669.3  414.28  4675.1  414.63  4690.9  413.82
  4710.4  413.63  4710.7  413.13  4714.2  413.13  4714.4  413.63  4739.7  413.83
  4749.8  414.44  4755.5  413.87  4777.1  414.57  4798.7  414.32  4808.7  415.14
  4820.3  414.67  4830.2  415.41  4857.6  415.85  4866.5  414.87  4873.4  416.11
  4924.2  416.80  4999.6  415.92  5049.1  416.32  5054.9  415.99  5106.9  416.78
  5112.8  416.29  5134.5  417.36  5180.2  417.91  5207.3  418.80  5276.7  419.25
#Mann=3,-1,0
  4646.9    0.05       0  4710.4    0.05       0  4714.4    0.05       0
Bank Sta=4710.4,4714.4
Exp/Cntr=0.3,0.1

Type RM Length L Ch R = 1,2237,172,172,172
BEGIN DESCRIPTION:
Lacy 133 1172
END DESCRIPTION:
XS GIS Cut Line= 3
      2717554.94      6871260.31      2717317.82      6871067.04
      2716945.42      6870882.55
#Sta/Elev= 30
  4694.1  415.12  4749.6  414.10  4757.2  413.66  4764.0  413.78  4770.4  412.80
  4776.3  412.75  4776.6  412.25  4780.1  412.25  4780.3  412.75  4807.1  413.52
  4848.7  413.38  4899.1  414.24  4912.6  414.00  4920.5  414.52  4927.0  414.08
  4934.9  415.43  4941.3  414.85  4970.0  414.65  4976.6  413.69  4984.4  413.87
  5000.0  413.12  5013.2  413.91  5044.2  413.76  5066.7  414.72  5102.5  414.69
  5201.2  416.12  5251.6  416.22  5335.7  417.75  5341.3  417.33  5415.6  418.16
#Mann=3,-1,0
  4694.1    0.05       0  4776.3    0.05       0  4780.3    0.05       0
Bank Sta=4776.3,4780.3
Exp/Cntr=0.3,0.1

Type RM Length L Ch R = 1,2065,180,180,180
BEGIN DESCRIPTION:
Lacy 133 1173
END DESCRIPTION:
XS GIS Cut Line= 3
      2717723.58      6871030.44      2717409.54      6870927.75
      2716929.55      6870836.96
#Sta/Elev= 30
  4669.6  415.19  4698.6  414.81  4730.2  415.15  4784.2  413.37  4803.8  413.48
  4874.6  412.37  4879.8  411.88  4911.7  411.19  4930.1  411.69  4961.6  411.96
  4970.2  411.46  4975.4  411.64  5022.0  411.14  5022.2  410.64  5025.7  410.64
  5026.0  411.14  5034.1  411.76  5044.3  413.40  5054.5  413.81  5074.8  413.04
  5085.0  413.01  5146.1  413.62  5166.1  413.66  5171.2  413.33  5186.8  413.75
  5228.6  413.90  5400.5  416.54  5443.1  417.51  5451.4  418.11  5488.5  418.43
#Mann=3,-1,0
  4669.6    0.05       0  5022.0    0.04       0  5026.0    0.05       0
Bank Sta=5022,5026
Exp/Cntr=0.3,0.1

Type RM Length L Ch R = 1,1885,170,170,170
BEGIN DESCRIPTION:
Lacy 133 1174
END DESCRIPTION:
XS GIS Cut Line= 3
      2717762.82      6870758.58      2717427.06      6870752.89
      2716980.56      6870731.85
#Sta/Elev= 30
  4664.2  414.62  4731.0  415.03  4741.0  415.66  4751.0  414.62  4771.0  413.62
  4821.4  412.33  4831.0  411.69  4851.0  411.69  4891.0  410.25  4941.1  410.51
  4979.1  409.75  4979.3  409.25  4982.8  409.25  4983.1  409.75  5031.1  410.26
  5051.1  410.91  5061.1  411.74  5091.2  412.48  5111.2  411.86  5161.2  412.34
  5201.3  413.50  5211.3  413.17  5231.3  413.67  5241.3  413.51  5281.4  414.80
  5331.4  415.48  5357.6  416.59  5362.6  416.18  5371.5  416.25  5447.0  417.69
#Mann=3,-1,0
  4664.2    0.05       0  4979.1    0.04       0  4983.1    0.05       0
Bank Sta=4979.1,4983.1
Exp/Cntr=0.3,0.1

Type RM Length L Ch R = 1,1715,289,289,289
BEGIN DESCRIPTION:
Lacy 133 1175
END DESCRIPTION:
XS GIS Cut Line= 3
      2717678.82      6870665.73      2717475.98      6870597.85
      2717010.44      6870630.74
#Sta/Elev= 30
  4786.1  414.58  4799.6  414.57  4816.1  415.18  4821.4  414.88  4841.8  414.82
  4847.7  414.25  4852.9  413.05  4873.4  411.37  4942.4  409.82  4947.7  409.24
  4972.0  408.37  4972.2  407.87  4975.7  407.87  4976.0  408.37  4989.4  408.78
  5010.0  408.39  5050.1  408.76  5080.2  409.76  5090.2  410.67  5110.3  410.61
  5115.5  411.17  5140.3  412.07  5170.4  411.40  5200.5  411.51  5280.7  413.27
  5320.8  413.54  5370.9  415.11  5380.9  415.01  5402.7  415.67  5466.7  415.75
#Mann=3,-1,0
  4786.1    0.05       0  4972.0    0.05       0  4976.0    0.05       0
Bank Sta=4972,4976
Exp/Cntr=0.3,0.1

Type RM Length L Ch R = 1,1426,164,164,164
BEGIN DESCRIPTION:
Lacy 133 1176
END DESCRIPTION:
XS GIS Cut Line= 3
      2717727.75      6870372.45      2717475.73      6870340.83
      2717041.97      6870276.50
#Sta/Elev= 30
  4746.0  412.39  4767.9  412.19  4828.4  410.28  4868.7  409.60  4929.2  407.68
  4949.3  406.19  4956.4  405.33  4961.5  405.26  4967.5  404.22  4967.7  403.72
  4971.2  403.72  4971.5  404.22  4989.6  405.17  5002.4  405.06  5009.8  405.67
  5019.9  405.57  5050.3  406.70  5060.4  406.47  5070.5  407.00  5080.6  406.72
  5090.7  407.35  5141.3  407.60  5167.9  408.49  5237.4  409.85  5262.6  410.03
  5313.1  411.65  5333.3  412.14  5343.4  412.04  5383.9  413.34  5438.5  414.50
#Mann=3,-1,0
  4746.0    0.05       0  4967.5    0.04       0  4971.5    0.05       0
Bank Sta=4967.5,4971.5
Exp/Cntr=0.3,0.1

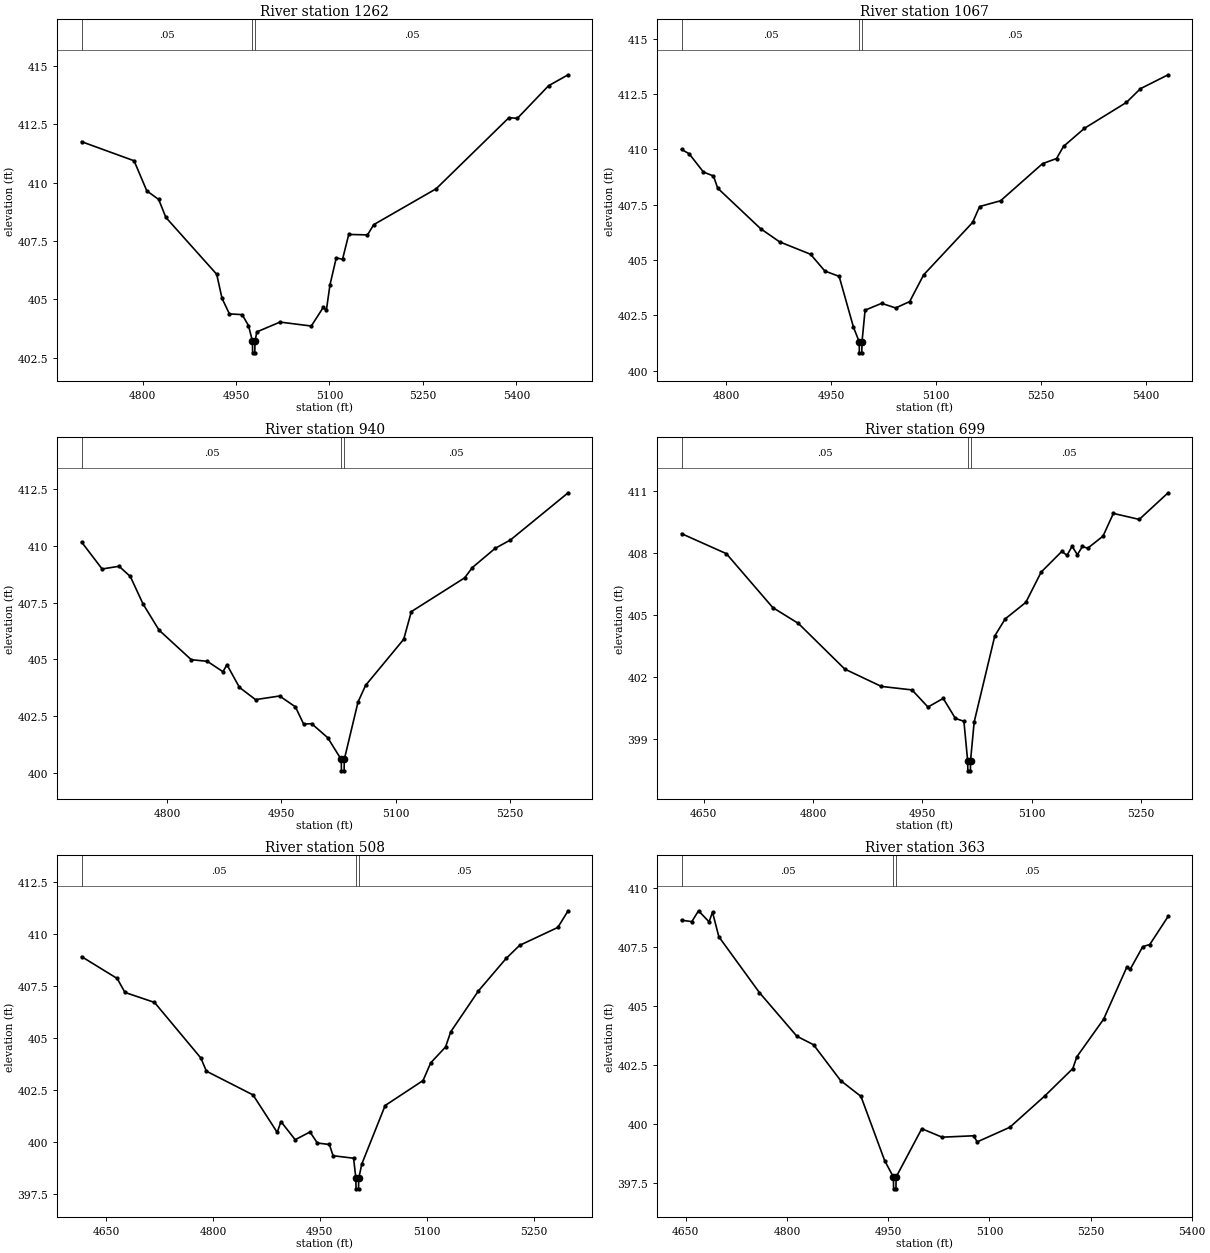
Type RM Length L Ch R = 1,1262,195,195,195
BEGIN DESCRIPTION:
Lacy 133 1177
END DESCRIPTION:
XS GIS Cut Line= 3
      2717818.64      6870251.17      2717526.60      6870192.37
      2717044.71      6870159.67
#Sta/Elev= 30
  4702.1  411.76  4786.4  410.94  4806.8  409.65  4825.9  409.28  4837.4  408.51
  4919.0  406.07  4927.5  405.04  4939.4  404.37  4959.8  404.34  4970.0  403.87
  4976.4  403.20  4976.6  402.70  4980.1  402.70  4980.4  403.20  4983.5  403.60
  5020.6  404.02  5070.8  403.85  5090.0  404.65  5095.0  404.53  5100.8  405.62
  5110.9  406.78  5120.9  406.71  5130.9  407.78  5161.0  407.76  5171.0  408.20
  5271.2  409.74  5388.0  412.79  5401.5  412.76  5451.6  414.16  5483.0  414.63
#Mann=3,-1,0
  4702.1    0.05       0  4976.4    0.04       0  4980.4    0.05       0
Bank Sta=4976.4,4980.4
Exp/Cntr=0.3,0.1

Type RM Length L Ch R = 1,1067,127,127,127
BEGIN DESCRIPTION:
Lacy 133 1178
END DESCRIPTION:
XS GIS Cut Line= 3
      2717826.61      6870065.19      2717568.44      6870011.00
      2717136.44      6870001.60
#Sta/Elev= 30
  4736.2  410.00  4747.0  409.81  4767.5  408.98  4781.9  408.80  4787.9  408.25
  4849.2  406.42  4876.5  405.82  4920.7  405.26  4941.2  404.50  4961.6  404.26
  4982.1  401.96  4990.3  401.30  4990.5  400.80  4994.0  400.80  4994.3  401.30
  4998.7  402.73  5022.4  403.04  5042.4  402.83  5062.5  403.12  5082.5  404.33
  5152.5  406.70  5162.5  407.42  5192.5  407.68  5252.5  409.36  5272.5  409.59
  5282.5  410.14  5312.5  410.96  5372.5  412.13  5392.5  412.75  5432.1  413.38
#Mann=3,-1,0
  4736.2    0.05       0  4990.3    0.04       0  4994.3    0.05       0
Bank Sta=4990.3,4994.3
Exp/Cntr=0.3,0.1

Type RM Length L Ch R = 1,940,241,241,241
BEGIN DESCRIPTION:
Lacy 133 1168
END DESCRIPTION:
XS GIS Cut Line= 3
      2717822.68      6869995.82      2717520.47      6869895.76
      2717200.26      6869890.51
#Sta/Elev= 30
  4687.9  410.17  4714.9  408.98  4737.1  409.10  4751.9  408.65  4768.7  407.43
  4789.7  406.28  4831.9  404.98  4852.9  404.91  4873.5  404.45  4878.7  404.76
  4895.1  403.76  4916.2  403.22  4947.8  403.38  4968.6  402.90  4979.4  402.14
  4989.9  402.16  5011.0  401.54  5028.7  400.58  5029.0  400.08  5032.5  400.08
  5032.7  400.58  5050.7  403.11  5060.7  403.85  5110.7  405.88  5120.7  407.10
  5190.7  408.59  5200.7  409.04  5230.7  409.89  5250.8  410.26  5326.5  412.34
#Mann=3,-1,0
  4687.9    0.05       0  5028.7    0.04       0  5032.7    0.05       0
Bank Sta=5028.7,5032.7
Exp/Cntr=0.3,0.1

Type RM Length L Ch R = 1,699,191,191,191
BEGIN DESCRIPTION:
Lacy 133 1169
END DESCRIPTION:
XS GIS Cut Line= 3
      2717814.36      6869958.81      2717569.63      6869673.93
      2717360.34      6869470.55
#Sta/Elev= 30
  4619.7  408.93  4681.2  407.96  4744.8  405.35  4780.0  404.58  4843.6  402.37
  4893.7  401.53  4935.8  401.36  4957.7  400.53  4978.6  400.95  4995.3  399.98
  5007.0  399.84  5012.1  397.94  5012.4  397.44  5015.9  397.44  5016.1  397.94
  5021.1  399.81  5049.4  403.98  5063.6  404.80  5091.9  405.60  5113.0  407.07
  5141.3  408.07  5148.4  407.88  5155.4  408.32  5162.6  407.91  5169.6  408.31
  5176.7  408.22  5197.8  408.81  5212.0  409.91  5247.5  409.62  5287.1  410.91
#Mann=3,-1,0
  4619.7    0.05       0  5012.1    0.04       0  5016.1    0.05       0
Bank Sta=5012.1,5016.1
Exp/Cntr=0.3,0.1

Type RM Length L Ch R = 1,508,145,145,145
BEGIN DESCRIPTION:
Lacy 133 1170
END DESCRIPTION:
XS GIS Cut Line= 3
      2717825.83      6869939.59      2717707.14      6869519.09
      2717470.60      6869450.94
#Sta/Elev= 30
  4615.5  408.92  4665.5  407.87  4676.4  407.20  4717.9  406.72  4783.0  404.05
  4790.7  403.42  4856.2  402.28  4890.2  400.48  4895.4  401.00  4915.4  400.13
  4936.2  400.50  4946.5  399.97  4963.4  399.90  4968.6  399.36  4997.4  399.24
  5000.6  398.27  5000.8  397.77  5004.3  397.77  5004.6  398.27  5008.9  398.96
  5041.7  401.77  5094.9  402.97  5105.7  403.82  5126.5  404.58  5133.8  405.31
  5172.6  407.27  5211.5  408.83  5230.5  409.46  5284.1  410.32  5298.6  411.12
#Mann=3,-1,0
  4615.5    0.05       0  5000.6    0.04       0  5004.6    0.05       0
Bank Sta=5000.6,5004.6
Exp/Cntr=0.3,0.1

Type RM Length L Ch R = 1,363,0,0,0
BEGIN DESCRIPTION:
Lacy 133 1179
END DESCRIPTION:
XS GIS Cut Line= 3
      2717874.19      6869946.16      2717841.10      6869517.86
      2717559.80      6869440.23
#Sta/Elev= 30
  4643.6  408.64  4658.8  408.58  4668.8  409.04  4684.4  408.57  4689.5  408.98
  4698.9  407.94  4759.1  405.57  4814.6  403.72  4839.3  403.36  4879.5  401.84
  4909.6  401.17  4944.7  398.45  4957.7  397.75  4958.0  397.25  4961.5  397.25
  4961.7  397.75  4999.8  399.80  5029.9  399.44  5076.7  399.50  5081.9  399.24
  5130.3  399.86  5182.2  401.19  5223.7  402.35  5229.7  402.85  5269.3  404.44
  5303.6  406.64  5308.8  406.56  5327.4  407.52  5337.8  407.61  5365.0  408.80
#Mann=3,-1,0
  4643.6    0.05       0  4957.7    0.04       0  4961.7    0.05       0
Bank Sta=4957.7,4961.7
Exp/Cntr=0.3,0.1

Chan Stop Cuts=-1