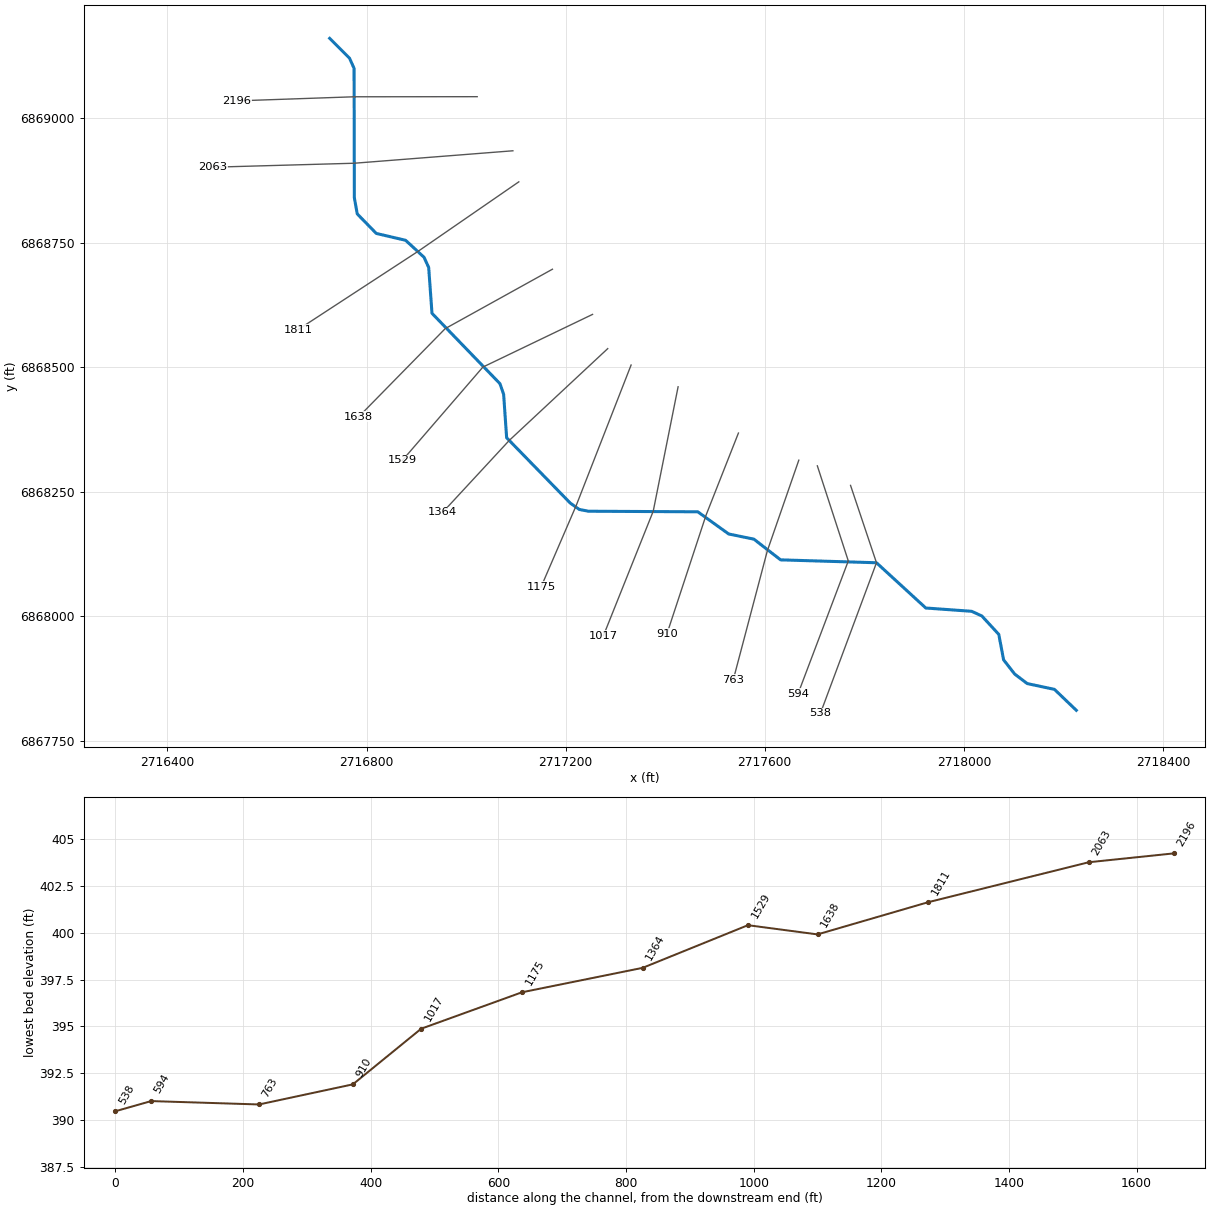
--- Lacy 134.prj (project) ---

Proj Title=Lacy 134 Base Level Engineering
Current Plan=p01
Default Exp/Contr=0.3,0.1
English Units
Geom File=g01
Flow File=f01
Plan File=p01
BEGIN DESCRIPTION:
Lacy 134
END DESCRIPTION:

--- Lacy 134.p01 (plan) ---

Plan Title=Multiple Run
Short Identifier=Multiple
Geom File=g01
Flow File=f01
Subcritical Flow
K Sum by GR= 0
Std Step Tol= 0.01
Critical Tol= 0.01
Num of Std Step Trials= 20
Max Error Tol= 0.3
Flow Tol Ratio= 0.001
Split Flow NTrial= 30
Split Flow Tol= 0.02
Split Flow Ratio= 0.02
Log Output Level= 0
Friction Slope Method= 1
Unsteady Friction Slope Method= 2
Unsteady Bridges Friction Slope Method= 1
Parabolic Critical Depth
Global Vel Dist=  1 , 1 , 1
Global Log Level= 0
CheckData=True
Encroach Param= -1, 0, 0, 0
BEGIN DESCRIPTION:
Multiple Run
END DESCRIPTION:

--- Lacy 134.f01 (steady flow) ---

Flow Title=Multiple
Number of Profiles=7
Profile Names=10-year,25-year,50-year,1pct_min,100-year,1pct_plu,500-year
River Rch & RM= Lacy 134,Reach-1,2196
     227     285     328     188     376     750     492
Boundary for River Rch & Prof#=Lacy 134,Reach-1,1
Up Type=0
Dn Type=3
Dn Slope=0.005
Boundary for River Rch & Prof#=Lacy 134,Reach-1,2
Up Type=0
Dn Type=3
Dn Slope=0.005
Boundary for River Rch & Prof#=Lacy 134,Reach-1,3
Up Type=0
Dn Type=3
Dn Slope=0.005
Boundary for River Rch & Prof#=Lacy 134,Reach-1,4
Up Type=0
Dn Type=3
Dn Slope=0.005
Boundary for River Rch & Prof#=Lacy 134,Reach-1,5
Up Type=0
Dn Type=3
Dn Slope=0.005
Boundary for River Rch & Prof#=Lacy 134,Reach-1,6
Up Type=0
Dn Type=3
Dn Slope=0.005
Boundary for River Rch & Prof#=Lacy 134,Reach-1,7
Up Type=0
Dn Type=3
Dn Slope=0.005

--- Lacy 134.g01 (geometry) ---

Geom Title=Existing Conditions

River Reach=Lacy 134,Reach-1
Reach XY= 30
      2716726.00      6869161.00      2716765.95      6869120.98
      2716775.04      6869100.60      2716775.54      6868840.75
      2716781.36      6868808.30      2716819.64      6868769.03
      2716878.55      6868755.25      2716915.61      6868721.10
      2716924.90      6868700.67      2716931.53      6868608.58
      2717068.14      6868467.17      2717075.47      6868445.78
      2717081.52      6868358.57      2717209.23      6868227.43
      2717227.46      6868214.54      2717245.98      6868210.96
      2717465.50      6868209.80      2717527.74      6868165.19
      2717578.18      6868154.88      2717631.93      6868113.24
      2717824.53      6868107.45      2717923.58      6868016.54
      2718015.67      6868009.90      2718036.10      6868000.61
      2718070.25      6867963.55      2718079.90      6867912.46
      2718102.14      6867883.84      2718127.35      6867864.71
      2718182.11      6867853.05      2718226.00      6867811.00

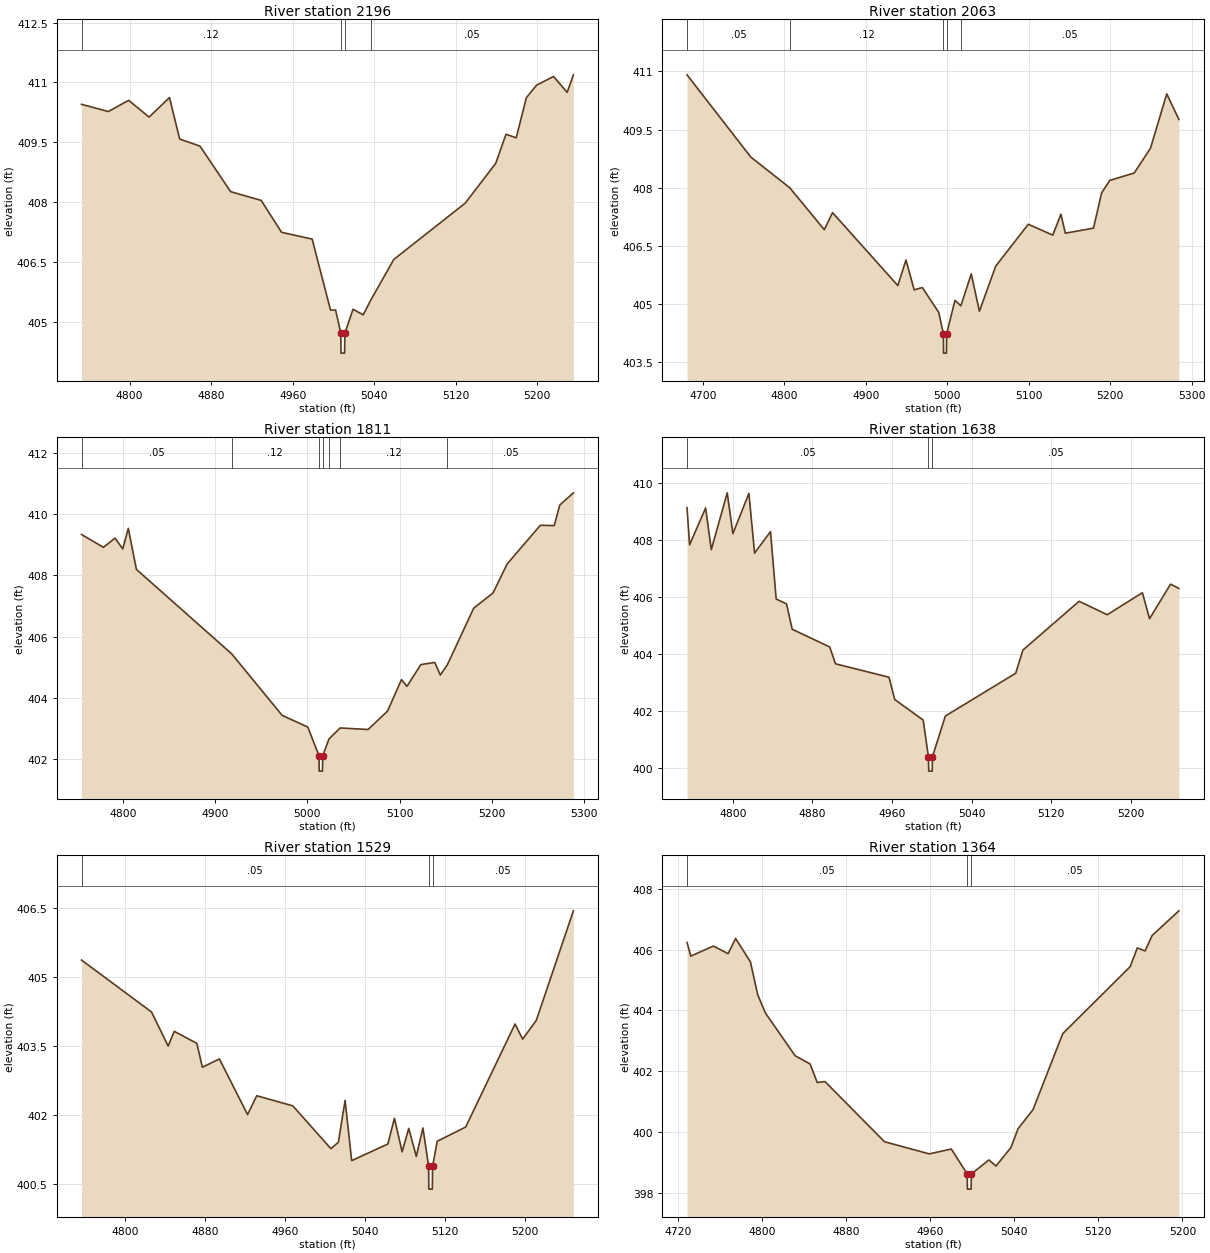
Type RM Length L Ch R = 1,2196,133,133,133
BEGIN DESCRIPTION:
Lacy 134 1163
END DESCRIPTION:
XS GIS Cut Line= 3
      2717022.35      6869043.78      2716775.15      6869043.59
      2716539.89      6869035.37
#Sta/Elev= 30
  4752.8  410.45  4779.1  410.27  4799.1  410.55  4819.1  410.13  4839.1  410.62
  4849.1  409.58  4869.1  409.40  4899.1  408.26  4929.1  408.04  4949.1  407.24
  4979.1  407.07  4997.1  405.29  5002.1  405.29  5007.2  404.71  5007.4  404.21
  5010.9  404.21  5011.2  404.71  5019.2  405.31  5029.2  405.17  5036.4  405.53
  5059.2  406.56  5129.2  407.97  5159.2  408.97  5169.3  409.70  5179.3  409.61
  5189.3  410.62  5199.3  410.93  5215.9  411.15  5229.3  410.75  5235.4  411.19
#Mann=4,-1,0
  4752.8    0.12       0  5007.2    0.07       0  5011.2    0.12       0
  5036.4    0.05       0
Bank Sta=5007.2,5011.2
Exp/Cntr=0.3,0.1

Type RM Length L Ch R = 1,2063,252,252,252
BEGIN DESCRIPTION:
Lacy 134 1162
END DESCRIPTION:
XS GIS Cut Line= 3
      2717094.12      6868935.10      2716775.41      6868910.08
      2716491.12      6868902.10
#Sta/Elev= 30
  4680.3  410.91  4758.7  408.79  4806.5  408.00  4848.9  406.92  4859.0  407.36
  4939.2  405.48  4949.2  406.14  4959.3  405.37  4969.3  405.43  4989.4  404.79
  4995.2  404.24  4995.4  403.74  4998.9  403.74  4999.2  404.24  5009.4  405.10
  5016.6  404.96  5029.4  405.78  5039.4  404.82  5059.4  405.98  5099.4  407.06
  5129.5  406.78  5139.5  407.32  5144.9  406.83  5179.5  406.96  5189.5  407.87
  5199.5  408.19  5229.5  408.38  5249.5  409.02  5269.5  410.42  5284.4  409.76
#Mann=5,-1,0
  4680.3    0.05       0  4806.5    0.12       0  4995.2    0.07       0
  4999.2    0.12       0  5016.6    0.05       0
Bank Sta=4995.2,4999.2
Exp/Cntr=0.3,0.1

Type RM Length L Ch R = 1,1811,173,173,173
BEGIN DESCRIPTION:
Lacy 134 1157
END DESCRIPTION:
XS GIS Cut Line= 3
      2717105.97      6868872.70      2716903.70      6868733.18
      2716662.23      6868575.53
#Sta/Elev= 30
  4754.7  409.34  4778.5  408.92  4791.1  409.22  4799.5  408.87  4805.5  409.54
  4814.3  408.20  4917.8  405.44  4972.6  403.43  5000.4  403.05  5012.6  402.11
  5012.8  401.61  5016.3  401.61  5016.6  402.11  5023.4  402.66  5035.5  403.02
  5065.9  402.97  5087.0  403.57  5102.1  404.60  5108.1  404.38  5123.2  405.09
  5138.3  405.16  5144.3  404.75  5151.9  405.08  5180.5  406.93  5201.6  407.43
  5216.7  408.37  5252.9  409.64  5268.0  409.63  5274.0  410.30  5288.8  410.70
#Mann=7,-1,0
  4754.7    0.05       0  4917.8    0.12       0  5012.6    0.07       0
  5016.6    0.12       0  5023.4    0.05       0  5035.5    0.12       0
  5151.9    0.05       0
Bank Sta=5012.6,5016.6
Exp/Cntr=0.3,0.1

Type RM Length L Ch R = 1,1638,109,109,109
BEGIN DESCRIPTION:
Lacy 134 1154
END DESCRIPTION:
XS GIS Cut Line= 3
      2717173.52      6868697.17      2716958.10      6868577.78
      2716784.39      6868400.77
#Sta/Elev= 30
  4754.0  409.13  4756.6  407.83  4772.7  409.12  4778.4  407.66  4794.4  409.65
  4800.1  408.22  4816.2  409.63  4821.9  407.54  4837.9  408.29  4843.6  405.93
  4854.0  405.76  4859.7  404.87  4897.4  404.25  4903.2  403.66  4957.0  403.19
  4962.7  402.41  4991.3  401.69  4996.6  400.40  4996.9  399.90  5000.4  399.90
  5000.6  400.40  5013.6  401.83  5084.3  403.33  5091.5  404.14  5148.0  405.85
  5176.3  405.38  5211.6  406.15  5218.8  405.24  5239.9  406.45  5248.3  406.30
#Mann=3,-1,0
  4754.0    0.05       0  4996.6    0.05       0  5000.6    0.05       0
Bank Sta=4996.6,5000.6
Exp/Cntr=0.3,0.1

Type RM Length L Ch R = 1,1529,165,165,165
BEGIN DESCRIPTION:
Lacy 134 1153
END DESCRIPTION:
XS GIS Cut Line= 3
      2717254.13      6868606.41      2717033.77      6868500.52
      2716871.87      6868312.90
#Sta/Elev= 30
  4756.5  405.37  4826.6  404.24  4843.2  403.50  4849.3  403.82  4871.9  403.56
  4877.5  403.04  4894.5  403.22  4922.7  402.01  4931.9  402.42  4968.0  402.20
  5006.1  401.27  5013.6  401.41  5020.3  402.32  5026.9  401.01  5063.1  401.37
  5069.7  401.93  5077.4  401.20  5084.0  401.71  5091.6  401.10  5098.2  401.72
  5103.9  400.89  5104.1  400.39  5107.6  400.39  5107.9  400.89  5112.5  401.43
  5141.0  401.74  5190.4  403.98  5198.0  403.65  5211.7  404.06  5248.8  406.44
#Mann=3,-1,0
  4756.5    0.05       0  5103.9    0.05       0  5107.9    0.05       0
Bank Sta=5103.9,5107.9
Exp/Cntr=0.3,0.1

Type RM Length L Ch R = 1,1364,189,189,189
BEGIN DESCRIPTION:
Lacy 134 1155
END DESCRIPTION:
XS GIS Cut Line= 3
      2717284.59      6868537.63      2717086.83      6868353.26
      2716952.76      6868208.47
#Sta/Elev= 30
  4728.9  406.24  4732.5  405.79  4754.0  406.12  4768.0  405.87  4775.1  406.37
  4789.2  405.60  4796.1  404.52  4803.4  403.92  4831.7  402.51  4845.9  402.24
  4852.7  401.63  4860.1  401.66  4916.7  399.68  4959.2  399.28  4980.2  399.44
  4995.3  398.62  4995.5  398.12  4999.0  398.12  4999.3  398.62  5015.9  399.08
  5022.7  398.88  5036.9  399.49  5043.7  400.11  5057.8  400.73  5086.2  403.24
  5150.2  405.44  5157.1  406.06  5164.4  405.96  5171.2  406.47  5196.6  407.28
#Mann=3,-1,0
  4728.9    0.05       0  4995.3    0.04       0  4999.3    0.05       0
Bank Sta=4995.3,4999.3
Exp/Cntr=0.3,0.1

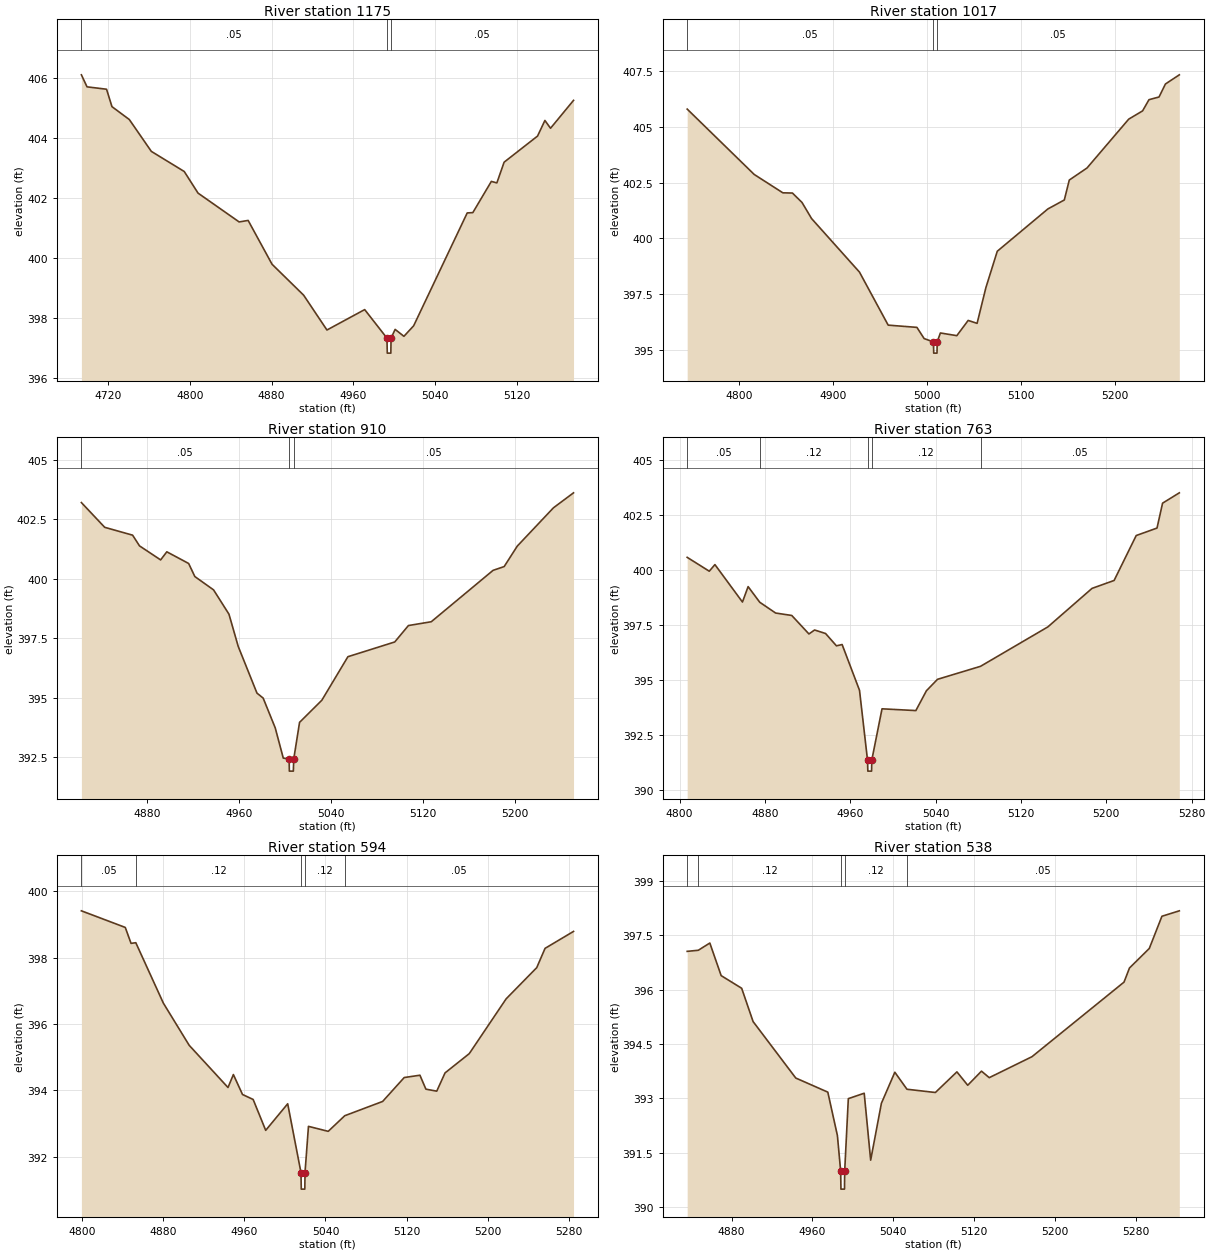
Type RM Length L Ch R = 1,1175,158,158,158
BEGIN DESCRIPTION:
Lacy 134 1156
END DESCRIPTION:
XS GIS Cut Line= 3
      2717331.57      6868504.71      2717221.46      6868222.88
      2717150.63      6868058.69
#Sta/Elev= 30
  4694.0  406.09  4699.5  405.69  4718.6  405.61  4723.9  405.03  4740.9  404.60
  4762.4  403.54  4794.6  402.87  4808.1  402.15  4848.3  401.19  4857.1  401.24
  4880.5  399.78  4911.4  398.75  4934.2  397.59  4971.1  398.27  4992.9  397.32
  4993.2  396.82  4996.7  396.82  4996.9  397.32  5000.9  397.61  5009.5  397.38
  5019.0  397.73  5071.4  401.49  5076.9  401.50  5095.0  402.54  5100.4  402.49
  5107.5  403.18  5140.2  404.05  5147.4  404.57  5152.9  404.31  5175.4  405.24
#Mann=3,-1,0
  4694.0    0.05       0  4992.9    0.04       0  4996.9    0.05       0
Bank Sta=4992.9,4996.9
Exp/Cntr=0.3,0.1

Type RM Length L Ch R = 1,1017,107,107,107
BEGIN DESCRIPTION:
Lacy 134 78
END DESCRIPTION:
XS GIS Cut Line= 3
      2717425.99      6868460.97      2717376.00      6868211.00
      2717275.99      6867960.98
#Sta/Elev= 30
  4744.3  405.78  4815.7  402.86  4846.2  402.04  4856.4  402.03  4866.6  401.61
  4876.8  400.89  4927.8  398.50  4958.4  396.13  4989.0  396.03  4996.7  395.53
  5006.6  395.38  5006.9  394.88  5010.4  394.88  5010.6  395.38  5014.0  395.78
  5031.5  395.66  5043.6  396.34  5053.1  396.21  5062.5  397.81  5074.6  399.43
  5128.5  401.32  5146.0  401.72  5151.3  402.61  5170.2  403.15  5214.6  405.33
  5229.4  405.70  5236.2  406.20  5246.9  406.32  5253.7  406.90  5268.5  407.31
#Mann=3,-1,0
  4744.3    0.05       0  5006.6    0.04       0  5010.6    0.05       0
Bank Sta=5006.6,5010.6
Exp/Cntr=0.3,0.1

Type RM Length L Ch R = 1,910,147,147,147
BEGIN DESCRIPTION:
Lacy 134 1161
END DESCRIPTION:
XS GIS Cut Line= 3
      2717547.18      6868368.03      2717482.08      6868202.91
      2717403.50      6867964.41
#Sta/Elev= 30
  4822.5  403.21  4842.8  402.17  4867.1  401.84  4873.1  401.39  4891.5  400.80
  4896.9  401.14  4915.9  400.65  4921.3  400.10  4937.6  399.54  4951.0  398.52
  4959.1  397.16  4975.4  395.20  4980.8  394.99  4991.3  393.74  4998.3  392.47
  5003.4  392.42  5003.6  391.92  5007.1  391.92  5007.4  392.42  5012.5  393.97
  5031.9  394.90  5054.6  396.73  5095.4  397.35  5107.3  398.04  5127.2  398.20
  5181.0  400.36  5190.7  400.52  5202.1  401.38  5233.6  402.99  5251.1  403.62
#Mann=3,-1,0
  4822.5    0.05       0  5003.4    0.05       0  5007.4    0.05       0
Bank Sta=5003.4,5007.4
Exp/Cntr=0.3,0.1

Type RM Length L Ch R = 1,763,169,169,169
BEGIN DESCRIPTION:
Lacy 134 1160
END DESCRIPTION:
XS GIS Cut Line= 3
      2717668.48      6868313.54      2717605.25      6868131.41
      2717536.70      6867871.91
#Sta/Elev= 30
  4807.2  400.56  4827.9  399.93  4833.2  400.23  4859.0  398.53  4864.3  399.23
  4875.2  398.52  4890.1  398.03  4905.2  397.92  4921.3  397.08  4926.6  397.26
  4936.9  397.10  4947.1  396.54  4952.4  396.60  4968.7  394.52  4976.2  391.35
  4976.5  390.85  4980.0  390.85  4980.2  391.35  4989.8  393.68  5021.5  393.60
  5031.4  394.50  5041.8  395.02  5082.1  395.61  5145.2  397.40  5186.6  399.15
  5207.3  399.51  5228.0  401.55  5247.5  401.89  5252.7  403.02  5268.4  403.49
#Mann=5,-1,0
  4807.2    0.05       0  4875.2    0.12       0  4976.2    0.07       0
  4980.2    0.12       0  5082.1    0.05       0
Bank Sta=4976.2,4980.2
Exp/Cntr=0.3,0.1

Type RM Length L Ch R = 1,594,56,56,56
BEGIN DESCRIPTION:
Lacy 134 1158
END DESCRIPTION:
XS GIS Cut Line= 3
      2717705.72      6868302.15      2717767.90      6868111.12
      2717667.11      6867844.75
#Sta/Elev= 30
  4799.1  399.41  4842.4  398.91  4848.1  398.43  4852.8  398.45  4880.0  396.63
  4905.5  395.36  4943.8  394.09  4949.1  394.48  4958.1  393.88  4968.6  393.73
  4981.0  392.80  5002.7  393.60  5015.8  391.53  5016.1  391.03  5019.6  391.03
  5019.8  391.53  5023.2  392.92  5042.7  392.77  5059.0  393.24  5096.4  393.67
  5117.7  394.39  5133.2  394.46  5139.1  394.04  5149.8  393.98  5158.0  394.53
  5181.9  395.11  5218.3  396.76  5248.5  397.70  5256.7  398.28  5284.8  398.79
#Mann=5,-1,0
  4799.1    0.05       0  4852.8    0.12       0  5015.8    0.07       0
  5019.8    0.12       0  5059.0    0.05       0
Bank Sta=5015.8,5019.8
Exp/Cntr=0.3,0.1

Type RM Length L Ch R = 1,538,0,0,0
BEGIN DESCRIPTION:
Lacy 134 1159
END DESCRIPTION:
XS GIS Cut Line= 3
      2717772.43      6868262.85      2717824.53      6868107.45
      2717711.87      6867804.84
#Sta/Elev= 30
  4836.1  397.06  4847.1  397.09  4858.5  397.29  4869.7  396.39  4890.0  396.04
  4901.3  395.12  4943.5  393.56  4975.2  393.17  4984.7  391.97  4987.9  390.99
  4988.2  390.49  4991.7  390.49  4991.9  390.99  4995.5  392.99  5011.2  393.14
  5017.6  391.29  5028.2  392.86  5041.5  393.72  5053.5  393.25  5081.6  393.16
  5102.9  393.73  5113.6  393.36  5127.2  393.75  5134.9  393.57  5177.2  394.15
  5268.2  396.21  5273.6  396.60  5293.2  397.14  5305.7  398.03  5322.9  398.18
#Mann=5,-1,0
  4836.1    0.05       0  4847.1    0.12       0  4987.9    0.07       0
  4991.9    0.12       0  5053.5    0.05       0
Bank Sta=4987.9,4991.9
Exp/Cntr=0.3,0.1

Chan Stop Cuts=-1