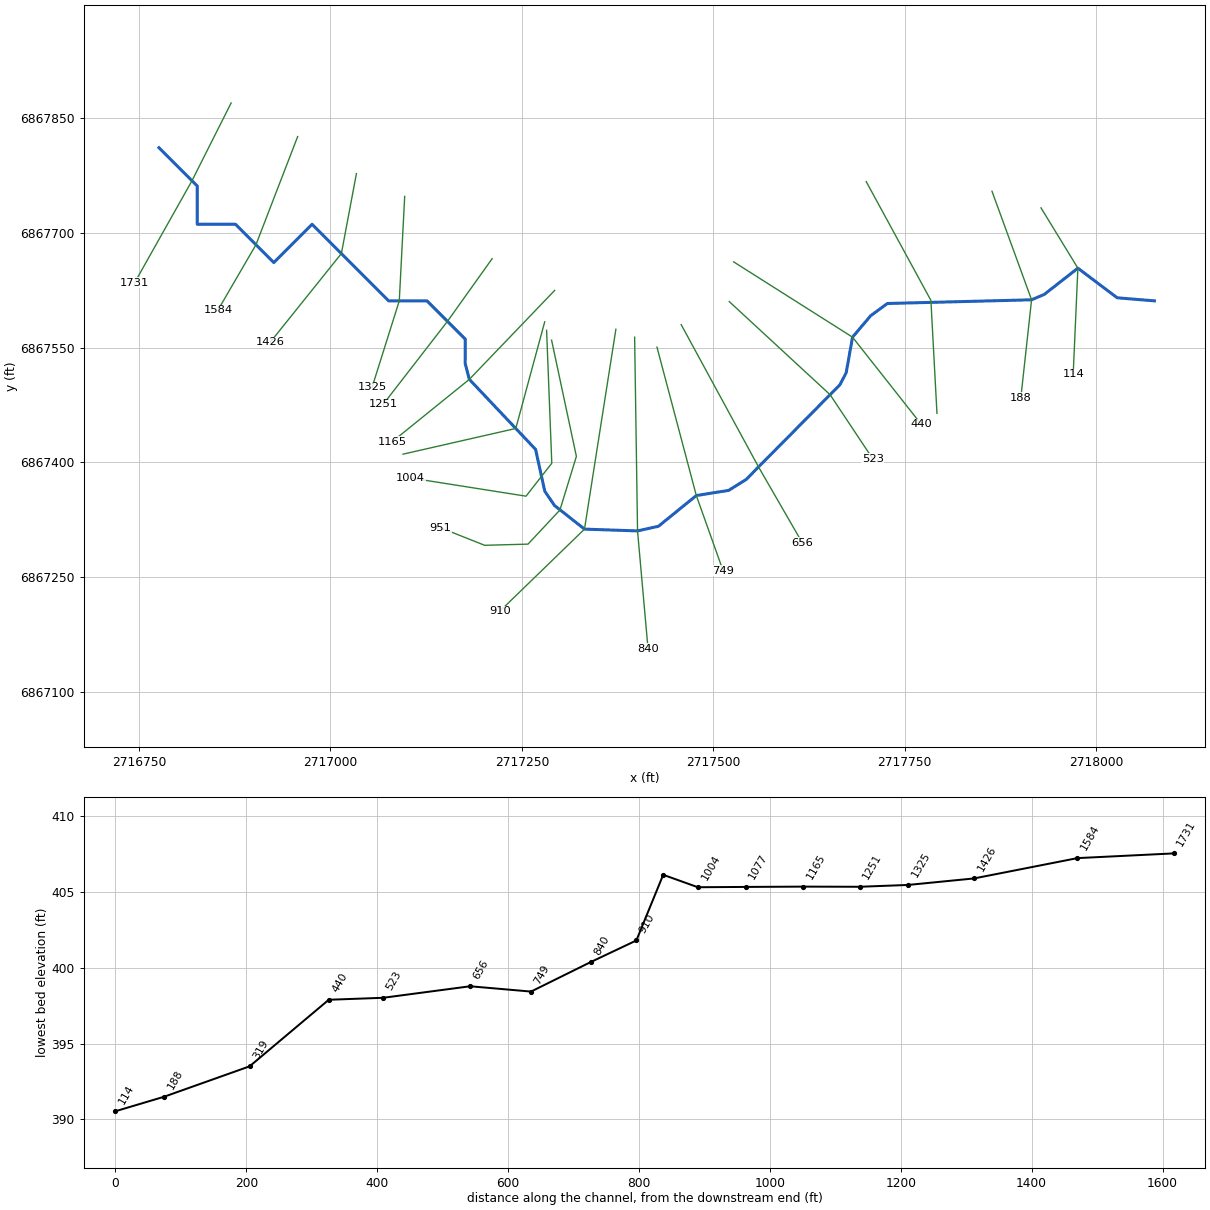
--- Lacy 135.prj (project) ---

Proj Title=Lacy 135 Base Level Engineering
Current Plan=p01
Default Exp/Contr=0.3,0.1
English Units
Geom File=g01
Flow File=f01
Plan File=p01
BEGIN DESCRIPTION:
Lacy 135
END DESCRIPTION:

--- Lacy 135.p01 (plan) ---

Plan Title=Multiple Run
Short Identifier=Multiple
Geom File=g01
Flow File=f01
Subcritical Flow
K Sum by GR= 0
Std Step Tol= 0.01
Critical Tol= 0.01
Num of Std Step Trials= 20
Max Error Tol= 0.3
Flow Tol Ratio= 0.001
Split Flow NTrial= 30
Split Flow Tol= 0.02
Split Flow Ratio= 0.02
Log Output Level= 0
Friction Slope Method= 1
Unsteady Friction Slope Method= 2
Unsteady Bridges Friction Slope Method= 1
Parabolic Critical Depth
Global Vel Dist=  1 , 1 , 1
Global Log Level= 0
CheckData=True
Encroach Param= -1, 0, 0, 0
BEGIN DESCRIPTION:
Multiple Run
END DESCRIPTION:

--- Lacy 135.f01 (steady flow) ---

Flow Title=Multiple
Number of Profiles=7
Profile Names=10-year,25-year,50-year,1pct_min,100-year,1pct_plu,500-year
River Rch & RM= Lacy 135,Reach-1,1731
      39      42      44      23      46      92      49
Boundary for River Rch & Prof#=Lacy 135,Reach-1,1
Up Type=0
Dn Type=3
Dn Slope=0.005
Boundary for River Rch & Prof#=Lacy 135,Reach-1,2
Up Type=0
Dn Type=3
Dn Slope=0.005
Boundary for River Rch & Prof#=Lacy 135,Reach-1,3
Up Type=0
Dn Type=3
Dn Slope=0.005
Boundary for River Rch & Prof#=Lacy 135,Reach-1,4
Up Type=0
Dn Type=3
Dn Slope=0.005
Boundary for River Rch & Prof#=Lacy 135,Reach-1,5
Up Type=0
Dn Type=3
Dn Slope=0.005
Boundary for River Rch & Prof#=Lacy 135,Reach-1,6
Up Type=0
Dn Type=3
Dn Slope=0.005
Boundary for River Rch & Prof#=Lacy 135,Reach-1,7
Up Type=0
Dn Type=3
Dn Slope=0.005

--- Lacy 135.g01 (geometry) ---

Geom Title=Existing Conditions

River Reach=Lacy 135,Reach-1
Reach XY= 30
      2716776.00      6867811.00      2716826.00      6867761.00
      2716826.00      6867711.00      2716876.00      6867711.00
      2716926.00      6867661.00      2716976.00      6867711.00
      2717076.00      6867611.00      2717126.00      6867611.00
      2717176.00      6867561.00      2717175.93      6867529.12
      2717181.33      6867508.49      2717267.83      6867417.03
      2717279.87      6867362.40      2717292.46      6867343.85
      2717331.71      6867312.89      2717400.99      6867310.57
      2717428.32      6867316.64      2717477.75      6867356.78
      2717519.97      6867363.49      2717542.68      6867377.64
      2717665.21      6867501.34      2717673.45      6867517.09
      2717681.74      6867563.58      2717705.45      6867591.56
      2717727.25      6867607.55      2717915.57      6867612.37
      2717932.19      6867619.43      2717976.04      6867653.69
      2718027.36      6867615.00      2718076.00      6867611.00

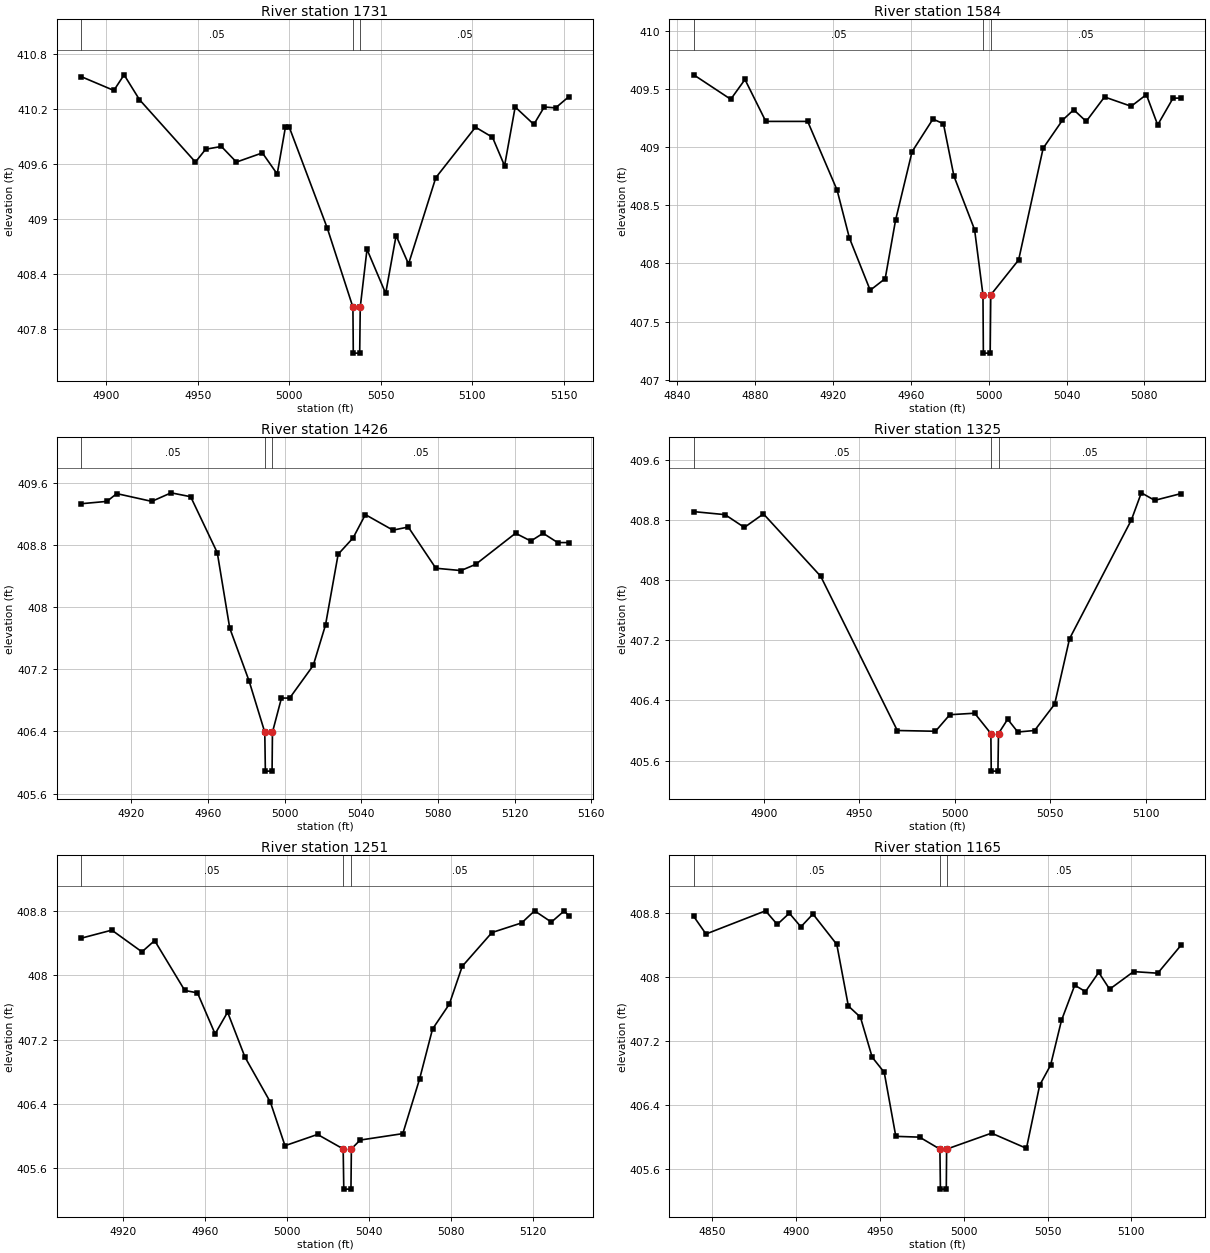
Type RM Length L Ch R = 1,1731,147,147,147
BEGIN DESCRIPTION:
Lacy 135 3443
END DESCRIPTION:
XS GIS Cut Line= 3
      2716870.25      6867869.43      2716819.14      6867767.86
      2716744.27      6867634.78
#Sta/Elev= 30
  4886.3  410.55  4904.1  410.40  4909.7  410.57  4918.1  410.30  4948.7  409.62
  4954.3  409.76  4962.9  409.79  4971.1  409.62  4985.3  409.72  4993.4  409.49
  4997.9  410.00  5000.0  410.00  5020.8  408.90  5034.8  408.04  5035.0  407.54
  5038.5  407.54  5038.8  408.04  5042.5  408.67  5052.7  408.19  5058.4  408.82
  5065.2  408.51  5080.1  409.45  5101.8  410.00  5111.1  409.89  5117.7  409.58
  5123.5  410.22  5133.7  410.03  5139.4  410.22  5145.6  410.21  5152.7  410.33
#Mann=3,-1,0
  4886.3    0.05       0  5034.8    0.05       0  5038.8    0.05       0
Bank Sta=5034.8,5038.8
Exp/Cntr=0.3,0.1

Type RM Length L Ch R = 1,1584,158,158,158
BEGIN DESCRIPTION:
Lacy 135 3438
END DESCRIPTION:
XS GIS Cut Line= 3
      2716957.14      6867825.57      2716902.70      6867684.30
      2716853.02      6867598.89
#Sta/Elev= 30
  4848.6  409.62  4867.6  409.41  4874.9  409.58  4885.6  409.22  4907.1  409.22
  4922.2  408.63  4928.5  408.22  4939.2  407.77  4946.9  407.87  4952.2  408.37
  4960.7  408.96  4971.4  409.24  4976.8  409.20  4982.2  408.75  4992.8  408.29
  4997.1  407.73  4997.3  407.23  5000.8  407.23  5001.1  407.73  5015.4  408.03
  5028.0  408.99  5037.9  409.23  5043.7  409.32  5050.1  409.22  5059.5  409.43
  5073.2  409.35  5081.0  409.45  5086.8  409.19  5094.7  409.42  5098.8  409.42
#Mann=3,-1,0
  4848.6    0.05       0  4997.1    0.04       0  5001.1    0.05       0
Bank Sta=4997.1,5001.1
Exp/Cntr=0.3,0.1

Type RM Length L Ch R = 1,1426,101,101,101
BEGIN DESCRIPTION:
Lacy 135 3437
END DESCRIPTION:
XS GIS Cut Line= 3
      2717033.86      6867777.13      2717014.24      6867672.76
      2716921.49      6867557.17
#Sta/Elev= 30
  4893.8  409.33  4907.2  409.36  4912.3  409.46  4930.6  409.36  4940.7  409.47
  4950.9  409.42  4964.8  408.70  4971.3  407.73  4981.4  407.05  4989.6  406.39
  4989.9  405.89  4993.4  405.89  4993.6  406.39  4998.3  406.83  5002.6  406.83
  5014.9  407.25  5021.3  407.77  5027.9  408.68  5035.7  408.89  5042.1  409.19
  5056.5  408.99  5064.5  409.03  5078.9  408.50  5092.0  408.47  5099.7  408.55
  5120.5  408.95  5128.5  408.85  5134.9  408.95  5142.5  408.83  5148.2  408.83
#Mann=3,-1,0
  4893.8    0.05       0  4989.6    0.04       0  4993.6    0.05       0
Bank Sta=4989.6,4993.6
Exp/Cntr=0.3,0.1

Type RM Length L Ch R = 1,1325,74,74,74
BEGIN DESCRIPTION:
Lacy 135 3436
END DESCRIPTION:
XS GIS Cut Line= 3
      2717096.92      6867747.42      2717089.85      6867611.00
      2717054.24      6867497.87
#Sta/Elev= 22
  4863.4  408.91  4879.8  408.87  4889.9  408.70  4899.9  408.88  4929.9  408.05
  4970.0  406.00  4990.0  405.99  4997.5  406.21  5010.5  406.23  5019.0  405.96
  5019.2  405.46  5022.7  405.46  5023.0  405.96  5027.8  406.15  5033.1  405.98
  5041.9  406.00  5052.4  406.35  5060.2  407.22  5092.6  408.80  5097.8  409.16
  5104.8  409.06  5118.6  409.15
#Mann=3,-1,0
  4863.4    0.05       0  5019.0    0.04       0  5023.0    0.05       0
Bank Sta=5019,5023
Exp/Cntr=0.3,0.1

Type RM Length L Ch R = 1,1251,86,86,86
BEGIN DESCRIPTION:
Lacy 135 3434
END DESCRIPTION:
XS GIS Cut Line= 3
      2717211.10      6867666.07      2717152.76      6867584.24
      2717068.68      6867475.70
#Sta/Elev= 28
  4899.5  408.46  4914.4  408.56  4929.1  408.29  4935.3  408.43  4950.0  407.81
  4956.2  407.78  4964.8  407.27  4970.9  407.54  4979.4  406.98  4991.8  406.42
  4998.9  405.88  5014.8  406.02  5027.3  405.84  5027.6  405.34  5031.1  405.34
  5031.3  405.84  5035.6  405.95  5056.4  406.03  5064.6  406.71  5070.9  407.33
  5079.1  407.64  5085.4  408.11  5099.9  408.53  5114.4  408.65  5120.7  408.80
  5128.9  408.66  5135.2  408.80  5137.3  408.74
#Mann=3,-1,0
  4899.5    0.05       0  5027.3    0.04       0  5031.3    0.05       0
Bank Sta=5027.3,5031.3
Exp/Cntr=0.3,0.1

Type RM Length L Ch R = 1,1165,88,88,88
BEGIN DESCRIPTION:
Lacy 135 1149
END DESCRIPTION:
XS GIS Cut Line= 3
      2717292.79      6867624.67      2717181.33      6867508.49
      2717080.56      6867427.00
#Sta/Elev= 30
  4839.0  408.76  4846.3  408.54  4881.8  408.83  4888.8  408.66  4896.0  408.80
  4902.9  408.63  4910.1  408.79  4924.3  408.41  4931.2  407.64  4938.4  407.50
  4945.4  407.00  4952.6  406.81  4959.5  406.01  4973.7  406.00  4985.8  405.85
  4986.1  405.35  4989.6  405.35  4989.8  405.85  5016.6  406.05  5037.4  405.86
  5045.3  406.65  5051.8  406.90  5058.3  407.46  5066.2  407.90  5072.6  407.82
  5080.5  408.06  5087.0  407.85  5101.3  408.07  5115.7  408.05  5129.6  408.40
#Mann=3,-1,0
  4839.0    0.05       0  4985.8    0.04       0  4989.8    0.05       0
Bank Sta=4985.8,4989.8
Exp/Cntr=0.3,0.1

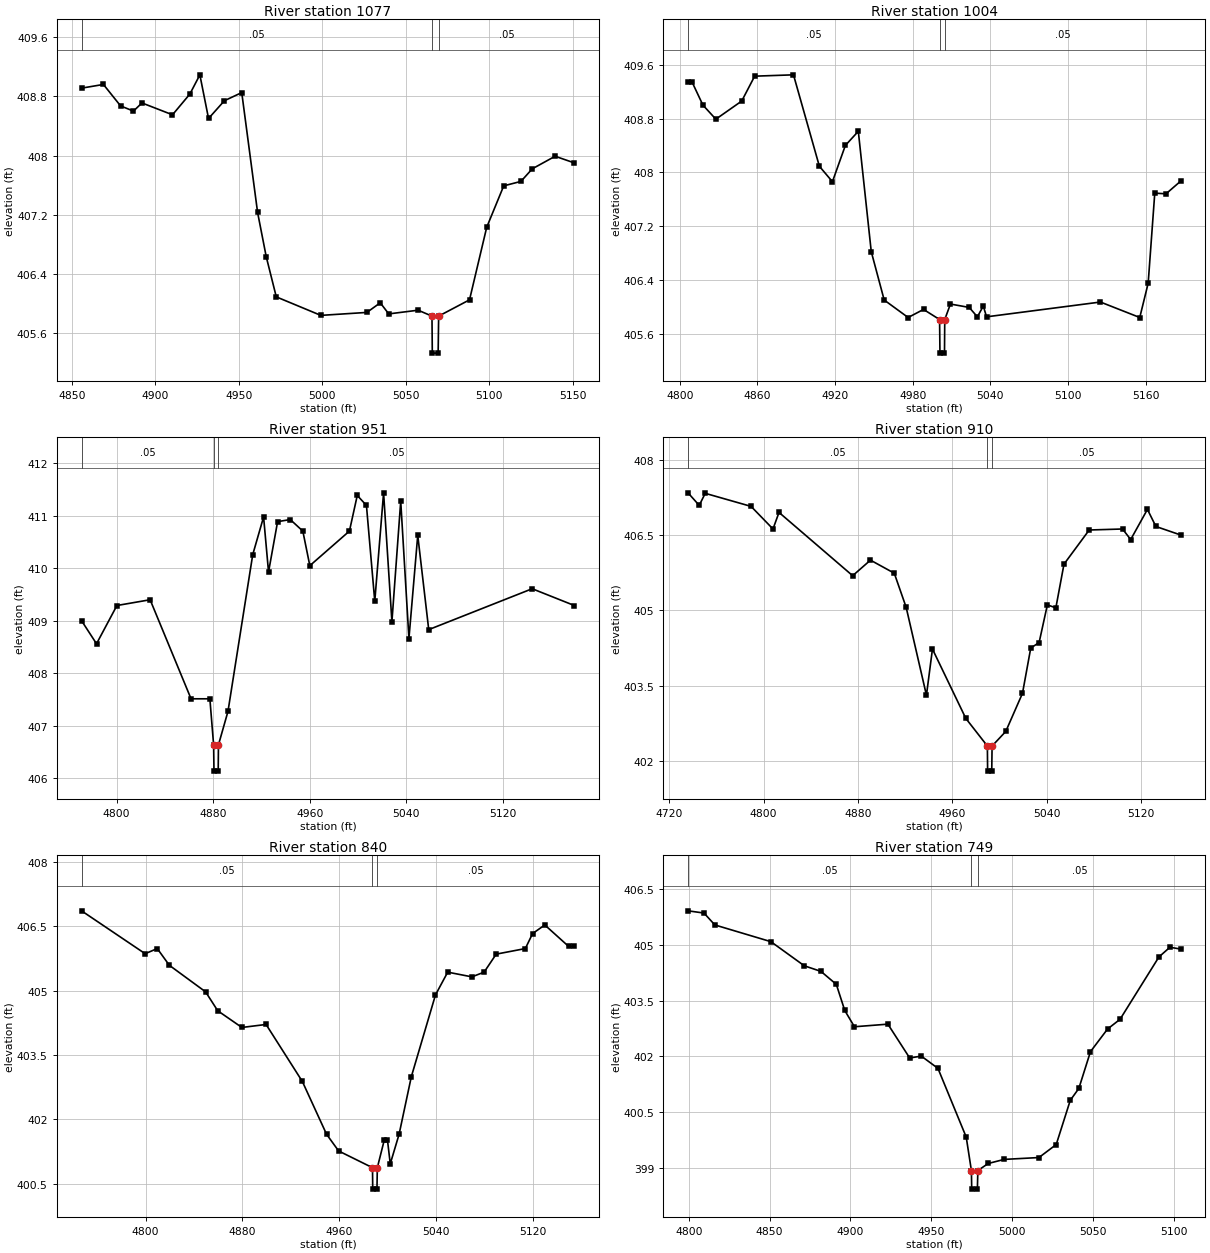
Type RM Length L Ch R = 1,1077,73,73,73
BEGIN DESCRIPTION:
Lacy 135 1148
END DESCRIPTION:
XS GIS Cut Line= 3
      2717279.77      6867583.61      2717241.99      6867444.35
      2717094.77      6867410.79
#Sta/Elev= 30
  4855.7  408.91  4868.8  408.96  4879.1  408.67  4886.8  408.60  4891.9  408.71
  4910.2  408.55  4920.6  408.83  4926.6  409.09  4931.8  408.50  4941.3  408.74
  4951.7  408.85  4961.2  407.23  4966.4  406.63  4972.4  406.09  4999.1  405.84
  5026.7  405.88  5034.7  406.01  5039.8  405.86  5057.4  405.91  5065.7  405.83
  5065.9  405.33  5069.4  405.33  5069.7  405.83  5088.2  406.05  5098.5  407.03
  5108.7  407.59  5119.0  407.65  5125.8  407.82  5139.5  407.99  5151.0  407.90
#Mann=3,-1,0
  4855.7    0.05       0  5065.7    0.04       0  5069.7    0.05       0
Bank Sta=5065.7,5069.7
Exp/Cntr=0.3,0.1

Type RM Length L Ch R = 1,1004,53,53,53
BEGIN DESCRIPTION:
Lacy 135 1147
END DESCRIPTION:
XS GIS Cut Line= 4
      2717282.24      6867572.47      2717289.01      6867398.93
      2717255.36      6867355.92      2717104.69      6867379.69
#Sta/Elev= 30
  4806.4  409.34  4809.6  409.34  4817.9  409.00  4827.9  408.79  4847.9  409.06
  4857.9  409.43  4887.9  409.45  4907.9  408.09  4918.0  407.86  4928.0  408.40
  4938.0  408.61  4948.0  406.82  4958.0  406.10  4976.5  405.84  4988.4  405.96
  5000.8  405.81  5001.1  405.31  5004.6  405.31  5004.8  405.81  5009.2  406.04
  5023.7  405.99  5030.0  405.85  5034.6  406.01  5037.1  405.85  5125.1  406.07
  5155.5  405.84  5162.0  406.35  5167.1  407.69  5175.8  407.68  5187.2  407.87
#Mann=3,-1,0
  4806.4    0.05       0  5000.8    0.04       0  5004.8    0.05       0
Bank Sta=5000.8,5004.8
Exp/Cntr=0.3,0.1

Type RM Length L Ch R = 1,951,41,41,41
BEGIN DESCRIPTION:
Lacy 135 1146
END DESCRIPTION:
XS GIS Cut Line= 6
      2717288.75      6867559.66      2717321.13      6867407.85
      2717299.65      6867337.88      2717257.96      6867293.32
      2717201.40      6867291.77      2717143.60      6867314.69
#Sta/Elev= 30
  4770.9  409.00  4783.3  408.56  4800.2  409.29  4827.7  409.40  4861.6  407.51
  4877.2  407.51  4880.3  406.63  4880.6  406.13  4884.1  406.13  4884.3  406.63
  4892.2  407.27  4912.7  410.26  4921.7  410.98  4925.8  409.93  4933.3  410.89
  4943.8  410.93  4954.2  410.71  4960.0  410.05  4992.8  410.71  4999.3  411.39
  5006.9  411.20  5013.8  409.37  5021.1  411.44  5028.0  408.98  5035.3  411.28
  5042.1  408.66  5049.4  410.63  5058.5  408.83  5144.2  409.61  5179.1  409.29
#Mann=3,-1,0
  4770.9    0.05       0  4880.3    0.04       0  4884.3    0.05       0
Bank Sta=4880.3,4884.3
Exp/Cntr=0.3,0.1

Type RM Length L Ch R = 1,910,70,70,70
BEGIN DESCRIPTION:
Lacy 135 1150
END DESCRIPTION:
XS GIS Cut Line= 3
      2717372.71      6867573.89      2717331.71      6867312.89
      2717221.23      6867205.75
#Sta/Elev= 30
  4735.8  407.34  4745.3  407.09  4750.4  407.33  4789.3  407.07  4807.9  406.62
  4813.0  406.95  4875.5  405.69  4890.6  406.00  4910.8  405.74  4920.9  405.06
  4938.1  403.31  4943.2  404.23  4971.5  402.85  4989.8  402.30  4990.0  401.80
  4993.5  401.80  4993.8  402.30  5005.4  402.59  5019.6  403.35  5026.6  404.25
  5033.7  404.36  5040.7  405.11  5047.9  405.05  5054.8  405.92  5076.2  406.60
  5104.5  406.62  5111.4  406.41  5125.6  407.01  5132.8  406.67  5153.9  406.50
#Mann=3,-1,0
  4735.8    0.05       0  4989.8    0.05       0  4993.8    0.05       0
Bank Sta=4989.8,4993.8
Exp/Cntr=0.3,0.1

Type RM Length L Ch R = 1,840,91,91,91
BEGIN DESCRIPTION:
Lacy 135 1151
END DESCRIPTION:
XS GIS Cut Line= 3
      2717397.20      6867563.55      2717400.99      6867310.57
      2717414.68      6867156.68
#Sta/Elev= 30
  4747.0  406.86  4799.6  405.86  4809.6  405.98  4819.6  405.59  4849.6  404.97
  4859.6  404.53  4879.6  404.14  4899.6  404.21  4929.6  402.88  4949.6  401.65
  4959.6  401.26  4987.6  400.87  4987.8  400.37  4991.3  400.37  4991.6  400.87
  4997.3  401.51  5000.0  401.51  5002.3  400.96  5009.6  401.65  5019.7  402.99
  5039.7  404.90  5049.8  405.43  5069.8  405.32  5079.9  405.43  5089.9  405.85
  5114.0  405.98  5120.0  406.33  5130.1  406.53  5149.8  406.03  5154.5  406.03
#Mann=3,-1,0
  4747.0    0.05       0  4987.6    0.05       0  4991.6    0.05       0
Bank Sta=4987.6,4991.6
Exp/Cntr=0.3,0.1

Type RM Length L Ch R = 1,749,93,93,93
BEGIN DESCRIPTION:
Lacy 135 1152
END DESCRIPTION:
XS GIS Cut Line= 3
      2717426.36      6867550.58      2717477.75      6867356.78
      2717512.79      6867258.33
#Sta/Elev= 30
  4799.5  405.92  4809.4  405.86  4816.1  405.54  4850.8  405.09  4871.5  404.44
  4881.8  404.29  4891.3  403.94  4896.5  403.24  4902.5  402.80  4923.2  402.87
  4936.7  401.96  4943.9  402.01  4954.2  401.68  4971.7  399.83  4974.9  398.93
  4975.1  398.43  4978.6  398.43  4978.9  398.93  4985.3  399.12  4995.2  399.23
  5016.7  399.28  5027.4  399.63  5036.1  400.82  5041.4  401.14  5048.6  402.13
  5059.2  402.74  5066.9  403.00  5091.0  404.68  5097.8  404.94  5104.5  404.89
#Mann=3,-1,0
  4799.5    0.05       0  4974.9    0.05       0  4978.9    0.05       0
Bank Sta=4974.9,4978.9
Exp/Cntr=0.3,0.1

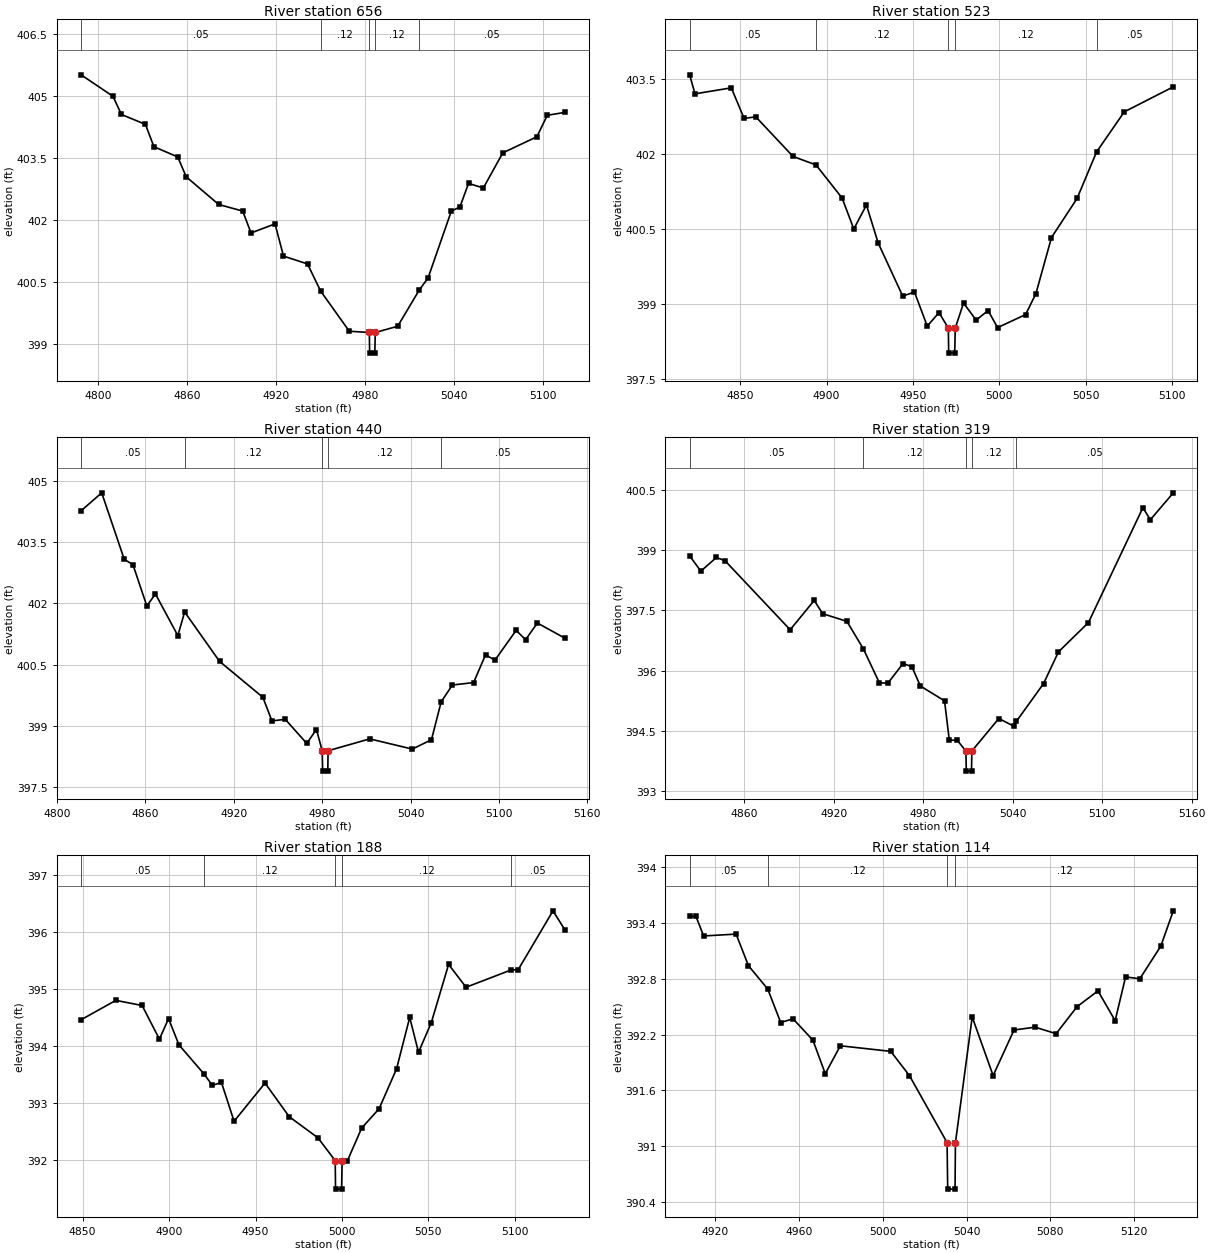
Type RM Length L Ch R = 1,656,133,133,133
BEGIN DESCRIPTION:
Lacy 135 1145
END DESCRIPTION:
XS GIS Cut Line= 3
      2717458.00      6867579.94      2717558.99      6867394.11
      2717616.30      6867294.75
#Sta/Elev= 30
  4788.5  405.52  4810.0  405.00  4815.7  404.56  4831.9  404.32  4837.6  403.78
  4853.7  403.53  4859.4  403.05  4881.3  402.38  4897.5  402.22  4903.1  401.69
  4919.3  401.91  4925.0  401.13  4941.2  400.94  4950.1  400.28  4969.4  399.31
  4982.9  399.28  4983.1  398.78  4986.6  398.78  4986.9  399.28  5002.0  399.43
  5016.6  400.31  5022.5  400.60  5038.2  402.22  5044.0  402.32  5049.8  402.89
  5059.8  402.78  5072.9  403.63  5095.9  404.02  5102.9  404.54  5114.7  404.61
#Mann=5,-1,0
  4788.5    0.05       0  4950.1    0.12       0  4982.9    0.07       0
  4986.9    0.12       0  5016.6    0.05       0
Bank Sta=4982.9,4986.9
Exp/Cntr=0.3,0.1

Type RM Length L Ch R = 1,523,83,83,83
BEGIN DESCRIPTION:
Lacy 135 1144
END DESCRIPTION:
XS GIS Cut Line= 3
      2717520.79      6867610.02      2717652.44      6867488.44
      2717708.24      6867404.62
#Sta/Elev= 30
  4820.8  403.58  4823.9  403.20  4844.9  403.32  4852.3  402.71  4859.1  402.74
  4880.6  401.95  4893.9  401.78  4909.0  401.12  4915.8  400.50  4923.1  400.98
  4929.9  400.22  4944.1  399.16  4950.9  399.24  4958.3  398.56  4965.1  398.83
  4970.5  398.52  4970.7  398.02  4974.2  398.02  4974.5  398.52  4979.3  399.02
  4986.6  398.68  4993.5  398.87  4999.0  398.53  5015.2  398.79  5021.2  399.21
  5030.2  400.33  5045.0  401.11  5056.3  402.04  5072.3  402.84  5100.7  403.34
#Mann=5,-1,0
  4820.8    0.05       0  4893.9    0.12       0  4970.5    0.07       0
  4974.5    0.12       0  5056.3    0.05       0
Bank Sta=4970.5,4974.5
Exp/Cntr=0.3,0.1

Type RM Length L Ch R = 1,440,121,121,121
BEGIN DESCRIPTION:
Lacy 135 1143
END DESCRIPTION:
XS GIS Cut Line= 3
      2717526.55      6867661.88      2717681.74      6867563.58
      2717771.34      6867449.95
#Sta/Elev= 30
  4816.3  404.27  4830.3  404.71  4845.6  403.08  4851.5  402.95  4860.9  401.94
  4866.8  402.23  4882.0  401.21  4886.6  401.79  4910.3  400.58  4939.7  399.70
  4945.9  399.12  4954.9  399.16  4969.5  398.57  4976.1  398.91  4980.0  398.39
  4980.3  397.89  4983.8  397.89  4984.0  398.39  5012.3  398.68  5041.2  398.43
  5054.2  398.66  5060.8  399.59  5068.4  400.00  5082.8  400.06  5090.9  400.74
  5097.3  400.61  5111.7  401.34  5118.1  401.11  5126.1  401.52  5144.7  401.15
#Mann=5,-1,0
  4816.3    0.05       0  4886.6    0.12       0  4980.0    0.07       0
  4984.0    0.12       0  5060.8    0.05       0
Bank Sta=4980,4984
Exp/Cntr=0.3,0.1

Type RM Length L Ch R = 1,319,131,131,131
BEGIN DESCRIPTION:
Lacy 135 1142
END DESCRIPTION:
XS GIS Cut Line= 3
      2717699.62      6867766.70      2717784.10      6867611.62
      2717792.01      6867464.13
#Sta/Elev= 30
  4823.4  398.86  4830.9  398.48  4841.3  398.82  4847.1  398.74  4890.8  397.02
  4906.9  397.75  4912.6  397.42  4928.8  397.23  4939.8  396.55  4950.6  395.70
  4956.3  395.69  4966.5  396.18  4972.4  396.10  4978.1  395.62  4994.3  395.25
  4997.5  394.27  5002.8  394.27  5008.6  394.00  5008.9  393.50  5012.4  393.50
  5012.6  394.00  5030.7  394.81  5040.7  394.62  5042.5  394.74  5060.7  395.68
  5070.7  396.47  5090.8  397.20  5127.3  400.06  5132.3  399.76  5147.7  400.43
#Mann=5,-1,0
  4823.4    0.05       0  4939.8    0.12       0  5008.6    0.07       0
  5012.6    0.12       0  5042.5    0.05       0
Bank Sta=5008.6,5012.6
Exp/Cntr=0.3,0.1

Type RM Length L Ch R = 1,188,74,74,74
BEGIN DESCRIPTION:
Lacy 135 1141
END DESCRIPTION:
XS GIS Cut Line= 3
      2717863.87      6867754.14      2717915.57      6867612.37
      2717901.51      6867484.24
#Sta/Elev= 30
  4849.1  394.46  4869.2  394.80  4884.4  394.71  4894.4  394.12  4899.7  394.48
  4905.7  394.02  4920.2  393.51  4925.0  393.31  4930.3  393.36  4937.6  392.68
  4955.5  393.35  4969.5  392.76  4986.1  392.39  4996.1  391.99  4996.3  391.49
  4999.8  391.49  5000.1  391.99  5003.2  391.99  5011.4  392.56  5021.5  392.90
  5031.6  393.60  5039.2  394.50  5044.3  393.89  5051.7  394.41  5061.7  395.43
  5071.8  395.03  5097.6  395.33  5102.0  395.34  5122.1  396.37  5128.9  396.04
#Mann=5,-1,0
  4849.1    0.05       0  4920.2    0.12       0  4996.1    0.07       0
  5000.1    0.12       0  5097.6    0.05       0
Bank Sta=4996.1,5000.1
Exp/Cntr=0.3,0.1

Type RM Length L Ch R = 1,114,0,0,0
BEGIN DESCRIPTION:
Lacy 135 1140
END DESCRIPTION:
XS GIS Cut Line= 3
      2717927.89      6867732.43      2717976.04      6867653.69
      2717969.91      6867515.02
#Sta/Elev= 29
  4907.7  393.47  4910.7  393.47  4914.4  393.26  4929.9  393.28  4935.8  392.94
  4945.0  392.69  4951.2  392.33  4957.1  392.37  4966.6  392.14  4972.5  391.78
  4979.7  392.08  5003.8  392.02  5012.7  391.76  5030.7  391.04  5031.0  390.54
  5034.5  390.54  5034.7  391.04  5042.7  392.39  5052.7  391.76  5062.7  392.25
  5072.8  392.28  5082.8  392.21  5092.8  392.50  5102.8  392.67  5111.0  392.35
  5116.0  392.82  5122.8  392.80  5132.8  393.15  5138.8  393.53
#Mann=4,-1,0
  4907.7    0.05       0  4945.0    0.12       0  5030.7    0.07       0
  5034.7    0.12       0
Bank Sta=5030.7,5034.7
Exp/Cntr=0.3,0.1

Chan Stop Cuts=-1