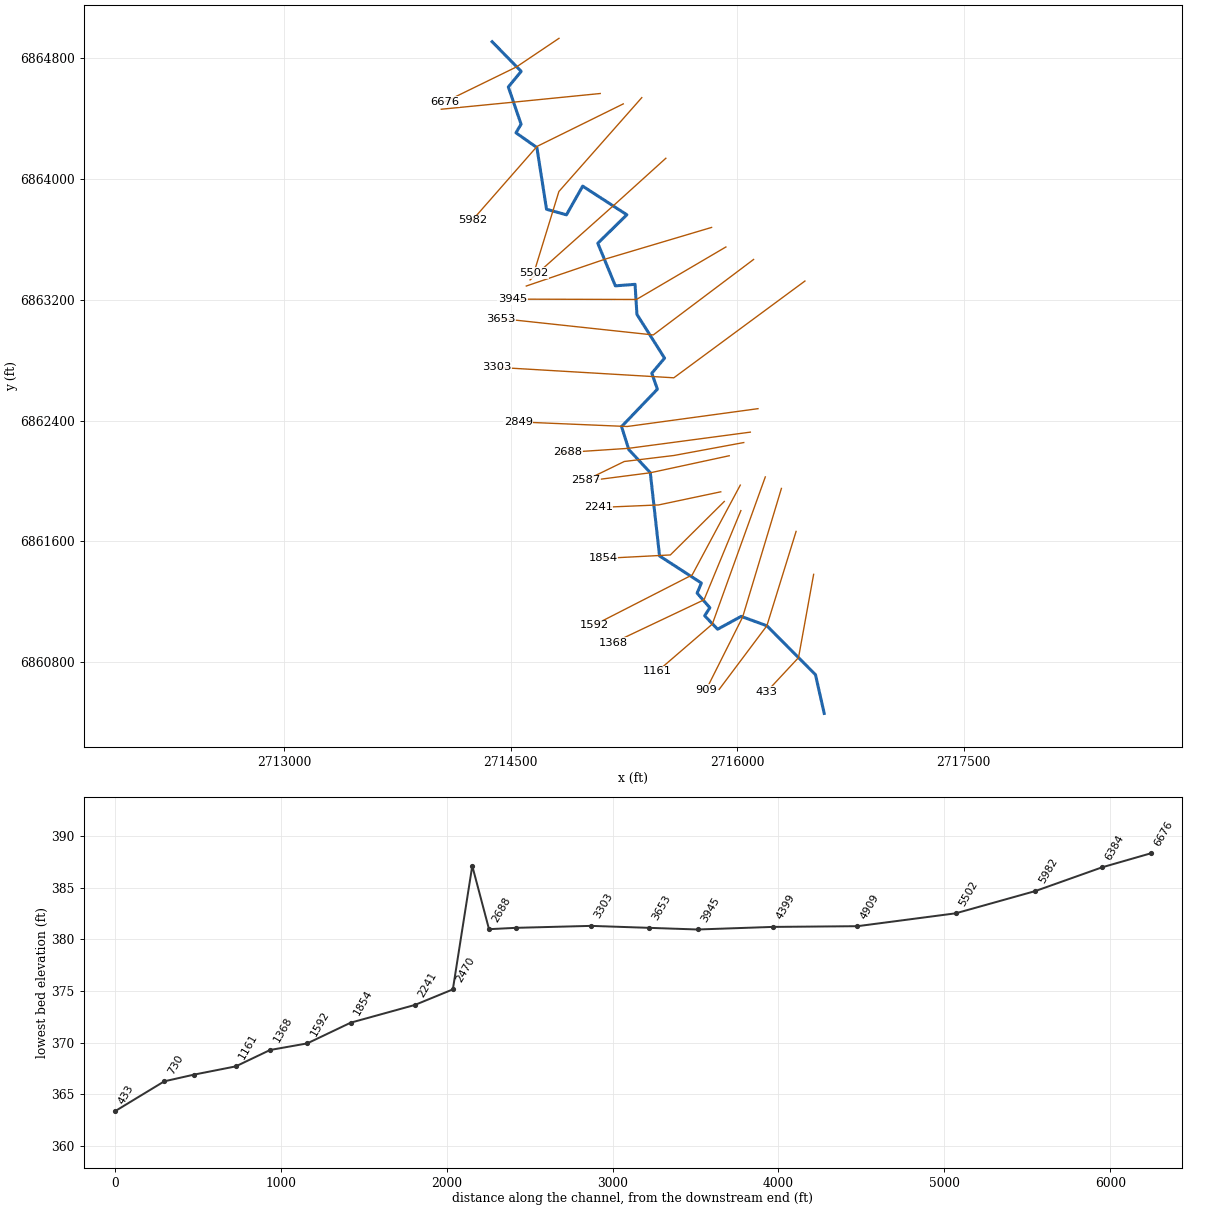
--- Lacy 136.prj (project) ---

Proj Title=Lacy 136 Base Level Engineering
Current Plan=p01
Default Exp/Contr=0.3,0.1
English Units
Geom File=g01
Flow File=f01
Plan File=p01
BEGIN DESCRIPTION:
Lacy 136
END DESCRIPTION:

--- Lacy 136.p01 (plan) ---

Plan Title=Multiple Run
Short Identifier=Multiple
Geom File=g01
Flow File=f01
Subcritical Flow
K Sum by GR= 0
Std Step Tol= 0.01
Critical Tol= 0.01
Num of Std Step Trials= 20
Max Error Tol= 0.3
Flow Tol Ratio= 0.001
Split Flow NTrial= 30
Split Flow Tol= 0.02
Split Flow Ratio= 0.02
Log Output Level= 0
Friction Slope Method= 1
Unsteady Friction Slope Method= 2
Unsteady Bridges Friction Slope Method= 1
Parabolic Critical Depth
Global Vel Dist=  1 , 1 , 1
Global Log Level= 0
CheckData=True
Encroach Param= -1, 0, 0, 0
BEGIN DESCRIPTION:
Multiple Run
END DESCRIPTION:

--- Lacy 136.f01 (steady flow) ---

Flow Title=Multiple
Number of Profiles=7
Profile Names=10-year,25-year,50-year,1pct_min,100-year,1pct_plu,500-year
River Rch & RM= Lacy 136,Reach-1,6676
     541     714     850     502    1002    1999    1390
Boundary for River Rch & Prof#=Lacy 136,Reach-1,1
Up Type=0
Dn Type=3
Dn Slope=0.005
Boundary for River Rch & Prof#=Lacy 136,Reach-1,2
Up Type=0
Dn Type=3
Dn Slope=0.005
Boundary for River Rch & Prof#=Lacy 136,Reach-1,3
Up Type=0
Dn Type=3
Dn Slope=0.005
Boundary for River Rch & Prof#=Lacy 136,Reach-1,4
Up Type=0
Dn Type=3
Dn Slope=0.005
Boundary for River Rch & Prof#=Lacy 136,Reach-1,5
Up Type=0
Dn Type=3
Dn Slope=0.005
Boundary for River Rch & Prof#=Lacy 136,Reach-1,6
Up Type=0
Dn Type=3
Dn Slope=0.005
Boundary for River Rch & Prof#=Lacy 136,Reach-1,7
Up Type=0
Dn Type=3
Dn Slope=0.005

--- Lacy 136.g01 (geometry) ---

Geom Title=Existing Conditions

River Reach=Lacy 136,Reach-1
Reach XY= 30
      2714376.00      6864911.00      2714568.39      6864714.33
      2714483.34      6864611.10      2714567.71      6864364.21
      2714533.89      6864307.42      2714672.55      6864209.75
      2714736.37      6863800.83      2714868.28      6863764.00
      2714975.98      6863953.92      2715268.42      6863764.35
      2715076.02      6863575.48      2715192.45      6863293.36
      2715322.84      6863303.39      2715335.31      6863104.34
      2715518.38      6862814.33      2715433.85      6862714.41
      2715470.89      6862608.70      2715233.53      6862361.01
      2715281.52      6862208.57      2715423.82      6862055.55
      2715485.18      6861504.05      2715762.36      6861324.36
      2715734.03      6861257.67      2715818.41      6861161.00
      2715784.00      6861107.65      2715869.92      6861018.46
      2716025.90      6861103.67      2716196.15      6861041.37
      2716518.18      6860717.19      2716576.00      6860461.00

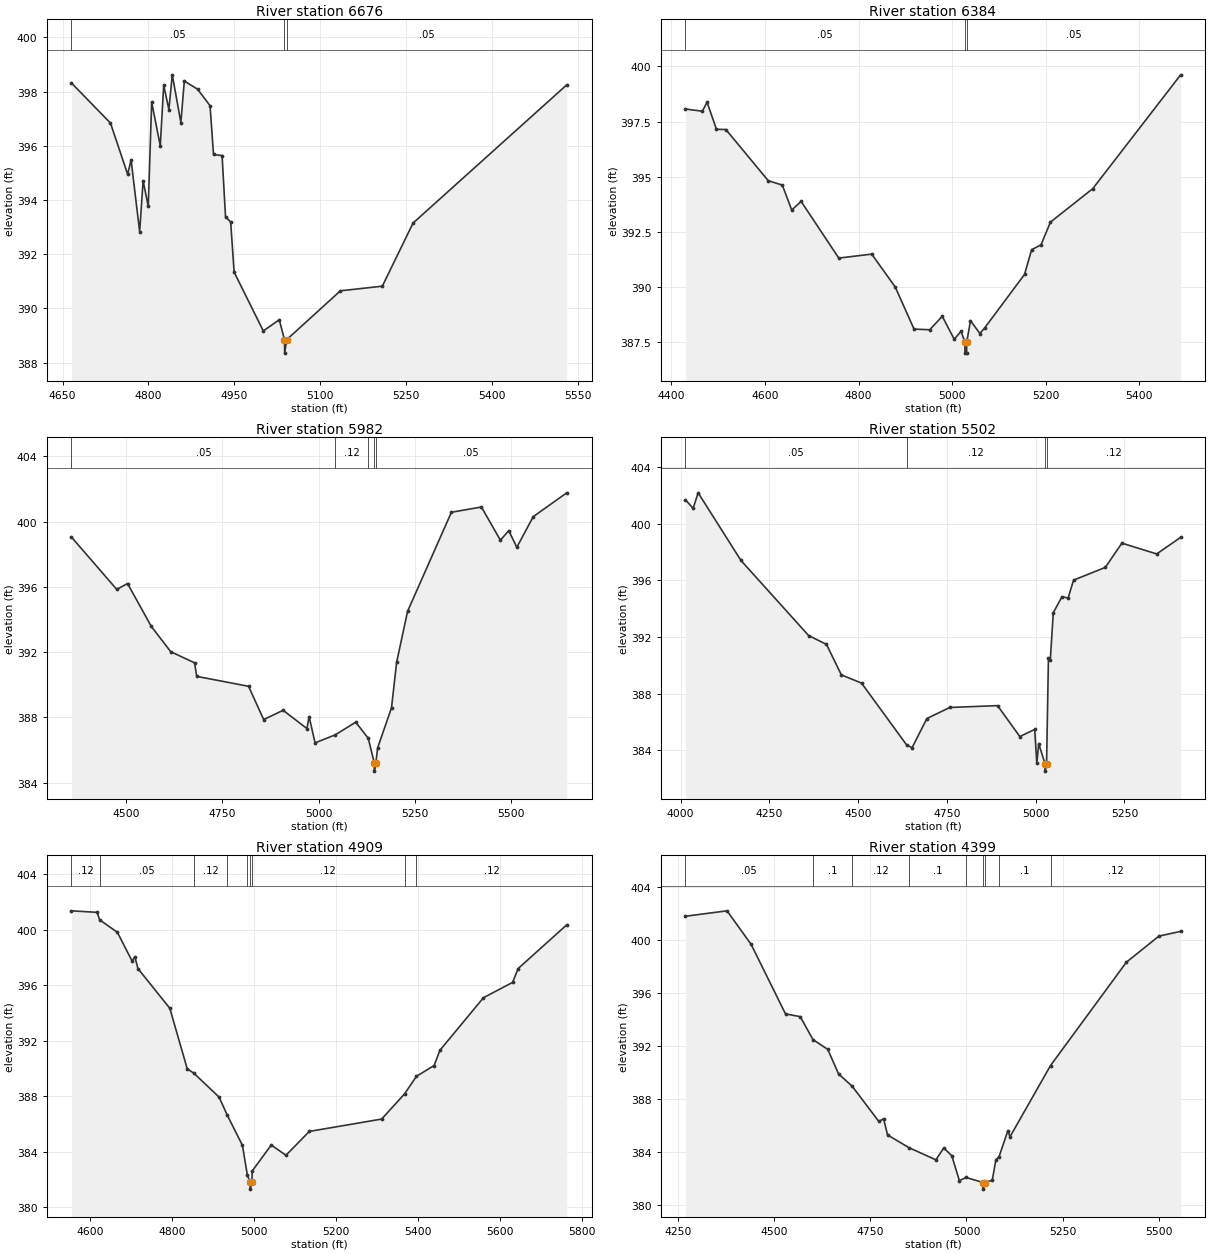
Type RM Length L Ch R = 1,6676,292,292,292
BEGIN DESCRIPTION:
Lacy 136 1120
END DESCRIPTION:
XS GIS Cut Line= 3
      2714818.92      6864933.19      2714536.58      6864743.37
      2714064.72      6864513.02
#Sta/Elev= 30
  4665.5  398.32  4733.7  396.84  4763.7  394.95  4769.7  395.48  4784.7  392.83
  4790.7  394.71  4799.7  393.77  4805.7  397.61  4820.7  396.00  4826.7  398.24
  4835.7  397.34  4841.7  398.62  4856.7  396.86  4862.7  398.39  4885.9  398.09
  4907.7  397.48  4913.7  395.68  4928.7  395.64  4934.7  393.38  4943.7  393.19
  4949.7  391.34  5000.7  389.17  5028.6  389.58  5037.7  388.85  5038.0  388.35
  5041.7  388.85  5135.4  390.65  5208.6  390.82  5262.3  393.15  5530.8  398.25
#Mann=3,-1,0
  4665.5    0.05       0  5037.7    0.04       0  5041.7    0.05       0
Bank Sta=5037.7,5041.7
Exp/Cntr=0.3,0.1

Type RM Length L Ch R = 1,6384,402,402,402
BEGIN DESCRIPTION:
Lacy 136 1119
END DESCRIPTION:
XS GIS Cut Line= 3
      2715092.21      6864567.67      2714520.06      6864510.58
      2714039.15      6864463.49
#Sta/Elev= 30
  4429.9  398.07  4466.3  397.97  4476.3  398.38  4496.4  397.15  4516.5  397.14
  4607.0  394.82  4637.1  394.62  4657.2  393.49  4677.3  393.88  4757.7  391.31
  4828.1  391.49  4878.3  390.00  4918.5  388.09  4952.0  388.06  4978.8  388.67
  5004.4  387.63  5019.0  387.99  5027.1  387.50  5027.3  387.00  5030.8  387.00
  5031.1  387.50  5039.1  388.47  5059.2  387.89  5069.3  388.14  5154.6  390.57
  5169.7  391.69  5189.8  391.91  5209.9  392.94  5300.4  394.46  5488.1  399.62
#Mann=3,-1,0
  4429.9    0.05       0  5027.1    0.04       0  5031.1    0.05       0
Bank Sta=5027.1,5031.1
Exp/Cntr=0.3,0.1

Type RM Length L Ch R = 1,5982,480,480,480
BEGIN DESCRIPTION:
Lacy 136 1118
END DESCRIPTION:
XS GIS Cut Line= 3
      2715244.85      6864498.88      2714673.48      6864217.16
      2714245.34      6863728.67
#Sta/Elev= 30
  4357.8  399.05  4475.5  395.84  4503.5  396.20  4565.3  393.57  4615.8  392.02
  4677.6  391.34  4683.2  390.51  4817.9  389.90  4857.2  387.86  4907.7  388.43
  4969.5  387.31  4975.1  388.04  4990.7  386.43  5043.5  386.93  5096.2  387.70
  5128.7  386.72  5144.5  385.20  5144.7  384.70  5148.5  385.20  5153.1  386.12
  5189.2  388.58  5202.5  391.37  5231.0  394.50  5344.8  400.57  5422.7  400.89
  5472.0  398.86  5493.8  399.44  5514.7  398.42  5557.4  400.30  5644.4  401.76
#Mann=5,-1,0
  4357.8    0.05       0  5043.5    0.12       0  5128.7    0.05       0
  5144.5    0.04       0  5148.5    0.05       0
Bank Sta=5144.5,5148.5
Exp/Cntr=0.3,0.1

Type RM Length L Ch R = 1,5502,593,593,593
BEGIN DESCRIPTION:
Lacy 136 1117
END DESCRIPTION:
XS GIS Cut Line= 3
      2715367.35      6864540.28      2714818.26      6863918.37
      2714652.28      6863378.11
#Sta/Elev= 30
  4013.5  401.68  4035.4  401.08  4049.6  402.17  4170.1  397.40  4360.8  392.10
  4411.0  391.48  4452.8  389.33  4509.7  388.75  4636.6  384.39  4651.9  384.19
  4693.7  386.25  4758.2  387.03  4892.7  387.16  4955.4  384.98  4997.3  385.48
  5003.3  383.08  5008.5  384.48  5026.7  383.04  5026.9  382.54  5030.7  383.04
  5036.0  390.51  5041.2  390.36  5049.6  393.71  5074.0  394.84  5091.4  394.75
  5106.7  396.01  5196.1  396.91  5242.8  398.62  5340.9  397.86  5408.3  399.03
#Mann=4,-1,0
  4013.5    0.05       0  4636.6    0.12       0  5026.7    0.07       0
  5030.7    0.12       0
Bank Sta=5026.7,5030.7
Exp/Cntr=0.3,0.1

Type RM Length L Ch R = 1,4909,510,510,510
BEGIN DESCRIPTION:
Lacy 136 1116
END DESCRIPTION:
XS GIS Cut Line= 3
      2715526.81      6864138.73      2715198.72      6863841.92
      2714627.38      6863332.79
#Sta/Elev= 30
  4554.2  401.35  4616.9  401.24  4623.0  400.70  4666.3  399.80  4702.1  397.73
  4708.8  398.05  4716.3  397.19  4794.0  394.33  4836.6  389.96  4852.6  389.65
  4914.3  387.92  4933.5  386.66  4971.1  384.45  4983.2  382.30  4990.0  381.79
  4990.3  381.29  4994.0  381.79  4995.1  382.60  5041.4  384.47  5077.3  383.73
  5134.2  385.45  5310.6  386.34  5366.6  388.16  5395.4  389.42  5438.5  390.20
  5452.7  391.30  5558.9  395.09  5629.8  396.19  5643.4  397.19  5761.9  400.34
#Mann=9,-1,0
  4554.2    0.12       0  4623.0    0.05       0  4852.6    0.12       0
  4933.5     0.1       0  4983.2    0.12       0  4990.0    0.07       0
  4994.0    0.12       0  5366.6     0.1       0  5395.4    0.12       0
Bank Sta=4990,4994
Exp/Cntr=0.3,0.1

Type RM Length L Ch R = 1,4399,454,454,454
BEGIN DESCRIPTION:
Lacy 136 1115
END DESCRIPTION:
XS GIS Cut Line= 3
      2715829.94      6863680.49      2715126.27      6863470.98
      2714602.42      6863292.24
#Sta/Elev= 30
  4269.1  401.82  4377.5  402.23  4440.1  399.70  4529.5  394.45  4567.9  394.24
  4600.9  392.51  4639.4  391.77  4667.4  389.92  4703.4  388.97  4772.1  386.33
  4784.5  386.53  4794.9  385.31  4849.9  384.36  4920.5  383.43  4941.0  384.33
  4961.8  383.74  4981.6  381.86  4998.8  382.10  5043.1  381.72  5043.4  381.22
  5047.1  381.72  5067.0  381.89  5076.5  383.44  5084.4  383.65  5107.8  385.64
  5113.1  385.17  5218.5  390.55  5415.7  398.35  5500.2  400.32  5556.8  400.68
#Mann=9,-1,0
  4269.1    0.05       0  4600.9     0.1       0  4703.4    0.12       0
  4849.9     0.1       0  4998.8    0.12       0  5043.1    0.07       0
  5047.1    0.12       0  5084.4     0.1       0  5218.5    0.12       0
Bank Sta=5043.1,5047.1
Exp/Cntr=0.3,0.1

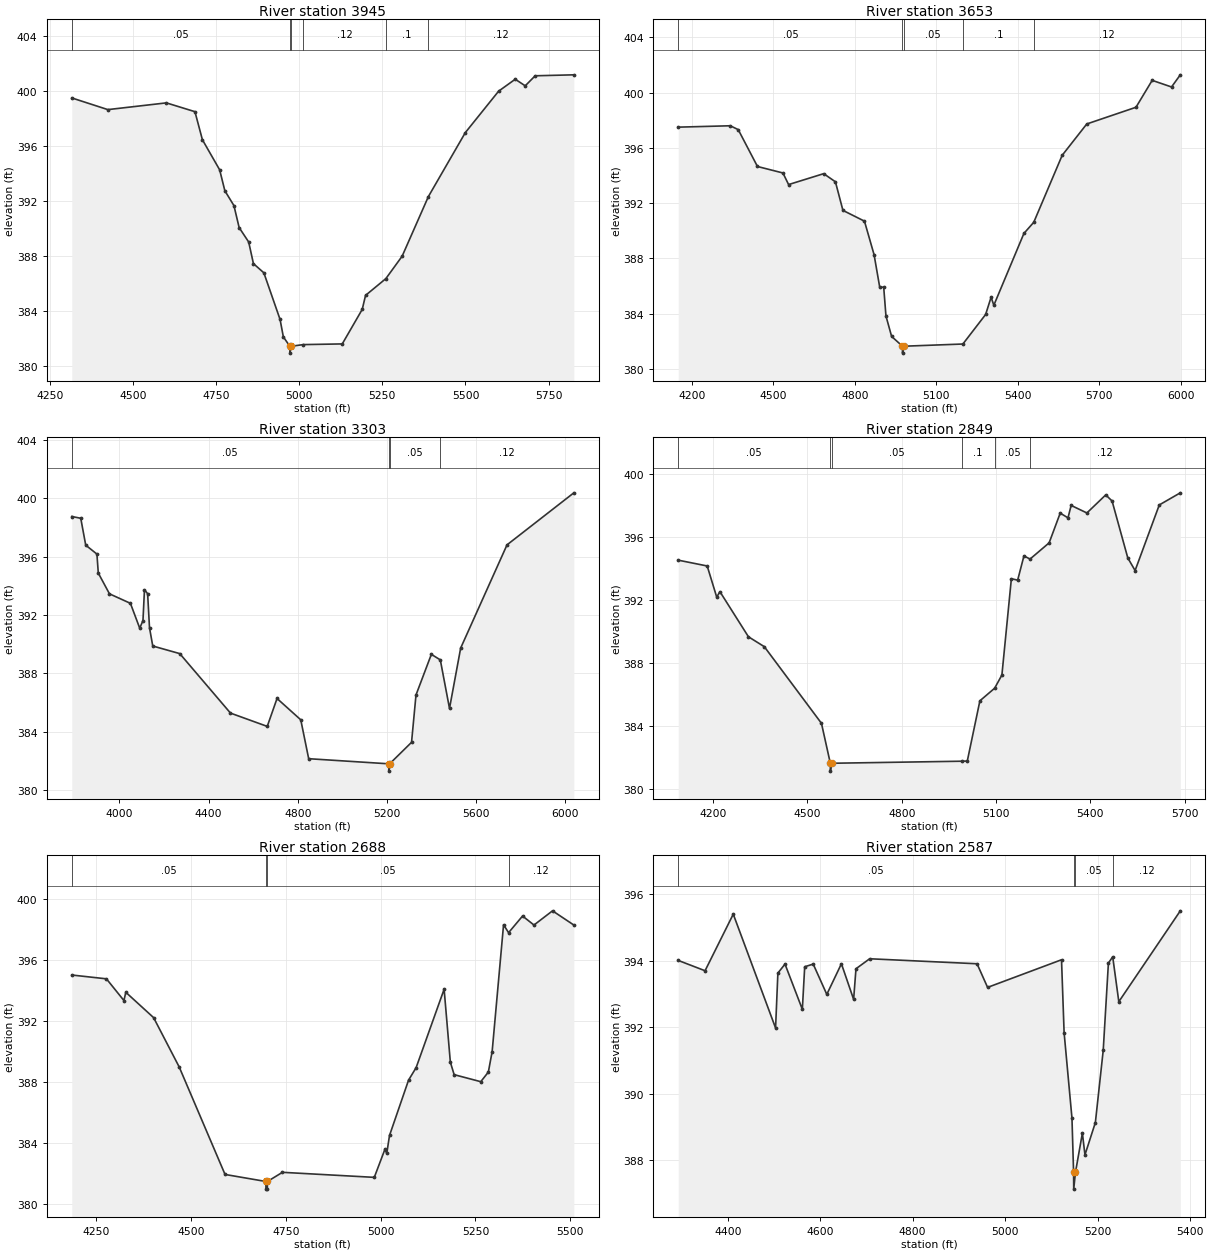
Type RM Length L Ch R = 1,3945,292,292,292
BEGIN DESCRIPTION:
Lacy 136 3450
END DESCRIPTION:
XS GIS Cut Line= 3
      2715924.66      6863550.92      2715332.39      6863203.18
      2714509.80      6863205.37
#Sta/Elev= 30
  4316.5  399.53  4425.0  398.68  4600.9  399.17  4686.8  398.53  4709.2  396.49
  4761.1  394.30  4776.7  392.78  4804.0  391.70  4819.7  390.10  4848.4  389.05
  4862.6  387.48  4894.0  386.81  4942.7  383.42  4952.6  382.15  4972.1  381.47
  4972.3  380.97  4976.1  381.47  5012.6  381.59  5129.7  381.64  5189.7  384.15
  5199.7  385.17  5260.8  386.39  5309.7  388.02  5388.7  392.36  5499.7  397.01
  5599.7  400.02  5649.7  400.89  5679.7  400.41  5709.7  401.14  5825.9  401.21
#Mann=6,-1,0
  4316.5    0.05       0  4972.1   0.035       0  4976.1    0.05       0
  5012.6    0.12       0  5260.8     0.1       0  5388.7    0.12       0
Bank Sta=4972.1,4976.1
Exp/Cntr=0.3,0.1

Type RM Length L Ch R = 1,3653,350,350,350
BEGIN DESCRIPTION:
Lacy 136 3452
END DESCRIPTION:
XS GIS Cut Line= 3
      2716108.08      6863468.12      2715443.51      6862968.12
      2714433.88      6863076.60
#Sta/Elev= 30
  4150.5  397.50  4342.0  397.60  4371.2  397.32  4442.0  394.65  4535.7  394.18
  4556.5  393.34  4685.6  394.13  4728.8  393.54  4756.4  391.47  4835.6  390.69
  4871.0  388.26  4891.8  385.90  4906.4  385.91  4914.7  383.82  4935.5  382.34
  4975.5  381.63  4975.7  381.13  4979.5  381.63  5197.7  381.79  5281.4  383.93
  5301.5  385.18  5311.6  384.60  5422.2  389.80  5458.5  390.61  5563.0  395.46
  5653.5  397.73  5834.5  398.94  5894.1  400.89  5965.3  400.41  5997.6  401.29
#Mann=5,-1,0
  4150.5    0.05       0  4975.5    0.03       0  4979.5    0.05       0
  5197.7     0.1       0  5458.5    0.12       0
Bank Sta=4975.5,4979.5
Exp/Cntr=0.3,0.1

Type RM Length L Ch R = 1,3303,454,454,454
BEGIN DESCRIPTION:
Lacy 136 3451
END DESCRIPTION:
XS GIS Cut Line= 3
      2716448.41      6863325.40      2715579.69      6862684.24
      2714409.15      6862753.58
#Sta/Elev= 30
  3785.9  398.74  3826.2  398.62  3848.5  396.78  3898.7  396.17  3904.9  394.87
  3955.0  393.45  4049.0  392.80  4090.7  391.10  4105.3  391.62  4112.0  393.73
  4126.2  393.46  4134.6  391.13  4149.2  389.88  4270.3  389.36  4497.9  385.29
  4662.8  384.38  4706.7  386.29  4813.2  384.83  4848.7  382.17  5207.9  381.82
  5208.1  381.32  5211.9  381.82  5310.1  383.29  5330.1  386.53  5399.0  389.31
  5439.2  388.93  5480.4  385.61  5530.5  389.74  5738.4  396.80  6038.2  400.36
#Mann=4,-1,0
  3785.9    0.05       0  5207.9    0.03       0  5211.9    0.05       0
  5439.2    0.12       0
Bank Sta=5207.9,5211.9
Exp/Cntr=0.3,0.1

Type RM Length L Ch R = 1,2849,161,161,161
BEGIN DESCRIPTION:
Lacy 136 1113
END DESCRIPTION:
XS GIS Cut Line= 3
      2716137.29      6862479.70      2715270.93      6862361.58
      2714549.16      6862392.16
#Sta/Elev= 30
  4089.2  394.54  4181.3  394.17  4211.6  392.19  4221.7  392.54  4312.5  389.67
  4363.0  389.04  4544.7  384.17  4572.9  381.63  4573.2  381.13  4576.9  381.63
  4990.3  381.76  5008.5  381.77  5048.6  385.60  5095.5  386.40  5118.6  387.24
  5148.7  393.36  5168.7  393.27  5188.7  394.81  5208.1  394.61  5268.8  395.64
  5304.0  397.53  5328.8  397.23  5338.8  398.02  5388.9  397.54  5448.9  398.69
  5469.0  398.30  5519.0  394.68  5542.2  393.88  5619.1  398.05  5686.0  398.82
#Mann=6,-1,0
  4089.2    0.05       0  4572.9    0.07       0  4576.9    0.05       0
  4990.3     0.1       0  5095.5    0.05       0  5208.1    0.12       0
Bank Sta=4572.9,4576.9
Exp/Cntr=0.3,0.1

Type RM Length L Ch R = 1,2688,101,101,101
BEGIN DESCRIPTION:
Lacy 136 1111
END DESCRIPTION:
XS GIS Cut Line= 4
      2716086.59      6862324.21      2715279.96      6862216.96
      2714823.31      6862186.86      2714875.57      6862189.56
#Sta/Elev= 30
  4185.7  395.01  4277.1  394.76  4323.2  393.34  4328.2  393.88  4401.5  392.22
  4468.8  389.00  4589.8  381.96  4697.5  381.50  4697.7  381.00  4701.2  381.00
  4701.5  381.50  4741.1  382.10  4983.3  381.77  5011.2  383.60  5016.2  383.34
  5023.4  384.51  5073.6  388.13  5093.6  388.95  5167.4  394.08  5183.8  389.31
  5193.8  388.49  5264.0  388.03  5284.0  388.66  5294.0  390.00  5324.1  398.30
  5337.3  397.78  5374.2  398.87  5404.3  398.28  5453.2  399.21  5509.4  398.28
#Mann=4,-1,0
  4185.7    0.05       0  4697.5    0.04       0  4701.5    0.05       0
  5337.3    0.12       0
Bank Sta=4697.5,4701.5
Exp/Cntr=0.3,0.1

Type RM Length L Ch R = 1,2587,117,117,117
BEGIN DESCRIPTION:
Lacy 136 1107
END DESCRIPTION:
XS GIS Cut Line= 4
      2716043.05      6862255.21      2715580.95      6862169.67
      2715251.51      6862129.74      2714996.13      6862005.49
#Sta/Elev= 30
  4293.0  394.01  4351.0  393.70  4412.0  395.40  4503.5  391.98  4508.5  393.63
  4523.9  393.90  4561.4  392.54  4566.5  393.82  4584.9  393.90  4614.3  392.99
  4645.9  393.91  4672.3  392.84  4677.4  393.76  4707.0  394.06  4939.2  393.91
  4962.0  393.20  5121.9  394.03  5127.5  391.84  5144.5  389.27  5148.0  387.64
  5148.3  387.14  5152.0  387.64  5167.0  388.82  5172.6  388.17  5195.1  389.14
  5212.1  391.31  5223.3  393.93  5232.6  394.12  5245.8  392.77  5378.8  395.50
#Mann=4,-1,0
  4293.0    0.05       0  5148.0    0.04       0  5152.0    0.05       0
  5232.6    0.12       0
Bank Sta=5148,5152
Exp/Cntr=0.3,0.1

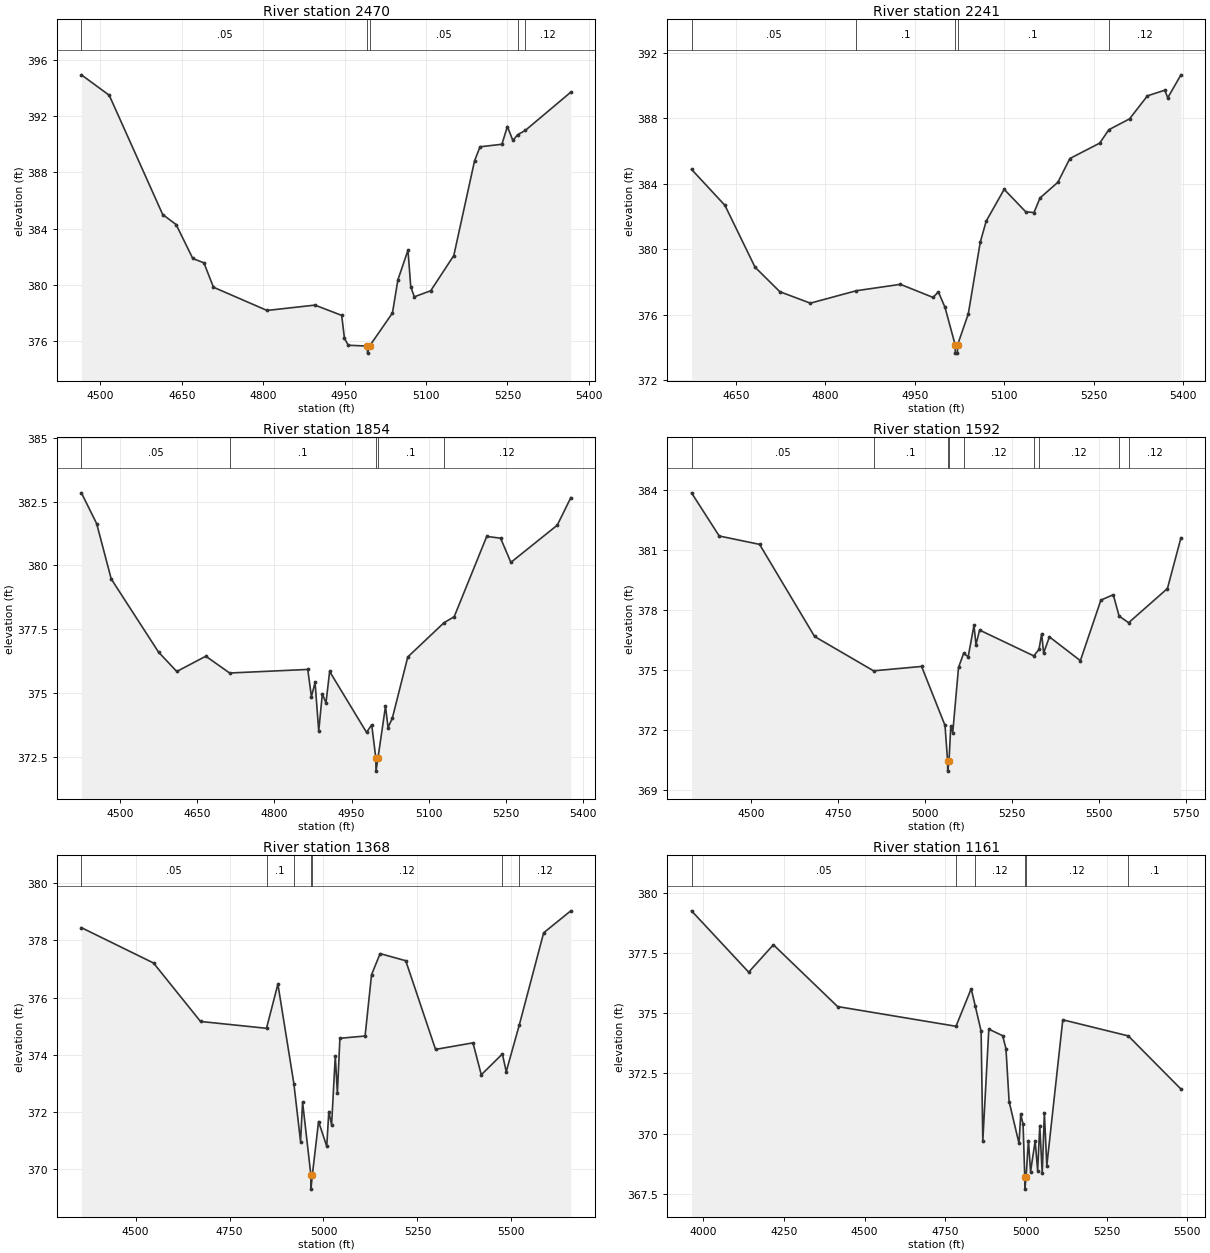
Type RM Length L Ch R = 1,2470,229,229,229
BEGIN DESCRIPTION:
Lacy 136 1108
END DESCRIPTION:
XS GIS Cut Line= 3
      2715946.61      6862167.78      2715423.79      6862055.01
      2715060.17      6862007.98
#Sta/Elev= 30
  4465.2  394.92  4516.5  393.47  4615.0  385.00  4639.7  384.29  4670.4  381.88
  4690.9  381.57  4708.5  379.84  4807.1  378.19  4895.4  378.57  4944.7  377.84
  4949.8  376.20  4956.9  375.72  4992.0  375.66  4992.3  375.16  4996.0  375.66
  5038.2  378.01  5048.2  380.36  5066.8  382.47  5071.9  379.87  5078.5  379.16
  5108.7  379.59  5151.2  382.09  5189.4  388.81  5199.5  389.81  5239.8  389.99
  5249.9  391.25  5260.0  390.26  5268.9  390.67  5282.8  390.97  5366.7  393.69
#Mann=5,-1,0
  4465.2    0.05       0  4992.0    0.04       0  4996.0    0.05       0
  5268.9     0.1       0  5282.8    0.12       0
Bank Sta=4992,4996
Exp/Cntr=0.3,0.1

Type RM Length L Ch R = 1,2241,387,387,387
BEGIN DESCRIPTION:
Lacy 136 1109
END DESCRIPTION:
XS GIS Cut Line= 3
      2715890.78      6861928.91      2715479.06      6861841.95
      2715079.92      6861825.02
#Sta/Elev= 30
  4575.6  384.87  4631.6  382.67  4682.0  378.90  4723.6  377.40  4774.7  376.70
  4851.9  377.46  4925.7  377.85  4980.5  377.05  4989.3  377.39  5000.4  376.45
  5017.5  374.15  5017.7  373.65  5021.2  373.65  5021.5  374.15  5039.5  376.05
  5059.5  380.42  5069.5  381.71  5099.6  383.65  5135.7  382.28  5149.6  382.23
  5159.6  383.12  5189.6  384.08  5209.7  385.53  5259.7  386.47  5275.1  387.29
  5309.7  387.95  5339.8  389.36  5368.8  389.70  5373.8  389.24  5395.9  390.64
#Mann=5,-1,0
  4575.6    0.05       0  4851.9     0.1       0  5017.5    0.07       0
  5021.5     0.1       0  5275.1    0.12       0
Bank Sta=5017.5,5021.5
Exp/Cntr=0.3,0.1

Type RM Length L Ch R = 1,1854,262,262,262
BEGIN DESCRIPTION:
Lacy 136 1110
END DESCRIPTION:
XS GIS Cut Line= 3
      2715914.14      6861864.88      2715556.75      6861510.63
      2715109.76      6861487.45
#Sta/Elev= 30
  4425.2  382.85  4454.9  381.64  4483.2  379.47  4575.1  376.60  4610.5  375.84
  4667.0  376.44  4713.2  375.78  4865.0  375.92  4872.1  374.85  4879.2  375.41
  4886.3  373.50  4893.3  374.96  4900.4  374.61  4907.5  375.84  4979.2  373.45
  4989.2  373.75  4997.3  372.43  4997.5  371.93  5001.3  372.43  5016.0  374.47
  5021.0  373.64  5029.3  374.01  5059.3  376.41  5129.5  377.75  5149.5  377.99
  5212.7  381.14  5239.6  381.07  5259.6  380.12  5349.7  381.58  5376.0  382.66
#Mann=5,-1,0
  4425.2    0.05       0  4713.2     0.1       0  4997.3    0.07       0
  5001.3     0.1       0  5129.5    0.12       0
Bank Sta=4997.3,5001.3
Exp/Cntr=0.3,0.1

Type RM Length L Ch R = 1,1592,224,224,224
BEGIN DESCRIPTION:
Lacy 136 1106
END DESCRIPTION:
XS GIS Cut Line= 3
      2716020.05      6861973.16      2715701.36      6861378.24
      2715051.44      6861045.82
#Sta/Elev= 30
  4329.4  383.85  4408.8  381.69  4524.7  381.27  4682.6  376.66  4852.0  374.94
  4989.8  375.16  5057.0  372.21  5064.5  370.42  5064.7  369.92  5068.5  370.42
  5073.6  372.17  5079.2  371.84  5095.8  375.11  5110.4  375.81  5123.6  375.65
  5140.2  377.22  5145.9  376.25  5156.3  376.98  5311.7  375.69  5326.8  376.01
  5334.5  376.80  5340.1  375.83  5356.7  376.64  5445.6  375.45  5504.5  378.48
  5540.1  378.75  5556.8  377.68  5584.1  377.35  5695.5  379.06  5734.3  381.60
#Mann=9,-1,0
  4329.4    0.05       0  4852.0     0.1       0  5064.5    0.07       0
  5068.5     0.1       0  5110.4    0.12       0  5311.7     0.1       0
  5326.8    0.12       0  5556.8     0.1       0  5584.1    0.12       0
Bank Sta=5064.5,5068.5
Exp/Cntr=0.3,0.1

Type RM Length L Ch R = 1,1368,207,207,207
BEGIN DESCRIPTION:
Lacy 136 1105
END DESCRIPTION:
XS GIS Cut Line= 3
      2716023.91      6861804.32      2715779.91      6861213.40
      2715180.77      6860929.55
#Sta/Elev= 30
  4355.8  378.45  4547.8  377.21  4672.8  375.16  4848.4  374.92  4878.7  376.47
  4921.2  372.98  4939.0  370.95  4944.4  372.33  4966.4  369.78  4966.6  369.28
  4970.4  369.78  4986.9  371.65  5008.7  370.78  5014.2  372.00  5021.6  371.53
  5031.4  373.95  5037.0  372.64  5043.7  374.57  5110.7  374.65  5127.9  376.80
  5150.7  377.54  5218.9  377.29  5298.2  374.18  5397.8  374.41  5419.9  373.29
  5476.0  374.02  5486.3  373.40  5520.9  375.03  5585.9  378.27  5658.1  379.04
#Mann=7,-1,0
  4355.8    0.05       0  4848.4     0.1       0  4921.2    0.12       0
  4966.4    0.07       0  4970.4    0.12       0  5476.0     0.1       0
  5520.9    0.12       0
Bank Sta=4966.4,4970.4
Exp/Cntr=0.3,0.1

Type RM Length L Ch R = 1,1161,252,252,252
BEGIN DESCRIPTION:
Lacy 136 1104
END DESCRIPTION:
XS GIS Cut Line= 3
      2716185.78      6862027.63      2715834.78      6861052.48
      2715471.17      6860739.13
#Sta/Elev= 30
  3963.6  379.26  4140.7  376.71  4217.2  377.85  4416.2  375.28  4783.0  374.46
  4830.1  376.02  4842.9  375.29  4860.8  374.26  4866.1  369.70  4884.7  374.34
  4927.5  374.07  4937.8  373.53  4947.6  371.33  4978.3  369.59  4983.6  370.81
  4990.9  370.38  4996.1  368.19  4996.4  367.69  5000.1  368.19  5007.5  369.71
  5014.1  368.42  5028.3  369.69  5036.0  368.46  5042.6  370.33  5050.2  368.34
  5056.8  370.87  5064.4  368.67  5113.9  374.73  5316.8  374.06  5480.0  371.85
#Mann=6,-1,0
  3963.6    0.05       0  4783.0     0.1       0  4842.9    0.12       0
  4996.1    0.07       0  5000.1    0.12       0  5316.8     0.1       0
Bank Sta=4996.1,5000.1
Exp/Cntr=0.3,0.1

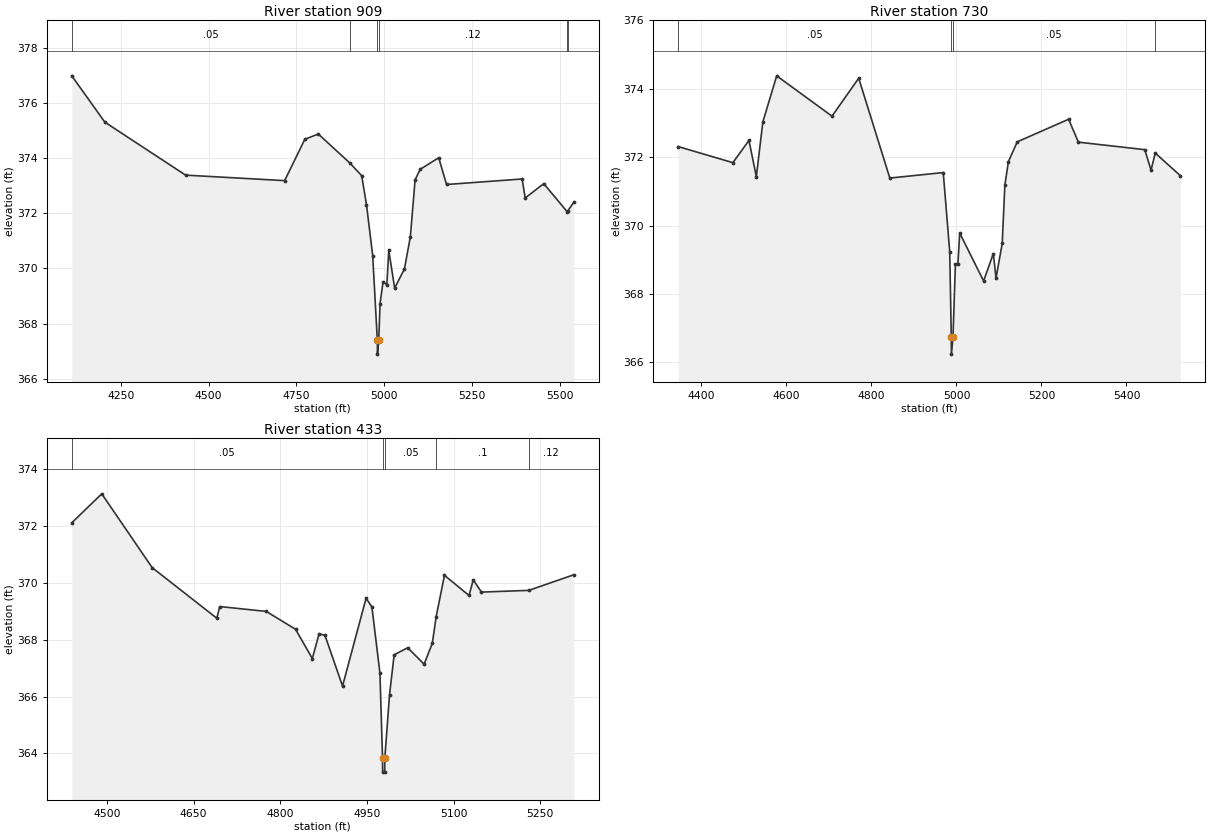
Type RM Length L Ch R = 1,909,179,179,179
BEGIN DESCRIPTION:
Lacy 136 1103
END DESCRIPTION:
XS GIS Cut Line= 3
      2716292.49      6861951.24      2716035.85      6861099.67
      2715793.67      6860617.13
#Sta/Elev= 30
  4110.6  376.98  4204.8  375.30  4434.6  373.38  4716.6  373.18  4774.1  374.68
  4812.4  374.87  4902.2  373.82  4935.9  373.36  4949.6  372.31  4967.3  370.46
  4980.5  367.39  4980.8  366.89  4984.5  367.39  4988.2  368.72  4996.7  369.51
  5007.5  369.41  5013.1  370.65  5029.8  369.28  5057.7  369.98  5074.5  371.15
  5088.0  373.21  5102.4  373.59  5155.2  374.01  5177.5  373.04  5392.8  373.24
  5401.3  372.55  5454.2  373.07  5521.8  372.04  5523.0  372.09  5539.9  372.40
#Mann=6,-1,0
  4110.6    0.05       0  4902.2    0.12       0  4980.5    0.07       0
  4984.5    0.12       0  5521.8     0.1       0  5523.0    0.12       0
Bank Sta=4980.5,4984.5
Exp/Cntr=0.3,0.1

Type RM Length L Ch R = 1,730,297,297,297
BEGIN DESCRIPTION:
Lacy 136 1102
END DESCRIPTION:
XS GIS Cut Line= 3
      2716389.73      6861666.49      2716196.15      6861041.37
      2715880.23      6860620.07
#Sta/Elev= 30
  4345.6  372.31  4474.1  371.84  4512.0  372.49  4529.3  371.43  4544.6  373.03
  4577.2  374.38  4707.3  373.20  4770.1  374.31  4843.3  371.39  4969.0  371.55
  4984.2  369.23  4987.9  366.74  4988.2  366.24  4991.9  366.74  4997.6  368.87
  5003.4  368.87  5007.7  369.78  5063.9  368.38  5086.8  369.18  5093.1  368.46
  5107.7  369.48  5113.9  371.18  5122.2  371.87  5143.1  372.45  5263.9  373.11
  5286.8  372.44  5443.1  372.22  5457.7  371.62  5467.7  372.12  5526.6  371.46
#Mann=4,-1,0
  4345.6    0.05       0  4987.9    0.07       0  4991.9    0.05       0
  5467.7    0.12       0
Bank Sta=4987.9,4991.9
Exp/Cntr=0.3,0.1

Type RM Length L Ch R = 1,433,0,0,0
BEGIN DESCRIPTION:
Lacy 136 1101
END DESCRIPTION:
XS GIS Cut Line= 3
      2716506.02      6861382.08      2716405.82      6860830.30
      2716195.76      6860604.92
#Sta/Elev= 30
  4439.2  372.12  4491.1  373.14  4578.4  370.54  4690.2  368.76  4695.3  369.17
  4775.7  369.00  4826.5  368.37  4855.5  367.34  4867.2  368.21  4877.3  368.16
  4907.8  366.37  4948.5  369.46  4958.6  369.16  4972.5  366.83  4977.0  363.84
  4977.2  363.34  4980.7  363.34  4981.0  363.84  4989.1  366.06  4997.1  367.47
  5020.6  367.72  5049.0  367.14  5063.2  367.88  5069.8  368.81  5084.2  370.27
  5126.7  369.56  5134.0  370.11  5148.2  369.68  5230.1  369.74  5308.1  370.29
#Mann=5,-1,0
  4439.2    0.05       0  4977.0    0.04       0  4981.0    0.05       0
  5069.8     0.1       0  5230.1    0.12       0
Bank Sta=4977,4981
Exp/Cntr=0.3,0.1

Chan Stop Cuts=-1