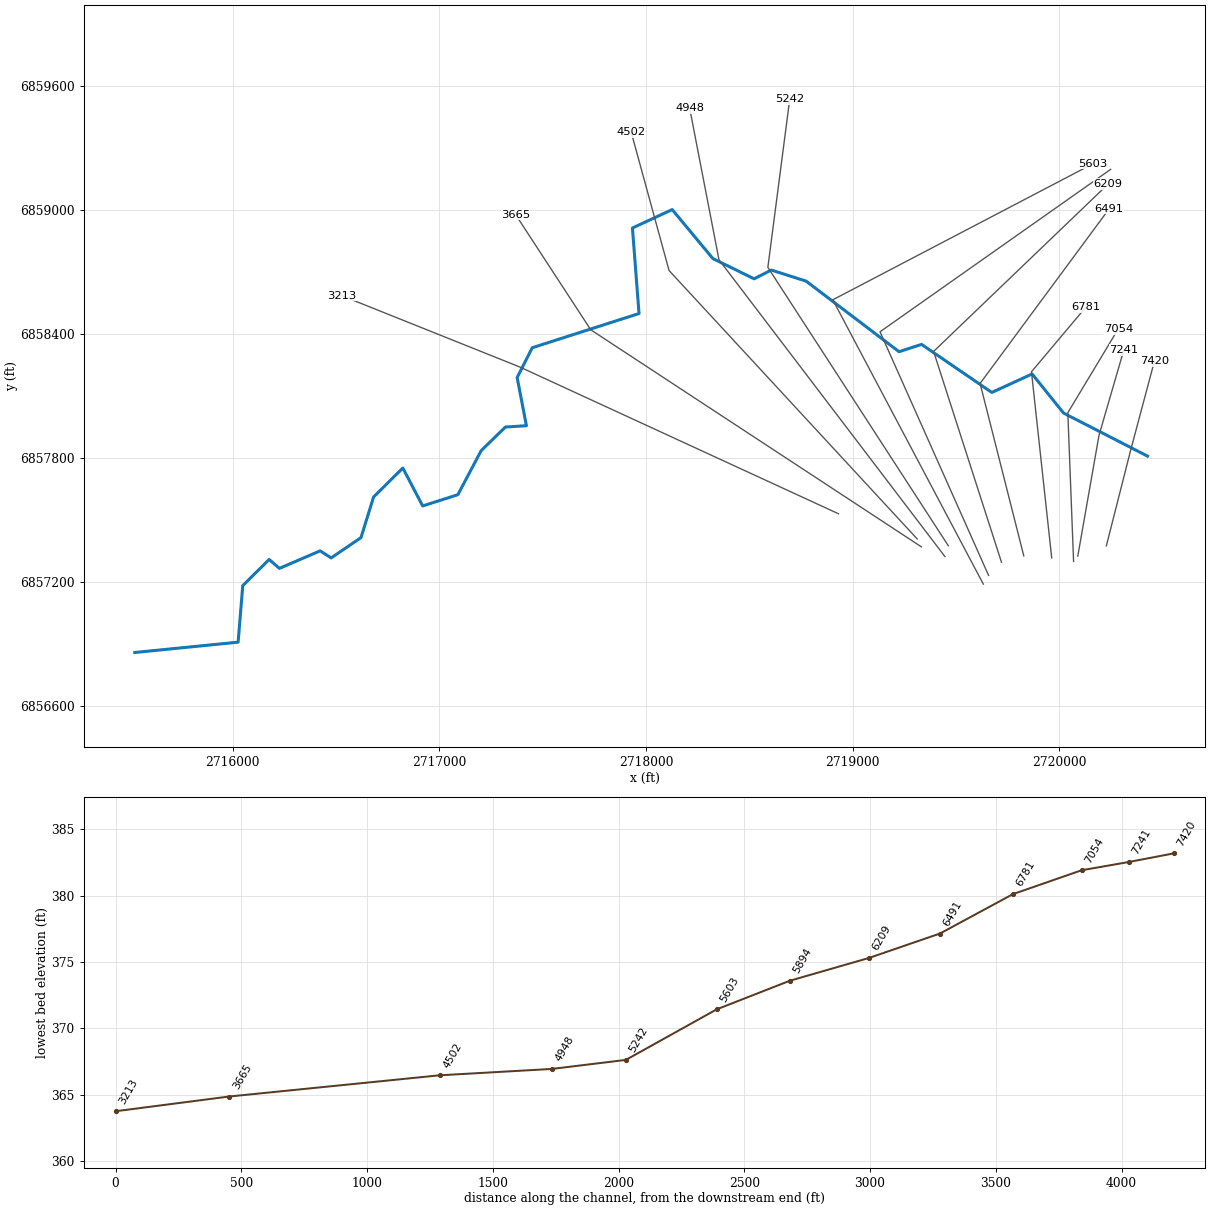
--- Lacy 137.prj (project) ---

Proj Title=Lacy 137 Base Level Engineering
Current Plan=p01
Default Exp/Contr=0.3,0.1
English Units
Geom File=g01
Flow File=f01
Plan File=p01
BEGIN DESCRIPTION:
Lacy 137
END DESCRIPTION:

--- Lacy 137.p01 (plan) ---

Plan Title=Multiple Run
Short Identifier=Multiple
Geom File=g01
Flow File=f01
Subcritical Flow
K Sum by GR= 0
Std Step Tol= 0.01
Critical Tol= 0.01
Num of Std Step Trials= 20
Max Error Tol= 0.3
Flow Tol Ratio= 0.001
Split Flow NTrial= 30
Split Flow Tol= 0.02
Split Flow Ratio= 0.02
Log Output Level= 0
Friction Slope Method= 1
Unsteady Friction Slope Method= 2
Unsteady Bridges Friction Slope Method= 1
Parabolic Critical Depth
Global Vel Dist=  1 , 1 , 1
Global Log Level= 0
CheckData=True
Encroach Param= -1, 0, 0, 0
BEGIN DESCRIPTION:
Multiple Run
END DESCRIPTION:

--- Lacy 137.f01 (steady flow) ---

Flow Title=Multiple
Number of Profiles=7
Profile Names=10-year,25-year,50-year,1pct_min,100-year,1pct_plu,500-year
River Rch & RM= Lacy 137,Reach-1,7420
     512     676     807     478     954    1903    1330
Boundary for River Rch & Prof#=Lacy 137,Reach-1,1
Up Type=0
Dn Type=3
Dn Slope=0.005
Boundary for River Rch & Prof#=Lacy 137,Reach-1,2
Up Type=0
Dn Type=3
Dn Slope=0.005
Boundary for River Rch & Prof#=Lacy 137,Reach-1,3
Up Type=0
Dn Type=3
Dn Slope=0.005
Boundary for River Rch & Prof#=Lacy 137,Reach-1,4
Up Type=0
Dn Type=3
Dn Slope=0.005
Boundary for River Rch & Prof#=Lacy 137,Reach-1,5
Up Type=0
Dn Type=3
Dn Slope=0.005
Boundary for River Rch & Prof#=Lacy 137,Reach-1,6
Up Type=0
Dn Type=3
Dn Slope=0.005
Boundary for River Rch & Prof#=Lacy 137,Reach-1,7
Up Type=0
Dn Type=3
Dn Slope=0.005

--- Lacy 137.g01 (geometry) ---

Geom Title=Existing Conditions

River Reach=Lacy 137,Reach-1
Reach XY= 30
      2720426.00      6857811.00      2720019.95      6858019.16
      2719867.52      6858208.37      2719672.69      6858119.02
      2719332.61      6858351.57      2719223.72      6858316.13
      2718774.50      6858657.38      2718605.79      6858711.21
      2718522.60      6858668.83      2718323.33      6858766.42
      2718126.10      6859003.69      2717933.87      6858914.62
      2717965.68      6858500.82      2717449.01      6858335.36
      2717376.04      6858190.97      2717420.91      6857958.16
      2717319.34      6857951.69      2717202.18      6857837.87
      2717089.33      6857624.39      2716918.93      6857569.99
      2716822.87      6857753.50      2716681.52      6857613.43
      2716620.41      6857416.61      2716476.00      6857318.56
      2716422.78      6857352.71      2716225.86      6857267.90
      2716176.00      6857311.00      2716048.43      6857184.36
      2716026.00      6856911.00      2715526.00      6856861.00

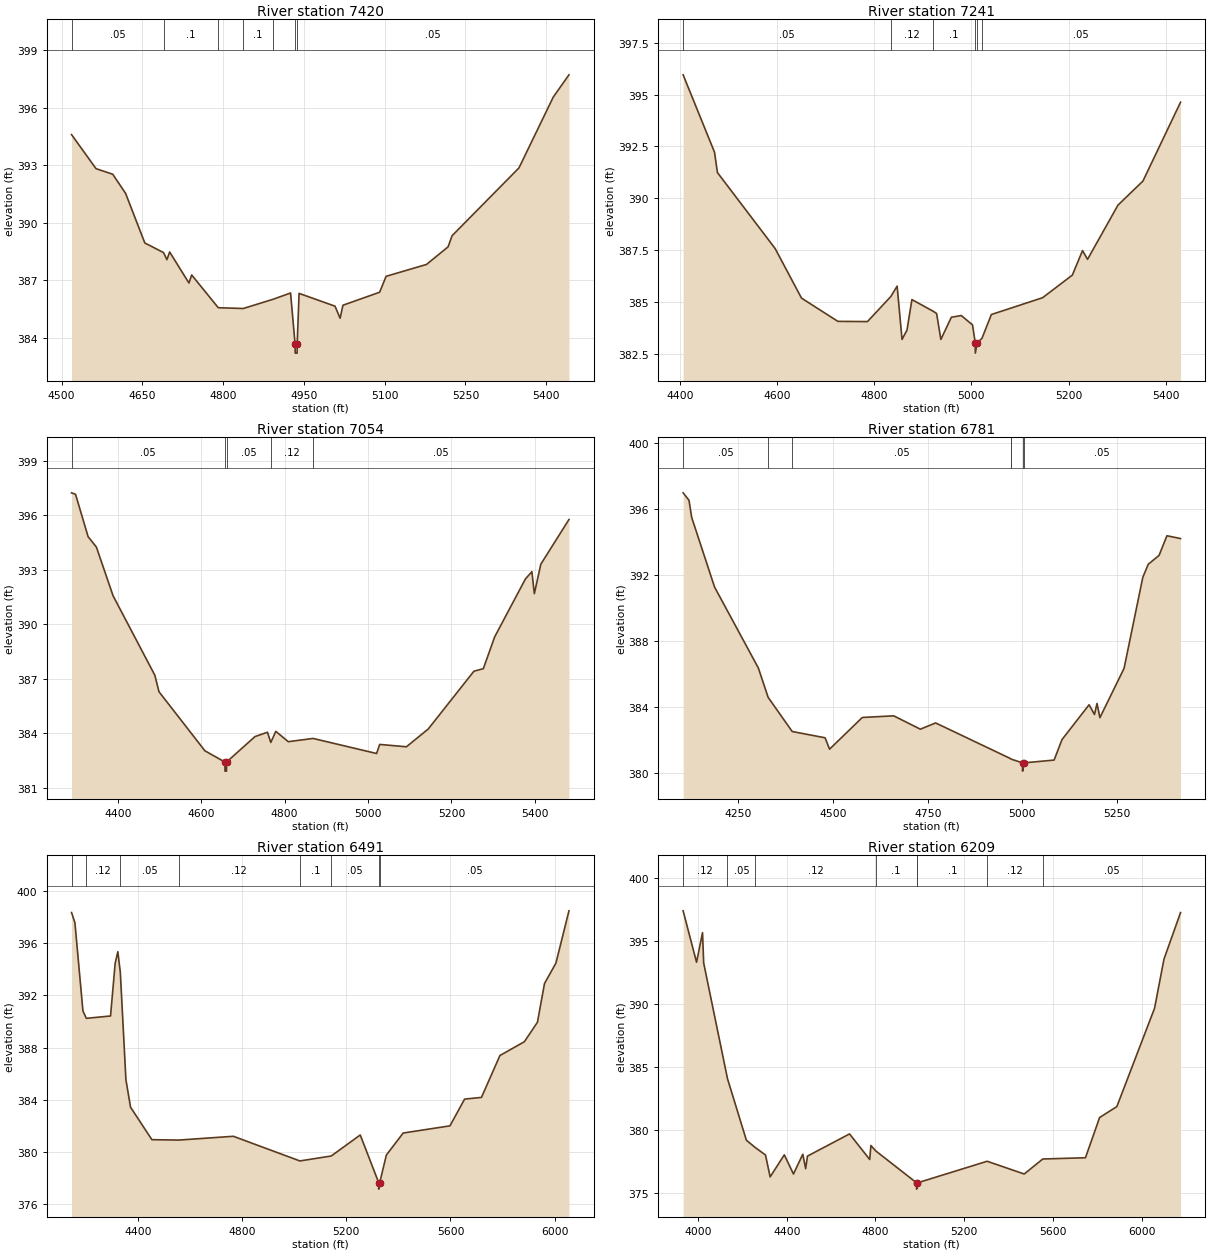
Type RM Length L Ch R = 1,7420,179,179,179
BEGIN DESCRIPTION:
Lacy 137 1087
END DESCRIPTION:
XS GIS Cut Line= 3
      2720226.72      6857376.86      2720345.44      6857843.50
      2720459.43      6858270.65
#Sta/Elev= 30
  4518.5  394.60  4564.0  392.82  4595.0  392.53  4618.9  391.53  4654.6  388.94
  4689.3  388.44  4695.6  388.07  4700.7  388.47  4736.5  386.85  4741.6  387.27
  4791.0  385.56  4837.3  385.52  4892.6  386.00  4925.2  386.33  4933.5  383.69
  4933.8  383.19  4937.3  383.19  4937.5  383.69  4941.0  386.31  5007.8  385.64
  5017.2  385.01  5022.4  385.69  5090.6  386.37  5102.6  387.20  5177.6  387.82
  5217.7  388.74  5225.1  389.32  5349.3  392.86  5413.0  396.56  5442.1  397.72
#Mann=7,-1,0
  4518.5    0.05       0  4689.3     0.1       0  4791.0    0.12       0
  4837.3     0.1       0  4892.6    0.05       0  4933.5    0.04       0
  4937.5    0.05       0
Bank Sta=4933.5,4937.5
Exp/Cntr=0.3,0.1

Type RM Length L Ch R = 1,7241,187,187,187
BEGIN DESCRIPTION:
Lacy 137 1086
END DESCRIPTION:
XS GIS Cut Line= 3
      2720088.65      6857327.37      2720191.22      6857911.53
      2720311.36      6858324.72
#Sta/Elev= 30
  4406.9  395.95  4471.5  392.22  4477.5  391.24  4596.2  387.58  4650.5  385.19
  4725.3  384.07  4786.2  384.06  4834.3  385.27  4847.2  385.77  4857.3  383.20
  4867.5  383.65  4877.6  385.12  4921.2  384.56  4928.4  384.45  4937.2  383.20
  4958.8  384.27  4979.2  384.35  5002.3  383.90  5007.9  383.04  5008.1  382.54
  5011.9  383.04  5021.7  383.25  5041.1  384.40  5146.5  385.21  5207.7  386.30
  5228.6  387.48  5239.0  387.06  5301.5  389.67  5352.9  390.83  5430.3  394.63
#Mann=6,-1,0
  4406.9    0.05       0  4834.3    0.12       0  4921.2     0.1       0
  5007.9    0.07       0  5011.9     0.1       0  5021.7    0.05       0
Bank Sta=5007.9,5011.9
Exp/Cntr=0.3,0.1

Type RM Length L Ch R = 1,7054,273,273,273
BEGIN DESCRIPTION:
Lacy 137 1085
END DESCRIPTION:
XS GIS Cut Line= 3
      2720068.22      6857301.37      2720040.42      6858020.95
      2720284.30      6858426.33
#Sta/Elev= 30
  4288.8  397.24  4298.4  397.16  4328.5  394.83  4348.5  394.25  4388.5  391.57
  4488.6  387.20  4498.6  386.29  4608.7  383.04  4656.7  382.42  4657.0  381.92
  4660.5  381.92  4660.7  382.42  4728.8  383.82  4758.8  384.06  4766.8  383.50
  4778.8  384.11  4808.8  383.54  4868.1  383.72  5020.6  382.89  5028.0  383.39
  5092.1  383.26  5144.5  384.24  5254.0  387.42  5276.6  387.56  5303.8  389.31
  5377.6  392.50  5393.1  392.90  5399.0  391.69  5414.5  393.31  5482.0  395.77
#Mann=5,-1,0
  4288.8    0.05       0  4656.7    0.04       0  4660.7    0.05       0
  4766.8    0.12       0  4868.1    0.05       0
Bank Sta=4656.7,4660.7
Exp/Cntr=0.3,0.1

Type RM Length L Ch R = 1,6781,290,290,290
BEGIN DESCRIPTION:
Lacy 137 1084
END DESCRIPTION:
XS GIS Cut Line= 3
      2719962.44      6857318.50      2719864.47      6858218.97
      2720126.62      6858530.45
#Sta/Elev= 30
  4104.5  396.98  4120.0  396.53  4127.1  395.49  4187.5  391.27  4303.0  386.37
  4328.9  384.59  4392.4  382.52  4479.2  382.14  4491.0  381.45  4577.4  383.37
  4660.3  383.47  4730.7  382.66  4770.9  383.04  4968.6  380.88  4969.9  380.85
  5000.3  380.62  5000.5  380.12  5004.3  380.62  5083.7  380.79  5104.5  382.03
  5176.0  384.14  5190.3  383.55  5196.9  384.22  5204.6  383.36  5268.4  386.35
  5317.8  391.86  5332.1  392.65  5360.7  393.19  5381.5  394.38  5417.4  394.21
#Mann=7,-1,0
  4104.5    0.05       0  4328.9    0.12       0  4392.4    0.05       0
  4968.6    0.12       0  4969.9    0.05       0  5000.3    0.04       0
  5004.3    0.05       0
Bank Sta=5000.3,5004.3
Exp/Cntr=0.3,0.1

Type RM Length L Ch R = 1,6491,282,282,282
BEGIN DESCRIPTION:
Lacy 137 1083
END DESCRIPTION:
XS GIS Cut Line= 3
      2719827.23      6857328.52      2719615.89      6858162.68
      2720240.17      6859007.05
#Sta/Elev= 30
  4144.6  398.35  4157.5  397.58  4188.4  390.81  4201.4  390.24  4294.4  390.42
  4312.2  394.46  4322.5  395.35  4332.0  393.76  4353.5  385.54  4371.3  383.43
  4453.2  380.94  4556.7  380.91  4766.1  381.20  5021.8  379.31  5142.2  379.69
  5253.6  381.30  5324.4  377.65  5324.6  377.15  5328.4  377.65  5353.8  379.76
  5418.5  381.45  5598.1  382.00  5654.4  384.05  5719.1  384.18  5790.1  387.39
  5884.1  388.45  5934.2  389.94  5961.3  392.91  6005.1  394.47  6055.2  398.48
#Mann=8,-1,0
  4144.6    0.05       0  4201.4    0.12       0  4332.0    0.05       0
  4556.7    0.12       0  5021.8     0.1       0  5142.2    0.05       0
  5324.4    0.07       0  5328.4    0.05       0
Bank Sta=5324.4,5328.4
Exp/Cntr=0.3,0.1

Type RM Length L Ch R = 1,6209,315,315,315
BEGIN DESCRIPTION:
Lacy 137 1082
END DESCRIPTION:
XS GIS Cut Line= 3
      2719719.38      6857297.80      2719390.97      6858317.47
      2720235.37      6859127.13
#Sta/Elev= 30
  3933.4  397.39  3993.9  393.31  4020.8  395.66  4026.0  393.25  4133.2  384.08
  4218.4  379.19  4259.1  378.60  4304.5  378.02  4325.5  376.28  4389.3  378.03
  4430.5  376.51  4472.6  378.08  4485.5  376.93  4493.6  377.93  4683.1  379.69
  4774.1  377.66  4779.4  378.77  4801.5  378.34  4985.3  375.81  4985.6  375.31
  4989.3  375.81  5303.1  377.52  5470.3  376.51  5553.8  377.70  5746.1  377.80
  5809.9  380.99  5887.6  381.86  6057.4  389.66  6099.9  393.56  6174.5  397.25
#Mann=8,-1,0
  3933.4    0.12       0  4133.2    0.05       0  4259.1    0.12       0
  4801.5     0.1       0  4985.3    0.07       0  4989.3     0.1       0
  5303.1    0.12       0  5553.8    0.05       0
Bank Sta=4985.3,4989.3
Exp/Cntr=0.3,0.1

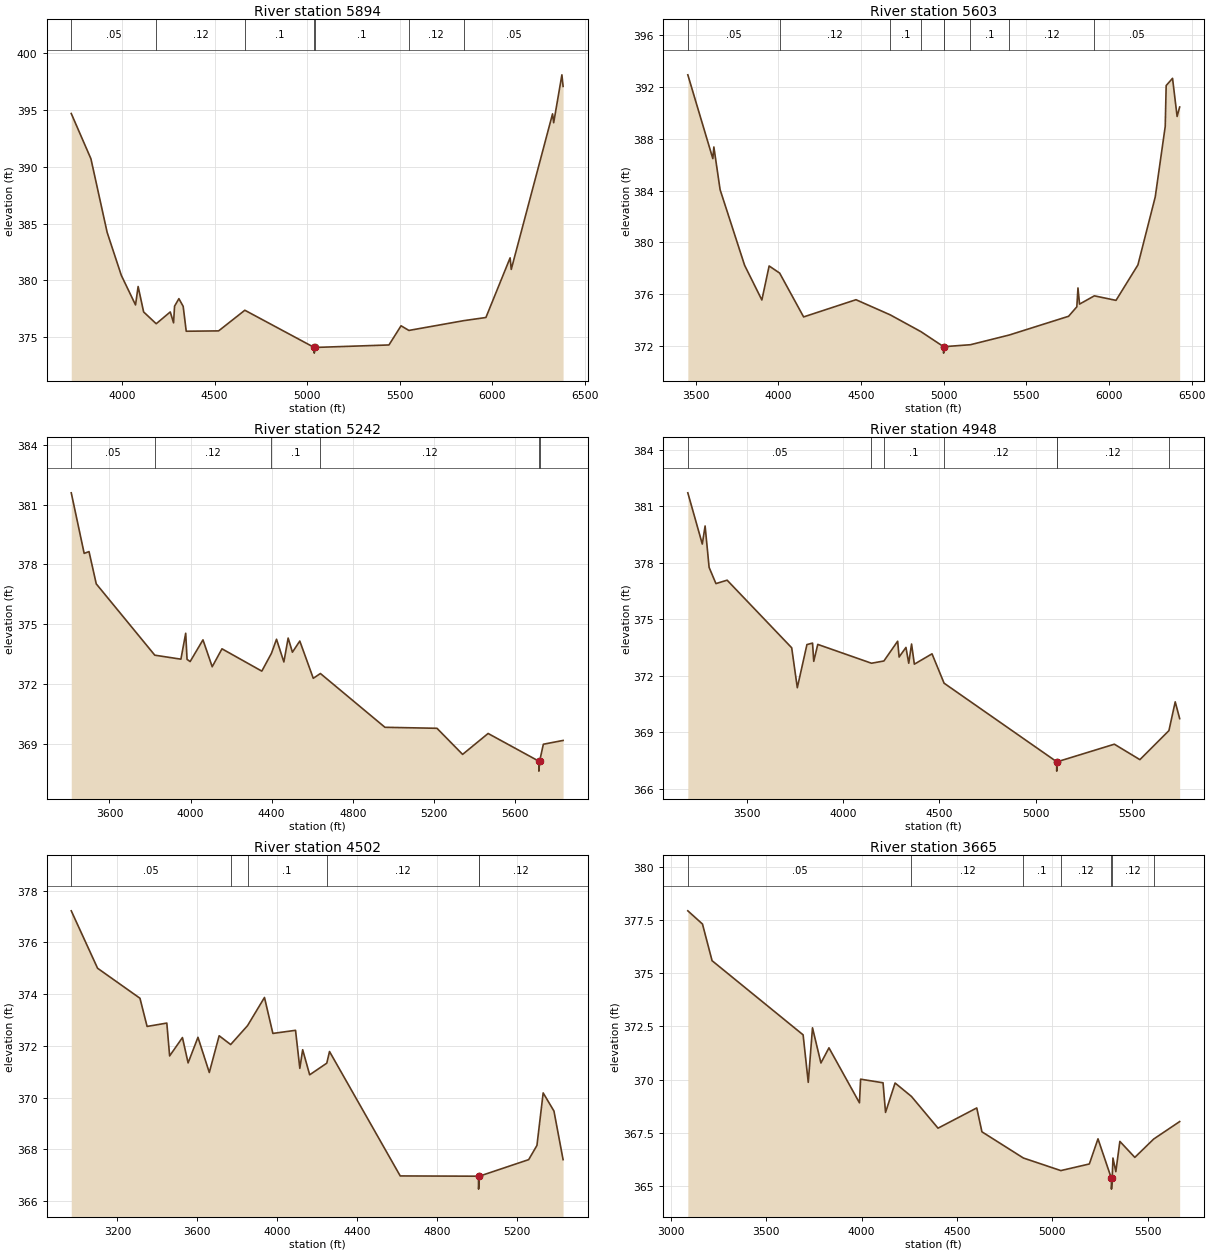
Type RM Length L Ch R = 1,5894,291,291,291
BEGIN DESCRIPTION:
Lacy 137 1081
END DESCRIPTION:
XS GIS Cut Line= 3
      2719656.98      6857234.02      2719131.74      6858412.51
      2720247.91      6859198.54
#Sta/Elev= 30
  3726.1  394.71  3832.3  390.72  3919.9  384.23  3996.5  380.44  4073.1  377.84
  4087.1  379.46  4116.9  377.22  4184.7  376.18  4260.7  377.22  4278.4  376.26
  4283.9  377.73  4307.2  378.39  4330.4  377.71  4346.8  375.52  4521.7  375.55
  4663.3  377.37  5037.8  374.09  5038.1  373.59  5041.8  374.09  5441.4  374.31
  5506.7  376.00  5549.0  375.59  5844.5  376.45  5964.8  376.73  6095.5  381.99
  6101.6  380.97  6324.6  394.68  6330.7  393.90  6375.1  398.12  6381.5  397.10
#Mann=7,-1,0
  3726.1    0.05       0  4184.7    0.12       0  4663.3     0.1       0
  5037.8    0.07       0  5041.8     0.1       0  5549.0    0.12       0
  5844.5    0.05       0
Bank Sta=5037.8,5041.8
Exp/Cntr=0.3,0.1

Type RM Length L Ch R = 1,5603,361,361,361
BEGIN DESCRIPTION:
Lacy 137 1080
END DESCRIPTION:
XS GIS Cut Line= 3
      2719631.55      6857191.82      2718903.26      6858567.22
      2720161.15      6859224.98
#Sta/Elev= 30
  3451.8  392.95  3603.1  386.47  3609.3  387.37  3647.1  384.07  3795.4  378.22
  3899.8  375.54  3943.8  378.17  4007.3  377.62  4152.4  374.23  4469.3  375.56
  4676.3  374.39  4862.3  373.09  4999.1  371.93  4999.3  371.43  5003.1  371.93
  5161.5  372.08  5396.4  372.83  5755.6  374.28  5805.4  375.01  5812.4  376.47
  5821.8  375.22  5911.5  375.86  6042.5  375.51  6175.0  378.25  6279.7  383.50
  6340.3  388.96  6346.0  392.12  6384.5  392.68  6412.2  389.73  6427.6  390.46
#Mann=9,-1,0
  3451.8    0.05       0  4007.3    0.12       0  4676.3     0.1       0
  4862.3    0.12       0  4999.1    0.07       0  5003.1    0.12       0
  5161.5     0.1       0  5396.4    0.12       0  5911.5    0.05       0
Bank Sta=4999.1,5003.1
Exp/Cntr=0.3,0.1

Type RM Length L Ch R = 1,5242,294,294,294
BEGIN DESCRIPTION:
Lacy 137 1079
END DESCRIPTION:
XS GIS Cut Line= 3
      2719462.07      6857377.51      2718589.06      6858724.15
      2718694.91      6859537.63
#Sta/Elev= 30
  3411.8  381.59  3475.5  378.55  3499.4  378.64  3535.1  377.02  3823.7  373.44
  3952.5  373.24  3976.1  374.54  3982.8  373.23  3998.0  373.12  4061.3  374.21
  4106.8  372.86  4155.0  373.76  4351.4  372.64  4398.7  373.53  4423.9  374.24
  4460.2  373.10  4481.3  374.30  4502.4  373.59  4538.7  374.15  4605.2  372.28
  4640.4  372.52  4958.6  369.82  5215.2  369.77  5341.5  368.46  5467.3  369.51
  5717.4  368.12  5717.6  367.62  5721.4  368.12  5739.6  368.97  5837.0  369.16
#Mann=6,-1,0
  3411.8    0.05       0  3823.7    0.12       0  4398.7     0.1       0
  4640.4    0.12       0  5717.4    0.07       0  5721.4    0.12       0
Bank Sta=5717.4,5721.4
Exp/Cntr=0.3,0.1

Type RM Length L Ch R = 1,4948,446,446,446
BEGIN DESCRIPTION:
Lacy 137 1078
END DESCRIPTION:
XS GIS Cut Line= 3
      2719445.66      6857325.19      2718352.60      6858760.78
      2718210.84      6859493.54
#Sta/Elev= 30
  3195.4  381.72  3270.5  379.00  3285.0  379.96  3305.8  377.76  3341.2  376.90
  3399.3  377.08  3734.1  373.49  3763.2  371.37  3813.1  373.66  3842.2  373.74
  3848.4  372.77  3869.3  373.67  4147.9  372.67  4212.3  372.79  4283.6  373.84
  4291.2  373.00  4326.6  373.51  4341.1  372.67  4355.7  373.69  4370.2  372.62
  4461.8  373.17  4524.4  371.61  5108.2  367.44  5108.5  366.94  5112.2  367.44
  5407.4  368.37  5539.8  367.55  5690.4  369.09  5723.1  370.62  5746.1  369.73
#Mann=7,-1,0
  3195.4    0.05       0  4147.9    0.12       0  4212.3     0.1       0
  4524.4    0.12       0  5108.2    0.07       0  5112.2    0.12       0
  5690.4     0.1       0
Bank Sta=5108.2,5112.2
Exp/Cntr=0.3,0.1

Type RM Length L Ch R = 1,4502,837,837,837
BEGIN DESCRIPTION:
Lacy 137 1077
END DESCRIPTION:
XS GIS Cut Line= 3
      2719311.49      6857410.46      2718111.06      6858708.88
      2717928.11      6859377.18
#Sta/Elev= 30
  2968.7  377.22  3100.4  375.00  3312.5  373.84  3348.2  372.75  3446.9  372.88
  3461.0  371.61  3525.1  372.32  3553.4  371.34  3602.8  372.33  3659.5  370.97
  3708.8  372.39  3766.4  372.05  3850.8  372.78  3935.6  373.87  3977.6  372.48
  4091.0  372.60  4112.5  371.13  4126.7  371.85  4161.8  370.88  4247.4  371.33
  4261.1  371.78  4614.9  366.97  5006.8  366.96  5007.0  366.46  5010.8  366.96
  5257.6  367.60  5299.1  368.15  5330.2  370.18  5384.1  369.48  5429.9  367.60
#Mann=6,-1,0
  2968.7    0.05       0  3766.4    0.12       0  3850.8     0.1       0
  4247.4    0.12       0  5006.8    0.07       0  5010.8    0.12       0
Bank Sta=5006.8,5010.8
Exp/Cntr=0.3,0.1

Type RM Length L Ch R = 1,3665,452,452,452
BEGIN DESCRIPTION:
Lacy 137 1076
END DESCRIPTION:
XS GIS Cut Line= 3
      2719332.23      6857371.94      2717732.16      6858422.22
      2717369.45      6858978.07
#Sta/Elev= 30
  3089.4  377.92  3166.2  377.30  3216.5  375.58  3693.6  372.10  3720.6  369.87
  3742.8  372.43  3787.0  370.78  3829.1  371.49  3988.9  368.91  3994.9  370.02
  4112.5  369.85  4125.6  368.46  4175.7  369.84  4261.4  369.21  4400.7  367.72
  4603.7  368.67  4630.8  367.55  4848.1  366.32  5044.3  365.73  5193.7  366.04
  5239.1  367.22  5309.5  365.36  5309.7  364.86  5313.5  365.36  5317.5  366.32
  5332.6  365.68  5353.7  367.10  5432.1  366.35  5530.9  367.21  5667.1  368.03
#Mann=7,-1,0
  3089.4    0.05       0  4261.4    0.12       0  4848.1     0.1       0
  5044.3    0.12       0  5309.5    0.07       0  5313.5    0.12       0
  5530.9     0.1       0
Bank Sta=5309.5,5313.5
Exp/Cntr=0.3,0.1

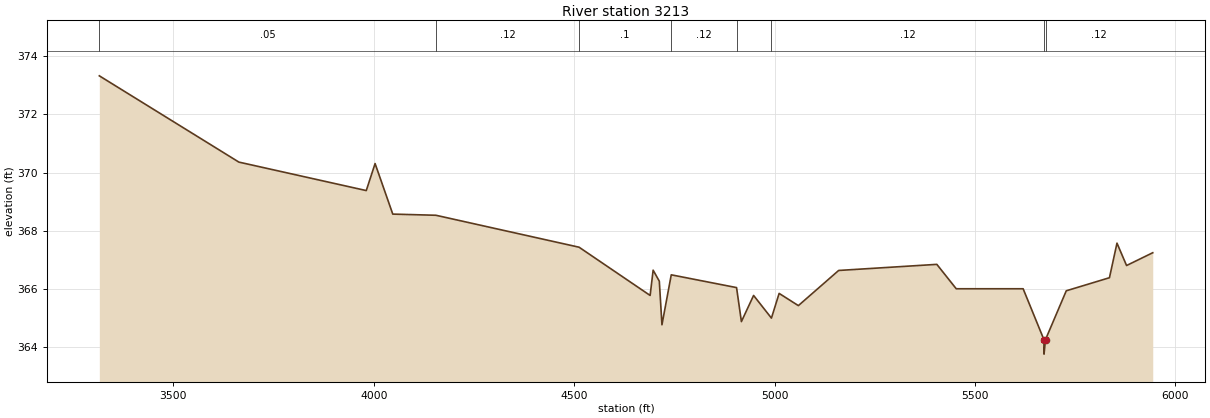
Type RM Length L Ch R = 1,3213,0,0,0
BEGIN DESCRIPTION:
Lacy 137 1075
END DESCRIPTION:
XS GIS Cut Line= 3
      2718930.81      6857532.07      2717390.06      6858241.68
      2716525.34      6858588.00
#Sta/Elev= 30
  3315.6  373.33  3663.7  370.36  3981.5  369.38  4003.5  370.31  4047.6  368.57
  4155.2  368.53  4512.4  367.43  4689.6  365.77  4697.1  366.64  4712.5  366.26
  4719.1  364.76  4742.3  366.48  4905.2  366.04  4917.3  364.87  4947.7  365.77
  4992.2  364.99  5011.4  365.84  5059.4  365.42  5159.9  366.63  5404.8  366.84
  5453.2  366.00  5620.1  366.00  5671.9  364.25  5672.2  363.75  5675.9  364.25
  5727.7  365.93  5835.4  366.38  5854.2  367.57  5878.1  366.80  5943.4  367.24
#Mann=8,-1,0
  3315.6    0.05       0  4155.2    0.12       0  4512.4     0.1       0
  4742.3    0.12       0  4905.2     0.1       0  4992.2    0.12       0
  5671.9    0.07       0  5675.9    0.12       0
Bank Sta=5671.9,5675.9
Exp/Cntr=0.3,0.1

Chan Stop Cuts=-1