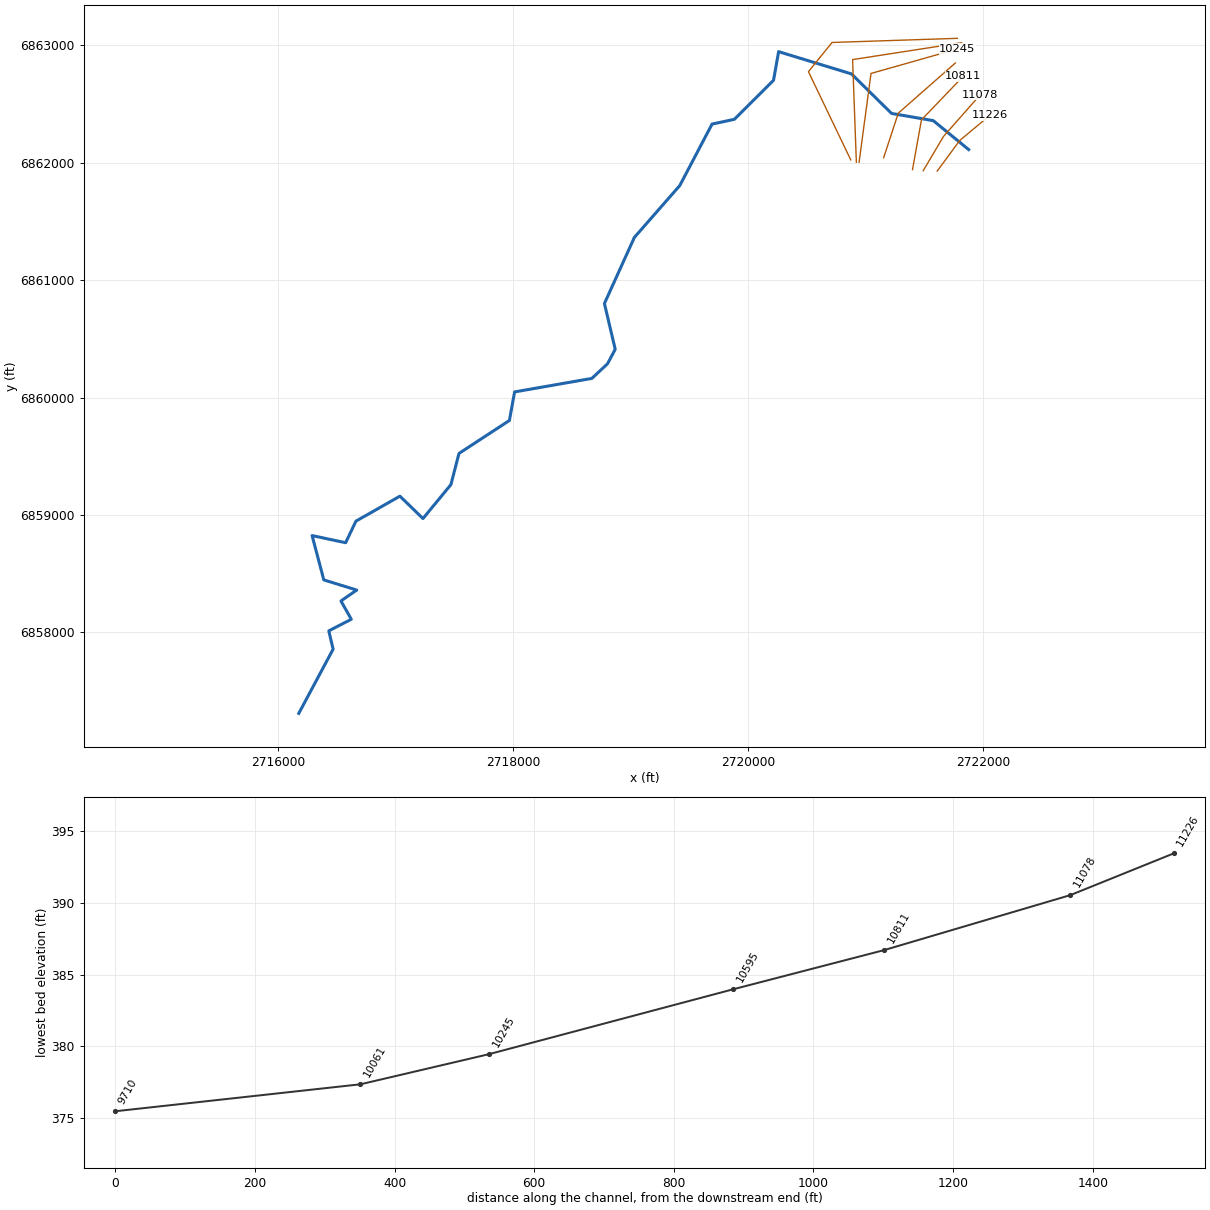
--- Lacy 138.prj (project) ---

Proj Title=Lacy 138 Base Level Engineering
Current Plan=p01
Default Exp/Contr=0.3,0.1
English Units
Geom File=g01
Flow File=f01
Plan File=p01
BEGIN DESCRIPTION:
Lacy 138
END DESCRIPTION:

--- Lacy 138.p01 (plan) ---

Plan Title=Multiple Run
Short Identifier=Multiple
Geom File=g01
Flow File=f01
Subcritical Flow
K Sum by GR= 0
Std Step Tol= 0.01
Critical Tol= 0.01
Num of Std Step Trials= 20
Max Error Tol= 0.3
Flow Tol Ratio= 0.001
Split Flow NTrial= 30
Split Flow Tol= 0.02
Split Flow Ratio= 0.02
Log Output Level= 0
Friction Slope Method= 1
Unsteady Friction Slope Method= 2
Unsteady Bridges Friction Slope Method= 1
Parabolic Critical Depth
Global Vel Dist=  1 , 1 , 1
Global Log Level= 0
CheckData=True
Encroach Param= -1, 0, 0, 0
BEGIN DESCRIPTION:
Multiple Run
END DESCRIPTION:

--- Lacy 138.f01 (steady flow) ---

Flow Title=Multiple
Number of Profiles=7
Profile Names=10-year,25-year,50-year,1pct_min,100-year,1pct_plu,500-year
River Rch & RM= Lacy 138,Reach-1,11226
     147     178     201     114     227     453     286
Boundary for River Rch & Prof#=Lacy 138,Reach-1,1
Up Type=0
Dn Type=3
Dn Slope=0.005
Boundary for River Rch & Prof#=Lacy 138,Reach-1,2
Up Type=0
Dn Type=3
Dn Slope=0.005
Boundary for River Rch & Prof#=Lacy 138,Reach-1,3
Up Type=0
Dn Type=3
Dn Slope=0.005
Boundary for River Rch & Prof#=Lacy 138,Reach-1,4
Up Type=0
Dn Type=3
Dn Slope=0.005
Boundary for River Rch & Prof#=Lacy 138,Reach-1,5
Up Type=0
Dn Type=3
Dn Slope=0.005
Boundary for River Rch & Prof#=Lacy 138,Reach-1,6
Up Type=0
Dn Type=3
Dn Slope=0.005
Boundary for River Rch & Prof#=Lacy 138,Reach-1,7
Up Type=0
Dn Type=3
Dn Slope=0.005

--- Lacy 138.g01 (geometry) ---

Geom Title=Existing Conditions

River Reach=Lacy 138,Reach-1
Reach XY= 30
      2721876.00      6862111.00      2721574.75      6862357.55
      2721219.66      6862419.02      2720878.43      6862755.48
      2720258.83      6862944.91      2720215.52      6862701.20
      2719882.19      6862368.82      2719692.45      6862328.14
      2719417.86      6861804.94      2719031.54      6861363.42
      2718776.65      6860800.36      2718868.47      6860410.99
      2718803.00      6860287.53      2718670.15      6860163.06
      2718012.26      6860047.80      2717968.19      6859804.81
      2717539.36      6859524.34      2717470.27      6859258.45
      2717232.80      6858969.77      2717036.71      6859160.28
      2716662.37      6858947.54      2716574.60      6858764.00
      2716289.36      6858824.81      2716388.96      6858447.37
      2716669.12      6858361.03      2716534.85      6858267.95
      2716622.90      6858112.18      2716431.40      6858013.46
      2716468.20      6857857.58      2716176.00      6857311.00

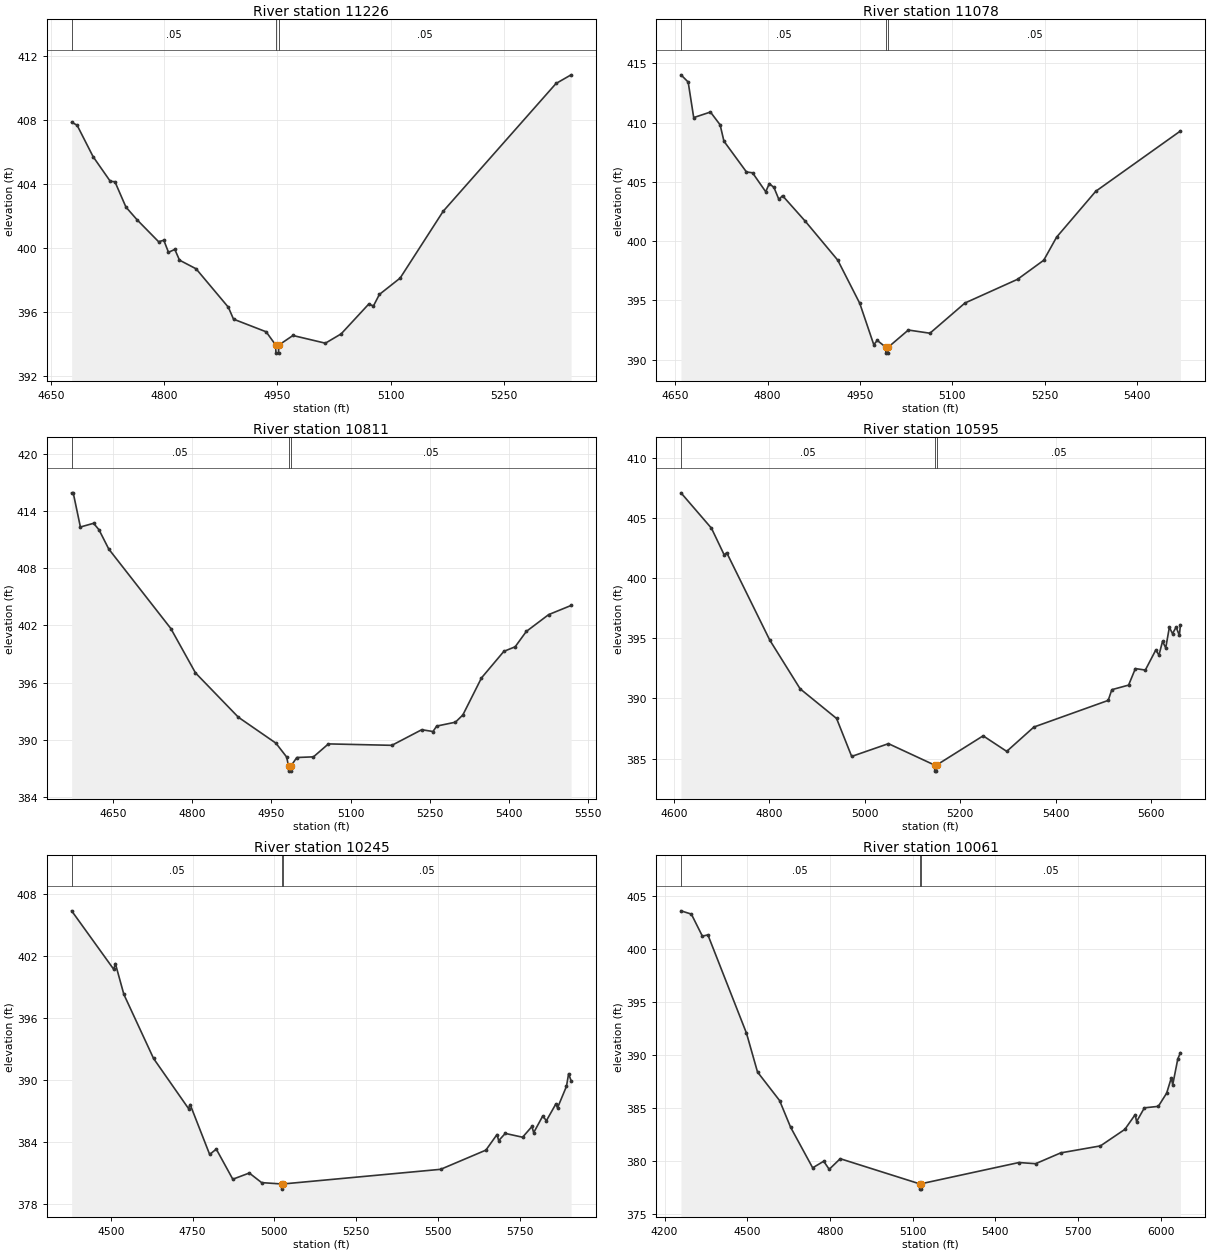
Type RM Length L Ch R = 1,11226,148,148,148
BEGIN DESCRIPTION:
Lacy 138 1099
END DESCRIPTION:
XS GIS Cut Line= 3
      2721608.24      6861928.12      2721799.57      6862188.23
      2722059.96      6862405.77
#Sta/Elev= 30
  4677.1  407.85  4684.3  407.67  4705.5  405.71  4728.3  404.17  4734.5  404.14
  4749.1  402.56  4763.8  401.77  4792.4  400.40  4799.3  400.49  4805.5  399.74
  4813.9  399.92  4820.1  399.25  4842.1  398.71  4884.9  396.31  4891.7  395.57
  4935.0  394.78  4947.7  393.95  4947.9  393.45  4951.4  393.45  4951.7  393.95
  4970.5  394.55  5013.5  394.07  5034.4  394.65  5070.8  396.50  5077.3  396.40
  5085.1  397.11  5112.6  398.13  5169.7  402.30  5319.3  410.27  5339.3  410.81
#Mann=3,-1,0
  4677.1    0.05       0  4947.7   0.035       0  4951.7    0.05       0
Bank Sta=4947.7,4951.7
Exp/Cntr=0.3,0.1

Type RM Length L Ch R = 1,11078,267,267,267
BEGIN DESCRIPTION:
Lacy 138 1100
END DESCRIPTION:
XS GIS Cut Line= 3
      2721488.86      6861930.92      2721662.35      6862224.26
      2721973.84      6862577.15
#Sta/Elev= 30
  4659.2  414.03  4670.9  413.42  4679.9  410.42  4707.1  410.89  4722.8  409.81
  4729.0  408.43  4765.6  405.83  4775.5  405.76  4796.9  404.16  4802.7  404.85
  4810.3  404.52  4818.3  403.51  4824.2  403.83  4861.2  401.67  4913.9  398.39
  4949.7  394.74  4972.4  391.26  4978.2  391.61  4991.9  391.04  4992.1  390.54
  4995.6  390.54  4995.9  391.04  5028.6  392.49  5063.7  392.22  5120.6  394.77
  5206.0  396.77  5248.6  398.38  5269.5  400.33  5333.1  404.20  5470.7  409.29
#Mann=3,-1,0
  4659.2    0.05       0  4991.9   0.035       0  4995.9    0.05       0
Bank Sta=4991.9,4995.9
Exp/Cntr=0.3,0.1

Type RM Length L Ch R = 1,10811,216,216,216
BEGIN DESCRIPTION:
Lacy 138 1090
END DESCRIPTION:
XS GIS Cut Line= 3
      2721398.00      6861940.05      2721474.03      6862363.97
      2721830.83      6862736.19
#Sta/Elev= 30
  4571.6  415.93  4574.6  415.93  4588.2  412.34  4613.2  412.73  4623.4  412.05
  4641.9  410.03  4759.5  401.68  4806.2  397.02  4887.5  392.36  4958.6  389.64
  4979.0  388.18  4982.6  387.20  4982.8  386.70  4986.3  386.70  4986.6  387.20
  4998.2  388.13  5029.8  388.20  5058.1  389.56  5178.3  389.41  5234.9  391.05
  5256.2  390.86  5263.2  391.43  5298.7  391.84  5312.8  392.60  5348.1  396.49
  5390.5  399.28  5411.9  399.76  5433.0  401.37  5475.4  403.14  5517.9  404.10
#Mann=3,-1,0
  4571.6    0.05       0  4982.6   0.035       0  4986.6    0.05       0
Bank Sta=4982.6,4986.6
Exp/Cntr=0.3,0.1

Type RM Length L Ch R = 1,10595,350,350,350
BEGIN DESCRIPTION:
Lacy 138 1091
END DESCRIPTION:
XS GIS Cut Line= 3
      2721152.33      6862041.36      2721277.08      6862421.31
      2721762.17      6862848.07
#Sta/Elev= 30
  4615.1  407.07  4679.0  404.13  4705.6  401.92  4710.9  402.10  4801.0  394.85
  4864.7  390.80  4941.0  388.34  4972.6  385.19  5049.6  386.25  5146.3  384.47
  5146.6  383.97  5150.1  383.97  5150.3  384.47  5247.9  386.90  5297.3  385.61
  5354.2  387.63  5509.8  389.84  5517.4  390.73  5552.5  391.11  5566.7  392.48
  5587.6  392.36  5609.4  394.02  5616.1  393.60  5623.6  394.74  5630.3  394.20
  5637.9  395.91  5644.5  395.38  5652.1  395.93  5658.8  395.23  5661.1  396.12
#Mann=3,-1,0
  4615.1    0.05       0  5146.3   0.035       0  5150.3    0.05       0
Bank Sta=5146.3,5150.3
Exp/Cntr=0.3,0.1

Type RM Length L Ch R = 1,10245,184,184,184
BEGIN DESCRIPTION:
Lacy 138 1092
END DESCRIPTION:
XS GIS Cut Line= 3
      2720943.28      6862002.72      2721044.98      6862759.24
      2721779.66      6862967.67
#Sta/Elev= 30
  4380.4  406.41  4509.1  400.74  4514.1  401.30  4540.1  398.31  4630.9  392.10
  4737.7  387.25  4742.7  387.64  4802.4  382.80  4822.6  383.32  4873.1  380.40
  4923.5  381.00  4961.3  380.07  5022.4  379.94  5022.7  379.44  5026.4  379.94
  5508.6  381.36  5646.9  383.22  5680.8  384.73  5686.0  384.14  5706.1  384.84
  5759.0  384.47  5787.7  385.51  5792.9  384.91  5820.4  386.51  5832.0  386.08
  5860.7  387.69  5865.9  387.32  5893.2  389.40  5899.8  390.63  5907.4  389.94
#Mann=3,-1,0
  4380.4    0.05       0  5022.4   0.035       0  5026.4    0.05       0
Bank Sta=5022.4,5026.4
Exp/Cntr=0.3,0.1

Type RM Length L Ch R = 1,10061,351,351,351
BEGIN DESCRIPTION:
Lacy 138 3454
END DESCRIPTION:
XS GIS Cut Line= 3
      2720920.35      6862003.36      2720888.23      6862877.29
      2721815.37      6863020.80
#Sta/Elev= 30
  4259.5  403.60  4297.2  403.29  4337.2  401.21  4357.2  401.33  4497.3  392.05
  4537.3  388.39  4617.4  385.70  4657.4  383.18  4737.5  379.35  4777.5  379.97
  4797.5  379.21  4837.5  380.21  5125.7  377.84  5126.0  377.34  5129.5  377.34
  5129.7  377.84  5485.9  379.85  5546.6  379.74  5637.7  380.76  5781.9  381.42
  5870.5  382.98  5908.0  384.37  5913.0  383.71  5941.3  385.01  5991.9  385.15
  6022.2  386.40  6039.1  387.84  6044.2  387.19  6062.7  389.64  6072.2  390.21
#Mann=3,-1,0
  4259.5    0.05       0  5125.7   0.035       0  5129.7    0.05       0
Bank Sta=5125.7,5129.7
Exp/Cntr=0.3,0.1

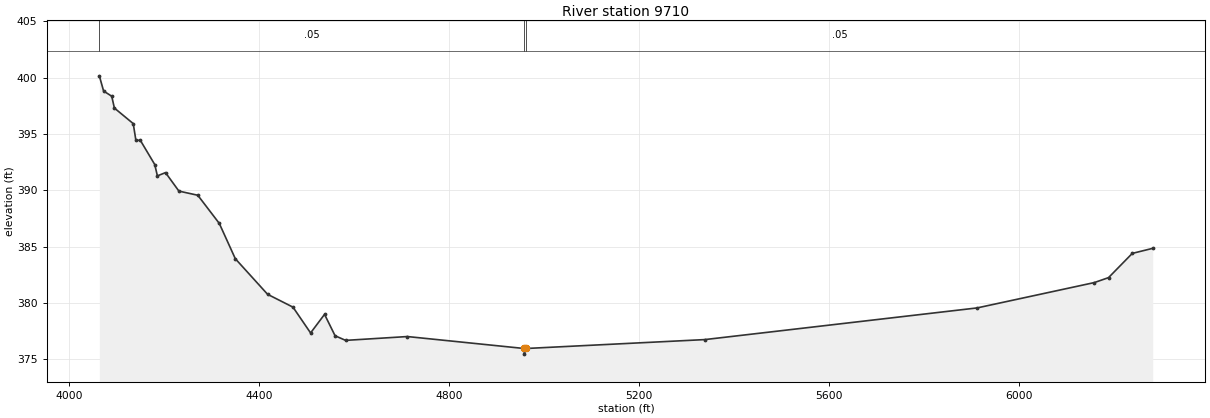
Type RM Length L Ch R = 1,9710,0,0,0
BEGIN DESCRIPTION:
Lacy 138 3455
END DESCRIPTION:
XS GIS Cut Line= 4
      2720872.63      6862023.16      2720512.51      6862774.48
      2720713.51      6863023.07      2721779.08      6863058.29
#Sta/Elev= 30
  4063.3  400.16  4072.3  398.81  4089.4  398.35  4095.0  397.30  4134.7  395.92
  4140.3  394.44  4149.6  394.44  4180.0  392.29  4185.6  391.28  4202.7  391.57
  4230.9  389.93  4270.7  389.56  4316.0  387.06  4349.7  383.93  4417.7  380.77
  4471.2  379.63  4508.3  377.34  4537.7  378.99  4559.9  377.09  4582.1  376.68
  4712.2  377.02  4958.2  375.96  4958.5  375.46  4962.2  375.96  5338.7  376.75
  5912.2  379.56  6159.2  381.81  6189.2  382.25  6239.2  384.40  6282.3  384.85
#Mann=3,-1,0
  4063.3    0.05       0  4958.2   0.035       0  4962.2    0.05       0
Bank Sta=4958.2,4962.2
Exp/Cntr=0.3,0.1

Chan Stop Cuts=-1