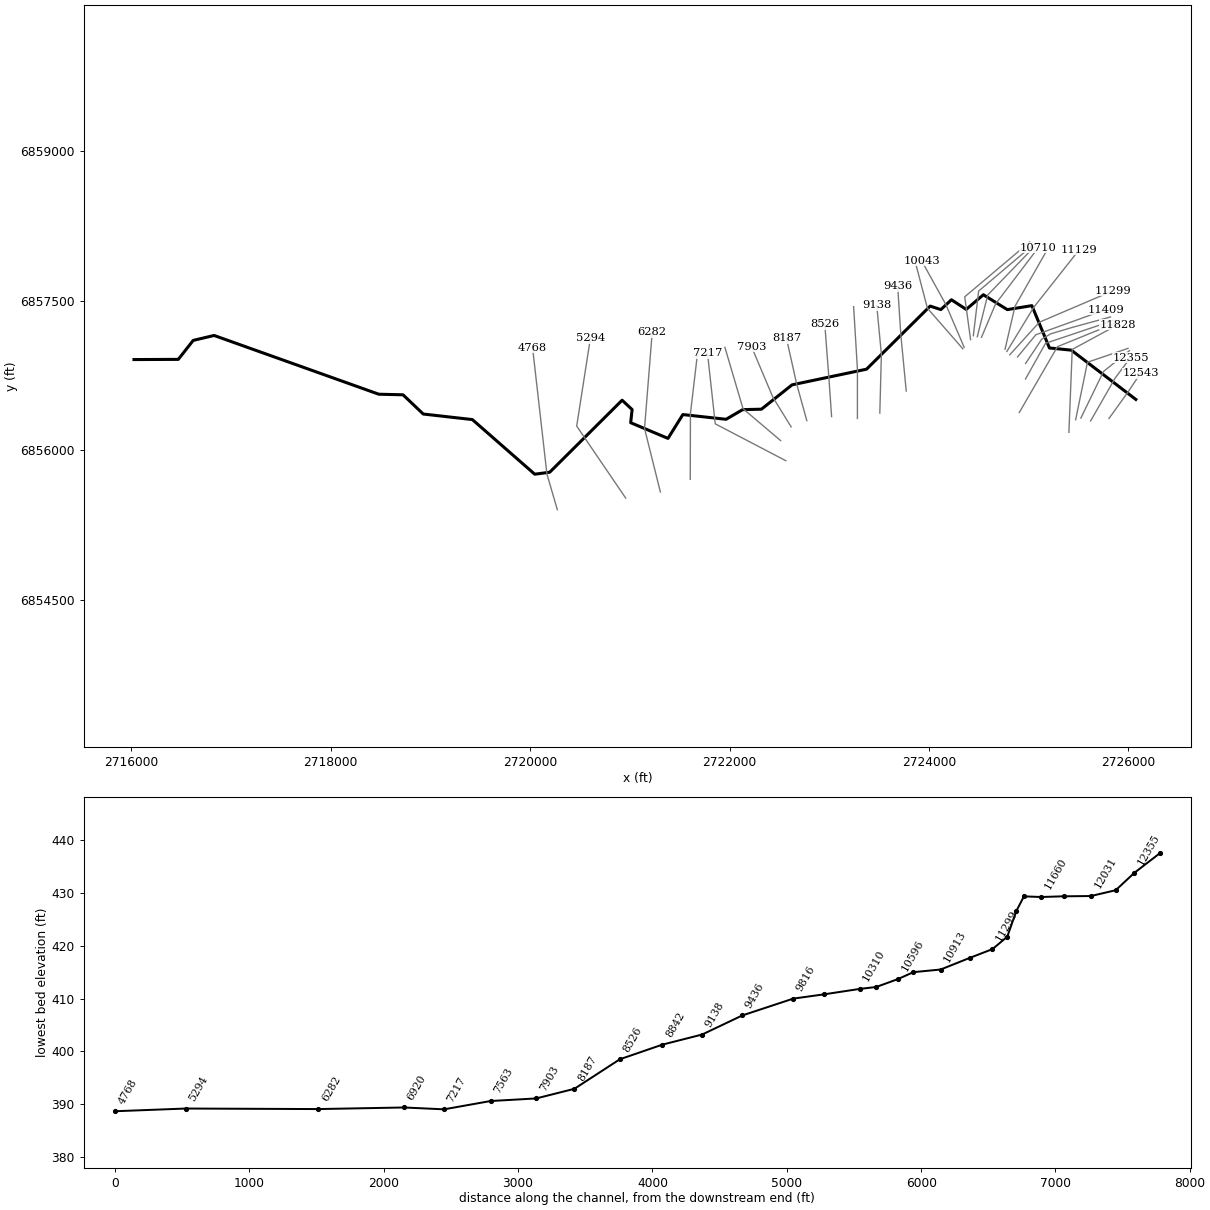
--- Lacy 139.prj (project) ---

Proj Title=Lacy 139 Base Level Engineering
Current Plan=p01
Default Exp/Contr=0.3,0.1
English Units
Geom File=g01
Flow File=f01
Plan File=p01
Y Axis Title=Elevation
X Axis Title(PF)=Main Channel Distance
X Axis Title(XS)=Station
BEGIN DESCRIPTION:
Lacy 139
END DESCRIPTION:
DSS Export Rating Curves= 0
DSS Export Rating Curve Sorted= 0
DSS Export Volume Flow Curves= 0
DXF OffsetX= 0
DXF OffsetY= 0
DXF ScaleX= 1
DXF ScaleY= 10

--- Lacy 139.p01 (plan) ---

Plan Title=Multiple Run
Short Identifier=Multiple
Geom File=g01
Flow File=f01
Subcritical Flow
K Sum by GR= 0
Std Step Tol= 0.01
Critical Tol= 0.01
Num of Std Step Trials= 20
Max Error Tol= 0.3
Flow Tol Ratio= 0.001
Split Flow NTrial= 30
Split Flow Tol= 0.02
Split Flow Ratio= 0.02
Log Output Level= 0
Friction Slope Method= 1
Unsteady Friction Slope Method= 2
Unsteady Bridges Friction Slope Method= 1
Parabolic Critical Depth
Global Vel Dist=  1 , 1 , 1
Global Log Level= 0
CheckData=True
Encroach Param= -1, 0, 0, 0
BEGIN DESCRIPTION:
Multiple Run
END DESCRIPTION:

--- Lacy 139.f01 (steady flow) ---

Flow Title=Multiple
Number of Profiles=7
Profile Names=10-year,25-year,50-year,1pct_min,100-year,1pct_plu,500-year
River Rch & RM= Lacy 139,Reach-1,12543
     345     448     530     312     623    1243     857
River Rch & RM= Lacy 139,Reach-1,10043
     573     767     924     553    1104    2203    1573
River Rch & RM= Lacy 139,Reach-1,6920
     649     871    1051     629    1254    2503    1786
River Rch & RM= Lacy 139,Reach-1,3852
     748    1014    1231     741    1479    2950    2132
Boundary for River Rch & Prof#=Lacy 139,Reach-1,1
Up Type=0
Dn Type=3
Dn Slope=0.005
Boundary for River Rch & Prof#=Lacy 139,Reach-1,2
Up Type=0
Dn Type=3
Dn Slope=0.005
Boundary for River Rch & Prof#=Lacy 139,Reach-1,3
Up Type=0
Dn Type=3
Dn Slope=0.005
Boundary for River Rch & Prof#=Lacy 139,Reach-1,4
Up Type=0
Dn Type=3
Dn Slope=0.005
Boundary for River Rch & Prof#=Lacy 139,Reach-1,5
Up Type=0
Dn Type=3
Dn Slope=0.005
Boundary for River Rch & Prof#=Lacy 139,Reach-1,6
Up Type=0
Dn Type=3
Dn Slope=0.005
Boundary for River Rch & Prof#=Lacy 139,Reach-1,7
Up Type=0
Dn Type=3
Dn Slope=0.005

--- Lacy 139.g01 (geometry) ---

Geom Title=Existing Conditions
Program Version=4.10

River Reach=Lacy 139        ,Reach-1
Reach XY= 30
        2726076.        6856511.      2725428.45      6857005.54
       2725209.2      6857027.41      2725033.07      6857452.01
       2724786.5       6857412.2      2724546.37      6857561.37
      2724374.27       6857414.3        2724226.        6857511.
      2724119.96       6857412.6      2724012.62      6857447.46
       2723374.5      6856814.61      2722627.47      6856657.45
      2722320.15      6856413.06      2722131.93      6856408.76
       2721965.3       6856311.8      2721531.67      6856359.14
      2721382.76      6856120.12      2721008.44      6856277.63
      2721022.84      6856409.38      2720922.68      6856503.42
      2720196.16       6855780.6      2720045.99      6855760.94
      2719420.16      6856308.98       2718927.5      6856364.62
      2718724.74      6856557.52      2718481.94      6856563.26
       2716829.3      6857152.92      2716619.79      6857103.19
      2716470.33      6856912.98        2716026.        6856911.

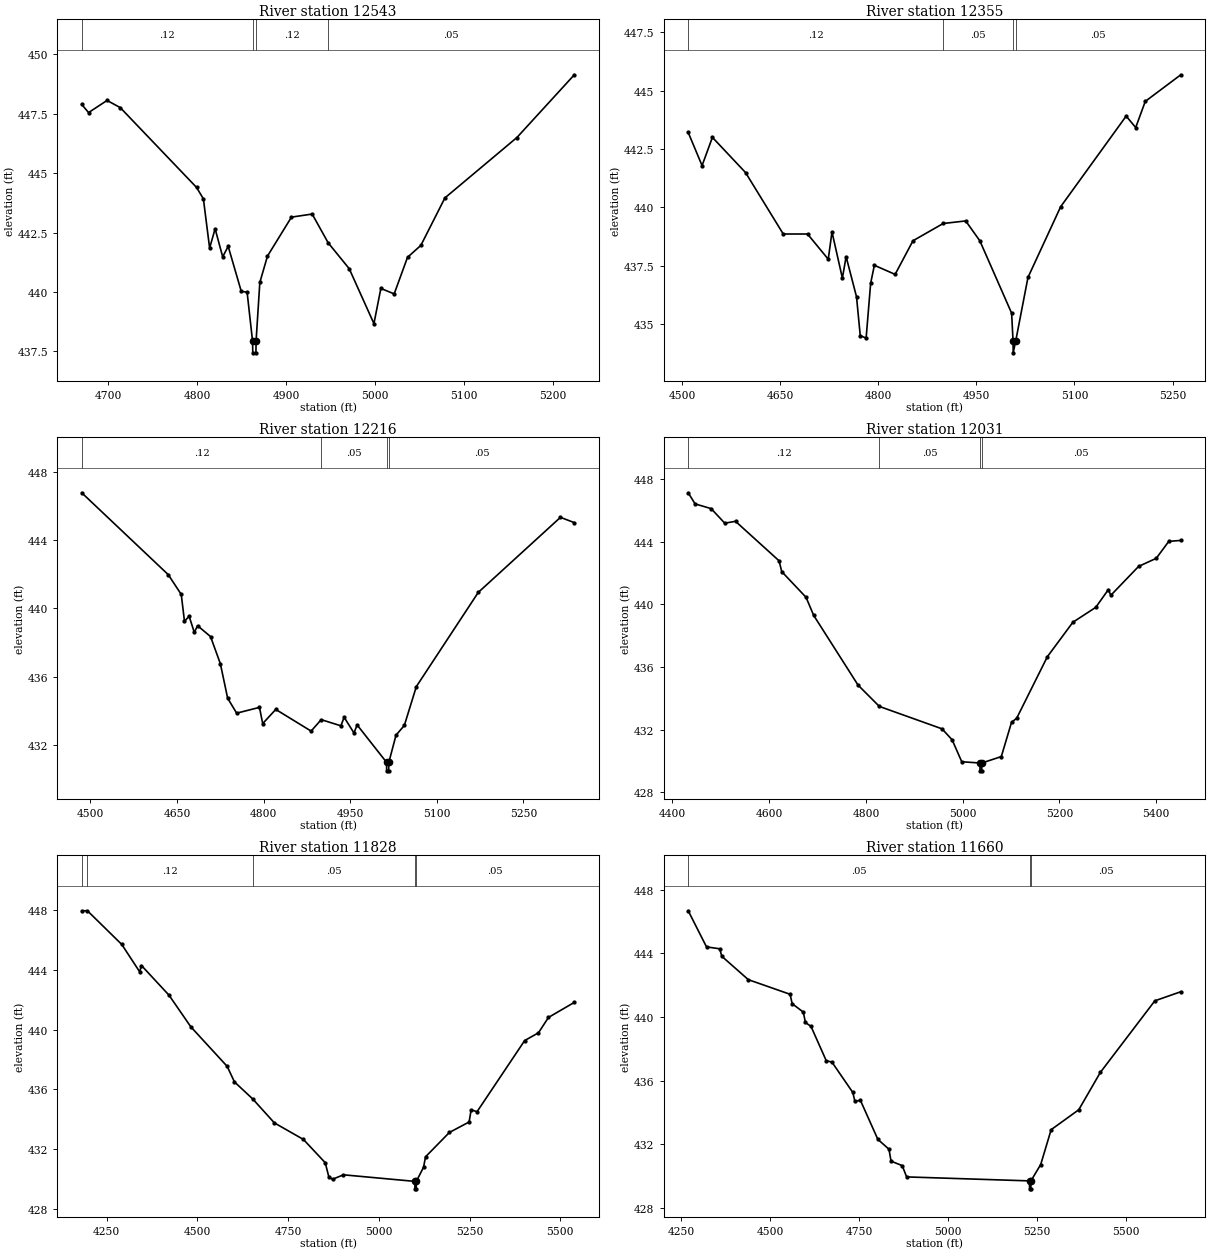
Type RM Length L Ch R = 1 ,12543   ,188,188,188
BEGIN DESCRIPTION:
Lacy 139 1074
END DESCRIPTION:
XS GIS Cut Line= 3
      2725806.42      6856319.91      2725999.03      6856587.63
      2726123.98      6856774.14
#Sta/Elev= 30
  4670.2  447.89  4677.9  447.55  4698.7  448.06  4713.5  447.76  4799.4   444.4
  4807.1  443.92  4814.1  441.85  4820.3  442.66  4828.8  441.48    4835  441.92
  4849.7  440.03  4856.3  439.99  4862.4  437.94  4862.7  437.44  4866.2  437.44
  4866.4  437.94  4870.6   440.4  4879.2  441.51  4906.2  443.15  4929.5  443.28
  4947.5  442.07  4971.2  440.98    4999  438.67  5006.8  440.15  5021.8  439.92
  5036.8  441.46  5051.8  441.96  5078.9  443.96  5159.9   446.5  5224.5  449.14
#Mann= 4 ,-1 , 0
  4670.2     .12       0  4862.4     .04       0  4866.4     .12       0
  4947.5     .05       0
Bank Sta=4862.4,4866.4
XS Rating Curve= 0 ,0
Exp/Cntr=0.3,0.1

Type RM Length L Ch R = 1 ,12355   ,139,139,139
BEGIN DESCRIPTION:
Lacy 139 1073
END DESCRIPTION:
XS GIS Cut Line= 3
      2725622.02      6856294.86      2725867.47        6856724.
      2726022.18      6856931.26
#Sta/Elev= 30
  4509.6  443.21  4530.8  441.79  4546.6     443  4597.3  441.49  4654.9  438.86
    4692  438.86  4723.7  437.78  4729.4  438.95  4745.3  436.97    4751  437.89
  4766.9  436.17  4772.6  434.51  4781.6   434.4  4788.5  436.75  4794.2  437.52
  4825.9  437.13  4853.2  438.57  4899.4  439.31  4933.8  439.42  4955.4  438.57
    5004  435.47  5006.2  434.27  5006.4  433.77  5010.2  434.27    5029     437
    5079  440.03  5179.1  443.91  5193.7  443.42  5208.3  444.54  5262.6  445.68
#Mann= 4 ,-1 , 0
  4509.6     .12       0  4899.4     .05       0  5006.2     .04       0
  5010.2     .05       0
Bank Sta=5006.2,5010.2
XS Rating Curve= 0 ,0
Exp/Cntr=0.3,0.1

Type RM Length L Ch R = 1 ,12216   ,185,185,185
BEGIN DESCRIPTION:
Lacy 139 1072
END DESCRIPTION:
XS GIS Cut Line= 3
      2725524.42      6856323.72      2725751.37      6856791.42
       2726010.8      6857000.11
#Sta/Elev= 30
  4485.2  446.78    4635  441.98  4657.5  440.82  4663.1  439.24  4671.1  439.55
  4680.1  438.59  4685.7  438.99  4708.2  438.35  4725.2  436.76  4737.8  434.74
  4753.4  433.86  4792.9   434.2  4798.5  433.25  4821.1  434.08  4882.3  432.81
  4899.8  433.48  4933.9  433.12  4939.5  433.62  4956.5   432.7    4962  433.17
  5012.9  430.98  5013.1  430.48  5016.6  430.48  5016.9  430.98  5029.3  432.57
  5043.7  433.14  5064.5  435.42  5171.7  440.94    5314  445.34    5338  445.03
#Mann= 4 ,-1 , 0
  4485.2     .12       0  4899.8     .05       0  5012.9     .04       0
  5016.9     .05       0
Bank Sta=5012.9,5016.9
XS Rating Curve= 0 ,0
Exp/Cntr=0.3,0.1

Type RM Length L Ch R = 1 ,12031   ,203,203,203
BEGIN DESCRIPTION:
Lacy 139 1071
END DESCRIPTION:
XS GIS Cut Line= 3
      2725471.97      6856306.96      2725590.63      6856883.78
        2725997.      6857023.15
#Sta/Elev= 30
  4432.5  447.12  4446.8  446.41  4479.9  446.11  4508.1  445.18  4530.3   445.3
  4620.4  442.78  4625.9  442.09  4676.2  440.45  4691.9   439.3  4783.7  434.85
  4827.7  433.49  4957.3  432.06  4978.2  431.36  4998.1  429.96  5035.6  429.88
  5035.9  429.38  5039.4  429.38  5039.6  429.88  5079.9  430.29  5101.1  432.48
  5111.6  432.73  5175.1  436.66  5227.9  438.86  5275.2  439.81  5301.2  440.94
  5306.4  440.58  5363.7  442.42  5400.3  442.94  5426.2  444.02    5451  444.08
#Mann= 4 ,-1 , 0
  4432.5     .12       0  4827.7     .05       0  5035.6     .04       0
  5039.6     .05       0
Bank Sta=5035.6,5039.6
XS Rating Curve= 0 ,0
Exp/Cntr=0.3,0.1

Type RM Length L Ch R = 1 ,11828   ,168,168,168
BEGIN DESCRIPTION:
Lacy 139 1069
END DESCRIPTION:
XS GIS Cut Line= 3
      2725404.43      6856180.65      2725437.85      6857012.69
      2725898.94      6857262.45
#Sta/Elev= 30
  4181.5  447.97  4197.2  447.97  4291.9  445.71  4341.1  443.88  4346.1   444.3
    4422  442.31  4482.1  440.19  4582.2  437.54  4602.2   436.5  4652.4  435.36
  4712.3  433.75  4792.3  432.64  4852.4  431.08  4862.4  430.12  4872.4  429.97
  4902.4  430.27  5099.3  429.83  5099.5  429.33    5103  429.33  5103.3  429.83
  5123.1  430.77  5128.8  431.48  5194.4  433.11  5248.7  433.81  5254.4  434.63
  5270.6   434.5  5401.8  439.27  5439.8  439.79  5467.4  440.82  5538.6  441.83
#Mann= 5 ,-1 , 0
  4181.5     .05       0  4197.2     .12       0  4652.4     .05       0
  5099.3     .03       0  5103.3     .05       0
Bank Sta=5099.3,5103.3
XS Rating Curve= 0 ,0
Exp/Cntr=0.3,0.1

Type RM Length L Ch R = 1 ,11660   ,127,127,127
BEGIN DESCRIPTION:
Lacy 139 1070
END DESCRIPTION:
XS GIS Cut Line= 3
       2724906.4       6856379.4      2725289.64       6857040.4
      2725865.65      6857274.68
#Sta/Elev= 30
  4269.5  446.68    4321  444.41  4358.2  444.29    4364  443.82  4438.6  442.35
  4556.2  441.43    4562  440.84  4593.4  440.31  4599.2  439.66    4615  439.41
    4658  437.25  4673.8  437.17  4732.6  435.26  4738.4  434.71  4754.1  434.76
  4803.1  432.31  4834.4  431.69  4840.2  430.94  4871.7  430.66    4884  429.95
  5229.8   429.7    5230   429.2  5233.5   429.2  5233.8   429.7  5261.3  430.73
  5290.7  432.92  5368.3  434.17  5429.1  436.52  5582.4  441.02  5655.4  441.59
#Mann= 3 ,-1 , 0
  4269.5     .05       0  5229.8     .04       0  5233.8     .05       0
Bank Sta=5229.8,5233.8
XS Rating Curve= 0 ,0
Exp/Cntr=0.3,0.1

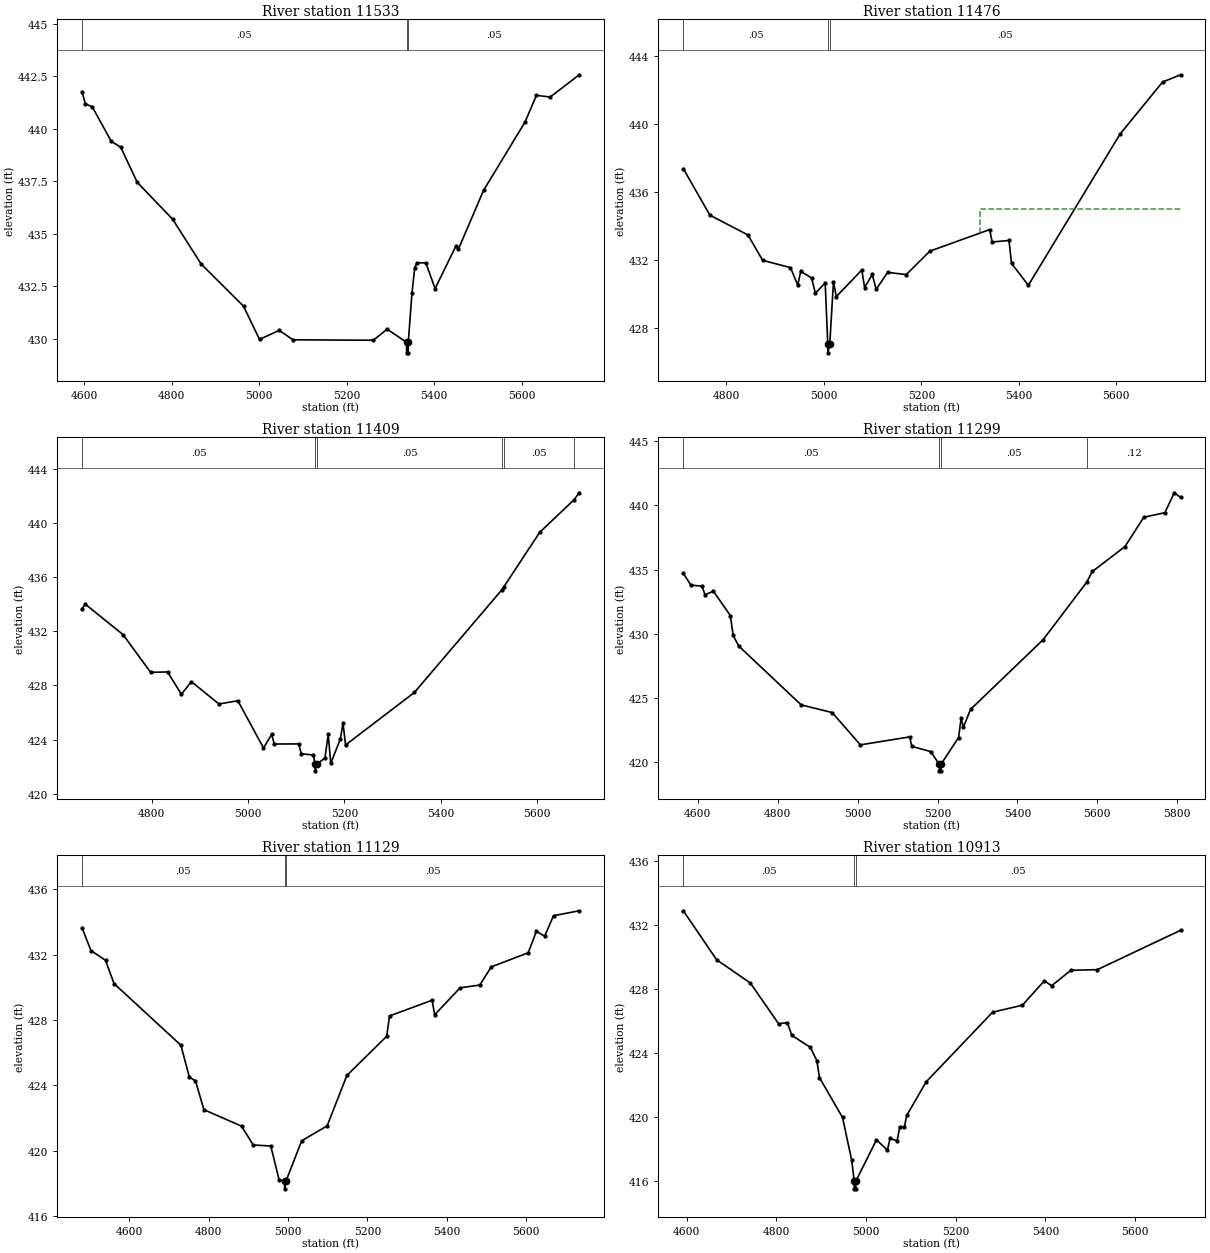
Type RM Length L Ch R = 1 ,11533   ,57,57,57
BEGIN DESCRIPTION:
Lacy 139 1068
END DESCRIPTION:
XS GIS Cut Line= 3
      2724969.06      6856716.02      2725169.92      6857073.97
      2725858.31      6857305.67
#Sta/Elev= 30
    4595  441.76  4602.7  441.18  4618.7  441.03    4662  439.39  4683.7  439.11
  4721.3  437.44  4802.4  435.68  4867.4  433.55  4964.4  431.54  5000.9  429.96
    5046  430.39  5077.5  429.94  5261.2  429.92  5292.7  430.45    5337  429.82
  5337.2  429.32  5340.7  429.32    5341  429.82  5349.5  432.18  5355.7  433.36
    5361  433.61  5381.2   433.6  5402.3  432.38  5450.2  434.42  5455.5  434.25
  5513.2  437.06  5607.7   440.3    5634  441.58  5665.5   441.5  5731.8  442.56
#Mann= 3 ,-1 , 0
    4595     .05       0    5337     .04       0    5341     .05       0
Bank Sta=5337,5341
XS Rating Curve= 0 ,0
Exp/Cntr=0.3,0.1

Type RM Length L Ch R = 1 ,11476   ,67,67,67
BEGIN DESCRIPTION:
Lacy 139 1057
END DESCRIPTION:
XS GIS Cut Line= 5
      2724969.82      6856871.89      2725131.53      6857114.63
      2725220.57      6857168.67       2725437.1      6857233.47
      2725821.68      6857338.43
#Sta/Elev= 30
  4711.4  437.37    4766  434.63  4844.2  433.46  4874.2  431.97  4931.3  431.54
  4946.3  430.51  4952.3  431.32  4974.7  430.93  4982.4  430.03  5002.6  430.64
  5007.9  427.02  5008.2  426.52  5011.9  427.02  5019.6  430.71  5025.4  429.83
  5077.7   431.4  5083.6  430.36  5099.1  431.14  5107.2  430.26  5130.7  431.26
    5169  431.13  5217.3  432.51  5340.1  433.78  5345.3  433.05  5379.8  433.14
    5385  431.79  5419.5   430.5  5607.8  439.41  5694.9  442.47  5731.9   442.9
#Mann= 3 ,-1 , 0
  4711.4     .05       0  5007.9     .04       0  5011.9     .05       0
#XS Ineff= 2 , 0
       0                    5321       0     435
Permanent Ineff=
       F       F
Bank Sta=5007.9,5011.9
XS Rating Curve= 0 ,0
Exp/Cntr=0.3,0.1

Type RM Length L Ch R = 1 ,11409   ,110,110,110
BEGIN DESCRIPTION:
Lacy 139 1058
END DESCRIPTION:
XS GIS Cut Line= 3
      2724888.98      6856937.52       2725073.2      6857160.03
      2725772.65      6857412.21
#Sta/Elev= 30
    4655  433.68  4662.1     434  4740.2  431.76  4797.6  428.97  4832.7     429
  4861.4  427.35  4882.2  428.28  4939.5  426.63  4978.7  426.87  5031.9  423.38
  5048.9  424.38  5054.2  423.67  5104.9  423.68  5110.3  422.95  5135.6  422.86
  5138.9  422.19  5139.2  421.69  5142.9  422.19  5159.5  422.64  5166.3  424.38
  5171.6  422.24  5191.3  424.03    5197   425.2  5202.3   423.6  5345.1  427.48
  5526.9  435.07  5531.3  435.31  5605.4  439.32  5676.9  441.73  5687.4  442.24
#Mann= 6 ,-1 , 0
    4655     .05       0  5138.9     .04       0  5142.9     .05       0
  5526.9     .12       0  5531.3     .05       0  5676.9     .12       0
Bank Sta=5138.9,5142.9
XS Rating Curve= 0 ,0
Exp/Cntr=0.3,0.1

Type RM Length L Ch R = 1 ,11299   ,170,170,170
BEGIN DESCRIPTION:
Lacy 139 1059
END DESCRIPTION:
XS GIS Cut Line= 3
       2724811.4      6856959.09      2725107.71      6857285.52
      2725846.94      6857601.52
#Sta/Elev= 30
  4563.6  434.71  4582.2   433.8  4610.5   433.7    4618  433.04  4638.9  433.32
  4681.5  431.42  4688.3  429.89  4702.4  429.05  4858.6  424.48  4936.3  423.88
  5006.9  421.37  5130.3  421.99  5135.7  421.25  5182.9  420.85  5204.5  419.85
  5204.7  419.35  5208.2  419.35  5208.5  419.85  5252.7  421.94  5259.1  423.44
  5264.6  422.73  5282.7  424.13  5464.2  429.54  5573.3  434.01  5587.6  434.85
  5669.3  436.79  5716.5  439.07  5769.1  439.42  5792.7  440.97  5808.4  440.61
#Mann= 4 ,-1 , 0
  4563.6     .05       0  5204.5     .04       0  5208.5     .05       0
  5573.3     .12       0
Bank Sta=5204.5,5208.5
XS Rating Curve= 0 ,0
Exp/Cntr=0.3,0.1

Type RM Length L Ch R = 1 ,11129   ,216,216,216
BEGIN DESCRIPTION:
Lacy 139 1060
END DESCRIPTION:
XS GIS Cut Line= 3
      2724781.97      6856992.14      2725051.37      6857434.87
        2725507.       6858011.8
#Sta/Elev= 30
  4480.6  433.65  4503.2  432.25    4540  431.65  4561.4  430.23  4729.9  426.46
  4751.2  424.52  4766.7  424.28    4788  422.52  4882.9  421.51  4912.4  420.36
  4956.5   420.3  4977.8  418.21  4991.3  418.18  4991.6  417.68  4995.3  418.18
  5034.5  420.62  5098.6  421.53  5148.3  424.61  5248.8  427.01  5255.8  428.25
  5363.2  429.21  5369.6  428.32  5433.7  429.97  5483.4  430.14  5512.3  431.25
  5605.3  432.11  5626.1  433.42  5646.9  433.13  5669.3  434.38    5734  434.68
#Mann= 3 ,-1 , 0
  4480.6     .05       0  4991.3     .04       0  4995.3     .05       0
Bank Sta=4991.3,4995.3
XS Rating Curve= 0 ,0
Exp/Cntr=0.3,0.1

Type RM Length L Ch R = 1 ,10913   ,203,203,203
BEGIN DESCRIPTION:
Lacy 139 1061
END DESCRIPTION:
XS GIS Cut Line= 3
      2724763.84      6857015.14       2724863.9      6857446.08
      2725193.93      6858025.24
#Sta/Elev= 30
  4592.3  432.87  4666.6  429.81    4742  428.35  4804.8  425.81  4824.2  425.88
  4834.4  425.08  4875.5  424.34  4890.1  423.51    4896  422.44  4947.4  419.95
  4967.9  417.27  4973.4  415.99  4973.6  415.49  4977.1  415.49  4977.4  415.99
  5023.1  418.55  5047.6  417.91  5053.3  418.64  5069.2  418.49    5075  419.36
  5085.1  419.33  5090.8  420.09    5134  422.18  5282.1  426.53  5348.7  426.97
  5397.7   428.5  5413.5  428.18  5456.7  429.15  5515.8  429.19  5701.3  431.65
#Mann= 3 ,-1 , 0
  4592.3     .05       0  4973.4     .04       0  4977.4     .05       0
Bank Sta=4973.4,4977.4
XS Rating Curve= 0 ,0
Exp/Cntr=0.3,0.1

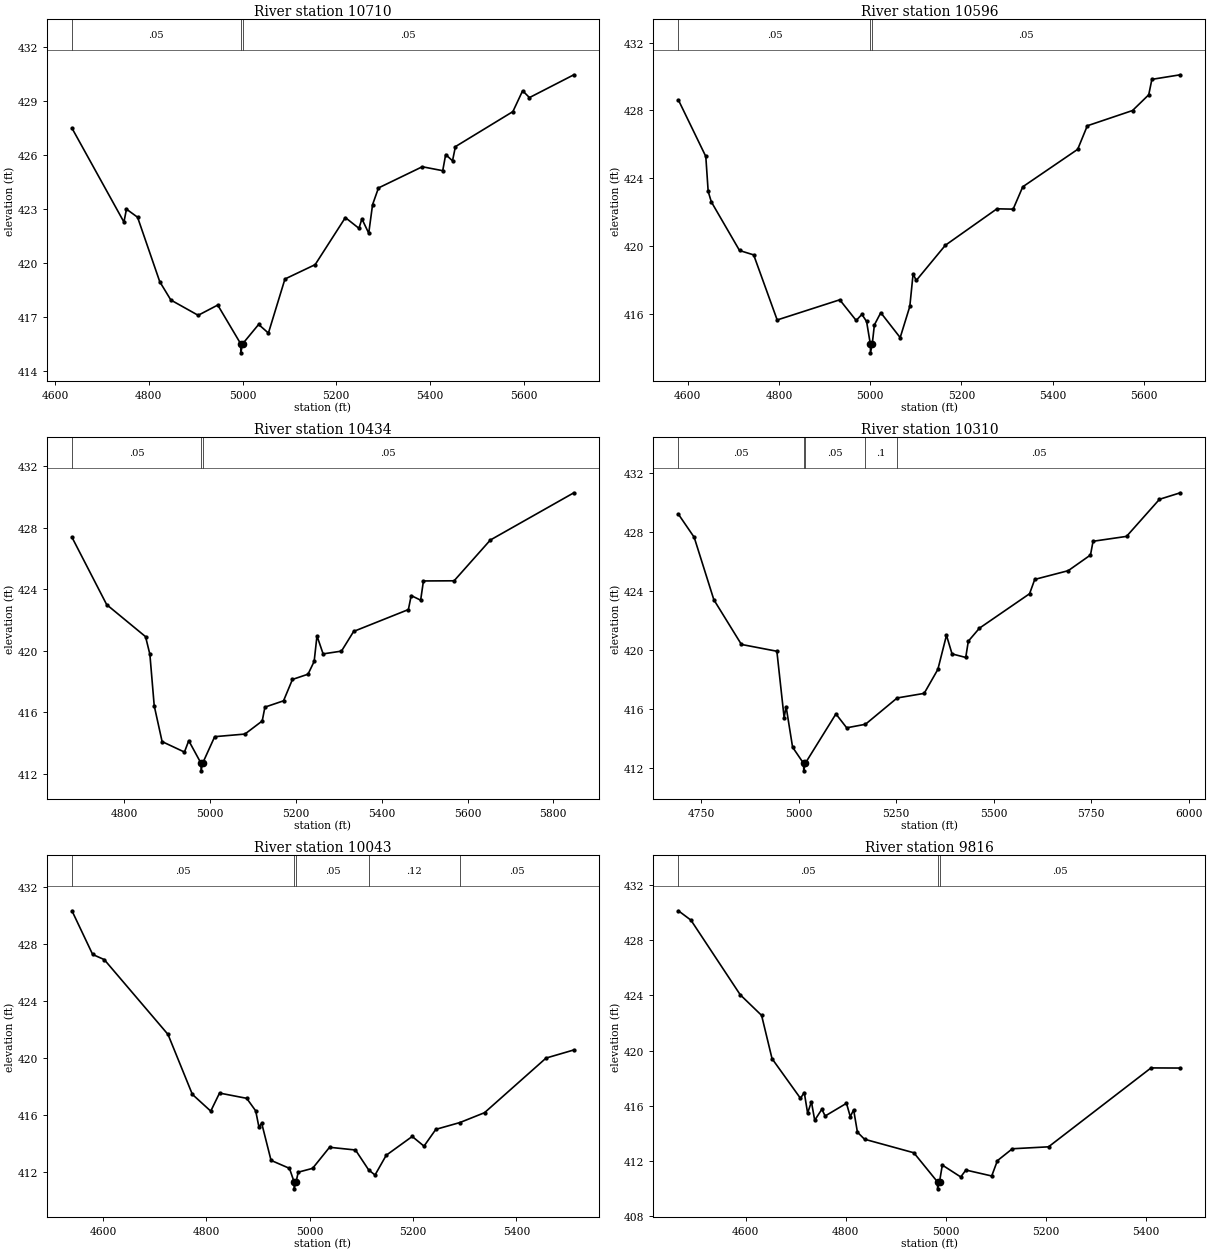
Type RM Length L Ch R = 1 ,10710   ,114,114,114
BEGIN DESCRIPTION:
Lacy 139 1062
END DESCRIPTION:
XS GIS Cut Line= 3
      2724527.57      6857134.26      2724669.52      6857470.12
      2725096.88      6858033.43
#Sta/Elev= 30
  4635.8   427.5  4746.8  422.27  4752.2  422.99  4775.9  422.54  4823.3  418.95
    4847  417.93  4905.3  417.08  4947.1  417.65  4996.2  415.49  4996.4  414.99
  5000.2  415.49  5034.4  416.57  5055.3  416.09  5090.6   419.1  5155.1   419.9
  5219.6  422.52  5248.7  421.92  5254.9  422.45  5269.5  421.65  5277.7  423.24
  5290.3  424.17  5383.9  425.35  5427.5  425.13  5433.8  426.03  5448.4  425.68
  5454.6  426.47  5577.3  428.42  5598.1  429.58  5612.7   429.2  5707.5  430.47
#Mann= 3 ,-1 , 0
  4635.8     .05       0  4996.2     .04       0  5000.2     .05       0
Bank Sta=4996.2,5000.2
XS Rating Curve= 0 ,0
Exp/Cntr=0.3,0.1

Type RM Length L Ch R = 1 ,10596   ,162,162,162
BEGIN DESCRIPTION:
Lacy 139 1063
END DESCRIPTION:
XS GIS Cut Line= 3
      2724485.58      6857141.08      2724590.36      6857559.19
      2725054.84      6858040.19
#Sta/Elev= 30
  4579.8  428.61  4639.8  425.28    4645  423.22  4651.9   422.6  4713.7  419.73
  4744.7  419.47  4796.2  415.63  4933.3  416.82  4969.3   415.6  4981.8  415.96
  4992.1  415.54  5000.4  414.19  5000.6  413.69  5004.4  414.19  5009.2  415.34
  5023.2  416.06  5065.7  414.59  5086.8  416.43    5094  418.35  5100.9  417.96
  5164.7  420.04  5277.7  422.19  5313.2  422.17  5334.3  423.49  5454.6   425.7
  5475.7  427.09  5574.8  427.99  5610.3  428.92  5617.2  429.83  5679.5   430.1
#Mann= 3 ,-1 , 0
  4579.8     .05       0  5000.4     .04       0  5004.4     .05       0
Bank Sta=5000.4,5004.4
XS Rating Curve= 0 ,0
Exp/Cntr=0.3,0.1

Type RM Length L Ch R = 1 ,10434   ,124,124,124
BEGIN DESCRIPTION:
Lacy 139 1064
END DESCRIPTION:
XS GIS Cut Line= 3
      2724445.72      6857150.56      2724499.14      6857598.62
      2725047.68       6858063.4
#Sta/Elev= 30
  4677.7  427.37  4758.7  422.99  4849.3  420.91  4859.4  419.76  4869.5  416.42
  4887.9  414.09    4940  413.41    4950  414.15  4978.5  412.69  4978.8  412.19
  4982.5  412.69  5010.5  414.41    5081  414.58  5121.3  415.43  5127.6  416.33
    5171  416.74  5191.8  418.13  5228.1  418.47  5242.4   419.3    5249  420.96
  5263.3  419.79  5306.1  419.97  5334.5  421.25  5462.1  422.67  5468.7  423.58
  5490.7  423.28  5497.2  424.53  5568.7  424.54  5653.2  427.19  5847.9  430.26
#Mann= 3 ,-1 , 0
  4677.7     .05       0  4978.5     .04       0  4982.5     .05       0
Bank Sta=4978.5,4982.5
XS Rating Curve= 0 ,0
Exp/Cntr=0.3,0.1

Type RM Length L Ch R = 1 ,10310   ,267,267,267
BEGIN DESCRIPTION:
Lacy 139 1065
END DESCRIPTION:
XS GIS Cut Line= 3
      2724418.02      6857110.93      2724359.53      6857540.81
      2725011.37      6858090.79
#Sta/Elev= 30
    4692  429.18  4732.4  427.62  4782.9  423.39  4853.5  420.37  4944.4  419.91
    4963  415.42  4968.1  416.16  4984.7  413.42    5013  412.32  5013.3  411.82
    5017  412.32  5095.8  415.67  5123.4  414.73  5171.5  414.97  5252.8  416.75
    5322  417.06  5357.1  418.68  5379.2  420.99  5393.5  419.73  5428.6  419.49
  5435.2  420.59  5463.7  421.47  5592.2   423.8  5605.5  424.77  5691.3  425.36
  5748.4  426.42    5755  427.35  5840.8  427.68  5925.3  430.19  5978.7  430.63
#Mann= 5 ,-1 , 0
    4692     .05       0    5013     .04       0    5017     .05       0
  5171.5      .1       0  5252.8     .05       0
Bank Sta=5013,5017
XS Rating Curve= 0 ,0
Exp/Cntr=0.3,0.1

Type RM Length L Ch R = 1 ,10043   ,227,227,227
BEGIN DESCRIPTION:
Lacy 139 1066
END DESCRIPTION:
XS GIS Cut Line= 3
      2724353.74      6857034.11      2724169.72      6857463.65
      2723925.96      6857904.79
#Sta/Elev= 30
  4539.8  430.33  4579.9  427.26  4602.3   426.9  4725.7  421.64  4772.8  417.43
  4808.4  416.25  4825.4  417.52    4878  417.15  4895.4  416.27  4901.6  415.14
    4907   415.4  4925.1  412.79  4960.7  412.23  4969.6  411.29  4969.8  410.79
  4973.6  411.29  4977.7  411.96  5005.5  412.23  5038.3  413.71  5088.5  413.52
    5114  412.12  5126.3  411.76    5148  413.15  5198.3  414.47  5221.1  413.79
    5244  414.97  5290.7  415.45  5338.2  416.14  5457.3  419.98  5511.1  420.55
#Mann= 5 ,-1 , 0
  4539.8     .05       0  4969.6     .04       0  4973.6     .05       0
    5114     .12       0  5290.7     .05       0
Bank Sta=4969.6,4973.6
XS Rating Curve= 0 ,0
Exp/Cntr=0.3,0.1

Type RM Length L Ch R = 1 ,9816    ,380,380,380
BEGIN DESCRIPTION:
Lacy 139 1067
END DESCRIPTION:
XS GIS Cut Line= 3
      2724339.95      6857019.92      2723985.15      6857426.12
        2723867.      6857876.13
#Sta/Elev= 30
    4465  430.11  4490.1  429.43  4588.8  424.03  4631.5  422.54  4652.4  419.41
  4709.3  416.54  4716.9  416.96  4723.6  415.47  4731.2  416.29  4737.8  414.95
  4752.1  415.75  4758.7  415.26  4801.4  416.18    4809  415.21  4815.7  415.71
  4823.3  414.09  4837.5  413.58  4936.2   412.6  4983.6  410.49  4983.8  409.99
  4987.6  410.49  4993.2  411.71  5030.1  410.85  5040.4  411.35  5092.1  410.92
  5103.5  412.03  5133.4  412.89  5205.8  413.03    5411  418.74  5469.6  418.73
#Mann= 3 ,-1 , 0
    4465     .05       0  4983.6     .04       0  4987.6     .05       0
Bank Sta=4983.6,4987.6
XS Rating Curve= 0 ,0
Exp/Cntr=0.3,0.1

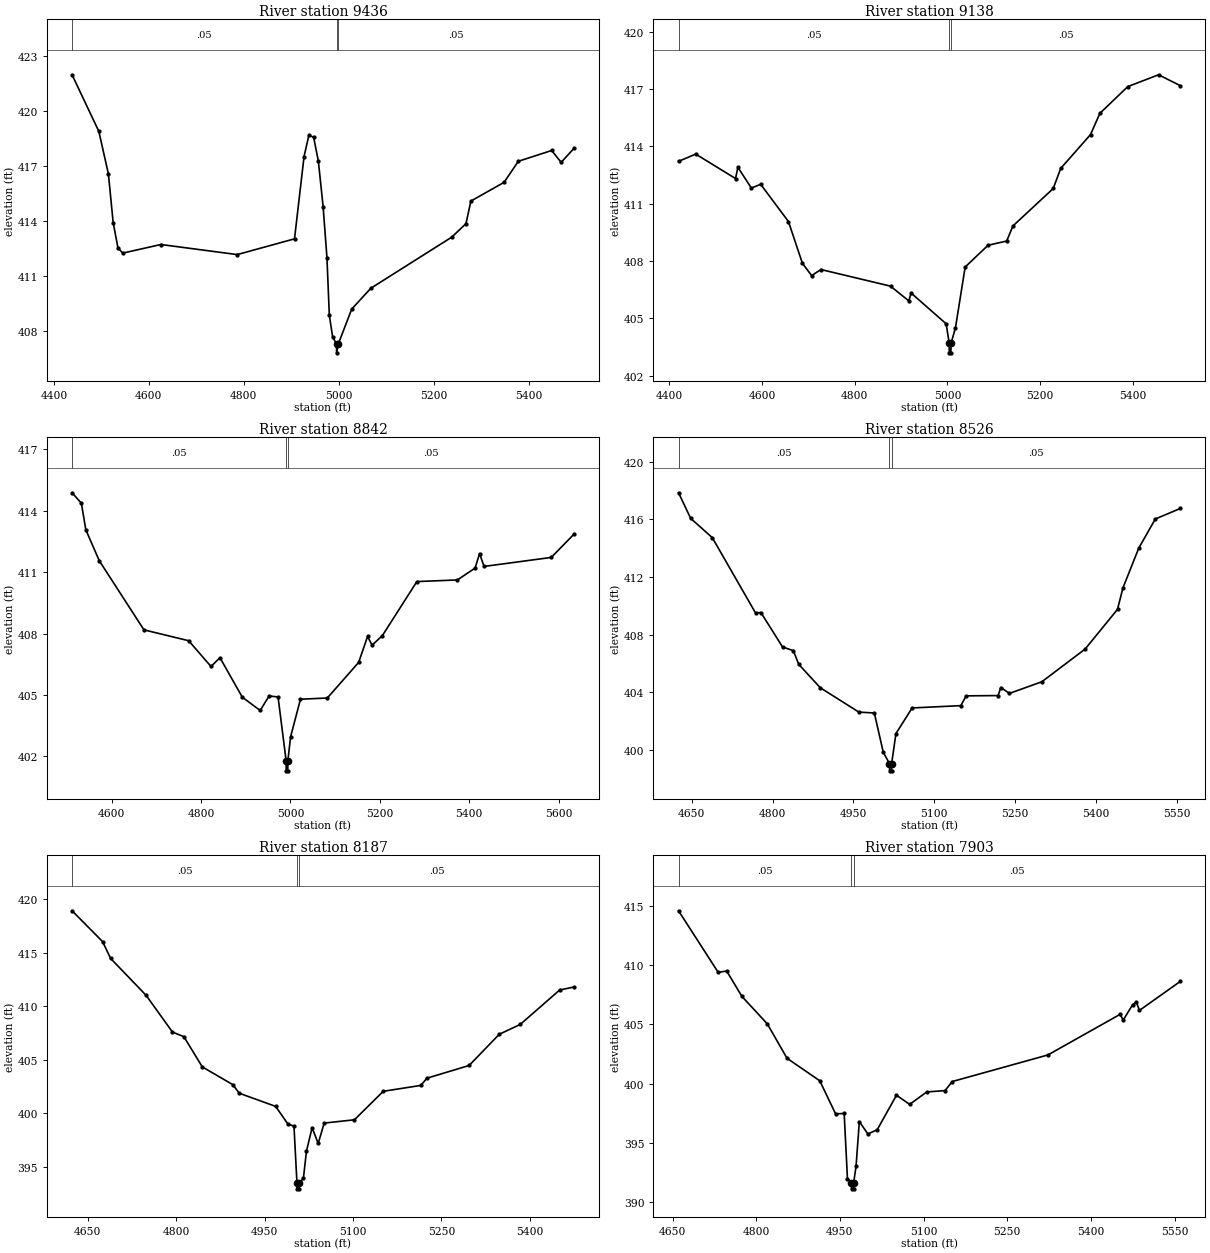
Type RM Length L Ch R = 1 ,9436    ,298,298,298
BEGIN DESCRIPTION:
Lacy 139 965
END DESCRIPTION:
XS GIS Cut Line= 3
      2723772.73      6856594.89      2723718.49      6857158.16
      2723686.59      6857647.65
#Sta/Elev= 30
  4438.4  421.97  4494.8  418.88  4514.9  416.56  4524.9  413.91    4535  412.53
    4545  412.24  4625.4  412.71  4786.1  412.16  4906.7  413.02  4926.8  417.51
  4936.8  418.66  4946.9  418.57  4956.9  417.26  4966.9  414.78    4975  411.99
    4980  408.85    4987  407.66  4995.1   407.3  4995.3   406.8  4999.1   407.3
  5027.2  409.19  5067.2  410.32  5237.6  413.11  5267.7  413.85    5278  415.08
  5347.8   416.1  5377.9  417.25  5448.1  417.84  5468.1  417.19  5494.8  417.95
#Mann= 3 ,-1 , 0
  4438.4     .05       0  4995.1     .04       0  4999.1     .05       0
Bank Sta=4995.1,4999.1
XS Rating Curve= 0 ,0
Exp/Cntr=0.3,0.1

Type RM Length L Ch R = 1 ,9138    ,296,296,296
BEGIN DESCRIPTION:
Lacy 139 963
END DESCRIPTION:
XS GIS Cut Line= 3
      2723507.71      6856373.97      2723523.35      6856963.11
      2723476.67      6857453.85
#Sta/Elev= 30
    4420  413.22    4457   413.6    4543  412.32    4548  412.91  4577.1  411.82
  4597.1  412.02  4657.1  410.07  4687.1  407.89  4707.1  407.24  4727.1  407.56
  4877.2  406.69  4916.6  405.92  4921.6  406.33  4997.2  404.72  5003.8   403.7
    5004   403.2  5007.5   403.2  5007.8   403.7  5017.3  404.51  5038.2  407.69
  5087.6  408.83  5127.8  409.05  5141.3  409.84  5228.2   411.8  5244.3  412.85
  5308.6  414.62  5328.7  415.73  5388.9  417.13  5455.4  417.75  5502.3  417.18
#Mann= 3 ,-1 , 0
    4420     .05       0  5003.8     .04       0  5007.8     .05       0
Bank Sta=5003.8,5007.8
XS Rating Curve= 0 ,0
Exp/Cntr=0.3,0.1

Type RM Length L Ch R = 1 ,8842    ,316,316,316
BEGIN DESCRIPTION:
Lacy 139 964
END DESCRIPTION:
XS GIS Cut Line= 3
      2723282.84      6856320.18      2723283.12      6856812.05
      2723244.97      6857441.52
#Sta/Elev= 30
  4511.5  414.88  4532.3  414.37  4542.3  413.07  4572.3  411.56  4672.3  408.18
  4772.3  407.65  4822.3  406.39  4842.3  406.82  4892.3  404.89  4932.3  404.24
  4952.3  404.95  4972.3   404.9  4990.3  401.79  4990.6  401.29  4994.1  401.29
  4994.3  401.79  5000.3  402.95  5022.4  404.79  5082.5  404.85  5152.6  406.59
  5172.6  407.86  5182.6  407.43  5205.7   407.9  5282.8  410.54  5373.5  410.62
  5413.1   411.2  5423.1  411.91  5433.1  411.28  5583.4  411.72    5634  412.85
#Mann= 3 ,-1 , 0
  4511.5     .05       0  4990.3     .04       0  4994.3     .05       0
Bank Sta=4990.3,4994.3
XS Rating Curve= 0 ,0
Exp/Cntr=0.3,0.1

Type RM Length L Ch R = 1 ,8526    ,339,339,339
BEGIN DESCRIPTION:
Lacy 139 962
END DESCRIPTION:
XS GIS Cut Line= 3
      2723023.98      6856338.45      2722997.51      6856718.81
      2722955.44      6857267.22
#Sta/Elev= 30
  4625.5  417.85  4648.1  416.07  4688.2  414.73  4768.4   409.5  4778.4  409.53
  4818.5  407.14  4838.6  406.88  4848.6  405.93  4888.7   404.3  4960.2  402.61
  4988.9  402.55  5005.4  399.83    5017  399.03  5017.3  398.53  5020.8  398.53
    5021  399.03    5029  401.12  5059.1   402.9  5149.4  403.06  5159.4  403.74
  5218.6  403.76  5223.6  404.32  5239.7  403.91  5299.8  404.72  5380.1  406.99
  5440.2  409.75  5450.3  411.24  5479.7  414.01  5510.4  416.03  5556.8  416.76
#Mann= 3 ,-1 , 0
  4625.5     .05       0    5017     .05       0    5021     .05       0
Bank Sta=5017,5021
XS Rating Curve= 0 ,0
Exp/Cntr=0.3,0.1

Type RM Length L Ch R = 1 ,8187    ,284,284,284
BEGIN DESCRIPTION:
Lacy 139 961
END DESCRIPTION:
XS GIS Cut Line= 3
      2722775.31      6856298.01      2722672.68      6856669.68
      2722571.06      6857124.48
#Sta/Elev= 30
  4623.3  418.91  4675.1  416.03  4688.7  414.46    4749  411.01  4793.7  407.58
  4813.1  407.15  4844.3  404.33  4896.1  402.67  4907.1  401.87  4968.8  400.64
  4989.5     399  4999.9  398.79    5005  393.44  5005.2  392.94  5008.7  392.94
    5009  393.44    5016  393.97  5021.1  396.47  5030.7  398.65    5041  397.18
  5051.2  399.08  5102.5  399.39  5151.4  402.05  5215.2   402.6  5225.4  403.27
  5297.1  404.46  5348.4  407.38  5383.8  408.29  5450.8  411.51  5474.9  411.79
#Mann= 3 ,-1 , 0
  4623.3     .05       0    5005     .04       0    5009     .05       0
Bank Sta=5005,5009
XS Rating Curve= 0 ,0
Exp/Cntr=0.3,0.1

Type RM Length L Ch R = 1 ,7903    ,340,340,340
BEGIN DESCRIPTION:
Lacy 139 960
END DESCRIPTION:
XS GIS Cut Line= 3
      2722618.19      6856235.46      2722435.07      6856532.53
      2722220.83      6857039.66
#Sta/Elev= 30
  4660.8  414.59  4731.8   409.4  4747.2   409.5  4774.3  407.37    4820  405.04
  4855.3  402.14    4914  400.24  4942.3  397.45  4957.7  397.48  4963.6  391.99
  4970.7  391.62    4971  391.12  4974.5  391.12  4974.7  391.62    4979  393.02
  4984.9  396.79  5000.3  395.75  5016.9  396.11  5051.5  399.02  5075.1  398.25
  5105.8   399.3  5138.4  399.41  5151.7  400.18  5322.9  402.42  5452.4  405.85
  5457.9  405.36  5474.9  406.67  5481.6  406.88    5487  406.18  5560.3  408.63
#Mann= 3 ,-1 , 0
  4660.8     .05       0  4970.7     .04       0  4974.7     .05       0
Bank Sta=4970.7,4974.7
XS Rating Curve= 0 ,0
Exp/Cntr=0.3,0.1

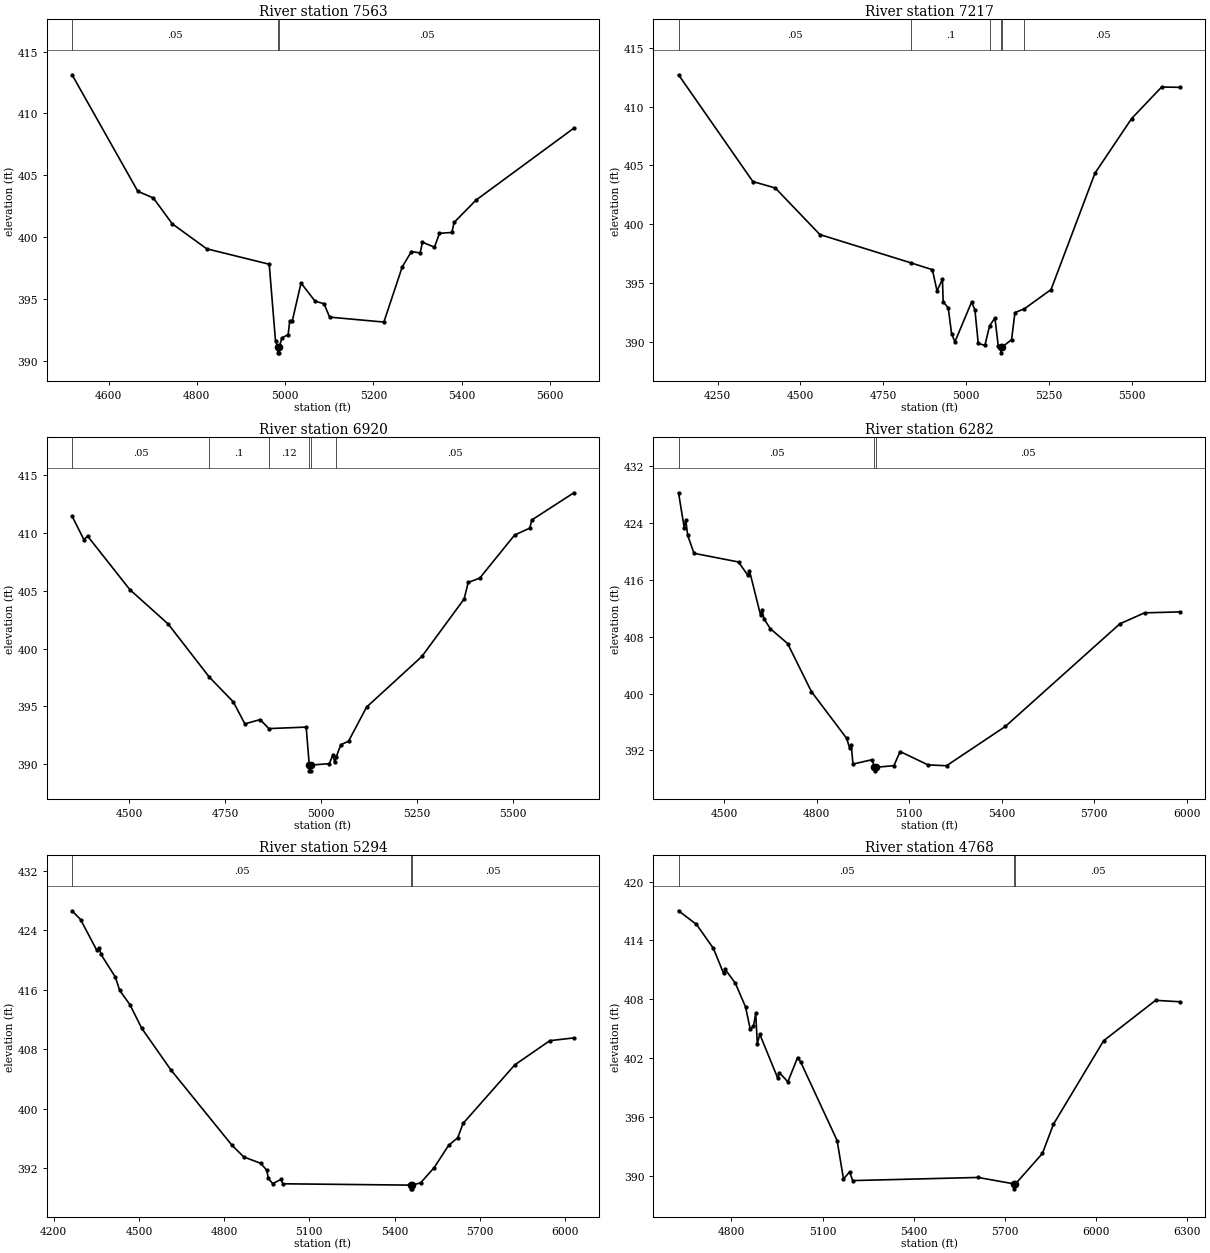
Type RM Length L Ch R = 1 ,7563    ,346,346,346
BEGIN DESCRIPTION:
Lacy 139 959
END DESCRIPTION:
XS GIS Cut Line= 3
      2722512.75      6856097.96      2722135.25      6856418.19
      2721953.55      6857033.91
#Sta/Elev= 30
  4517.4  413.13  4666.4   403.7  4701.6  403.16  4744.4  401.07  4822.4  399.05
  4964.1   397.8  4978.4  391.57  4983.2  391.13  4983.5  390.63    4987  390.63
  4987.2  391.13  4992.7  391.84    5007   392.1  5010.7  393.23  5016.5  393.23
  5036.2  396.28  5067.7  394.82  5088.3   394.6    5101  393.52  5223.9  393.12
  5265.6  397.59  5286.4  398.83  5306.1  398.71  5311.3  399.58  5338.6  399.18
  5349.8   400.3  5377.9  400.37  5383.1  401.18  5432.4  402.98  5654.4  408.81
#Mann= 3 ,-1 , 0
  4517.4     .05       0  4983.2     .04       0  4987.2     .05       0
Bank Sta=4983.2,4987.2
XS Rating Curve= 0 ,0
Exp/Cntr=0.3,0.1

Type RM Length L Ch R = 1 ,7217    ,297,297,297
BEGIN DESCRIPTION:
Lacy 139 958
END DESCRIPTION:
XS GIS Cut Line= 3
      2722564.67      6855896.21      2721856.86      6856266.25
      2721778.75      6856976.97
#Sta/Elev= 30
  4132.4  412.71  4356.6  403.63  4424.3  403.08  4558.8  399.12  4833.8  396.71
  4898.2  396.13  4912.1  394.33  4928.5  395.31  4930.8  393.38  4945.9   392.9
    4956   390.7  4966.1  389.99  5016.4  393.38  5026.4  392.73  5036.5  389.87
  5056.6  389.69  5070.7  391.36  5086.8  392.02  5096.8  389.67  5104.9  389.56
  5105.2  389.06  5108.9  389.56  5137.1  390.18  5147.1  392.48  5175.9  392.81
  5256.1  394.44  5388.6  404.34  5499.3  408.99  5589.8  411.67  5646.1  411.64
#Mann= 6 ,-1 , 0
  4132.4     .05       0  4833.8      .1       0  5070.7     .12       0
  5104.9     .07       0  5108.9     .12       0  5175.9     .05       0
Bank Sta=5104.9,5108.9
XS Rating Curve= 0 ,0
Exp/Cntr=0.3,0.1

Type RM Length L Ch R = 1 ,6920    ,638,638,638
BEGIN DESCRIPTION:
Lacy 139 954
END DESCRIPTION:
XS GIS Cut Line= 3
      2721605.98      6855710.28      2721607.82      6856367.82
      2721683.89      6857014.72
#Sta/Elev= 30
  4350.7  411.48  4381.4  409.45  4391.4  409.74  4501.4  405.11  4601.4  402.13
    4709  397.52  4771.4  395.38  4801.4  393.48  4841.4  393.85  4863.9  393.07
  4961.4   393.2  4969.4  389.91  4969.7  389.41  4973.2  389.41  4973.4  389.91
  5021.5  390.03    5031  390.78    5036  390.14  5040.2  390.65  5051.7  391.67
  5071.9  391.98  5119.1  394.94  5263.2  399.32  5373.4   404.3    5384  405.73
  5414.2  406.11  5504.8  409.83  5544.7  410.44  5549.7  411.14  5659.6   413.5
#Mann= 6 ,-1 , 0
  4350.7     .05       0    4709      .1       0  4863.9     .12       0
  4969.4     .07       0  4973.4     .12       0  5040.2     .05       0
Bank Sta=4969.4,4973.4
XS Rating Curve= 0 ,0
Exp/Cntr=0.3,0.1

Type RM Length L Ch R = 1 ,6282    ,988,988,988
BEGIN DESCRIPTION:
Lacy 139 3449
END DESCRIPTION:
XS GIS Cut Line= 3
      2721306.46      6855582.25      2721147.34      6856220.03
      2721224.72      6857186.71
#Sta/Elev= 30
  4352.3  428.29  4370.7  423.38  4375.8  424.46  4381.9   422.3  4402.5  419.76
  4546.8  418.54    4577  416.66  4582.2  417.33  4618.3  411.05  4623.4  411.83
  4629.3  410.53  4649.9  409.14    4706  407.05  4783.4  400.26  4897.3   393.7
  4907.2   392.3  4912.3  392.82  4917.9  390.06  4979.7  390.68  4987.7  389.61
  4987.9  389.11  4991.7  389.61  5050.6  389.84  5070.8  391.83  5161.1  389.95
  5221.3  389.83  5411.9  395.36  5783.1  409.82  5863.3  411.37  5979.4  411.51
#Mann= 3 ,-1 , 0
  4352.3     .05       0  4987.7     .03       0  4991.7     .05       0
Bank Sta=4987.7,4991.7
XS Rating Curve= 0 ,0
Exp/Cntr=0.3,0.1

Type RM Length L Ch R = 1 ,5294    ,526,526,526
BEGIN DESCRIPTION:
Lacy 139 3448
END DESCRIPTION:
XS GIS Cut Line= 3
      2720958.19       6855521.8       2720466.9       6856243.5
      2720604.48       6857126.6
#Sta/Elev= 30
  4264.7  426.61  4294.6  425.43  4351.5  421.31  4360.4  421.67  4366.4  420.75
  4417.3  417.68  4432.2  415.91  4468.1     414  4510.1   410.8  4611.8  405.25
  4827.3  395.09  4869.3   393.5    4929  392.64    4950  391.72    4956  390.61
    4971  389.91  5000.8  390.48  5006.9  389.89  5457.1  389.71  5457.3  389.21
  5460.8  389.21  5461.1  389.71  5491.8  390.01    5540  392.08  5590.6  395.07
  5622.6  396.08  5641.3     398  5823.4  405.88  5946.9  409.14  6031.5  409.51
#Mann= 3 ,-1 , 0
  4264.7     .05       0  5457.1     .03       0  5461.1     .05       0
Bank Sta=5457.1,5461.1
XS Rating Curve= 0 ,0
Exp/Cntr=0.3,0.1

Type RM Length L Ch R = 1 ,4768    ,98,98,98
BEGIN DESCRIPTION:
Lacy 139 951
END DESCRIPTION:
XS GIS Cut Line= 3
      2720272.69       6855404.4       2720168.2      6855762.91
      2720024.02      6857031.82
#Sta/Elev= 30
    4626  417.02    4685  415.63  4740.7  413.19  4774.2  410.64  4779.5  411.05
  4812.9  409.64  4846.4  407.23    4862  404.93  4872.4  405.26  4879.9  406.56
  4885.1  403.46  4893.3  404.44  4952.1  399.99  4957.3  400.54  4985.6   399.6
  5017.6  402.07  5027.7  401.62  5147.6  393.62  5168.6   389.7  5188.7  390.43
  5198.8  389.54  5611.4  389.86  5730.2   389.2  5730.5   388.7  5734.2   389.2
  5822.8   392.3  5859.2  395.28  6024.1  403.78  6195.2   407.9  6276.5  407.75
#Mann= 3 ,-1 , 0
    4626     .05       0  5730.2     .04       0  5734.2     .05       0
Bank Sta=5730.2,5734.2
XS Rating Curve= 0 ,0
Exp/Cntr=0.3,0.1