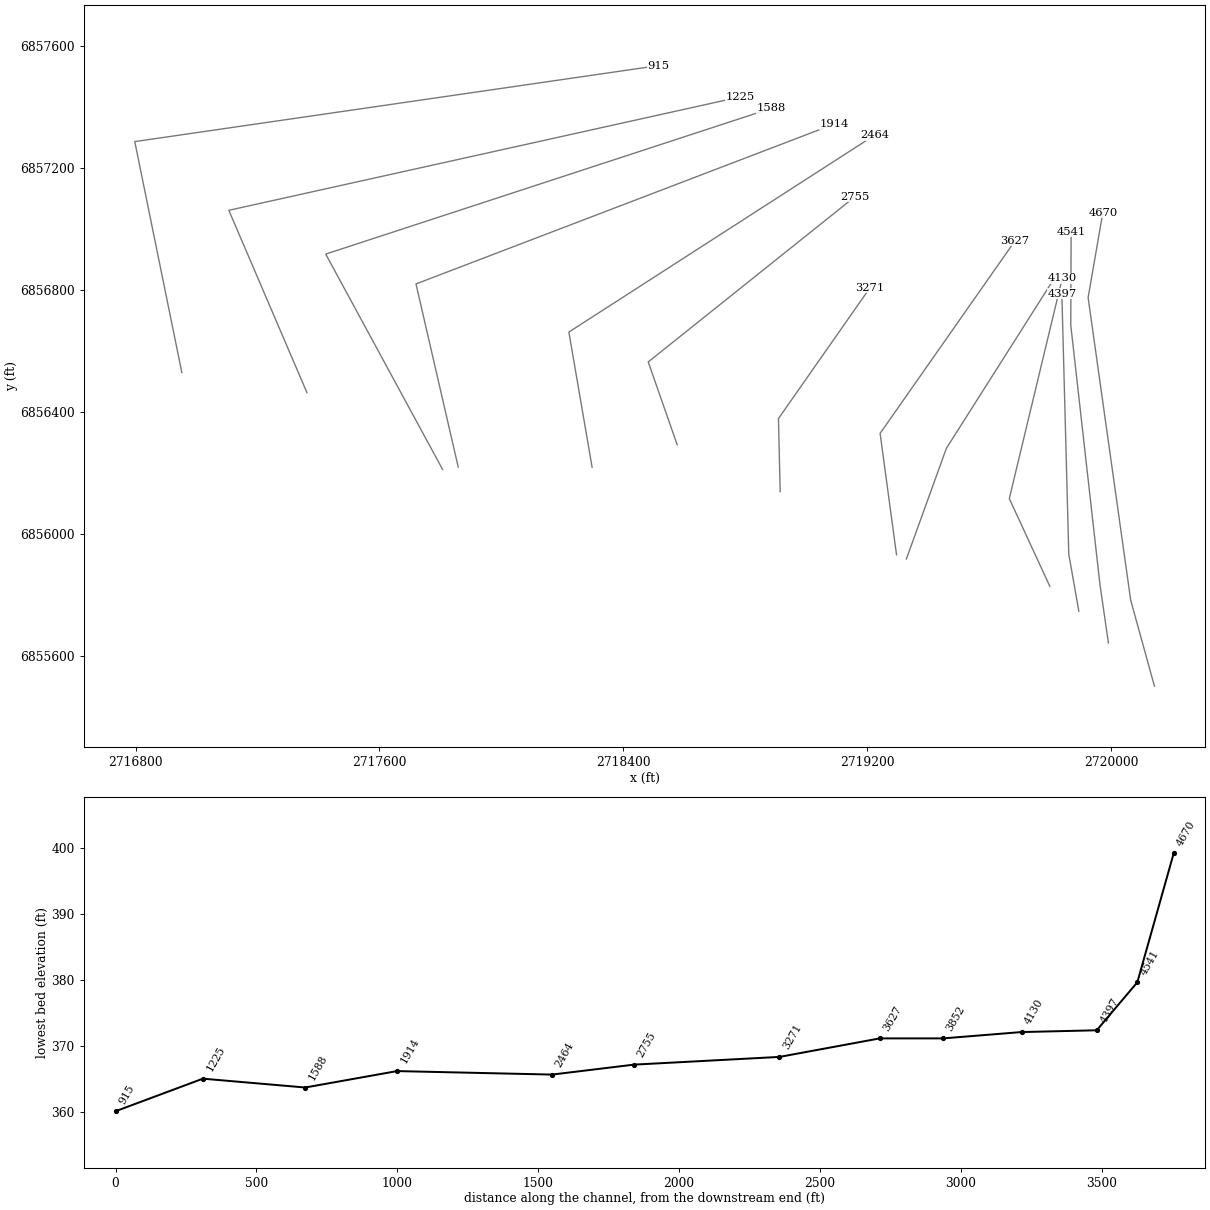
HEC-RAS study Lacy 139.prj: Lacy 139 Base Level Engineering

--- Lacy 139.g01 (geometry) --- (continued)

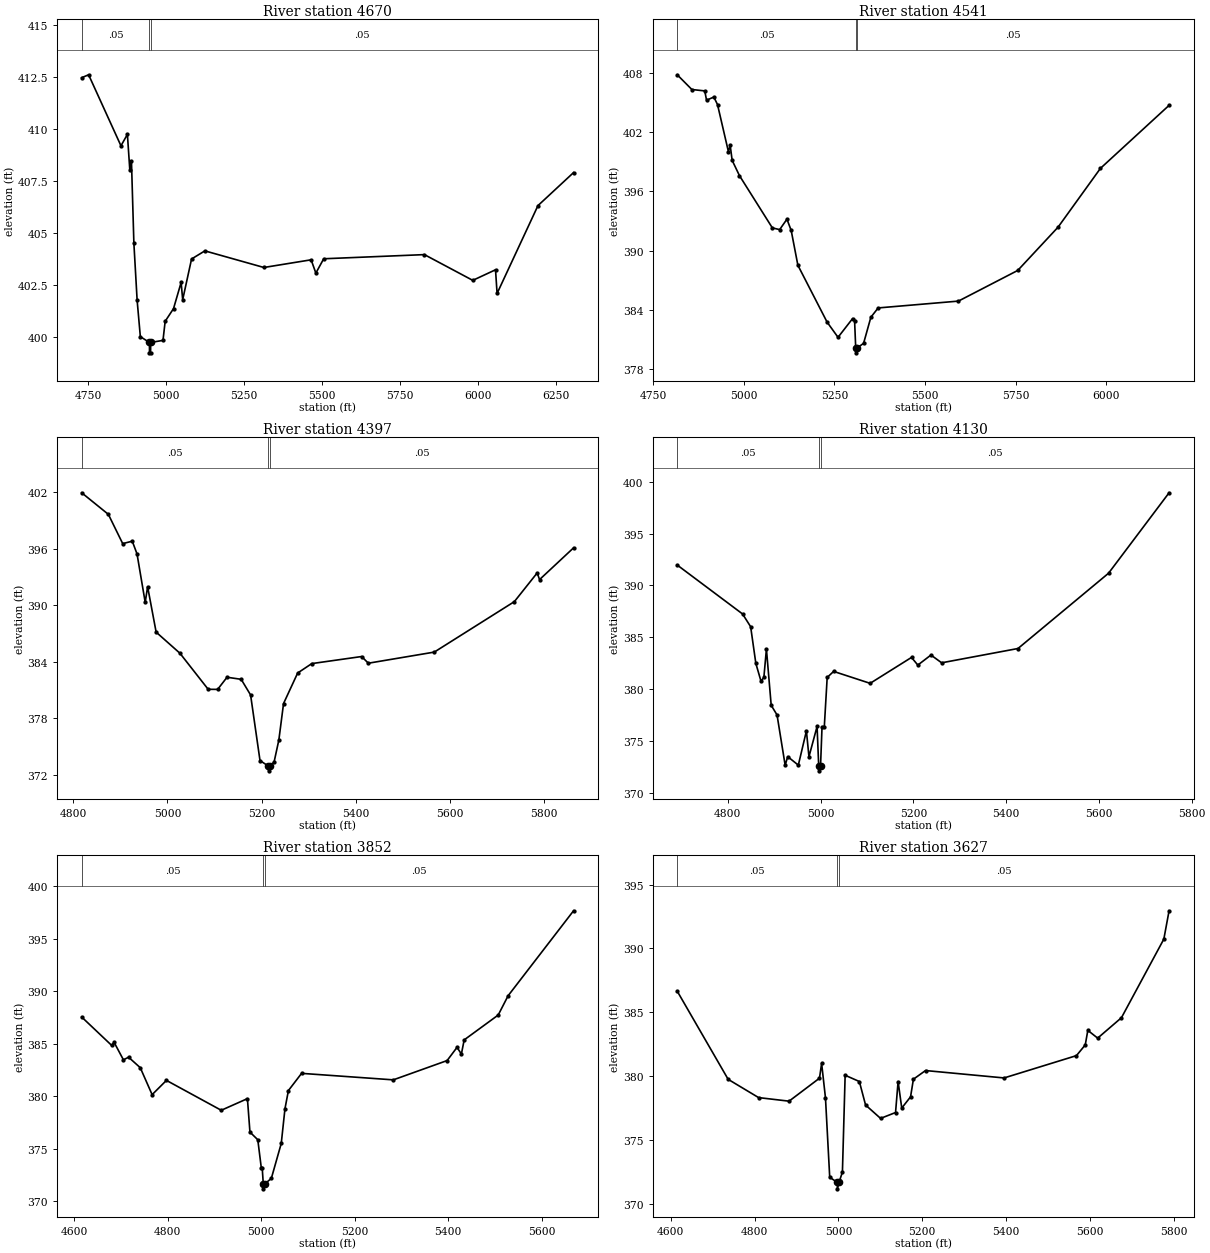
Type RM Length L Ch R = 1 ,4670    ,129,129,129
BEGIN DESCRIPTION:
Lacy 139 950
END DESCRIPTION:
XS GIS Cut Line= 4
      2720142.82      6855499.57      2720064.99      6855781.29
      2719925.24      6856774.36      2719973.57      6857053.58
#Sta/Elev= 30
  4728.9  412.47  4751.1  412.61  4854.9  409.19  4875.6  409.74  4883.4  408.01
  4888.6  408.46  4896.4  404.49  4906.8  401.75  4917.1     400  4946.3  399.72
  4946.5  399.22    4950  399.22  4950.3  399.72  4989.8  399.82  4996.8  400.74
  5023.6  401.35    5048  402.61    5053  401.78  5081.5  403.74  5124.2  404.13
  5313.7  403.33  5465.2   403.7  5480.4  403.06  5505.6  403.75  5828.8  403.95
    5984  402.71    6057  403.22    6062  402.08  6193.2  406.31  6307.4   407.9
#Mann= 3 ,-1 , 0
  4728.9     .05       0  4946.3     .04       0  4950.3     .05       0
Bank Sta=4946.3,4950.3
XS Rating Curve= 0 ,0
Exp/Cntr=0.3,0.1

Type RM Length L Ch R = 1 ,4541    ,144,144,144
BEGIN DESCRIPTION:
Lacy 139 948
END DESCRIPTION:
XS GIS Cut Line= 4
      2719991.89      6855641.06      2719963.91      6855834.37
      2719868.29      6856684.19      2719869.48      6856990.28
#Sta/Elev= 30
  4816.4  407.78  4856.8  406.29  4892.3  406.15  4897.3  405.21  4917.4  405.53
  4927.5  404.77  4957.5  400.02  4962.5  400.64  4967.9  399.13  4988.1  397.58
  5078.8   392.3  5098.9  392.13    5119  393.18  5130.7  392.05  5149.2  388.52
  5229.7  382.78  5259.9  381.24  5300.2  383.14  5305.6  382.91  5308.7  380.17
  5308.9  379.67  5312.7  380.17  5330.4  380.63  5350.5  383.27  5370.6  384.21
    5592   384.9  5755.6     388  5866.9  392.38  5983.7  398.32    6173  404.69
#Mann= 3 ,-1 , 0
  4816.4     .05       0  5308.7     .04       0  5312.7     .05       0
Bank Sta=5308.7,5312.7
XS Rating Curve= 0 ,0
Exp/Cntr=0.3,0.1

Type RM Length L Ch R = 1 ,4397    ,267,267,267
BEGIN DESCRIPTION:
Lacy 139 949
END DESCRIPTION:
XS GIS Cut Line= 3
       2719894.8      6855745.27      2719861.79      6855932.44
      2719839.04      6856786.68
#Sta/Elev= 30
  4817.8  401.92  4874.4  399.63  4904.9  396.52  4925.2  396.78  4935.3  395.43
  4952.7  390.28  4957.8  391.95  4975.9  387.12  5026.4  384.88  5086.4  381.05
  5106.5  381.04  5126.5  382.33  5156.5  382.11  5176.5  380.45  5196.5  373.48
  5214.5  372.89  5214.7  372.39  5218.5  372.89  5226.5  373.35  5236.5  375.66
  5246.5  379.54  5276.5  382.78  5306.5  383.78  5412.3  384.53  5426.6  383.82
  5566.6     385  5736.7  390.36  5785.2  393.41  5790.2   392.7  5862.4  396.07
#Mann= 3 ,-1 , 0
  4817.8     .05       0  5214.5     .04       0  5218.5     .05       0
Bank Sta=5214.5,5218.5
XS Rating Curve= 0 ,0
Exp/Cntr=0.3,0.1

Type RM Length L Ch R = 1 ,4130    ,278,278,278
BEGIN DESCRIPTION:
Lacy 139 947
END DESCRIPTION:
XS GIS Cut Line= 3
      2719799.62      6855827.09      2719666.67      6856114.95
      2719840.34      6856837.69
#Sta/Elev= 30
  4690.9  391.97  4831.8  387.25  4849.2  386.02  4860.4  382.48  4871.5  380.77
  4877.7  381.13  4883.2  383.87  4893.5  378.44  4906.1  377.51  4923.6  372.66
  4929.1  373.49    4952  372.67  4969.4  375.97  4974.9  373.48  4992.4   376.4
  4995.9  372.62  4996.1  372.12  4999.9  372.62  5003.1  376.37    5008  376.37
  5014.2  381.13  5028.1  381.71  5106.8  380.56    5196  383.06  5209.6  382.32
  5237.9  383.29    5261  382.54  5425.6  383.92  5620.8  391.18  5751.3  398.94
#Mann= 3 ,-1 , 0
  4690.9     .05       0  4995.9     .04       0  4999.9     .05       0
Bank Sta=4995.9,4999.9
XS Rating Curve= 0 ,0
Exp/Cntr=0.3,0.1

Type RM Length L Ch R = 1 ,3852    ,225,225,225
BEGIN DESCRIPTION:
Lacy 139 946
END DESCRIPTION:
XS GIS Cut Line= 3
      2719328.95      6855916.65      2719460.21      6856279.87
      2719817.21      6856842.34
#Sta/Elev= 30
  4615.9  387.54  4679.9  384.84  4685.2  385.13  4705.2  383.46  4716.2  383.71
  4741.2  382.71  4766.6  380.14  4797.2   381.5  4914.5  378.65  4970.5  379.76
  4975.9  376.57  4992.7  375.84  5000.1  373.19  5002.1  373.19  5004.4  371.66
  5004.7  371.16  5008.5  371.66  5021.7  372.16  5042.9  375.49  5050.8  378.79
  5058.2  380.53  5086.4  382.17  5282.6  381.55  5397.8  383.39    5419  384.65
  5428.3  384.01  5434.3  385.36  5507.1  387.73  5528.3  389.57  5668.3  397.67
#Mann= 3 ,-1 , 0
  4615.9     .05       0  5004.4     .04       0  5008.5     .05       0
Bank Sta=5004.4,5008.5
XS Rating Curve= 0 ,0
Exp/Cntr=0.3,0.1

Type RM Length L Ch R = 1 ,3627    ,356,356,356
BEGIN DESCRIPTION:
Lacy 139 979
END DESCRIPTION:
XS GIS Cut Line= 3
      2719296.62      6855930.58      2719242.72      6856328.84
      2719685.23      6856960.46
#Sta/Elev= 30
  4615.6  386.65  4737.1  379.74  4809.7  378.31  4882.3  378.03  4954.9  379.83
    4960  380.99  4969.2  378.28  4979.3  372.07  4997.4  371.66  4997.7  371.16
  5001.5  371.66  5009.6  372.48  5016.1  380.06    5050  379.57  5064.8  377.73
  5100.6  376.68  5136.3  377.14  5142.4  379.57  5151.1  377.49  5172.1  378.37
  5178.9  379.75  5207.8  380.43  5395.2  379.85  5567.8   381.6  5588.8  382.44
  5594.9  383.58  5618.4  382.97  5675.1  384.57  5776.2  390.73  5788.7  392.95
#Mann= 3 ,-1 , 0
  4615.6     .05       0  4997.4     .05       0  5001.5     .05       0
Bank Sta=4997.4,5001.5
XS Rating Curve= 0 ,0
Exp/Cntr=0.3,0.1

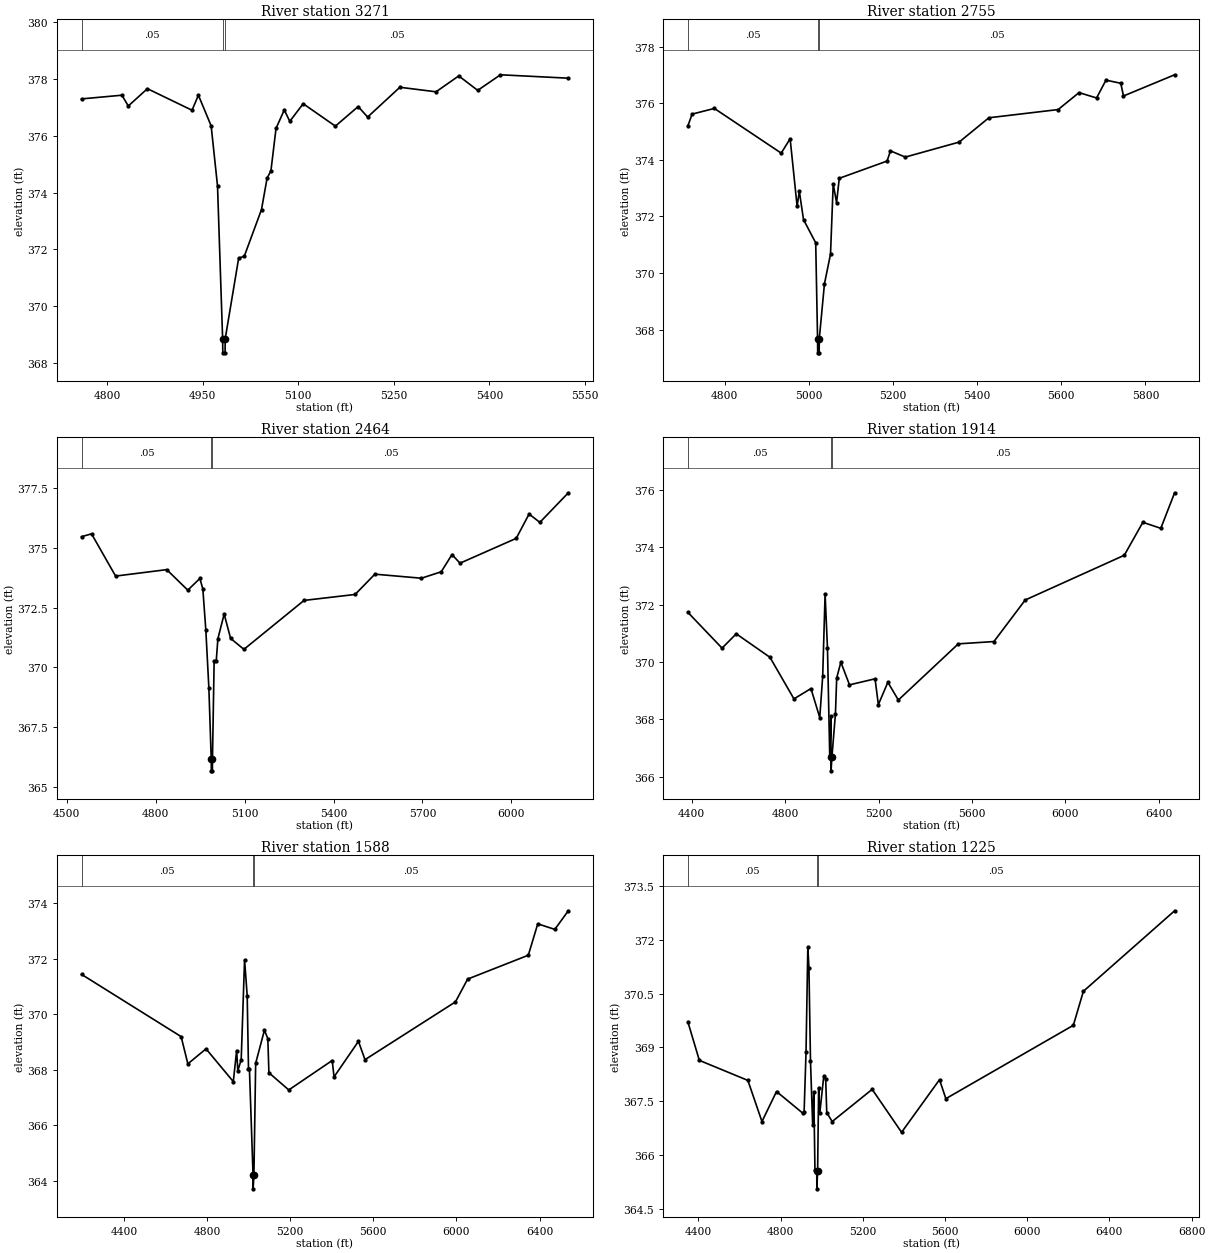
Type RM Length L Ch R = 1 ,3271    ,516,516,516
BEGIN DESCRIPTION:
Lacy 139 977
END DESCRIPTION:
XS GIS Cut Line= 3
      2718914.86      6856137.75      2718909.26      6856377.49
      2719209.61      6856806.74
#Sta/Elev= 30
  4760.2   377.3  4823.5  377.43  4833.5  377.05  4863.5  377.66  4933.5   376.9
  4943.5  377.43  4963.5  376.35  4973.5  374.23  4981.5  368.85  4981.8  368.35
  4985.3  368.35  4985.6  368.85  5006.7  371.69  5015.4  371.75  5042.5   373.4
  5051.2   374.5  5057.3  374.77  5065.3  376.26  5078.2  376.91  5086.9  376.51
  5107.9  377.13  5158.4  376.34  5194.2  377.03    5209  376.66  5259.6  377.71
  5316.3  377.55    5352  378.11  5381.7   377.6  5417.4  378.15  5523.9  378.03
#Mann= 3 ,-1 , 0
  4760.2     .05       0  4981.5     .04       0  4985.6     .05       0
Bank Sta=4981.5,4985.6
XS Rating Curve= 0 ,0
Exp/Cntr=0.3,0.1

Type RM Length L Ch R = 1 ,2755    ,291,291,291
BEGIN DESCRIPTION:
Lacy 139 975
END DESCRIPTION:
XS GIS Cut Line= 3
      2718577.02      6856291.41      2718481.94      6856563.26
      2719160.88      6857105.98
#Sta/Elev= 30
    4712   375.2  4722.2  375.62  4775.1  375.82    4934  374.24  4955.2  374.75
  4971.8  372.36  4977.1  372.89    4987  371.89    5016  371.07  5020.4  367.68
  5020.7  367.18  5024.2  367.18  5024.5  367.68  5036.8  369.62  5051.2  370.67
  5057.6  373.15  5065.6  372.49    5072  373.35  5185.7  373.96  5193.7  374.32
  5228.9   374.1    5357  374.63  5427.7  375.49  5592.3  375.78    5642  376.38
  5683.7  376.19    5706  376.82  5741.2  376.71  5747.7  376.26  5869.2  377.01
#Mann= 3 ,-1 , 0
    4712     .05       0  5020.4     .04       0  5024.5     .05       0
Bank Sta=5020.4,5024.5
XS Rating Curve= 0 ,0
Exp/Cntr=0.3,0.1

Type RM Length L Ch R = 1 ,2464    ,550,550,550
BEGIN DESCRIPTION:
Lacy 139 974
END DESCRIPTION:
XS GIS Cut Line= 3
      2718297.78      6856217.84      2718221.57      6856661.24
      2719223.82      6857306.68
#Sta/Elev= 30
  4550.1  375.48  4583.7   375.6  4664.9  373.83  4837.4   374.1  4908.4  373.24
  4949.2  373.73  4959.2  373.29  4969.3  371.56  4979.5  369.15  4987.5  366.17
  4987.9  365.67  4991.4  365.67  4991.7  366.17  4997.3  370.28  5004.4  370.28
    5010  371.21  5031.1  372.24  5052.8  371.22  5097.8  370.76  5300.5  372.81
  5472.8  373.06  5539.5  373.91  5696.6  373.74  5763.3  374.01  5799.6  374.73
  5826.7  374.37  6016.3  375.41  6059.7  376.43    6096  376.08  6192.1  377.32
#Mann= 3 ,-1 , 0
  4550.1     .05       0  4987.5     .04       0  4991.7     .05       0
Bank Sta=4987.5,4991.7
XS Rating Curve= 0 ,0
Exp/Cntr=0.3,0.1

Type RM Length L Ch R = 1 ,1914    ,326,326,326
BEGIN DESCRIPTION:
Lacy 139 972
END DESCRIPTION:
XS GIS Cut Line= 3
      2717858.59      6856218.17      2717719.97      6856819.19
      2719091.19      6857343.38
#Sta/Elev= 30
  4383.2  371.73  4529.8  370.48  4590.6  370.98    4735  370.16  4837.7  368.71
  4910.5  369.07  4948.2  368.06  4960.8   369.5  4971.1  372.37  4981.3  370.47
  4990.9  366.73  4996.1  368.11  4996.3   366.7  4996.6   366.2  5000.5   366.7
  5015.4  368.19  5020.8  369.44  5038.6  369.99  5075.6   369.2  5185.1  369.41
  5199.2  368.51  5239.9  369.29  5284.8  368.67  5541.7  370.63  5694.1  370.71
  5828.3  372.16  6252.5  373.72    6332  374.87  6408.9  374.66    6468   375.9
#Mann= 3 ,-1 , 0
  4383.2     .05       0  4996.3     .04       0  5000.5     .05       0
Bank Sta=4996.3,5000.5
XS Rating Curve= 0 ,0
Exp/Cntr=0.3,0.1

Type RM Length L Ch R = 1 ,1588    ,363,363,363
BEGIN DESCRIPTION:
Lacy 139 971
END DESCRIPTION:
XS GIS Cut Line= 3
      2717807.18      6856210.71       2717423.8      6856917.08
      2718885.77      6857395.33
#Sta/Elev= 30
  4196.3  371.43  4675.3  369.19  4707.7  368.21  4795.1  368.75  4926.3  367.57
  4942.4  368.69  4948.1  367.96  4964.3  368.36  4980.5  371.95  4993.1  370.67
  4999.4  368.04  5003.8  368.04  5021.3  364.21  5021.6  363.71  5025.5  364.21
  5033.9  368.23    5076  369.42  5092.4  369.12  5097.6  367.89  5193.2  367.27
  5402.1  368.33    5411  367.74  5528.4  369.02  5559.9  368.36  5995.1  370.44
  6053.6  371.26  6345.6  372.12  6391.1  373.25    6473  373.05  6538.2  373.72
#Mann= 3 ,-1 , 0
  4196.3     .05       0  5021.3     .04       0  5025.5     .05       0
Bank Sta=5021.3,5025.5
XS Rating Curve= 0 ,0
Exp/Cntr=0.3,0.1

Type RM Length L Ch R = 1 ,1225    ,310,310,310
BEGIN DESCRIPTION:
Lacy 139 970
END DESCRIPTION:
XS GIS Cut Line= 3
      2717362.18      6856462.54       2717105.9      6857060.76
      2718782.27      6857432.52
#Sta/Elev= 30
  4349.2  369.72  4405.2  368.64  4641.3  368.08  4709.8  366.93  4780.6  367.77
  4909.3  367.16  4914.8   367.2  4924.1  368.86  4932.9  371.81  4938.3  371.23
  4945.9  368.62  4956.5  366.83  4961.9  367.75  4967.6  365.57  4976.4  365.55
  4976.8  365.05  4980.6  365.55  4985.5  367.88  4990.9  367.16  5010.3  368.19
  5019.8  368.12    5025  367.18  5051.3  366.93  5245.9  367.83    5389  366.63
  5573.5   368.1  5604.4  367.57  6224.6  369.62  6273.3  370.57  6717.1  372.82
#Mann= 3 ,-1 , 0
  4349.2     .05       0  4976.4     .04       0  4980.6     .05       0
Bank Sta=4976.4,4980.6
XS Rating Curve= 0 ,0
Exp/Cntr=0.3,0.1

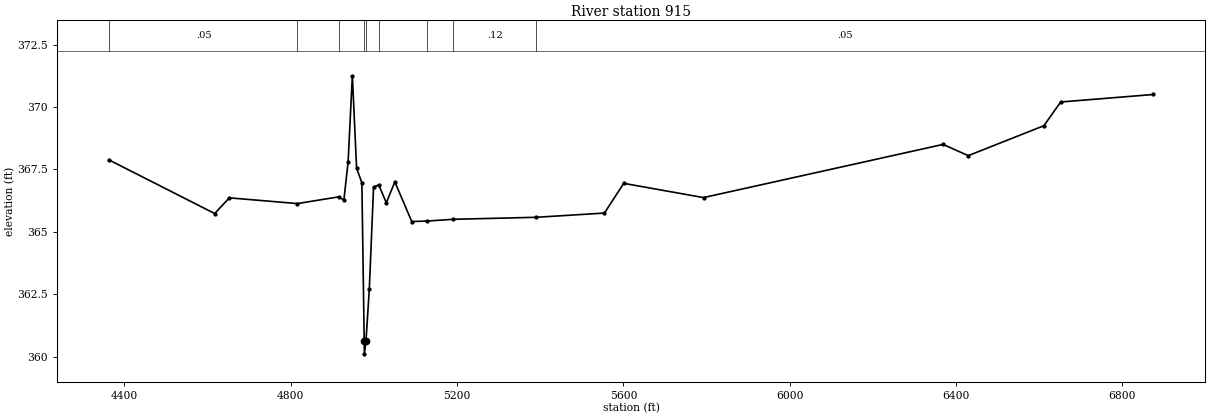
Type RM Length L Ch R = 1 ,915     ,0,0,0
BEGIN DESCRIPTION:
Lacy 139 3465
END DESCRIPTION:
XS GIS Cut Line= 3
       2716951.7      6856528.55       2716797.3      6857286.19
      2718516.17      6857535.65
#Sta/Elev= 30
    4364  367.87  4617.2  365.73  4652.3  366.36  4816.1  366.13  4915.6   366.4
  4927.8  366.27    4938   367.8  4948.2  371.25  4958.4  367.55  4971.1  366.96
  4976.7  360.61  4977.1  360.11  4980.9  360.61    4989  362.71  4999.2  366.79
  5011.6  366.88  5029.9  366.16  5050.3     367  5091.1  365.41  5127.7  365.43
  5190.6   365.5    5390  365.58  5554.4  365.75  5600.7  366.94  5792.7  366.37
  6368.7   368.5  6429.3  368.05  6611.2  369.25  6651.6   370.2  6874.1   370.5
#Mann= 9 ,-1 , 0
    4364     .05       0  4816.1     .12       0  4915.6      .1       0
  4976.7     .07       0  4980.9      .1       0  5011.6     .12       0
  5127.7      .1       0  5190.6     .12       0    5390     .05       0
Bank Sta=4976.7,4980.9
XS Rating Curve= 0 ,0
Exp/Cntr=0.3,0.1

Chan Stop Cuts=-1
Use User Specified Reach Order=0
Composite Channel Slope=5