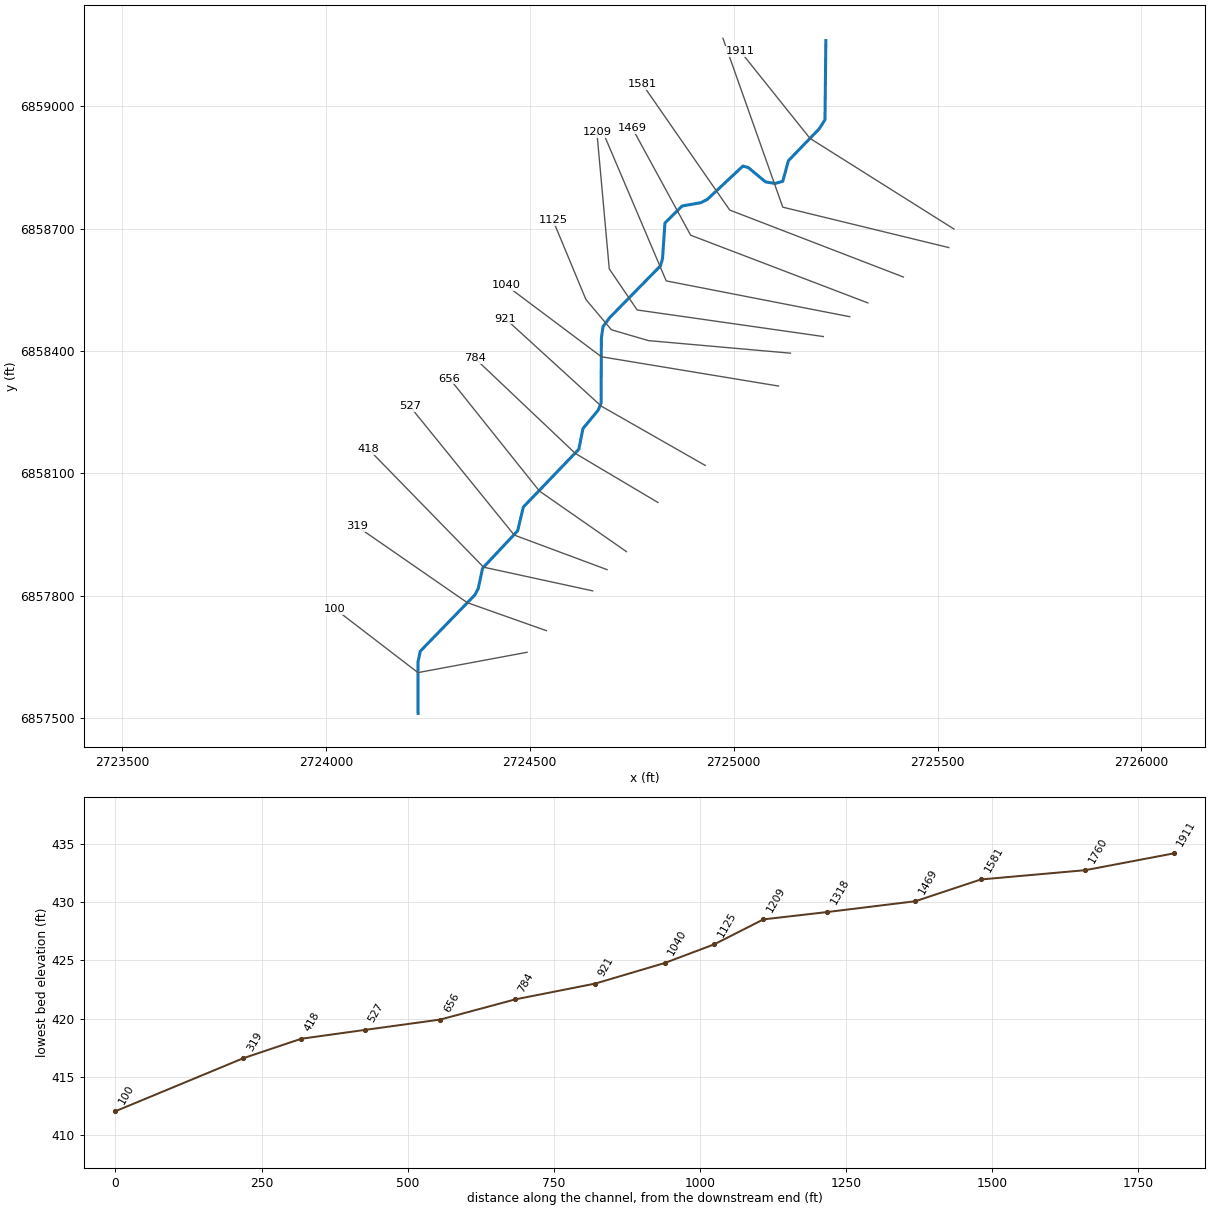
--- Lacy 140.prj (project) ---

Proj Title=Lacy 140 Base Level Engineering
Current Plan=p01
Default Exp/Contr=0.3,0.1
English Units
Geom File=g01
Flow File=f01
Plan File=p01
BEGIN DESCRIPTION:
Lacy 140
END DESCRIPTION:

--- Lacy 140.p01 (plan) ---

Plan Title=Multiple Run
Short Identifier=Multiple
Geom File=g01
Flow File=f01
Subcritical Flow
K Sum by GR= 0
Std Step Tol= 0.01
Critical Tol= 0.01
Num of Std Step Trials= 20
Max Error Tol= 0.3
Flow Tol Ratio= 0.001
Split Flow NTrial= 30
Split Flow Tol= 0.02
Split Flow Ratio= 0.02
Log Output Level= 0
Friction Slope Method= 1
Unsteady Friction Slope Method= 2
Unsteady Bridges Friction Slope Method= 1
Parabolic Critical Depth
Global Vel Dist=  1 , 1 , 1
Global Log Level= 0
CheckData=True
Encroach Param= -1, 0, 0, 0
BEGIN DESCRIPTION:
Multiple Run
END DESCRIPTION:

--- Lacy 140.f01 (steady flow) ---

Flow Title=Multiple
Number of Profiles=7
Profile Names=10-year,25-year,50-year,1pct_min,100-year,1pct_plu,500-year
River Rch & RM= Lacy 140,Reach-1,1911
     137     165     186     105     209     417     261
Boundary for River Rch & Prof#=Lacy 140,Reach-1,1
Up Type=0
Dn Type=3
Dn Slope=0.005
Boundary for River Rch & Prof#=Lacy 140,Reach-1,2
Up Type=0
Dn Type=3
Dn Slope=0.005
Boundary for River Rch & Prof#=Lacy 140,Reach-1,3
Up Type=0
Dn Type=3
Dn Slope=0.005
Boundary for River Rch & Prof#=Lacy 140,Reach-1,4
Up Type=0
Dn Type=3
Dn Slope=0.005
Boundary for River Rch & Prof#=Lacy 140,Reach-1,5
Up Type=0
Dn Type=3
Dn Slope=0.005
Boundary for River Rch & Prof#=Lacy 140,Reach-1,6
Up Type=0
Dn Type=3
Dn Slope=0.005
Boundary for River Rch & Prof#=Lacy 140,Reach-1,7
Up Type=0
Dn Type=3
Dn Slope=0.005

--- Lacy 140.g01 (geometry) ---

Geom Title=Existing Conditions

River Reach=Lacy 140,Reach-1
Reach XY= 30
      2725226.00      6859161.00      2725223.94      6858966.85
      2725209.54      6858944.24      2725134.30      6858866.64
      2725120.38      6858815.81      2725101.09      6858810.56
      2725078.01      6858814.44      2725035.92      6858849.58
      2725022.62      6858853.16      2724935.66      6858771.83
      2724919.91      6858763.57      2724873.43      6858755.26
      2724831.42      6858713.67      2724825.47      6858626.22
      2724820.47      6858608.58      2724695.61      6858481.16
      2724679.54      6858459.54      2724675.57      6858431.18
      2724674.80      6858271.50      2724667.91      6858254.92
      2724630.22      6858209.25      2724620.17      6858158.70
      2724484.16      6858017.05      2724470.13      6857958.72
      2724384.18      6857867.04      2724373.47      6857817.05
      2724365.22      6857801.32      2724231.43      6857663.46
      2724225.62      6857636.16      2724226.00      6857511.00

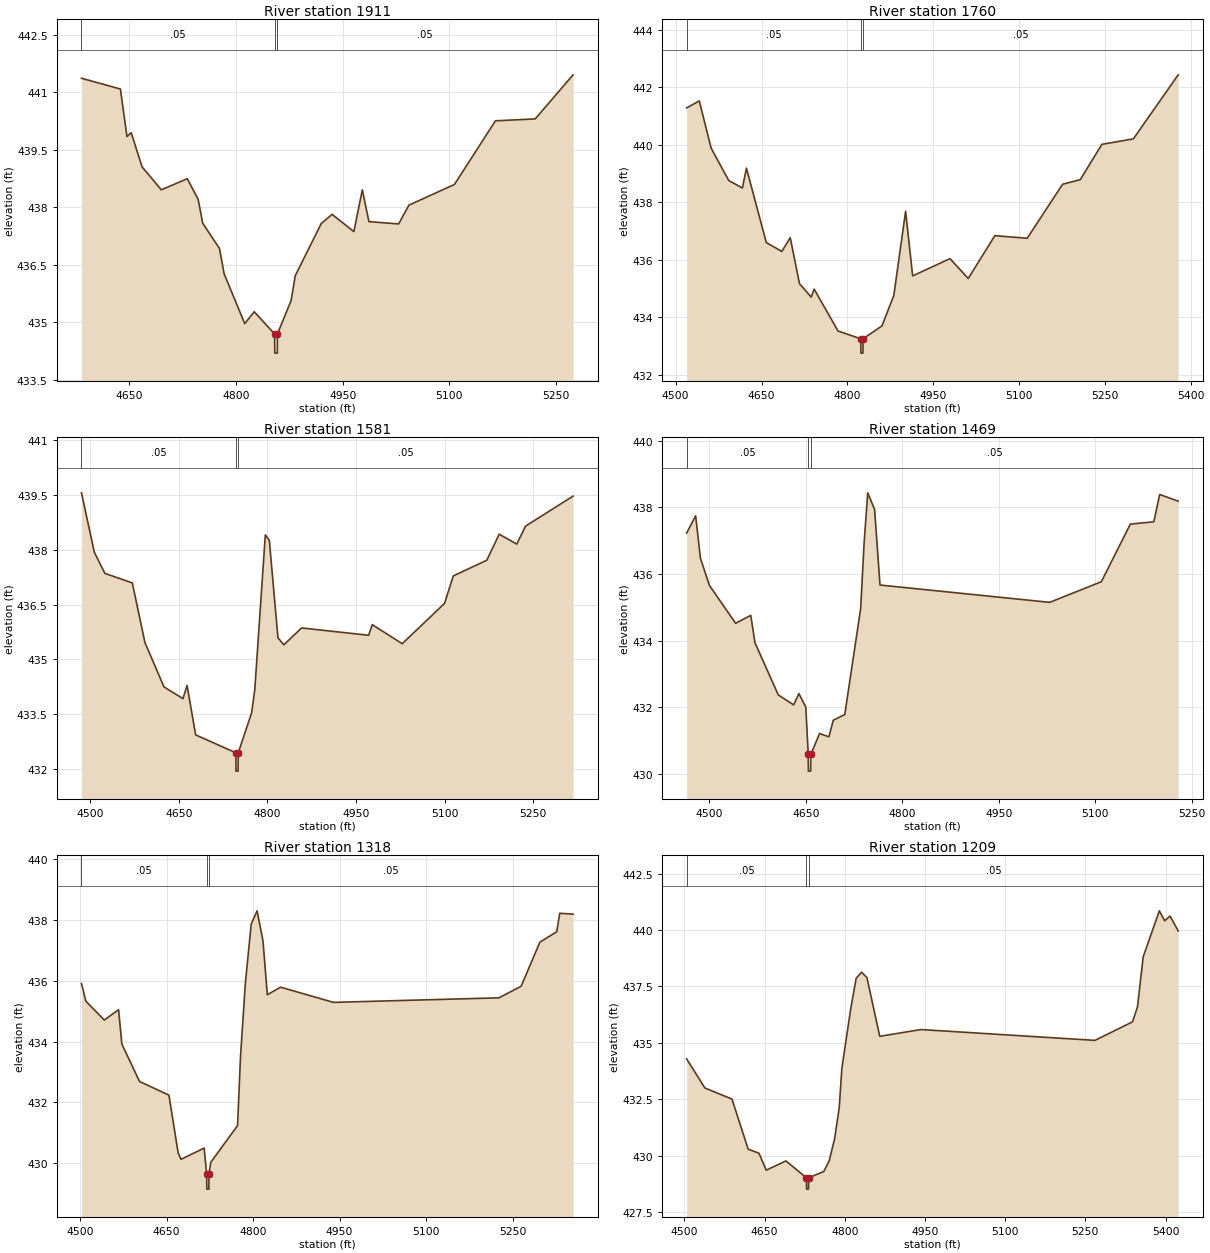
Type RM Length L Ch R = 1,1911,151,151,151
BEGIN DESCRIPTION:
Lacy 140 1056
END DESCRIPTION:
XS GIS Cut Line= 3
      2725540.26      6858698.78      2725187.14      6858921.14
      2725015.93      6859135.20
#Sta/Elev= 30
  4582.7  441.36  4637.4  441.08  4646.7  439.84  4652.6  439.94  4667.9  439.05
  4695.0  438.45  4731.5  438.74  4746.8  438.20  4753.2  437.58  4776.8  436.92
  4783.3  436.26  4812.3  434.96  4825.7  435.27  4854.3  434.69  4854.6  434.19
  4858.1  434.19  4858.3  434.69  4877.5  435.56  4883.4  436.21  4919.9  437.57
  4935.2  437.81  4965.8  437.36  4977.7  438.45  4987.0  437.62  5028.8  437.56
  5043.2  438.05  5107.3  438.59  5164.9  440.25  5220.9  440.30  5274.1  441.45
#Mann=3,-1,0
  4582.7    0.05       0  4854.3   0.035       0  4858.3    0.05       0
Bank Sta=4854.3,4858.3
Exp/Cntr=0.3,0.1

Type RM Length L Ch R = 1,1760,179,179,179
BEGIN DESCRIPTION:
Lacy 140 1052
END DESCRIPTION:
XS GIS Cut Line= 3
      2725527.44      6858653.39      2725120.40      6858752.47
      2724973.67      6859166.51
#Sta/Elev= 30
  4519.2  441.29  4541.3  441.53  4561.9  439.89  4592.7  438.76  4616.6  438.50
  4623.6  439.19  4658.3  436.60  4685.4  436.29  4700.1  436.77  4716.2  435.17
  4736.7  434.70  4741.8  434.98  4783.5  433.52  4823.2  433.25  4823.5  432.75
  4827.0  432.75  4827.2  433.25  4860.3  433.70  4880.9  434.76  4901.5  437.69
  4913.8  435.44  4979.0  436.04  5010.8  435.35  5057.3  436.84  5113.8  436.75
  5175.6  438.63  5206.4  438.79  5244.2  440.02  5299.1  440.21  5377.4  442.44
#Mann=3,-1,0
  4519.2    0.05       0  4823.2    0.03       0  4827.2    0.05       0
Bank Sta=4823.2,4827.2
Exp/Cntr=0.3,0.1

Type RM Length L Ch R = 1,1581,112,112,112
BEGIN DESCRIPTION:
Lacy 140 1051
END DESCRIPTION:
XS GIS Cut Line= 3
      2725416.25      6858581.13      2724990.29      6858745.34
      2724776.38      6859053.81
#Sta/Elev= 30
  4485.3  439.55  4507.0  437.93  4524.9  437.35  4571.3  437.09  4592.7  435.46
  4624.9  434.25  4657.0  433.93  4664.0  434.29  4678.5  432.94  4746.6  432.45
  4746.8  431.95  4750.3  431.95  4750.6  432.45  4773.2  433.54  4778.6  434.18
  4796.4  438.40  4803.2  438.25  4817.8  435.59  4827.8  435.40  4857.8  435.86
  4971.3  435.66  4977.4  435.95  5028.1  435.43  5099.7  436.53  5114.5  437.28
  5171.3  437.71  5192.2  438.42  5221.9  438.15  5236.8  438.64  5317.2  439.46
#Mann=3,-1,0
  4485.3    0.05       0  4746.6    0.03       0  4750.6    0.05       0
Bank Sta=4746.6,4750.6
Exp/Cntr=0.3,0.1

Type RM Length L Ch R = 1,1469,151,151,151
BEGIN DESCRIPTION:
Lacy 140 1050
END DESCRIPTION:
XS GIS Cut Line= 3
      2725329.10      6858517.64      2724894.46      6858683.68
      2724751.29      6858946.32
#Sta/Elev= 30
  4464.6  437.23  4478.6  437.75  4486.0  436.48  4500.0  435.66  4540.8  434.52
  4564.3  434.76  4570.8  433.94  4607.1  432.37  4631.0  432.07  4639.2  432.41
  4649.9  432.00  4653.7  430.58  4653.9  430.08  4657.4  430.08  4657.7  430.58
  4671.3  431.21  4685.8  431.11  4692.7  431.61  4710.5  431.78  4735.2  434.96
  4740.6  436.94  4746.2  438.44  4756.9  437.94  4765.3  435.67  5029.3  435.15
  5109.5  435.77  5154.6  437.50  5191.1  437.57  5200.2  438.39  5229.0  438.19
#Mann=3,-1,0
  4464.6    0.05       0  4653.7    0.03       0  4657.7    0.05       0
Bank Sta=4653.7,4657.7
Exp/Cntr=0.3,0.1

Type RM Length L Ch R = 1,1318,109,109,109
BEGIN DESCRIPTION:
Lacy 140 1049
END DESCRIPTION:
XS GIS Cut Line= 3
      2725284.75      6858483.82      2724834.54      6858571.65
      2724680.58      6858933.78
#Sta/Elev= 30
  4502.6  435.91  4510.2  435.33  4542.1  434.71  4566.9  435.05  4572.6  433.92
  4603.2  432.69  4654.2  432.24  4670.1  430.35  4675.1  430.13  4715.3  430.50
  4719.6  429.65  4719.9  429.15  4723.4  429.15  4723.6  429.65  4726.7  430.03
  4773.2  431.24  4778.3  433.51  4786.6  435.90  4796.8  437.86  4807.0  438.30
  4817.2  437.32  4824.8  435.54  4847.7  435.79  4939.4  435.29  5226.4  435.44
  5264.8  435.82  5297.3  437.27  5326.4  437.61  5331.8  438.22  5354.8  438.19
#Mann=3,-1,0
  4502.6    0.05       0  4719.6    0.03       0  4723.6    0.05       0
Bank Sta=4719.6,4723.6
Exp/Cntr=0.3,0.1

Type RM Length L Ch R = 1,1209,84,84,84
BEGIN DESCRIPTION:
Lacy 140 1048
END DESCRIPTION:
XS GIS Cut Line= 4
      2725219.91      6858435.18      2724763.25      6858500.32
      2724694.89      6858601.17      2724664.50      6858936.18
#Sta/Elev= 30
  4504.2  434.29  4538.4  433.00  4589.0  432.51  4619.3  430.29  4639.5  430.11
  4653.1  429.36  4690.0  429.77  4728.4  429.02  4728.6  428.52  4732.1  428.52
  4732.4  429.02  4760.7  429.30  4770.8  429.77  4780.9  430.74  4789.6  432.12
  4794.6  433.88  4811.2  436.52  4821.3  437.86  4831.4  438.13  4841.5  437.89
  4865.4  435.29  4942.5  435.59  5267.9  435.11  5338.2  435.93  5347.5  436.59
  5358.2  438.81  5388.4  440.85  5398.4  440.41  5408.5  440.62  5423.7  439.96
#Mann=3,-1,0
  4504.2    0.05       0  4728.4   0.035       0  4732.4    0.05       0
Bank Sta=4728.4,4732.4
Exp/Cntr=0.3,0.1

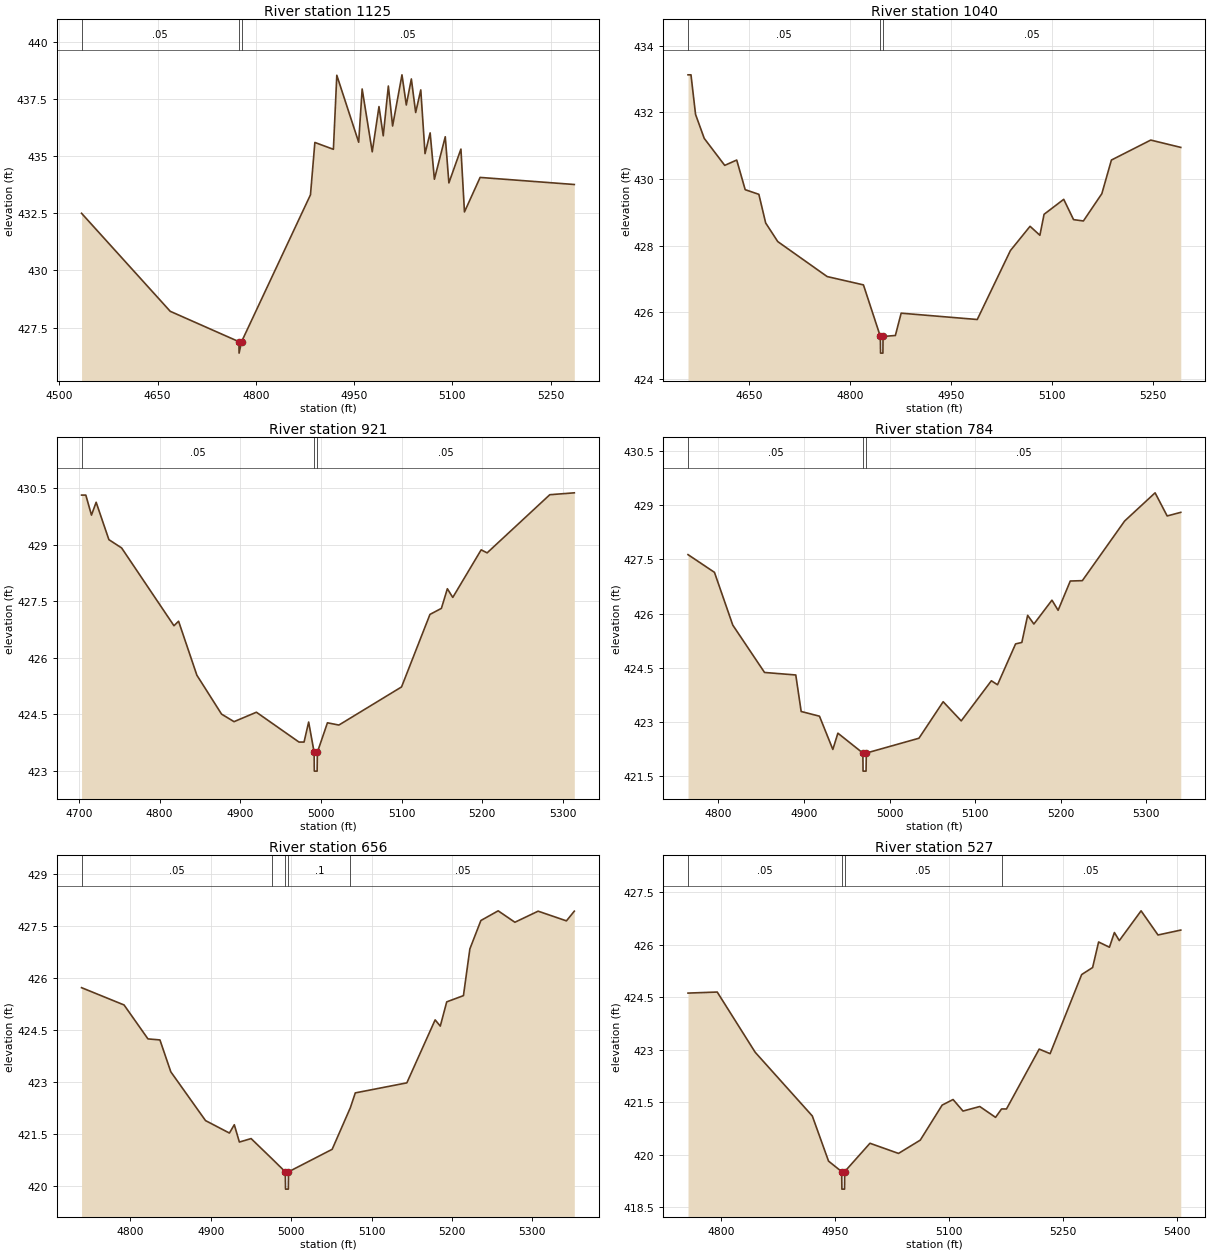
Type RM Length L Ch R = 1,1125,85,85,85
BEGIN DESCRIPTION:
Lacy 140 1047
END DESCRIPTION:
XS GIS Cut Line= 5
      2725139.20      6858394.37      2724791.06      6858425.17
      2724700.11      6858451.73      2724637.58      6858526.07
      2724556.62      6858720.83
#Sta/Elev= 30
  4534.0  432.50  4669.4  428.21  4774.3  426.88  4774.5  426.38  4778.3  426.88
  4883.5  433.31  4890.2  435.60  4918.5  435.30  4923.7  438.54  4957.1  435.61
  4962.4  437.94  4977.8  435.19  4988.1  437.17  4994.6  435.89  5002.4  438.07
  5008.9  436.32  5023.2  438.56  5029.8  437.24  5037.5  438.38  5044.1  436.91
  5051.9  437.90  5058.4  435.11  5066.2  436.02  5072.7  433.99  5089.3  435.85
  5094.8  433.83  5113.2  435.31  5118.6  432.56  5142.5  434.07  5286.3  433.76
#Mann=3,-1,0
  4534.0    0.05       0  4774.3   0.035       0  4778.3    0.05       0
Bank Sta=4774.3,4778.3
Exp/Cntr=0.3,0.1

Type RM Length L Ch R = 1,1040,119,119,119
BEGIN DESCRIPTION:
Lacy 140 1046
END DESCRIPTION:
XS GIS Cut Line= 3
      2725109.79      6858313.78      2724675.60      6858385.59
      2724442.23      6858560.45
#Sta/Elev= 30
  4559.6  433.13  4564.0  433.13  4570.8  431.94  4583.7  431.22  4614.1  430.41
  4631.9  430.57  4644.5  429.68  4664.8  429.54  4674.9  428.68  4692.9  428.12
  4766.2  427.07  4820.1  426.82  4845.2  425.27  4845.5  424.77  4849.0  424.77
  4849.2  425.27  4867.5  425.30  4876.1  425.97  4989.1  425.78  5038.3  427.85
  5067.5  428.58  5082.1  428.31  5088.3  428.94  5117.5  429.39  5132.1  428.78
  5146.7  428.74  5174.1  429.56  5188.3  430.57  5246.7  431.17  5291.3  430.95
#Mann=3,-1,0
  4559.6    0.05       0  4845.2   0.035       0  4849.2    0.05       0
Bank Sta=4845.2,4849.2
Exp/Cntr=0.3,0.1

Type RM Length L Ch R = 1,921,137,137,137
BEGIN DESCRIPTION:
Lacy 140 1045
END DESCRIPTION:
XS GIS Cut Line= 3
      2724930.20      6858119.06      2724674.95      6858264.70
      2724440.68      6858478.44
#Sta/Elev= 30
  4703.2  430.31  4708.5  430.31  4715.5  429.78  4721.3  430.12  4737.1  429.13
  4752.9  428.91  4817.8  426.85  4823.5  426.97  4846.2  425.54  4876.8  424.51
  4892.3  424.31  4920.0  424.56  4972.8  423.77  4979.1  423.77  4984.8  424.30
  4991.6  423.50  4991.8  423.00  4995.3  423.00  4995.6  423.50  5008.1  424.28
  5022.3  424.22  5100.0  425.23  5135.2  427.15  5149.4  427.31  5156.8  427.83
  5163.5  427.60  5198.7  428.86  5206.1  428.78  5283.8  430.32  5314.2  430.37
#Mann=3,-1,0
  4703.2    0.05       0  4991.6    0.04       0  4995.6    0.05       0
Bank Sta=4991.6,4995.6
Exp/Cntr=0.3,0.1

Type RM Length L Ch R = 1,784,128,128,128
BEGIN DESCRIPTION:
Lacy 140 1044
END DESCRIPTION:
XS GIS Cut Line= 3
      2724814.23      6858028.24      2724611.65      6858148.49
      2724364.76      6858382.42
#Sta/Elev= 30
  4764.6  427.63  4795.5  427.14  4816.9  425.68  4854.0  424.37  4890.5  424.30
  4896.8  423.29  4918.2  423.16  4933.8  422.24  4939.7  422.69  4968.9  422.14
  4969.1  421.64  4972.6  421.64  4972.9  422.14  5034.4  422.55  5062.7  423.56
  5083.8  423.03  5119.0  424.14  5126.2  424.03  5147.3  425.16  5154.6  425.20
  5161.4  425.95  5168.7  425.71  5189.8  426.37  5197.0  426.09  5211.2  426.90
  5225.3  426.91  5274.7  428.56  5310.3  429.34  5324.4  428.70  5340.3  428.80
#Mann=3,-1,0
  4764.6    0.05       0  4968.9    0.04       0  4972.9    0.05       0
Bank Sta=4968.9,4972.9
Exp/Cntr=0.3,0.1

Type RM Length L Ch R = 1,656,129,129,129
BEGIN DESCRIPTION:
Lacy 140 1043
END DESCRIPTION:
XS GIS Cut Line= 3
      2724737.10      6857907.63      2724523.48      6858056.28
      2724303.40      6858331.83
#Sta/Elev= 30
  4739.3  425.73  4792.2  425.23  4821.9  424.25  4836.8  424.22  4850.3  423.30
  4893.5  421.89  4923.2  421.53  4929.3  421.77  4935.6  421.27  4950.2  421.37
  4976.5  420.78  4992.7  420.41  4993.0  419.91  4996.5  419.91  4996.7  420.41
  5051.0  421.06  5073.6  422.26  5079.8  422.69  5143.9  422.98  5179.1  424.80
  5185.5  424.62  5193.5  425.32  5214.3  425.50  5222.3  426.85  5236.0  427.67
  5257.5  427.95  5278.3  427.62  5307.2  427.94  5342.4  427.66  5352.2  427.94
#Mann=5,-1,0
  4739.3    0.05       0  4976.5     0.1       0  4992.7    0.07       0
  4996.7     0.1       0  5073.6    0.05       0
Bank Sta=4992.7,4996.7
Exp/Cntr=0.3,0.1

Type RM Length L Ch R = 1,527,109,109,109
BEGIN DESCRIPTION:
Lacy 140 1042
END DESCRIPTION:
XS GIS Cut Line= 3
      2724689.54      6857863.47      2724461.73      6857948.31
      2724205.96      6858264.00
#Sta/Elev= 30
  4755.9  424.62  4794.4  424.65  4844.4  422.93  4919.7  421.11  4941.1  419.82
  4958.4  419.52  4958.7  419.02  4962.2  419.02  4962.4  419.52  4995.7  420.33
  5033.3  420.04  5062.0  420.42  5090.8  421.42  5105.2  421.58  5118.3  421.25
  5140.4  421.38  5161.2  421.07  5169.1  421.31  5175.6  421.31  5218.7  423.02
  5233.1  422.89  5274.7  425.15  5289.1  425.35  5297.0  426.08  5311.3  425.93
  5317.8  426.35  5324.3  426.12  5353.0  426.97  5375.3  426.28  5405.3  426.42
#Mann=4,-1,0
  4755.9    0.05       0  4958.4    0.07       0  4962.4    0.05       0
  5169.1    0.05       0
Bank Sta=4958.4,4962.4
Exp/Cntr=0.3,0.1

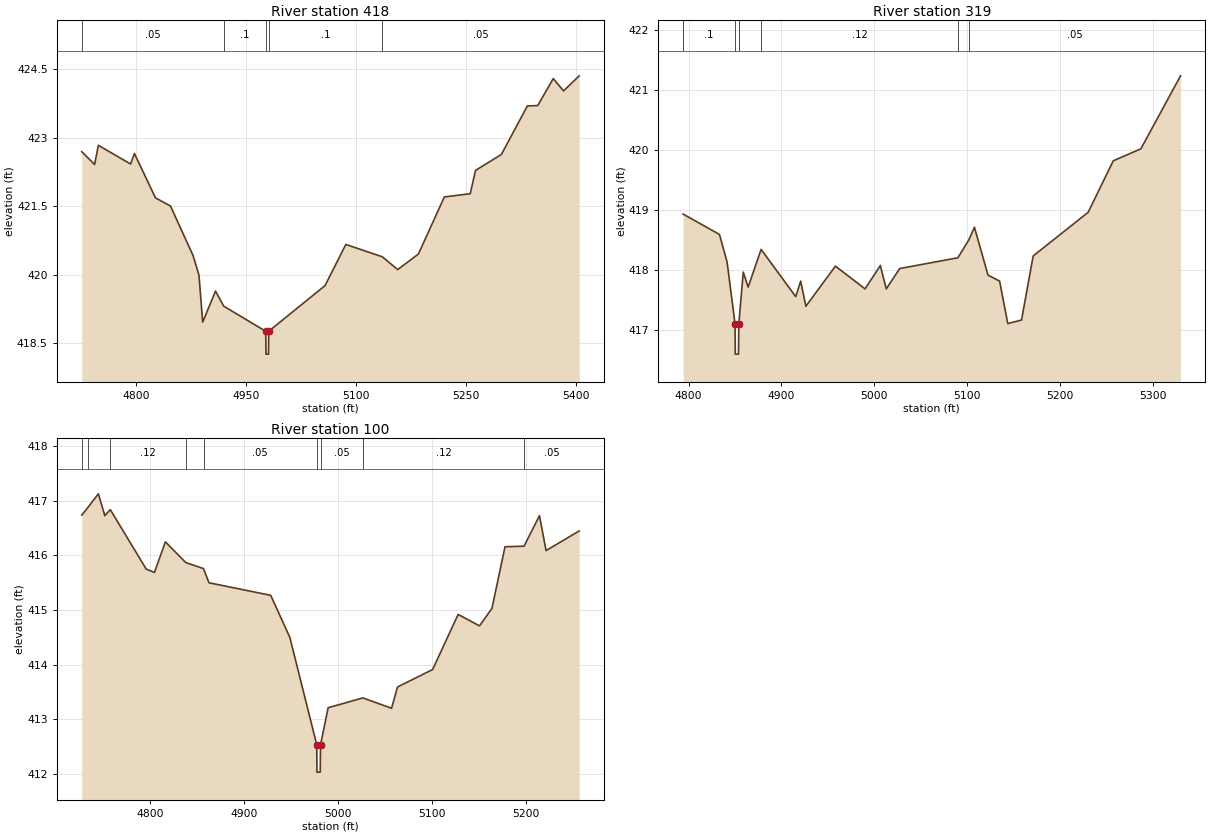
Type RM Length L Ch R = 1,418,99,99,99
BEGIN DESCRIPTION:
Lacy 140 1055
END DESCRIPTION:
XS GIS Cut Line= 3
      2724654.24      6857811.44      2724386.58      6857869.61
      2724104.17      6858159.20
#Sta/Elev= 30
  4726.1  422.69  4743.6  422.41  4748.7  422.83  4792.7  422.42  4797.9  422.65
  4826.6  421.68  4847.1  421.50  4877.8  420.42  4885.9  419.99  4891.0  418.96
  4908.5  419.64  4919.7  419.31  4977.0  418.76  4977.3  418.26  4980.8  418.26
  4981.0  418.76  5057.9  419.76  5086.2  420.66  5136.0  420.39  5156.9  420.11
  5185.2  420.45  5220.6  421.70  5255.9  421.77  5263.1  422.28  5298.4  422.63
  5333.8  423.69  5348.0  423.70  5369.1  424.29  5383.2  424.02  5404.5  424.35
#Mann=5,-1,0
  4726.1    0.05       0  4919.7     0.1       0  4977.0    0.07       0
  4981.0     0.1       0  5136.0    0.05       0
Bank Sta=4977,4981
Exp/Cntr=0.3,0.1

Type RM Length L Ch R = 1,319,219,219,219
BEGIN DESCRIPTION:
Lacy 140 1054
END DESCRIPTION:
XS GIS Cut Line= 3
      2724540.54      6857713.87      2724346.55      6857782.58
      2724075.57      6857970.04
#Sta/Elev= 30
  4794.2  418.93  4833.3  418.59  4841.5  418.13  4850.1  417.09  4850.3  416.59
  4853.8  416.59  4854.1  417.09  4858.9  417.96  4864.2  417.71  4878.1  418.34
  4915.4  417.55  4920.7  417.81  4926.3  417.39  4958.1  418.06  4990.0  417.68
  5006.4  418.07  5012.8  417.68  5027.3  418.02  5089.9  418.20  5101.7  418.50
  5107.7  418.71  5122.3  417.91  5134.8  417.81  5143.6  417.10  5158.4  417.16
  5170.9  418.23  5230.1  418.96  5257.1  419.82  5286.8  420.02  5329.5  421.24
#Mann=6,-1,0
  4794.2     0.1       0  4850.1    0.07       0  4854.1     0.1       0
  4878.1    0.12       0  5089.9     0.1       0  5101.7    0.05       0
Bank Sta=4850.1,4854.1
Exp/Cntr=0.3,0.1

Type RM Length L Ch R = 1,100,0,0,0
BEGIN DESCRIPTION:
Lacy 140 1053
END DESCRIPTION:
XS GIS Cut Line= 3
      2724493.29      6857660.83      2724225.70      6857610.96
      2724022.51      6857767.01
#Sta/Elev= 30
  4727.8  416.74  4734.3  416.88  4745.4  417.13  4752.3  416.73  4758.1  416.84
  4796.3  415.75  4805.0  415.69  4816.6  416.25  4838.3  415.87  4857.1  415.76
  4862.9  415.50  4928.5  415.27  4948.8  414.50  4977.4  412.53  4977.6  412.03
  4981.1  412.03  4981.4  412.53  4989.5  413.21  5026.4  413.39  5056.9  413.20
  5063.2  413.59  5100.5  413.91  5127.6  414.92  5150.3  414.71  5163.5  415.03
  5177.4  416.16  5197.6  416.17  5214.0  416.73  5221.0  416.09  5256.2  416.45
#Mann=9,-1,0
  4727.8    0.05       0  4734.3     0.1       0  4758.1    0.12       0
  4838.3     0.1       0  4857.1    0.05       0  4977.4    0.04       0
  4981.4    0.05       0  5026.4    0.12       0  5197.6    0.05       0
Bank Sta=4977.4,4981.4
Exp/Cntr=0.3,0.1

Chan Stop Cuts=-1