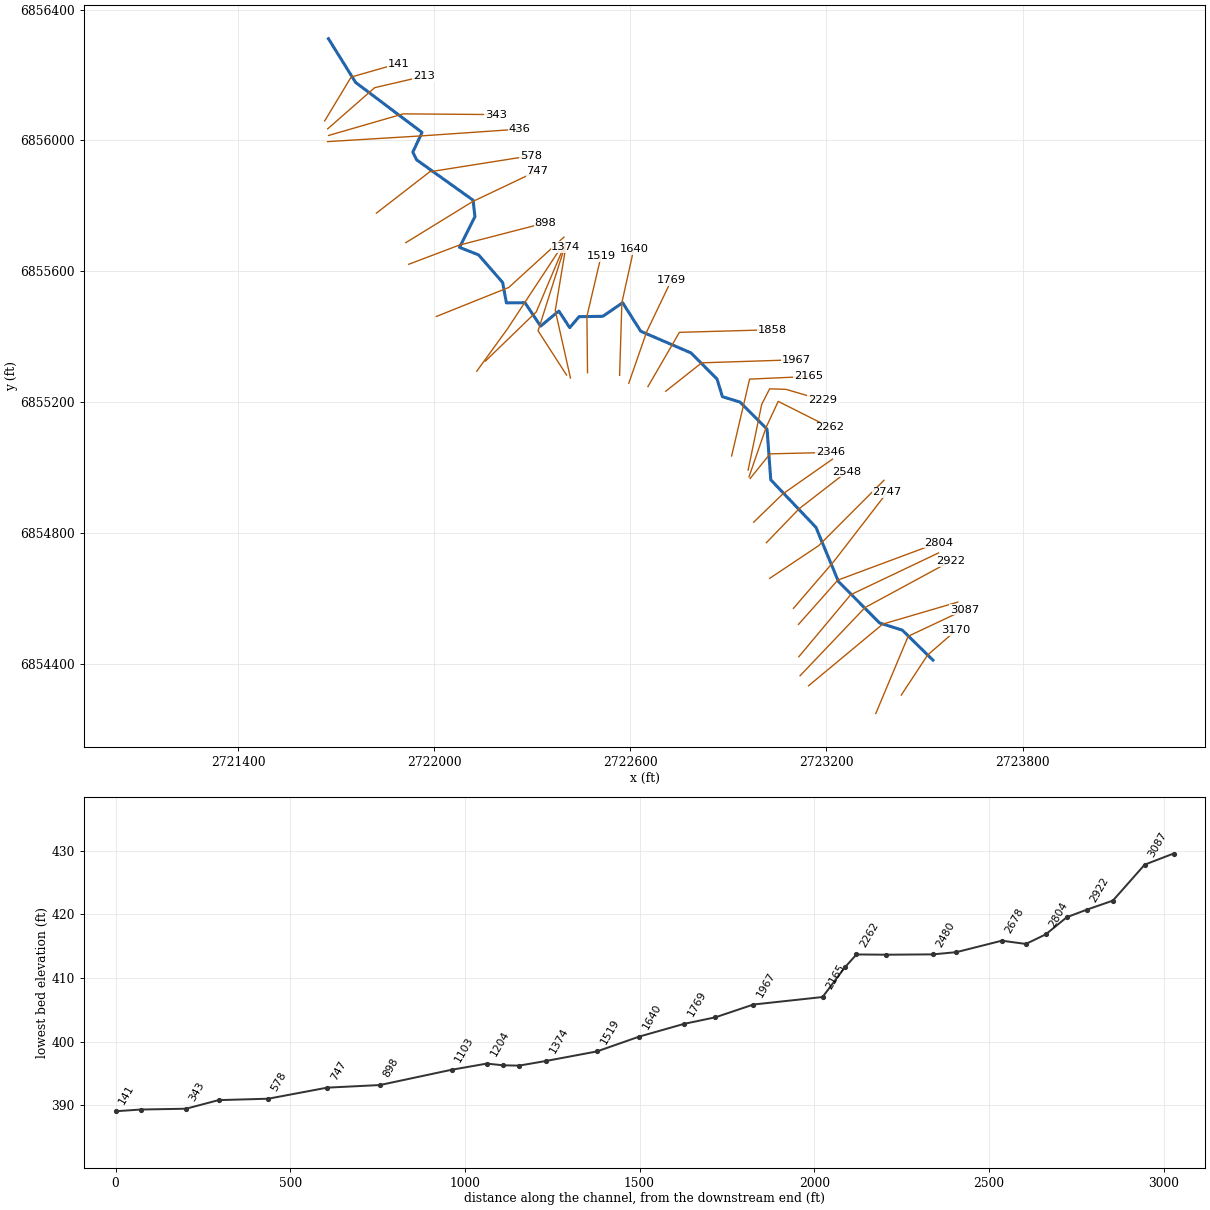
--- Lacy 141.prj (project) ---

Proj Title=Lacy 141 Base Level Engineering
Current Plan=p01
Default Exp/Contr=0.3,0.1
English Units
Geom File=g01
Flow File=f01
Plan File=p01
Y Axis Title=Elevation
X Axis Title(PF)=Main Channel Distance
X Axis Title(XS)=Station
BEGIN DESCRIPTION:
Lacy 141
END DESCRIPTION:
DSS Export Rating Curves= 0
DSS Export Rating Curve Sorted= 0
DSS Export Volume Flow Curves= 0
DXF OffsetX= 0
DXF OffsetY= 0
DXF ScaleX= 1
DXF ScaleY= 10

--- Lacy 141.p01 (plan) ---

Plan Title=Multiple Run
Short Identifier=Multiple
Geom File=g01
Flow File=f01
Subcritical Flow
K Sum by GR= 0
Std Step Tol= 0.01
Critical Tol= 0.01
Num of Std Step Trials= 20
Max Error Tol= 0.3
Flow Tol Ratio= 0.001
Split Flow NTrial= 30
Split Flow Tol= 0.02
Split Flow Ratio= 0.02
Log Output Level= 0
Friction Slope Method= 1
Unsteady Friction Slope Method= 2
Unsteady Bridges Friction Slope Method= 1
Parabolic Critical Depth
Global Vel Dist=  1 , 1 , 1
Global Log Level= 0
CheckData=True
Encroach Param= -1, 0, 0, 0
BEGIN DESCRIPTION:
Multiple Run
END DESCRIPTION:

--- Lacy 141.f01 (steady flow) ---

Flow Title=Multiple
Number of Profiles=7
Profile Names=10-year,25-year,50-year,1pct_min,100-year,1pct_plu,500-year
River Rch & RM= Lacy 141,Reach-1,3170
     209     263     303     175     349     697     461
River Rch & RM= Lacy 141,Reach-1,1250
     296     382     450     264     527    1051     720
Boundary for River Rch & Prof#=Lacy 141,Reach-1,1
Up Type=0
Dn Type=3
Dn Slope=0.005
Boundary for River Rch & Prof#=Lacy 141,Reach-1,2
Up Type=0
Dn Type=3
Dn Slope=0.005
Boundary for River Rch & Prof#=Lacy 141,Reach-1,3
Up Type=0
Dn Type=3
Dn Slope=0.005
Boundary for River Rch & Prof#=Lacy 141,Reach-1,4
Up Type=0
Dn Type=3
Dn Slope=0.005
Boundary for River Rch & Prof#=Lacy 141,Reach-1,5
Up Type=0
Dn Type=3
Dn Slope=0.005
Boundary for River Rch & Prof#=Lacy 141,Reach-1,6
Up Type=0
Dn Type=3
Dn Slope=0.005
Boundary for River Rch & Prof#=Lacy 141,Reach-1,7
Up Type=0
Dn Type=3
Dn Slope=0.005

--- Lacy 141.g01 (geometry) ---

Geom Title=Existing Conditions
Program Version=4.10

River Reach=Lacy 141        ,Reach-1
Reach XY= 30
        2723526.        6854411.      2723432.07      6854502.89
      2723362.79      6854524.63      2723236.76      6854651.32
      2723167.86      6854817.06      2723029.54      6854962.47
      2723018.19      6855117.21      2722935.44      6855200.12
      2722881.62      6855216.62      2722865.12      6855270.44
       2722785.7      6855350.24      2722631.61      6855416.66
       2722576.3      6855503.74      2722515.57      6855462.39
      2722442.92      6855461.09      2722414.28      6855427.65
      2722380.95      6855478.31      2722325.19      6855432.33
      2722277.27      6855503.95      2722220.52      6855503.39
      2722209.01      6855565.77      2722135.36      6855650.12
      2722077.18      6855673.01       2722124.2      6855767.14
      2722118.63      6855817.34      2721945.36      6855940.96
      2721934.16      6855964.32      2721962.36      6856024.36
      2721758.92      6856177.42        2721676.        6856311.

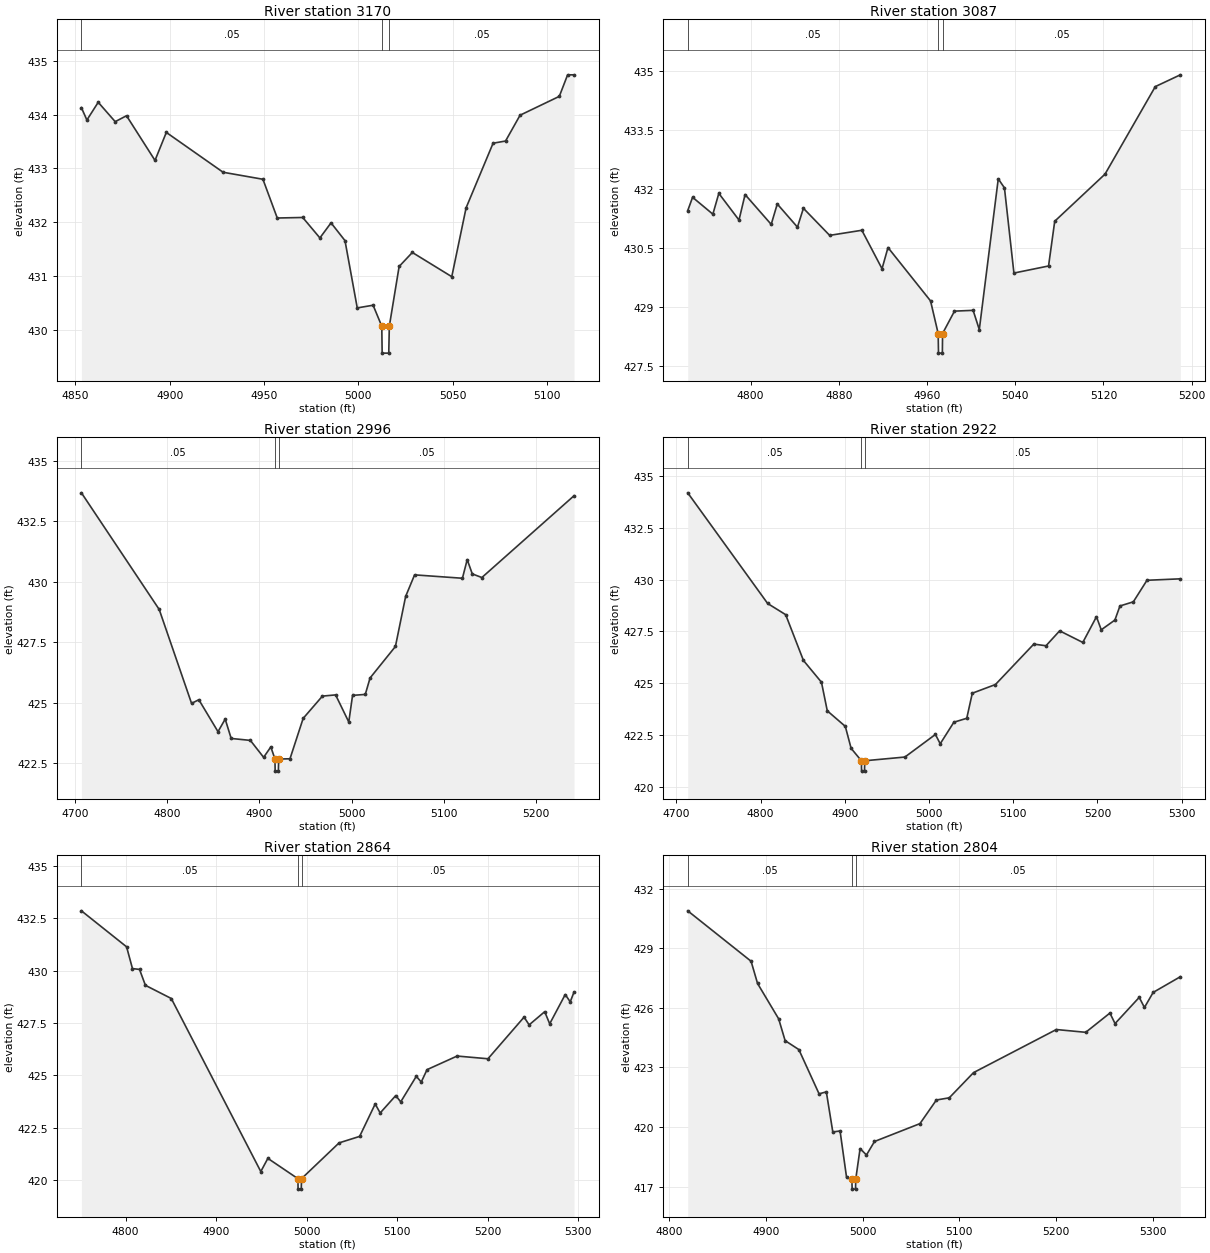
Type RM Length L Ch R = 1 ,3170    ,83,83,83
BEGIN DESCRIPTION:
Lacy 141 1041
END DESCRIPTION:
XS GIS Cut Line= 3
      2723428.93      6854304.37       2723509.7      6854426.95
      2723596.11      6854501.77
#Sta/Elev= 30
  4853.2  434.13  4856.1   433.9  4862.1  434.23  4871.1  433.87  4877.1  433.98
  4892.2  433.15  4898.2  433.67  4928.3  432.93  4949.4   432.8    4957  432.08
  4970.5  432.09  4979.6  431.71  4985.5  431.99  4992.9  431.66  4999.4  430.41
  5007.8  430.46  5012.4  430.07  5012.6  429.57  5016.1  429.57  5016.4  430.07
  5021.6  431.18  5028.6  431.44  5049.5  430.99  5057.1  432.27  5071.4  433.47
    5078  433.51  5085.7  433.99  5106.5  434.34  5110.9  434.74  5114.3  434.74
#Mann= 3 ,-1 , 0
  4853.2     .05       0  5012.4     .04       0  5016.4     .05       0
Bank Sta=5012.4,5016.4
XS Rating Curve= 0 ,0
Exp/Cntr=0.3,0.1

Type RM Length L Ch R = 1 ,3087    ,91,91,91
BEGIN DESCRIPTION:
Lacy 141 1040
END DESCRIPTION:
XS GIS Cut Line= 3
      2723350.93      6854247.97      2723450.07       6854484.1
      2723622.54      6854565.23
#Sta/Elev= 30
    4743  431.45  4747.4  431.79  4765.8  431.36  4771.2  431.89  4789.5  431.21
    4795  431.86  4818.7   431.1  4824.2  431.62  4842.5  431.03  4847.9  431.51
  4871.7  430.82  4900.9  430.95  4919.2  429.97  4924.6  430.51  4963.2  429.15
  4970.1  428.32  4970.4  427.82  4973.9  427.82  4974.1  428.32  4984.9  428.89
  5001.8  428.91  5007.4  428.42  5024.6  432.26  5030.2  432.03  5038.8  429.86
  5070.2  430.04  5075.8  431.18  5121.4  432.38    5167  434.61  5189.7  434.91
#Mann= 3 ,-1 , 0
    4743     .05       0  4970.1     .04       0  4974.1     .05       0
Bank Sta=4970.1,4974.1
XS Rating Curve= 0 ,0
Exp/Cntr=0.3,0.1

Type RM Length L Ch R = 1 ,2996    ,74,74,74
BEGIN DESCRIPTION:
Lacy 141 1039
END DESCRIPTION:
XS GIS Cut Line= 3
      2723145.21      6854332.81      2723372.11      6854521.25
      2723601.97       6854588.7
#Sta/Elev= 30
  4706.9  433.67  4791.3  428.85  4826.4  424.97  4834.3  425.12  4855.1   423.8
  4862.9  424.32  4869.4  423.52  4890.2  423.44  4904.6  422.74  4912.4  423.17
  4916.9  422.67  4917.1  422.17  4920.6  422.17  4920.9  422.67  4933.2  422.68
  4947.5  424.35  4968.4  425.27  4982.7  425.32    4997   424.2  5001.1   425.3
  5014.9  425.34  5020.1  426.02  5047.6  427.32  5058.7  429.39  5068.4  430.28
  5120.3  430.14  5125.5  430.91    5131  430.32  5141.4  430.17  5241.4  433.55
#Mann= 3 ,-1 , 0
  4706.9     .05       0  4916.9     .04       0  4920.9     .05       0
Bank Sta=4916.9,4920.9
XS Rating Curve= 0 ,0
Exp/Cntr=0.3,0.1

Type RM Length L Ch R = 1 ,2922    ,58,58,58
BEGIN DESCRIPTION:
Lacy 141 1037
END DESCRIPTION:
XS GIS Cut Line= 3
      2723119.19      6854363.41      2723318.07      6854571.94
      2723579.08       6854713.1
#Sta/Elev= 30
  4713.5  434.19  4808.4  428.85  4829.8  428.31  4850.9   426.1  4872.3  425.05
  4879.2  423.67  4900.6  422.92  4907.5  421.86  4919.7  421.26  4919.9  420.76
  4923.4  420.76  4923.7  421.26  4971.4  421.44  5007.6  422.53  5013.3  422.08
  5029.5  423.12  5044.8  423.31  5051.4  424.52  5078.9  424.94  5124.4  426.89
  5138.9  426.81  5155.1  427.53  5182.6  426.97  5198.8  428.21  5204.5  427.58
  5220.7  428.05  5226.7  428.73  5242.6  428.93  5258.8  429.97  5298.4  430.04
#Mann= 3 ,-1 , 0
  4713.5     .05       0  4919.7     .04       0  4923.7     .05       0
Bank Sta=4919.7,4923.7
XS Rating Curve= 0 ,0
Exp/Cntr=0.3,0.1

Type RM Length L Ch R = 1 ,2864    ,60,60,60
BEGIN DESCRIPTION:
Lacy 141 1038
END DESCRIPTION:
XS GIS Cut Line= 3
      2723115.63      6854421.77       2723274.2      6854611.18
      2723542.69      6854738.79
#Sta/Elev= 30
  4751.1  432.86    4801  431.14  4807.5   430.1  4815.3  430.06  4821.8   429.3
  4850.4  428.67  4949.3   420.4  4957.1  421.03  4990.3  420.06  4990.5  419.56
    4994  419.56  4994.3  420.06  5035.8  421.77  5058.5  422.08  5075.7  423.63
  5081.2   423.2  5098.4  424.03  5103.9  423.73  5121.1  424.95  5126.6  424.68
    5133  425.27  5166.2  425.92  5200.3  425.79  5240.2  427.78  5245.8  427.41
    5263  428.04  5268.5  427.46  5285.7  428.86  5291.2  428.51  5295.4  428.98
#Mann= 3 ,-1 , 0
  4751.1     .05       0  4990.3     .04       0  4994.3     .05       0
Bank Sta=4990.3,4994.3
XS Rating Curve= 0 ,0
Exp/Cntr=0.3,0.1

Type RM Length L Ch R = 1 ,2804    ,57,57,57
BEGIN DESCRIPTION:
Lacy 141 1036
END DESCRIPTION:
XS GIS Cut Line= 3
      2723114.42      6854520.44      2723234.62      6854655.72
      2723542.34      6854770.25
#Sta/Elev= 30
  4819.2  430.89  4884.7  428.35  4891.4  427.23  4913.2  425.45  4919.9  424.35
  4934.1   423.9    4955  421.67  4962.5  421.77  4969.2  419.75  4976.7   419.8
  4983.4  417.47  4988.9  417.37  4989.2  416.87  4992.7  416.87  4992.9  417.37
  4997.4  418.91    5004  418.59  5012.3  419.27  5059.3  420.17  5076.3  421.36
  5089.6  421.47  5114.7  422.74  5200.3  424.91  5230.7  424.77  5255.7  425.74
    5261  425.21    5286  426.53  5291.4  426.02  5300.4  426.78  5328.5  427.57
#Mann= 3 ,-1 , 0
  4819.2     .05       0  4988.9     .04       0  4992.9     .05       0
Bank Sta=4988.9,4992.9
XS Rating Curve= 0 ,0
Exp/Cntr=0.3,0.1

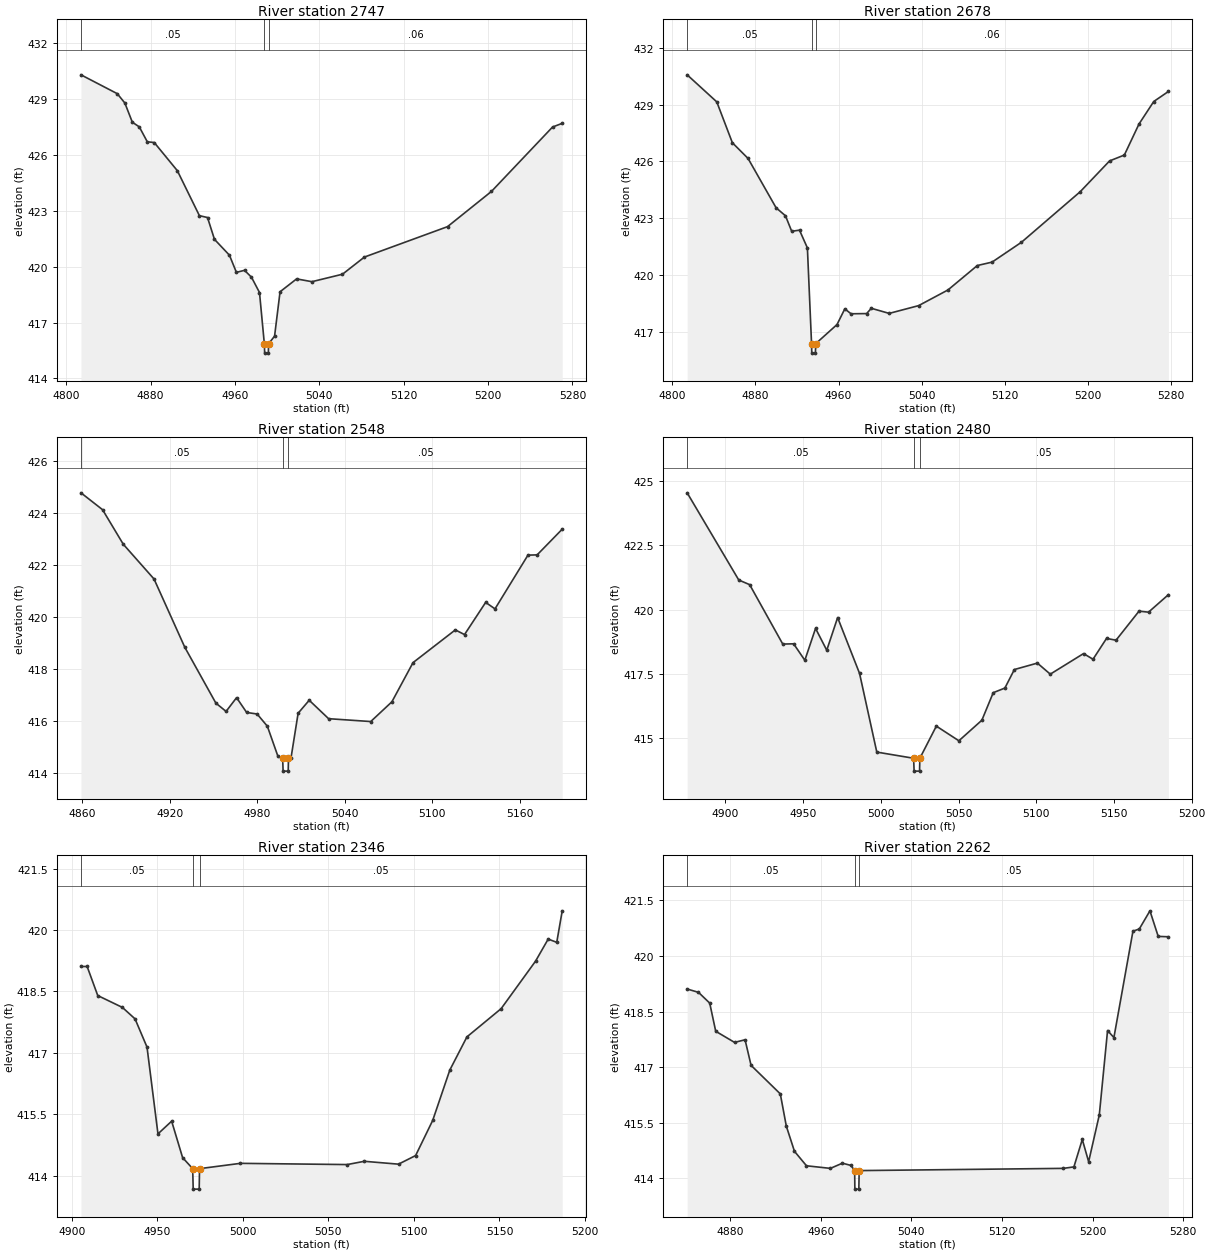
Type RM Length L Ch R = 1 ,2747    ,69,69,69
BEGIN DESCRIPTION:
Lacy 141 1035
END DESCRIPTION:
XS GIS Cut Line= 3
      2723098.98      6854569.45      2723223.35      6854713.91
      2723385.86      6854924.22
#Sta/Elev= 30
  4813.9  430.28  4848.3  429.27  4855.5  428.77  4862.6  427.74  4869.2  427.49
  4876.8  426.69  4883.4  426.65  4905.3  425.14  4926.2  422.73  4933.9  422.63
  4940.5  421.46  4954.7  420.61  4961.3  419.69    4969   419.8  4975.6  419.43
  4983.2  418.61  4987.8  415.86  4988.1  415.36  4991.6  415.36  4991.8  415.86
  4997.5  416.27  5002.7  418.65  5018.4  419.34  5032.9  419.19  5061.9  419.59
  5082.7  420.51  5161.5  422.14  5203.2  424.03  5261.1  427.48  5270.3  427.68
#Mann= 3 ,-1 , 0
  4813.9     .05       0  4987.8     .05       0  4991.8     .06       0
Bank Sta=4987.8,4991.8
XS Rating Curve= 0 ,0
Exp/Cntr=0.3,0.1

Type RM Length L Ch R = 1 ,2678    ,130,130,130
BEGIN DESCRIPTION:
Lacy 141 76
END DESCRIPTION:
XS GIS Cut Line= 3
      2723026.02      6854661.02        2723176.        6854761.
        2723376.        6854961.
#Sta/Elev= 30
  4814.3  430.58  4842.8  429.15  4857.8  426.99  4872.9  426.16  4899.9  423.55
  4908.9  423.13  4914.9  422.31  4922.4  422.37    4930  421.43    4934  416.37
  4934.2  415.87  4937.7  415.87    4938  416.37  4958.5  417.38    4966  418.21
    4972  417.95    4987  417.96  4991.5  418.24  5008.7  417.97    5037  418.38
  5065.3  419.21  5093.5   420.5  5107.7  420.68    5136  421.73  5192.5   424.4
  5220.8  426.03    5235  426.34  5249.1  427.98  5263.3  429.17  5277.4   429.7
#Mann= 3 ,-1 , 0
  4814.3     .05       0    4934     .04       0    4938     .06       0
Bank Sta=4934,4938
XS Rating Curve= 0 ,0
Exp/Cntr=0.3,0.1

Type RM Length L Ch R = 1 ,2548    ,68,68,68
BEGIN DESCRIPTION:
Lacy 141 1034
END DESCRIPTION:
XS GIS Cut Line= 3
      2723016.09      6854770.12       2723116.1      6854873.76
       2723263.2      6854987.56
#Sta/Elev= 30
    4859  424.79  4873.8  424.14    4888  422.81  4909.1  421.47  4930.2  418.84
  4951.5  416.69  4958.5  416.37  4965.7   416.9  4972.6  416.33  4979.8  416.27
  4986.8   415.8    4994  414.65  4997.3  414.57  4997.6  414.07  5001.1  414.07
  5001.3  414.57    5003  414.57  5007.9   416.3  5015.5   416.8  5028.8  416.09
  5057.7  415.98  5072.2  416.74  5086.7  418.25  5115.7  419.51    5122  419.33
  5136.5  420.57  5142.9  420.32  5165.5  422.39  5171.8   422.4    5189  423.39
#Mann= 3 ,-1 , 0
    4859     .05       0  4997.3     .04       0  5001.3     .05       0
Bank Sta=4997.3,5001.3
XS Rating Curve= 0 ,0
Exp/Cntr=0.3,0.1

Type RM Length L Ch R = 1 ,2480    ,134,134,134
BEGIN DESCRIPTION:
Lacy 141 1033
END DESCRIPTION:
XS GIS Cut Line= 3
      2722977.16      6854832.83      2723066.58      6854919.37
       2723218.3      6855025.51
#Sta/Elev= 30
  4875.4  424.54  4908.6  421.15  4915.6  420.97  4936.9  418.66  4943.9  418.67
  4951.1  418.03    4958  419.27  4965.2  418.42  4972.2  419.69  4986.3  417.52
  4997.4  414.46  5021.1  414.22  5021.4  413.72  5024.9  413.72  5025.1  414.22
  5035.7  415.47  5050.2   414.9    5065   415.7  5072.3  416.77  5079.8  416.95
  5085.9  417.67  5100.7  417.92    5109  417.49  5130.4  418.29  5136.5  418.07
  5145.2  418.88  5151.3  418.81  5166.1  419.94  5172.2   419.9    5185  420.58
#Mann= 3 ,-1 , 0
  4875.4     .05       0  5021.1     .04       0  5025.1     .05       0
Bank Sta=5021.1,5025.1
XS Rating Curve= 0 ,0
Exp/Cntr=0.3,0.1

Type RM Length L Ch R = 1 ,2346    ,84,84,84
BEGIN DESCRIPTION:
Lacy 141 1032
END DESCRIPTION:
XS GIS Cut Line= 3
       2722966.4      6854966.42      2723027.39      6855041.84
      2723211.64      6855046.13
#Sta/Elev= 26
  4905.4  419.11    4909  419.11  4915.2   418.4  4929.6  418.11    4937  417.83
    4944  417.14  4950.4  415.02  4958.4  415.33  4964.8  414.44  4970.7  414.17
    4971  413.67  4974.5  413.67  4974.7  414.17  4998.6   414.3    5061  414.27
    5071  414.35    5091  414.28    5101  414.49    5111  415.35    5121  416.58
    5131  417.39    5151  418.08  5171.1  419.24  5178.5  419.78  5183.5   419.7
  5186.7  420.47
#Mann= 3 ,-1 , 0
  4905.4     .05       0  4970.7     .05       0  4974.7     .05       0
Bank Sta=4970.7,4974.7
XS Rating Curve= 0 ,0
Exp/Cntr=0.3,0.1

Type RM Length L Ch R = 1 ,2262    ,33,33,33
BEGIN DESCRIPTION:
Lacy 141 1031
END DESCRIPTION:
XS GIS Cut Line= 4
      2722962.96      6854971.55      2723015.58      6855123.39
      2723052.29      6855202.18      2723210.54      6855122.73
#Sta/Elev= 30
  4842.1  419.11  4852.1  419.02    4862  418.73  4867.3  417.97  4883.9  417.67
  4893.2  417.74  4898.5  417.05  4924.3  416.28  4929.6  415.41  4936.8  414.73
  4947.4  414.34  4968.5  414.27  4979.1  414.41  4986.6  414.35  4989.9  414.21
  4990.1  413.71  4993.6  413.71  4993.9  414.21  5174.1  414.27  5183.4  414.31
  5190.8  415.05  5196.4  414.45  5205.8  415.71  5213.1  417.99  5218.7   417.8
  5235.5  420.67  5241.1  420.73  5250.5  421.22  5257.8  420.53  5266.8  420.52
#Mann= 3 ,-1 , 0
  4842.1     .05       0  4989.9     .05       0  4993.9     .05       0
Bank Sta=4989.9,4993.9
XS Rating Curve= 0 ,0
Exp/Cntr=0.3,0.1

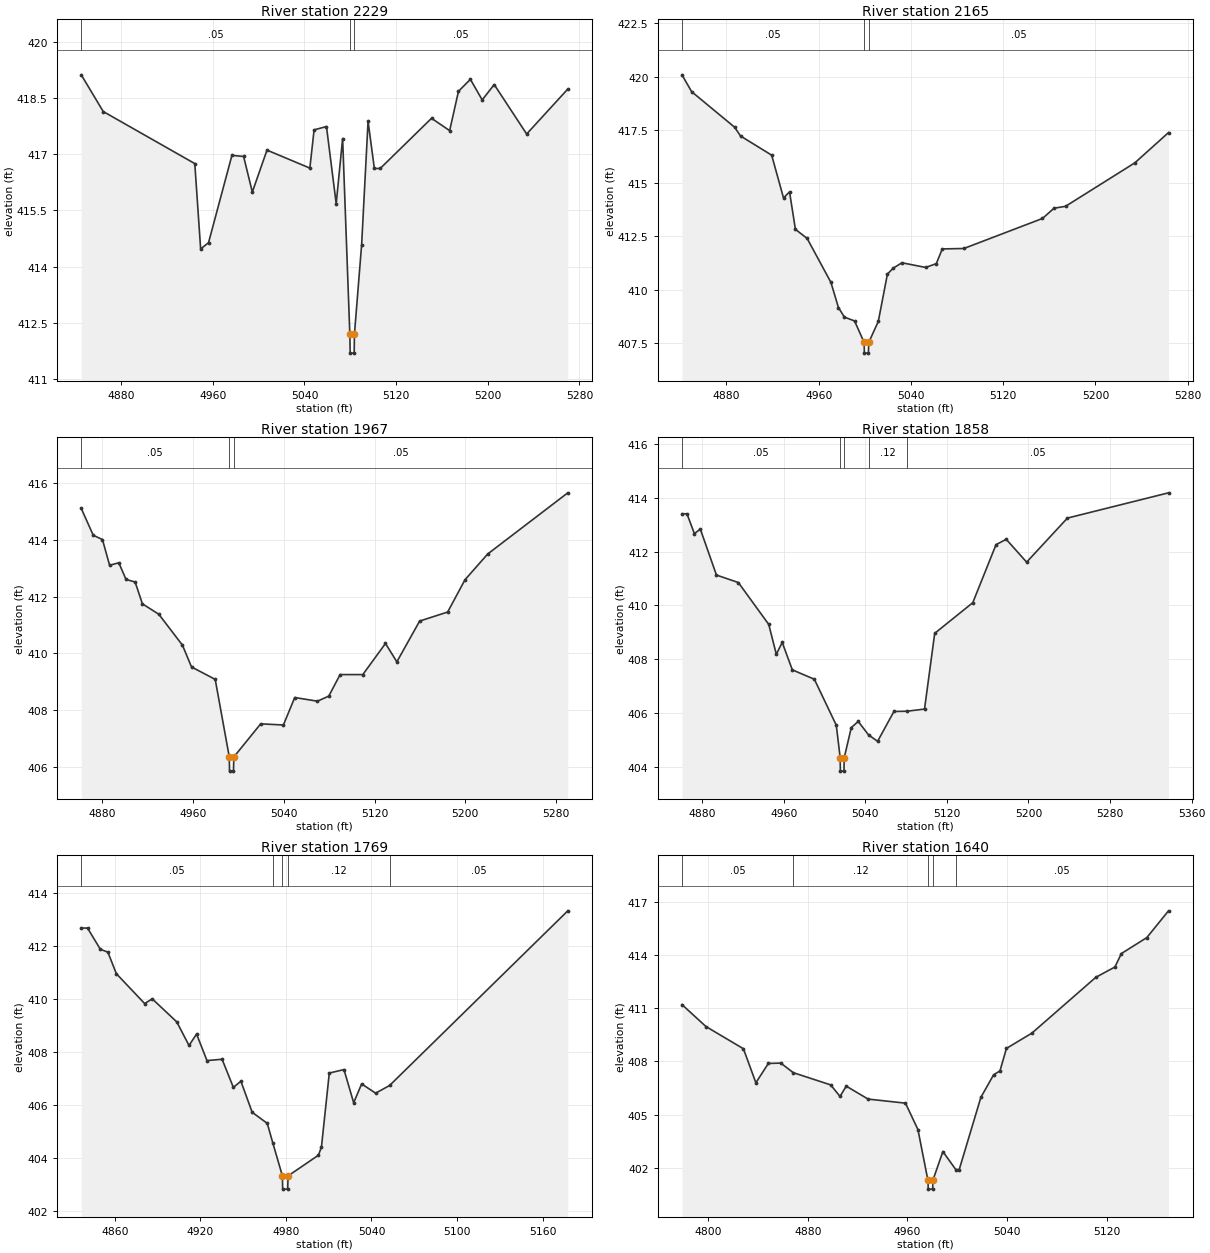
Type RM Length L Ch R = 1 ,2229    ,64,64,64
BEGIN DESCRIPTION:
Lacy 141 1030
END DESCRIPTION:
XS GIS Cut Line= 5
      2722960.27      6854992.24      2723001.84      6855193.21
      2723026.07      6855240.53      2723075.66      6855239.09
      2723187.64      6855206.63
#Sta/Elev= 30
  4845.2  419.12  4864.4  418.14  4944.3  416.75  4949.4  414.47  4956.3  414.64
  4976.7  416.97  4986.9  416.94  4994.5  415.99  5007.3  417.11  5044.7  416.63
  5048.4  417.65  5059.2  417.74  5067.7  415.68  5073.3  417.42  5079.6  412.19
  5079.9  411.69  5083.4  411.69  5083.6  412.19  5089.9  414.59  5095.5  417.88
    5101  416.62  5106.1  416.62  5150.9  417.96  5166.7  417.63  5174.4  418.68
  5184.8     419  5195.1  418.45  5205.6  418.86  5233.9  417.54  5269.8  418.74
#Mann= 3 ,-1 , 0
  4845.2     .05       0  5079.6     .05       0  5083.6     .05       0
Bank Sta=5079.6,5083.6
XS Rating Curve= 0 ,0
Exp/Cntr=0.3,0.1

Type RM Length L Ch R = 1 ,2165    ,198,198,198
BEGIN DESCRIPTION:
Lacy 141 1029
END DESCRIPTION:
XS GIS Cut Line= 3
      2722909.71      6855035.22       2722964.8      6855270.28
       2723145.2      6855278.37
#Sta/Elev= 30
  4841.4  420.08  4849.8  419.29  4887.1  417.62  4892.2  417.21  4919.2  416.31
  4929.5   414.3  4934.7  414.59  4939.8  412.83    4950   412.4  4970.6  410.34
  4977.1  409.16  4982.3  408.71  4991.1  408.53  4999.4  407.52  4999.6  407.02
  5003.1  407.02  5003.4  407.52  5011.7  408.51  5019.6  410.73  5024.7  411.01
  5032.2  411.26  5052.8  411.04    5062  411.22  5067.2  411.91  5085.9  411.93
  5154.1  413.34  5164.1  413.82  5174.1  413.91  5234.2  415.95  5263.4  417.37
#Mann= 3 ,-1 , 0
  4841.4     .05       0  4999.4     .05       0  5003.4     .05       0
Bank Sta=4999.4,5003.4
XS Rating Curve= 0 ,0
Exp/Cntr=0.3,0.1

Type RM Length L Ch R = 1 ,1967    ,109,109,109
BEGIN DESCRIPTION:
Lacy 141 1028
END DESCRIPTION:
XS GIS Cut Line= 3
      2722707.99      6855233.15      2722818.27      6855320.12
      2723106.57      6855329.43
#Sta/Elev= 30
  4861.4  415.12    4872  414.17  4880.1  414.02  4886.4  413.11  4894.5   413.2
  4900.9  412.61  4908.9  412.52  4915.3  411.75  4929.8  411.38  4950.6  410.29
  4958.6  409.52  4979.5  409.08  4991.9  406.34  4992.1  405.84  4995.6  405.84
  4995.9  406.34  5019.6  407.51  5039.6  407.47  5049.6  408.44  5069.6  408.31
  5079.6  408.49  5089.6  409.25  5109.6  409.25  5129.6  410.35  5139.6   409.7
  5159.7  411.14  5184.4  411.46  5199.7   412.6  5219.7  413.51  5290.3  415.67
#Mann= 3 ,-1 , 0
  4861.4     .05       0  4991.9     .04       0  4995.9     .05       0
Bank Sta=4991.9,4995.9
XS Rating Curve= 0 ,0
Exp/Cntr=0.3,0.1

Type RM Length L Ch R = 1 ,1858    ,89,89,89
BEGIN DESCRIPTION:
Lacy 141 1027
END DESCRIPTION:
XS GIS Cut Line= 3
      2722653.67      6855247.45      2722750.02      6855413.34
      2723035.07      6855421.28
#Sta/Elev= 30
  4860.3  413.41  4865.2  413.41  4872.5  412.67  4878.3  412.84  4894.1  411.13
  4915.6  410.85  4945.4  409.29  4952.8  408.18  4958.6  408.62  4968.5   407.6
  4990.1  407.25  5011.6  405.54  5015.4  404.33  5015.6  403.83  5019.1  403.83
  5019.4  404.33  5026.3  405.45  5033.1  405.68  5043.2  405.18  5052.1  404.94
  5068.1  406.05  5080.9  406.06  5098.1  406.14  5108.1  408.96  5145.4   410.1
  5168.2  412.26  5178.2  412.46  5198.2  411.61  5238.2  413.25  5337.3  414.19
#Mann= 5 ,-1 , 0
  4860.3     .05       0  5015.4     .04       0  5019.4     .05       0
  5043.2     .12       0  5080.9     .05       0
Bank Sta=5015.4,5019.4
XS Rating Curve= 0 ,0
Exp/Cntr=0.3,0.1

Type RM Length L Ch R = 1 ,1769    ,129,129,129
BEGIN DESCRIPTION:
Lacy 141 1024
END DESCRIPTION:
XS GIS Cut Line= 3
      2722595.04      6855257.72      2722649.77       6855414.9
      2722725.41      6855572.56
#Sta/Elev= 30
  4836.4  412.66  4840.8  412.66  4849.8  411.86  4855.1  411.75    4861  410.94
  4880.9  409.81  4886.2  409.99  4903.4  409.12    4912  408.23  4917.3  408.66
  4924.6  407.66  4935.2  407.71  4943.1  406.65  4948.4  406.88  4956.3  405.71
  4966.9  405.29  4970.8  404.55  4977.5  403.31  4977.7  402.81  4981.2  402.81
  4981.5  403.31  5002.8  404.09  5004.9   404.4  5010.4  407.19  5020.7  407.32
  5027.5  406.07  5033.1  406.78  5042.9  406.43  5052.7  406.72  5177.7  413.31
#Mann= 5 ,-1 , 0
  4836.4     .05       0  4970.8     .12       0  4977.5     .07       0
  4981.5     .12       0  5052.7     .05       0
Bank Sta=4977.5,4981.5
XS Rating Curve= 0 ,0
Exp/Cntr=0.3,0.1

Type RM Length L Ch R = 1 ,1640    ,121,121,121
BEGIN DESCRIPTION:
Lacy 141 1025
END DESCRIPTION:
XS GIS Cut Line= 3
      2722566.97      6855281.75      2722573.91      6855504.06
      2722610.37      6855667.94
#Sta/Elev= 30
  4779.1  411.21  4798.4  409.97  4828.4  408.72  4838.4   406.8  4848.4  407.89
  4858.4  407.91  4868.4  407.37  4898.4  406.68  4905.9  406.03  4910.9  406.61
  4928.4  405.88  4958.4  405.65  4968.4  404.16  4976.4   401.3  4976.7   400.8
  4980.2   400.8  4980.4   401.3  4988.4  402.92  4998.8   401.9  5001.5   401.9
  5018.9  405.98  5029.1  407.25  5034.2  407.47  5039.4  408.74  5059.8   409.6
  5111.1  412.75  5126.4  413.33  5131.6  414.09    5152  414.99  5169.4   416.5
#Mann= 5 ,-1 , 0
  4779.1     .05       0  4868.4     .12       0  4976.4     .04       0
  4980.4     .12       0  4998.8     .05       0
Bank Sta=4976.4,4980.4
XS Rating Curve= 0 ,0
Exp/Cntr=0.3,0.1

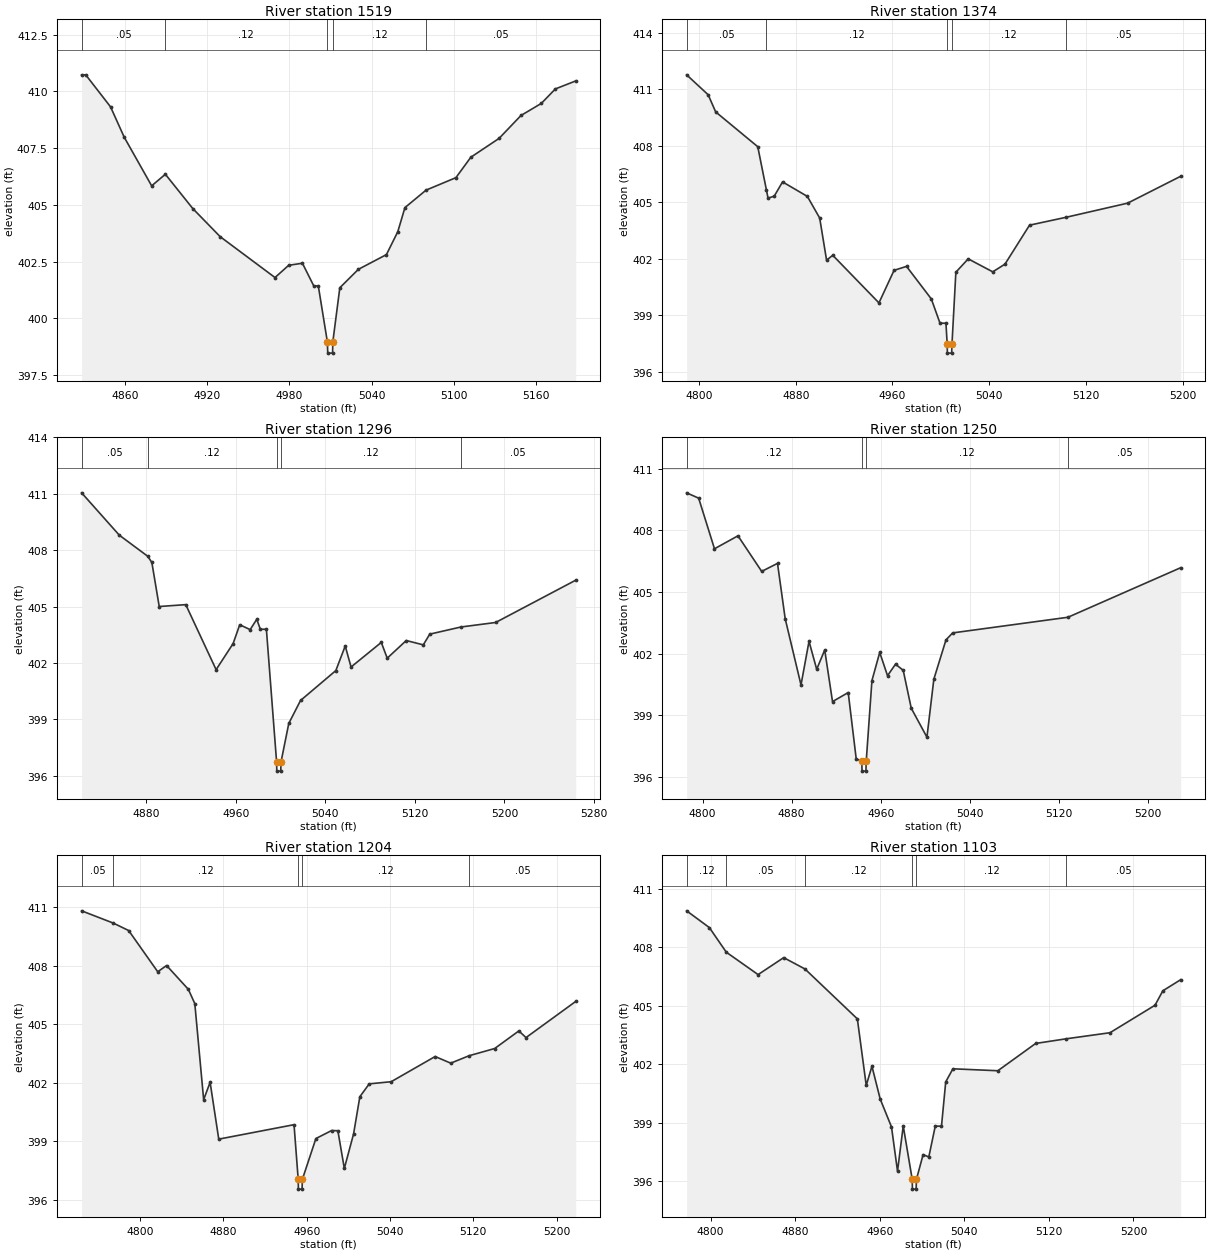
Type RM Length L Ch R = 1 ,1519    ,145,145,145
BEGIN DESCRIPTION:
Lacy 141 1026
END DESCRIPTION:
XS GIS Cut Line= 3
      2722468.76      6855289.93      2722466.95       6855462.6
      2722510.04      6855645.41
#Sta/Elev= 30
  4828.4  410.73  4831.4  410.73  4849.5  409.32  4859.5  407.98  4879.5  405.84
  4889.5  406.35  4909.5  404.84  4929.5   403.6  4969.5   401.8  4979.5  402.34
  4989.5  402.43  4997.8  401.43  5001.1  401.43  5007.7  398.97    5008  398.47
  5011.5  398.47  5011.7  398.97  5016.8  401.35  5030.3  402.16  5050.8  402.81
  5059.1  403.82  5064.3  404.88  5079.7  405.65  5101.5   406.2  5112.4   407.1
    5133  407.93    5149  408.94  5163.8  409.47  5174.1  410.11  5188.9  410.46
#Mann= 5 ,-1 , 0
  4828.4     .05       0  4889.5     .12       0  5007.7     .07       0
  5011.7     .12       0  5079.7     .05       0
Bank Sta=5007.7,5011.7
XS Rating Curve= 0 ,0
Exp/Cntr=0.3,0.1

Type RM Length L Ch R = 1 ,1374    ,78,78,78
BEGIN DESCRIPTION:
Lacy 141 1000
END DESCRIPTION:
XS GIS Cut Line= 3
      2722416.53      6855273.66      2722370.08      6855480.06
      2722402.31      6855674.35
#Sta/Elev= 30
  4789.8  411.77  4807.6  410.71  4813.8   409.8  4848.6  407.95  4855.8  405.64
  4857.1  405.22  4862.2  405.32  4869.1  406.08  4889.6  405.31  4899.8  404.16
  4905.5  401.92  4910.6  402.18  4948.8  399.65  4961.3  401.38  4971.6  401.59
  4992.1  399.86  4999.3  398.57  5004.2  398.57  5005.2  397.48  5005.4  396.98
  5008.9  396.98  5009.2  397.48  5012.4  401.28  5022.6  401.99  5042.9   401.3
    5053  401.71  5073.3  403.78  5103.6   404.2  5154.4  404.95  5198.3  406.38
#Mann= 5 ,-1 , 0
  4789.8     .05       0  4855.8     .12       0  5005.2     .07       0
  5009.2     .12       0  5103.6     .05       0
Bank Sta=5005.2,5009.2
XS Rating Curve= 0 ,0
Exp/Cntr=0.3,0.1

Type RM Length L Ch R = 1 ,1296    ,46,46,46
BEGIN DESCRIPTION:
Lacy 141 3449
END DESCRIPTION:
XS GIS Cut Line= 3
      2722404.62      6855282.76      2722317.49      6855417.87
      2722402.32      6855685.17
#Sta/Elev= 30
  4822.4  411.05    4856   408.8  4881.3  407.68  4885.1  407.35  4891.7     405
  4915.4   405.1  4942.5  401.64  4957.7  403.03  4963.6  404.03  4972.9  403.77
  4978.8  404.32    4982  403.79  4987.4  403.79  4996.5  396.74  4996.7  396.24
  5000.2  396.24  5000.5  396.74  5007.4  398.78  5017.9     400  5049.4  401.59
  5057.8   402.9    5063  401.78    5090  403.09  5095.3  402.25  5112.3  403.19
  5127.5  402.96  5133.3  403.53  5161.1  403.91  5192.1  404.15  5263.6   406.4
#Mann= 5 ,-1 , 0
  4822.4     .05       0  4881.3     .12       0  4996.5     .07       0
  5000.5     .12       0  5161.1     .05       0
Bank Sta=4996.5,5000.5
XS Rating Curve= 0 ,0
Exp/Cntr=0.3,0.1

Type RM Length L Ch R = 1 ,1250    ,46,46,46
BEGIN DESCRIPTION:
Lacy 141 3448
END DESCRIPTION:
XS GIS Cut Line= 3
      2722156.35      6855325.45      2722312.03      6855475.93
      2722400.56      6855685.14
#Sta/Elev= 30
  4785.7  409.82  4796.5  409.56  4810.7   407.1  4831.8  407.73  4853.1     406
  4867.3  406.39  4874.2   403.7  4888.4  400.48  4895.6   402.6  4902.5  401.24
  4909.7  402.18  4916.7  399.67  4930.8  400.11    4938  396.88    4943  396.79
  4943.2  396.29  4946.7  396.29    4947  396.79  4952.1  400.69  4959.1  402.06
  4966.1  400.93  4973.3  401.49  4980.2  401.19  4987.4  399.35  5001.5  397.94
  5007.7  400.76  5018.6  402.67  5024.6  403.01  5128.1  403.77  5229.4  406.18
#Mann= 4 ,-1 , 0
  4785.7     .12       0    4943     .07       0    4947     .12       0
  5128.1     .05       0
Bank Sta=4943,4947
XS Rating Curve= 0 ,0
Exp/Cntr=0.3,0.1

Type RM Length L Ch R = 1 ,1204    ,101,101,101
BEGIN DESCRIPTION:
Lacy 141 999
END DESCRIPTION:
XS GIS Cut Line= 3
      2722129.83      6855294.39      2722223.46      6855423.52
      2722396.71       6855686.6
#Sta/Elev= 30
  4743.9  410.81  4774.4  410.18  4789.1   409.8    4817  407.69  4825.5  408.01
  4846.4  406.79  4852.6  406.06  4861.1  401.14  4867.3  402.03  4875.6  399.12
  4947.9  399.86  4951.9  397.06  4952.1  396.56  4955.6  396.56  4955.9  397.06
  4968.9  399.15    4984  399.56    4990  399.55  4996.2  397.62  5005.1  399.39
  5011.1  401.29  5020.1  401.95  5041.2  402.06  5083.4  403.35  5098.4  403.01
    5116  403.39  5140.6  403.76  5163.8  404.66  5170.7  404.32  5218.4  406.17
#Mann= 5 ,-1 , 0
  4743.9     .05       0  4774.4     .12       0  4951.9     .07       0
  4955.9     .12       0    5116     .05       0
Bank Sta=4951.9,4955.9
XS Rating Curve= 0 ,0
Exp/Cntr=0.3,0.1

Type RM Length L Ch R = 1 ,1103    ,205,205,205
BEGIN DESCRIPTION:
Lacy 141 998
END DESCRIPTION:
XS GIS Cut Line= 3
      2722006.05      6855461.73      2722227.84      6855550.56
      2722396.69      6855704.49
#Sta/Elev= 30
  4777.3  409.86  4798.8     409  4814.8  407.74  4844.9  406.59  4869.1  407.46
  4889.2  406.88  4938.8  404.32  4947.2  400.91  4952.6  401.89  4960.4  400.21
  4971.1  398.78  4976.8  396.51  4982.2  398.83  4990.7  396.09  4990.9  395.59
  4994.4  395.59  4994.7  396.09    5001  397.36  5006.4  397.24  5012.5  398.82
  5018.4  398.82  5022.4  401.09  5029.2  401.76  5071.7  401.66  5107.5  403.06
  5136.6   403.3  5177.8  403.61  5220.4  405.02  5227.8  405.76  5244.7  406.33
#Mann= 6 ,-1 , 0
  4777.3     .12       0  4814.8     .05       0  4889.2     .12       0
  4990.7     .07       0  4994.7     .12       0  5136.6     .05       0
Bank Sta=4990.7,4994.7
XS Rating Curve= 0 ,0
Exp/Cntr=0.3,0.1

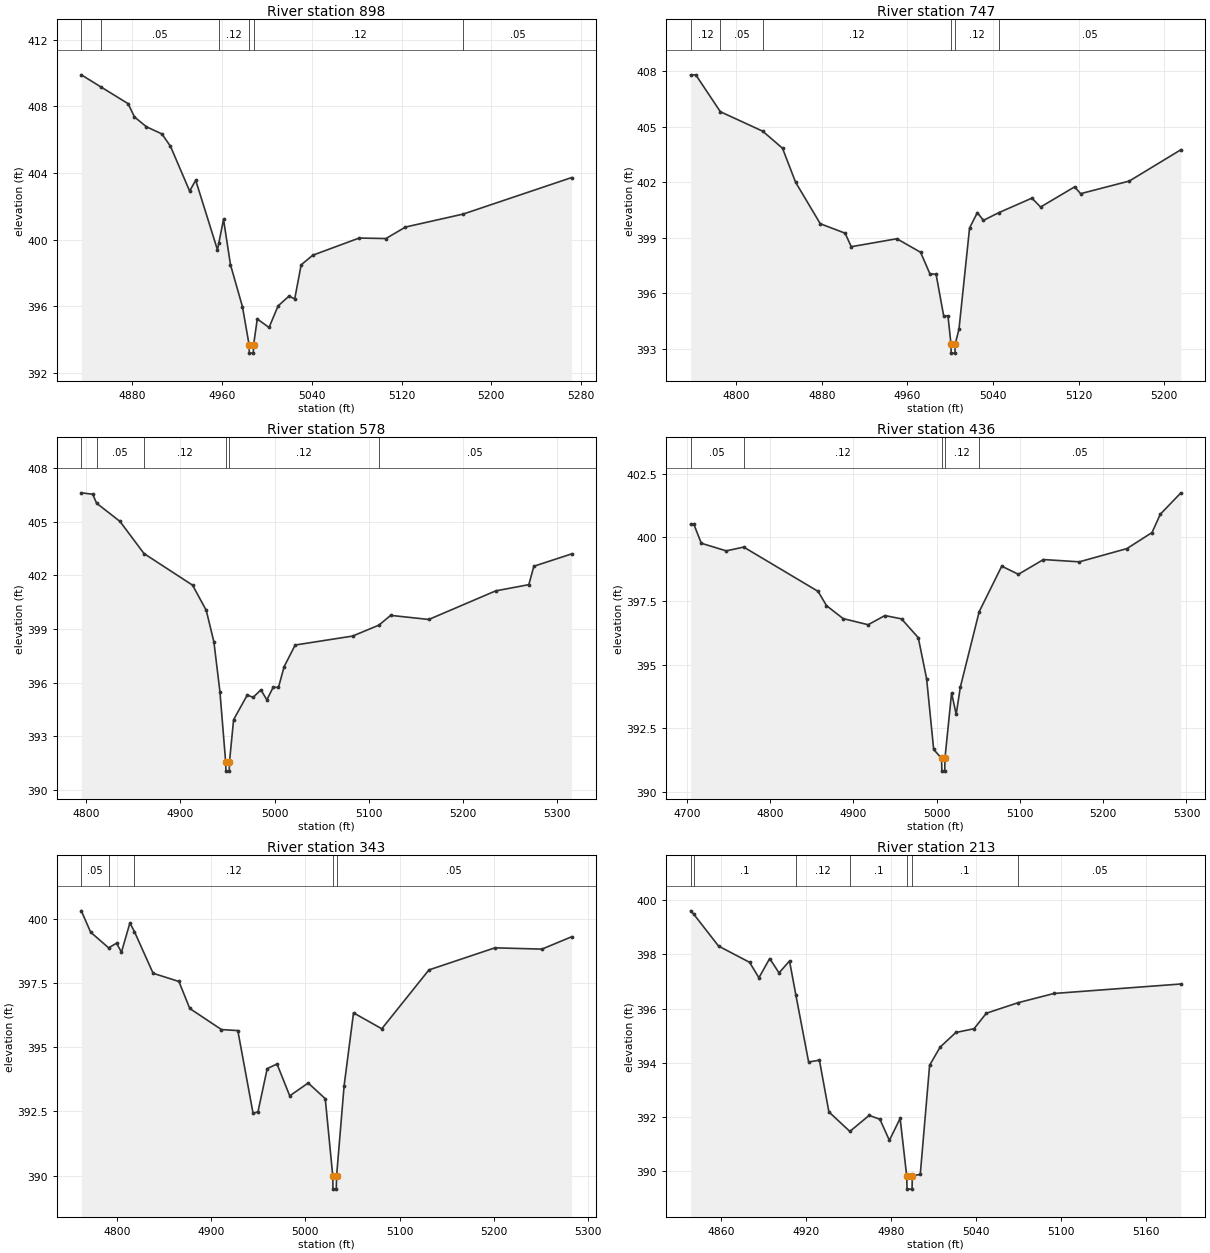
Type RM Length L Ch R = 1 ,898     ,151,151,151
BEGIN DESCRIPTION:
Lacy 141 997
END DESCRIPTION:
XS GIS Cut Line= 3
      2721921.66      6855621.34      2722075.62      6855679.73
       2722339.4      6855747.88
#Sta/Elev= 30
  4834.4   409.9  4852.2  409.16  4876.1  408.17  4881.8  407.37  4892.5  406.78
  4906.3  406.35  4913.9  405.61    4931  402.92  4936.4  403.57  4955.8  399.39
  4957.1  399.83  4961.2  401.22  4967.4   398.5  4978.1  395.97    4984  393.69
  4984.2  393.19  4987.7  393.19    4988  393.69  4991.3  395.24  5001.8  394.73
  5009.8  396.02  5019.5  396.61  5024.7  396.45  5030.4  398.49  5040.8  399.07
  5082.1   400.1    5106  400.07  5123.4  400.76  5174.9  401.54  5271.5  403.73
#Mann= 6 ,-1 , 0
  4834.4     .12       0  4852.2     .05       0  4957.1     .12       0
    4984     .07       0    4988     .12       0  5174.9     .05       0
Bank Sta=4984,4988
XS Rating Curve= 0 ,0
Exp/Cntr=0.3,0.1

Type RM Length L Ch R = 1 ,747     ,169,169,169
BEGIN DESCRIPTION:
Lacy 141 995
END DESCRIPTION:
XS GIS Cut Line= 3
      2721912.77      6855687.48      2722117.76      6855813.41
      2722314.59      6855906.72
#Sta/Elev= 30
  4757.3  407.79  4762.1  407.79  4785.1   405.8  4824.7  404.75  4843.2  403.83
  4855.4     402  4878.5  399.76  4901.7  399.25  4907.5  398.52  4950.1  398.95
  4972.3  398.22    4981  397.06  4986.8  397.03  4993.9  394.79  4997.9  394.79
  5000.7  393.28  5000.9  392.78  5004.4  392.78  5004.7  393.28  5008.2  394.07
  5018.1  399.53  5025.4  400.36    5031  399.94  5045.6  400.36  5076.4  401.14
  5084.5  400.66  5116.4  401.75  5121.9  401.38  5167.4  402.06  5215.7  403.75
#Mann= 6 ,-1 , 0
  4757.3     .12       0  4785.1     .05       0  4824.7     .12       0
  5000.7     .07       0  5004.7     .12       0  5045.6     .05       0
Bank Sta=5000.7,5004.7
XS Rating Curve= 0 ,0
Exp/Cntr=0.3,0.1

Type RM Length L Ch R = 1 ,578     ,142,142,142
BEGIN DESCRIPTION:
Lacy 141 996
END DESCRIPTION:
XS GIS Cut Line= 3
      2721822.63      6855777.72      2721986.01      6855904.11
      2722295.49      6855953.14
#Sta/Elev= 30
  4795.1  406.62  4807.2  406.54  4811.3  406.04  4836.1  405.02  4861.6  403.22
  4913.1  401.45  4927.6  400.04  4935.7  398.28  4942.1  395.49  4948.2  391.54
  4948.5  391.04    4952  391.04  4952.2  391.54  4956.6  393.92  4971.1   395.3
  4977.4  395.17  4985.5  395.59  4991.9  395.03  4998.5  395.73  5004.2  395.73
  5010.2  396.89  5021.9   398.1  5082.7   398.6  5110.6  399.21  5123.2  399.76
  5163.6  399.53  5234.5  401.13  5269.7  401.48    5275  402.51    5315   403.2
#Mann= 6 ,-1 , 0
  4795.1     .12       0  4811.3     .05       0  4861.6     .12       0
  4948.2     .07       0  4952.2     .12       0  5110.6     .05       0
Bank Sta=4948.2,4952.2
XS Rating Curve= 0 ,0
Exp/Cntr=0.3,0.1

Type RM Length L Ch R = 1 ,436     ,93,93,93
BEGIN DESCRIPTION:
Lacy 141 1017
END DESCRIPTION:
XS GIS Cut Line= 3
      2721673.25      6855996.37        2721968.      6856014.35
      2722260.61      6856034.55
#Sta/Elev= 30
  4704.7  400.51  4708.6  400.51  4717.5  399.77  4747.5  399.47  4768.4  399.62
  4857.7  397.88  4867.8  397.32  4887.8  396.81  4917.8  396.57  4937.9  396.93
  4957.9   396.8    4978  396.06    4988  394.45  4996.5  391.67    5006  391.32
  5006.3  390.82  5009.8  390.82    5010  391.32    5018  393.89  5023.5  393.05
  5028.5  394.12  5051.1  397.08  5078.2  398.87  5098.2  398.55  5128.3  399.13
  5171.3  399.04  5228.5  399.56  5258.6  400.19  5268.6  400.91  5293.3  401.75
#Mann= 5 ,-1 , 0
  4704.7     .05       0  4768.4     .12       0    5006     .07       0
    5010     .12       0  5051.1     .05       0
Bank Sta=5006,5010
XS Rating Curve= 0 ,0
Exp/Cntr=0.3,0.1

Type RM Length L Ch R = 1 ,343     ,130,130,130
BEGIN DESCRIPTION:
Lacy 141 1015
END DESCRIPTION:
XS GIS Cut Line= 3
      2721676.47      6856015.21      2721904.93      6856081.21
      2722187.42      6856079.01
#Sta/Elev= 30
  4762.2   400.3  4772.1  399.47  4791.2  398.86  4799.6  399.04  4804.8  398.69
  4813.8  399.83  4818.6  399.49  4838.4  397.87  4865.8  397.55  4877.3   396.5
  4910.9  395.68  4928.3  395.64  4944.5  392.42  4949.7  392.48  4959.5  394.16
  4969.9  394.34  4983.4   393.1    5003   393.6  5021.1  392.99  5029.1  389.97
  5029.3  389.47  5032.8  389.47  5033.1  389.97  5041.1  393.49  5051.1  396.33
  5081.1  395.71  5131.1     398  5201.1  398.86  5251.1  398.81  5282.5  399.29
#Mann= 5 ,-1 , 0
  4762.2     .05       0  4791.2      .1       0  4818.6     .12       0
  5029.1     .07       0  5033.1     .05       0
Bank Sta=5029.1,5033.1
XS Rating Curve= 0 ,0
Exp/Cntr=0.3,0.1

Type RM Length L Ch R = 1 ,213     ,72,72,72
BEGIN DESCRIPTION:
Lacy 141 1014
END DESCRIPTION:
XS GIS Cut Line= 3
      2721673.51      6856035.31      2721817.36      6856161.28
      2721968.25      6856196.28
#Sta/Elev= 30
  4838.6  399.61  4840.9  399.48  4858.3  398.31  4880.2  397.71  4886.8  397.14
  4894.4  397.85    4901  397.32  4908.4  397.76  4912.9   396.5  4921.9  394.03
  4929.5   394.1  4936.2  392.19    4951  391.47  4964.6  392.06  4972.2  391.92
  4978.9  391.14  4986.5  391.95  4991.1  389.84  4991.4  389.34  4994.9  389.34
  4995.1  389.84  5000.7  389.88  5007.3  393.91  5014.7  394.58  5025.8  395.12
  5038.7  395.26  5047.3  395.83  5069.8  396.22  5095.1  396.56  5184.7  396.91
#Mann= 7 ,-1 , 0
  4838.6     .05       0  4840.9      .1       0  4912.9     .12       0
    4951      .1       0  4991.1     .07       0  4995.1      .1       0
  5069.8     .05       0
Bank Sta=4991.1,4995.1
XS Rating Curve= 0 ,0
Exp/Cntr=0.3,0.1

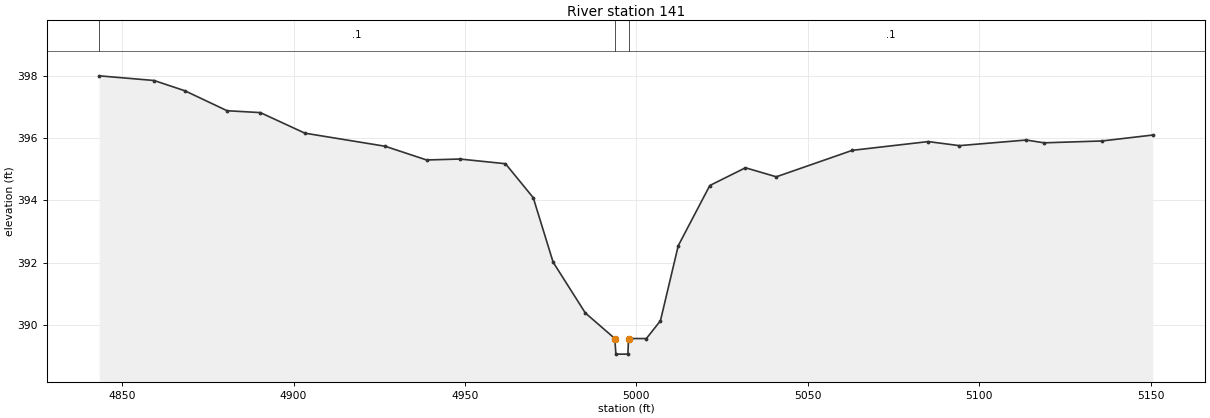
Type RM Length L Ch R = 1 ,141     ,0,0,0
BEGIN DESCRIPTION:
Lacy 141 1016
END DESCRIPTION:
XS GIS Cut Line= 3
      2721664.38      6856059.61       2721745.4      6856193.73
      2721890.21      6856235.09
#Sta/Elev= 30
  4843.3     398  4859.3  397.85  4868.3  397.52  4880.6  396.88  4890.3  396.82
  4903.3  396.16  4926.7  395.74  4938.8   395.3  4948.5  395.33  4961.8  395.18
  4969.9  394.09  4975.7  392.02  4985.1  390.39  4993.7  389.57    4994  389.07
  4997.5  389.07  4997.7  389.57  5002.9  389.57    5007  390.14  5012.2  392.55
  5021.4  394.48  5031.8  395.05  5040.8  394.76    5063  395.61  5085.1  395.89
  5094.2  395.76  5113.7  395.94  5118.9  395.85  5135.8  395.91  5150.6   396.1
#Mann= 3 ,-1 , 0
  4843.3      .1       0  4993.7     .07       0  4997.7      .1       0
Bank Sta=4993.7,4997.7
XS Rating Curve= 0 ,0
Exp/Cntr=0.3,0.1

Chan Stop Cuts=-1
Use User Specified Reach Order=0
Composite Channel Slope=5