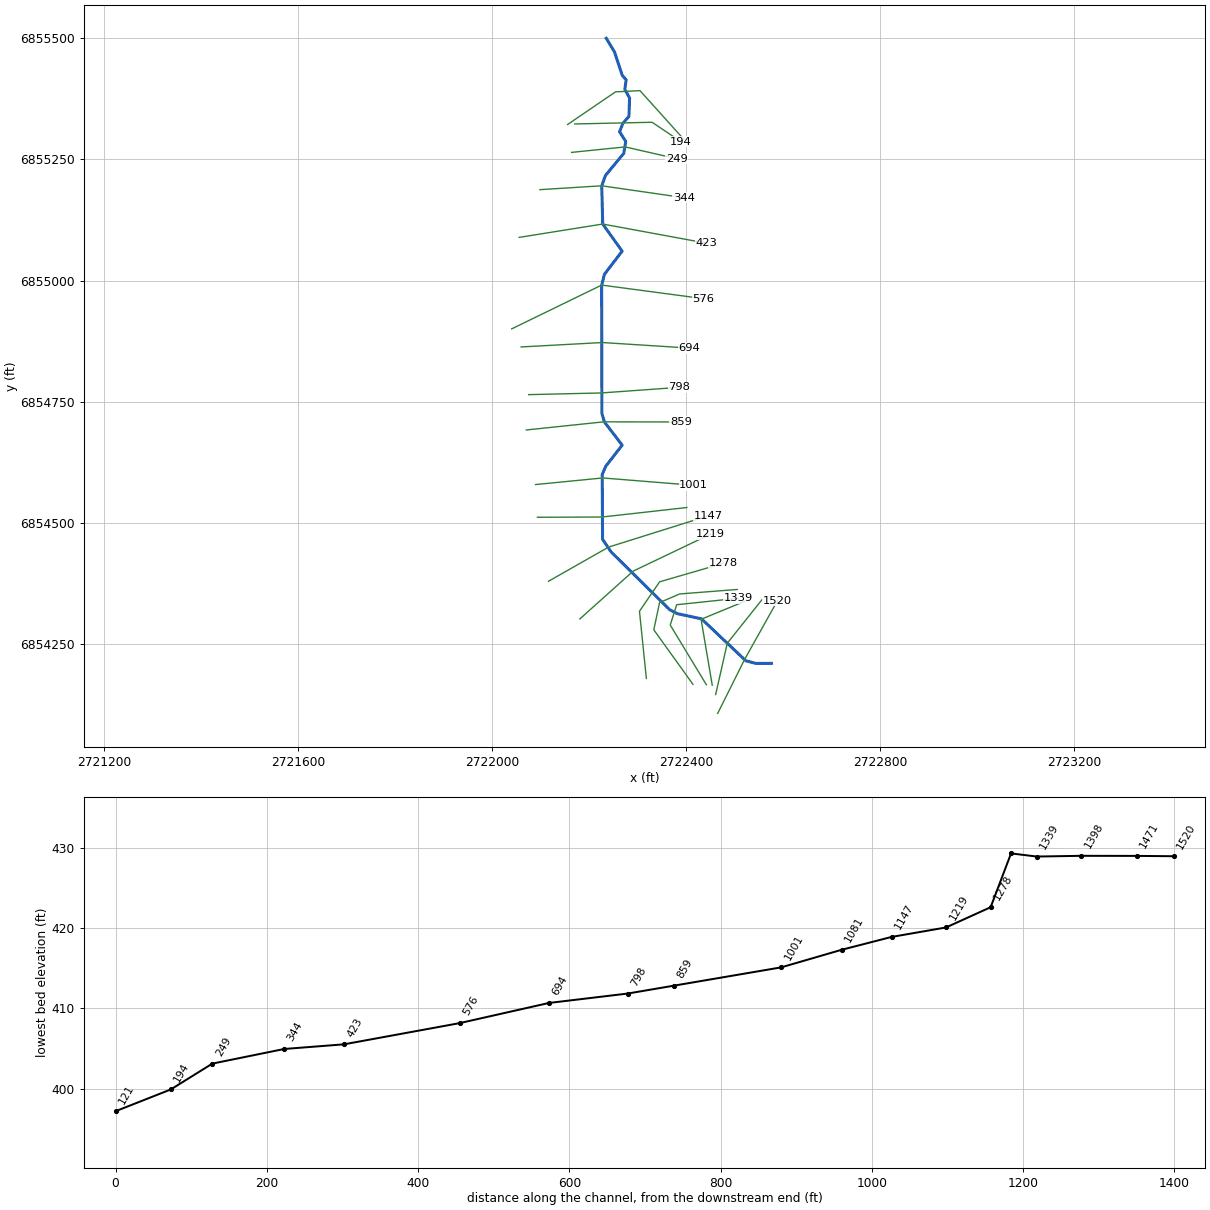
--- Lacy 142.prj (project) ---

Proj Title=Lacy 142 Base Level Engineering
Current Plan=p01
Default Exp/Contr=0.3,0.1
English Units
Geom File=g01
Flow File=f01
Plan File=p01
BEGIN DESCRIPTION:
Lacy 142
END DESCRIPTION:

--- Lacy 142.p01 (plan) ---

Plan Title=Multiple Run
Short Identifier=Multiple
Geom File=g01
Flow File=f01
Subcritical Flow
K Sum by GR= 0
Std Step Tol= 0.01
Critical Tol= 0.01
Num of Std Step Trials= 20
Max Error Tol= 0.3
Flow Tol Ratio= 0.001
Split Flow NTrial= 30
Split Flow Tol= 0.02
Split Flow Ratio= 0.02
Log Output Level= 0
Friction Slope Method= 1
Unsteady Friction Slope Method= 2
Unsteady Bridges Friction Slope Method= 1
Parabolic Critical Depth
Global Vel Dist=  1 , 1 , 1
Global Log Level= 0
CheckData=True
Encroach Param= -1, 0, 0, 0
BEGIN DESCRIPTION:
Multiple Run
END DESCRIPTION:

--- Lacy 142.f01 (steady flow) ---

Flow Title=Multiple
Number of Profiles=7
Profile Names=10-year,25-year,50-year,1pct_min,100-year,1pct_plu,500-year
River Rch & RM= Lacy 142,Reach-1,1520
     104     124     138      77     154     308     190
Boundary for River Rch & Prof#=Lacy 142,Reach-1,1
Up Type=0
Dn Type=3
Dn Slope=0.005
Boundary for River Rch & Prof#=Lacy 142,Reach-1,2
Up Type=0
Dn Type=3
Dn Slope=0.005
Boundary for River Rch & Prof#=Lacy 142,Reach-1,3
Up Type=0
Dn Type=3
Dn Slope=0.005
Boundary for River Rch & Prof#=Lacy 142,Reach-1,4
Up Type=0
Dn Type=3
Dn Slope=0.005
Boundary for River Rch & Prof#=Lacy 142,Reach-1,5
Up Type=0
Dn Type=3
Dn Slope=0.005
Boundary for River Rch & Prof#=Lacy 142,Reach-1,6
Up Type=0
Dn Type=3
Dn Slope=0.005
Boundary for River Rch & Prof#=Lacy 142,Reach-1,7
Up Type=0
Dn Type=3
Dn Slope=0.005

--- Lacy 142.g01 (geometry) ---

Geom Title=Existing Conditions

River Reach=Lacy 142,Reach-1
Reach XY= 30
      2722576.00      6854211.00      2722544.12      6854210.93
      2722523.49      6854216.33      2722432.05      6854302.84
      2722382.05      6854313.53      2722366.32      6854321.78
      2722245.60      6854440.84      2722228.05      6854466.86
      2722227.37      6854600.56      2722234.45      6854617.18
      2722268.44      6854661.00      2722232.02      6854708.55
      2722226.66      6854726.16      2722226.18      6854991.02
      2722232.02      6855013.45      2722268.44      6855061.00
      2722228.36      6855116.89      2722226.37      6855195.73
      2722234.05      6855217.05      2722271.84      6855262.74
      2722275.88      6855287.07      2722263.11      6855307.22
      2722269.97      6855324.52      2722282.43      6855338.86
      2722283.75      6855376.82      2722273.93      6855394.51
      2722276.72      6855414.06      2722268.56      6855423.74
      2722252.46      6855472.20      2722235.70      6855499.79

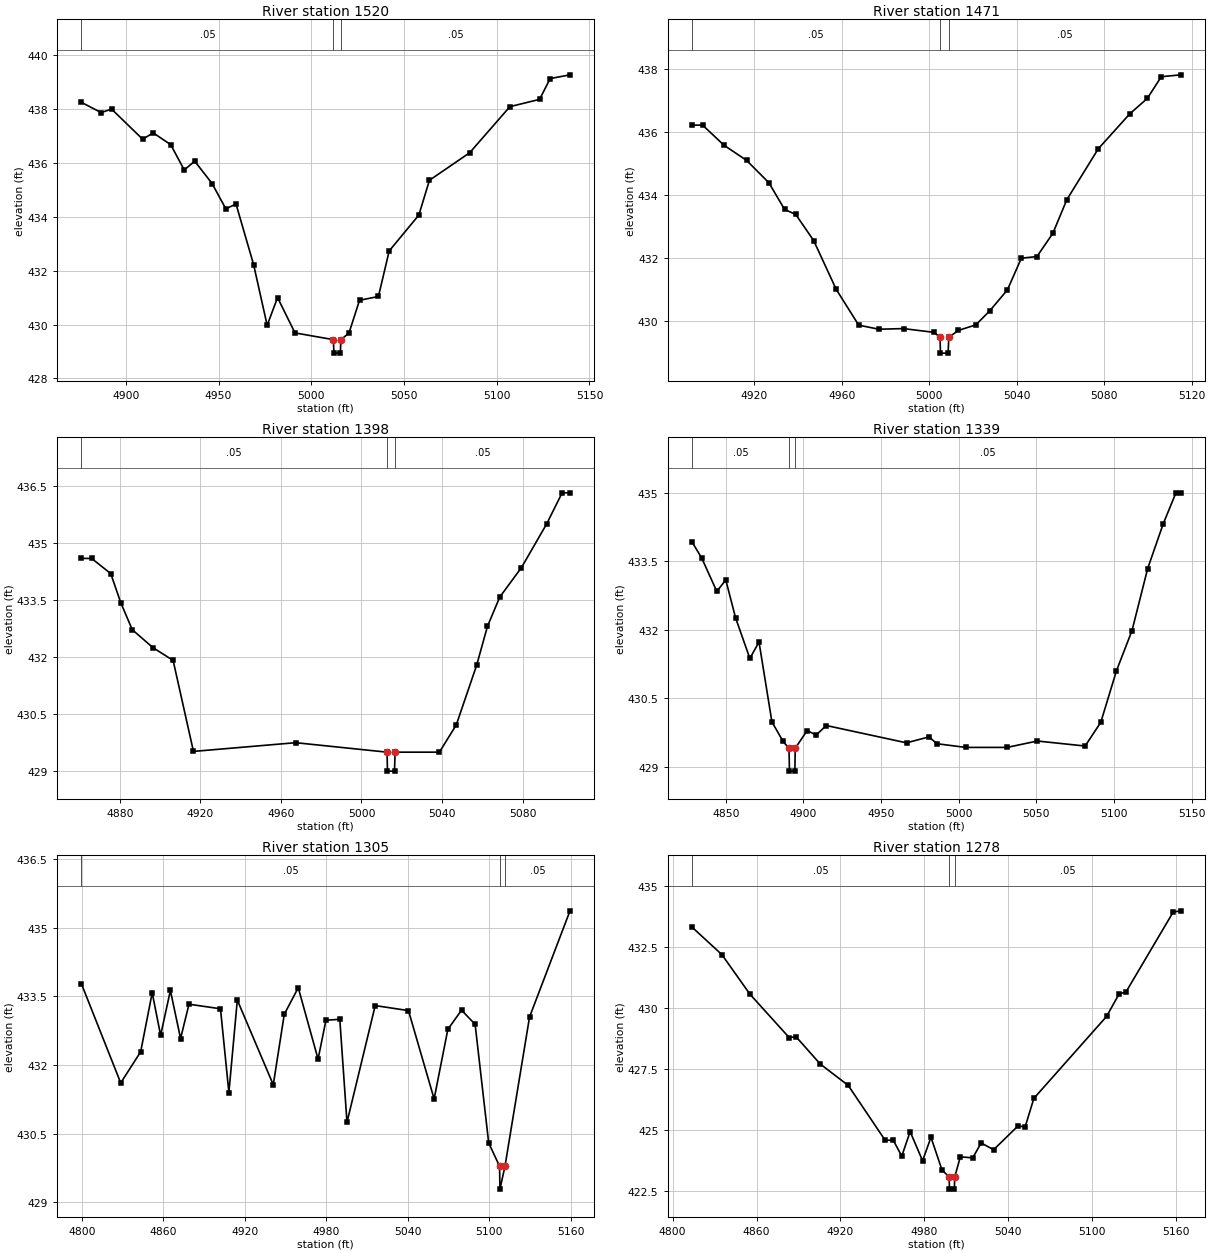
Type RM Length L Ch R = 1,1520,49,49,49
BEGIN DESCRIPTION:
Lacy 142 1005
END DESCRIPTION:
XS GIS Cut Line= 3
      2722465.44      6854107.90      2722521.20      6854219.59
      2722588.86      6854340.63
#Sta/Elev= 30
  4876.0  438.24  4886.7  437.86  4892.3  437.99  4909.1  436.87  4914.7  437.11
  4924.2  436.67  4931.5  435.73  4937.1  436.06  4946.5  435.23  4953.9  434.29
  4959.4  434.47  4968.9  432.22  4976.2  429.97  4981.8  431.00  4991.2  429.69
  5011.9  429.44  5012.2  428.94  5015.7  428.94  5015.9  429.44  5020.3  429.68
  5026.0  430.90  5036.2  431.04  5042.0  432.73  5058.0  434.06  5063.7  435.35
  5085.4  436.37  5107.1  438.08  5123.1  438.35  5128.8  439.12  5139.5  439.26
#Mann=3,-1,0
  4876.0    0.05       0  5011.9    0.04       0  5015.9    0.05       0
Bank Sta=5011.9,5015.9
Exp/Cntr=0.3,0.1

Type RM Length L Ch R = 1,1471,73,73,73
BEGIN DESCRIPTION:
Lacy 142 1009
END DESCRIPTION:
XS GIS Cut Line= 3
      2722461.22      6854146.73      2722485.20      6854252.52
      2722556.87      6854342.49
#Sta/Elev= 30
  4891.5  436.23  4896.3  436.23  4906.1  435.59  4916.4  435.11  4926.6  434.40
  4933.8  433.55  4938.9  433.39  4947.1  432.56  4957.4  431.01  4967.7  429.87
  4976.9  429.74  4988.2  429.76  5002.2  429.64  5004.9  429.48  5005.1  428.98
  5008.6  428.98  5008.9  429.48  5013.2  429.70  5021.3  429.88  5027.7  430.33
  5035.7  430.99  5042.1  432.00  5049.2  432.05  5056.5  432.79  5062.9  433.86
  5077.3  435.48  5091.7  436.59  5099.7  437.08  5106.1  437.77  5115.0  437.83
#Mann=3,-1,0
  4891.5    0.05       0  5004.9    0.04       0  5008.9    0.05       0
Bank Sta=5004.9,5008.9
Exp/Cntr=0.3,0.1

Type RM Length L Ch R = 1,1398,59,59,59
BEGIN DESCRIPTION:
Lacy 142 1008
END DESCRIPTION:
XS GIS Cut Line= 3
      2722454.18      6854166.03      2722431.18      6854301.92
      2722528.28      6854341.84
#Sta/Elev= 22
  4860.8  434.60  4865.9  434.60  4875.4  434.20  4880.4  433.43  4886.1  432.72
  4896.3  432.25  4906.4  431.91  4916.5  429.51  4967.3  429.74  5012.7  429.49
  5012.9  428.99  5016.4  428.99  5016.7  429.49  5038.7  429.49  5047.1  430.21
  5057.2  431.78  5062.6  432.81  5068.7  433.58  5079.5  434.36  5092.0  435.51
  5099.7  436.33  5103.6  436.33
#Mann=3,-1,0
  4860.8    0.05       0  5012.7    0.04       0  5016.7    0.05       0
Bank Sta=5012.7,5016.7
Exp/Cntr=0.3,0.1

Type RM Length L Ch R = 1,1339,34,34,34
BEGIN DESCRIPTION:
Lacy 142 1007
END DESCRIPTION:
XS GIS Cut Line= 4
      2722442.04      6854167.07      2722367.58      6854290.05
      2722380.92      6854331.92      2722507.22      6854345.25
#Sta/Elev= 30
  4828.3  433.92  4834.5  433.57  4844.2  432.84  4850.0  433.09  4856.3  432.26
  4865.5  431.37  4871.4  431.73  4879.7  429.98  4886.9  429.55  4890.7  429.40
  4891.0  428.90  4894.5  428.90  4894.7  429.40  4902.4  429.79  4908.2  429.69
  4914.7  429.90  4966.4  429.52  4980.8  429.65  4986.1  429.50  5004.5  429.42
  5031.2  429.42  5050.6  429.56  5081.4  429.45  5091.5  429.97  5101.6  431.10
  5111.6  431.98  5121.7  433.34  5131.7  434.32  5139.9  435.00  5143.0  435.00
#Mann=3,-1,0
  4828.3    0.05       0  4890.7    0.04       0  4894.7    0.05       0
Bank Sta=4890.7,4894.7
Exp/Cntr=0.3,0.1

Type RM Length L Ch R = 1,1305,27,27,27
BEGIN DESCRIPTION:
Lacy 142 1006
END DESCRIPTION:
XS GIS Cut Line= 5
      2722414.49      6854167.74      2722333.67      6854280.17
      2722345.58      6854336.29      2722387.02      6854354.14
      2722505.70      6854363.40
#Sta/Elev= 30
  4799.6  433.78  4828.6  431.61  4843.3  432.29  4851.8  433.58  4858.0  432.65
  4865.2  433.63  4872.7  432.58  4878.9  433.33  4902.1  433.23  4908.3  431.40
  4914.5  433.42  4941.0  431.57  4949.1  433.11  4959.4  433.69  4974.0  432.13
  4979.8  432.98  4990.0  433.00  4995.3  430.75  5016.1  433.30  5040.6  433.19
  5059.5  431.26  5069.6  432.78  5079.7  433.20  5089.7  432.89  5099.7  430.30
  5107.7  429.79  5108.0  429.29  5111.7  429.79  5129.8  433.05  5159.6  435.37
#Mann=3,-1,0
  4799.6    0.05       0  5107.7    0.04       0  5111.7    0.05       0
Bank Sta=5107.7,5111.7
Exp/Cntr=0.3,0.1

Type RM Length L Ch R = 1,1278,59,59,59
BEGIN DESCRIPTION:
Lacy 142 1010
END DESCRIPTION:
XS GIS Cut Line= 4
      2722318.38      6854179.85      2722304.15      6854318.44
      2722345.68      6854379.16      2722476.97      6854417.28
#Sta/Elev= 30
  4813.9  433.30  4835.2  432.18  4855.3  430.56  4883.3  428.79  4888.3  428.82
  4905.5  427.71  4925.6  426.83  4952.0  424.59  4957.8  424.59  4963.9  423.94
  4969.9  424.94  4978.8  423.75  4984.8  424.71  4992.7  423.37  4997.8  423.09
  4998.0  422.59  5001.5  422.59  5001.8  423.09  5005.8  423.91  5014.7  423.87
  5020.7  424.48  5029.6  424.20  5047.0  425.17  5052.2  425.14  5058.4  426.30
  5110.4  429.65  5119.3  430.56  5124.5  430.67  5158.1  433.92  5163.5  433.97
#Mann=3,-1,0
  4813.9    0.05       0  4997.8    0.04       0  5001.8    0.05       0
Bank Sta=4997.8,5001.8
Exp/Cntr=0.3,0.1

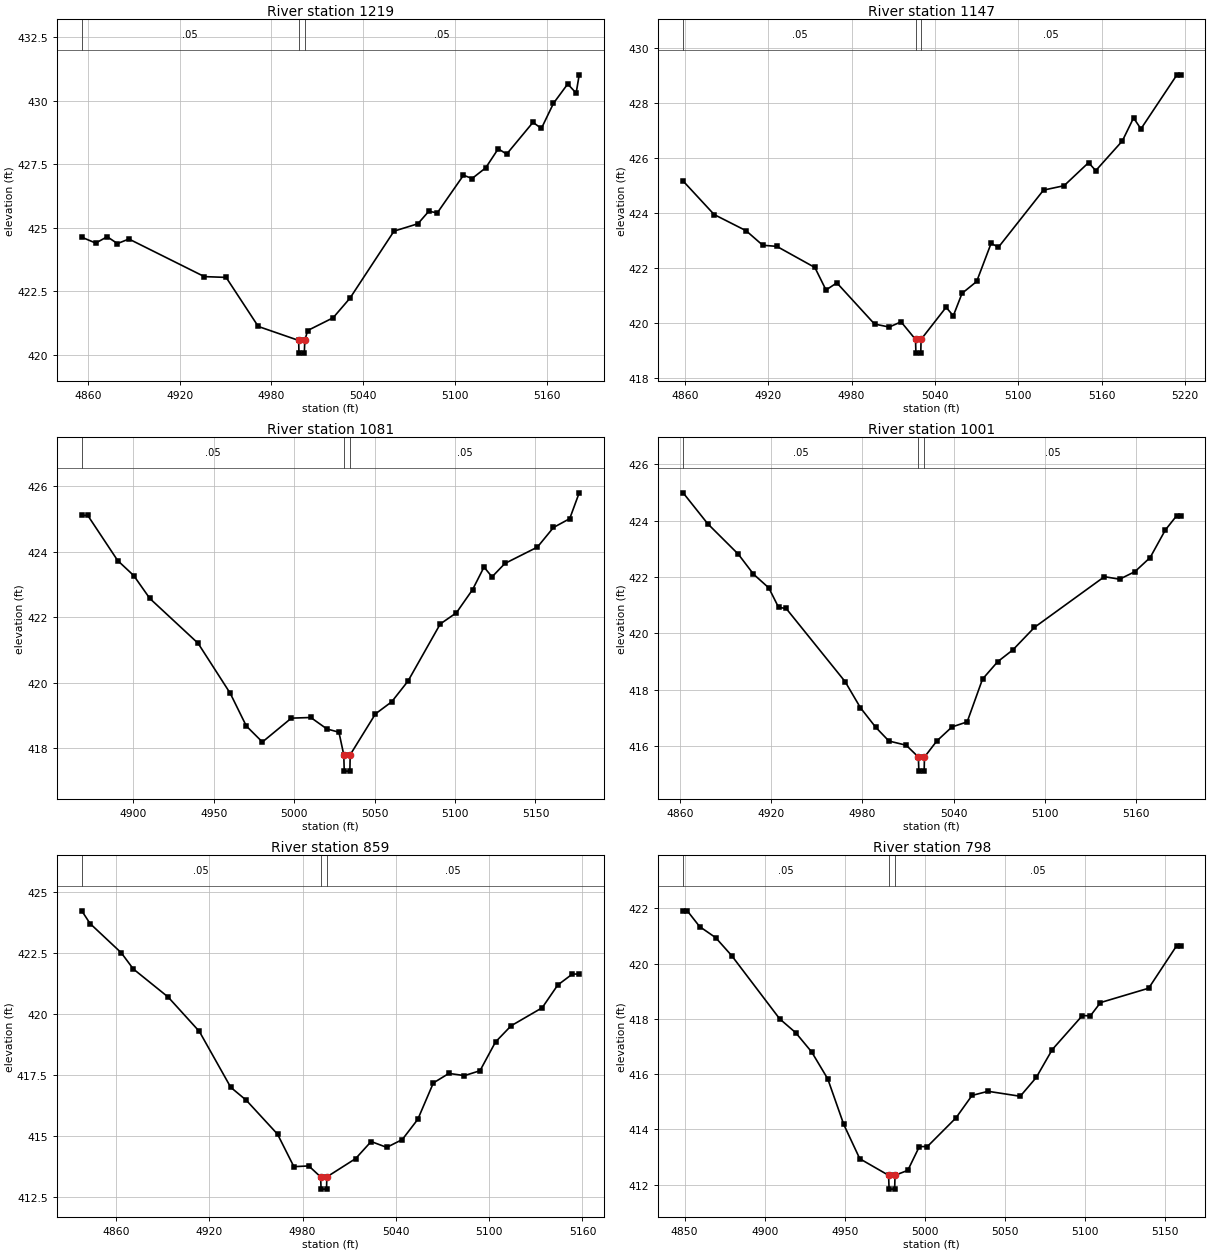
Type RM Length L Ch R = 1,1219,72,72,72
BEGIN DESCRIPTION:
Lacy 142 1011
END DESCRIPTION:
XS GIS Cut Line= 3
      2722181.20      6854302.62      2722291.21      6854401.27
      2722451.15      6854477.64
#Sta/Elev= 30
  4856.1  424.63  4865.2  424.40  4872.7  424.65  4879.4  424.38  4886.9  424.56
  4936.2  423.08  4950.4  423.05  4971.4  421.12  4997.8  420.57  4998.0  420.07
  5001.5  420.07  5001.8  420.57  5003.7  420.96  5020.3  421.46  5031.3  422.23
  5060.1  424.87  5075.7  425.16  5082.8  425.65  5088.4  425.59  5105.5  427.07
  5111.1  426.94  5120.0  427.36  5128.2  428.11  5133.7  427.90  5150.9  429.15
  5156.4  428.91  5164.3  429.90  5173.6  430.66  5179.1  430.30  5181.1  431.02
#Mann=3,-1,0
  4856.1    0.05       0  4997.8    0.04       0  5001.8    0.05       0
Bank Sta=4997.8,5001.8
Exp/Cntr=0.3,0.1

Type RM Length L Ch R = 1,1147,66,66,66
BEGIN DESCRIPTION:
Lacy 142 1012
END DESCRIPTION:
XS GIS Cut Line= 3
      2722116.59      6854380.33      2722240.49      6854450.74
      2722445.99      6854515.26
#Sta/Elev= 30
  4858.8  425.16  4881.1  423.94  4904.1  423.35  4916.1  422.82  4926.2  422.78
  4953.6  422.01  4961.6  421.19  4969.4  421.45  4996.5  419.95  5007.1  419.84
  5015.6  420.03  5026.0  419.39  5026.3  418.89  5029.8  418.89  5030.0  419.39
  5048.0  420.56  5053.2  420.25  5059.5  421.07  5070.0  421.50  5080.4  422.89
  5085.7  422.75  5118.1  424.83  5132.9  424.99  5150.5  425.83  5155.7  425.54
  5174.8  426.62  5182.9  427.46  5188.2  427.06  5214.1  429.03  5216.7  429.03
#Mann=3,-1,0
  4858.8    0.05       0  5026.0    0.04       0  5030.0    0.05       0
Bank Sta=5026,5030
Exp/Cntr=0.3,0.1

Type RM Length L Ch R = 1,1081,80,80,80
BEGIN DESCRIPTION:
Lacy 142 1013
END DESCRIPTION:
XS GIS Cut Line= 3
      2722093.68      6854512.27      2722226.94      6854512.77
      2722401.88      6854532.36
#Sta/Elev= 30
  4867.9  425.11  4871.6  425.11  4890.2  423.73  4900.2  423.27  4910.2  422.57
  4940.2  421.20  4960.2  419.67  4970.2  418.67  4980.2  418.18  4998.2  418.91
  5010.3  418.93  5020.3  418.58  5027.8  418.48  5030.8  417.79  5031.1  417.29
  5034.6  417.29  5034.8  417.79  5050.5  419.04  5060.6  419.41  5070.7  420.04
  5090.8  421.79  5100.8  422.13  5110.9  422.84  5118.0  423.53  5123.0  423.23
  5131.0  423.64  5151.2  424.14  5161.2  424.74  5171.3  425.01  5177.2  425.80
#Mann=3,-1,0
  4867.9    0.05       0  5030.8    0.04       0  5034.8    0.05       0
Bank Sta=5030.8,5034.8
Exp/Cntr=0.3,0.1

Type RM Length L Ch R = 1,1001,142,142,142
BEGIN DESCRIPTION:
Lacy 142 1004
END DESCRIPTION:
XS GIS Cut Line= 3
      2722089.90      6854579.72      2722228.37      6854593.33
      2722415.92      6854578.21
#Sta/Elev= 30
  4862.0  424.99  4878.2  423.89  4898.3  422.81  4908.3  422.10  4918.4  421.61
  4924.8  420.92  4929.8  420.88  4968.6  418.28  4978.7  417.35  4988.7  416.66
  4997.4  416.17  5008.8  416.02  5016.8  415.60  5017.1  415.10  5020.6  415.10
  5020.8  415.60  5028.9  416.17  5038.9  416.67  5048.9  416.85  5059.0  418.37
  5069.0  418.99  5079.0  419.41  5093.2  420.21  5139.2  422.01  5149.2  421.92
  5159.3  422.19  5169.3  422.69  5179.3  423.67  5186.8  424.18  5189.3  424.18
#Mann=3,-1,0
  4862.0    0.05       0  5016.8    0.04       0  5020.8    0.05       0
Bank Sta=5016.8,5020.8
Exp/Cntr=0.3,0.1

Type RM Length L Ch R = 1,859,61,61,61
BEGIN DESCRIPTION:
Lacy 142 1003
END DESCRIPTION:
XS GIS Cut Line= 3
      2722070.77      6854692.27      2722230.08      6854708.97
      2722389.79      6854708.79
#Sta/Elev= 30
  4838.0  424.22  4843.3  423.70  4863.4  422.50  4871.1  421.84  4893.5  420.69
  4913.6  419.28  4933.8  416.99  4943.8  416.46  4963.9  415.07  4974.4  413.74
  4984.0  413.77  4991.6  413.32  4991.9  412.82  4995.4  412.82  4995.6  413.32
  5014.1  414.07  5024.1  414.77  5034.1  414.53  5044.1  414.85  5054.1  415.68
  5064.1  417.17  5074.1  417.56  5084.1  417.47  5094.1  417.67  5104.1  418.85
  5114.1  419.51  5134.1  420.25  5144.1  421.18  5153.5  421.63  5157.9  421.63
#Mann=3,-1,0
  4838.0    0.05       0  4991.6    0.04       0  4995.6    0.05       0
Bank Sta=4991.6,4995.6
Exp/Cntr=0.3,0.1

Type RM Length L Ch R = 1,798,104,104,104
BEGIN DESCRIPTION:
Lacy 142 1002
END DESCRIPTION:
XS GIS Cut Line= 3
      2722075.72      6854765.12      2722225.39      6854768.60
      2722385.87      6854780.13
#Sta/Elev= 30
  4849.1  421.91  4851.7  421.91  4859.4  421.34  4869.4  420.94  4879.4  420.29
  4909.4  418.00  4919.4  417.50  4929.4  416.80  4939.4  415.83  4949.4  414.18
  4959.4  412.94  4977.4  412.34  4977.7  411.84  4981.2  411.84  4981.4  412.34
  4989.4  412.52  4996.6  413.38  5001.6  413.38  5019.5  414.42  5029.5  415.23
  5039.5  415.38  5059.6  415.20  5069.6  415.88  5079.6  416.89  5098.4  418.12
  5103.4  418.11  5109.7  418.59  5139.8  419.11  5157.3  420.65  5159.7  420.65
#Mann=3,-1,0
  4849.1    0.05       0  4977.4    0.04       0  4981.4    0.05       0
Bank Sta=4977.4,4981.4
Exp/Cntr=0.3,0.1

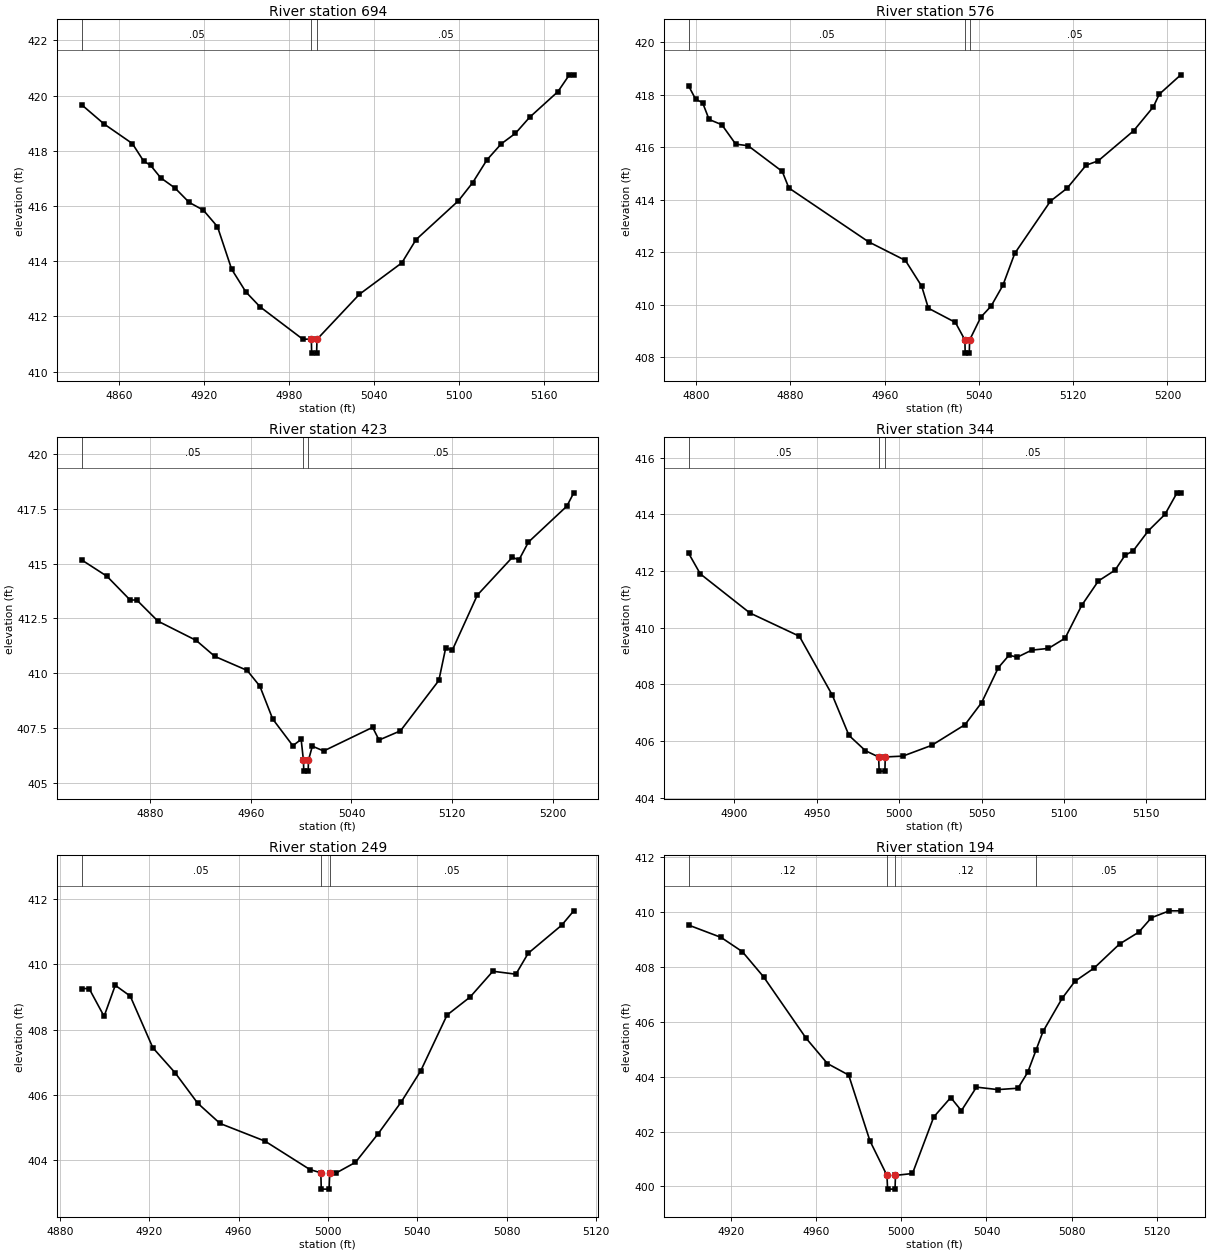
Type RM Length L Ch R = 1,694,118,118,118
BEGIN DESCRIPTION:
Lacy 142 1001
END DESCRIPTION:
XS GIS Cut Line= 3
      2722060.14      6854863.47      2722227.38      6854872.55
      2722407.13      6854861.15
#Sta/Elev= 30
  4833.5  419.67  4849.4  418.97  4869.4  418.26  4877.3  417.63  4882.3  417.47
  4889.4  417.02  4899.5  416.65  4909.5  416.13  4919.5  415.85  4929.5  415.25
  4939.5  413.71  4949.5  412.89  4959.5  412.35  4989.6  411.18  4995.8  411.17
  4996.0  410.67  4999.5  410.67  4999.8  411.17  5029.7  412.80  5059.7  413.94
  5069.7  414.78  5099.7  416.19  5109.8  416.85  5119.8  417.67  5129.9  418.25
  5139.9  418.63  5149.9  419.21  5169.9  420.14  5178.0  420.75  5181.1  420.75
#Mann=3,-1,0
  4833.5    0.05       0  4995.8    0.04       0  4999.8    0.05       0
Bank Sta=4995.8,4999.8
Exp/Cntr=0.3,0.1

Type RM Length L Ch R = 1,576,153,153,153
BEGIN DESCRIPTION:
Lacy 142 1023
END DESCRIPTION:
XS GIS Cut Line= 3
      2722040.60      6854900.68      2722226.18      6854991.02
      2722435.63      6854963.12
#Sta/Elev= 30
  4793.6  418.34  4799.6  417.83  4805.5  417.70  4811.0  417.06  4821.8  416.86
  4833.6  416.12  4844.1  416.06  4873.1  415.08  4878.7  414.45  4946.3  412.40
  4977.6  411.69  4991.4  410.71  4997.1  409.87  5020.0  409.33  5028.1  408.66
  5028.3  408.16  5031.8  408.16  5032.1  408.66  5041.6  409.53  5050.3  409.95
  5060.3  410.74  5070.4  411.96  5100.7  413.95  5114.8  414.44  5131.0  415.32
  5141.1  415.48  5171.3  416.63  5188.0  417.54  5193.0  418.02  5211.3  418.76
#Mann=3,-1,0
  4793.6    0.05       0  5028.1    0.04       0  5032.1    0.05       0
Bank Sta=5028.1,5032.1
Exp/Cntr=0.3,0.1

Type RM Length L Ch R = 1,423,79,79,79
BEGIN DESCRIPTION:
Lacy 142 1022
END DESCRIPTION:
XS GIS Cut Line= 3
      2722056.05      6855089.37      2722228.36      6855116.89
      2722441.38      6855077.63
#Sta/Elev= 30
  4825.5  415.17  4845.7  414.42  4864.2  413.33  4869.3  413.34  4886.2  412.37
  4916.6  411.49  4931.4  410.76  4957.1  410.12  4967.2  409.40  4977.4  407.90
  4993.4  406.68  5000.0  406.97  5001.8  406.02  5002.1  405.52  5005.6  405.52
  5005.8  406.02  5008.9  406.66  5017.9  406.44  5056.8  407.52  5061.9  406.94
  5078.9  407.36  5109.4  409.66  5114.9  411.16  5120.0  411.03  5140.0  413.56
  5167.9  415.29  5173.0  415.16  5180.6  415.98  5211.1  417.62  5216.6  418.23
#Mann=3,-1,0
  4825.5    0.05       0  5001.8    0.04       0  5005.8    0.05       0
Bank Sta=5001.8,5005.8
Exp/Cntr=0.3,0.1

Type RM Length L Ch R = 1,344,95,95,95
BEGIN DESCRIPTION:
Lacy 142 1021
END DESCRIPTION:
XS GIS Cut Line= 3
      2722098.92      6855187.78      2722226.37      6855195.73
      2722395.52      6855171.30
#Sta/Elev= 30
  4872.3  412.63  4879.4  411.90  4909.5  410.52  4939.5  409.70  4959.5  407.62
  4969.6  406.20  4979.6  405.66  4987.6  405.44  4987.9  404.94  4991.4  404.94
  4991.6  405.44  5002.3  405.47  5019.8  405.85  5040.0  406.58  5050.1  407.36
  5060.2  408.59  5066.7  409.03  5071.7  408.96  5080.5  409.21  5090.6  409.27
  5100.7  409.63  5110.8  410.79  5120.9  411.65  5131.0  412.03  5137.0  412.55
  5142.1  412.72  5151.2  413.42  5161.3  414.00  5168.6  414.76  5170.9  414.76
#Mann=3,-1,0
  4872.3    0.05       0  4987.6    0.04       0  4991.6    0.05       0
Bank Sta=4987.6,4991.6
Exp/Cntr=0.3,0.1

Type RM Length L Ch R = 1,249,55,55,55
BEGIN DESCRIPTION:
Lacy 142 1020
END DESCRIPTION:
XS GIS Cut Line= 3
      2722164.29      6855264.63      2722274.56      6855275.92
      2722381.27      6855251.57
#Sta/Elev= 27
  4889.7  409.26  4893.1  409.26  4899.8  408.41  4904.8  409.36  4911.5  409.03
  4921.6  407.45  4931.6  406.68  4941.7  405.75  4951.7  405.13  4971.8  404.59
  4991.9  403.72  4996.8  403.62  4997.0  403.12  5000.5  403.12  5000.8  403.62
  5003.8  403.62  5012.3  403.94  5022.5  404.82  5032.8  405.79  5041.5  406.74
  5053.3  408.45  5063.6  409.00  5073.8  409.79  5084.1  409.70  5089.6  410.34
  5104.6  411.20  5110.0  411.64
#Mann=3,-1,0
  4889.7    0.05       0  4996.8    0.04       0  5000.8    0.05       0
Bank Sta=4996.8,5000.8
Exp/Cntr=0.3,0.1

Type RM Length L Ch R = 1,194,73,73,73
BEGIN DESCRIPTION:
Lacy 142 1019
END DESCRIPTION:
XS GIS Cut Line= 3
      2722170.68      6855323.23      2722330.19      6855326.73
      2722389.88      6855286.55
#Sta/Elev= 30
  4899.9  409.53  4915.2  409.08  4925.2  408.56  4935.2  407.64  4955.2  405.40
  4965.2  404.48  4975.2  404.06  4985.2  401.66  4993.2  400.40  4993.5  399.90
  4997.0  399.90  4997.2  400.40  5005.2  400.47  5015.2  402.53  5023.2  403.24
  5028.2  402.76  5035.3  403.62  5045.3  403.53  5054.8  403.58  5059.4  404.16
  5063.4  404.99  5066.6  405.65  5075.6  406.86  5081.6  407.48  5090.6  407.96
  5102.6  408.84  5111.6  409.27  5117.6  409.80  5126.0  410.05  5131.4  410.05
#Mann=4,-1,0
  4899.9    0.12       0  4993.2    0.07       0  4997.2    0.12       0
  5063.4    0.05       0
Bank Sta=4993.2,4997.2
Exp/Cntr=0.3,0.1

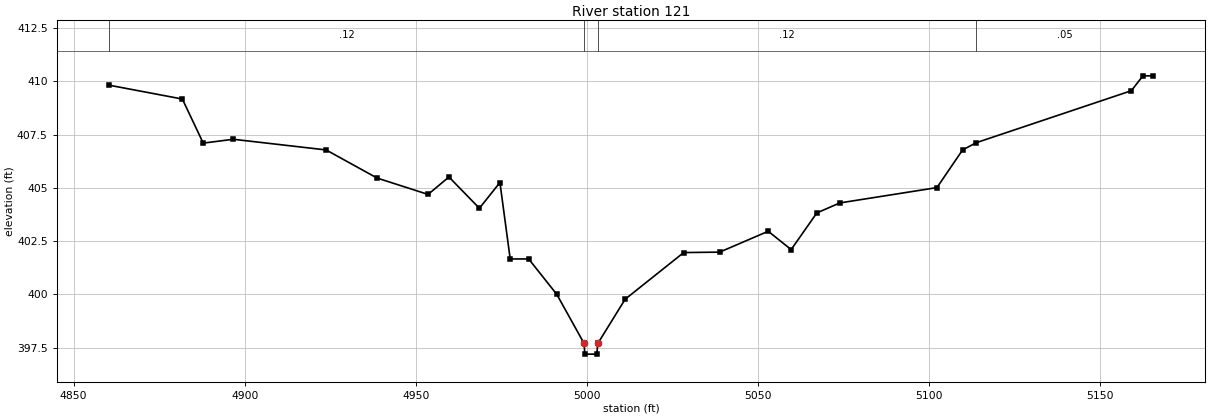
Type RM Length L Ch R = 1,121,0,0,0
BEGIN DESCRIPTION:
Lacy 142 1018
END DESCRIPTION:
XS GIS Cut Line= 4
      2722155.98      6855322.11      2722254.72      6855389.40
      2722305.17      6855391.96      2722395.58      6855291.57
#Sta/Elev= 30
  4860.4  409.82  4881.8  409.17  4887.9  407.10  4896.7  407.28  4923.8  406.78
  4938.7  405.46  4953.6  404.69  4959.7  405.51  4968.6  404.04  4974.6  405.25
  4977.6  401.66  4983.0  401.66  4991.2  400.00  4999.2  397.69  4999.4  397.19
  5002.9  397.19  5003.2  397.69  5011.2  399.77  5028.3  401.96  5038.8  401.98
  5053.0  402.96  5059.7  402.10  5067.2  403.82  5073.9  404.29  5102.3  405.01
  5109.8  406.78  5113.8  407.12  5159.1  409.56  5162.5  410.26  5165.5  410.26
#Mann=4,-1,0
  4860.4    0.12       0  4999.2    0.07       0  5003.2    0.12       0
  5113.8    0.05       0
Bank Sta=4999.2,5003.2
Exp/Cntr=0.3,0.1

Chan Stop Cuts=-1