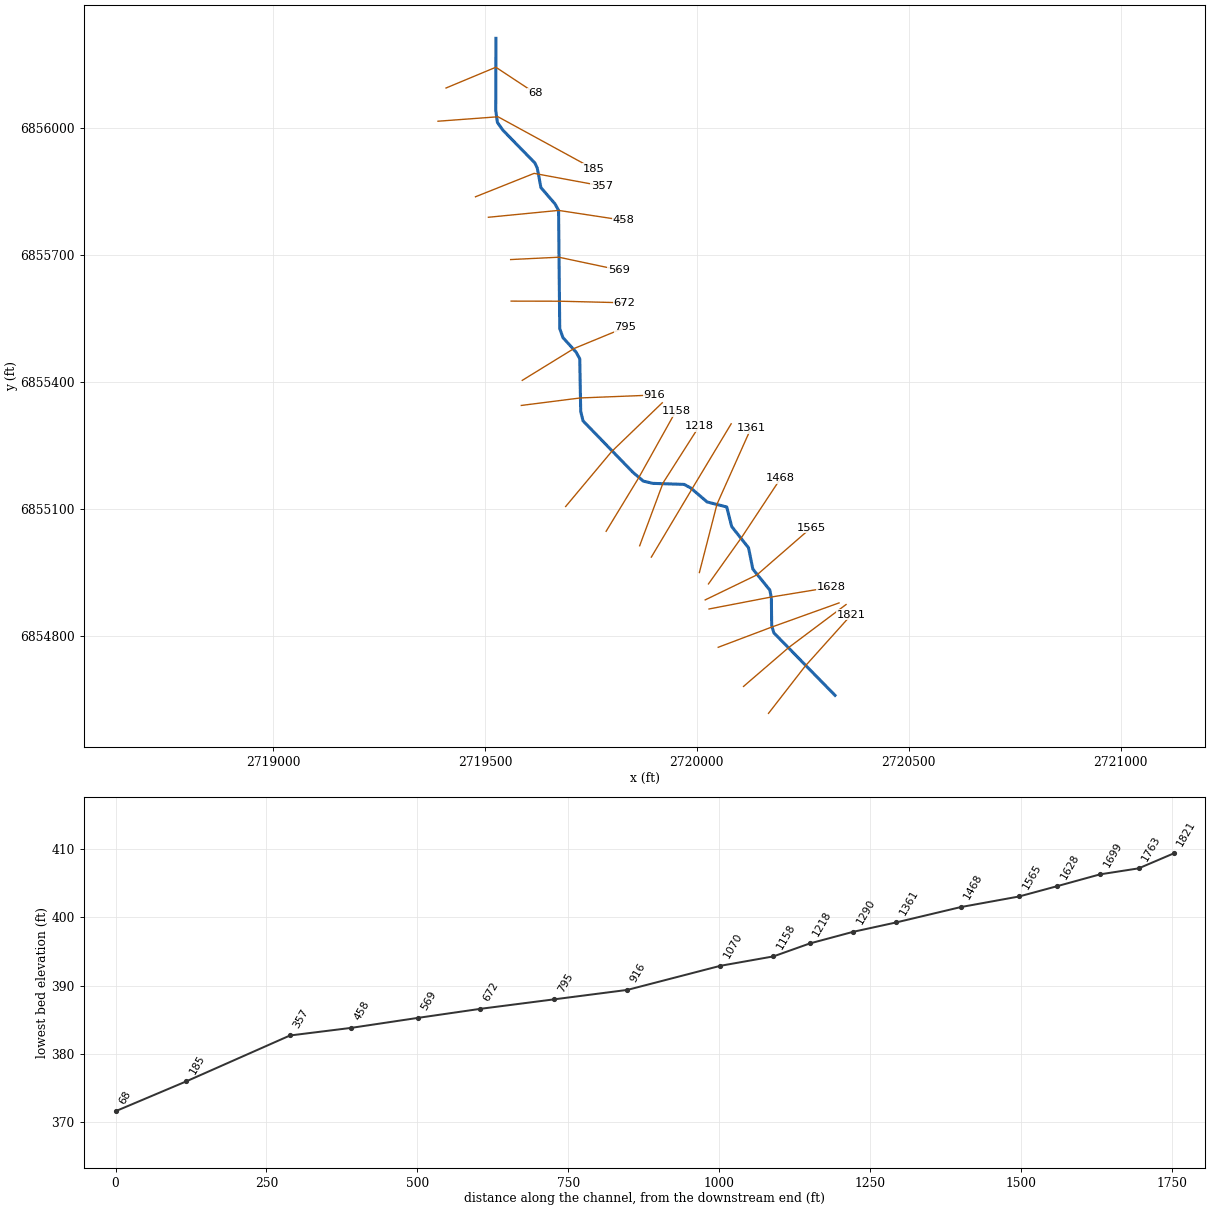
--- Lacy 143.prj (project) ---

Proj Title=Lacy 143 Base Level Engineering
Current Plan=p01
Default Exp/Contr=0.3,0.1
English Units
Geom File=g01
Flow File=f01
Plan File=p01
BEGIN DESCRIPTION:
Lacy 143
END DESCRIPTION:

--- Lacy 143.p01 (plan) ---

Plan Title=Multiple Run
Short Identifier=Multiple
Geom File=g01
Flow File=f01
Subcritical Flow
K Sum by GR= 0
Std Step Tol= 0.01
Critical Tol= 0.01
Num of Std Step Trials= 20
Max Error Tol= 0.3
Flow Tol Ratio= 0.001
Split Flow NTrial= 30
Split Flow Tol= 0.02
Split Flow Ratio= 0.02
Log Output Level= 0
Friction Slope Method= 1
Unsteady Friction Slope Method= 2
Unsteady Bridges Friction Slope Method= 1
Parabolic Critical Depth
Global Vel Dist=  1 , 1 , 1
Global Log Level= 0
CheckData=True
Encroach Param= -1, 0, 0, 0
BEGIN DESCRIPTION:
Multiple Run
END DESCRIPTION:

--- Lacy 143.f01 (steady flow) ---

Flow Title=Multiple
Number of Profiles=7
Profile Names=10-year,25-year,50-year,1pct_min,100-year,1pct_plu,500-year
River Rch & RM= Lacy 143,Reach-1,1821
     104     123     137      77     153     305     188
Boundary for River Rch & Prof#=Lacy 143,Reach-1,1
Up Type=0
Dn Type=3
Dn Slope=0.005
Boundary for River Rch & Prof#=Lacy 143,Reach-1,2
Up Type=0
Dn Type=3
Dn Slope=0.005
Boundary for River Rch & Prof#=Lacy 143,Reach-1,3
Up Type=0
Dn Type=3
Dn Slope=0.005
Boundary for River Rch & Prof#=Lacy 143,Reach-1,4
Up Type=0
Dn Type=3
Dn Slope=0.005
Boundary for River Rch & Prof#=Lacy 143,Reach-1,5
Up Type=0
Dn Type=3
Dn Slope=0.005
Boundary for River Rch & Prof#=Lacy 143,Reach-1,6
Up Type=0
Dn Type=3
Dn Slope=0.005
Boundary for River Rch & Prof#=Lacy 143,Reach-1,7
Up Type=0
Dn Type=3
Dn Slope=0.005

--- Lacy 143.g01 (geometry) ---

Geom Title=Existing Conditions

River Reach=Lacy 143,Reach-1
Reach XY= 30
      2720326.00      6854661.00      2720181.52      6854808.57
      2720176.52      6854826.22      2720175.76      6854890.90
      2720172.17      6854909.41      2720132.12      6854958.82
      2720121.85      6855009.31      2720082.24      6855059.15
      2720070.42      6855105.42      2720024.16      6855117.28
      2719985.71      6855150.19      2719970.06      6855158.68
      2719896.05      6855161.13      2719873.57      6855166.52
      2719849.13      6855187.18      2719731.47      6855308.55
      2719725.98      6855330.99      2719723.73      6855455.06
      2719715.14      6855470.64      2719684.14      6855504.94
      2719676.52      6855526.22      2719673.76      6855805.07
      2719665.21      6855820.67      2719632.14      6855858.83
      2719623.50      6855904.96      2719617.84      6855917.05
      2719542.46      6855994.25      2719529.54      6856012.47
      2719525.55      6856040.82      2719526.00      6856211.00

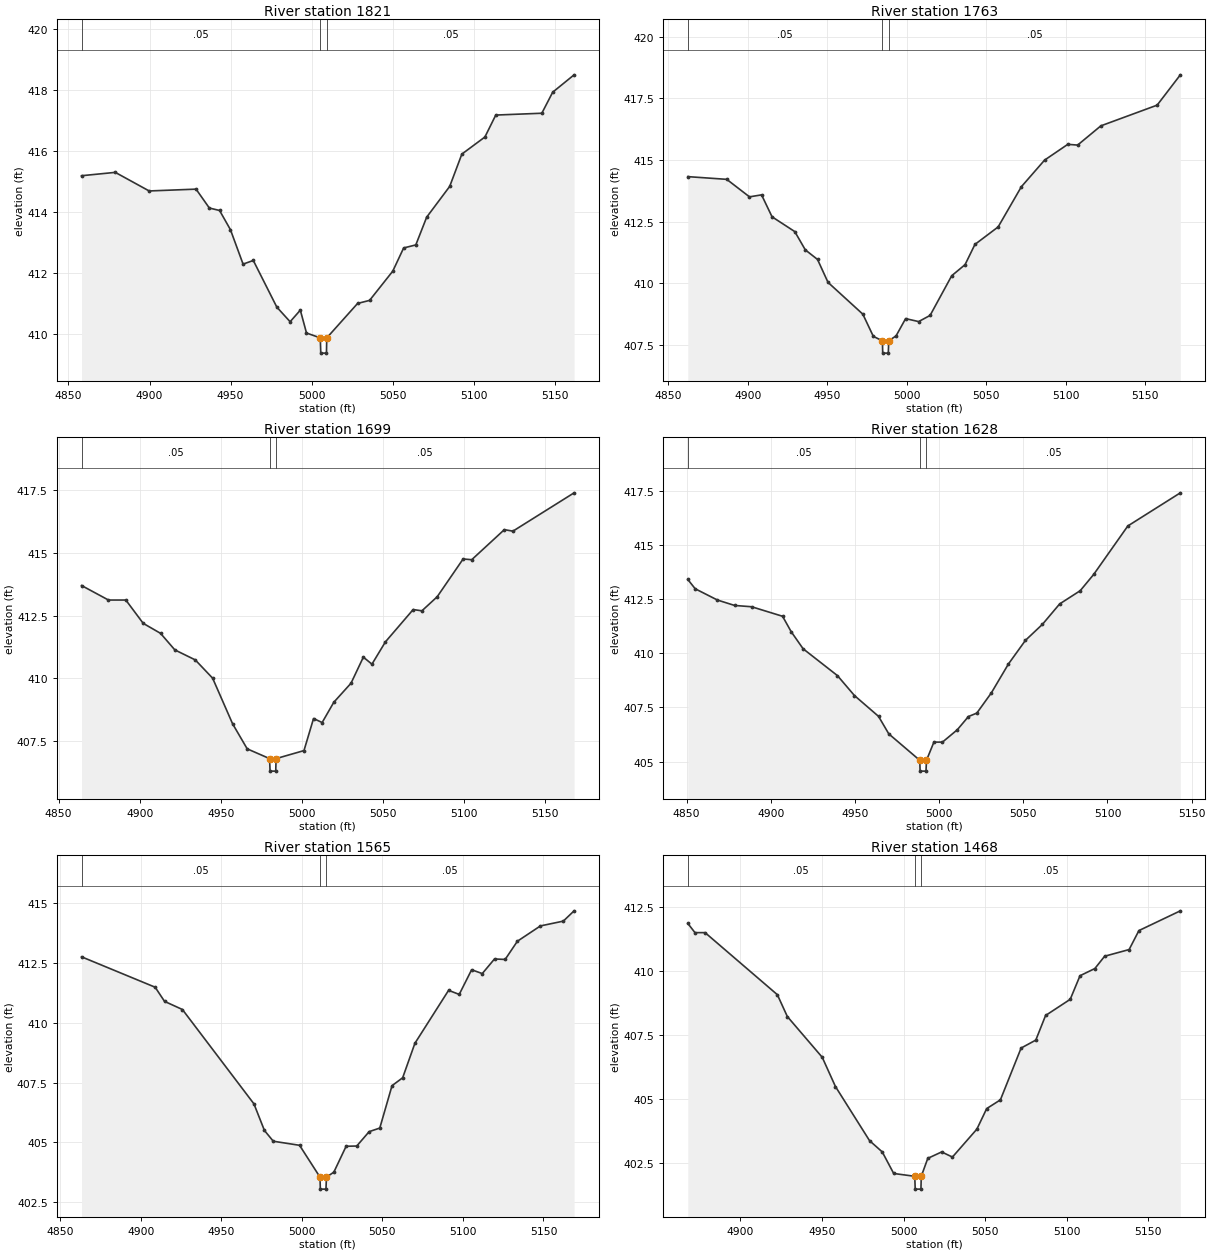
Type RM Length L Ch R = 1,1821,58,58,58
BEGIN DESCRIPTION:
Lacy 143 985
END DESCRIPTION:
XS GIS Cut Line= 3
      2720169.01      6854618.51      2720255.70      6854730.13
      2720364.20      6854850.93
#Sta/Elev= 30
  4858.1  415.18  4878.9  415.29  4899.8  414.68  4928.7  414.74  4936.9  414.12
  4943.2  414.04  4949.9  413.41  4957.7  412.28  4964.0  412.40  4978.5  410.87
  4986.7  410.39  4993.0  410.77  4996.8  410.02  5005.3  409.86  5005.6  409.36
  5009.1  409.36  5009.3  409.86  5028.3  410.99  5035.7  411.09  5050.0  412.05
  5056.7  412.81  5064.2  412.91  5070.9  413.82  5085.1  414.83  5092.6  415.89
  5106.8  416.45  5113.5  417.17  5141.9  417.23  5148.6  417.92  5161.8  418.49
#Mann=3,-1,0
  4858.1    0.05       0  5005.3    0.04       0  5009.3    0.05       0
Bank Sta=5005.3,5009.3
Exp/Cntr=0.3,0.1

Type RM Length L Ch R = 1,1763,64,64,64
BEGIN DESCRIPTION:
Lacy 143 987
END DESCRIPTION:
XS GIS Cut Line= 3
      2720110.04      6854682.04      2720216.76      6854773.94
      2720351.97      6854875.27
#Sta/Elev= 30
  4862.2  414.33  4886.7  414.22  4901.0  413.51  4908.6  413.59  4915.2  412.70
  4929.5  412.10  4936.1  411.36  4943.8  410.97  4950.4  410.04  4972.3  408.75
  4978.9  407.85  4984.6  407.67  4984.8  407.17  4988.3  407.17  4988.6  407.67
  4993.2  407.87  4999.2  408.57  5007.4  408.45  5014.6  408.70  5028.2  410.31
  5036.6  410.76  5042.8  411.58  5057.4  412.29  5072.0  413.92  5086.6  415.00
  5101.2  415.64  5107.4  415.61  5122.0  416.39  5157.4  417.23  5172.0  418.46
#Mann=3,-1,0
  4862.2    0.05       0  4984.6    0.04       0  4988.6    0.05       0
Bank Sta=4984.6,4988.6
Exp/Cntr=0.3,0.1

Type RM Length L Ch R = 1,1699,71,71,71
BEGIN DESCRIPTION:
Lacy 143 986
END DESCRIPTION:
XS GIS Cut Line= 3
      2720050.45      6854774.43      2720176.51      6854822.05
      2720335.42      6854879.11
#Sta/Elev= 30
  4864.1  413.70  4880.7  413.12  4891.4  413.12  4902.1  412.19  4912.8  411.79
  4921.6  411.13  4934.2  410.73  4944.9  410.00  4957.2  408.18  4966.2  407.18
  4980.0  406.79  4980.3  406.29  4983.8  406.29  4984.0  406.79  5001.2  407.11
  5007.1  408.39  5012.4  408.23  5019.6  409.04  5030.2  409.80  5037.8  410.84
  5043.1  410.56  5051.4  411.45  5068.5  412.74  5073.9  412.69  5083.3  413.25
  5099.3  414.76  5104.6  414.73  5124.7  415.93  5130.0  415.87  5167.7  417.40
#Mann=3,-1,0
  4864.1    0.05       0  4980.0    0.04       0  4984.0    0.05       0
Bank Sta=4980,4984
Exp/Cntr=0.3,0.1

Type RM Length L Ch R = 1,1628,63,63,63
BEGIN DESCRIPTION:
Lacy 143 988
END DESCRIPTION:
XS GIS Cut Line= 3
      2720028.75      6854864.78      2720173.64      6854892.67
      2720316.79      6854916.09
#Sta/Elev= 30
  4850.7  413.41  4855.1  412.98  4868.3  412.46  4878.5  412.21  4888.6  412.15
  4907.0  411.71  4912.1  411.00  4919.2  410.21  4939.6  408.97  4949.7  408.05
  4964.0  407.09  4970.1  406.28  4988.5  405.06  4988.7  404.56  4992.2  404.56
  4992.5  405.06  4996.9  405.90  5002.0  405.90  5010.8  406.47  5017.4  407.08
  5022.4  407.24  5031.0  408.17  5041.2  409.51  5051.3  410.60  5061.4  411.34
  5071.6  412.28  5083.8  412.89  5091.8  413.64  5112.1  415.88  5143.3  417.41
#Mann=3,-1,0
  4850.7    0.05       0  4988.5    0.04       0  4992.5    0.05       0
Bank Sta=4988.5,4992.5
Exp/Cntr=0.3,0.1

Type RM Length L Ch R = 1,1565,97,97,97
BEGIN DESCRIPTION:
Lacy 143 989
END DESCRIPTION:
XS GIS Cut Line= 3
      2720019.65      6854886.19      2720141.85      6854945.30
      2720270.08      6855056.84
#Sta/Elev= 30
  4863.3  412.75  4909.0  411.48  4914.8  410.89  4925.9  410.55  4970.3  406.61
  4976.8  405.50  4982.3  405.05  4998.6  404.88  5011.3  403.55  5011.5  403.05
  5015.0  403.05  5015.3  403.55  5019.9  403.76  5027.5  404.84  5034.1  404.85
  5041.8  405.45  5048.4  405.60  5056.0  407.37  5062.6  407.70  5070.2  409.14
  5091.1  411.35  5097.7  411.18  5105.4  412.21  5112.0  412.05  5119.6  412.66
  5126.2  412.64  5133.8  413.40  5148.1  414.04  5162.3  414.24  5169.0  414.67
#Mann=3,-1,0
  4863.3    0.05       0  5011.3    0.04       0  5015.3    0.05       0
Bank Sta=5011.3,5015.3
Exp/Cntr=0.3,0.1

Type RM Length L Ch R = 1,1468,107,107,107
BEGIN DESCRIPTION:
Lacy 143 990
END DESCRIPTION:
XS GIS Cut Line= 3
      2720027.36      6854923.88      2720106.73      6855035.36
      2720197.72      6855173.07
#Sta/Elev= 30
  4867.7  411.85  4872.1  411.49  4878.3  411.49  4922.6  409.07  4928.7  408.22
  4950.1  406.63  4958.2  405.49  4979.1  403.38  4986.9  402.94  4993.9  402.10
  5006.8  401.99  5007.1  401.49  5010.6  401.49  5010.8  401.99  5014.8  402.69
  5023.3  402.94  5029.9  402.74  5044.9  403.83  5050.9  404.63  5059.3  404.97
  5072.0  406.99  5081.0  407.30  5087.0  408.26  5102.1  408.89  5108.1  409.81
  5117.2  410.09  5123.2  410.57  5138.2  410.83  5144.2  411.57  5169.6  412.34
#Mann=3,-1,0
  4867.7    0.05       0  5006.8    0.04       0  5010.8    0.05       0
Bank Sta=5006.8,5010.8
Exp/Cntr=0.3,0.1

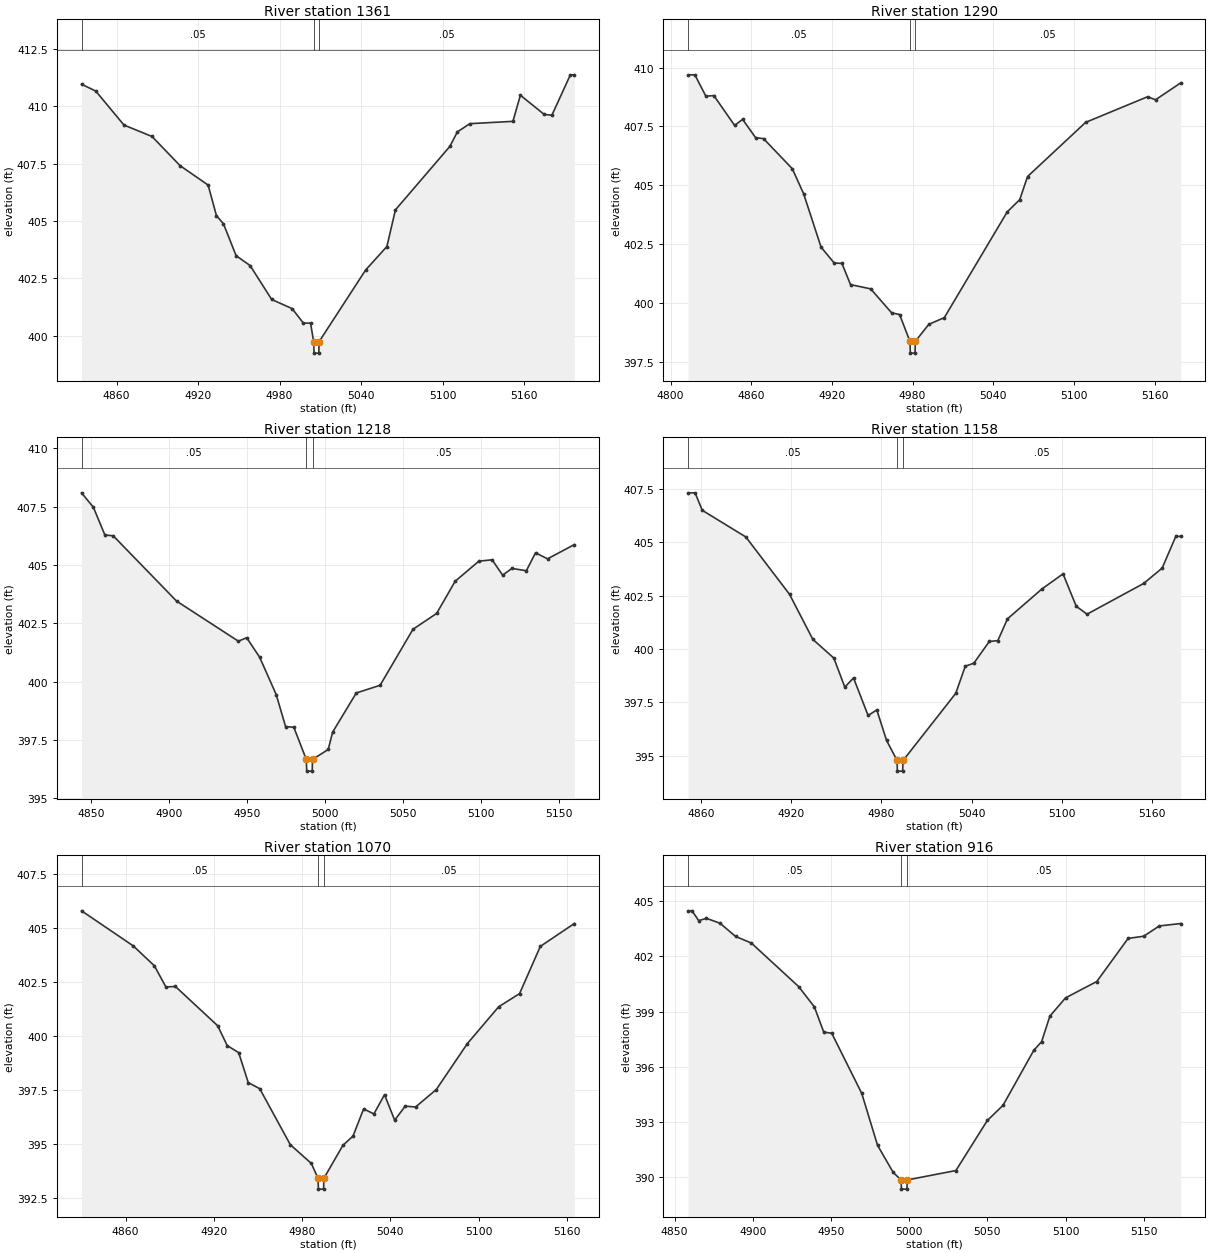
Type RM Length L Ch R = 1,1361,71,71,71
BEGIN DESCRIPTION:
Lacy 143 991
END DESCRIPTION:
XS GIS Cut Line= 3
      2720005.95      6854950.79      2720047.47      6855111.88
      2720127.71      6855291.18
#Sta/Elev= 30
  4834.2  410.97  4844.7  410.67  4865.4  409.19  4886.1  408.69  4906.7  407.42
  4927.4  406.57  4933.5  405.24  4938.7  404.88  4948.0  403.49  4958.3  403.06
  4974.2  401.58  4989.3  401.18  4997.5  400.55  5002.8  400.55  5005.1  399.74
  5005.4  399.24  5008.9  399.24  5009.1  399.74  5043.4  402.87  5059.0  403.89
  5065.3  405.49  5105.4  408.26  5110.9  408.89  5120.1  409.25  5151.8  409.35
  5157.3  410.49  5174.9  409.65  5180.5  409.62  5194.1  411.38  5197.0  411.38
#Mann=3,-1,0
  4834.2    0.05       0  5005.1    0.04       0  5009.1    0.05       0
Bank Sta=5005.1,5009.1
Exp/Cntr=0.3,0.1

Type RM Length L Ch R = 1,1290,72,72,72
BEGIN DESCRIPTION:
Lacy 143 992
END DESCRIPTION:
XS GIS Cut Line= 3
      2719892.60      6854987.15      2719990.30      6855150.94
      2720081.00      6855301.64
#Sta/Elev= 30
  4812.9  409.69  4818.0  409.69  4826.2  408.78  4832.1  408.81  4847.6  407.54
  4853.5  407.80  4863.2  407.02  4869.1  406.98  4890.5  405.70  4898.9  404.64
  4911.9  402.37  4921.6  401.70  4927.4  401.68  4933.8  400.78  4948.8  400.60
  4964.4  399.58  4970.3  399.51  4978.0  398.37  4978.3  397.87  4981.8  397.87
  4982.0  398.37  4992.0  399.09  5003.6  399.38  5050.4  403.87  5059.7  404.39
  5065.5  405.37  5108.7  407.67  5154.8  408.76  5160.7  408.63  5179.5  409.35
#Mann=3,-1,0
  4812.9    0.05       0  4978.0    0.04       0  4982.0    0.05       0
Bank Sta=4978,4982
Exp/Cntr=0.3,0.1

Type RM Length L Ch R = 1,1218,60,60,60
BEGIN DESCRIPTION:
Lacy 143 993
END DESCRIPTION:
XS GIS Cut Line= 3
      2719865.05      6855013.87      2719920.32      6855162.30
      2720005.29      6855295.53
#Sta/Elev= 30
  4843.7  408.09  4851.3  407.47  4858.7  406.28  4864.0  406.25  4904.7  403.45
  4944.4  401.73  4949.7  401.88  4958.0  401.05  4968.7  399.44  4974.7  398.07
  4980.0  398.04  4988.0  396.66  4988.3  396.16  4991.8  396.16  4992.0  396.66
  5002.1  397.09  5004.9  397.83  5020.1  399.51  5035.4  399.84  5056.5  402.24
  5071.7  402.92  5083.6  404.30  5098.8  405.16  5107.3  405.22  5114.1  404.56
  5120.0  404.85  5129.3  404.75  5135.2  405.52  5142.9  405.26  5160.1  405.87
#Mann=3,-1,0
  4843.7    0.05       0  4988.0    0.04       0  4992.0    0.05       0
Bank Sta=4988,4992
Exp/Cntr=0.3,0.1

Type RM Length L Ch R = 1,1158,88,88,88
BEGIN DESCRIPTION:
Lacy 143 994
END DESCRIPTION:
XS GIS Cut Line= 3
      2719785.97      6855048.08      2719862.57      6855173.94
      2719950.65      6855331.79
#Sta/Elev= 30
  4851.2  407.32  4855.9  407.32  4860.7  406.50  4889.7  405.25  4918.8  402.56
  4934.3  400.45  4948.3  399.57  4955.6  398.21  4961.4  398.64  4971.1  396.88
  4976.9  397.14  4983.4  395.71  4990.4  394.77  4990.6  394.27  4994.1  394.27
  4994.4  394.77  5029.5  397.92  5035.8  399.19  5041.5  399.33  5051.8  400.35
  5057.5  400.39  5063.9  401.41  5086.8  402.81  5100.9  403.52  5109.7  402.00
  5116.9  401.63  5154.6  403.07  5166.9  403.79  5176.0  405.28  5179.3  405.28
#Mann=3,-1,0
  4851.2    0.05       0  4990.4    0.04       0  4994.4    0.05       0
Bank Sta=4990.4,4994.4
Exp/Cntr=0.3,0.1

Type RM Length L Ch R = 1,1070,154,154,154
BEGIN DESCRIPTION:
Lacy 143 984
END DESCRIPTION:
XS GIS Cut Line= 3
      2719690.47      6855106.51      2719798.75      6855235.93
      2719918.39      6855351.23
#Sta/Elev= 30
  4830.1  405.80  4865.3  404.17  4879.6  403.25  4887.4  402.27  4893.9  402.29
  4922.6  400.47  4929.1  399.55  4936.9  399.22  4943.4  397.83  4951.2  397.55
  4972.0  394.95  4986.3  394.08  4990.8  393.39  4991.1  392.89  4994.6  392.89
  4994.8  393.39  5007.7  394.92  5014.6  395.35  5021.8  396.61  5028.8  396.38
  5036.0  397.27  5042.9  396.09  5050.1  396.74  5057.1  396.70  5071.2  397.51
  5092.3  399.64  5113.6  401.35  5127.8  401.96  5141.9  404.15  5165.0  405.21
#Mann=3,-1,0
  4830.1    0.05       0  4990.8    0.04       0  4994.8    0.05       0
Bank Sta=4990.8,4994.8
Exp/Cntr=0.3,0.1

Type RM Length L Ch R = 1,916,121,121,121
BEGIN DESCRIPTION:
Lacy 143 983
END DESCRIPTION:
XS GIS Cut Line= 3
      2719585.80      6855344.95      2719724.88      6855362.60
      2719899.65      6855369.54
#Sta/Elev= 30
  4858.6  404.48  4861.2  404.48  4865.4  403.95  4870.4  404.07  4879.0  403.81
  4889.0  403.09  4899.1  402.73  4929.4  400.36  4939.4  399.26  4945.4  397.89
  4950.5  397.83  4969.7  394.56  4979.8  391.74  4989.8  390.27  4994.8  389.86
  4995.1  389.36  4998.6  389.36  4998.8  389.86  5029.9  390.37  5050.0  393.09
  5060.0  393.91  5079.7  396.90  5084.7  397.37  5090.0  398.76  5100.0  399.75
  5120.0  400.64  5140.0  402.98  5150.0  403.10  5160.0  403.66  5173.7  403.79
#Mann=3,-1,0
  4858.6    0.05       0  4994.8    0.04       0  4998.8    0.05       0
Bank Sta=4994.8,4998.8
Exp/Cntr=0.3,0.1

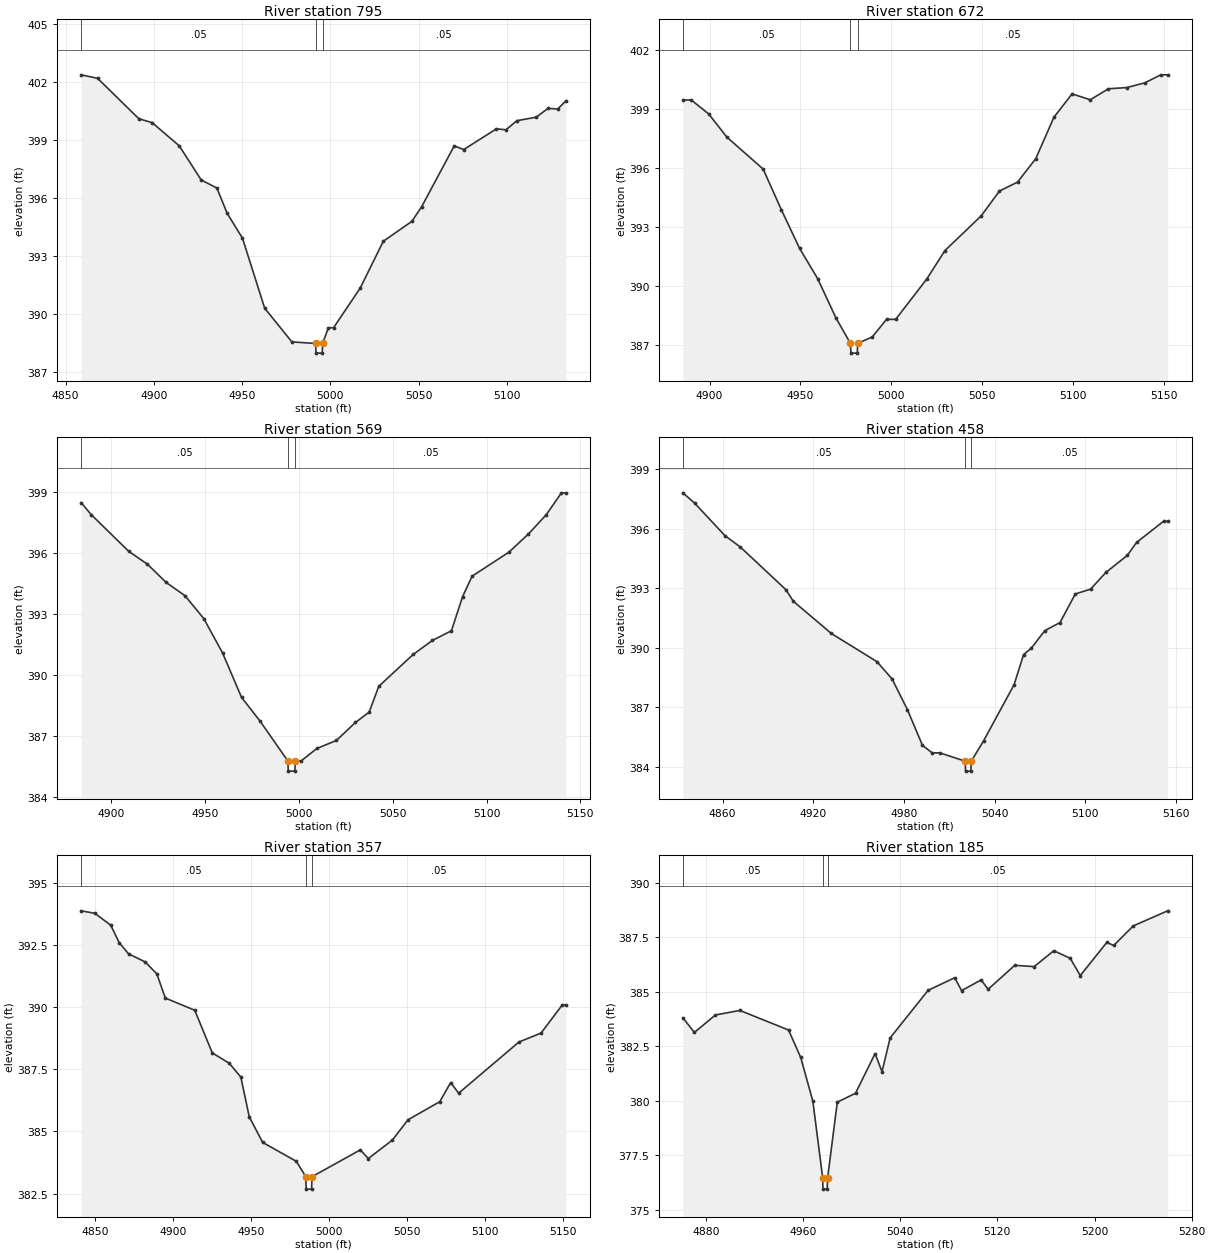
Type RM Length L Ch R = 1,795,123,123,123
BEGIN DESCRIPTION:
Lacy 143 982
END DESCRIPTION:
XS GIS Cut Line= 3
      2719588.12      6855404.13      2719709.94      6855479.10
      2719831.67      6855529.27
#Sta/Elev= 30
  4858.8  402.36  4868.1  402.18  4891.5  400.09  4899.0  399.89  4914.4  398.69
  4926.8  396.93  4935.7  396.51  4941.5  395.21  4950.2  393.92  4962.8  390.30
  4978.2  388.56  4991.6  388.48  4991.9  387.98  4995.4  387.98  4995.6  388.48
  4998.9  389.29  5001.8  389.29  5016.9  391.34  5030.0  393.76  5046.2  394.79
  5051.7  395.54  5070.2  398.69  5075.6  398.50  5094.1  399.57  5099.5  399.52
  5105.7  399.99  5116.6  400.17  5123.4  400.63  5128.8  400.59  5133.5  401.02
#Mann=3,-1,0
  4858.8    0.05       0  4991.6    0.04       0  4995.6    0.05       0
Bank Sta=4991.6,4995.6
Exp/Cntr=0.3,0.1

Type RM Length L Ch R = 1,672,103,103,103
BEGIN DESCRIPTION:
Lacy 143 981
END DESCRIPTION:
XS GIS Cut Line= 3
      2719561.80      6855591.06      2719676.78      6855590.84
      2719828.55      6855587.15
#Sta/Elev= 30
  4885.3  399.47  4889.9  399.47  4899.5  398.76  4909.5  397.58  4929.5  395.95
  4939.5  393.88  4949.5  391.92  4959.5  390.37  4969.5  388.38  4977.5  387.08
  4977.8  386.58  4981.3  386.58  4981.5  387.08  4989.5  387.40  4997.4  388.30
  5002.4  388.30  5019.5  390.35  5029.5  391.80  5049.5  393.57  5059.5  394.83
  5069.5  395.29  5079.5  396.48  5089.5  398.59  5099.5  399.78  5109.5  399.48
  5119.5  400.04  5129.5  400.10  5139.5  400.34  5148.3  400.75  5152.1  400.75
#Mann=3,-1,0
  4885.3    0.05       0  4977.5    0.04       0  4981.5    0.05       0
Bank Sta=4977.5,4981.5
Exp/Cntr=0.3,0.1

Type RM Length L Ch R = 1,569,111,111,111
BEGIN DESCRIPTION:
Lacy 143 980
END DESCRIPTION:
XS GIS Cut Line= 3
      2719560.74      6855689.12      2719674.37      6855694.64
      2719815.68      6855664.75
#Sta/Elev= 30
  4884.1  398.50  4889.4  397.91  4909.4  396.10  4919.4  395.46  4929.4  394.56
  4939.4  393.91  4949.4  392.78  4959.4  391.09  4969.5  388.90  4979.5  387.71
  4994.2  385.76  4994.4  385.26  4997.9  385.26  4998.2  385.76  5001.2  385.76
  5009.7  386.38  5020.0  386.77  5030.2  387.66  5037.5  388.17  5042.6  389.44
  5060.9  391.01  5071.1  391.70  5081.3  392.18  5087.2  393.85  5092.3  394.87
  5112.0  396.06  5122.2  396.94  5131.8  397.90  5139.9  398.98  5142.3  398.98
#Mann=3,-1,0
  4884.1    0.05       0  4994.2    0.04       0  4998.2    0.05       0
Bank Sta=4994.2,4998.2
Exp/Cntr=0.3,0.1

Type RM Length L Ch R = 1,458,101,101,101
BEGIN DESCRIPTION:
Lacy 143 969
END DESCRIPTION:
XS GIS Cut Line= 3
      2719508.25      6855788.88      2719673.76      6855805.07
      2719826.41      6855781.84
#Sta/Elev= 30
  4833.7  397.80  4841.5  397.28  4861.6  395.64  4871.6  395.08  4901.8  392.93
  4906.8  392.34  4931.9  390.72  4962.1  389.30  4972.1  388.43  4982.2  386.89
  4992.2  385.09  4998.6  384.71  5003.7  384.71  5020.5  384.29  5020.7  383.79
  5024.2  383.79  5024.5  384.29  5032.6  385.31  5052.8  388.14  5059.1  389.66
  5064.2  389.98  5073.1  390.86  5083.2  391.27  5093.3  392.71  5103.4  392.95
  5113.5  393.79  5127.7  394.65  5133.8  395.30  5151.7  396.37  5154.4  396.37
#Mann=3,-1,0
  4833.7    0.05       0  5020.5    0.04       0  5024.5    0.05       0
Bank Sta=5020.5,5024.5
Exp/Cntr=0.3,0.1

Type RM Length L Ch R = 1,357,172,172,172
BEGIN DESCRIPTION:
Lacy 143 968
END DESCRIPTION:
XS GIS Cut Line= 3
      2719477.78      6855837.20      2719616.09      6855892.42
      2719775.66      6855862.87
#Sta/Elev= 30
  4840.8  393.88  4849.6  393.78  4859.8  393.30  4865.2  392.60  4871.2  392.15
  4882.0  391.82  4889.4  391.34  4894.8  390.37  4913.7  389.88  4925.0  388.16
  4935.8  387.75  4943.3  387.19  4948.7  385.59  4957.3  384.56  4978.9  383.80
  4985.0  383.18  4985.2  382.68  4988.7  382.68  4989.0  383.18  5020.0  384.26
  5025.1  383.91  5040.5  384.65  5050.6  385.47  5071.0  386.20  5078.0  386.97
  5083.1  386.54  5121.8  388.60  5136.0  388.96  5149.6  390.09  5152.0  390.09
#Mann=3,-1,0
  4840.8    0.05       0  4985.0    0.04       0  4989.0    0.05       0
Bank Sta=4985,4989
Exp/Cntr=0.3,0.1

Type RM Length L Ch R = 1,185,117,117,117
BEGIN DESCRIPTION:
Lacy 143 967
END DESCRIPTION:
XS GIS Cut Line= 3
      2719389.26      6856015.47      2719530.93      6856025.97
      2719756.42      6855902.80
#Sta/Elev= 30
  4861.2  383.81  4870.7  383.14  4888.0  383.94  4908.1  384.15  4948.2  383.25
  4958.2  381.99  4968.2  379.98  4976.3  376.45  4976.5  375.95  4980.0  375.95
  4980.3  376.45  4988.3  379.94  5003.3  380.35  5019.4  382.17  5025.1  381.34
  5031.8  382.89  5063.0  385.07  5084.9  385.65  5090.6  385.06  5106.7  385.55
  5112.4  385.12  5134.4  386.22  5150.3  386.16  5166.5  386.89  5180.0  386.54
  5188.3  385.75  5210.1  387.27  5215.8  387.13  5231.9  388.03  5260.2  388.72
#Mann=3,-1,0
  4861.2    0.05       0  4976.3    0.04       0  4980.3    0.05       0
Bank Sta=4976.3,4980.3
Exp/Cntr=0.3,0.1

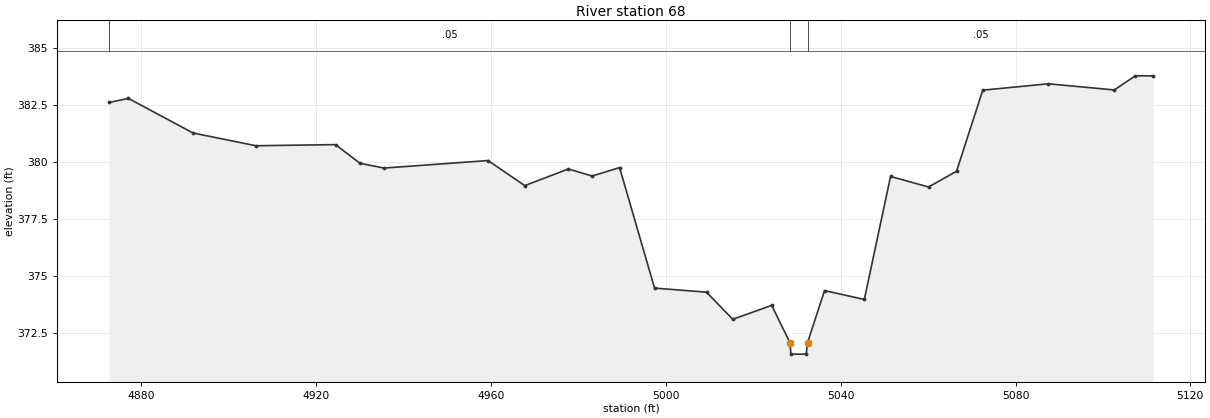
Type RM Length L Ch R = 1,68,0,0,0
BEGIN DESCRIPTION:
Lacy 143 966
END DESCRIPTION:
XS GIS Cut Line= 3
      2719408.23      6856093.79      2719525.82      6856142.82
      2719618.88      6856081.41
#Sta/Elev= 30
  4872.6  382.63  4877.0  382.81  4891.8  381.29  4906.2  380.73  4924.4  380.78
  4930.0  379.96  4935.5  379.75  4959.3  380.08  4967.7  378.98  4977.7  379.71
  4983.1  379.40  4989.4  379.77  4997.4  374.48  5009.3  374.30  5015.3  373.11
  5024.2  373.72  5028.4  372.08  5028.6  371.58  5032.1  371.58  5032.4  372.08
  5036.3  374.37  5045.4  373.98  5051.4  379.38  5060.1  378.92  5066.5  379.61
  5072.5  383.17  5087.5  383.45  5102.6  383.18  5107.4  383.80  5111.5  383.80
#Mann=3,-1,0
  4872.6    0.05       0  5028.4    0.04       0  5032.4    0.05       0
Bank Sta=5028.4,5032.4
Exp/Cntr=0.3,0.1

Chan Stop Cuts=-1