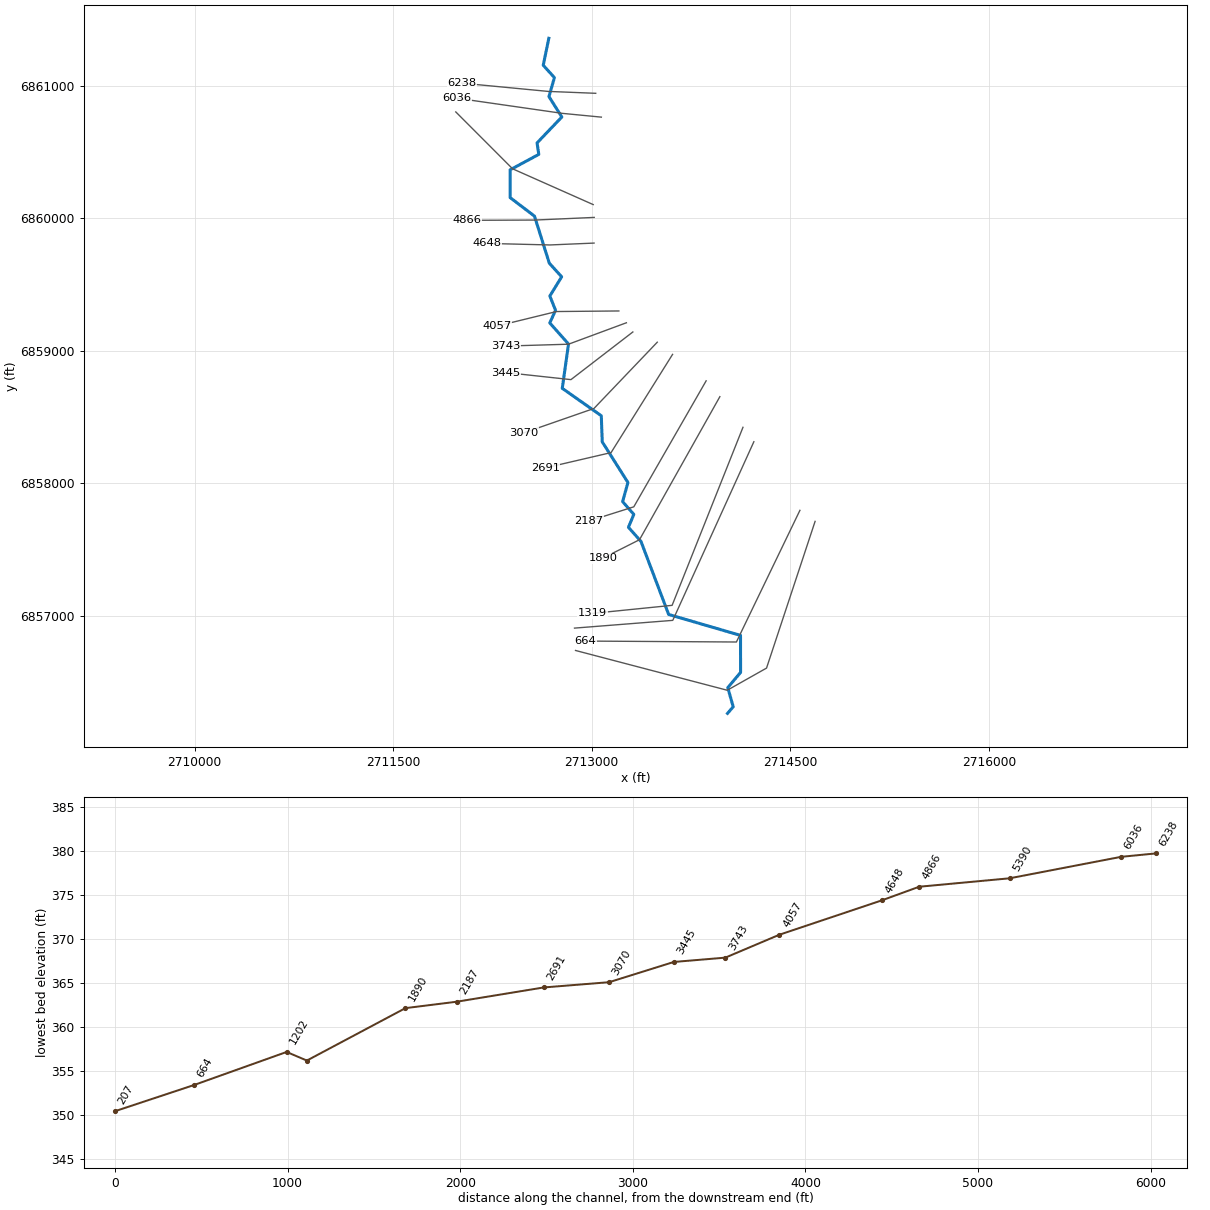
--- Lacy 144.prj (project) ---

Proj Title=Lacy 144 Base Level Engineering
Current Plan=p01
Default Exp/Contr=0.3,0.1
English Units
Geom File=g01
Flow File=f01
Plan File=p01
BEGIN DESCRIPTION:
Lacy 144
END DESCRIPTION:

--- Lacy 144.p01 (plan) ---

Plan Title=Multiple Run
Short Identifier=Multiple
Geom File=g01
Flow File=f01
Subcritical Flow
K Sum by GR= 0
Std Step Tol= 0.01
Critical Tol= 0.01
Num of Std Step Trials= 20
Max Error Tol= 0.3
Flow Tol Ratio= 0.001
Split Flow NTrial= 30
Split Flow Tol= 0.02
Split Flow Ratio= 0.02
Log Output Level= 0
Friction Slope Method= 1
Unsteady Friction Slope Method= 2
Unsteady Bridges Friction Slope Method= 1
Parabolic Critical Depth
Global Vel Dist=  1 , 1 , 1
Global Log Level= 0
CheckData=True
Encroach Param= -1, 0, 0, 0
BEGIN DESCRIPTION:
Multiple Run
END DESCRIPTION:

--- Lacy 144.f01 (steady flow) ---

Flow Title=Multiple
Number of Profiles=7
Profile Names=10-year,25-year,50-year,1pct_min,100-year,1pct_plu,500-year
River Rch & RM= Lacy 144,Reach-1,6238
     536     706     841     497     991    1978    1376
Boundary for River Rch & Prof#=Lacy 144,Reach-1,1
Up Type=0
Dn Type=3
Dn Slope=0.005
Boundary for River Rch & Prof#=Lacy 144,Reach-1,2
Up Type=0
Dn Type=3
Dn Slope=0.005
Boundary for River Rch & Prof#=Lacy 144,Reach-1,3
Up Type=0
Dn Type=3
Dn Slope=0.005
Boundary for River Rch & Prof#=Lacy 144,Reach-1,4
Up Type=0
Dn Type=3
Dn Slope=0.005
Boundary for River Rch & Prof#=Lacy 144,Reach-1,5
Up Type=0
Dn Type=3
Dn Slope=0.005
Boundary for River Rch & Prof#=Lacy 144,Reach-1,6
Up Type=0
Dn Type=3
Dn Slope=0.005
Boundary for River Rch & Prof#=Lacy 144,Reach-1,7
Up Type=0
Dn Type=3
Dn Slope=0.005

--- Lacy 144.g01 (geometry) ---

Geom Title=Existing Conditions

River Reach=Lacy 144,Reach-1
Reach XY= 30
      2712676.00      6861361.00      2712633.82      6861157.58
      2712718.17      6861064.42      2712677.11      6860920.64
      2712774.31      6860766.64      2712587.24      6860571.00
      2712600.25      6860484.27      2712383.63      6860367.50
      2712383.99      6860157.65      2712567.98      6860017.34
      2712679.56      6859662.47      2712772.89      6859559.35
      2712683.81      6859414.41      2712726.74      6859306.42
      2712683.32      6859210.90      2712824.90      6859051.36
      2712777.55      6858716.85      2713072.47      6858509.55
      2713079.54      6858312.46      2713273.83      6858005.02
      2713233.34      6857860.90      2713318.15      6857764.41
      2713277.67      6857667.05      2713372.44      6857559.53
      2713581.40      6857008.29      2714124.28      6856850.16
      2714124.79      6856570.59      2714027.97      6856455.11
      2714069.09      6856310.86      2714026.00      6856261.00

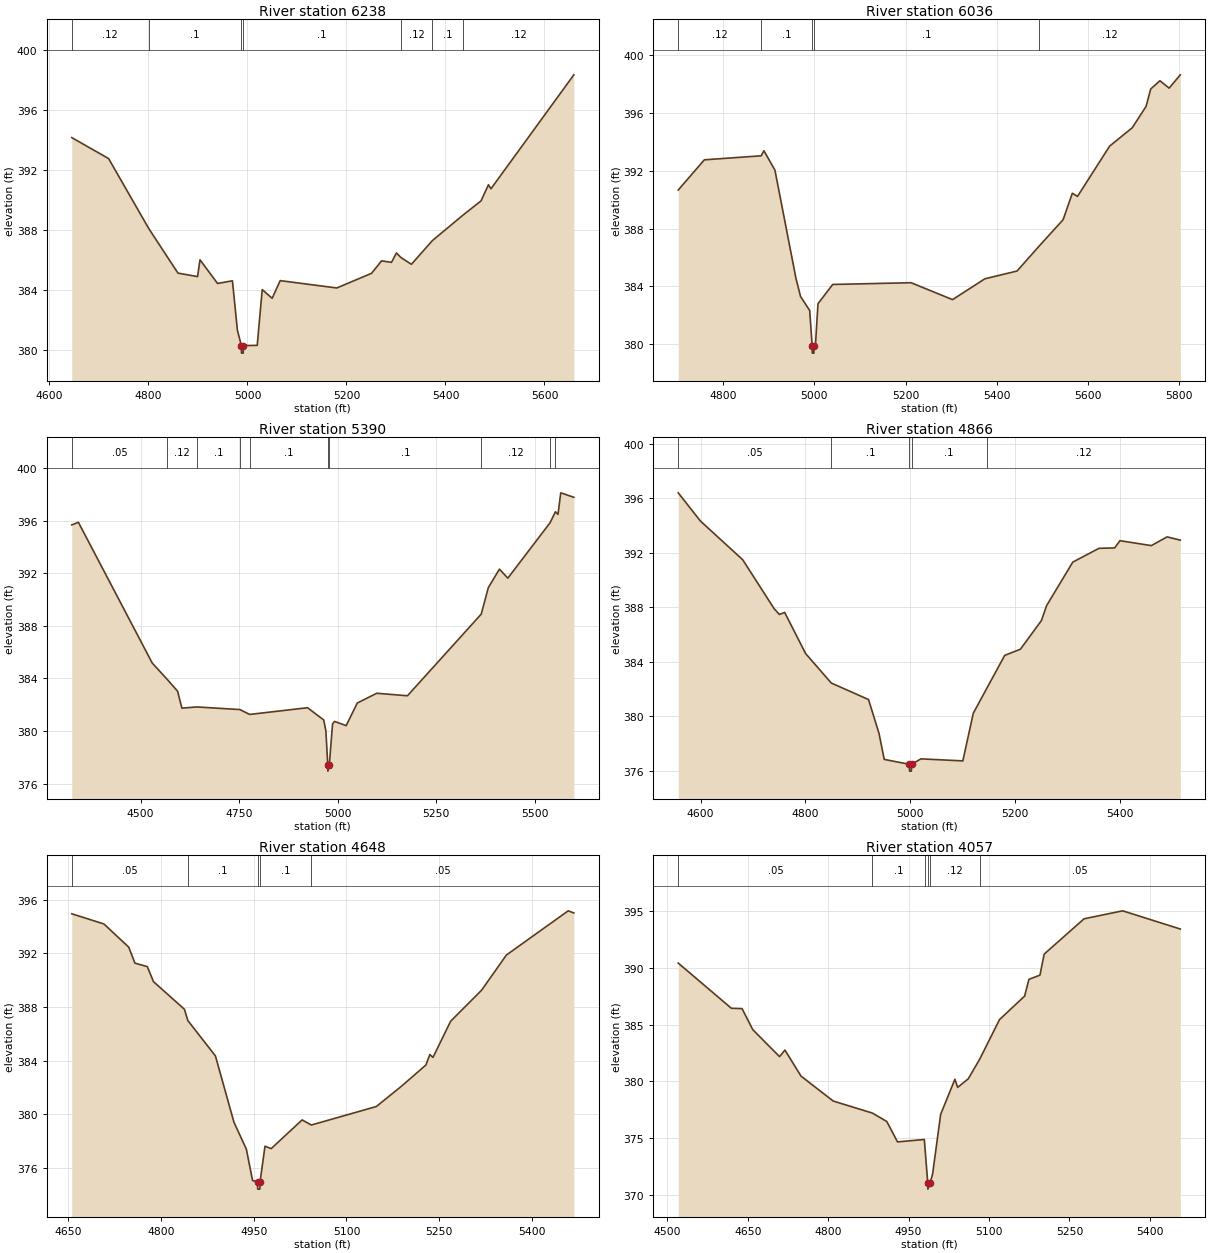
Type RM Length L Ch R = 1,6238,202,202,202
BEGIN DESCRIPTION:
Lacy 144 931
END DESCRIPTION:
XS GIS Cut Line= 3
      2713030.38      6860945.67      2712671.06      6860960.04
      2712019.25      6861022.43
#Sta/Elev= 30
  4645.0  394.17  4719.4  392.77  4800.7  388.09  4859.6  385.12  4899.1  384.89
  4904.1  386.01  4939.6  384.43  4969.6  384.61  4979.7  381.30  4987.7  380.28
  4987.9  379.78  4991.4  379.78  4991.7  380.28  5019.7  380.30  5029.8  384.02
  5049.9  383.44  5066.1  384.62  5180.5  384.13  5250.8  385.11  5270.9  385.94
  5291.0  385.84  5301.0  386.47  5309.7  386.17  5331.2  385.71  5373.8  387.30
  5436.4  389.02  5471.8  389.94  5486.9  391.02  5491.9  390.75  5659.4  398.36
#Mann=7,-1,0
  4645.0    0.12       0  4800.7     0.1       0  4987.7    0.07       0
  4991.7     0.1       0  5309.7    0.12       0  5373.8     0.1       0
  5436.4    0.12       0
Bank Sta=4987.7,4991.7
Exp/Cntr=0.3,0.1

Type RM Length L Ch R = 1,6036,646,646,646
BEGIN DESCRIPTION:
Lacy 144 930
END DESCRIPTION:
XS GIS Cut Line= 3
      2713072.89      6860765.64      2712776.25      6860794.38
      2711981.75      6860908.65
#Sta/Elev= 30
  4701.6  390.67  4758.8  392.76  4883.5  393.04  4889.4  393.39  4913.6  392.05
  4959.7  384.56  4969.7  383.31  4989.8  382.34  4995.2  379.89  4995.5  379.39
  4999.0  379.39  4999.2  379.89  5002.3  379.89  5008.0  382.81  5040.3  384.14
  5212.0  384.26  5303.0  383.09  5373.7  384.53  5444.4  385.07  5493.0  386.80
  5545.4  388.62  5565.6  390.45  5576.9  390.23  5647.4  393.71  5697.0  394.98
  5727.3  396.46  5737.4  397.66  5757.6  398.23  5777.8  397.72  5802.3  398.64
#Mann=5,-1,0
  4701.6    0.12       0  4883.5     0.1       0  4995.2    0.07       0
  4999.2     0.1       0  5493.0    0.12       0
Bank Sta=4995.2,4999.2
Exp/Cntr=0.3,0.1

Type RM Length L Ch R = 1,5390,524,524,524
BEGIN DESCRIPTION:
Lacy 144 929
END DESCRIPTION:
XS GIS Cut Line= 3
      2713011.32      6860104.86      2712402.26      6860375.30
      2711973.14      6860805.04
#Sta/Elev= 30
  4325.2  395.67  4342.0  395.87  4529.3  385.17  4567.5  383.92  4593.6  383.03
  4604.6  381.74  4642.5  381.83  4751.9  381.63  4776.4  381.26  4923.4  381.77
  4964.4  380.84  4969.9  380.00  4974.6  377.45  4974.8  376.95  4978.6  377.45
  4986.8  380.54  4991.6  380.73  5021.3  380.41  5049.6  382.13  5099.0  382.87
  5176.8  382.68  5364.0  388.89  5381.9  390.90  5410.2  392.31  5431.4  391.62
  5538.5  395.83  5552.1  396.67  5558.7  396.47  5565.7  398.11  5598.9  397.77
#Mann=10,-1,0
  4325.2    0.05       0  4567.5    0.12       0  4642.5     0.1       0
  4751.9    0.12       0  4776.4     0.1       0  4974.6    0.07       0
  4978.6     0.1       0  5364.0    0.12       0  5538.5     0.1       0
  5552.1    0.12       0
Bank Sta=4974.6,4978.6
Exp/Cntr=0.3,0.1

Type RM Length L Ch R = 1,4866,218,218,218
BEGIN DESCRIPTION:
Lacy 144 928
END DESCRIPTION:
XS GIS Cut Line= 3
      2713019.03      6860008.08      2712570.08      6859988.07
      2712060.68      6859986.06
#Sta/Elev= 30
  4557.2  396.40  4599.6  394.33  4680.4  391.49  4740.4  387.90  4750.4  387.48
  4760.4  387.63  4800.5  384.61  4849.5  382.45  4920.6  381.24  4940.6  378.76
  4950.6  376.85  4998.7  376.49  4998.9  375.99  5002.4  375.99  5002.7  376.49
  5020.7  376.89  5100.7  376.74  5120.7  380.24  5146.4  382.06  5180.7  384.48
  5210.7  384.93  5250.7  387.03  5260.7  388.13  5310.7  391.32  5360.7  392.33
  5390.7  392.36  5400.7  392.89  5460.7  392.53  5490.7  393.17  5516.0  392.93
#Mann=5,-1,0
  4557.2    0.05       0  4849.5     0.1       0  4998.7    0.07       0
  5002.7     0.1       0  5146.4    0.12       0
Bank Sta=4998.7,5002.7
Exp/Cntr=0.3,0.1

Type RM Length L Ch R = 1,4648,591,591,591
BEGIN DESCRIPTION:
Lacy 144 927
END DESCRIPTION:
XS GIS Cut Line= 3
      2713017.97      6859814.12      2712684.01      6859799.98
      2712206.91      6859811.65
#Sta/Elev= 30
  4656.0  394.96  4708.0  394.20  4748.1  392.47  4758.1  391.28  4778.1  391.02
  4788.1  389.90  4838.1  387.84  4843.6  387.00  4888.2  384.36  4918.2  379.41
  4938.2  377.41  4948.2  375.08  4956.2  374.93  4956.5  374.43  4960.0  374.43
  4960.2  374.93  4968.3  377.63  4978.3  377.45  5028.3  379.59  5043.2  379.21
  5148.3  380.59  5188.3  382.08  5228.3  383.68  5234.8  384.47  5239.8  384.25
  5268.4  386.95  5318.4  389.26  5358.4  391.88  5458.4  395.18  5467.5  395.02
#Mann=5,-1,0
  4656.0    0.05       0  4843.6     0.1       0  4956.2    0.07       0
  4960.2     0.1       0  5043.2    0.05       0
Bank Sta=4956.2,4960.2
Exp/Cntr=0.3,0.1

Type RM Length L Ch R = 1,4057,314,314,314
BEGIN DESCRIPTION:
Lacy 144 926
END DESCRIPTION:
XS GIS Cut Line= 3
      2713205.14      6859301.28      2712733.93      6859296.91
      2712281.58      6859186.32
#Sta/Elev= 30
  4520.1  390.40  4619.2  386.43  4639.2  386.40  4659.2  384.55  4709.2  382.18
  4719.2  382.76  4749.2  380.47  4809.3  378.28  4882.5  377.22  4909.3  376.48
  4929.3  374.69  4979.3  374.90  4981.5  373.59  4985.8  371.04  4986.0  370.54
  4989.8  371.04  4994.8  371.88  5009.8  377.11  5036.4  380.19  5041.5  379.48
  5061.3  380.23  5082.6  381.95  5119.7  385.44  5166.5  387.50  5174.5  388.97
  5195.1  389.34  5203.0  391.19  5277.4  394.29  5349.5  394.99  5457.0  393.39
#Mann=6,-1,0
  4520.1    0.05       0  4882.5     0.1       0  4981.5    0.12       0
  4985.8    0.07       0  4989.8    0.12       0  5082.6    0.05       0
Bank Sta=4985.8,4989.8
Exp/Cntr=0.3,0.1

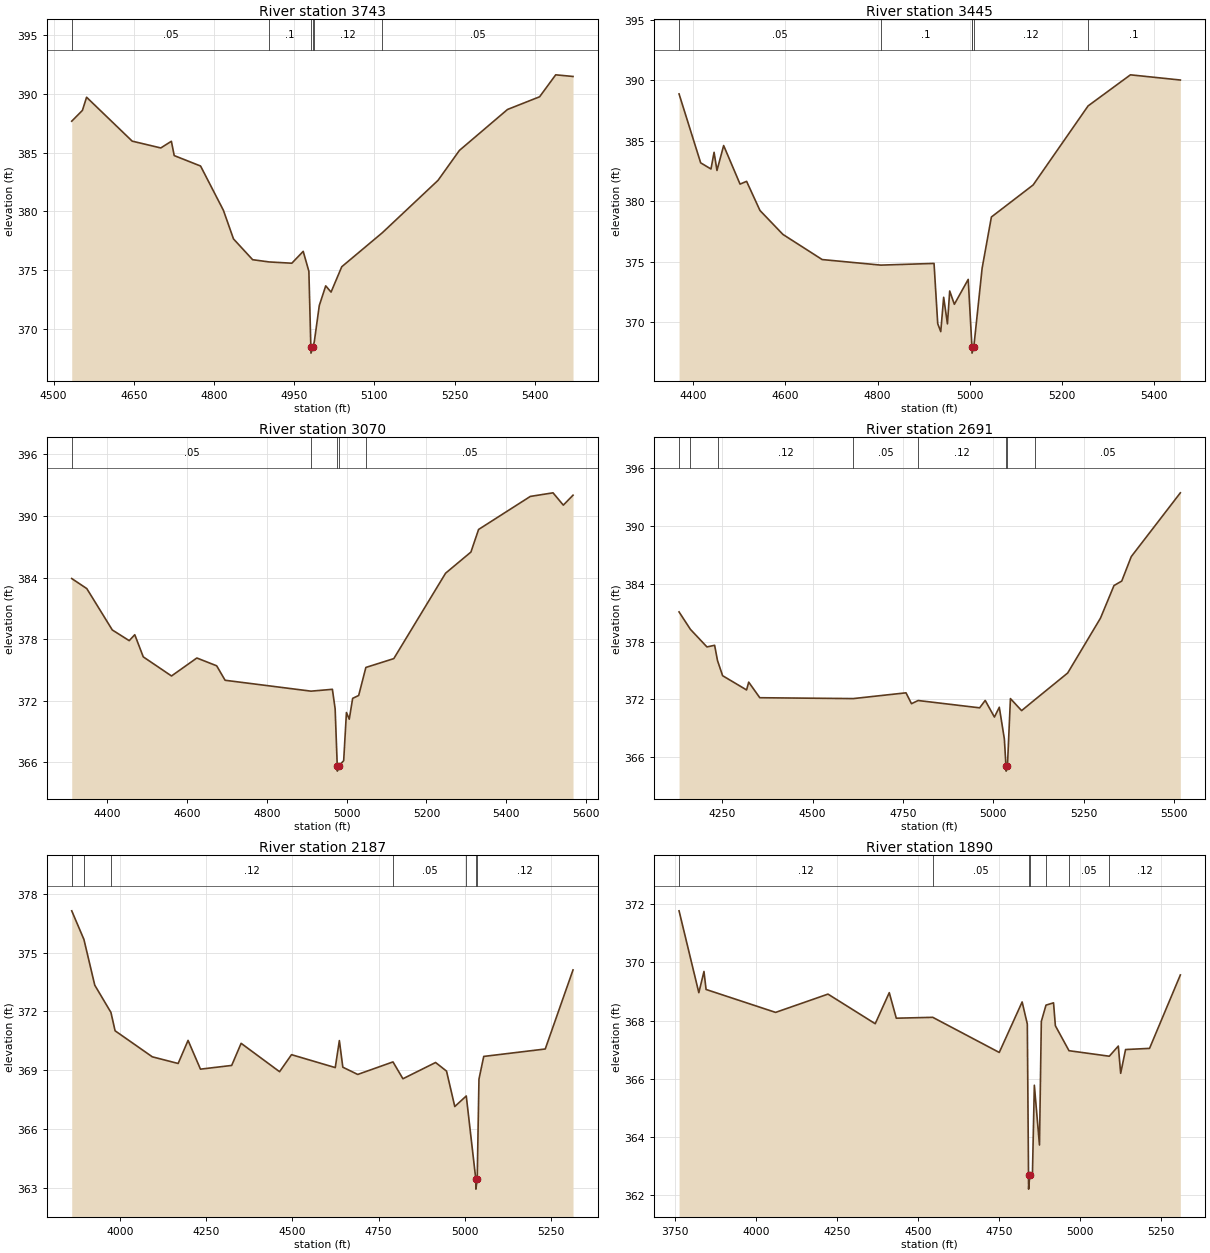
Type RM Length L Ch R = 1,3743,298,298,298
BEGIN DESCRIPTION:
Lacy 144 925
END DESCRIPTION:
XS GIS Cut Line= 3
      2713262.04      6859212.09      2712824.55      6859050.11
      2712353.57      6859036.06
#Sta/Elev= 30
  4533.9  387.69  4553.9  388.61  4561.7  389.73  4647.0  385.99  4700.5  385.41
  4720.3  385.98  4725.6  384.76  4774.9  383.87  4817.6  380.10  4836.5  377.66
  4872.3  375.89  4902.8  375.70  4945.6  375.59  4966.9  376.60  4977.5  374.90
  4981.2  368.43  4981.4  367.93  4985.2  368.43  4987.7  368.92  4997.0  371.99
  5009.0  373.66  5019.0  373.13  5039.0  375.29  5115.0  378.19  5219.1  382.65
  5259.1  385.20  5349.1  388.69  5409.1  389.77  5439.2  391.64  5471.6  391.50
#Mann=6,-1,0
  4533.9    0.05       0  4902.8     0.1       0  4981.2    0.07       0
  4985.2     0.1       0  4987.7    0.12       0  5115.0    0.05       0
Bank Sta=4981.2,4985.2
Exp/Cntr=0.3,0.1

Type RM Length L Ch R = 1,3445,375,375,375
BEGIN DESCRIPTION:
Lacy 144 3434
END DESCRIPTION:
XS GIS Cut Line= 3
      2713310.89      6859142.56      2712843.13      6858782.51
      2712348.32      6858836.20
#Sta/Elev= 30
  4369.1  388.88  4416.0  383.18  4438.4  382.67  4445.1  384.05  4451.4  382.55
  4465.9  384.61  4501.5  381.42  4515.7  381.65  4544.7  379.24  4594.5  377.26
  4679.7  375.18  4807.0  374.72  4922.5  374.86  4930.5  369.88  4937.1  369.22
  4943.4  372.06  4951.6  369.86  4956.5  372.58  4966.6  371.48  4996.7  373.54
  5004.2  368.35  5004.8  367.94  5005.0  367.44  5008.8  367.94  5026.9  374.47
  5047.0  378.70  5137.6  381.35  5256.9  387.89  5348.8  390.46  5457.1  390.03
#Mann=6,-1,0
  4369.1    0.05       0  4807.0     0.1       0  5004.2    0.12       0
  5004.8    0.07       0  5008.8    0.12       0  5256.9     0.1       0
Bank Sta=5004.8,5008.8
Exp/Cntr=0.3,0.1

Type RM Length L Ch R = 1,3070,379,379,379
BEGIN DESCRIPTION:
Lacy 144 3433
END DESCRIPTION:
XS GIS Cut Line= 3
      2713495.34      6859065.21      2713016.96      6858564.54
      2712484.33      6858379.30
#Sta/Elev= 30
  4311.0  383.90  4348.8  382.92  4412.7  378.89  4455.1  377.85  4469.0  378.43
  4490.3  376.27  4561.1  374.41  4624.6  376.16  4674.3  375.40  4695.4  373.99
  4910.8  372.93  4964.3  373.11  4971.2  371.21  4976.5  365.64  4976.7  365.14
  4980.5  365.64  4992.6  366.16  4999.5  370.85  5006.6  370.20  5015.1  372.23
  5030.2  372.51  5048.2  375.24  5118.2  376.10  5248.0  384.42  5311.5  386.48
  5330.7  388.68  5460.4  391.90  5517.3  392.25  5543.1  391.05  5567.4  392.02
#Mann=5,-1,0
  4311.0    0.05       0  4910.8    0.12       0  4976.5    0.07       0
  4980.5    0.12       0  5048.2    0.05       0
Bank Sta=4976.5,4980.5
Exp/Cntr=0.3,0.1

Type RM Length L Ch R = 1,2691,504,504,504
BEGIN DESCRIPTION:
Lacy 144 3435
END DESCRIPTION:
XS GIS Cut Line= 3
      2713610.89      6858973.17      2713146.39      6858231.28
      2712648.09      6858115.37
#Sta/Elev= 30
  4130.7  381.09  4162.1  379.28  4207.9  377.45  4229.1  377.62  4237.1  376.03
  4251.2  374.46  4317.5  372.98  4323.4  373.79  4354.1  372.17  4612.6  372.08
  4758.6  372.68  4773.7  371.55  4792.2  371.88  4962.3  371.12  4977.7  371.89
  5003.2  370.16  5016.7  371.18  5030.7  367.89  5035.2  365.04  5035.5  364.54
  5039.2  365.04  5047.5  372.08  5078.4  370.83  5115.0  371.96  5205.9  374.74
  5296.6  380.44  5334.0  383.83  5355.5  384.30  5381.8  386.84  5517.6  393.47
#Mann=8,-1,0
  4130.7    0.12       0  4162.1    0.05       0  4237.1    0.12       0
  4612.6    0.05       0  4792.2    0.12       0  5035.2    0.07       0
  5039.2    0.12       0  5115.0    0.05       0
Bank Sta=5035.2,5039.2
Exp/Cntr=0.3,0.1

Type RM Length L Ch R = 1,2187,297,297,297
BEGIN DESCRIPTION:
Lacy 144 3436
END DESCRIPTION:
XS GIS Cut Line= 3
      2713864.58      6858773.37      2713317.95      6857821.46
      2712979.25      6857714.46
#Sta/Elev= 30
  3860.7  377.14  3896.0  375.68  3927.5  373.34  3974.3  371.95  3986.4  371.01
  4094.3  369.68  4169.1  369.34  4197.9  370.52  4233.8  369.05  4324.3  369.24
  4351.7  370.37  4463.1  368.92  4497.7  369.79  4624.5  369.13  4636.4  370.51
  4646.4  369.15  4689.6  368.78  4791.8  369.42  4820.6  368.56  4915.3  369.39
  4947.0  368.95  4970.9  367.14  5004.2  367.68  5031.9  363.42  5032.1  362.92
  5035.9  363.42  5041.0  368.54  5054.8  369.70  5233.1  370.08  5313.6  374.12
#Mann=7,-1,0
  3860.7    0.12       0  3896.0    0.05       0  3974.3    0.12       0
  4791.8    0.05       0  5004.2    0.12       0  5031.9    0.03       0
  5035.9    0.12       0
Bank Sta=5031.9,5035.9
Exp/Cntr=0.3,0.1

Type RM Length L Ch R = 1,1890,571,571,571
BEGIN DESCRIPTION:
Lacy 144 3439
END DESCRIPTION:
XS GIS Cut Line= 3
      2713968.32      6858653.82      2713361.25      6857573.09
      2713084.86      6857433.72
#Sta/Elev= 30
  3761.4  371.78  3822.5  368.96  3838.4  369.69  3844.9  369.07  4059.7  368.28
  4221.6  368.91  4367.6  367.89  4411.0  368.96  4432.7  368.08  4545.4  368.11
  4750.9  366.90  4821.6  368.64  4837.6  367.88  4841.3  362.69  4841.6  362.19
  4845.3  362.69  4853.5  362.74  4859.3  365.77  4875.2  363.71  4880.9  367.97
  4895.3  368.53  4918.6  368.61  4924.3  367.82  4966.4  366.96  5091.0  366.77
  5118.8  367.12  5126.1  366.18  5141.2  367.00  5215.3  367.04  5310.5  369.57
#Mann=7,-1,0
  3761.4    0.12       0  4545.4    0.05       0  4841.3    0.03       0
  4845.3    0.05       0  4895.3     0.1       0  4966.4    0.05       0
  5091.0    0.12       0
Bank Sta=4841.3,4845.3
Exp/Cntr=0.3,0.1

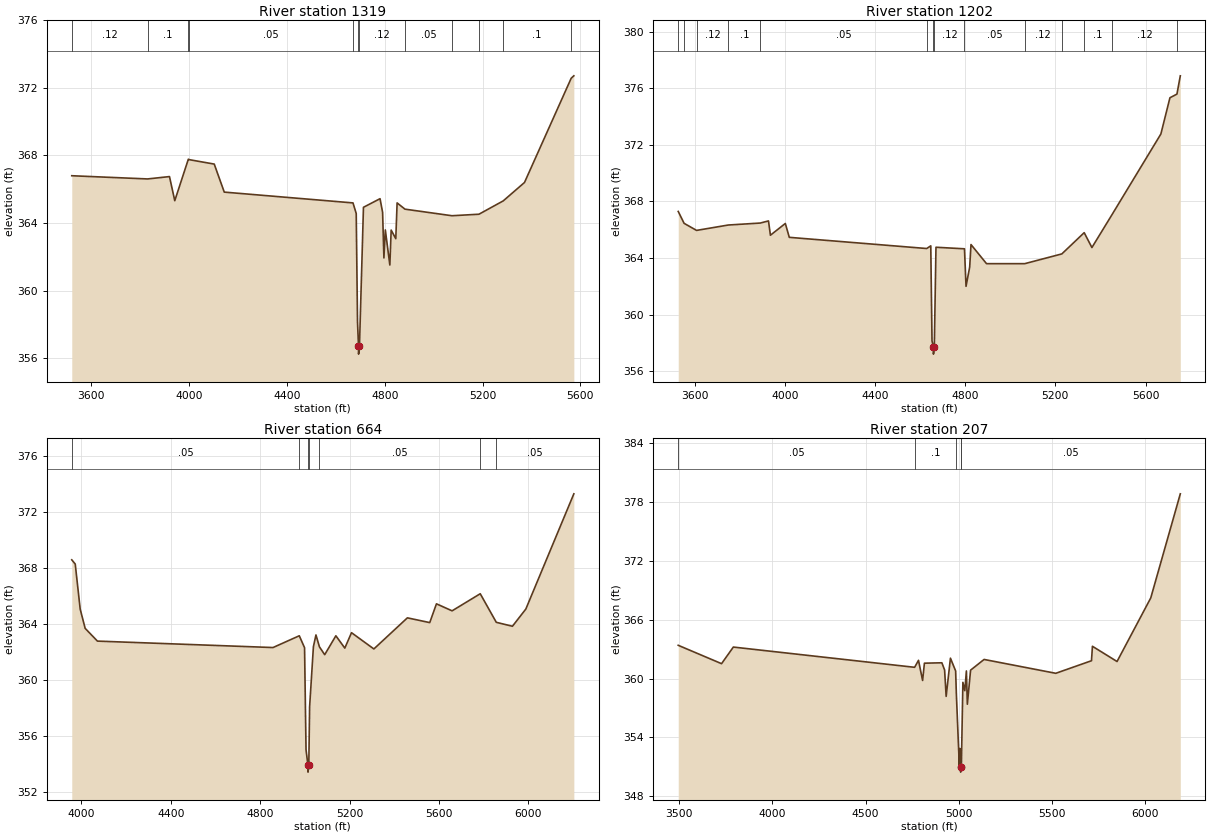
Type RM Length L Ch R = 1,1319,117,117,117
BEGIN DESCRIPTION:
Lacy 144 3440
END DESCRIPTION:
XS GIS Cut Line= 3
      2714142.79      6858422.32      2713607.58      6857077.23
      2713005.21      6857016.28
#Sta/Elev= 30
  3520.1  366.80  3830.1  366.61  3919.7  366.75  3941.3  365.32  3996.8  367.78
  4001.4  367.75  4102.7  367.49  4143.7  365.83  4670.1  365.19  4683.3  364.56
  4688.6  358.12  4692.6  356.73  4692.9  356.23  4696.6  356.73  4712.9  364.93
  4780.7  365.44  4791.2  364.63  4796.5  361.93  4802.3  363.59  4820.8  361.51
  4826.2  363.58  4845.1  363.07  4850.5  365.19  4882.6  364.82  5074.9  364.43
  5185.2  364.52  5284.5  365.31  5371.4  366.40  5562.5  372.58  5573.2  372.72
#Mann=12,-1,0
  3520.1    0.12       0  3830.1     0.1       0  3996.8    0.12       0
  4001.4    0.05       0  4670.1    0.12       0  4692.6    0.05       0
  4696.6    0.12       0  4882.6    0.05       0  5074.9    0.12       0
  5185.2    0.05       0  5284.5     0.1       0  5562.5    0.12       0
Bank Sta=4692.6,4696.6
Exp/Cntr=0.3,0.1

Type RM Length L Ch R = 1,1202,538,538,538
BEGIN DESCRIPTION:
Lacy 144 3438
END DESCRIPTION:
XS GIS Cut Line= 3
      2714225.17      6858313.38      2713612.54      6856963.74
      2712870.11      6856905.17
#Sta/Elev= 30
  3527.3  367.29  3553.3  366.45  3608.6  365.95  3749.2  366.33  3891.2  366.47
  3927.6  366.62  3936.2  365.61  4002.3  366.44  4019.9  365.46  4629.3  364.67
  4647.4  364.86  4652.9  358.15  4659.1  357.71  4659.3  357.21  4663.1  357.71
  4670.5  364.76  4796.9  364.65  4803.8  362.00  4820.0  363.36  4825.8  364.95
  4894.7  363.60  5064.2  363.60  5228.8  364.29  5327.9  365.79  5362.1  364.74
  5450.4  367.04  5668.0  372.76  5708.2  375.32  5739.3  375.58  5754.2  376.87
#Mann=14,-1,0
  3527.3    0.12       0  3553.3     0.1       0  3608.6    0.12       0
  3749.2     0.1       0  3891.2    0.05       0  4629.3    0.12       0
  4659.1    0.05       0  4663.1    0.12       0  4796.9    0.05       0
  5064.2    0.12       0  5228.8    0.05       0  5327.9     0.1       0
  5450.4    0.12       0  5739.3    0.05       0
Bank Sta=4659.1,4663.1
Exp/Cntr=0.3,0.1

Type RM Length L Ch R = 1,664,457,457,457
BEGIN DESCRIPTION:
Lacy 144 3437
END DESCRIPTION:
XS GIS Cut Line= 3
      2714573.06      6857794.96      2714093.20      6856800.24
      2712951.34      6856807.23
#Sta/Elev= 30
  3957.2  368.59  3972.7  368.29  3994.9  365.07  4017.1  363.70  4072.0  362.79
  4857.5  362.33  4975.1  363.17  4998.7  362.32  5005.3  355.04  5013.7  353.94
  5014.0  353.44  5017.7  353.94  5021.3  358.09  5038.3  362.39  5049.7  363.23
  5065.3  362.38  5088.8  361.82  5138.8  363.17  5178.8  362.29  5208.8  363.39
  5308.8  362.23  5458.8  364.45  5558.8  364.11  5588.8  365.45  5658.8  364.95
  5784.7  366.17  5856.6  364.13  5928.8  363.85  5988.8  365.08  6203.5  373.30
#Mann=7,-1,0
  3957.2    0.05       0  4975.1    0.12       0  5013.7    0.07       0
  5017.7    0.12       0  5065.3    0.05       0  5784.7    0.12       0
  5856.6    0.05       0
Bank Sta=5013.7,5017.7
Exp/Cntr=0.3,0.1

Type RM Length L Ch R = 1,207,0,0,0
BEGIN DESCRIPTION:
Lacy 144 3441
END DESCRIPTION:
XS GIS Cut Line= 4
      2714687.71      6857711.65      2714320.92      6856603.21
      2714024.06      6856435.67      2712877.74      6856736.27
#Sta/Elev= 30
  3494.9  363.38  3727.3  361.51  3790.5  363.20  4763.0  361.14  4783.8  361.85
  4805.9  359.80  4815.6  361.56  4909.2  361.60  4923.9  360.87  4932.2  358.18
  4955.2  362.07  4983.1  360.77  4986.8  358.51  5003.0  351.02  5005.5  352.88
  5009.7  350.97  5009.9  350.47  5013.7  350.97  5022.0  359.61  5032.3  358.76
  5040.8  360.77  5045.9  357.38  5063.3  360.85  5135.7  361.94  5520.3  360.53
  5711.9  361.81  5717.0  363.28  5849.0  361.73  6029.8  368.20  6188.4  378.80
#Mann=5,-1,0
  3494.9    0.05       0  4763.0     0.1       0  4986.8    0.05       0
  5009.7   0.035       0  5013.7    0.05       0
Bank Sta=5009.7,5013.7
Exp/Cntr=0.3,0.1

Chan Stop Cuts=-1