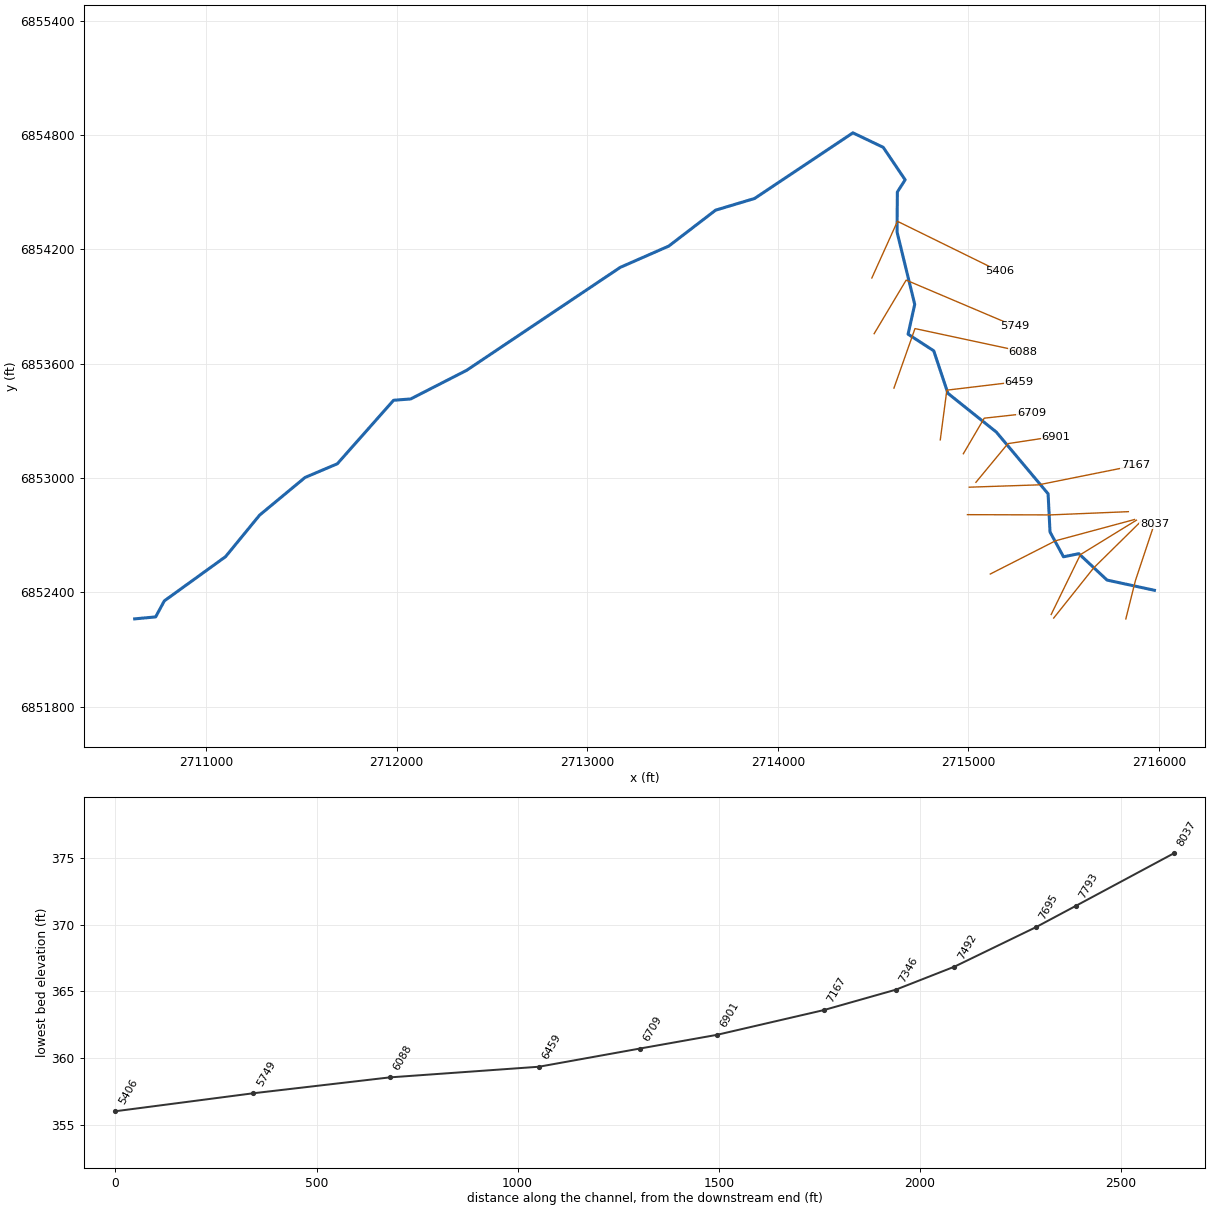
--- Lacy 145.prj (project) ---

Proj Title=Lacy 145 Base Level Engineering
Current Plan=p01
Default Exp/Contr=0.3,0.1
English Units
Geom File=g01
Flow File=f01
Plan File=p01
BEGIN DESCRIPTION:
Lacy 145
END DESCRIPTION:

--- Lacy 145.p01 (plan) ---

Plan Title=Multiple Run
Short Identifier=Multiple
Geom File=g01
Flow File=f01
Subcritical Flow
K Sum by GR= 0
Std Step Tol= 0.01
Critical Tol= 0.01
Num of Std Step Trials= 20
Max Error Tol= 0.3
Flow Tol Ratio= 0.001
Split Flow NTrial= 30
Split Flow Tol= 0.02
Split Flow Ratio= 0.02
Log Output Level= 0
Friction Slope Method= 1
Unsteady Friction Slope Method= 2
Unsteady Bridges Friction Slope Method= 1
Parabolic Critical Depth
Global Vel Dist=  1 , 1 , 1
Global Log Level= 0
CheckData=True
Encroach Param= -1, 0, 0, 0
BEGIN DESCRIPTION:
Multiple Run
END DESCRIPTION:

--- Lacy 145.f01 (steady flow) ---

Flow Title=Multiple
Number of Profiles=7
Profile Names=10-year,25-year,50-year,1pct_min,100-year,1pct_plu,500-year
River Rch & RM= Lacy 145,Reach-1,8037
     435     569     675     398     794    1584    1095
Boundary for River Rch & Prof#=Lacy 145,Reach-1,1
Up Type=0
Dn Type=3
Dn Slope=0.005
Boundary for River Rch & Prof#=Lacy 145,Reach-1,2
Up Type=0
Dn Type=3
Dn Slope=0.005
Boundary for River Rch & Prof#=Lacy 145,Reach-1,3
Up Type=0
Dn Type=3
Dn Slope=0.005
Boundary for River Rch & Prof#=Lacy 145,Reach-1,4
Up Type=0
Dn Type=3
Dn Slope=0.005
Boundary for River Rch & Prof#=Lacy 145,Reach-1,5
Up Type=0
Dn Type=3
Dn Slope=0.005
Boundary for River Rch & Prof#=Lacy 145,Reach-1,6
Up Type=0
Dn Type=3
Dn Slope=0.005
Boundary for River Rch & Prof#=Lacy 145,Reach-1,7
Up Type=0
Dn Type=3
Dn Slope=0.005

--- Lacy 145.g01 (geometry) ---

Geom Title=Existing Conditions

River Reach=Lacy 145,Reach-1
Reach XY= 30
      2715976.00      6852411.00      2715727.47      6852464.54
      2715579.32      6852602.99      2715499.01      6852586.64
      2715428.24      6852716.93      2715418.19      6852917.19
      2715146.42      6853241.23      2714892.64      6853444.32
      2714818.25      6853667.45      2714683.65      6853754.55
      2714718.44      6853911.00      2714625.71      6854290.82
      2714627.39      6854500.57      2714668.19      6854564.41
      2714553.16      6854734.86      2714394.19      6854810.90
      2713878.42      6854466.54      2713673.71      6854405.16
      2713428.29      6854216.85      2713173.71      6854105.15
      2712367.38      6853564.84      2712074.34      6853414.86
      2711984.34      6853407.84      2711689.21      6853074.62
      2711519.94      6853002.86      2711281.62      6852805.38
      2711102.82      6852587.30      2710781.63      6852355.35
      2710736.15      6852271.34      2710626.00      6852261.00

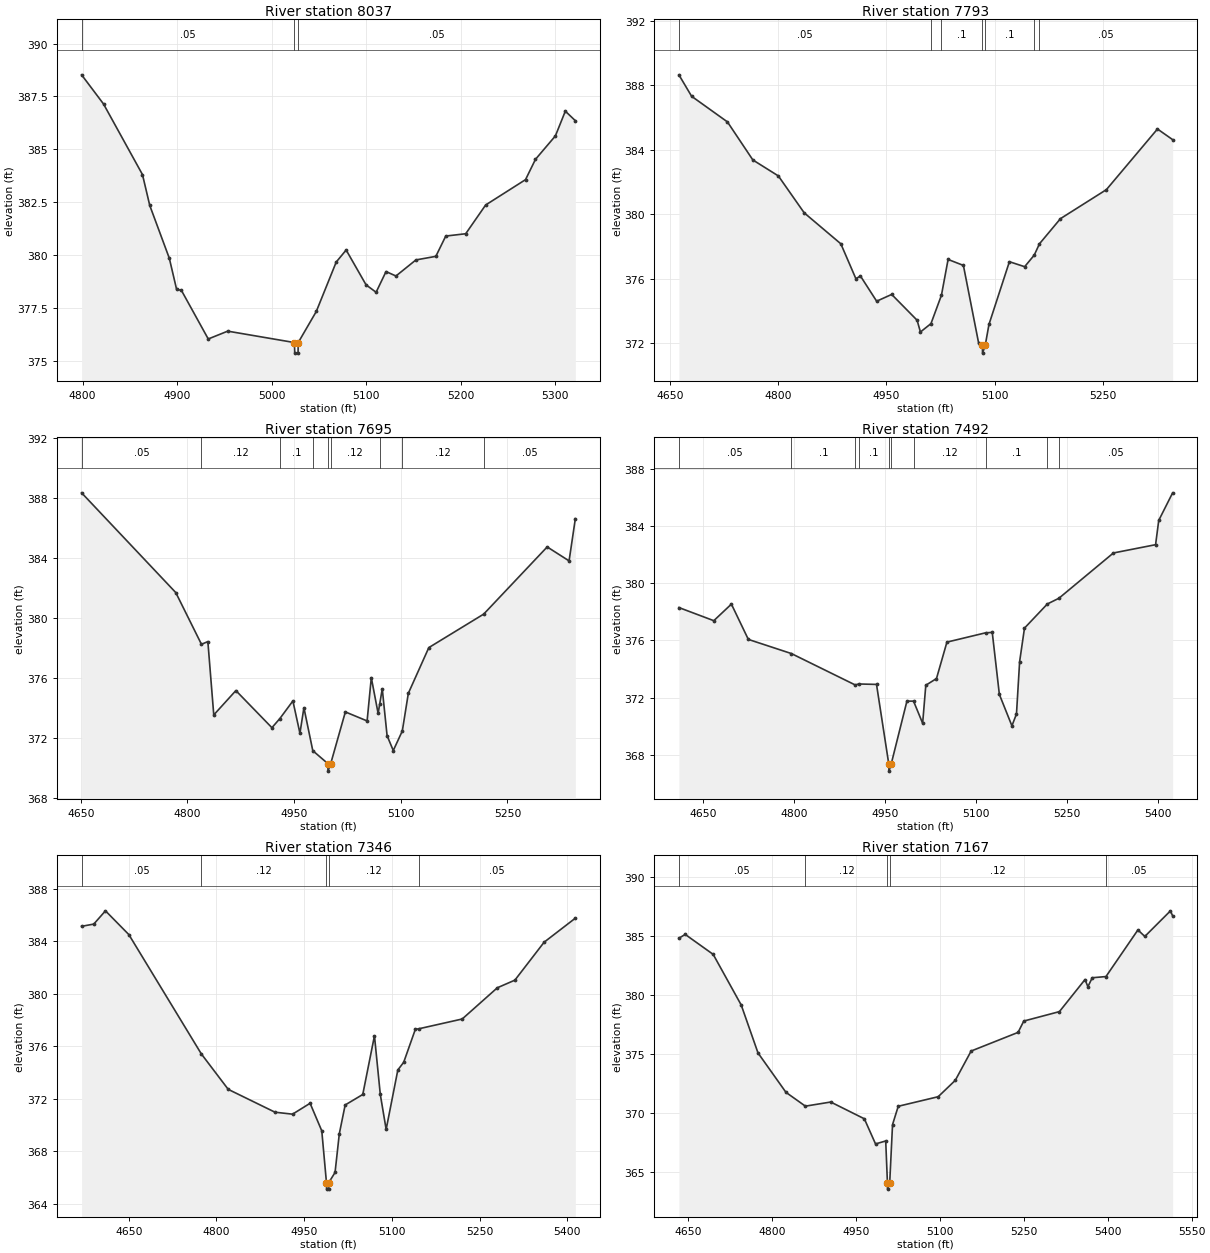
Type RM Length L Ch R = 1,8037,244,244,244
BEGIN DESCRIPTION:
Lacy 145 47
END DESCRIPTION:
XS GIS Cut Line= 3
      2715826.00      6852261.01      2715876.00      6852461.00
      2715976.01      6852761.03
#Sta/Elev= 30
  4798.9  388.52  4822.1  387.14  4863.3  383.80  4871.0  382.34  4891.7  379.84
  4899.4  378.37  4904.5  378.32  4932.9  376.02  4953.5  376.39  5024.1  375.85
  5024.4  375.35  5027.9  375.35  5028.1  375.85  5047.2  377.32  5068.3  379.66
  5078.8  380.23  5099.9  378.58  5110.5  378.23  5121.0  379.21  5131.5  379.00
  5152.6  379.76  5173.7  379.93  5184.2  380.89  5205.3  381.00  5226.4  382.36
  5268.6  383.56  5279.1  384.52  5300.2  385.63  5310.7  386.80  5321.3  386.35
#Mann=3,-1,0
  4798.9    0.05       0  5024.1    0.04       0  5028.1    0.05       0
Bank Sta=5024.1,5028.1
Exp/Cntr=0.3,0.1

Type RM Length L Ch R = 1,7793,98,98,98
BEGIN DESCRIPTION:
Lacy 145 907
END DESCRIPTION:
XS GIS Cut Line= 3
      2715447.59      6852265.35      2715656.69      6852527.68
      2715904.72      6852771.96
#Sta/Elev= 30
  4662.7  388.66  4680.3  387.33  4729.9  385.74  4765.1  383.38  4800.4  382.39
  4836.2  380.10  4886.9  378.18  4907.7  376.02  4914.1  376.18  4936.5  374.62
  4957.3  375.04  4992.5  373.44  4997.1  372.71  5011.7  373.23  5026.2  374.99
  5035.4  377.21  5056.6  376.84  5077.8  372.00  5082.9  371.90  5083.1  371.40
  5086.9  371.90  5092.0  373.18  5120.3  377.07  5141.4  376.76  5154.7  377.48
  5161.9  378.18  5191.0  379.74  5254.6  381.54  5325.3  385.30  5346.3  384.64
#Mann=7,-1,0
  4662.7    0.05       0  5011.7    0.12       0  5026.2     0.1       0
  5082.9    0.04       0  5086.9     0.1       0  5154.7    0.12       0
  5161.9    0.05       0
Bank Sta=5082.9,5086.9
Exp/Cntr=0.3,0.1

Type RM Length L Ch R = 1,7695,203,203,203
BEGIN DESCRIPTION:
Lacy 145 908
END DESCRIPTION:
XS GIS Cut Line= 3
      2715434.32      6852283.97      2715587.63      6852598.03
      2715881.57      6852778.69
#Sta/Elev= 30
  4651.1  388.34  4783.6  381.70  4819.7  378.26  4828.7  378.44  4837.0  373.56
  4868.1  375.18  4918.8  372.71  4930.0  373.32  4948.3  374.49  4958.2  372.34
  4963.8  374.04  4976.3  371.18  4997.5  370.32  4997.7  369.82  5001.5  370.32
  5022.1  373.76  5052.7  373.16  5058.6  376.04  5068.2  373.66  5070.5  374.31
  5074.0  375.30  5080.8  372.18  5089.5  371.19  5102.2  372.49  5110.7  375.00
  5139.5  378.04  5216.7  380.27  5306.0  384.74  5336.8  383.81  5345.6  386.62
#Mann=9,-1,0
  4651.1    0.05       0  4819.7    0.12       0  4930.0     0.1       0
  4976.3    0.12       0  4997.5    0.07       0  5001.5    0.12       0
  5070.5     0.1       0  5102.2    0.12       0  5216.7    0.05       0
Bank Sta=4997.5,5001.5
Exp/Cntr=0.3,0.1

Type RM Length L Ch R = 1,7492,146,146,146
BEGIN DESCRIPTION:
Lacy 145 906
END DESCRIPTION:
XS GIS Cut Line= 3
      2715114.79      6852496.26      2715457.52      6852670.76
      2715871.65      6852782.37
#Sta/Elev= 30
  4610.6  378.30  4668.1  377.38  4697.1  378.54  4725.0  376.07  4795.9  375.08
  4901.2  372.88  4906.7  372.95  4936.2  372.92  4956.4  367.35  4956.7  366.85
  4960.4  367.35  4986.3  371.75  4997.2  371.75  5012.2  370.20  5017.4  372.86
  5035.0  373.33  5052.2  375.88  5115.8  376.53  5126.9  376.56  5138.6  372.22
  5159.3  370.02  5166.8  370.85  5172.0  374.52  5180.0  376.86  5217.7  378.55
  5236.7  378.95  5326.5  382.12  5396.0  382.70  5401.2  384.40  5424.1  386.33
#Mann=10,-1,0
  4610.6    0.05       0  4795.9     0.1       0  4901.2    0.12       0
  4906.7     0.1       0  4956.4    0.07       0  4960.4     0.1       0
  4997.2    0.12       0  5115.8     0.1       0  5217.7    0.12       0
  5236.7    0.05       0
Bank Sta=4956.4,4960.4
Exp/Cntr=0.3,0.1

Type RM Length L Ch R = 1,7346,179,179,179
BEGIN DESCRIPTION:
Lacy 145 903
END DESCRIPTION:
XS GIS Cut Line= 3
      2714995.18      6852807.78      2715428.71      6852806.41
      2715839.33      6852823.45
#Sta/Elev= 30
  4569.3  385.14  4590.1  385.31  4610.1  386.32  4650.1  384.51  4774.1  375.42
  4820.1  372.72  4900.1  370.98  4930.1  370.83  4960.1  371.66  4980.1  369.56
  4988.1  365.62  4988.4  365.12  4991.9  365.12  4992.1  365.62  5002.8  366.39
  5010.1  369.34  5020.1  371.53  5050.2  372.33  5070.2  376.80  5080.2  372.33
  5090.2  369.67  5110.2  374.20  5120.2  374.78  5140.2  377.30  5145.6  377.33
  5220.3  378.08  5280.4  380.46  5310.4  381.04  5360.4  383.93  5413.8  385.76
#Mann=5,-1,0
  4569.3    0.05       0  4774.1    0.12       0  4988.1    0.07       0
  4992.1    0.12       0  5145.6    0.05       0
Bank Sta=4988.1,4992.1
Exp/Cntr=0.3,0.1

Type RM Length L Ch R = 1,7167,266,266,266
BEGIN DESCRIPTION:
Lacy 145 904
END DESCRIPTION:
XS GIS Cut Line= 3
      2715004.71      6852951.88      2715367.28      6852964.02
      2715876.93      6853066.35
#Sta/Elev= 30
  4633.4  384.85  4644.7  385.17  4694.7  383.48  4744.8  379.19  4774.8  375.13
  4824.8  371.79  4859.5  370.62  4904.8  370.97  4964.9  369.55  4984.9  367.42
  5003.1  367.67  5006.2  364.09  5006.4  363.59  5010.2  364.09  5015.3  369.06
  5025.5  370.61  5096.9  371.42  5127.5  372.81  5155.8  375.29  5239.7  376.87
  5249.9  377.83  5313.6  378.63  5359.4  381.35  5364.5  380.74  5372.3  381.50
  5396.8  381.60  5453.9  385.55  5466.3  385.00  5512.1  387.17  5516.0  386.74
#Mann=5,-1,0
  4633.4    0.05       0  4859.5    0.12       0  5006.2    0.07       0
  5010.2    0.12       0  5396.8    0.05       0
Bank Sta=5006.2,5010.2
Exp/Cntr=0.3,0.1

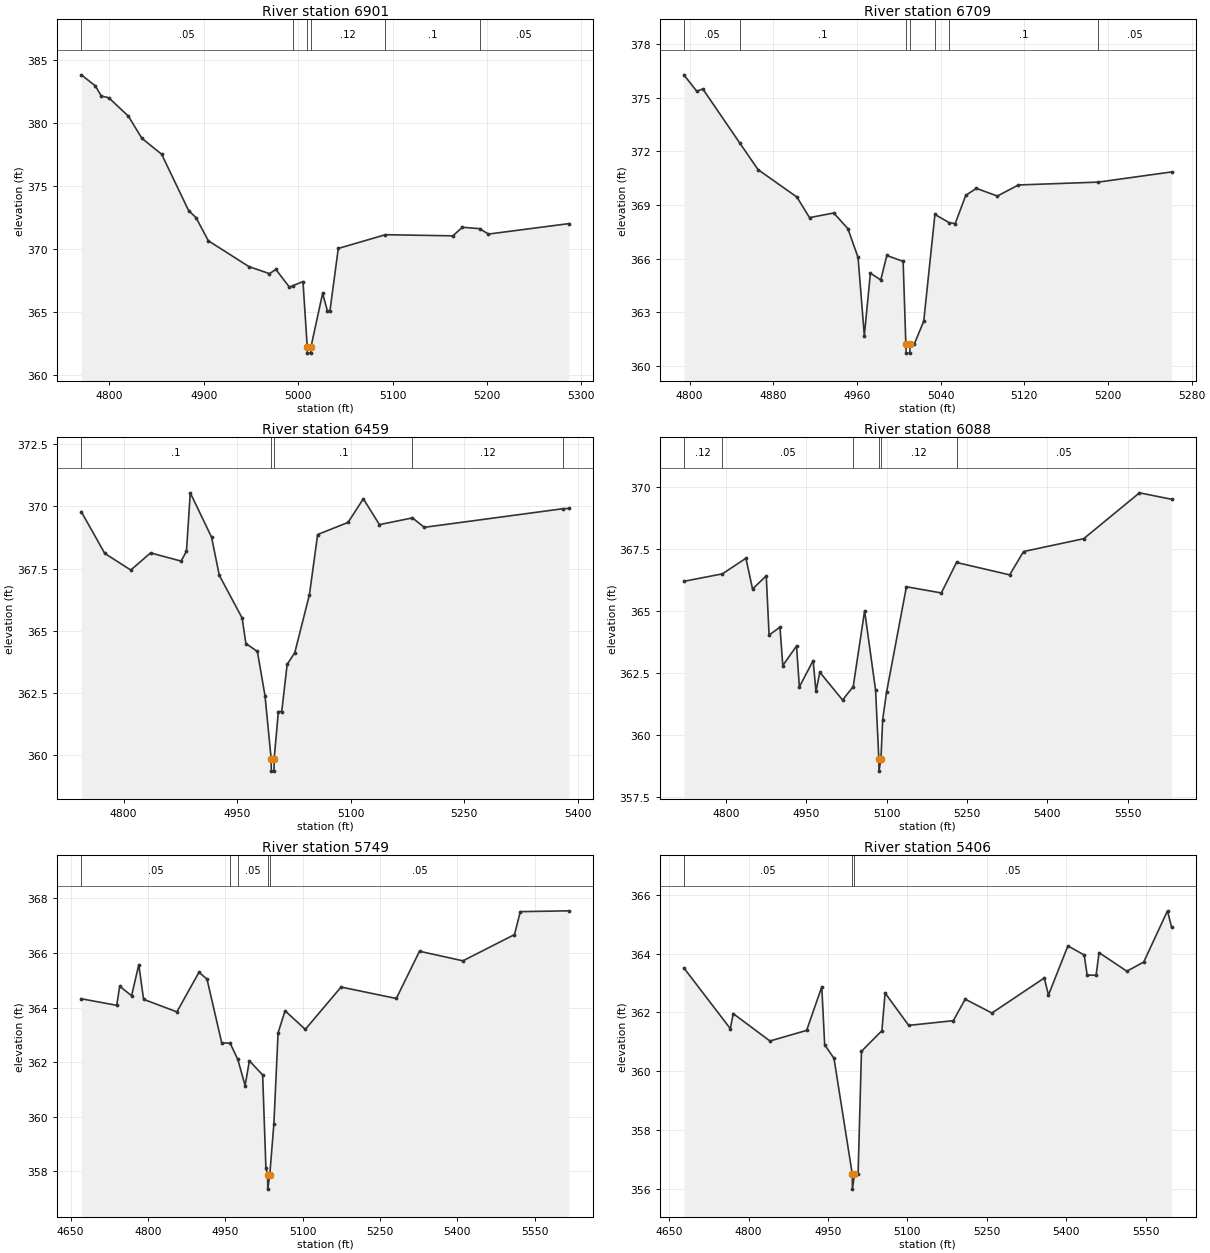
Type RM Length L Ch R = 1,6901,192,192,192
BEGIN DESCRIPTION:
Lacy 145 3442
END DESCRIPTION:
XS GIS Cut Line= 4
      2715039.39      6852977.30      2715207.28      6853180.36
      2715424.95      6853213.52      2715457.98      6853214.28
#Sta/Elev= 30
  4770.2  383.82  4785.0  382.95  4791.4  382.14  4799.3  382.00  4820.1  380.54
  4834.4  378.78  4855.3  377.52  4883.9  373.05  4891.8  372.48  4904.8  370.65
  4947.8  368.60  4969.6  368.04  4976.4  368.37  4990.8  366.96  4994.6  367.09
  5005.1  367.41  5009.6  362.23  5009.8  361.73  5013.3  361.73  5013.6  362.23
  5025.9  366.48  5030.9  365.10  5033.7  365.10  5042.5  370.04  5092.5  371.13
  5163.9  371.04  5174.0  371.72  5192.2  371.61  5201.6  371.18  5286.9  372.01
#Mann=6,-1,0
  4770.2    0.05       0  4994.6    0.12       0  5009.6    0.07       0
  5013.6    0.12       0  5092.5     0.1       0  5192.2    0.05       0
Bank Sta=5009.6,5013.6
Exp/Cntr=0.3,0.1

Type RM Length L Ch R = 1,6709,250,250,250
BEGIN DESCRIPTION:
Lacy 145 3443
END DESCRIPTION:
XS GIS Cut Line= 3
      2714973.57      6853127.39      2715083.06      6853313.87
      2715331.51      6853341.20
#Sta/Elev= 30
  4794.5  376.29  4806.8  375.37  4812.6  375.50  4847.9  372.47  4865.4  370.98
  4902.6  369.44  4914.6  368.29  4937.8  368.55  4951.3  367.67  4961.0  366.06
  4967.0  361.68  4972.8  365.18  4982.7  364.80  4988.5  366.17  5004.1  365.84
  5006.7  361.20  5007.0  360.70  5010.5  360.70  5010.7  361.20  5014.7  361.20
  5023.8  362.49  5034.5  368.47  5048.4  368.00  5053.9  367.96  5064.0  369.54
  5074.1  369.93  5094.2  369.50  5114.3  370.12  5190.7  370.28  5260.7  370.85
#Mann=7,-1,0
  4794.5    0.05       0  4847.9     0.1       0  5006.7    0.07       0
  5010.7     0.1       0  5034.5    0.12       0  5048.4     0.1       0
  5190.7    0.05       0
Bank Sta=5006.7,5010.7
Exp/Cntr=0.3,0.1

Type RM Length L Ch R = 1,6459,371,371,371
BEGIN DESCRIPTION:
Lacy 145 3445
END DESCRIPTION:
XS GIS Cut Line= 3
      2714852.55      6853200.28      2714886.94      6853460.88
      2715265.77      6853506.23
#Sta/Elev= 30
  4744.2  369.79  4775.2  368.11  4809.6  367.44  4835.7  368.13  4876.1  367.80
  4883.2  368.20  4888.2  370.55  4916.4  368.76  4926.5  367.23  4956.7  365.51
  4961.7  364.48  4976.9  364.16  4987.0  362.37  4995.1  359.84  4995.3  359.34
  4998.8  359.34  4999.1  359.84  5004.6  361.74  5009.1  361.74  5016.2  363.64
  5026.3  364.11  5045.7  366.45  5056.5  368.87  5096.8  369.36  5116.9  370.31
  5138.2  369.27  5181.8  369.54  5197.5  369.16  5380.6  369.91  5388.6  369.92
#Mann=5,-1,0
  4744.2     0.1       0  4995.1    0.07       0  4999.1     0.1       0
  5181.8    0.12       0  5380.6    0.05       0
Bank Sta=4995.1,4999.1
Exp/Cntr=0.3,0.1

Type RM Length L Ch R = 1,6088,339,339,339
BEGIN DESCRIPTION:
Lacy 145 3444
END DESCRIPTION:
XS GIS Cut Line= 3
      2714609.52      6853471.82      2714719.80      6853783.90
      2715286.09      6853662.75
#Sta/Elev= 30
  4721.8  366.20  4793.6  366.50  4837.6  367.13  4849.9  365.89  4875.5  366.42
  4880.8  364.03  4901.1  364.35  4906.4  362.80  4932.0  363.59  4937.3  361.94
  4963.0  363.00  4968.3  361.76  4975.5  362.53  5017.9  361.41  5037.8  361.95
  5059.1  365.01  5079.6  361.80  5085.6  359.04  5085.9  358.54  5089.6  359.04
  5092.8  360.62  5100.0  361.72  5137.1  365.98  5202.3  365.73  5230.6  366.96
  5329.8  366.46  5355.7  367.40  5468.0  367.92  5572.1  369.77  5631.9  369.51
#Mann=6,-1,0
  4721.8    0.12       0  4793.6    0.05       0  5037.8    0.12       0
  5085.6    0.04       0  5089.6    0.12       0  5230.6    0.05       0
Bank Sta=5085.6,5089.6
Exp/Cntr=0.3,0.1

Type RM Length L Ch R = 1,5749,343,343,343
BEGIN DESCRIPTION:
Lacy 145 3446
END DESCRIPTION:
XS GIS Cut Line= 3
      2714505.63      6853757.28      2714673.56      6854038.27
      2715242.78      6853796.72
#Sta/Elev= 30
  4670.8  364.32  4739.5  364.08  4745.3  364.78  4768.3  364.43  4782.3  365.57
  4791.6  364.30  4856.2  363.84  4899.0  365.29  4914.6  365.04  4943.1  362.71
  4959.5  362.69  4974.3  362.10  4988.5  361.14  4996.8  362.05  5022.5  361.53
  5028.8  358.14  5032.2  357.85  5032.4  357.35  5036.2  357.85  5044.3  359.74
  5052.4  363.07  5066.0  363.88  5105.2  363.20  5174.6  364.75  5281.7  364.33
  5326.7  366.06  5410.9  365.71  5510.9  366.67  5522.2  367.51  5616.5  367.54
#Mann=5,-1,0
  4670.8    0.05       0  4959.5    0.12       0  4974.3    0.05       0
  5032.2    0.04       0  5036.2    0.05       0
Bank Sta=5032.2,5036.2
Exp/Cntr=0.3,0.1

Type RM Length L Ch R = 1,5406,0,0,0
BEGIN DESCRIPTION:
Lacy 145 3447
END DESCRIPTION:
XS GIS Cut Line= 3
      2714493.41      6854049.24      2714627.91      6854346.77
      2715161.78      6854084.57
#Sta/Elev= 30
  4677.8  363.51  4765.5  361.45  4771.0  361.96  4840.4  361.03  4909.7  361.39
  4938.3  362.87  4943.8  360.90  4961.4  360.44  4996.0  356.50  4996.2  356.00
  5000.0  356.50  5006.9  356.50  5013.3  360.68  5051.9  361.38  5057.9  362.66
  5102.5  361.56  5186.8  361.72  5209.3  362.45  5259.8  361.98  5358.7  363.17
  5366.6  362.59  5403.3  364.26  5434.1  363.95  5439.7  363.27  5456.6  363.26
  5462.2  364.03  5514.7  363.40  5546.5  363.71  5591.5  365.45  5599.1  364.90
#Mann=3,-1,0
  4677.8    0.05       0  4996.0    0.04       0  5000.0    0.05       0
Bank Sta=4996,5000
Exp/Cntr=0.3,0.1

Chan Stop Cuts=-1