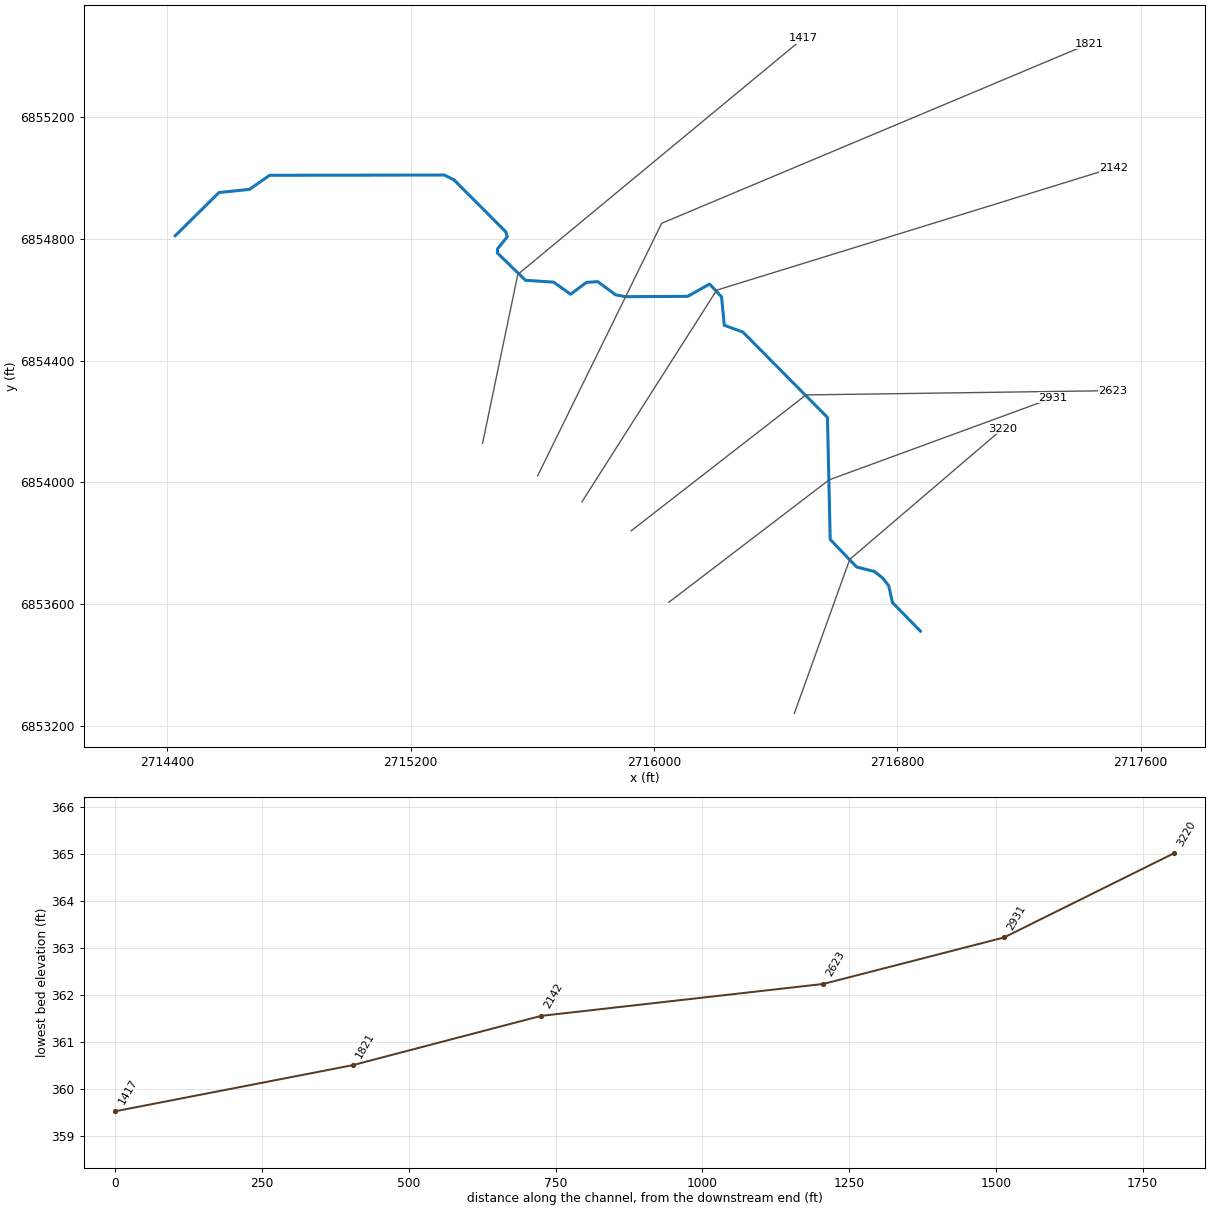
--- Lacy 146.prj (project) ---

Proj Title=Lacy 146 Base Level Engineering
Current Plan=p01
Default Exp/Contr=0.3,0.1
English Units
Geom File=g01
Flow File=f01
Plan File=p01
BEGIN DESCRIPTION:
Lacy 146
END DESCRIPTION:

--- Lacy 146.p01 (plan) ---

Plan Title=Multiple Run
Short Identifier=Multiple
Geom File=g01
Flow File=f01
Subcritical Flow
K Sum by GR= 0
Std Step Tol= 0.01
Critical Tol= 0.01
Num of Std Step Trials= 20
Max Error Tol= 0.3
Flow Tol Ratio= 0.001
Split Flow NTrial= 30
Split Flow Tol= 0.02
Split Flow Ratio= 0.02
Log Output Level= 0
Friction Slope Method= 1
Unsteady Friction Slope Method= 2
Unsteady Bridges Friction Slope Method= 1
Parabolic Critical Depth
Global Vel Dist=  1 , 1 , 1
Global Log Level= 0
CheckData=True
Encroach Param= -1, 0, 0, 0
BEGIN DESCRIPTION:
Multiple Run
END DESCRIPTION:

--- Lacy 146.f01 (steady flow) ---

Flow Title=Multiple
Number of Profiles=7
Profile Names=10-year,25-year,50-year,1pct_min,100-year,1pct_plu,500-year
River Rch & RM= Lacy 146,Reach-1,3220
     245     306     352     201     400     799     517
Boundary for River Rch & Prof#=Lacy 146,Reach-1,1
Up Type=0
Dn Type=3
Dn Slope=0.005
Boundary for River Rch & Prof#=Lacy 146,Reach-1,2
Up Type=0
Dn Type=3
Dn Slope=0.005
Boundary for River Rch & Prof#=Lacy 146,Reach-1,3
Up Type=0
Dn Type=3
Dn Slope=0.005
Boundary for River Rch & Prof#=Lacy 146,Reach-1,4
Up Type=0
Dn Type=3
Dn Slope=0.005
Boundary for River Rch & Prof#=Lacy 146,Reach-1,5
Up Type=0
Dn Type=3
Dn Slope=0.005
Boundary for River Rch & Prof#=Lacy 146,Reach-1,6
Up Type=0
Dn Type=3
Dn Slope=0.005
Boundary for River Rch & Prof#=Lacy 146,Reach-1,7
Up Type=0
Dn Type=3
Dn Slope=0.005

--- Lacy 146.g01 (geometry) ---

Geom Title=Existing Conditions

River Reach=Lacy 146,Reach-1
Reach XY= 30
      2716876.00      6853511.00      2716784.12      6853604.95
      2716772.13      6853659.57      2716753.14      6853684.84
      2716724.57      6853707.11      2716666.31      6853721.78
      2716579.53      6853812.45      2716570.54      6854213.45
      2716292.45      6854494.26      2716231.26      6854516.48
      2716222.36      6854609.91      2716183.06      6854652.00
      2716110.85      6854611.67      2715905.85      6854610.65
      2715873.65      6854616.78      2715815.29      6854660.18
      2715777.64      6854657.39      2715726.01      6854618.59
      2715670.10      6854658.45      2715577.47      6854664.61
      2715485.30      6854754.31      2715485.61      6854767.66
      2715517.84      6854807.67      2715512.35      6854824.33
      2715342.77      6854994.57      2715310.84      6855010.62
      2714736.50      6855009.78      2714670.02      6854963.36
      2714569.83      6854953.14      2714426.00      6854811.00

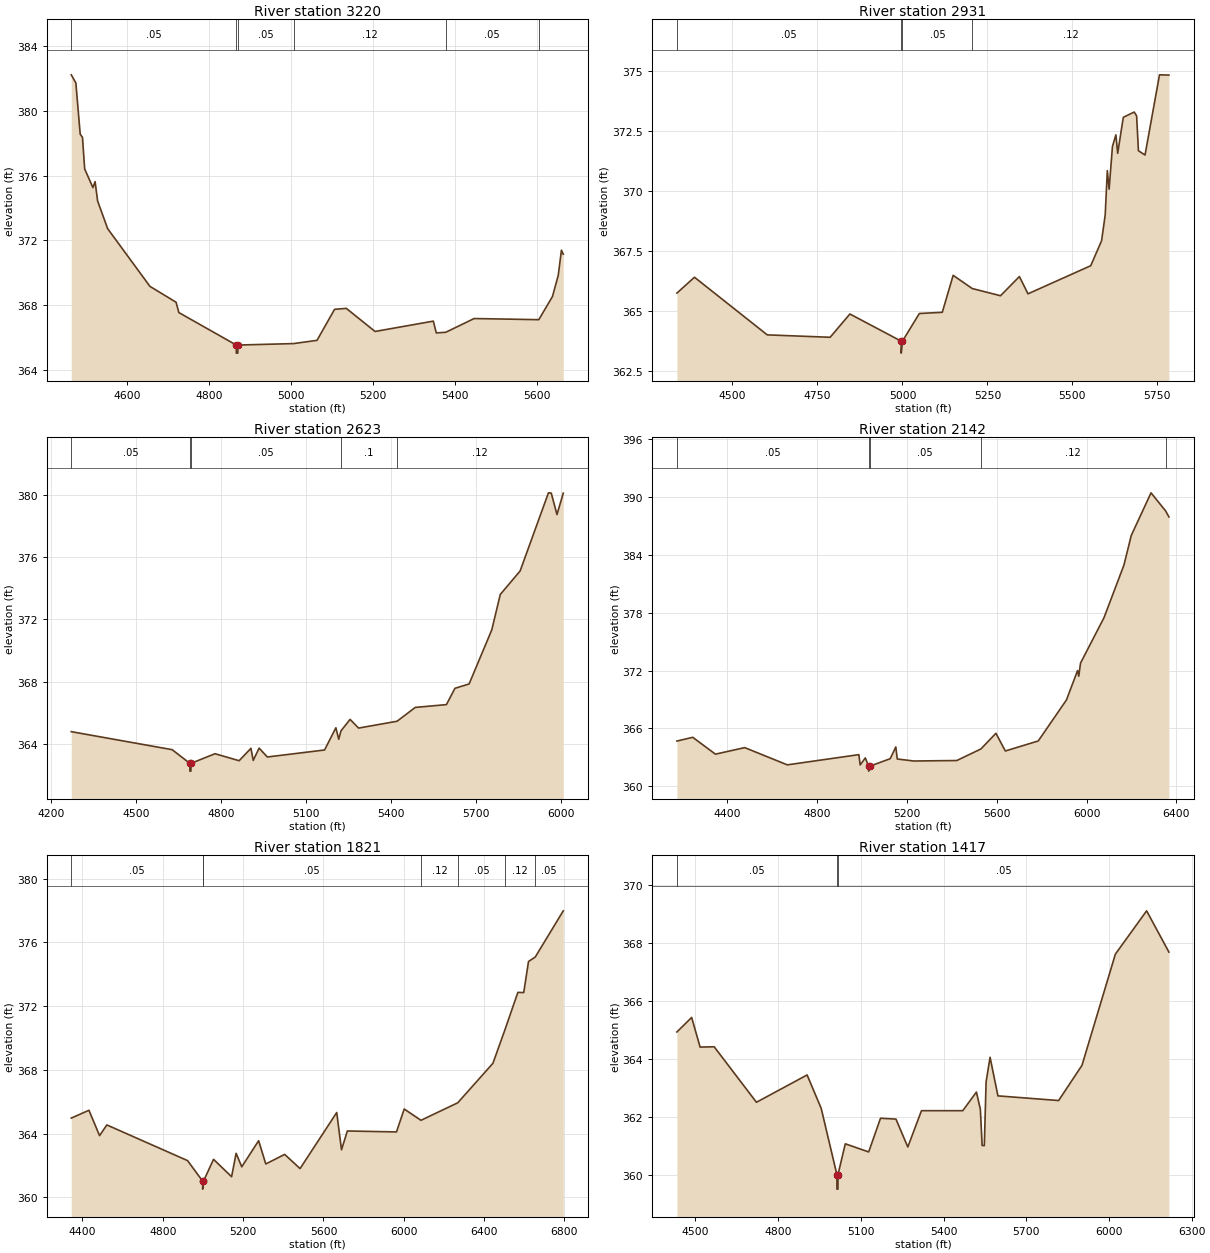
Type RM Length L Ch R = 1,3220,289,289,289
BEGIN DESCRIPTION:
Lacy 146 915
END DESCRIPTION:
XS GIS Cut Line= 3
      2716461.67      6853240.47      2716643.80      6853746.85
      2717146.87      6854176.78
#Sta/Elev= 30
  4464.3  382.24  4475.5  381.74  4486.1  378.57  4491.7  378.37  4497.0  376.42
  4517.1  375.26  4522.4  375.63  4528.6  374.43  4553.1  372.72  4656.2  369.15
  4719.9  368.17  4726.7  367.53  4866.7  365.52  4866.9  365.02  4870.4  365.02
  4870.7  365.52  5006.3  365.61  5063.6  365.81  5106.4  367.73  5135.0  367.79
  5205.2  366.36  5347.3  367.00  5354.5  366.27  5377.6  366.31  5446.8  367.16
  5604.5  367.09  5637.8  368.52  5652.0  369.84  5659.7  371.39  5664.2  371.14
#Mann=6,-1,0
  4464.3    0.05       0  4866.7    0.04       0  4870.7    0.05       0
  5006.3    0.12       0  5377.6    0.05       0  5604.5    0.12       0
Bank Sta=4866.7,4870.7
Exp/Cntr=0.3,0.1

Type RM Length L Ch R = 1,2931,308,308,308
BEGIN DESCRIPTION:
Lacy 146 916
END DESCRIPTION:
XS GIS Cut Line= 3
      2716048.63      6853605.58      2716575.96      6854008.27
      2717311.97      6854278.04
#Sta/Elev= 30
  4336.5  365.73  4388.2  366.39  4602.3  363.99  4787.3  363.89  4845.4  364.86
  4996.1  363.73  4996.4  363.23  5000.1  363.73  5049.7  364.88  5117.2  364.93
  5149.2  366.47  5205.3  365.92  5288.5  365.62  5344.1  366.42  5369.3  365.70
  5553.9  366.87  5585.8  367.91  5596.5  368.99  5602.7  370.83  5608.0  370.06
  5617.8  371.84  5627.9  372.32  5633.2  371.55  5649.7  373.05  5681.7  373.27
  5688.9  373.11  5694.2  371.66  5713.6  371.48  5756.2  374.82  5783.9  374.81
#Mann=4,-1,0
  4336.5    0.05       0  4996.1    0.04       0  5000.1    0.05       0
  5205.3    0.12       0
Bank Sta=4996.1,5000.1
Exp/Cntr=0.3,0.1

Type RM Length L Ch R = 1,2623,481,481,481
BEGIN DESCRIPTION:
Lacy 146 917
END DESCRIPTION:
XS GIS Cut Line= 3
      2715925.32      6853840.93      2716499.97      6854287.54
      2717508.27      6854301.66
#Sta/Elev= 30
  4272.2  364.78  4628.3  363.62  4690.6  362.74  4690.9  362.24  4694.4  362.24
  4694.6  362.74  4779.5  363.36  4864.6  362.91  4906.3  363.71  4914.3  362.93
  4935.1  363.72  4964.1  363.15  5166.0  363.60  5206.0  365.03  5216.0  364.29
  5223.9  364.83  5256.1  365.57  5286.1  365.01  5421.9  365.45  5486.1  366.34
  5596.1  366.52  5626.1  367.57  5676.1  367.85  5756.1  371.33  5786.1  373.61
  5856.1  375.12  5956.1  380.15  5966.1  380.13  5986.1  378.75  6008.4  380.13
#Mann=5,-1,0
  4272.2    0.05       0  4690.6    0.04       0  4694.6    0.05       0
  5223.9     0.1       0  5421.9    0.12       0
Bank Sta=4690.6,4694.6
Exp/Cntr=0.3,0.1

Type RM Length L Ch R = 1,2142,321,321,321
BEGIN DESCRIPTION:
Lacy 146 918
END DESCRIPTION:
XS GIS Cut Line= 3
      2715763.35      6853936.25      2716206.38      6854632.08
      2717512.16      6855035.24
#Sta/Elev= 30
  4175.1  364.68  4245.6  365.07  4346.7  363.32  4477.1  364.00  4666.8  362.21
  4985.5  363.27  4991.4  362.20  5014.3  362.93  5029.0  362.06  5029.2  361.56
  5033.0  362.06  5125.2  362.85  5150.1  364.07  5156.6  362.82  5229.8  362.61
  5421.8  362.66  5529.2  363.86  5596.1  365.49  5638.0  363.65  5784.5  364.69
  5910.1  368.94  5959.8  372.00  5965.0  371.41  5972.9  372.77  6077.6  377.49
  6166.2  382.94  6198.8  386.01  6286.9  390.44  6351.9  388.56  6366.6  387.94
#Mann=5,-1,0
  4175.1    0.05       0  5029.0    0.04       0  5033.0    0.05       0
  5529.2    0.12       0  6351.9    0.05       0
Bank Sta=5029,5033
Exp/Cntr=0.3,0.1

Type RM Length L Ch R = 1,1821,404,404,404
BEGIN DESCRIPTION:
Lacy 146 919
END DESCRIPTION:
XS GIS Cut Line= 3
      2715617.75      6854021.92      2716025.35      6854851.88
      2717431.68      6855442.59
#Sta/Elev= 30
  4344.1  364.97  4432.2  365.46  4485.0  363.87  4521.3  364.54  4923.3  362.30
  4998.4  361.01  4998.6  360.51  5002.4  361.01  5052.6  362.38  5142.5  361.29
  5165.0  362.76  5193.1  361.91  5277.1  363.55  5312.8  362.09  5406.8  362.69
  5483.5  361.80  5666.0  365.32  5689.8  362.98  5719.0  364.16  5963.6  364.10
  6002.0  365.54  6085.6  364.83  6268.7  365.93  6443.8  368.41  6504.1  370.53
  6568.0  372.86  6597.2  372.85  6621.0  374.80  6654.6  375.08  6794.1  377.98
#Mann=7,-1,0
  4344.1    0.05       0  4998.4    0.04       0  5002.4    0.05       0
  6085.6    0.12       0  6268.7    0.05       0  6504.1    0.12       0
  6654.6    0.05       0
Bank Sta=4998.4,5002.4
Exp/Cntr=0.3,0.1

Type RM Length L Ch R = 1,1417,0,0,0
BEGIN DESCRIPTION:
Lacy 146 914
END DESCRIPTION:
XS GIS Cut Line= 3
      2715436.54      6854128.63      2715552.37      6854683.88
      2716490.36      6855460.07
#Sta/Elev= 30
  4432.8  364.94  4486.3  365.44  4516.9  364.42  4568.0  364.43  4721.3  362.52
  4905.1  363.46  4956.2  362.31  5013.1  360.03  5013.4  359.53  5016.9  359.53
  5017.1  360.03  5043.6  361.09  5128.4  360.81  5171.4  361.97  5227.4  361.94
  5270.4  360.98  5319.9  362.23  5469.7  362.23  5519.2  362.87  5533.5  362.28
  5540.0  361.03  5547.9  361.03  5554.3  363.22  5568.7  364.07  5597.3  362.74
  5817.5  362.58  5902.1  363.79  6023.3  367.62  6136.6  369.11  6217.5  367.69
#Mann=3,-1,0
  4432.8    0.05       0  5013.1    0.04       0  5017.1    0.05       0
Bank Sta=5013.1,5017.1
Exp/Cntr=0.3,0.1

Chan Stop Cuts=-1