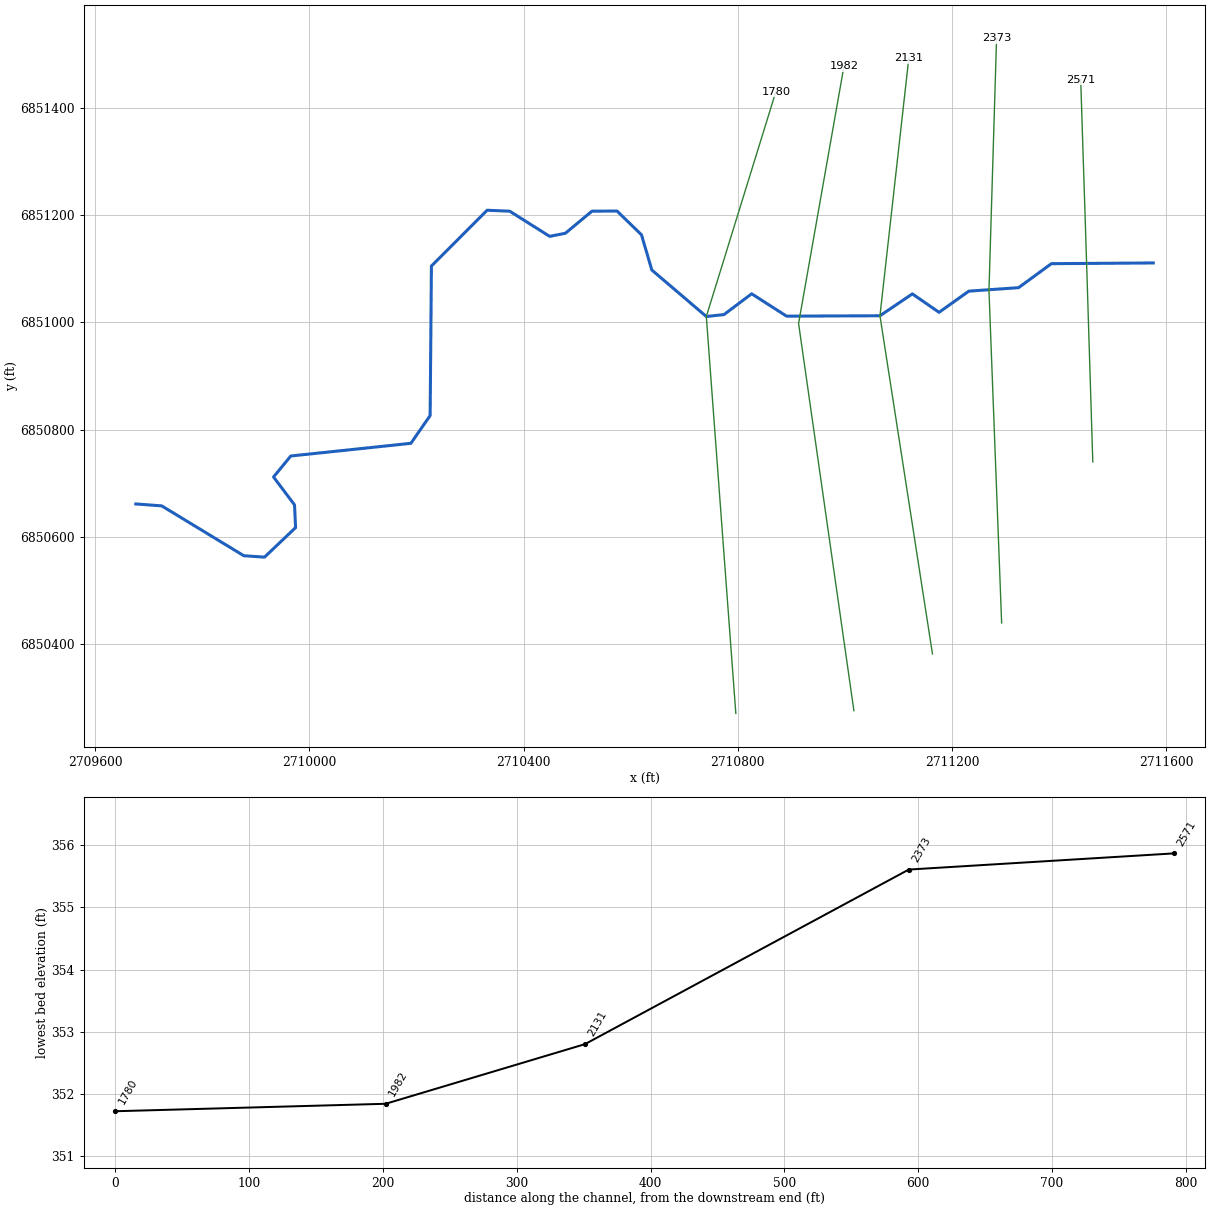
--- Lacy 147.prj (project) ---

Proj Title=Lacy 147 Base Level Engineering
Current Plan=p01
Default Exp/Contr=0.3,0.1
English Units
Geom File=g01
Flow File=f01
Plan File=p01
BEGIN DESCRIPTION:
Lacy 147
END DESCRIPTION:

--- Lacy 147.p01 (plan) ---

Plan Title=Multiple Run
Short Identifier=Multiple
Geom File=g01
Flow File=f01
Subcritical Flow
K Sum by GR= 0
Std Step Tol= 0.01
Critical Tol= 0.01
Num of Std Step Trials= 20
Max Error Tol= 0.3
Flow Tol Ratio= 0.001
Split Flow NTrial= 30
Split Flow Tol= 0.02
Split Flow Ratio= 0.02
Log Output Level= 0
Friction Slope Method= 1
Unsteady Friction Slope Method= 2
Unsteady Bridges Friction Slope Method= 1
Parabolic Critical Depth
Global Vel Dist=  1 , 1 , 1
Global Log Level= 0
CheckData=True
Encroach Param= -1, 0, 0, 0
BEGIN DESCRIPTION:
Multiple Run
END DESCRIPTION:

--- Lacy 147.f01 (steady flow) ---

Flow Title=Multiple
Number of Profiles=7
Profile Names=10-year,25-year,50-year,1pct_min,100-year,1pct_plu,500-year
River Rch & RM= Lacy 147,Reach-1,2571
     428     559     662     389     776    1548    1066
Boundary for River Rch & Prof#=Lacy 147,Reach-1,1
Up Type=0
Dn Type=3
Dn Slope=0.005
Boundary for River Rch & Prof#=Lacy 147,Reach-1,2
Up Type=0
Dn Type=3
Dn Slope=0.005
Boundary for River Rch & Prof#=Lacy 147,Reach-1,3
Up Type=0
Dn Type=3
Dn Slope=0.005
Boundary for River Rch & Prof#=Lacy 147,Reach-1,4
Up Type=0
Dn Type=3
Dn Slope=0.005
Boundary for River Rch & Prof#=Lacy 147,Reach-1,5
Up Type=0
Dn Type=3
Dn Slope=0.005
Boundary for River Rch & Prof#=Lacy 147,Reach-1,6
Up Type=0
Dn Type=3
Dn Slope=0.005
Boundary for River Rch & Prof#=Lacy 147,Reach-1,7
Up Type=0
Dn Type=3
Dn Slope=0.005

--- Lacy 147.g01 (geometry) ---

Geom Title=Existing Conditions

River Reach=Lacy 147,Reach-1
Reach XY= 30
      2711576.00      6851111.00      2711385.66      6851109.63
      2711324.40      6851064.85      2711231.48      6851058.34
      2711175.90      6851018.79      2711126.10      6851053.21
      2711065.57      6851012.37      2710891.16      6851011.66
      2710825.99      6851053.41      2710774.35      6851014.57
      2710741.35      6851011.01      2710639.63      6851097.77
      2710620.25      6851163.61      2710574.58      6851207.96
      2710527.76      6851207.64      2710478.20      6851166.42
      2710448.81      6851160.64      2710374.26      6851207.63
      2710332.03      6851209.38      2710228.05      6851105.16
      2710225.68      6850826.02      2710189.74      6850774.20
      2709965.47      6850750.53      2709933.25      6850711.33
      2709972.42      6850659.33      2709974.42      6850616.82
      2709916.42      6850561.68      2709877.77      6850564.30
      2709724.51      6850657.40      2709676.00      6850661.00

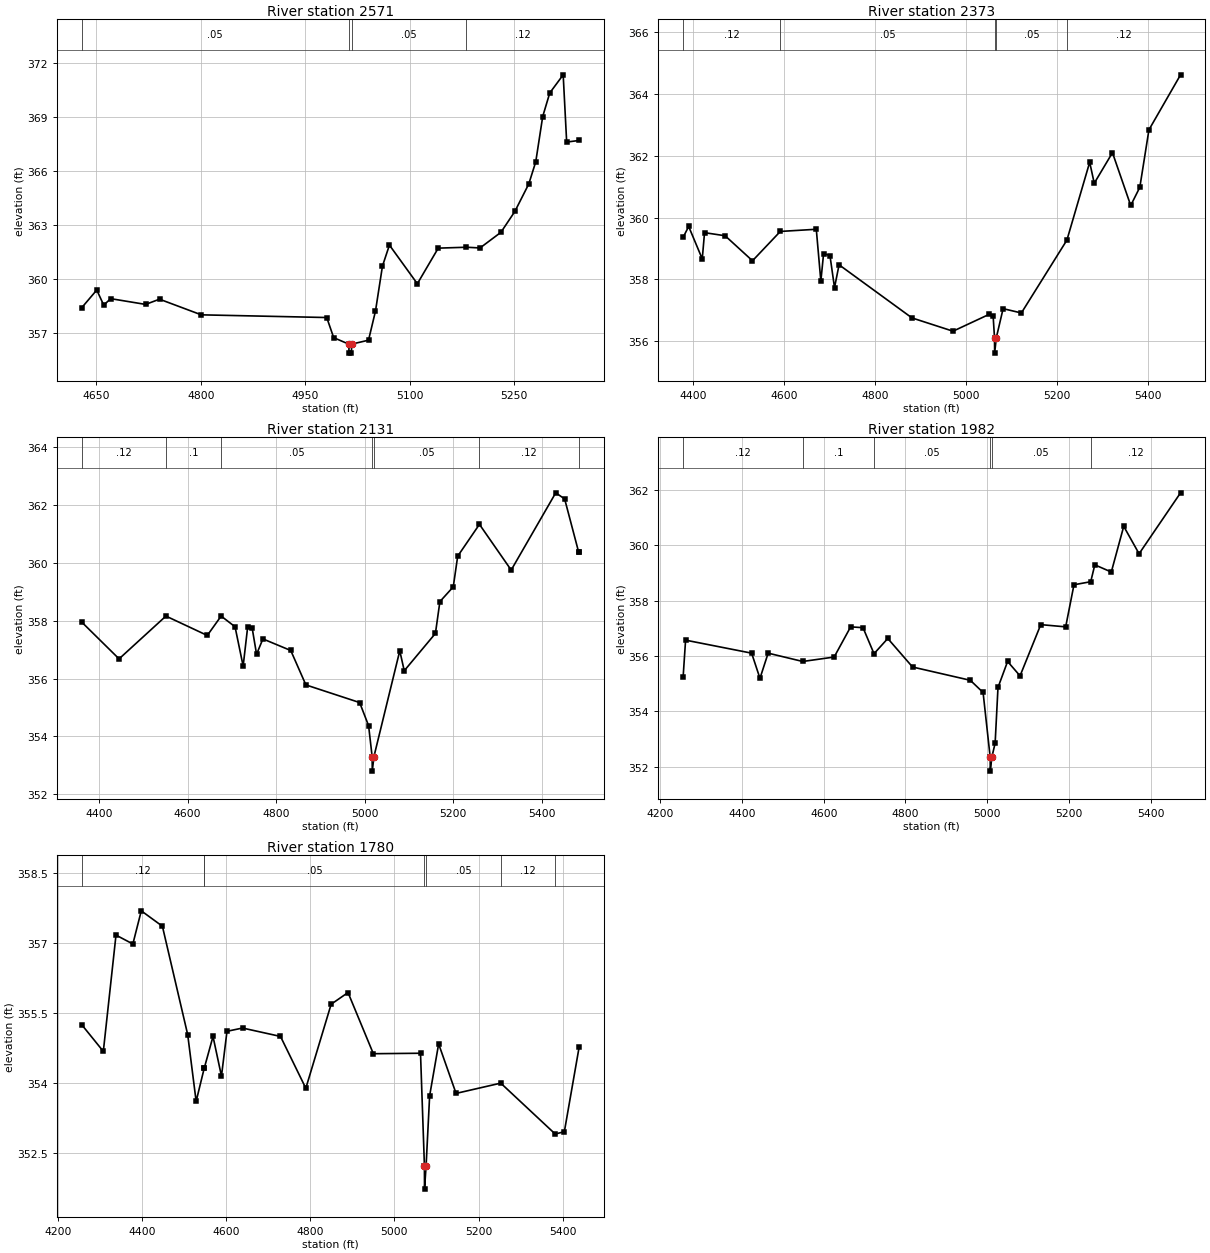
Type RM Length L Ch R = 1,2571,198,198,198
BEGIN DESCRIPTION:
Lacy 147 878
END DESCRIPTION:
XS GIS Cut Line= 3
      2711462.98      6850739.48      2711451.43      6851110.10
      2711440.40      6851453.33
#Sta/Elev= 30
  4629.2  358.40  4650.7  359.38  4660.7  358.54  4670.7  358.90  4720.8  358.58
  4740.8  358.87  4800.8  358.00  4980.9  357.85  4990.9  356.73  5012.6  356.37
  5012.9  355.87  5016.4  355.87  5016.6  356.37  5040.9  356.59  5050.9  358.21
  5060.9  360.71  5070.9  361.88  5111.0  359.73  5141.0  361.71  5181.5  361.76
  5201.0  361.72  5231.0  362.59  5251.0  363.75  5271.0  365.28  5281.0  366.51
  5291.0  369.03  5301.1  370.34  5320.4  371.35  5325.4  367.61  5343.4  367.70
#Mann=4,-1,0
  4629.2    0.05       0  5012.6    0.04       0  5016.6    0.05       0
  5181.5    0.12       0
Bank Sta=5012.6,5016.6
Exp/Cntr=0.3,0.1

Type RM Length L Ch R = 1,2373,242,242,242
BEGIN DESCRIPTION:
Lacy 147 877
END DESCRIPTION:
XS GIS Cut Line= 3
      2711292.78      6850438.85      2711269.12      6851059.80
      2711283.30      6851530.39
#Sta/Elev= 30
  4378.6  359.36  4390.8  359.71  4420.6  358.66  4425.6  359.51  4470.8  359.41
  4530.9  358.60  4592.0  359.55  4671.0  359.62  4681.0  357.94  4687.0  358.83
  4701.0  358.77  4711.0  357.73  4721.0  358.47  4881.1  356.75  4971.2  356.32
  5051.2  356.87  5059.3  356.81  5062.3  356.11  5062.6  355.61  5066.3  356.11
  5081.2  357.05  5121.3  356.91  5221.3  359.27  5271.3  361.79  5281.3  361.11
  5321.3  362.10  5361.4  360.39  5381.4  360.98  5401.4  362.84  5470.8  364.62
#Mann=5,-1,0
  4378.6    0.12       0  4592.0    0.05       0  5062.3    0.04       0
  5066.3    0.05       0  5221.3    0.12       0
Bank Sta=5062.3,5066.3
Exp/Cntr=0.3,0.1

Type RM Length L Ch R = 1,2131,149,149,149
BEGIN DESCRIPTION:
Lacy 147 876
END DESCRIPTION:
XS GIS Cut Line= 3
      2711163.62      6850380.94      2711065.57      6851012.37
      2711119.48      6851493.66
#Sta/Elev= 30
  4361.0  357.95  4445.2  356.68  4551.0  358.16  4644.4  357.49  4675.7  358.16
  4707.1  357.79  4725.4  356.43  4735.5  357.77  4745.6  357.76  4755.7  356.84
  4770.0  357.37  4832.9  356.97  4867.1  355.78  4988.5  355.17  5008.7  354.37
  5016.7  353.30  5017.0  352.80  5020.7  353.30  5079.1  356.96  5089.2  356.27
  5159.6  357.56  5169.7  358.66  5199.9  359.17  5209.9  360.23  5259.0  361.33
  5330.7  359.75  5431.3  362.42  5451.4  362.21  5482.9  360.38  5484.3  360.38
#Mann=7,-1,0
  4361.0    0.12       0  4551.0     0.1       0  4675.7    0.05       0
  5016.7    0.04       0  5020.7    0.05       0  5259.0    0.12       0
  5482.9     0.1       0
Bank Sta=5016.7,5020.7
Exp/Cntr=0.3,0.1

Type RM Length L Ch R = 1,1982,202,202,202
BEGIN DESCRIPTION:
Lacy 147 875
END DESCRIPTION:
XS GIS Cut Line= 3
      2711016.92      6850275.01      2710913.63      6850997.90
      2710998.29      6851477.96
#Sta/Elev= 30
  4255.7  355.24  4261.7  356.57  4423.4  356.10  4443.8  355.19  4463.8  356.10
  4548.5  355.80  4625.4  355.96  4665.8  357.05  4696.1  357.02  4723.0  356.08
  4756.7  356.63  4817.3  355.60  4958.8  355.12  4990.0  354.68  5007.4  352.34
  5007.6  351.84  5011.4  352.34  5019.5  352.85  5026.5  354.86  5050.0  355.80
  5080.5  355.28  5131.2  357.13  5192.2  357.05  5212.5  358.57  5253.5  358.68
  5263.5  359.29  5303.9  359.03  5334.3  360.68  5371.9  359.69  5473.4  361.89
#Mann=6,-1,0
  4255.7    0.12       0  4548.5     0.1       0  4723.0    0.05       0
  5007.4    0.04       0  5011.4    0.05       0  5253.5    0.12       0
Bank Sta=5007.4,5011.4
Exp/Cntr=0.3,0.1

Type RM Length L Ch R = 1,1780,0,0,0
BEGIN DESCRIPTION:
Lacy 147 874
END DESCRIPTION:
XS GIS Cut Line= 3
      2710796.45      6850269.95      2710741.35      6851011.01
      2710871.14      6851430.60
#Sta/Elev= 30
  4256.9  355.24  4308.1  354.67  4338.2  357.16  4378.3  356.97  4398.3  357.68
  4448.5  357.35  4508.6  355.03  4528.7  353.60  4547.9  354.31  4548.0  354.31
  4568.8  354.99  4588.9  354.14  4602.0  355.10  4639.0  355.17  4729.2  354.99
  4789.4  353.88  4849.6  355.68  4889.7  355.93  4949.9  354.62  5062.0  354.63
  5071.3  352.22  5071.5  351.72  5075.3  352.22  5083.7  353.72  5105.1  354.83
  5146.5  353.77  5252.7  353.99  5382.2  352.90  5403.9  352.95  5439.2  354.77
#Mann=7,-1,0
  4256.9    0.12       0  4547.9     0.1       0  4548.0    0.05       0
  5071.3    0.04       0  5075.3    0.05       0  5252.7    0.12       0
  5382.2     0.1       0
Bank Sta=5071.3,5075.3
Exp/Cntr=0.3,0.1

Chan Stop Cuts=-1