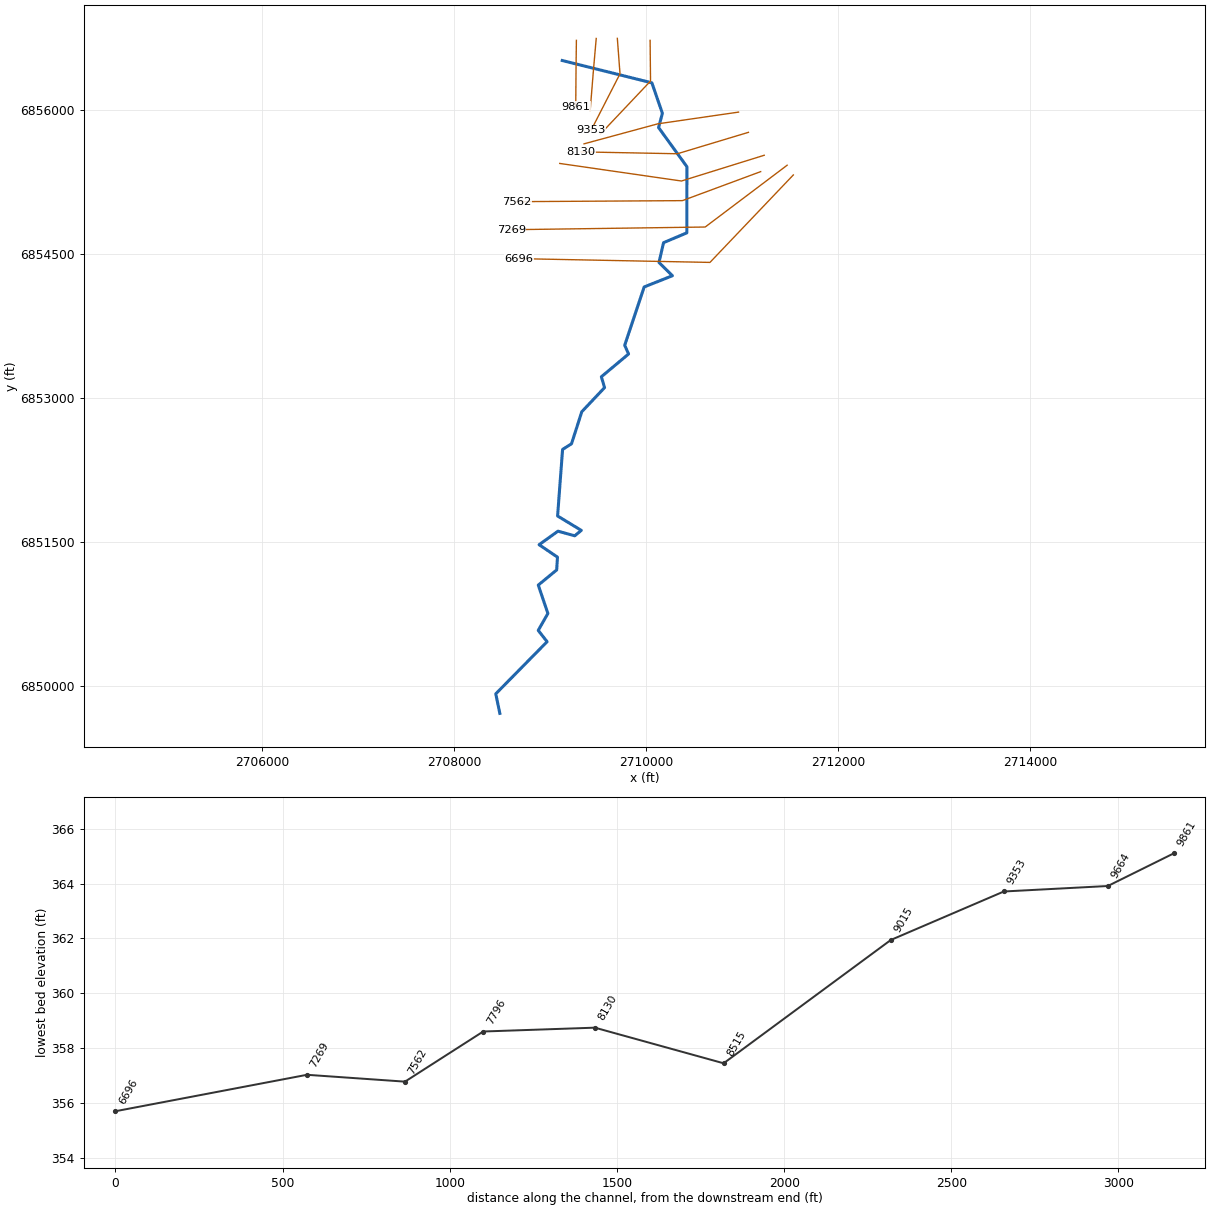
--- Lacy 148.prj (project) ---

Proj Title=Lacy 148 Base Level Engineering
Current Plan=p01
Default Exp/Contr=0.3,0.1
English Units
Geom File=g01
Flow File=f01
Plan File=p01
BEGIN DESCRIPTION:
Lacy 148
END DESCRIPTION:

--- Lacy 148.p01 (plan) ---

Plan Title=Multiple Run
Short Identifier=Multiple
Geom File=g01
Flow File=f01
Subcritical Flow
K Sum by GR= 0
Std Step Tol= 0.01
Critical Tol= 0.01
Num of Std Step Trials= 20
Max Error Tol= 0.3
Flow Tol Ratio= 0.001
Split Flow NTrial= 30
Split Flow Tol= 0.02
Split Flow Ratio= 0.02
Log Output Level= 0
Friction Slope Method= 1
Unsteady Friction Slope Method= 2
Unsteady Bridges Friction Slope Method= 1
Parabolic Critical Depth
Global Vel Dist=  1 , 1 , 1
Global Log Level= 0
CheckData=True
Encroach Param= -1, 0, 0, 0
BEGIN DESCRIPTION:
Multiple Run
END DESCRIPTION:

--- Lacy 148.f01 (steady flow) ---

Flow Title=Multiple
Number of Profiles=7
Profile Names=10-year,25-year,50-year,1pct_min,100-year,1pct_plu,500-year
River Rch & RM= Lacy 148,Reach-1,9861
     495     655     783     465     927    1849    1297
River Rch & RM= Lacy 148,Reach-1,8515
     924    1256    1527     918    1833    3656    2640
Boundary for River Rch & Prof#=Lacy 148,Reach-1,1
Up Type=0
Dn Type=3
Dn Slope=0.005
Boundary for River Rch & Prof#=Lacy 148,Reach-1,2
Up Type=0
Dn Type=3
Dn Slope=0.005
Boundary for River Rch & Prof#=Lacy 148,Reach-1,3
Up Type=0
Dn Type=3
Dn Slope=0.005
Boundary for River Rch & Prof#=Lacy 148,Reach-1,4
Up Type=0
Dn Type=3
Dn Slope=0.005
Boundary for River Rch & Prof#=Lacy 148,Reach-1,5
Up Type=0
Dn Type=3
Dn Slope=0.005
Boundary for River Rch & Prof#=Lacy 148,Reach-1,6
Up Type=0
Dn Type=3
Dn Slope=0.005
Boundary for River Rch & Prof#=Lacy 148,Reach-1,7
Up Type=0
Dn Type=3
Dn Slope=0.005

--- Lacy 148.g01 (geometry) ---

Geom Title=Existing Conditions

River Reach=Lacy 148,Reach-1
Reach XY= 30
      2709126.00      6856511.00      2710059.72      6856278.14
      2710169.09      6855961.14      2710129.46      6855812.50
      2710424.37      6855404.96      2710423.92      6854716.08
      2710181.36      6854613.70      2710133.69      6854407.33
      2710273.27      6854269.22      2709979.50      6854152.54
      2709776.59      6853544.84      2709816.92      6853454.02
      2709533.50      6853217.06      2709566.92      6853104.00
      2709329.53      6852852.51      2709222.65      6852519.06
      2709129.49      6852459.73      2709077.53      6851766.83
      2709324.51      6851616.86      2709256.00      6851560.56
      2709081.56      6851608.74      2708884.94      6851467.68
      2709076.29      6851338.51      2709068.20      6851204.80
      2708876.34      6851047.22      2708976.55      6850751.73
      2708876.05      6850575.06      2708968.40      6850457.66
      2708433.67      6849914.42      2708476.00      6849711.00

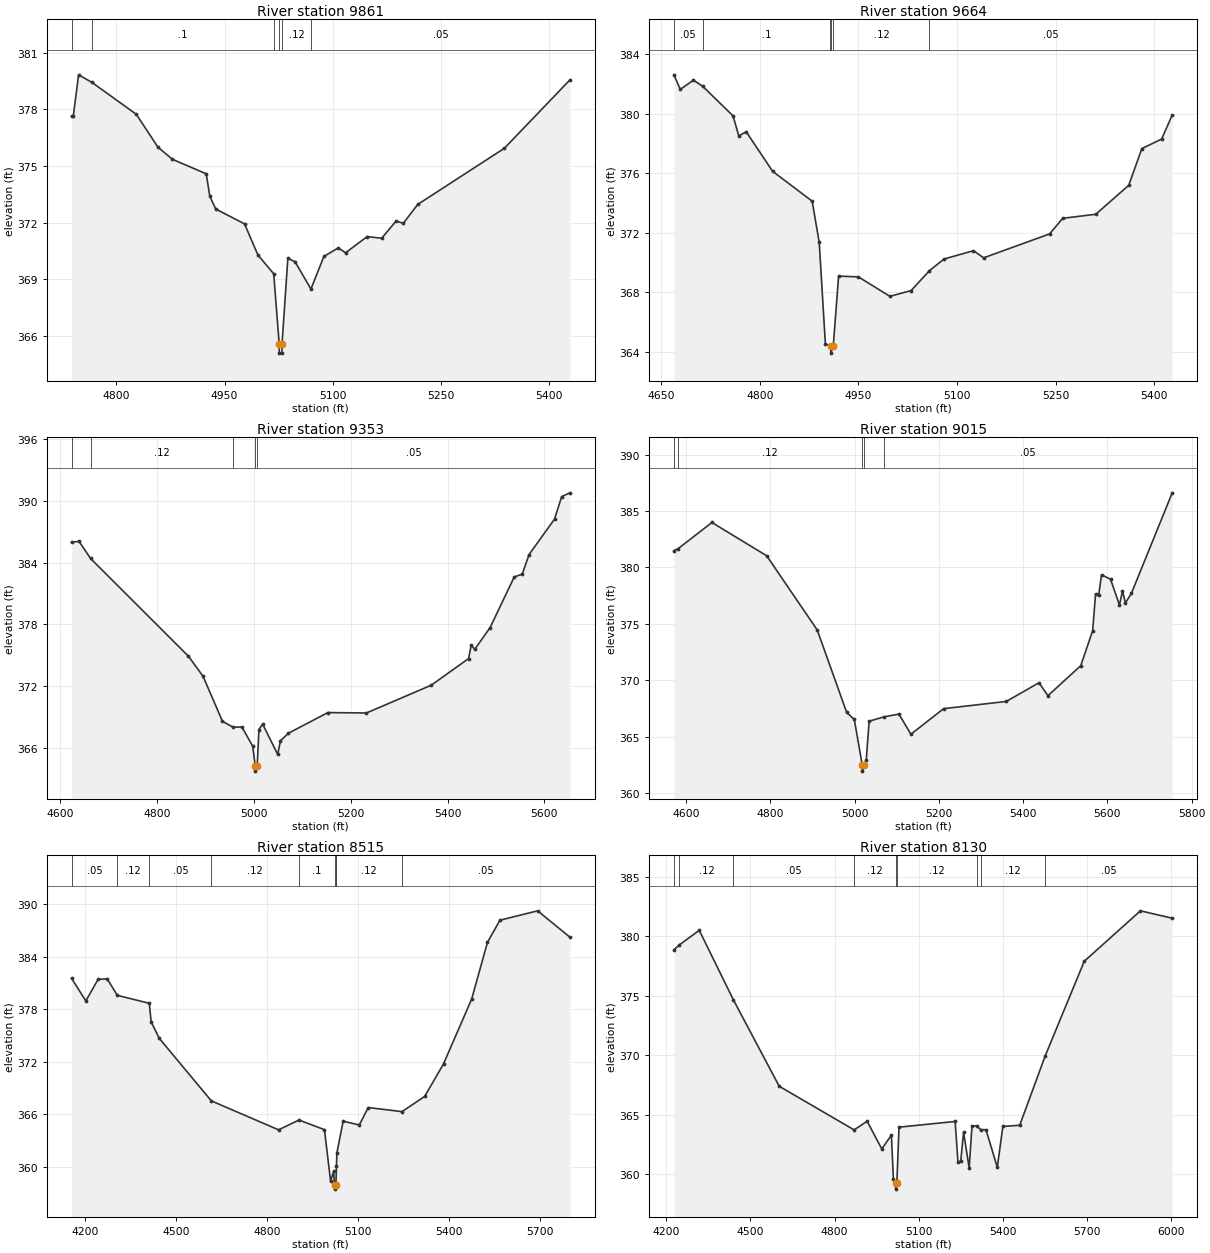
Type RM Length L Ch R = 1,9861,197,197,197
BEGIN DESCRIPTION:
Lacy 148 889
END DESCRIPTION:
XS GIS Cut Line= 3
      2709273.46      6856720.65      2709270.04      6856458.68
      2709266.62      6856030.09
#Sta/Elev= 30
  4738.0  377.63  4740.3  377.63  4747.7  379.83  4766.2  379.43  4827.7  377.74
  4857.7  376.00  4877.7  375.36  4924.6  374.59  4929.6  373.40  4937.7  372.73
  4977.7  371.94  4996.3  370.29  5018.1  369.30  5025.7  365.60  5025.9  365.10
  5029.4  365.10  5029.7  365.60  5037.7  370.11  5047.7  369.94  5069.7  368.49
  5087.7  370.22  5107.7  370.67  5117.7  370.41  5147.7  371.27  5167.7  371.18
  5187.7  372.09  5197.7  371.97  5217.7  372.97  5337.7  375.94  5428.6  379.56
#Mann=6,-1,0
  4738.0    0.05       0  4766.2     0.1       0  5018.1    0.12       0
  5025.7    0.07       0  5029.7    0.12       0  5069.7    0.05       0
Bank Sta=5025.7,5029.7
Exp/Cntr=0.3,0.1

Type RM Length L Ch R = 1,9664,311,311,311
BEGIN DESCRIPTION:
Lacy 148 885
END DESCRIPTION:
XS GIS Cut Line= 3
      2709479.98      6856740.62      2709451.75      6856419.57
      2709416.52      6855984.98
#Sta/Elev= 30
  4669.3  382.63  4679.0  381.65  4699.0  382.27  4712.8  381.87  4759.3  379.87
  4768.0  378.52  4779.3  378.80  4819.5  376.14  4879.7  374.13  4890.4  371.36
  4899.8  364.52  4906.9  364.42  4907.8  364.41  4908.1  363.91  4911.8  364.41
  4919.9  369.09  4950.0  369.04  4998.0  367.73  5030.3  368.12  5058.2  369.46
  5080.4  370.24  5125.1  370.80  5140.6  370.32  5241.0  371.93  5261.0  372.98
  5311.2  373.25  5361.4  375.20  5381.4  377.67  5411.5  378.31  5427.6  379.93
#Mann=6,-1,0
  4669.3    0.05       0  4712.8     0.1       0  4906.9    0.12       0
  4907.8    0.07       0  4911.8    0.12       0  5058.2    0.05       0
Bank Sta=4907.8,4911.8
Exp/Cntr=0.3,0.1

Type RM Length L Ch R = 1,9353,338,338,338
BEGIN DESCRIPTION:
Lacy 148 884
END DESCRIPTION:
XS GIS Cut Line= 3
      2709699.86      6856741.85      2709727.71      6856372.49
      2709427.45      6855785.89
#Sta/Elev= 30
  4623.3  386.00  4638.8  386.07  4662.5  384.41  4864.8  374.89  4894.9  372.94
  4935.0  368.56  4956.6  367.99  4975.2  368.00  4997.4  366.14  5002.7  364.21
  5003.0  363.71  5006.7  364.21  5010.3  367.76  5017.9  368.29  5049.1  365.34
  5054.8  366.67  5071.3  367.40  5152.7  369.41  5232.4  369.37  5366.1  372.07
  5443.3  374.66  5448.9  375.98  5456.0  375.56  5487.7  377.67  5537.7  382.61
  5554.3  382.89  5568.3  384.79  5620.9  388.24  5635.7  390.43  5652.7  390.80
#Mann=5,-1,0
  4623.3    0.05       0  4662.5    0.12       0  4956.6    0.05       0
  5002.7    0.05       0  5006.7    0.05       0
Bank Sta=5002.7,5006.7
Exp/Cntr=0.3,0.1

Type RM Length L Ch R = 1,9015,500,500,500
BEGIN DESCRIPTION:
Lacy 148 882
END DESCRIPTION:
XS GIS Cut Line= 3
      2710041.12      6856721.18      2710045.69      6856297.00
      2709524.03      6855745.83
#Sta/Elev= 30
  4570.8  381.49  4581.2  381.68  4661.0  383.99  4791.0  381.04  4911.0  374.46
  4981.0  367.14  4999.1  366.52  5018.1  362.44  5018.4  361.94  5022.1  362.44
  5027.4  362.90  5034.3  366.37  5069.3  366.75  5105.1  367.00  5133.4  365.21
  5211.1  367.48  5359.9  368.12  5437.6  369.78  5458.7  368.63  5536.7  371.29
  5565.0  374.40  5571.9  377.67  5579.2  377.54  5586.1  379.36  5607.5  378.95
  5628.6  376.67  5635.8  377.92  5642.7  376.85  5656.9  377.70  5753.9  386.62
#Mann=5,-1,0
  4570.8    0.05       0  4581.2    0.12       0  5018.1    0.07       0
  5022.1    0.12       0  5069.3    0.05       0
Bank Sta=5018.1,5022.1
Exp/Cntr=0.3,0.1

Type RM Length L Ch R = 1,8515,385,385,385
BEGIN DESCRIPTION:
Lacy 148 883
END DESCRIPTION:
XS GIS Cut Line= 3
      2710962.57      6855973.58      2710121.26      6855851.32
      2709353.05      6855643.02
#Sta/Elev= 30
  4154.1  381.54  4201.2  378.96  4241.6  381.42  4271.6  381.49  4305.5  379.59
  4410.9  378.69  4416.9  376.57  4443.7  374.68  4615.8  367.53  4837.8  364.22
  4905.2  365.34  4989.4  364.24  5009.7  358.35  5019.7  359.47  5022.6  357.94
  5023.1  357.44  5027.2  357.94  5029.1  360.09  5030.4  361.56  5051.1  365.20
  5104.6  364.78  5134.0  366.77  5245.6  366.30  5320.5  368.04  5382.7  371.76
  5475.9  379.19  5527.8  385.65  5569.2  388.19  5693.5  389.26  5800.2  386.25
#Mann=9,-1,0
  4154.1    0.05       0  4305.5    0.12       0  4410.9    0.05       0
  4615.8    0.12       0  4905.2     0.1       0  5022.6    0.07       0
  5027.2     0.1       0  5029.1    0.12       0  5245.6    0.05       0
Bank Sta=5022.6,5027.2
Exp/Cntr=0.3,0.1

Type RM Length L Ch R = 1,8130,334,334,334
BEGIN DESCRIPTION:
Lacy 148 881
END DESCRIPTION:
XS GIS Cut Line= 3
      2711065.21      6855762.73      2710325.13      6855539.70
      2709322.58      6855559.18
#Sta/Elev= 30
  4227.6  378.86  4247.1  379.28  4317.9  380.50  4439.6  374.65  4602.8  367.39
  4869.7  363.72  4916.1  364.45  4968.3  362.12  5002.6  363.28  5009.7  359.58
  5017.4  359.24  5017.9  358.74  5022.0  359.24  5029.7  363.95  5229.7  364.43
  5239.7  361.02  5249.7  361.10  5259.7  363.53  5279.7  360.52  5289.7  364.05
  5306.7  364.06  5320.1  363.75  5339.8  363.73  5379.8  360.57  5399.8  364.01
  5459.8  364.11  5550.6  369.94  5689.8  377.90  5889.9  382.14  6003.3  381.52
#Mann=9,-1,0
  4227.6    0.05       0  4247.1    0.12       0  4439.6    0.05       0
  4869.7    0.12       0  5017.4    0.07       0  5022.0    0.12       0
  5306.7     0.1       0  5320.1    0.12       0  5550.6    0.05       0
Bank Sta=5017.4,5022
Exp/Cntr=0.3,0.1

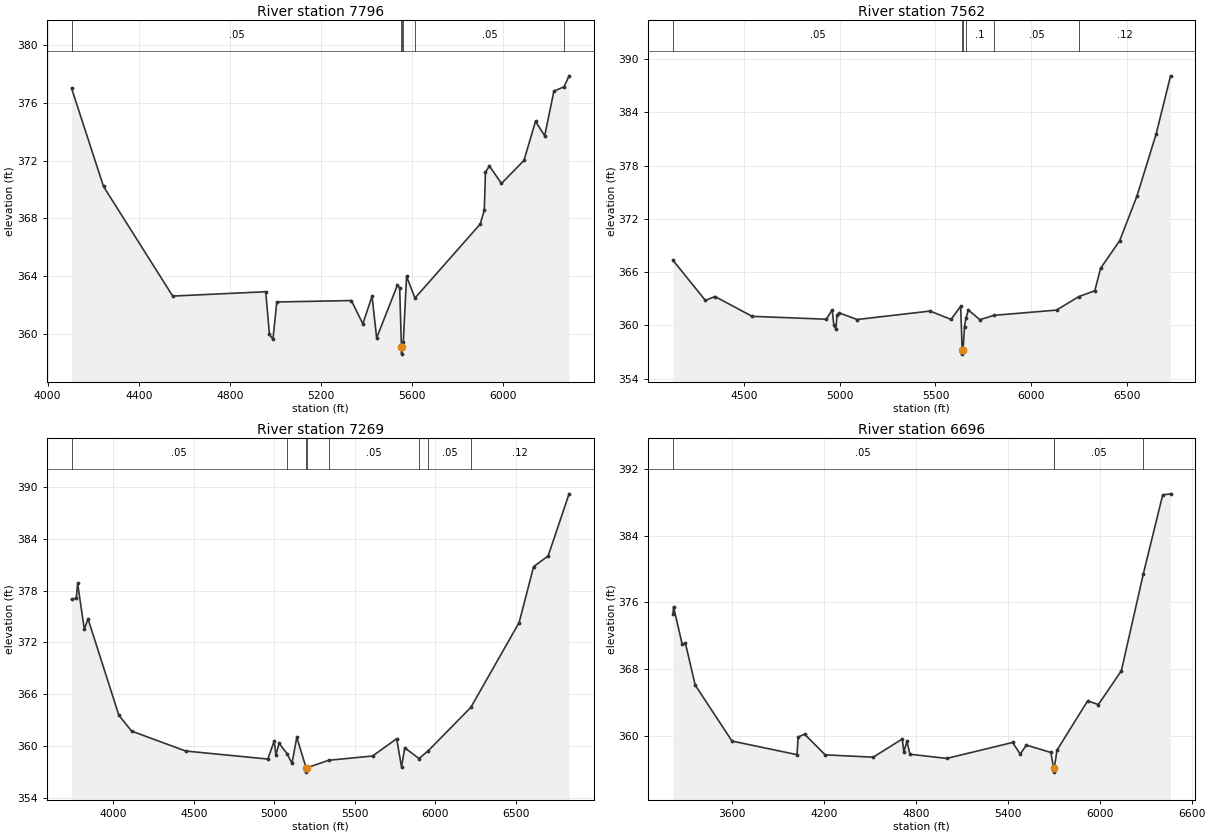
Type RM Length L Ch R = 1,7796,234,234,234
BEGIN DESCRIPTION:
Lacy 148 880
END DESCRIPTION:
XS GIS Cut Line= 3
      2711229.96      6855524.05      2710367.60      6855255.80
      2709100.06      6855438.78
#Sta/Elev= 30
  4105.2  377.01  4245.5  370.21  4549.2  362.62  4957.6  362.92  4973.7  359.97
  4989.1  359.63  5006.2  362.21  5333.3  362.31  5383.8  360.70  5424.2  362.61
  5444.4  359.72  5535.3  363.37  5545.4  363.20  5553.2  359.10  5553.7  358.60
  5557.8  359.10  5561.5  359.47  5575.7  363.99  5612.5  362.48  5899.1  367.61
  5916.9  368.57  5922.0  371.21  5939.5  371.62  5992.3  370.42  6091.0  372.01
  6141.6  374.72  6182.0  373.72  6222.4  376.81  6266.8  377.11  6289.0  377.87
#Mann=6,-1,0
  4105.2    0.05       0  5553.2    0.04       0  5557.8    0.05       0
  5561.5     0.1       0  5612.5    0.05       0  6266.8    0.12       0
Bank Sta=5553.2,5557.8
Exp/Cntr=0.3,0.1

Type RM Length L Ch R = 1,7562,293,293,293
BEGIN DESCRIPTION:
Lacy 148 888
END DESCRIPTION:
XS GIS Cut Line= 3
      2711192.78      6855353.49      2710377.55      6855051.41
      2708650.88      6855040.76
#Sta/Elev= 30
  4130.6  367.33  4299.6  362.82  4349.7  363.26  4543.1  361.03  4930.8  360.70
  4961.2  361.78  4969.7  360.01  4980.3  359.59  4986.2  361.15  4998.2  361.41
  5091.5  360.67  5471.6  361.62  5581.6  360.68  5631.6  362.16  5639.3  357.27
  5639.7  356.77  5643.9  357.27  5651.6  359.88  5658.6  360.79  5671.6  361.74
  5731.6  360.65  5805.5  361.14  6131.6  361.73  6248.0  363.25  6331.6  363.91
  6361.6  366.44  6461.6  369.56  6551.6  374.59  6651.6  381.58  6726.7  388.12
#Mann=6,-1,0
  4130.6    0.05       0  5639.3    0.04       0  5643.9    0.05       0
  5658.6     0.1       0  5805.5    0.05       0  6248.0    0.12       0
Bank Sta=5639.3,5643.9
Exp/Cntr=0.3,0.1

Type RM Length L Ch R = 1,7269,573,573,573
BEGIN DESCRIPTION:
Lacy 148 887
END DESCRIPTION:
XS GIS Cut Line= 3
      2711468.75      6855420.42      2710614.99      6854776.57
      2708595.91      6854748.57
#Sta/Elev= 30
  3741.6  376.99  3771.0  377.12  3779.3  378.82  3820.9  373.51  3843.8  374.73
  4035.3  363.59  4114.4  361.76  4449.6  359.46  4959.9  358.53  4999.9  360.63
  5009.9  358.97  5029.9  360.35  5079.0  359.17  5109.9  358.03  5139.9  361.04
  5197.6  357.52  5198.1  357.02  5202.3  357.52  5338.0  358.39  5610.0  358.88
  5760.0  360.88  5790.0  357.62  5810.0  359.83  5898.8  358.59  5955.0  359.47
  6220.3  364.50  6520.1  374.30  6610.1  380.76  6700.1  381.99  6830.2  389.17
#Mann=8,-1,0
  3741.6    0.05       0  5079.0    0.12       0  5197.6    0.04       0
  5202.3    0.12       0  5338.0    0.05       0  5898.8     0.1       0
  5955.0    0.05       0  6220.3    0.12       0
Bank Sta=5197.6,5202.3
Exp/Cntr=0.3,0.1

Type RM Length L Ch R = 1,6696,0,0,0
BEGIN DESCRIPTION:
Lacy 148 886
END DESCRIPTION:
XS GIS Cut Line= 3
      2711532.79      6855318.88      2710664.54      6854407.98
      2708674.74      6854447.31
#Sta/Elev= 30
  3213.6  374.66  3216.9  375.50  3273.5  371.00  3294.6  371.12  3358.4  366.11
  3598.7  359.41  4023.3  357.78  4030.3  359.89  4072.7  360.23  4207.0  357.76
  4520.6  357.48  4710.6  359.66  4720.6  358.08  4740.6  359.40  4760.6  357.83
  5000.7  357.33  5430.7  359.24  5480.8  357.85  5520.8  358.93  5680.8  358.04
  5698.4  356.19  5698.9  355.69  5703.1  356.19  5720.8  358.32  5920.8  364.22
  5990.9  363.78  6140.9  367.82  6284.0  379.40  6410.9  388.88  6462.2  389.01
#Mann=4,-1,0
  3213.6    0.05       0  5698.4    0.04       0  5703.1    0.05       0
  6284.0    0.12       0
Bank Sta=5698.4,5703.1
Exp/Cntr=0.3,0.1

Chan Stop Cuts=-1