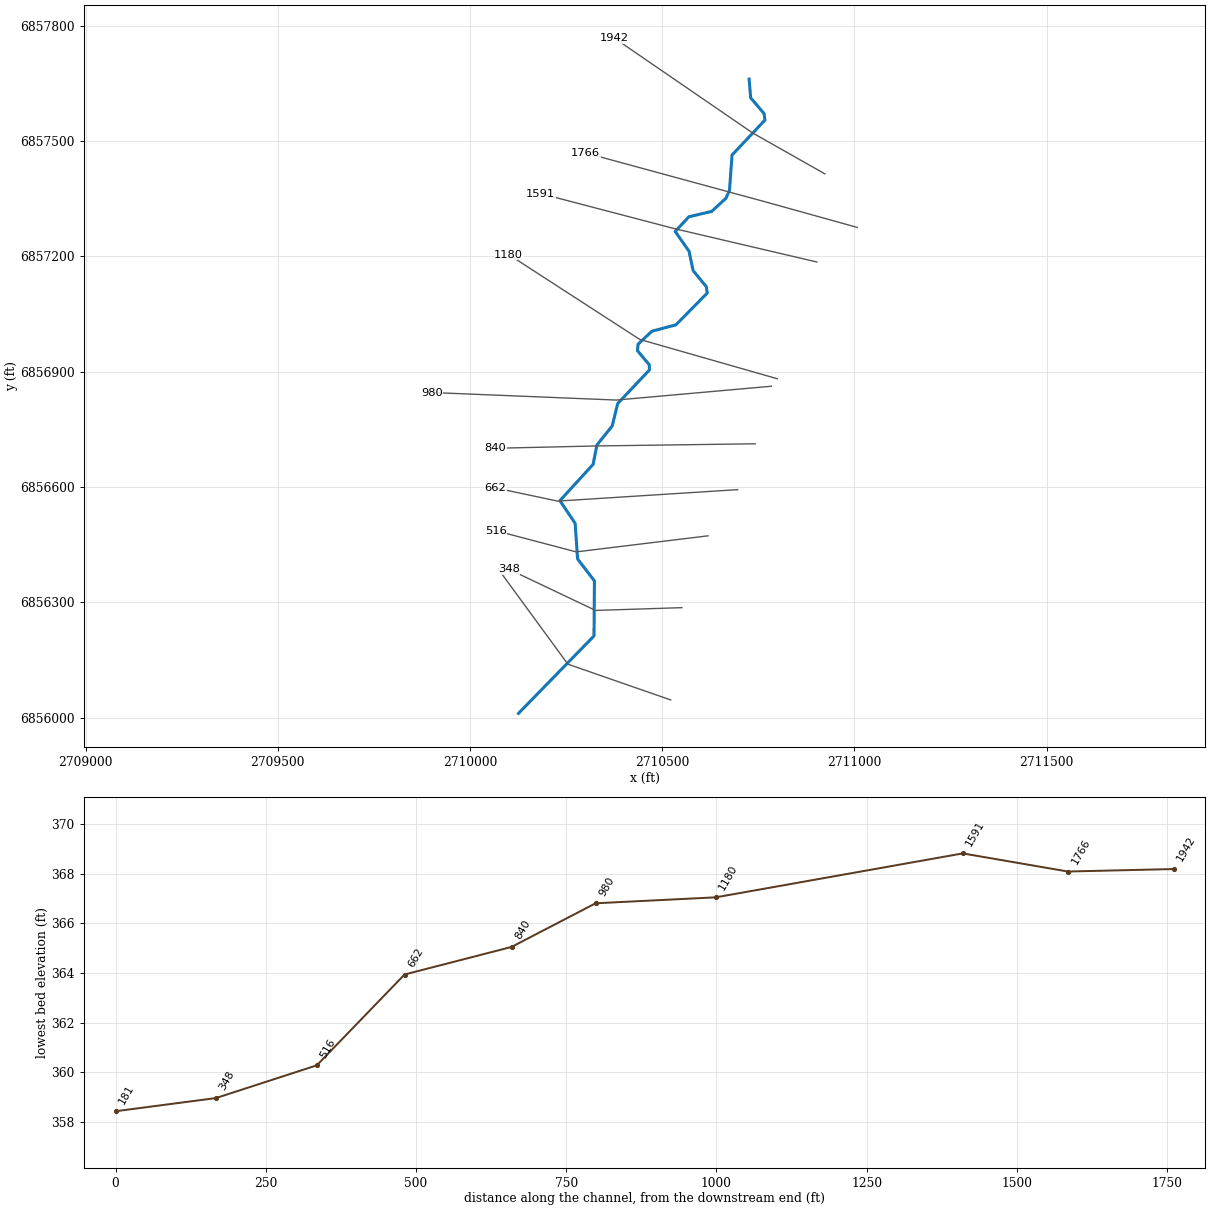
--- Lacy 149.prj (project) ---

Proj Title=Lacy 149 Base Level Engineering
Current Plan=p01
Default Exp/Contr=0.3,0.1
English Units
Geom File=g01
Flow File=f01
Plan File=p01
BEGIN DESCRIPTION:
Lacy 149
END DESCRIPTION:

--- Lacy 149.p01 (plan) ---

Plan Title=Multiple Run
Short Identifier=Multiple
Geom File=g01
Flow File=f01
Subcritical Flow
K Sum by GR= 0
Std Step Tol= 0.01
Critical Tol= 0.01
Num of Std Step Trials= 20
Max Error Tol= 0.3
Flow Tol Ratio= 0.001
Split Flow NTrial= 30
Split Flow Tol= 0.02
Split Flow Ratio= 0.02
Log Output Level= 0
Friction Slope Method= 1
Unsteady Friction Slope Method= 2
Unsteady Bridges Friction Slope Method= 1
Parabolic Critical Depth
Global Vel Dist=  1 , 1 , 1
Global Log Level= 0
CheckData=True
Encroach Param= -1, 0, 0, 0
BEGIN DESCRIPTION:
Multiple Run
END DESCRIPTION:

--- Lacy 149.f01 (steady flow) ---

Flow Title=Multiple
Number of Profiles=7
Profile Names=10-year,25-year,50-year,1pct_min,100-year,1pct_plu,500-year
River Rch & RM= Lacy 149,Reach-1,1942
     412     536     633     371     740    1476    1011
Boundary for River Rch & Prof#=Lacy 149,Reach-1,1
Up Type=0
Dn Type=3
Dn Slope=0.005
Boundary for River Rch & Prof#=Lacy 149,Reach-1,2
Up Type=0
Dn Type=3
Dn Slope=0.005
Boundary for River Rch & Prof#=Lacy 149,Reach-1,3
Up Type=0
Dn Type=3
Dn Slope=0.005
Boundary for River Rch & Prof#=Lacy 149,Reach-1,4
Up Type=0
Dn Type=3
Dn Slope=0.005
Boundary for River Rch & Prof#=Lacy 149,Reach-1,5
Up Type=0
Dn Type=3
Dn Slope=0.005
Boundary for River Rch & Prof#=Lacy 149,Reach-1,6
Up Type=0
Dn Type=3
Dn Slope=0.005
Boundary for River Rch & Prof#=Lacy 149,Reach-1,7
Up Type=0
Dn Type=3
Dn Slope=0.005

--- Lacy 149.g01 (geometry) ---

Geom Title=Existing Conditions

River Reach=Lacy 149,Reach-1
Reach XY= 30
      2710726.00      6857661.00      2710730.02      6857612.36
      2710765.11      6857570.90      2710767.00      6857554.29
      2710681.55      6857463.42      2710674.89      6857371.33
      2710665.61      6857350.90      2710628.52      6857316.74
      2710569.33      6857302.84      2710533.67      6857264.66
      2710569.62      6857213.30      2710580.40      6857162.65
      2710614.73      6857120.86      2710616.90      6857104.25
      2710535.69      6857021.78      2710473.17      6857005.14
      2710437.11      6856971.32      2710435.55      6856954.49
      2710466.37      6856917.69      2710466.68      6856904.35
      2710384.18      6856817.06      2710369.90      6856758.81
      2710330.19      6856709.26      2710320.14      6856658.70
      2710233.81      6856564.41      2710273.32      6856505.52
      2710279.85      6856412.60      2710323.63      6856355.47
      2710322.47      6856212.47      2710126.00      6856011.00

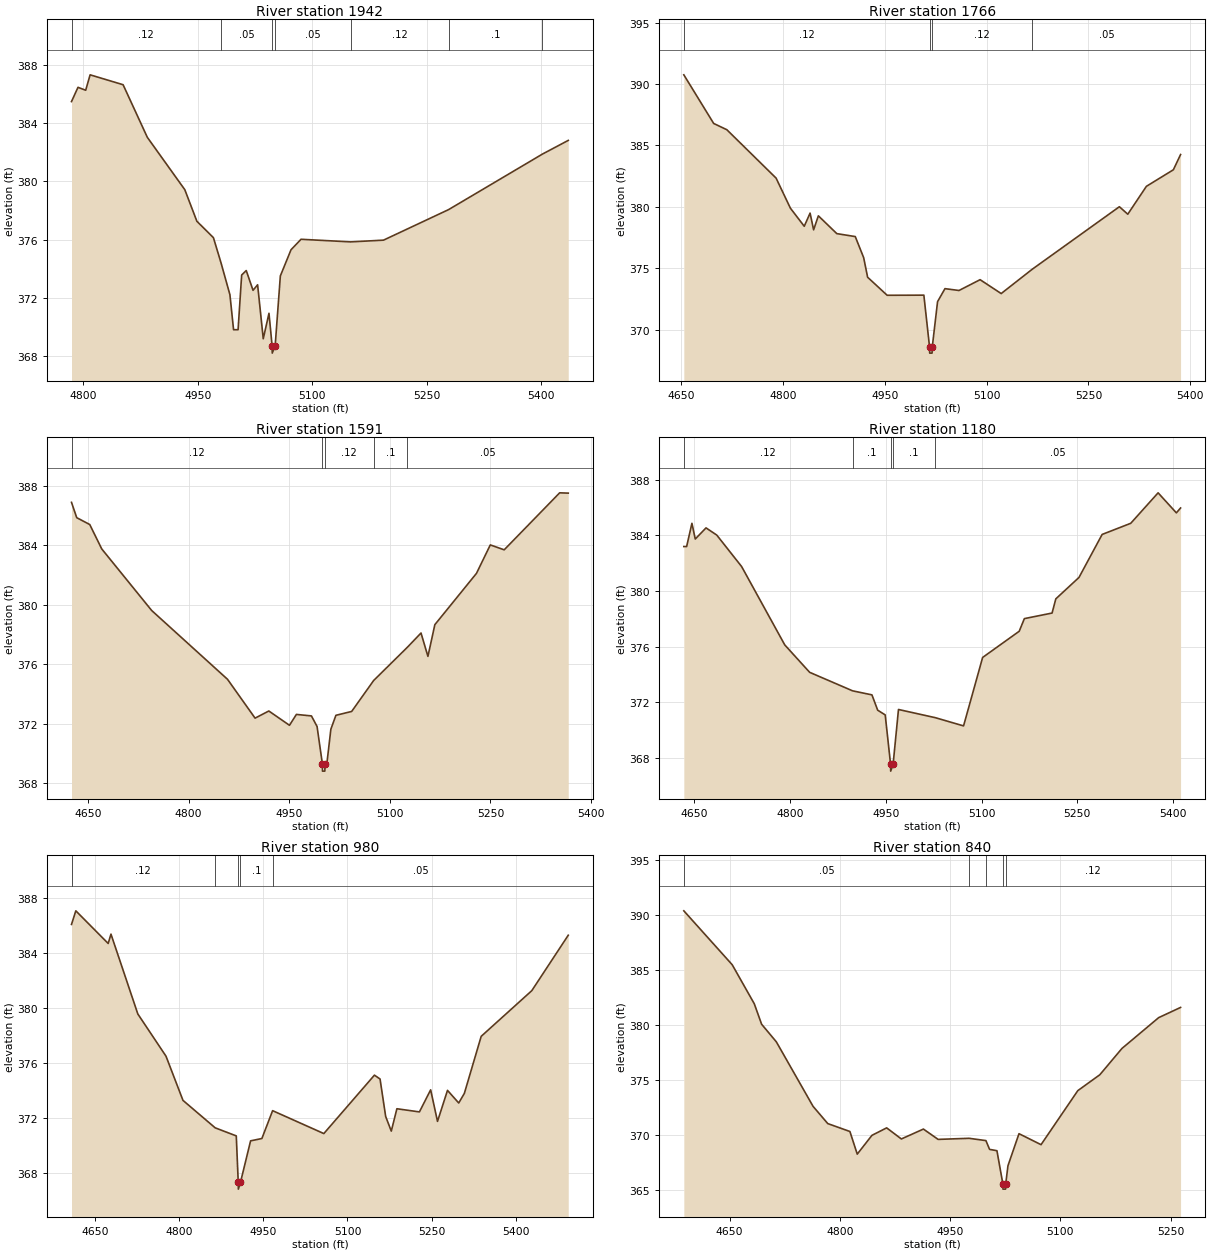
Type RM Length L Ch R = 1,1942,176,176,176
BEGIN DESCRIPTION:
Lacy 149 896
END DESCRIPTION:
XS GIS Cut Line= 3
      2710923.02      6857414.46      2710735.42      6857520.71
      2710376.39      6857767.02
#Sta/Elev= 30
  4784.4  385.49  4792.9  386.47  4803.0  386.27  4808.8  387.33  4852.0  386.65
  4883.8  383.03  4932.9  379.43  4948.7  377.26  4970.4  376.13  4980.4  374.39
  4992.0  372.21  4996.8  369.80  5002.7  369.80  5007.4  373.56  5013.4  373.87
  5022.3  372.51  5028.3  372.89  5035.7  369.18  5043.2  370.93  5047.3  368.69
  5047.5  368.19  5051.3  368.69  5058.1  373.50  5072.1  375.30  5085.2  376.02
  5150.1  375.84  5193.3  375.96  5278.6  378.06  5401.6  381.88  5435.4  382.82
#Mann=7,-1,0
  4784.4    0.12       0  4980.4    0.05       0  5047.3    0.03       0
  5051.3    0.05       0  5150.1    0.12       0  5278.6     0.1       0
  5401.6    0.12       0
Bank Sta=5047.3,5051.3
Exp/Cntr=0.3,0.1

Type RM Length L Ch R = 1,1766,175,175,175
BEGIN DESCRIPTION:
Lacy 149 890
END DESCRIPTION:
XS GIS Cut Line= 3
      2711007.05      6857275.25      2710766.24      6857342.19
      2710300.91      6857468.84
#Sta/Elev= 30
  4653.6  390.75  4697.6  386.79  4717.0  386.28  4789.6  382.34  4810.7  379.89
  4831.1  378.42  4839.7  379.49  4844.9  378.13  4851.9  379.27  4879.1  377.82
  4906.3  377.58  4918.7  375.86  4924.5  374.27  4953.3  372.80  5007.4  372.81
  5015.8  368.59  5016.0  368.09  5019.5  368.09  5019.8  368.59  5027.6  372.28
  5038.5  373.34  5059.2  373.19  5090.3  374.07  5121.4  372.94  5166.9  374.91
  5295.6  380.01  5308.0  379.40  5335.4  381.67  5375.2  383.02  5385.8  384.26
#Mann=4,-1,0
  4653.6    0.12       0  5015.8    0.07       0  5019.8    0.12       0
  5166.9    0.05       0
Bank Sta=5015.8,5019.8
Exp/Cntr=0.3,0.1

Type RM Length L Ch R = 1,1591,411,411,411
BEGIN DESCRIPTION:
Lacy 149 891
END DESCRIPTION:
XS GIS Cut Line= 3
      2710902.44      6857185.11      2710531.78      6857271.98
      2710183.63      6857363.18
#Sta/Elev= 30
  4625.4  386.88  4633.2  385.85  4652.6  385.39  4670.5  383.75  4745.0  379.61
  4858.0  374.99  4899.1  372.38  4919.6  372.86  4950.4  371.90  4960.7  372.63
  4983.1  372.53  4991.5  371.82  4999.4  369.32  4999.6  368.82  5003.1  368.82
  5003.4  369.32  5006.1  369.32  5012.1  371.64  5019.6  372.57  5043.1  372.83
  5075.9  374.91  5126.1  377.14  5146.5  378.10  5156.8  376.53  5167.1  378.66
  5229.2  382.11  5249.8  384.02  5270.5  383.69  5353.2  387.52  5366.0  387.50
#Mann=5,-1,0
  4625.4    0.12       0  4999.4    0.07       0  5003.4    0.12       0
  5075.9     0.1       0  5126.1    0.05       0
Bank Sta=4999.4,5003.4
Exp/Cntr=0.3,0.1

Type RM Length L Ch R = 1,1180,200,200,200
BEGIN DESCRIPTION:
Lacy 149 895
END DESCRIPTION:
XS GIS Cut Line= 3
      2710799.41      6856881.44      2710441.36      6856983.84
      2710100.48      6857204.55
#Sta/Elev= 30
  4633.4  383.19  4637.8  383.19  4646.1  384.86  4651.3  383.73  4668.2  384.53
  4685.1  384.01  4724.0  381.75  4791.6  376.12  4830.6  374.15  4897.9  372.82
  4928.2  372.53  4937.2  371.43  4949.0  371.09  4957.4  367.55  4957.6  367.05
  4961.4  367.55  4969.8  371.48  5027.6  370.89  5071.8  370.30  5101.7  375.22
  5159.0  377.10  5167.1  378.01  5210.5  378.41  5216.4  379.43  5252.7  380.97
  5289.0  384.06  5333.8  384.86  5376.7  387.05  5405.3  385.61  5411.9  385.96
#Mann=5,-1,0
  4633.4    0.12       0  4897.9     0.1       0  4957.4    0.07       0
  4961.4     0.1       0  5027.6    0.05       0
Bank Sta=4957.4,4961.4
Exp/Cntr=0.3,0.1

Type RM Length L Ch R = 1,980,140,140,140
BEGIN DESCRIPTION:
Lacy 149 892
END DESCRIPTION:
XS GIS Cut Line= 3
      2710783.68      6856862.00      2710380.29      6856826.06
      2709901.18      6856845.61
#Sta/Elev= 30
  4608.6  386.11  4616.3  387.10  4673.9  384.72  4678.9  385.40  4726.7  379.58
  4776.9  376.50  4807.1  373.28  4864.4  371.28  4902.0  370.69  4905.5  367.31
  4905.7  366.81  4909.5  367.31  4927.5  370.33  4947.6  370.50  4966.7  372.53
  5057.9  370.86  5148.0  375.12  5158.0  374.84  5168.0  372.11  5178.0  371.04
  5188.0  372.67  5228.1  372.44  5248.1  374.05  5260.3  371.75  5278.1  374.01
  5298.1  373.09  5308.1  373.79  5338.1  377.95  5428.2  381.28  5493.1  385.32
#Mann=5,-1,0
  4608.6    0.12       0  4864.4     0.1       0  4905.5    0.05       0
  4909.5     0.1       0  4966.7    0.05       0
Bank Sta=4905.5,4909.5
Exp/Cntr=0.3,0.1

Type RM Length L Ch R = 1,840,178,178,178
BEGIN DESCRIPTION:
Lacy 149 893
END DESCRIPTION:
XS GIS Cut Line= 3
      2710741.83      6856712.29      2710331.29      6856706.70
      2710066.24      6856700.63
#Sta/Elev= 30
  4587.8  390.40  4653.6  385.49  4683.6  381.94  4693.6  380.07  4713.6  378.47
  4763.6  372.59  4783.6  371.02  4813.7  370.30  4823.7  368.24  4843.7  369.95
  4863.7  370.63  4883.7  369.62  4913.7  370.52  4933.7  369.58  4975.8  369.68
  4998.7  369.47  5003.7  368.67  5013.7  368.55  5021.7  365.55  5021.9  365.05
  5025.4  365.05  5025.7  365.55  5028.7  367.18  5043.7  370.10  5073.7  369.10
  5123.7  374.02  5153.7  375.47  5183.7  377.86  5233.7  380.67  5263.5  381.60
#Mann=5,-1,0
  4587.8    0.05       0  4975.8     0.1       0  4998.7    0.12       0
  5021.7    0.07       0  5025.7    0.12       0
Bank Sta=5021.7,5025.7
Exp/Cntr=0.3,0.1

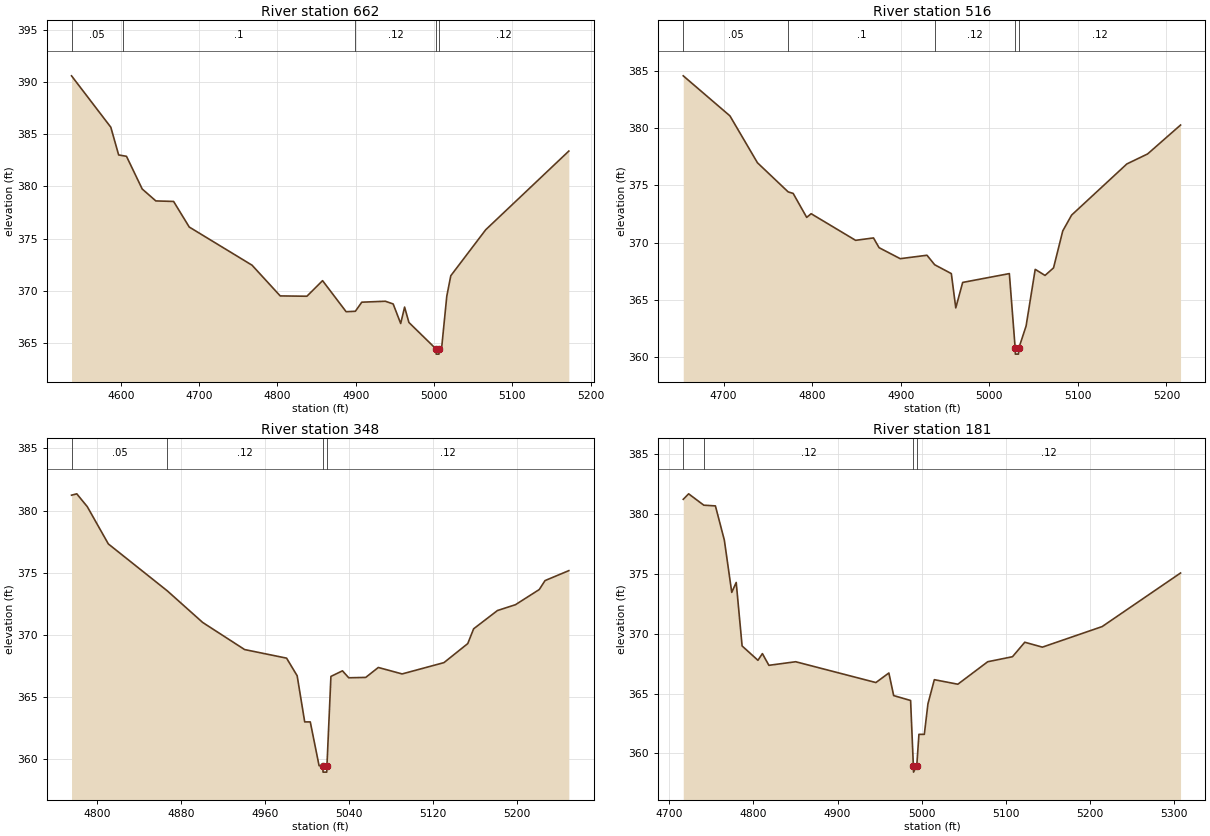
Type RM Length L Ch R = 1,662,146,146,146
BEGIN DESCRIPTION:
Lacy 149 894
END DESCRIPTION:
XS GIS Cut Line= 3
      2710696.09      6856593.00      2710227.85      6856563.20
      2710065.34      6856597.63
#Sta/Elev= 30
  4537.0  390.57  4587.2  385.65  4597.2  383.00  4602.5  382.93  4607.2  382.87
  4627.3  379.74  4644.7  378.60  4667.4  378.55  4687.4  376.10  4767.6  372.45
  4803.6  369.51  4837.7  369.48  4857.7  370.97  4887.8  368.00  4899.6  368.04
  4907.8  368.91  4937.9  369.00  4947.9  368.74  4957.5  366.87  4962.5  368.44
  4968.0  366.97  5002.6  364.44  5002.9  363.94  5006.4  363.94  5006.6  364.44
  5009.7  364.44  5016.4  369.49  5021.5  371.44  5066.1  375.84  5172.3  383.37
#Mann=5,-1,0
  4537.0    0.05       0  4602.5     0.1       0  4899.6    0.12       0
  5002.6    0.07       0  5006.6    0.12       0
Bank Sta=5002.6,5006.6
Exp/Cntr=0.3,0.1

Type RM Length L Ch R = 1,516,168,168,168
BEGIN DESCRIPTION:
Lacy 149 897
END DESCRIPTION:
XS GIS Cut Line= 3
      2710619.20      6856472.88      2710276.23      6856431.10
      2710067.35      6856486.09
#Sta/Elev= 30
  4654.5  384.54  4707.2  381.05  4738.3  376.96  4773.0  374.42  4778.6  374.29
  4793.9  372.20  4798.9  372.52  4849.1  370.20  4869.3  370.41  4875.6  369.56
  4899.5  368.60  4929.7  368.90  4938.4  368.07  4957.2  367.30  4962.2  364.31
  4970.0  366.53  5022.7  367.30  5029.3  360.78  5029.5  360.28  5033.0  360.28
  5033.3  360.78  5041.6  362.73  5051.9  367.67  5063.0  367.14  5072.6  367.80
  5083.0  371.02  5093.0  372.40  5155.4  376.86  5178.8  377.73  5216.0  380.25
#Mann=5,-1,0
  4654.5    0.05       0  4773.0     0.1       0  4938.4    0.12       0
  5029.3    0.07       0  5033.3    0.12       0
Bank Sta=5029.3,5033.3
Exp/Cntr=0.3,0.1

Type RM Length L Ch R = 1,348,167,167,167
BEGIN DESCRIPTION:
Lacy 149 898
END DESCRIPTION:
XS GIS Cut Line= 3
      2710551.04      6856286.00      2710326.46      6856278.80
      2710101.04      6856385.98
#Sta/Elev= 30
  4775.3  381.24  4780.3  381.35  4790.3  380.32  4810.4  377.32  4866.7  373.54
  4900.4  371.00  4940.4  368.82  4980.4  368.13  4990.5  366.71  4997.7  363.00
  5003.0  363.00  5011.4  359.48  5014.9  359.46  5015.2  358.96  5018.7  358.96
  5018.9  359.46  5022.7  366.66  5033.7  367.11  5039.7  366.55  5055.9  366.58
  5067.9  367.38  5090.6  366.86  5130.5  367.77  5153.2  369.30  5158.8  370.49
  5181.5  371.96  5198.7  372.43  5221.4  373.65  5226.9  374.37  5249.6  375.17
#Mann=4,-1,0
  4775.3    0.05       0  4866.7    0.12       0  5014.9    0.07       0
  5018.9    0.12       0
Bank Sta=5014.9,5018.9
Exp/Cntr=0.3,0.1

Type RM Length L Ch R = 1,181,0,0,0
BEGIN DESCRIPTION:
Lacy 149 899
END DESCRIPTION:
XS GIS Cut Line= 3
      2710522.06      6856045.92      2710254.49      6856139.01
      2710073.05      6856387.02
#Sta/Elev= 30
  4716.7  381.24  4723.1  381.70  4741.1  380.75  4754.9  380.69  4765.5  377.83
  4774.3  373.46  4779.6  374.29  4786.6  368.98  4805.4  367.78  4810.7  368.34
  4818.4  367.36  4850.2  367.66  4945.5  365.92  4960.9  366.72  4966.6  364.83
  4986.7  364.42  4990.0  358.93  4990.2  358.43  4994.0  358.93  4996.6  361.59
  5003.0  361.59  5007.3  364.14  5014.9  366.16  5042.8  365.78  5078.3  367.66
  5107.7  368.08  5122.3  369.29  5143.2  368.88  5214.2  370.60  5307.3  375.08
#Mann=4,-1,0
  4716.7    0.05       0  4741.1    0.12       0  4990.0    0.07       0
  4994.0    0.12       0
Bank Sta=4990,4994
Exp/Cntr=0.3,0.1

Chan Stop Cuts=-1