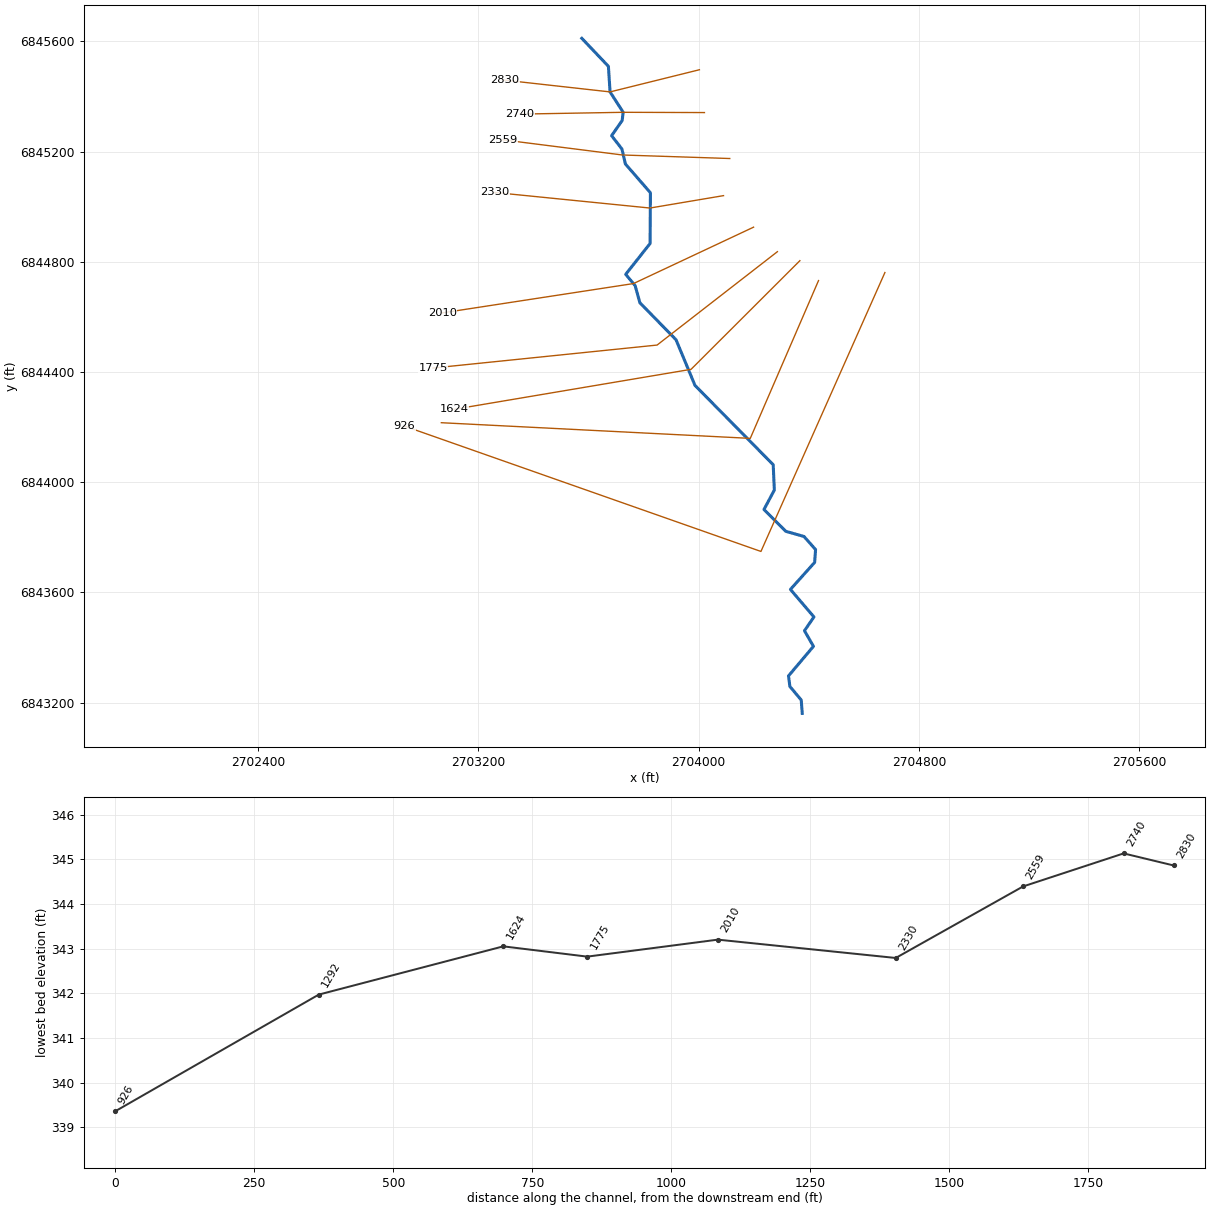
--- Lacy 151.prj (project) ---

Proj Title=Lacy 151 Base Level Engineering
Current Plan=p01
Default Exp/Contr=0.3,0.1
English Units
Geom File=g01
Flow File=f01
Plan File=p01
BEGIN DESCRIPTION:
Lacy 151
END DESCRIPTION:

--- Lacy 151.p01 (plan) ---

Plan Title=Multiple Run
Short Identifier=Multiple
Geom File=g01
Flow File=f01
Subcritical Flow
K Sum by GR= 0
Std Step Tol= 0.01
Critical Tol= 0.01
Num of Std Step Trials= 20
Max Error Tol= 0.3
Flow Tol Ratio= 0.001
Split Flow NTrial= 30
Split Flow Tol= 0.02
Split Flow Ratio= 0.02
Log Output Level= 0
Friction Slope Method= 1
Unsteady Friction Slope Method= 2
Unsteady Bridges Friction Slope Method= 1
Parabolic Critical Depth
Global Vel Dist=  1 , 1 , 1
Global Log Level= 0
CheckData=True
Encroach Param= -1, 0, 0, 0
BEGIN DESCRIPTION:
Multiple Run
END DESCRIPTION:

--- Lacy 151.f01 (steady flow) ---

Flow Title=Multiple
Number of Profiles=7
Profile Names=10-year,25-year,50-year,1pct_min,100-year,1pct_plu,500-year
River Rch & RM= Lacy 151,Reach-1,2830
     593     793     953     569    1135    2264    1606
Boundary for River Rch & Prof#=Lacy 151,Reach-1,1
Up Type=0
Dn Type=3
Dn Slope=0.005
Boundary for River Rch & Prof#=Lacy 151,Reach-1,2
Up Type=0
Dn Type=3
Dn Slope=0.005
Boundary for River Rch & Prof#=Lacy 151,Reach-1,3
Up Type=0
Dn Type=3
Dn Slope=0.005
Boundary for River Rch & Prof#=Lacy 151,Reach-1,4
Up Type=0
Dn Type=3
Dn Slope=0.005
Boundary for River Rch & Prof#=Lacy 151,Reach-1,5
Up Type=0
Dn Type=3
Dn Slope=0.005
Boundary for River Rch & Prof#=Lacy 151,Reach-1,6
Up Type=0
Dn Type=3
Dn Slope=0.005
Boundary for River Rch & Prof#=Lacy 151,Reach-1,7
Up Type=0
Dn Type=3
Dn Slope=0.005

--- Lacy 151.g01 (geometry) ---

Geom Title=Existing Conditions

River Reach=Lacy 151,Reach-1
Reach XY= 30
      2703576.00      6845611.00      2703672.44      6845509.52
      2703678.50      6845416.56      2703726.11      6845342.54
      2703722.39      6845312.64      2703684.07      6845257.69
      2703721.55      6845209.35      2703734.14      6845154.96
      2703824.95      6845050.56      2703823.81      6844866.44
      2703735.24      6844754.45      2703769.57      6844713.29
      2703786.75      6844651.32      2703917.86      6844517.06
      2703986.76      6844351.32      2704270.60      6844063.43
      2704274.73      6843971.48      2704237.09      6843900.92
      2704316.29      6843821.79      2704382.43      6843802.96
      2704424.38      6843755.54      2704420.92      6843708.73
      2704333.11      6843611.00      2704418.44      6843511.00
      2704384.05      6843461.00      2704416.69      6843404.34
      2704326.06      6843296.97      2704331.09      6843258.76
      2704372.31      6843209.51      2704376.00      6843161.00

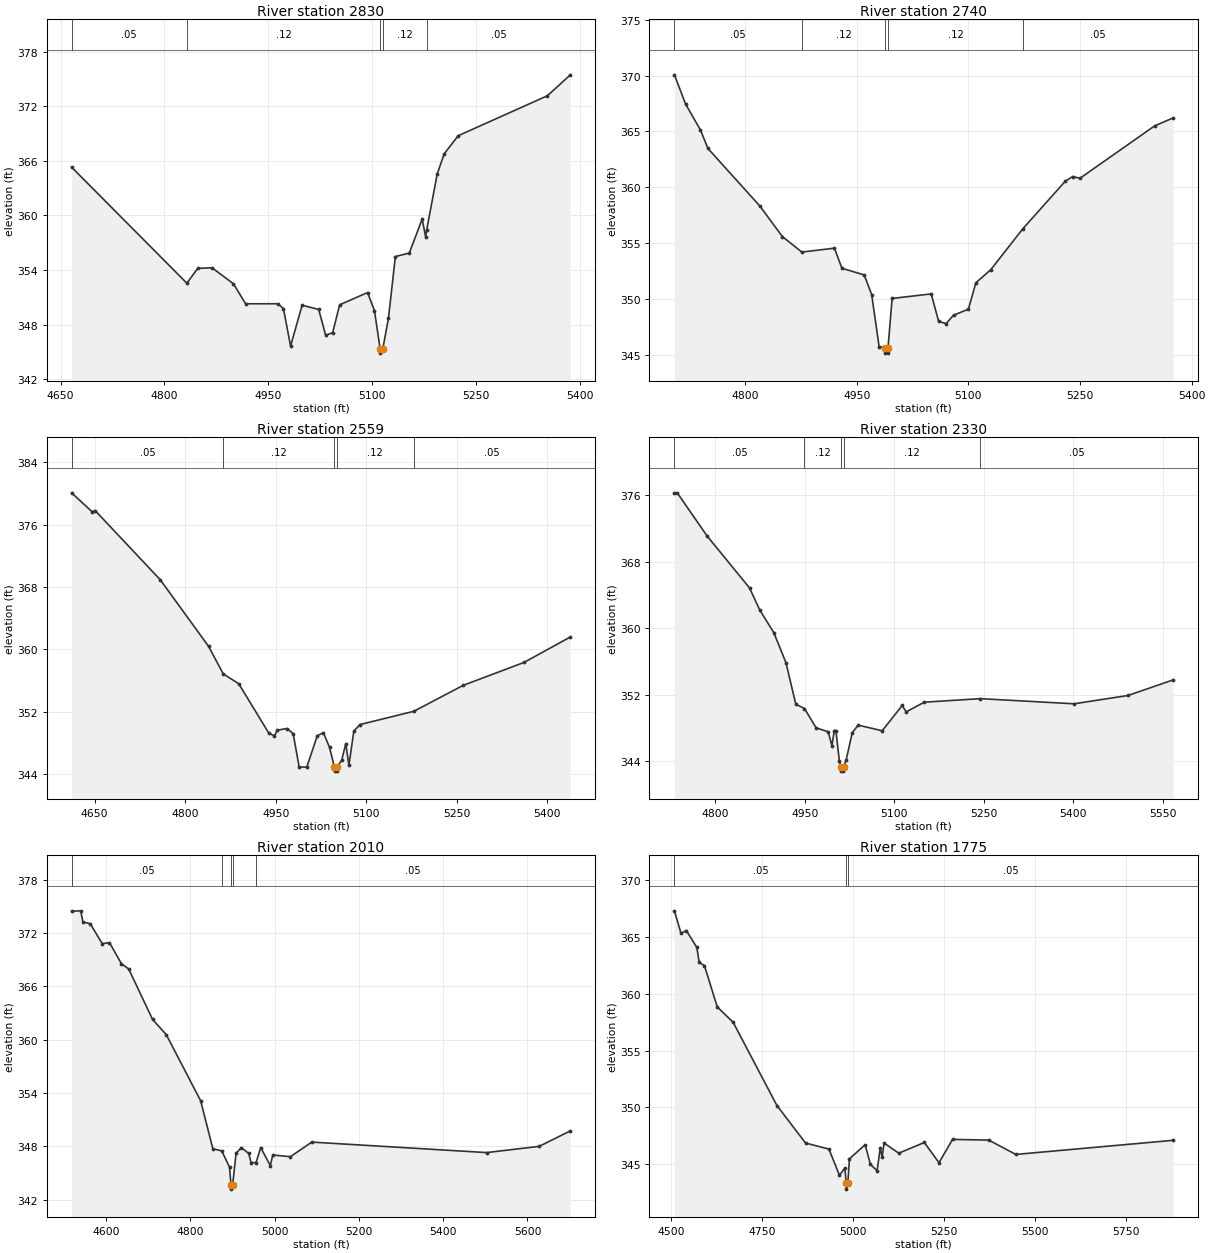
Type RM Length L Ch R = 1,2830,90,90,90
BEGIN DESCRIPTION:
Lacy 151 472
END DESCRIPTION:
XS GIS Cut Line= 3
      2704002.76      6845497.01      2703678.50      6845416.56
      2703294.97      6845459.32
#Sta/Elev= 30
  4665.9  365.31  4832.3  352.55  4848.0  354.18  4868.6  354.25  4899.5  352.49
  4917.1  350.29  4963.7  350.29  4971.7  349.76  4982.0  345.64  4998.7  350.13
  5022.6  349.66  5032.7  346.82  5042.8  347.12  5052.8  350.17  5093.1  351.52
  5103.1  349.54  5111.2  345.36  5111.4  344.86  5115.2  345.36  5123.3  348.70
  5133.3  355.48  5153.4  355.87  5172.0  359.61  5177.0  357.64  5178.5  358.42
  5193.7  364.57  5203.8  366.78  5223.9  368.77  5352.8  373.17  5385.9  375.47
#Mann=5,-1,0
  4665.9    0.05       0  4832.3    0.12       0  5111.2    0.07       0
  5115.2    0.12       0  5178.5    0.05       0
Bank Sta=5111.2,5115.2
Exp/Cntr=0.3,0.1

Type RM Length L Ch R = 1,2740,181,181,181
BEGIN DESCRIPTION:
Lacy 151 473
END DESCRIPTION:
XS GIS Cut Line= 3
      2704021.01      6845341.58      2703726.11      6845342.54
      2703350.97      6845336.00
#Sta/Elev= 30
  4705.1  370.08  4720.1  367.46  4740.1  365.13  4750.1  363.48  4820.1  358.30
  4850.1  355.58  4876.3  354.19  4920.1  354.54  4930.1  352.74  4960.1  352.14
  4970.1  350.38  4980.1  345.72  4988.1  345.63  4988.4  345.13  4991.9  345.13
  4992.1  345.63  4997.6  350.03  5050.1  350.44  5060.1  347.97  5070.1  347.78
  5080.1  348.53  5100.1  349.07  5110.1  351.44  5130.1  352.61  5173.2  356.28
  5230.1  360.53  5240.1  360.96  5250.1  360.81  5350.2  365.50  5375.2  366.22
#Mann=5,-1,0
  4705.1    0.05       0  4876.3    0.12       0  4988.1    0.07       0
  4992.1    0.12       0  5173.2    0.05       0
Bank Sta=4988.1,4992.1
Exp/Cntr=0.3,0.1

Type RM Length L Ch R = 1,2559,229,229,229
BEGIN DESCRIPTION:
Lacy 151 468
END DESCRIPTION:
XS GIS Cut Line= 3
      2704112.97      6845174.82      2703723.40      6845187.63
      2703289.94      6845242.57
#Sta/Elev= 30
  4611.8  380.07  4645.8  377.64  4650.8  377.80  4758.8  368.92  4838.9  360.38
  4863.1  356.86  4888.9  355.59  4938.9  349.23  4948.0  348.92  4953.0  349.65
  4969.0  349.85  4979.0  349.20  4989.0  344.92  5001.6  344.90  5019.1  348.94
  5029.2  349.31  5039.3  347.44  5047.4  344.89  5047.6  344.39  5051.1  344.39
  5051.4  344.89  5059.4  345.76  5066.3  347.92  5071.4  345.13  5079.6  349.51
  5089.7  350.36  5179.0  352.06  5261.0  355.39  5361.8  358.33  5438.5  361.59
#Mann=5,-1,0
  4611.8    0.05       0  4863.1    0.12       0  5047.4    0.07       0
  5051.4    0.12       0  5179.0    0.05       0
Bank Sta=5047.4,5051.4
Exp/Cntr=0.3,0.1

Type RM Length L Ch R = 1,2330,320,320,320
BEGIN DESCRIPTION:
Lacy 151 467
END DESCRIPTION:
XS GIS Cut Line= 3
      2704090.27      6845040.09      2703823.25      6844995.07
      2703260.56      6845051.53
#Sta/Elev= 30
  4731.5  376.31  4736.2  376.31  4786.5  371.09  4857.5  364.85  4874.6  362.19
  4898.1  359.48  4918.4  355.87  4935.1  350.84  4949.6  350.33  4969.1  348.00
  4989.4  347.53  4995.6  345.84  4999.5  347.68  5002.3  347.68  5008.1  343.97
  5011.1  343.29  5011.4  342.79  5014.9  342.79  5015.1  343.29  5019.6  344.18
  5029.7  347.43  5039.7  348.33  5079.9  347.65  5113.4  350.70  5120.1  349.92
  5150.3  351.09  5244.2  351.52  5401.5  350.90  5492.0  351.90  5567.8  353.78
#Mann=5,-1,0
  4731.5    0.05       0  4949.6    0.12       0  5011.1    0.07       0
  5015.1    0.12       0  5244.2    0.05       0
Bank Sta=5011.1,5015.1
Exp/Cntr=0.3,0.1

Type RM Length L Ch R = 1,2010,235,235,235
BEGIN DESCRIPTION:
Lacy 151 471
END DESCRIPTION:
XS GIS Cut Line= 3
      2704199.33      6844925.66      2703763.37      6844720.96
      2703069.51      6844614.50
#Sta/Elev= 30
  4518.2  374.46  4539.7  374.50  4545.2  373.24  4562.5  373.05  4590.8  370.81
  4608.1  370.92  4636.5  368.55  4653.7  367.96  4710.4  362.28  4742.8  360.58
  4824.5  353.13  4853.3  347.75  4874.7  347.49  4892.9  345.67  4896.4  343.70
  4896.7  343.20  4900.4  343.70  4908.5  347.24  4921.2  347.87  4938.5  347.21
  4944.1  346.19  4956.0  346.19  4966.9  347.88  4989.7  345.85  4995.6  347.04
  5037.6  346.85  5088.2  348.49  5503.0  347.31  5627.7  348.01  5701.8  349.75
#Mann=5,-1,0
  4518.2    0.05       0  4874.7    0.12       0  4896.4    0.04       0
  4900.4    0.12       0  4956.0    0.05       0
Bank Sta=4896.4,4900.4
Exp/Cntr=0.3,0.1

Type RM Length L Ch R = 1,1775,151,151,151
BEGIN DESCRIPTION:
Lacy 151 469
END DESCRIPTION:
XS GIS Cut Line= 3
      2704285.87      6844836.75      2703849.22      6844497.78
      2703035.86      6844414.39
#Sta/Elev= 30
  4510.2  367.28  4528.4  365.29  4542.9  365.55  4571.8  364.06  4578.2  362.74
  4592.6  362.47  4627.9  358.83  4671.4  357.49  4791.8  350.17  4870.5  346.87
  4934.8  346.34  4963.7  344.03  4978.2  344.68  4982.6  343.32  4982.8  342.82
  4986.6  343.32  4991.1  345.49  5034.3  346.72  5048.8  344.99  5067.1  344.44
  5075.8  346.44  5080.9  345.65  5086.3  346.87  5126.5  345.98  5196.9  346.92
  5237.1  345.14  5274.4  347.19  5373.7  347.13  5448.2  345.87  5880.6  347.11
#Mann=3,-1,0
  4510.2    0.05       0  4982.6    0.04       0  4986.6    0.05       0
Bank Sta=4982.6,4986.6
Exp/Cntr=0.3,0.1

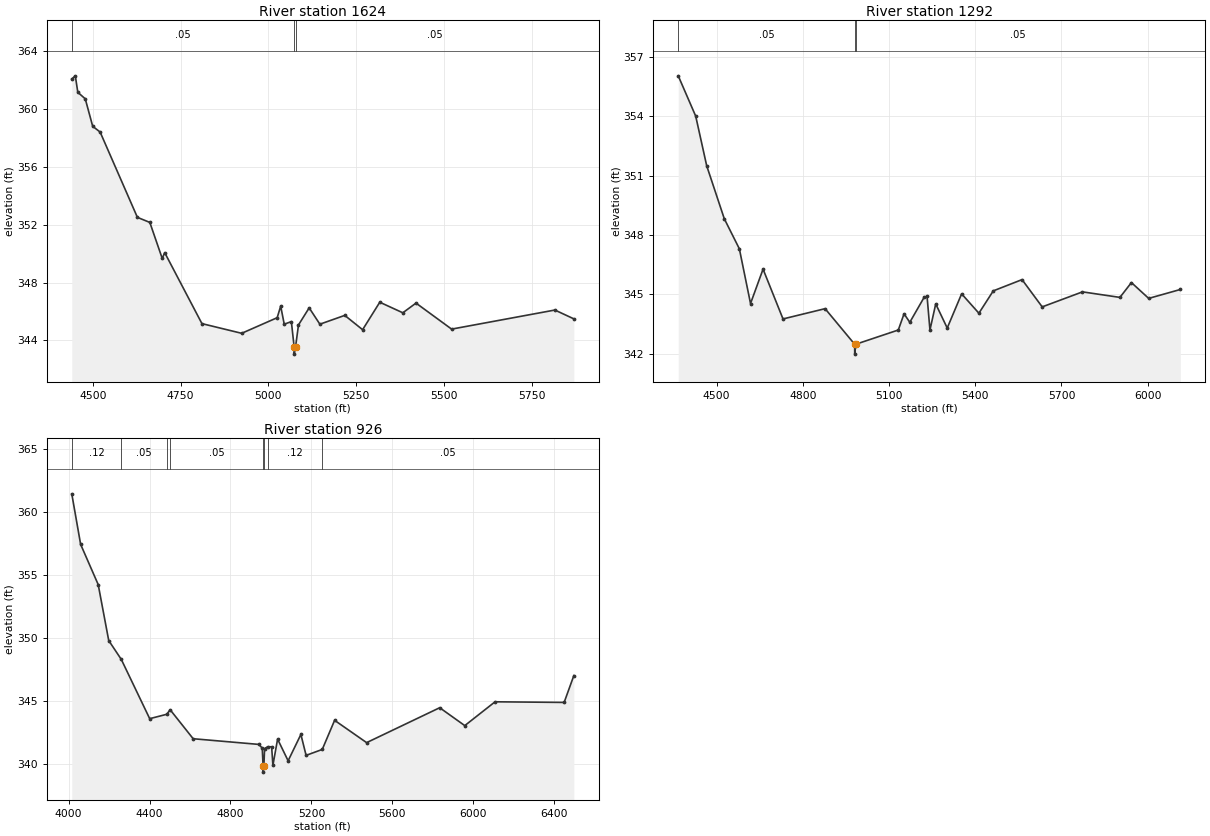
Type RM Length L Ch R = 1,1624,332,332,332
BEGIN DESCRIPTION:
Lacy 151 470
END DESCRIPTION:
XS GIS Cut Line= 3
      2704367.38      6844803.94      2703972.40      6844409.66
      2703112.74      6844264.61
#Sta/Elev= 30
  4440.1  362.08  4450.2  362.30  4457.3  361.16  4478.5  360.71  4499.7  358.81
  4520.9  358.41  4627.0  352.51  4662.4  352.16  4697.7  349.67  4704.8  350.07
  4810.8  345.16  4924.0  344.49  5025.1  345.57  5035.1  346.37  5045.2  345.12
  5065.5  345.30  5073.4  343.55  5073.7  343.05  5077.4  343.55  5085.8  345.07
  5116.2  346.25  5146.7  345.12  5217.6  345.73  5268.4  344.74  5317.3  346.64
  5382.9  345.91  5420.5  346.58  5521.9  344.78  5816.0  346.10  5870.0  345.49
#Mann=3,-1,0
  4440.1    0.05       0  5073.4    0.04       0  5077.4    0.05       0
Bank Sta=5073.4,5077.4
Exp/Cntr=0.3,0.1

Type RM Length L Ch R = 1,1292,366,366,366
BEGIN DESCRIPTION:
Lacy 151 466
END DESCRIPTION:
XS GIS Cut Line= 3
      2704435.10      6844731.85      2704187.39      6844159.11
      2703066.15      6844215.93
#Sta/Elev= 30
  4366.8  356.05  4427.6  354.01  4465.8  351.50  4527.0  348.82  4579.4  347.30
  4618.3  344.53  4661.9  346.27  4731.3  343.75  4877.7  344.27  4980.5  342.47
  4980.8  341.97  4984.5  342.47  5132.4  343.19  5152.4  344.01  5172.4  343.58
  5222.5  344.85  5232.5  344.89  5242.5  343.19  5262.6  344.51  5302.6  343.29
  5352.7  345.02  5412.8  344.04  5462.8  345.17  5562.9  345.74  5633.0  344.36
  5773.2  345.12  5903.4  344.84  5943.4  345.59  6003.5  344.79  6113.5  345.24
#Mann=3,-1,0
  4366.8    0.05       0  4980.5    0.04       0  4984.5    0.05       0
Bank Sta=4980.5,4984.5
Exp/Cntr=0.3,0.1

Type RM Length L Ch R = 1,926,0,0,0
BEGIN DESCRIPTION:
Lacy 151 53
END DESCRIPTION:
XS GIS Cut Line= 4
      2704676.00      6844761.00      2704276.00      6843861.00
      2704226.09      6843748.70      2702930.80      6844204.09
#Sta/Elev= 30
  4015.9  361.44  4059.7  357.43  4146.5  354.24  4198.5  349.80  4260.7  348.30
  4401.0  343.60  4485.2  343.95  4502.0  344.31  4615.7  342.01  4939.9  341.56
  4957.0  341.27  4961.2  339.86  4961.4  339.36  4965.2  339.86  4968.6  341.23
  4983.6  341.37  5003.5  341.37  5009.7  339.90  5032.9  341.98  5084.9  340.26
  5148.0  342.35  5173.7  340.69  5253.6  341.16  5314.6  343.47  5472.8  341.70
  5833.9  344.47  5957.8  343.05  6107.4  344.94  6448.8  344.89  6496.7  347.02
#Mann=8,-1,0
  4015.9    0.12       0  4260.7    0.05       0  4485.2    0.12       0
  4502.0    0.05       0  4961.2    0.07       0  4965.2    0.05       0
  4983.6    0.12       0  5253.6    0.05       0
Bank Sta=4961.2,4965.2
Exp/Cntr=0.3,0.1

Chan Stop Cuts=-1