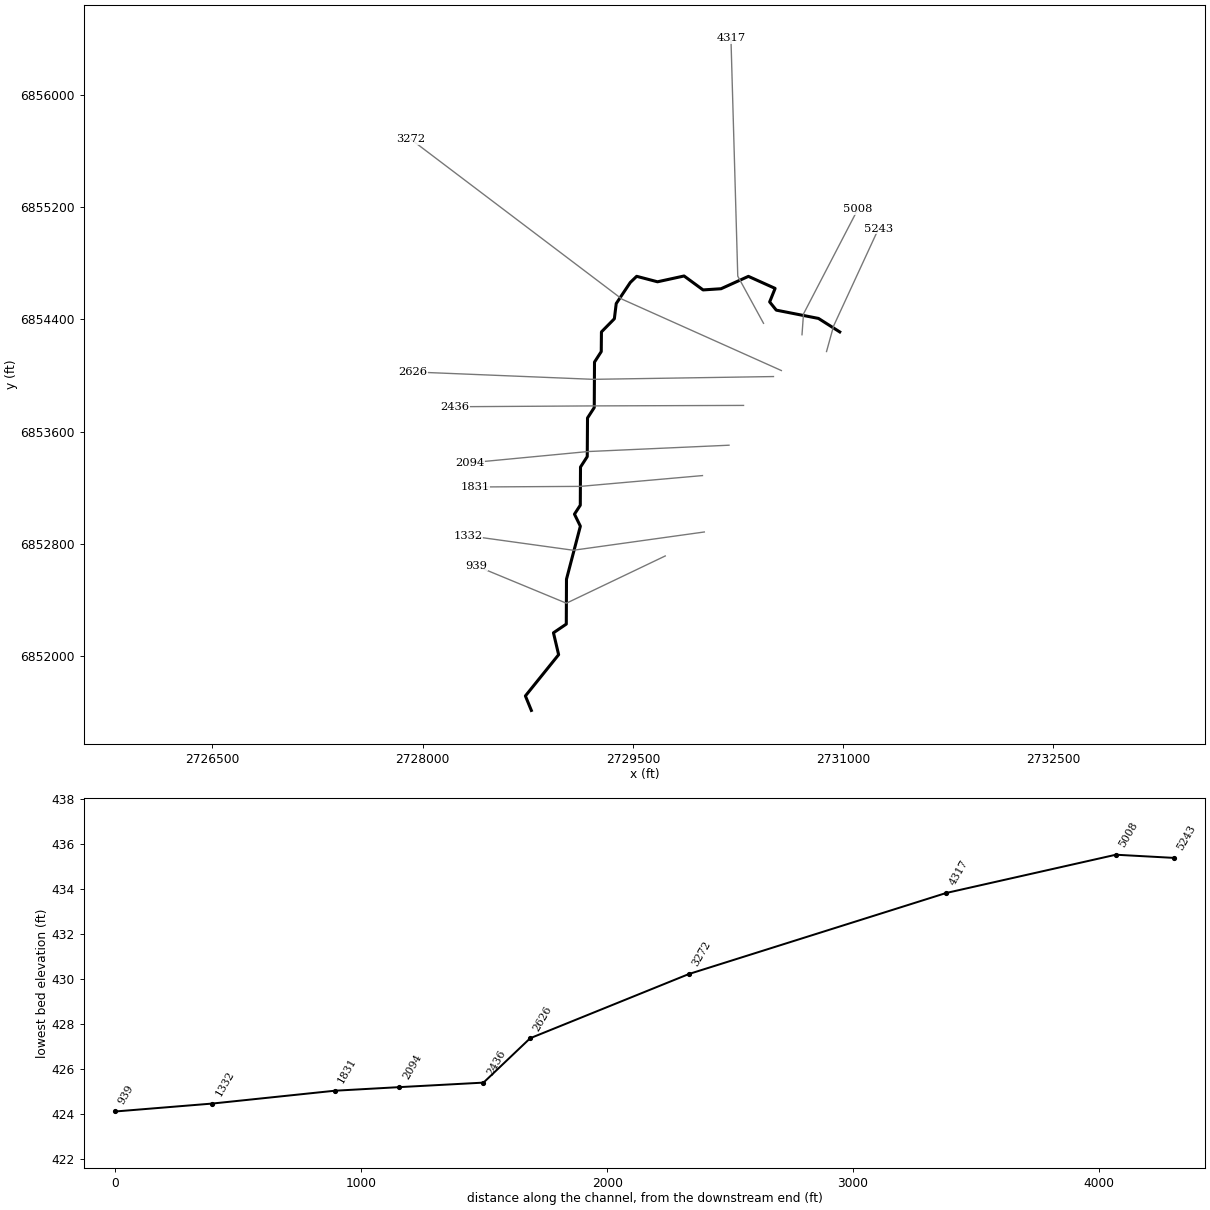
--- Lacy 154.prj (project) ---

Proj Title=Lacy 154 Base Level Engineering
Current Plan=p01
Default Exp/Contr=0.3,0.1
English Units
Geom File=g01
Flow File=f01
Plan File=p01
BEGIN DESCRIPTION:
Lacy 154
END DESCRIPTION:

--- Lacy 154.p01 (plan) ---

Plan Title=Multiple Run
Short Identifier=Multiple
Geom File=g01
Flow File=f01
Subcritical Flow
K Sum by GR= 0
Std Step Tol= 0.01
Critical Tol= 0.01
Num of Std Step Trials= 20
Max Error Tol= 0.3
Flow Tol Ratio= 0.001
Split Flow NTrial= 30
Split Flow Tol= 0.02
Split Flow Ratio= 0.02
Log Output Level= 0
Friction Slope Method= 1
Unsteady Friction Slope Method= 2
Unsteady Bridges Friction Slope Method= 1
Parabolic Critical Depth
Global Vel Dist=  1 , 1 , 1
Global Log Level= 0
CheckData=True
Encroach Param= -1, 0, 0, 0
BEGIN DESCRIPTION:
Multiple Run
END DESCRIPTION:

--- Lacy 154.f01 (steady flow) ---

Flow Title=Multiple
Number of Profiles=7
Profile Names=10-year,25-year,50-year,1pct_min,100-year,1pct_plu,500-year
River Rch & RM= Lacy 154,Reach-1,5243
     391     504     591     344     686    1369     924
River Rch & RM= Lacy 154,Reach-1,2626
     773    1038    1253     749    1494    2980    2122
Boundary for River Rch & Prof#=Lacy 154,Reach-1,1
Up Type=0
Dn Type=3
Dn Slope=0.005
Boundary for River Rch & Prof#=Lacy 154,Reach-1,2
Up Type=0
Dn Type=3
Dn Slope=0.005
Boundary for River Rch & Prof#=Lacy 154,Reach-1,3
Up Type=0
Dn Type=3
Dn Slope=0.005
Boundary for River Rch & Prof#=Lacy 154,Reach-1,4
Up Type=0
Dn Type=3
Dn Slope=0.005
Boundary for River Rch & Prof#=Lacy 154,Reach-1,5
Up Type=0
Dn Type=3
Dn Slope=0.005
Boundary for River Rch & Prof#=Lacy 154,Reach-1,6
Up Type=0
Dn Type=3
Dn Slope=0.005
Boundary for River Rch & Prof#=Lacy 154,Reach-1,7
Up Type=0
Dn Type=3
Dn Slope=0.005

--- Lacy 154.g01 (geometry) ---

Geom Title=Existing Conditions

River Reach=Lacy 154,Reach-1
Reach XY= 30
      2730976.00      6854311.00      2730824.42      6854407.18
      2730523.23      6854466.36      2730476.09      6854524.92
      2730515.04      6854621.43      2730324.40      6854707.30
      2730129.33      6854619.01      2730001.00      6854610.59
      2729865.56      6854709.96      2729676.00      6854668.56
      2729527.28      6854707.63      2729481.74      6854663.58
      2729381.54      6854513.42      2729368.21      6854404.80
      2729276.00      6854311.00      2729274.67      6854170.64
      2729226.52      6854095.78      2729224.78      6853771.50
      2729176.68      6853697.08      2729174.78      6853421.50
      2729126.68      6853347.08      2729125.17      6853074.86
      2729083.59      6853010.99      2729125.70      6852925.13
      2729026.68      6852547.08      2729025.31      6852226.83
      2728933.73      6852164.65      2728970.59      6852008.58
      2728733.59      6851714.39      2728776.00      6851611.00

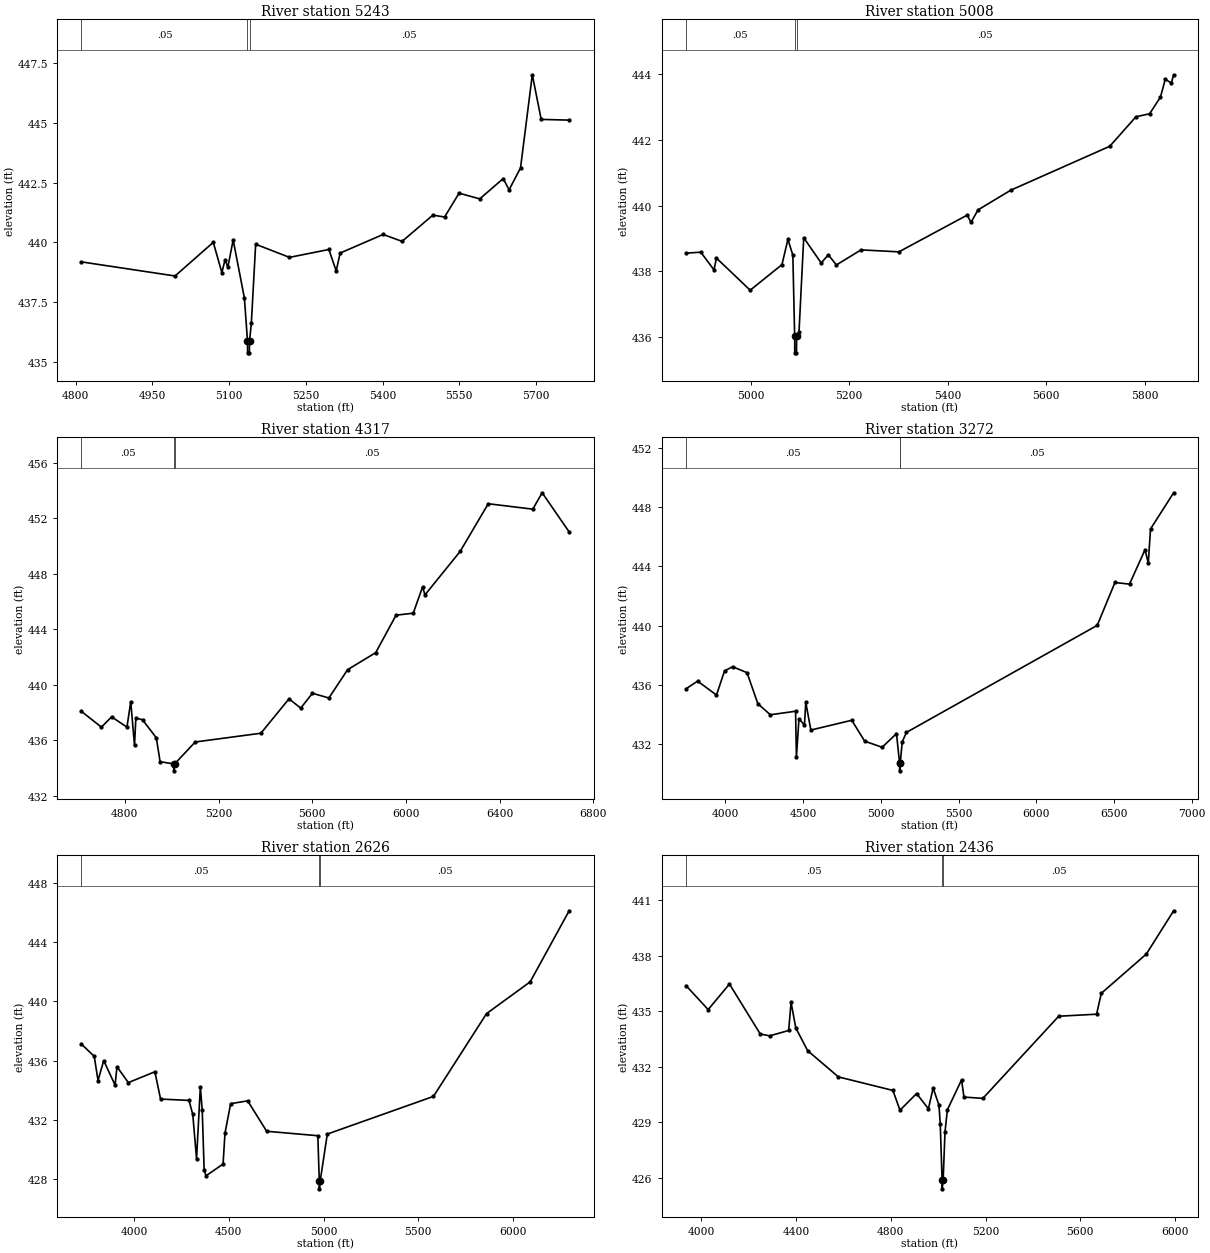
Type RM Length L Ch R = 1,5243,235,235,235
BEGIN DESCRIPTION:
Lacy 154 859
END DESCRIPTION:
XS GIS Cut Line= 3
      2730881.83      6854171.12      2730932.15      6854353.09
      2731253.01      6855047.66
#Sta/Elev= 30
  4811.2  439.18  4994.2  438.59  5069.0  440.00  5085.8  438.73  5092.0  439.27
  5097.5  438.96  5107.9  440.10  5129.9  437.66  5135.9  435.87  5136.1  435.37
  5139.6  435.37  5139.9  435.87  5143.4  436.60  5151.9  439.92  5218.0  439.37
  5295.1  439.70  5309.4  438.80  5317.1  439.55  5401.2  440.33  5438.3  440.04
  5498.5  441.14  5521.4  441.06  5549.8  442.06  5590.2  441.82  5636.1  442.67
  5647.6  442.20  5670.0  443.12  5693.0  447.02  5710.4  445.15  5765.1  445.12
#Mann=3,-1,0
  4811.2    0.05       0  5135.9    0.04       0  5139.9    0.05       0
Bank Sta=5135.9,5139.9
Exp/Cntr=0.3,0.1

Type RM Length L Ch R = 1,5008,691,691,691
BEGIN DESCRIPTION:
Lacy 154 853
END DESCRIPTION:
XS GIS Cut Line= 3
      2730706.79      6854290.96      2730717.47      6854439.22
      2731105.16      6855186.04
#Sta/Elev= 30
  4868.6  438.55  4898.7  438.58  4925.5  438.04  4930.5  438.40  4999.0  437.42
  5063.5  438.20  5075.6  438.97  5085.6  438.49  5089.3  436.01  5089.5  435.51
  5093.0  435.51  5093.3  436.01  5098.1  436.14  5107.7  439.02  5143.2  438.25
  5157.6  438.50  5174.1  438.19  5224.0  438.65  5300.9  438.59  5439.5  439.71
  5447.4  439.49  5461.6  439.87  5528.0  440.47  5729.1  441.81  5782.2  442.71
  5809.9  442.80  5832.0  443.31  5841.7  443.85  5854.2  443.74  5858.7  443.99
#Mann=3,-1,0
  4868.6    0.05       0  5089.3    0.04       0  5093.3    0.05       0
Bank Sta=5089.3,5093.3
Exp/Cntr=0.3,0.1

Type RM Length L Ch R = 1,4317,1045,1045,1045
BEGIN DESCRIPTION:
Lacy 154 855
END DESCRIPTION:
XS GIS Cut Line= 3
      2730432.30      6854372.41      2730248.57      6854708.74
      2730199.85      6856406.20
#Sta/Elev= 30
  4614.9  438.09  4699.9  436.96  4743.5  437.70  4809.0  436.96  4825.1  438.80
  4841.2  435.64  4847.0  437.62  4875.4  437.49  4934.3  436.19  4950.4  434.47
  5008.4  434.31  5008.7  433.81  5012.4  434.31  5100.4  435.89  5380.6  436.52
  5500.6  439.00  5550.6  438.33  5600.6  439.40  5670.7  439.06  5750.7  441.10
  5870.8  442.33  5957.5  445.03  6030.8  445.17  6070.8  447.07  6080.8  446.49
  6230.9  449.62  6351.0  453.06  6541.0  452.67  6581.1  453.85  6696.3  451.03
#Mann=3,-1,0
  4614.9    0.05       0  5008.4    0.04       0  5012.4    0.05       0
Bank Sta=5008.4,5012.4
Exp/Cntr=0.3,0.1

Type RM Length L Ch R = 1,3272,646,646,646
BEGIN DESCRIPTION:
Lacy 154 854
END DESCRIPTION:
XS GIS Cut Line= 3
      2730559.60      6854035.45      2729424.25      6854543.90
      2727914.01      6855686.89
#Sta/Elev= 30
  3746.0  435.75  3821.0  436.27  3942.4  435.33  3994.2  436.96  4046.1  437.24
  4138.9  436.84  4208.4  434.75  4289.0  434.00  4451.2  434.24  4456.8  431.14
  4473.1  433.73  4508.6  433.31  4516.9  434.85  4549.5  432.97  4812.8  433.63
  4896.1  432.22  5008.3  431.81  5100.7  432.73  5120.8  430.72  5121.0  430.22
  5124.8  430.72  5137.3  432.16  5164.4  432.81  6392.4  440.03  6506.5  442.92
  6600.1  442.81  6700.0  445.13  6720.8  444.22  6735.3  446.53  6884.0  448.97
#Mann=3,-1,0
  3746.0    0.05       0  5120.8    0.04       0  5124.8    0.05       0
Bank Sta=5120.8,5124.8
Exp/Cntr=0.3,0.1

Type RM Length L Ch R = 1,2626,190,190,190
BEGIN DESCRIPTION:
Lacy 154 852
END DESCRIPTION:
XS GIS Cut Line= 3
      2730503.31      6853992.58      2729217.39      6853972.75
      2727930.35      6854025.64
#Sta/Elev= 30
  3722.4  437.12  3789.7  436.30  3809.7  434.67  3839.7  436.01  3899.7  434.36
  3909.7  435.60  3969.7  434.53  4109.8  435.26  4139.8  433.42  4289.8  433.33
  4309.8  432.39  4329.8  429.39  4349.8  434.24  4359.8  432.66  4369.8  428.67
  4379.8  428.25  4469.8  429.04  4479.8  431.12  4509.8  433.11  4599.8  433.30
  4699.8  431.25  4969.9  430.95  4977.7  427.87  4978.1  427.37  4982.1  427.87
  5019.9  431.06  5580.3  433.60  5860.6  439.18  6090.8  441.32  6296.6  446.11
#Mann=3,-1,0
  3722.4    0.05       0  4977.7    0.04       0  4982.1    0.05       0
Bank Sta=4977.7,4982.1
Exp/Cntr=0.3,0.1

Type RM Length L Ch R = 1,2436,342,342,342
BEGIN DESCRIPTION:
Lacy 154 850
END DESCRIPTION:
XS GIS Cut Line= 3
      2730289.74      6853786.67      2729221.47      6853783.22
      2728230.66      6853777.28
#Sta/Elev= 30
  3935.1  436.39  4028.8  435.09  4118.8  436.47  4248.8  433.77  4288.8  433.67
  4368.8  433.96  4378.8  435.48  4398.8  434.10  4448.8  432.87  4578.8  431.45
  4808.8  430.72  4838.8  429.65  4908.8  430.55  4958.8  429.73  4978.8  430.85
  5003.4  429.92  5008.8  428.90  5016.5  425.90  5017.0  425.40  5021.1  425.90
  5028.8  428.47  5038.8  429.67  5098.8  431.29  5108.8  430.36  5188.8  430.29
  5508.9  434.73  5668.9  434.84  5688.9  435.97  5878.9  438.09  5994.2  440.43
#Mann=3,-1,0
  3935.1    0.05       0  5016.5    0.05       0  5021.1    0.05       0
Bank Sta=5016.5,5021.1
Exp/Cntr=0.3,0.1

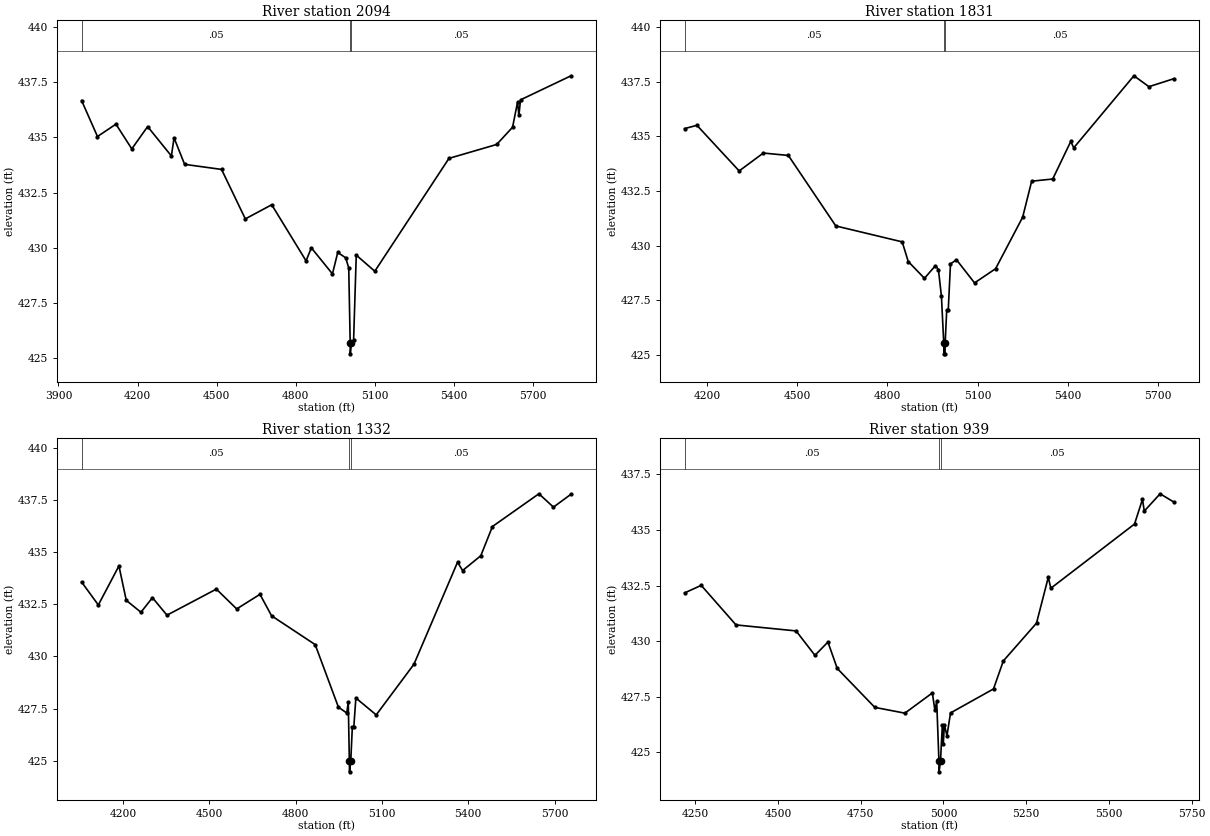
Type RM Length L Ch R = 1,2094,263,263,263
BEGIN DESCRIPTION:
Lacy 154 851
END DESCRIPTION:
XS GIS Cut Line= 3
      2730186.20      6853502.82      2729177.73      6853457.48
      2728335.24      6853377.10
#Sta/Elev= 30
  3987.8  436.67  4048.1  435.04  4118.1  435.60  4178.2  434.48  4238.2  435.49
  4328.3  434.16  4338.4  434.98  4378.4  433.78  4518.5  433.55  4608.6  431.31
  4708.7  431.95  4838.9  429.41  4858.9  430.00  4939.0  428.82  4959.0  429.79
  4989.0  429.55  5000.7  429.09  5006.2  425.70  5006.6  425.20  5010.8  425.70
  5019.1  425.81  5029.2  429.67  5099.5  428.94  5380.7  434.05  5561.6  434.68
  5621.8  435.46  5640.8  436.60  5645.8  436.00  5652.0  436.70  5843.6  437.79
#Mann=3,-1,0
  3987.8    0.05       0  5006.2   0.035       0  5010.8    0.05       0
Bank Sta=5006.2,5010.8
Exp/Cntr=0.3,0.1

Type RM Length L Ch R = 1,1831,499,499,499
BEGIN DESCRIPTION:
Lacy 154 858
END DESCRIPTION:
XS GIS Cut Line= 3
      2729996.71      6853286.22      2729125.92      6853209.15
      2728372.33      6853204.79
#Sta/Elev= 30
  4125.8  435.36  4166.7  435.51  4307.2  433.42  4387.5  434.24  4470.7  434.13
  4628.5  430.90  4849.3  430.17  4869.4  429.27  4923.4  428.50  4959.8  429.08
  4969.8  428.90  4979.8  427.68  4987.5  425.54  4988.0  425.04  4991.7  425.04
  4992.2  425.54  4997.4  427.05  5002.5  427.05  5009.9  429.16  5029.9  429.35
  5089.9  428.29  5159.9  428.94  5249.9  431.30  5279.9  432.95  5349.9  433.05
  5409.9  434.77  5419.9  434.48  5619.9  437.78  5669.9  437.28  5753.6  437.65
#Mann=3,-1,0
  4125.8    0.05       0  4987.5   0.035       0  4992.2    0.05       0
Bank Sta=4987.5,4992.2
Exp/Cntr=0.3,0.1

Type RM Length L Ch R = 1,1332,393,393,393
BEGIN DESCRIPTION:
Lacy 154 857
END DESCRIPTION:
XS GIS Cut Line= 3
      2730009.84      6852883.89      2729075.29      6852753.48
      2728325.35      6852857.34
#Sta/Elev= 30
  4056.4  433.57  4114.6  432.47  4186.2  434.34  4211.7  432.69  4262.7  432.12
  4302.6  432.82  4353.1  431.98  4524.7  433.23  4595.4  432.28  4676.2  432.98
  4716.6  431.95  4868.0  430.57  4948.8  427.57  4977.9  427.29  4983.0  427.82
  4986.8  424.97  4987.3  424.47  4991.6  424.97  4997.1  426.60  5002.2  426.60
  5009.4  428.01  5080.1  427.20  5211.3  429.63  5362.7  434.52  5380.3  434.12
  5443.5  434.83  5483.9  436.23  5645.4  437.80  5695.9  437.16  5757.1  437.78
#Mann=3,-1,0
  4056.4    0.05       0  4986.8    0.04       0  4991.6    0.05       0
Bank Sta=4986.8,4991.6
Exp/Cntr=0.3,0.1

Type RM Length L Ch R = 1,939,0,0,0
BEGIN DESCRIPTION:
Lacy 154 856
END DESCRIPTION:
XS GIS Cut Line= 3
      2729731.25      6852712.84      2729025.95      6852375.78
      2728381.86      6852642.18
#Sta/Elev= 30
  4218.3  432.17  4268.4  432.51  4373.5  430.73  4555.0  430.46  4612.0  429.36
  4651.2  429.96  4679.4  428.77  4792.8  427.02  4883.6  426.76  4966.7  427.67
  4974.3  426.89  4979.8  427.29  4986.5  424.62  4987.0  424.12  4991.3  424.62
  4996.9  426.24  4999.7  425.38  5003.0  426.24  5010.8  425.74  5021.5  426.77
  5151.4  427.85  5181.1  429.11  5281.3  430.81  5316.9  432.87  5324.6  432.38
  5577.5  435.27  5601.4  436.38  5606.9  435.85  5654.7  436.63  5697.0  436.25
#Mann=3,-1,0
  4218.3    0.05       0  4986.5    0.04       0  4991.3    0.05       0
Bank Sta=4986.5,4991.3
Exp/Cntr=0.3,0.1

Chan Stop Cuts=-1