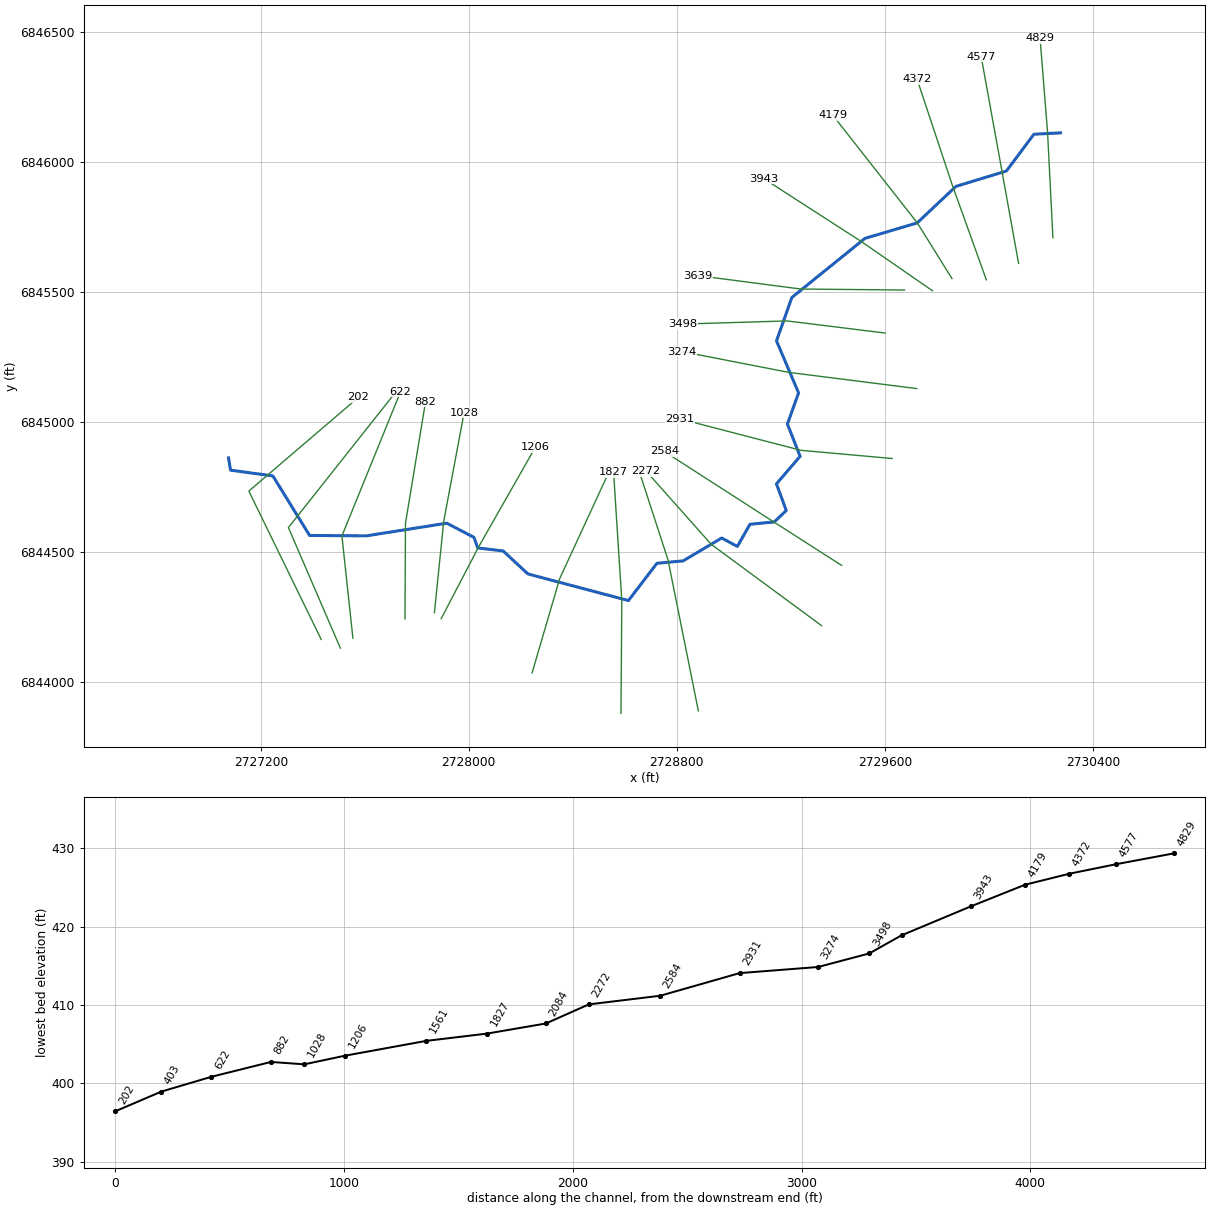
--- Lacy 155.prj (project) ---

Proj Title=Lacy 155 Base Level Engineering
Current Plan=p01
Default Exp/Contr=0.3,0.1
English Units
Geom File=g01
Flow File=f01
Plan File=p01
BEGIN DESCRIPTION:
Lacy 155
END DESCRIPTION:

--- Lacy 155.p01 (plan) ---

Plan Title=Multiple Run
Short Identifier=Multiple
Geom File=g01
Flow File=f01
Subcritical Flow
K Sum by GR= 0
Std Step Tol= 0.01
Critical Tol= 0.01
Num of Std Step Trials= 20
Max Error Tol= 0.3
Flow Tol Ratio= 0.001
Split Flow NTrial= 30
Split Flow Tol= 0.02
Split Flow Ratio= 0.02
Log Output Level= 0
Friction Slope Method= 1
Unsteady Friction Slope Method= 2
Unsteady Bridges Friction Slope Method= 1
Parabolic Critical Depth
Global Vel Dist=  1 , 1 , 1
Global Log Level= 0
CheckData=True
Encroach Param= -1, 0, 0, 0
BEGIN DESCRIPTION:
Multiple Run
END DESCRIPTION:

--- Lacy 155.f01 (steady flow) ---

Flow Title=Multiple
Number of Profiles=7
Profile Names=10-year,25-year,50-year,1pct_min,100-year,1pct_plu,500-year
River Rch & RM= Lacy 155,Reach-1,4829
     422     550     650     382     762    1521    1045
River Rch & RM= Lacy 155,Reach-1,1827
     742    1003    1215     730    1457    2908    2094
Boundary for River Rch & Prof#=Lacy 155,Reach-1,1
Up Type=0
Dn Type=3
Dn Slope=0.005
Boundary for River Rch & Prof#=Lacy 155,Reach-1,2
Up Type=0
Dn Type=3
Dn Slope=0.005
Boundary for River Rch & Prof#=Lacy 155,Reach-1,3
Up Type=0
Dn Type=3
Dn Slope=0.005
Boundary for River Rch & Prof#=Lacy 155,Reach-1,4
Up Type=0
Dn Type=3
Dn Slope=0.005
Boundary for River Rch & Prof#=Lacy 155,Reach-1,5
Up Type=0
Dn Type=3
Dn Slope=0.005
Boundary for River Rch & Prof#=Lacy 155,Reach-1,6
Up Type=0
Dn Type=3
Dn Slope=0.005
Boundary for River Rch & Prof#=Lacy 155,Reach-1,7
Up Type=0
Dn Type=3
Dn Slope=0.005

--- Lacy 155.g01 (geometry) ---

Geom Title=Existing Conditions

River Reach=Lacy 155,Reach-1
Reach XY= 30
      2730276.00      6846111.00      2730173.49      6846105.66
      2730067.66      6845964.16      2729873.70      6845905.17
      2729724.50      6845764.61      2729523.71      6845705.16
      2729242.45      6845477.75      2729183.56      6845311.00
      2729268.44      6845111.00      2729225.43      6844990.95
      2729274.36      6844867.03      2729183.36      6844761.08
      2729221.00      6844658.43      2729174.71      6844614.55
      2729081.48      6844605.68      2729032.93      6844520.23
      2728972.78      6844552.75      2728824.41      6844464.83
      2728723.56      6844455.48      2728613.99      6844312.17
      2728227.50      6844414.62      2728132.12      6844503.10
      2728034.48      6844514.50      2728020.21      6844554.98
      2727915.52      6844609.81      2727605.97      6844561.07
      2727387.83      6844562.62      2727246.55      6844791.55
      2727083.71      6844813.72      2727076.00      6844861.00

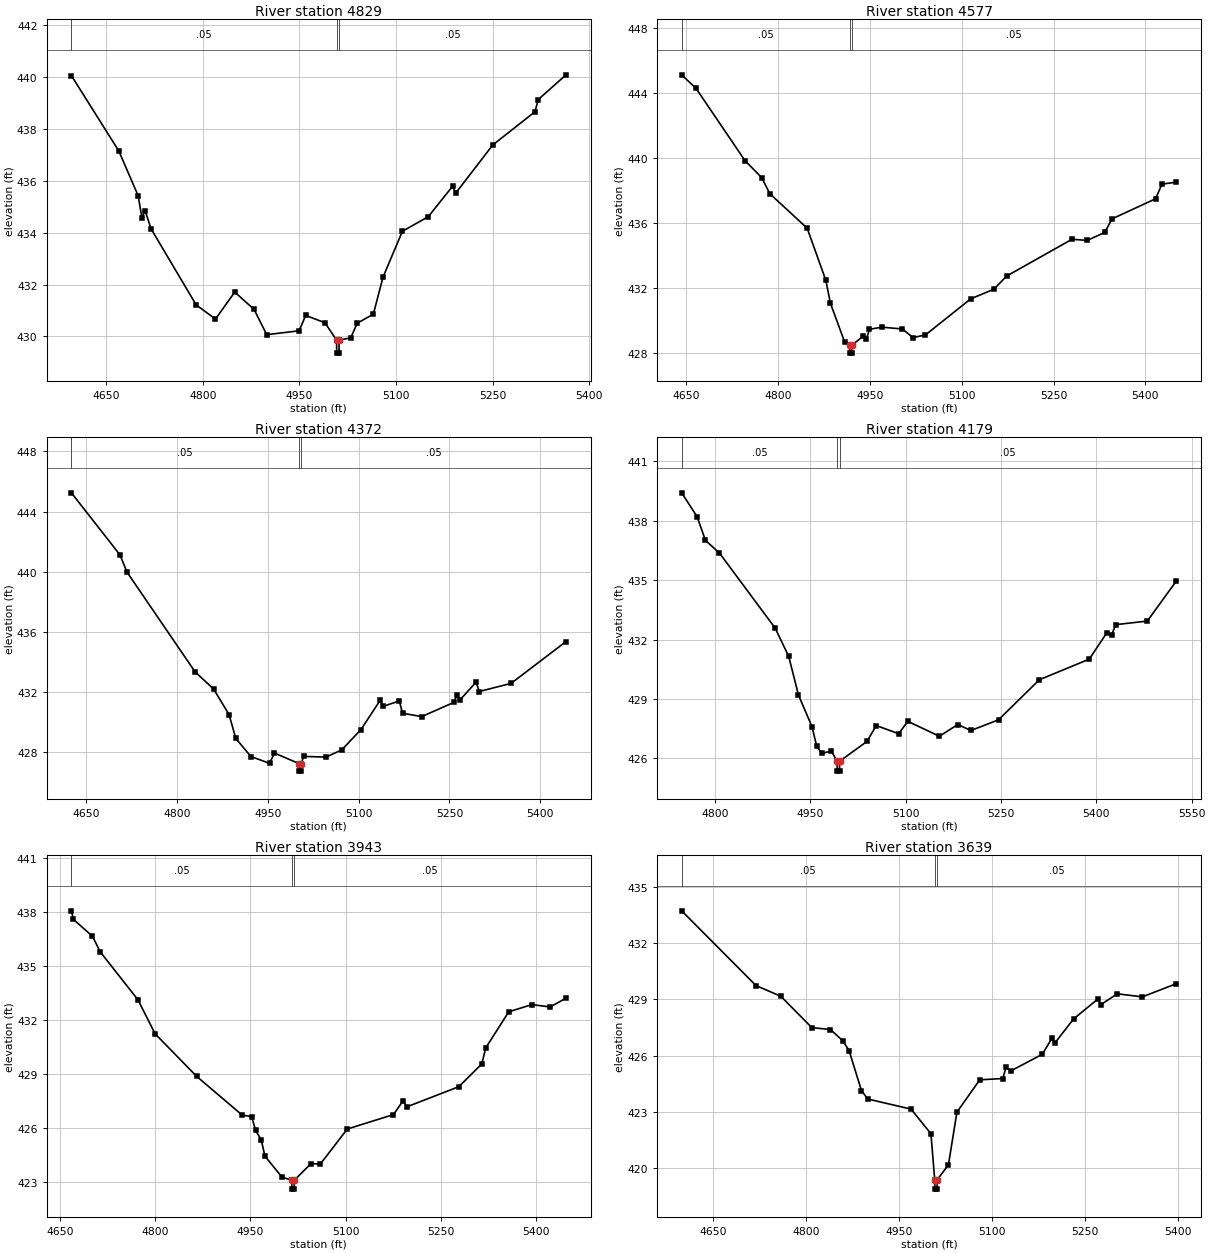
Type RM Length L Ch R = 1,4829,252,252,252
BEGIN DESCRIPTION:
Lacy 155 830
END DESCRIPTION:
XS GIS Cut Line= 3
      2730246.58      6845707.41      2730226.14      6846111.40
      2730197.20      6846474.54
#Sta/Elev= 30
  4595.5  440.04  4669.2  437.14  4699.2  435.42  4705.1  434.57  4710.1  434.84
  4719.2  434.15  4789.3  431.22  4819.4  430.67  4849.4  431.71  4879.5  431.04
  4899.1  430.07  4949.5  430.22  4959.6  430.81  4989.6  430.53  5007.6  429.86
  5007.9  429.36  5011.4  429.36  5011.6  429.86  5029.7  429.95  5039.7  430.51
  5064.8  430.86  5079.9  432.29  5110.0  434.05  5150.1  434.61  5187.9  435.78
  5192.9  435.52  5250.4  437.37  5316.0  438.65  5321.1  439.12  5364.3  440.07
#Mann=3,-1,0
  4595.5    0.05       0  5007.6    0.04       0  5011.6    0.05       0
Bank Sta=5007.6,5011.6
Exp/Cntr=0.3,0.1

Type RM Length L Ch R = 1,4577,205,205,205
BEGIN DESCRIPTION:
Lacy 155 829
END DESCRIPTION:
XS GIS Cut Line= 3
      2730114.53      6845609.24      2730051.12      6845960.87
      2729970.70      6846404.24
#Sta/Elev= 30
  4642.7  445.14  4666.2  444.30  4746.1  439.85  4773.4  438.80  4786.7  437.81
  4847.7  435.68  4878.2  432.46  4885.6  431.06  4908.7  428.68  4916.8  428.48
  4917.1  427.98  4920.6  427.98  4920.8  428.48  4939.2  429.02  4944.3  428.85
  4949.4  429.45  4969.6  429.58  5003.0  429.47  5020.5  428.94  5040.8  429.10
  5114.9  431.33  5152.6  431.92  5173.4  432.73  5280.2  435.00  5305.0  434.93
  5333.6  435.42  5345.7  436.26  5416.8  437.50  5427.0  438.40  5450.6  438.52
#Mann=3,-1,0
  4642.7    0.05       0  4916.8    0.04       0  4920.8    0.05       0
Bank Sta=4916.8,4920.8
Exp/Cntr=0.3,0.1

Type RM Length L Ch R = 1,4372,193,193,193
BEGIN DESCRIPTION:
Lacy 155 826
END DESCRIPTION:
XS GIS Cut Line= 3
      2729990.61      6845545.65      2729858.84      6845912.17
      2729724.27      6846317.11
#Sta/Elev= 30
  4626.2  445.25  4706.3  441.13  4718.0  439.98  4830.2  433.36  4860.9  432.21
  4886.3  430.52  4897.5  428.93  4922.4  427.73  4953.1  427.28  4961.3  427.96
  5001.8  427.26  5002.1  426.76  5005.6  426.76  5005.8  427.26  5009.2  427.74
  5046.1  427.69  5072.3  428.17  5104.0  429.52  5135.6  431.46  5140.9  431.07
  5167.3  431.42  5172.6  430.61  5204.2  430.38  5256.8  431.32  5262.3  431.79
  5267.6  431.50  5294.0  432.67  5299.2  432.05  5351.7  432.59  5442.4  435.37
#Mann=3,-1,0
  4626.2    0.05       0  5001.8    0.04       0  5005.8    0.05       0
Bank Sta=5001.8,5005.8
Exp/Cntr=0.3,0.1

Type RM Length L Ch R = 1,4179,236,236,236
BEGIN DESCRIPTION:
Lacy 155 825
END DESCRIPTION:
XS GIS Cut Line= 3
      2729858.37      6845550.45      2729725.72      6845763.83
      2729400.23      6846178.62
#Sta/Elev= 30
  4747.4  439.40  4771.6  438.20  4784.8  437.00  4806.9  436.36  4894.6  432.57
  4915.8  431.15  4931.2  429.20  4952.4  427.61  4960.0  426.61  4967.8  426.26
  4983.1  426.37  4992.0  425.86  4992.3  425.36  4995.8  425.36  4996.0  425.86
  5039.1  426.86  5053.6  427.66  5088.8  427.25  5103.3  427.87  5153.0  427.12
  5181.9  427.71  5202.7  427.41  5246.1  427.95  5310.3  429.97  5388.9  431.01
  5416.1  432.32  5424.2  432.24  5430.5  432.75  5480.2  432.93  5525.9  434.95
#Mann=3,-1,0
  4747.4    0.05       0  4992.0    0.04       0  4996.0    0.05       0
Bank Sta=4992,4996
Exp/Cntr=0.3,0.1

Type RM Length L Ch R = 1,3943,304,304,304
BEGIN DESCRIPTION:
Lacy 155 824
END DESCRIPTION:
XS GIS Cut Line= 3
      2729783.31      6845503.81      2729510.17      6845692.76
      2729134.98      6845934.78
#Sta/Elev= 30
  4668.1  438.07  4671.4  437.59  4701.2  436.66  4713.5  435.79  4772.8  433.13
  4799.8  431.24  4865.4  428.87  4937.0  426.72  4951.9  426.64  4958.0  425.87
  4966.8  425.36  4972.8  424.44  4999.7  423.27  5015.1  423.11  5015.3  422.61
  5018.8  422.61  5019.1  423.11  5045.0  424.02  5060.1  424.01  5102.4  425.95
  5175.0  426.75  5190.2  427.52  5196.1  427.18  5277.9  428.30  5314.2  429.57
  5320.2  430.45  5356.5  432.46  5392.8  432.86  5421.7  432.73  5446.7  433.22
#Mann=3,-1,0
  4668.1    0.05       0  5015.1    0.04       0  5019.1    0.05       0
Bank Sta=5015.1,5019.1
Exp/Cntr=0.3,0.1

Type RM Length L Ch R = 1,3639,141,141,141
BEGIN DESCRIPTION:
Lacy 155 823
END DESCRIPTION:
XS GIS Cut Line= 3
      2729675.76      6845506.55      2729277.07      6845510.39
      2728881.71      6845561.84
#Sta/Elev= 30
  4599.7  433.72  4719.5  429.74  4759.5  429.17  4809.5  427.50  4839.5  427.40
  4859.5  426.80  4869.5  426.28  4889.5  424.15  4899.5  423.70  4969.5  423.16
  5001.5  421.85  5007.6  419.40  5007.8  418.90  5011.3  418.90  5011.6  419.40
  5029.7  420.19  5043.4  423.00  5080.2  424.72  5117.4  424.79  5122.5  425.38
  5130.6  425.20  5181.0  426.08  5196.5  426.93  5201.5  426.69  5231.4  427.96
  5270.5  429.02  5275.6  428.73  5302.0  429.30  5342.4  429.14  5397.1  429.84
#Mann=3,-1,0
  4599.7    0.05       0  5007.6    0.05       0  5011.6    0.05       0
Bank Sta=5007.6,5011.6
Exp/Cntr=0.3,0.1

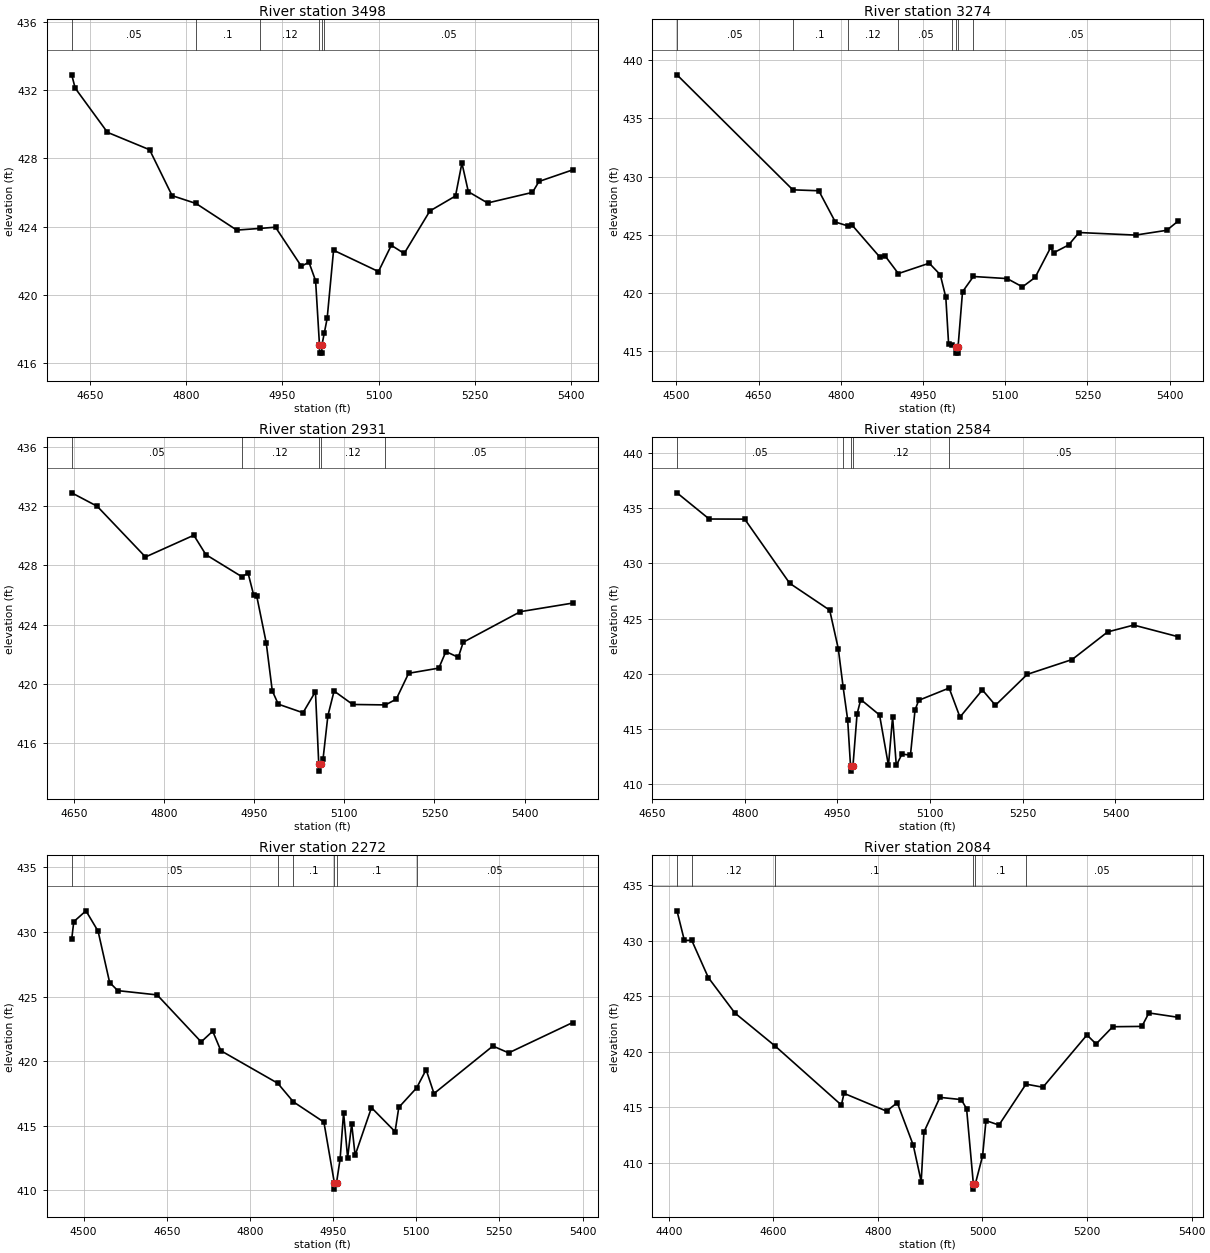
Type RM Length L Ch R = 1,3498,224,224,224
BEGIN DESCRIPTION:
Lacy 155 822
END DESCRIPTION:
XS GIS Cut Line= 3
      2729601.33      6845341.10      2729223.97      6845387.69
      2728823.37      6845375.65
#Sta/Elev= 30
  4621.6  432.90  4627.0  432.12  4677.3  429.53  4743.0  428.51  4778.1  425.82
  4815.4  425.36  4878.9  423.80  4915.4  423.90  4939.3  423.97  4979.6  421.68
  4991.4  421.92  5001.8  420.83  5007.8  417.09  5008.0  416.59  5011.5  416.59
  5011.8  417.09  5015.3  417.76  5019.8  418.62  5029.8  422.62  5099.8  421.37
  5119.8  422.91  5139.9  422.43  5179.9  424.92  5219.9  425.80  5229.9  427.73
  5239.9  426.05  5269.9  425.39  5339.9  426.01  5350.0  426.65  5402.6  427.33
#Mann=6,-1,0
  4621.6    0.05       0  4815.4     0.1       0  4915.4    0.12       0
  5007.8    0.07       0  5011.8    0.12       0  5015.3    0.05       0
Bank Sta=5007.8,5011.8
Exp/Cntr=0.3,0.1

Type RM Length L Ch R = 1,3274,343,343,343
BEGIN DESCRIPTION:
Lacy 155 814
END DESCRIPTION:
XS GIS Cut Line= 3
      2729722.73      6845127.46      2729230.85      6845189.83
      2728820.07      6845269.76
#Sta/Elev= 30
  4500.9  438.72  4712.3  428.86  4759.7  428.78  4789.9  426.10  4812.4  425.77
  4820.2  425.85  4870.6  423.12  4880.6  423.20  4904.9  421.68  4961.3  422.57
  4981.4  421.58  4991.5  419.65  4996.6  415.65  5003.3  415.59  5009.8  415.36
  5010.1  414.86  5013.6  414.86  5013.8  415.36  5022.0  420.12  5041.8  421.43
  5103.5  421.25  5131.4  420.54  5154.5  421.35  5183.0  423.93  5188.1  423.46
  5215.6  424.13  5234.7  425.20  5337.8  424.98  5394.7  425.39  5415.2  426.17
#Mann=8,-1,0
  4500.9    0.05       0  4712.3     0.1       0  4812.4    0.12       0
  4904.9    0.05       0  5003.3    0.12       0  5009.8    0.05       0
  5013.8    0.12       0  5041.8    0.05       0
Bank Sta=5009.8,5013.8
Exp/Cntr=0.3,0.1

Type RM Length L Ch R = 1,2931,347,347,347
BEGIN DESCRIPTION:
Lacy 155 815
END DESCRIPTION:
XS GIS Cut Line= 3
      2729628.26      6844858.57      2729278.20      6844889.95
      2728811.82      6845011.01
#Sta/Elev= 30
  4646.6  432.91  4689.0  432.00  4769.3  428.57  4849.7  430.04  4869.7  428.73
  4929.4  427.24  4940.0  427.47  4949.4  425.97  4954.4  425.91  4970.1  422.77
  4980.2  419.51  4990.2  418.61  5031.3  418.03  5052.0  419.46  5057.5  414.58
  5057.8  414.08  5061.5  414.58  5064.7  414.92  5072.7  417.83  5083.0  419.50
  5114.0  418.59  5168.5  418.56  5186.4  418.95  5207.0  420.70  5257.2  421.05
  5269.0  422.17  5289.6  421.78  5297.8  422.80  5392.9  424.87  5479.9  425.45
#Mann=5,-1,0
  4646.6    0.05       0  4929.4    0.12       0  5057.5    0.07       0
  5061.5    0.12       0  5168.5    0.05       0
Bank Sta=5057.5,5061.5
Exp/Cntr=0.3,0.1

Type RM Length L Ch R = 1,2584,312,312,312
BEGIN DESCRIPTION:
Lacy 155 817
END DESCRIPTION:
XS GIS Cut Line= 3
      2729434.16      6844447.41      2729163.59      6844620.60
      2728752.04      6844885.53
#Sta/Elev= 30
  4690.4  436.38  4742.5  434.01  4800.0  434.00  4872.8  428.19  4937.5  425.76
  4951.4  422.28  4959.3  418.78  4966.6  415.84  4971.2  411.69  4971.4  411.19
  4975.2  411.69  4981.8  416.36  4987.8  417.67  5018.2  416.27  5032.6  411.70
  5039.3  416.10  5045.3  411.71  5054.5  412.73  5068.2  412.64  5075.6  416.72
  5081.6  417.60  5130.8  418.71  5148.3  416.08  5184.6  418.54  5205.7  417.15
  5257.2  419.95  5329.8  421.29  5387.3  423.79  5429.5  424.41  5501.1  423.36
#Mann=5,-1,0
  4690.4    0.05       0  4959.3    0.12       0  4971.2    0.07       0
  4975.2    0.12       0  5130.8    0.05       0
Bank Sta=4971.2,4975.2
Exp/Cntr=0.3,0.1

Type RM Length L Ch R = 1,2272,188,188,188
BEGIN DESCRIPTION:
Lacy 155 816
END DESCRIPTION:
XS GIS Cut Line= 3
      2729356.73      6844215.89      2728932.86      6844528.05
      2728682.13      6844809.97
#Sta/Elev= 30
  4478.6  429.45  4482.3  430.80  4504.3  431.64  4526.2  430.06  4547.0  426.09
  4561.7  425.46  4632.7  425.13  4712.1  421.49  4732.9  422.32  4747.6  420.81
  4850.2  418.29  4878.4  416.85  4933.5  415.28  4952.3  410.59  4952.6  410.09
  4956.3  410.59  4962.7  412.41  4969.0  416.02  4976.3  412.51  4983.6  415.15
  4989.8  412.71  5019.3  416.40  5061.9  414.54  5068.6  416.42  5100.8  417.93
  5117.9  419.34  5132.1  417.49  5238.3  421.17  5266.8  420.64  5382.3  422.99
#Mann=6,-1,0
  4478.6    0.05       0  4850.2    0.12       0  4878.4     0.1       0
  4952.3    0.07       0  4956.3     0.1       0  5100.8    0.05       0
Bank Sta=4952.3,4956.3
Exp/Cntr=0.3,0.1

Type RM Length L Ch R = 1,2084,257,257,257
BEGIN DESCRIPTION:
Lacy 155 818
END DESCRIPTION:
XS GIS Cut Line= 3
      2728882.94      6843887.93      2728766.29      6844468.70
      2728653.07      6844816.57
#Sta/Elev= 30
  4415.7  432.67  4429.8  430.01  4443.9  430.02  4475.6  426.67  4526.5  423.48
  4603.8  420.50  4730.1  415.21  4735.2  416.26  4816.6  414.66  4837.0  415.42
  4867.6  411.60  4882.8  408.33  4888.0  412.78  4918.6  415.90  4959.4  415.70
  4969.6  414.88  4982.5  408.15  4982.8  407.65  4986.5  408.15  5000.2  410.64
  5006.7  413.81  5031.5  413.41  5083.2  417.09  5115.6  416.81  5199.8  421.51
  5217.3  420.70  5249.2  422.25  5304.9  422.28  5318.3  423.49  5373.9  423.10
#Mann=6,-1,0
  4415.7    0.05       0  4443.9    0.12       0  4603.8     0.1       0
  4982.5    0.07       0  4986.5     0.1       0  5083.2    0.05       0
Bank Sta=4982.5,4986.5
Exp/Cntr=0.3,0.1

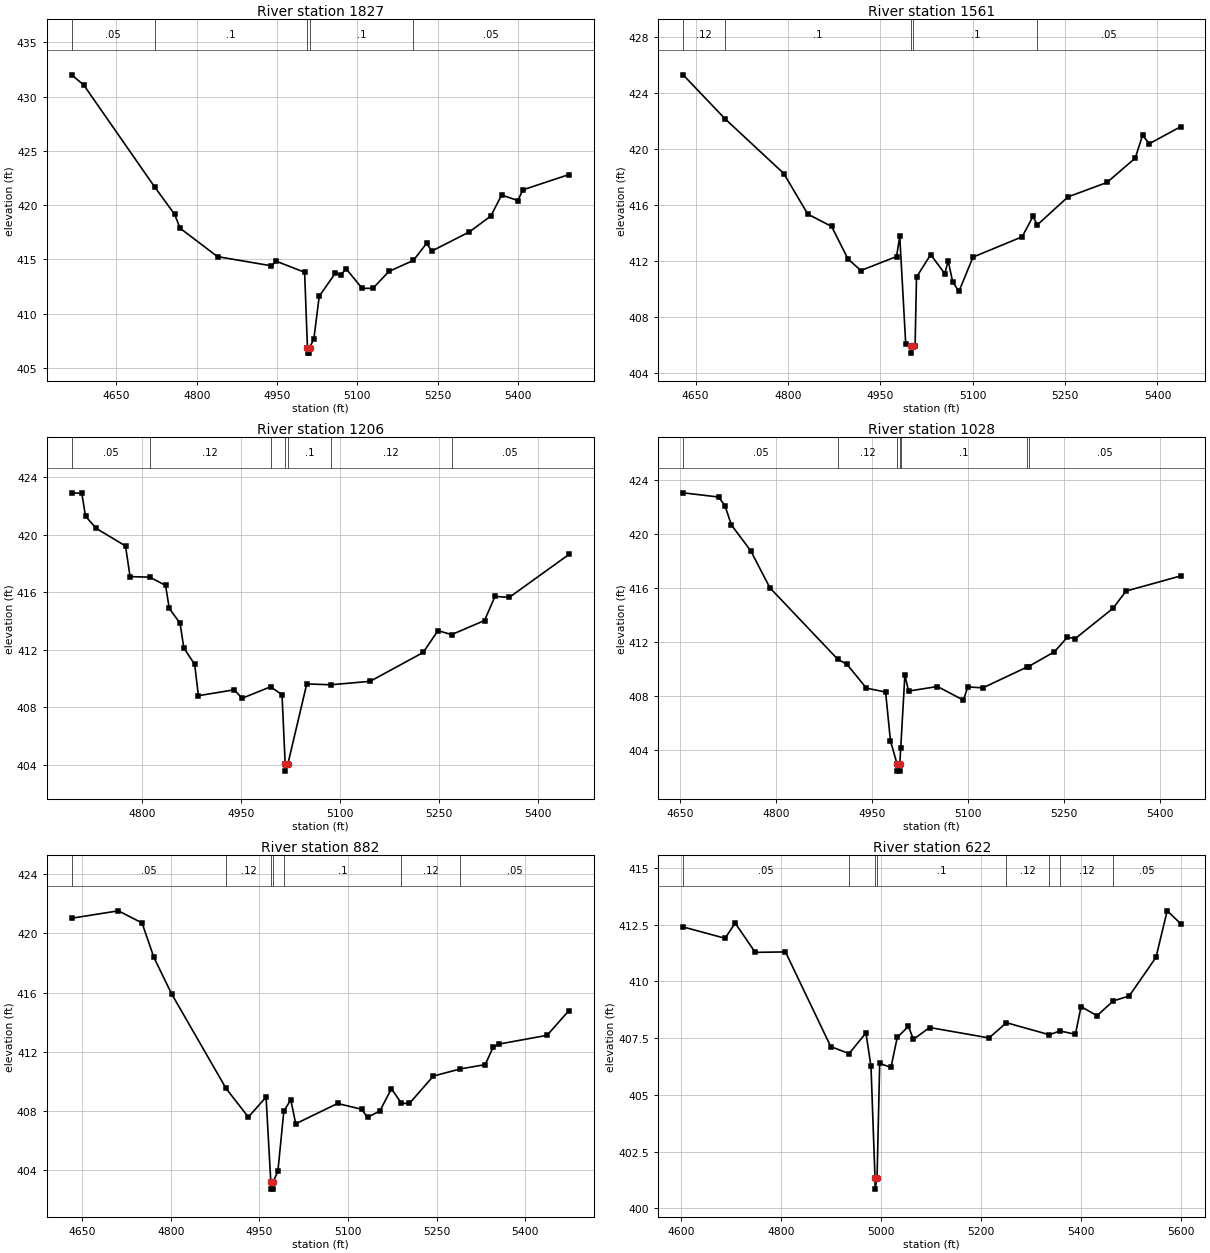
Type RM Length L Ch R = 1,1827,266,266,266
BEGIN DESCRIPTION:
Lacy 155 819
END DESCRIPTION:
XS GIS Cut Line= 3
      2728585.30      6843878.33      2728588.58      6844311.39
      2728556.84      6844806.50
#Sta/Elev= 30
  4566.2  432.00  4588.9  431.07  4721.3  421.68  4758.9  419.14  4768.9  417.87
  4838.9  415.25  4938.9  414.41  4948.9  414.82  5001.6  413.81  5006.9  406.86
  5007.2  406.36  5010.7  406.36  5010.9  406.86  5018.9  407.68  5028.9  411.60
  5059.0  413.73  5069.0  413.54  5079.0  414.14  5109.1  412.33  5129.2  412.33
  5159.2  413.89  5204.8  414.90  5229.4  416.47  5239.4  415.77  5309.5  417.53
  5349.6  419.00  5369.6  420.93  5399.7  420.42  5409.7  421.41  5495.4  422.81
#Mann=5,-1,0
  4566.2    0.05       0  4721.3     0.1       0  5006.9    0.07       0
  5010.9     0.1       0  5204.8    0.05       0
Bank Sta=5006.9,5010.9
Exp/Cntr=0.3,0.1

Type RM Length L Ch R = 1,1561,355,355,355
BEGIN DESCRIPTION:
Lacy 155 820
END DESCRIPTION:
XS GIS Cut Line= 3
      2728243.50      6844034.03      2728349.23      6844395.55
      2728529.95      6844786.99
#Sta/Elev= 30
  4629.7  425.31  4697.7  422.17  4793.2  418.26  4832.1  415.36  4870.8  414.48
  4897.4  412.16  4918.3  411.33  4976.3  412.33  4981.5  413.77  4991.2  406.08
  4999.3  405.93  4999.6  405.43  5003.4  405.93  5006.4  405.93  5008.7  410.86
  5031.7  412.47  5054.6  411.11  5060.1  412.02  5067.4  410.53  5077.6  409.84
  5100.5  412.29  5180.3  413.74  5197.8  415.19  5204.9  414.59  5254.7  416.59
  5318.0  417.62  5363.9  419.36  5375.8  420.99  5386.8  420.39  5437.5  421.60
#Mann=5,-1,0
  4629.7    0.12       0  4697.7     0.1       0  4999.3    0.07       0
  5003.4     0.1       0  5204.9    0.05       0
Bank Sta=4999.3,5003.4
Exp/Cntr=0.3,0.1

Type RM Length L Ch R = 1,1206,178,178,178
BEGIN DESCRIPTION:
Lacy 155 821
END DESCRIPTION:
XS GIS Cut Line= 3
      2727893.74      6844242.34      2728037.32      6844517.61
      2728256.72      6844902.96
#Sta/Elev= 30
  4693.3  422.91  4708.9  422.87  4714.5  421.28  4730.9  420.43  4775.1  419.21
  4782.0  417.08  4811.7  417.04  4835.8  416.47  4841.4  414.87  4857.8  413.83
  4863.5  412.11  4879.9  410.97  4885.6  408.79  4939.9  409.20  4951.8  408.61
  4994.9  409.41  5012.3  408.86  5017.1  404.04  5017.4  403.54  5021.2  404.04
  5049.8  409.61  5086.2  409.55  5145.8  409.79  5226.3  411.80  5248.7  413.32
  5269.3  413.04  5319.2  414.02  5335.1  415.70  5356.7  415.63  5447.2  418.62
#Mann=7,-1,0
  4693.3    0.05       0  4811.7    0.12       0  4994.9     0.1       0
  5017.1    0.07       0  5021.2     0.1       0  5086.2    0.12       0
  5269.3    0.05       0
Bank Sta=5017.1,5021.2
Exp/Cntr=0.3,0.1

Type RM Length L Ch R = 1,1028,146,146,146
BEGIN DESCRIPTION:
Lacy 155 813
END DESCRIPTION:
XS GIS Cut Line= 3
      2727867.86      6844265.89      2727903.69      6844617.40
      2727982.04      6845034.88
#Sta/Elev= 30
  4654.3  423.06  4709.7  422.75  4719.7  422.11  4729.8  420.68  4760.0  418.77
  4790.1  416.02  4896.1  410.73  4910.7  410.35  4940.9  408.59  4971.0  408.30
  4978.6  404.69  4989.1  402.94  4989.4  402.44  4992.9  402.44  4993.2  402.94
  4994.7  404.18  5001.2  409.57  5006.9  408.37  5052.2  408.71  5092.7  407.70
  5099.6  408.68  5123.2  408.61  5192.2  410.15  5194.6  410.19  5235.1  411.28
  5255.5  412.37  5267.4  412.25  5326.7  414.50  5347.1  415.78  5432.4  416.90
#Mann=7,-1,0
  4654.3    0.05       0  4896.1    0.12       0  4989.1    0.07       0
  4993.2    0.12       0  4994.7     0.1       0  5192.2    0.12       0
  5194.6    0.05       0
Bank Sta=4989.1,4993.2
Exp/Cntr=0.3,0.1

Type RM Length L Ch R = 1,882,260,260,260
BEGIN DESCRIPTION:
Lacy 155 828
END DESCRIPTION:
XS GIS Cut Line= 3
      2727754.59      6844241.59      2727756.61      6844609.79
      2727833.87      6845077.55
#Sta/Elev= 30
  4631.8  421.02  4711.2  421.52  4751.2  420.70  4771.2  418.38  4801.2  415.92
  4893.4  409.54  4931.2  407.60  4961.2  408.95  4969.2  403.24  4969.5  402.74
  4973.0  402.74  4973.3  403.24  4981.2  403.94  4991.3  408.00  5003.1  408.77
  5011.4  407.15  5082.3  408.52  5122.9  408.13  5133.0  407.58  5154.0  408.02
  5173.5  409.52  5190.4  408.53  5203.9  408.52  5244.5  410.37  5290.0  410.85
  5332.2  411.14  5345.8  412.32  5356.0  412.53  5437.1  413.12  5474.1  414.79
#Mann=7,-1,0
  4631.8    0.05       0  4893.4    0.12       0  4969.2    0.07       0
  4973.3    0.12       0  4991.3     0.1       0  5190.4    0.12       0
  5290.0    0.05       0
Bank Sta=4969.2,4973.3
Exp/Cntr=0.3,0.1

Type RM Length L Ch R = 1,622,219,219,219
BEGIN DESCRIPTION:
Lacy 155 827
END DESCRIPTION:
XS GIS Cut Line= 3
      2727554.35      6844167.60      2727512.09      6844560.73
      2727737.77      6845115.70
#Sta/Elev= 30
  4604.6  412.40  4688.5  411.90  4708.6  412.57  4748.8  411.28  4809.2  411.30
  4899.7  407.13  4936.4  406.82  4970.1  407.73  4980.2  406.26  4988.2  401.35
  4988.5  400.85  4992.3  401.35  4997.6  406.39  5020.1  406.21  5032.7  407.53
  5054.9  408.02  5065.1  407.45  5097.4  407.97  5216.2  407.51  5251.1  408.18
  5336.9  407.65  5357.8  407.82  5388.9  407.67  5400.2  408.89  5432.1  408.49
  5464.6  409.14  5496.5  409.36  5550.0  411.06  5572.4  413.11  5599.1  412.55
#Mann=8,-1,0
  4604.6    0.05       0  4936.4     0.1       0  4988.2    0.07       0
  4992.3     0.1       0  5251.1    0.12       0  5336.9     0.1       0
  5357.8    0.12       0  5464.6    0.05       0
Bank Sta=4988.2,4992.3
Exp/Cntr=0.3,0.1

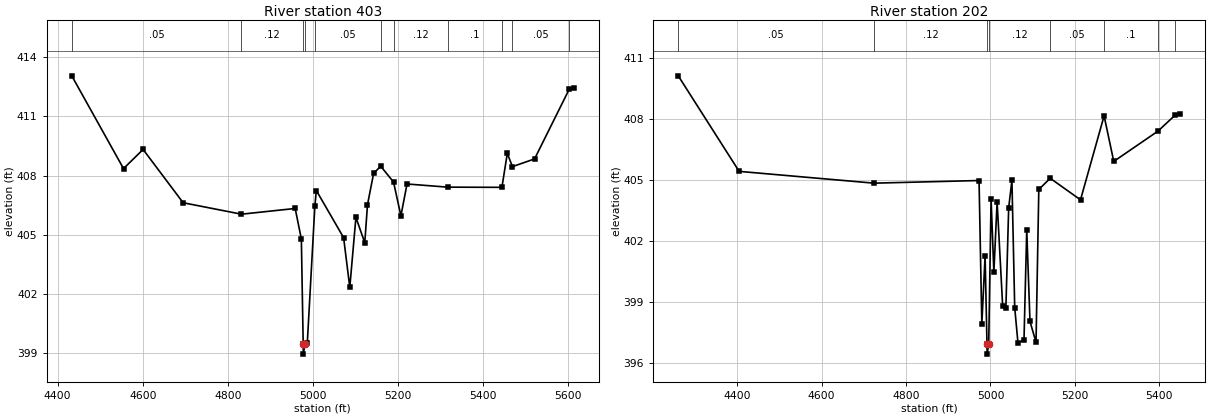
Type RM Length L Ch R = 1,403,201,201,201
BEGIN DESCRIPTION:
Lacy 155 3440
END DESCRIPTION:
XS GIS Cut Line= 3
      2727506.10      6844129.30      2727306.29      6844592.96
      2727725.37      6845122.00
#Sta/Elev= 30
  4433.1  413.06  4554.7  408.36  4600.7  409.33  4694.8  406.63  4831.9  406.05
  4958.1  406.34  4972.6  404.79  4976.9  399.46  4977.2  398.96  4981.0  399.46
  4986.5  399.50  5004.3  406.45  5007.8  407.25  5071.9  404.86  5086.4  402.34
  5100.8  405.89  5121.6  404.60  5128.0  406.53  5142.4  408.12  5159.1  408.48
  5189.2  407.68  5206.5  405.97  5220.9  407.58  5316.5  407.42  5443.9  407.41
  5456.5  409.13  5468.6  408.46  5520.6  408.85  5602.0  412.38  5612.9  412.43
#Mann=11,-1,0
  4433.1    0.05       0  4831.9    0.12       0  4976.9    0.07       0
  4981.0    0.12       0  5004.3    0.05       0  5159.1     0.1       0
  5189.2    0.12       0  5316.5     0.1       0  5443.9    0.12       0
  5468.6    0.05       0  5602.0    0.12       0
Bank Sta=4976.9,4981
Exp/Cntr=0.3,0.1

Type RM Length L Ch R = 1,202,0,0,0
BEGIN DESCRIPTION:
Lacy 155 3441
END DESCRIPTION:
XS GIS Cut Line= 3
      2727432.42      6844162.62      2727154.21      6844733.24
      2727575.80      6845093.99
#Sta/Elev= 30
  4260.2  410.14  4404.5  405.44  4724.1  404.86  4973.0  404.99  4979.6  397.92
  4987.3  401.29  4991.8  396.95  4992.1  396.45  4995.9  396.95  5001.5  404.09
  5008.1  400.47  5015.8  403.95  5029.0  398.80  5036.6  398.73  5043.2  403.65
  5050.9  405.00  5057.5  398.74  5065.2  397.00  5079.5  397.15  5086.0  402.55
  5093.7  398.06  5108.0  397.03  5114.6  404.55  5141.6  405.10  5213.4  404.04
  5269.3  408.17  5292.2  405.93  5397.0  407.42  5437.8  408.21  5449.9  408.27
#Mann=8,-1,0
  4260.2    0.05       0  4724.1    0.12       0  4991.8    0.07       0
  4995.9    0.12       0  5141.6    0.05       0  5269.3     0.1       0
  5397.0    0.12       0  5437.8    0.05       0
Bank Sta=4991.8,4995.9
Exp/Cntr=0.3,0.1

Chan Stop Cuts=-1