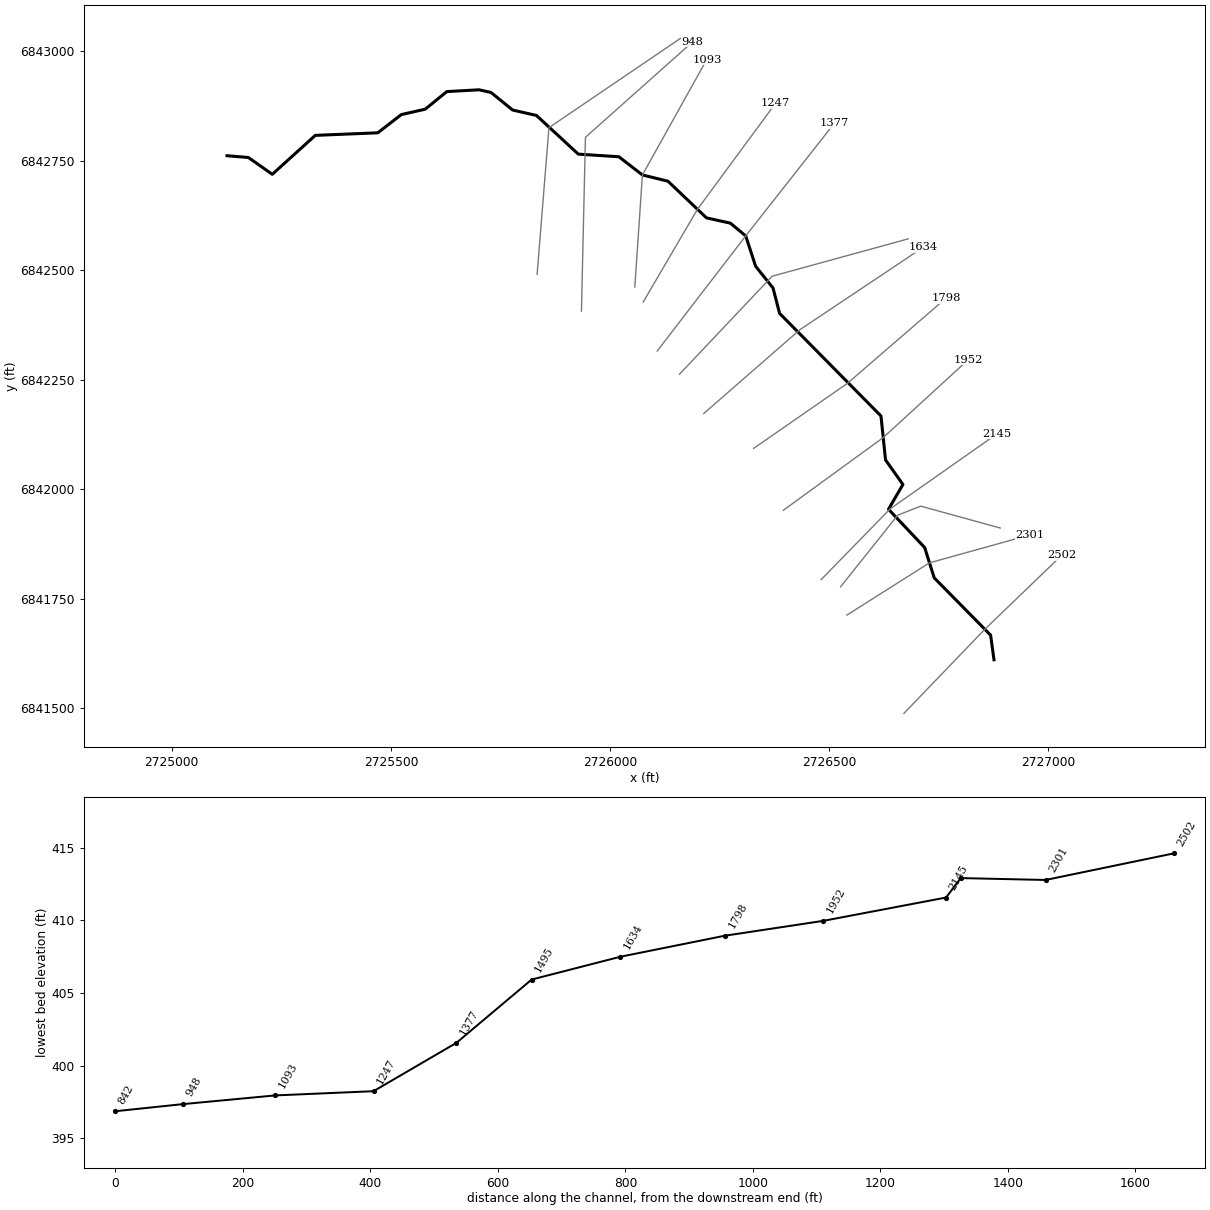
--- Lacy 156.prj (project) ---

Proj Title=Lacy 156 Base Level Engineering
Current Plan=p01
Default Exp/Contr=0.3,0.1
English Units
Geom File=g01
Flow File=f01
Plan File=p01
BEGIN DESCRIPTION:
Lacy 156
END DESCRIPTION:

--- Lacy 156.p01 (plan) ---

Plan Title=Multiple Run
Short Identifier=Multiple
Geom File=g01
Flow File=f01
Subcritical Flow
K Sum by GR= 0
Std Step Tol= 0.01
Critical Tol= 0.01
Num of Std Step Trials= 20
Max Error Tol= 0.3
Flow Tol Ratio= 0.001
Split Flow NTrial= 30
Split Flow Tol= 0.02
Split Flow Ratio= 0.02
Log Output Level= 0
Friction Slope Method= 1
Unsteady Friction Slope Method= 2
Unsteady Bridges Friction Slope Method= 1
Parabolic Critical Depth
Global Vel Dist=  1 , 1 , 1
Global Log Level= 0
CheckData=True
Encroach Param= -1, 0, 0, 0
BEGIN DESCRIPTION:
Multiple Run
END DESCRIPTION:

--- Lacy 156.f01 (steady flow) ---

Flow Title=Multiple
Number of Profiles=7
Profile Names=10-year,25-year,50-year,1pct_min,100-year,1pct_plu,500-year
River Rch & RM= Lacy 156,Reach-1,2502
     271     345     401     233     465     927     621
Boundary for River Rch & Prof#=Lacy 156,Reach-1,1
Up Type=0
Dn Type=3
Dn Slope=0.005
Boundary for River Rch & Prof#=Lacy 156,Reach-1,2
Up Type=0
Dn Type=3
Dn Slope=0.005
Boundary for River Rch & Prof#=Lacy 156,Reach-1,3
Up Type=0
Dn Type=3
Dn Slope=0.005
Boundary for River Rch & Prof#=Lacy 156,Reach-1,4
Up Type=0
Dn Type=3
Dn Slope=0.005
Boundary for River Rch & Prof#=Lacy 156,Reach-1,5
Up Type=0
Dn Type=3
Dn Slope=0.005
Boundary for River Rch & Prof#=Lacy 156,Reach-1,6
Up Type=0
Dn Type=3
Dn Slope=0.005
Boundary for River Rch & Prof#=Lacy 156,Reach-1,7
Up Type=0
Dn Type=3
Dn Slope=0.005

--- Lacy 156.g01 (geometry) ---

Geom Title=Existing Conditions

River Reach=Lacy 156,Reach-1
Reach XY= 30
      2726876.00      6841611.00      2726868.24      6841667.21
      2726739.63      6841797.79      2726717.80      6841867.05
      2726635.31      6841954.34      2726668.20      6842010.90
      2726628.55      6842066.89      2726618.14      6842167.17
      2726386.76      6842401.32      2726371.81      6842459.27
      2726332.11      6842508.84      2726309.51      6842578.05
      2726274.57      6842607.11      2726219.98      6842619.19
      2726132.05      6842702.84      2726073.83      6842717.14
      2726020.03      6842758.67      2725927.50      6842764.62
      2725832.05      6842852.84      2725777.75      6842865.22
      2725728.32      6842905.36      2725701.00      6842911.41
      2725627.58      6842907.33      2725578.18      6842867.12
      2725523.82      6842854.88      2725470.07      6842813.25
      2725327.47      6842807.43      2725229.38      6842718.60
      2725174.64      6842756.98      2725126.00      6842761.00

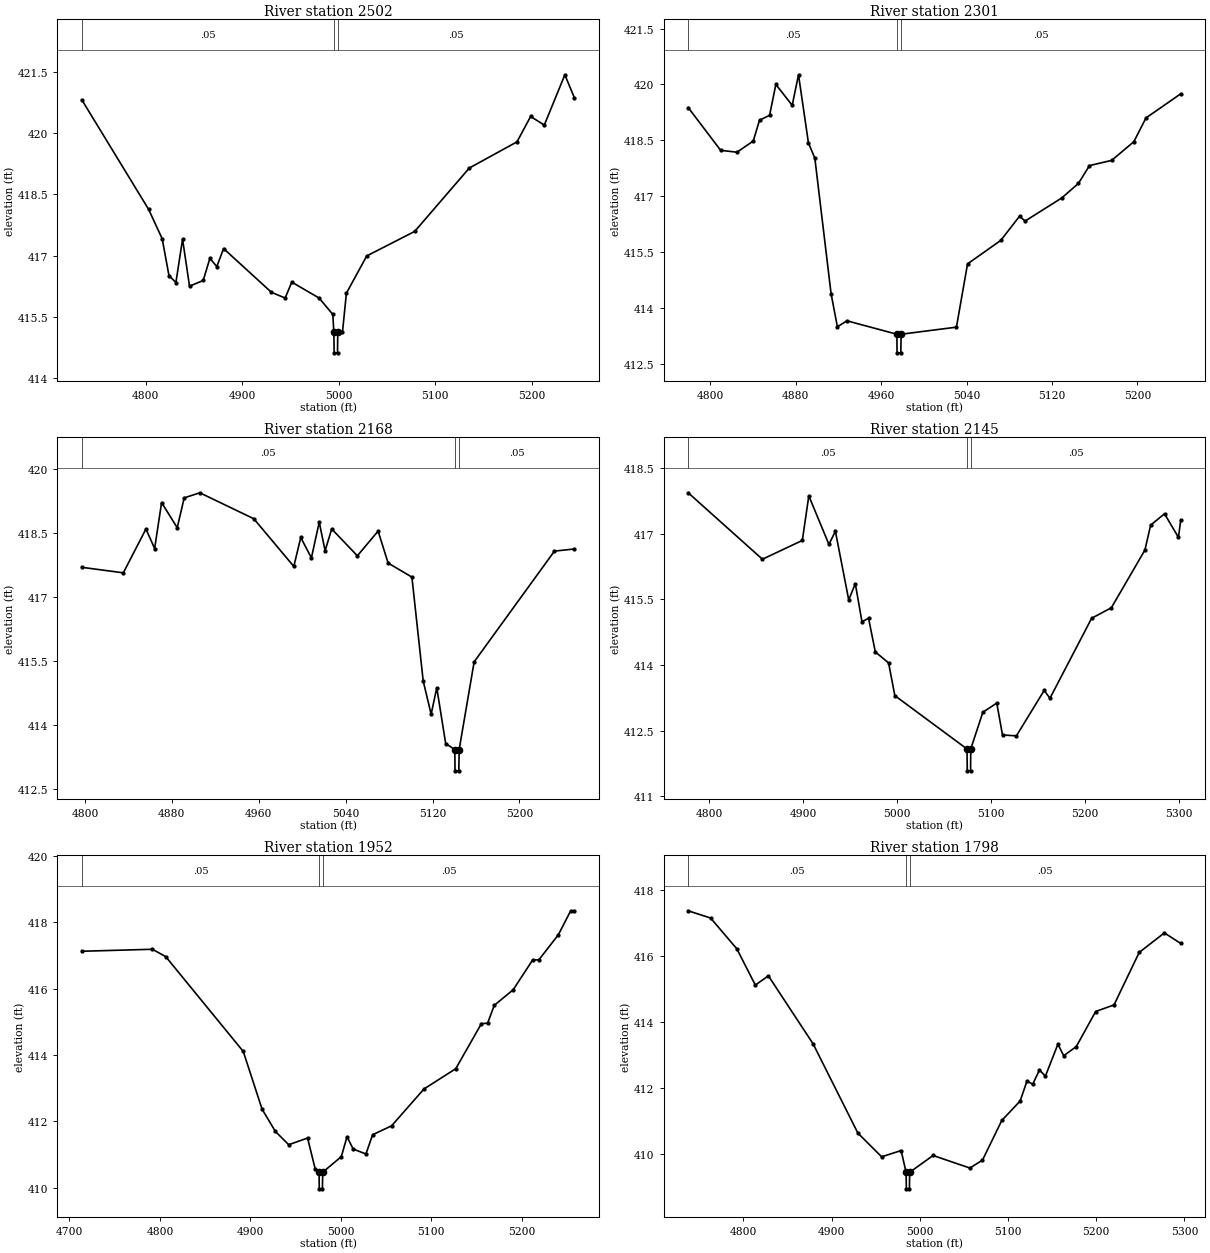
Type RM Length L Ch R = 1,2502,201,201,201
BEGIN DESCRIPTION:
Lacy 156 808
END DESCRIPTION:
XS GIS Cut Line= 3
      2726670.48      6841488.64      2726855.10      6841680.55
      2727031.06      6841849.88
#Sta/Elev= 30
  4733.7  420.81  4803.0  418.13  4817.1  417.41  4824.1  416.51  4831.3  416.34
  4838.2  417.40  4845.4  416.25  4859.6  416.39  4866.5  416.93  4873.7  416.73
  4880.7  417.17  4930.3  416.10  4944.5  415.96  4951.4  416.35  4979.7  415.96
  4993.9  415.56  4995.0  415.12  4995.3  414.62  4998.8  414.62  4999.0  415.12
  5003.9  415.12  5008.0  416.08  5029.1  416.99  5078.8  417.59  5135.4  419.14
  5184.8  419.78  5198.9  420.40  5213.1  420.19  5234.4  421.42  5244.2  420.86
#Mann=3,-1,0
  4733.7    0.05       0  4995.0    0.04       0  4999.0    0.05       0
Bank Sta=4995,4999
Exp/Cntr=0.3,0.1

Type RM Length L Ch R = 1,2301,133,133,133
BEGIN DESCRIPTION:
Lacy 156 802
END DESCRIPTION:
XS GIS Cut Line= 3
      2726540.35      6841712.89      2726728.56      6841832.04
      2726958.41      6841895.86
#Sta/Elev= 30
  4779.3  419.38  4809.7  418.23  4825.0  418.18  4840.2  418.48  4846.1  419.04
  4855.5  419.17  4861.4  420.00  4876.7  419.44  4882.6  420.26  4891.9  418.43
  4897.9  418.02  4913.1  414.38  4919.0  413.49  4928.0  413.65  4974.7  413.29
  4974.9  412.79  4978.4  412.79  4978.7  413.29  5030.5  413.48  5040.9  415.18
  5072.0  415.81  5089.6  416.46  5094.8  416.33  5129.1  416.95  5144.7  417.34
  5155.1  417.82  5175.8  417.96  5196.6  418.46  5208.0  419.10  5240.6  419.75
#Mann=3,-1,0
  4779.3    0.05       0  4974.7    0.05       0  4978.7    0.05       0
Bank Sta=4974.7,4978.7
Exp/Cntr=0.3,0.1

Type RM Length L Ch R = 1,2168,23,23,23
BEGIN DESCRIPTION:
Lacy 156 801
END DESCRIPTION:
XS GIS Cut Line= 4
      2726526.00      6841777.50      2726656.24      6841940.74
      2726709.01      6841961.46      2726890.14      6841911.58
#Sta/Elev= 30
  4797.1  417.70  4835.4  417.57  4856.2  418.60  4864.2  418.14  4870.6  419.22
  4885.0  418.63  4891.4  419.33  4905.8  419.45  4955.5  418.84  4992.3  417.72
  4998.7  418.40  5008.5  417.92  5015.7  418.76  5021.1  418.09  5027.2  418.60
  5050.8  417.97  5069.9  418.55  5079.1  417.80  5101.0  417.47  5111.4  415.03
  5118.7  414.25  5123.9  414.87  5132.1  413.56  5140.5  413.42  5140.7  412.92
  5144.2  412.92  5144.5  413.42  5158.3  415.48  5232.2  418.08  5250.5  418.13
#Mann=3,-1,0
  4797.1    0.05       0  5140.5    0.05       0  5144.5    0.05       0
Bank Sta=5140.5,5144.5
Exp/Cntr=0.3,0.1

Type RM Length L Ch R = 1,2145,193,193,193
BEGIN DESCRIPTION:
Lacy 156 800
END DESCRIPTION:
XS GIS Cut Line= 3
      2726481.56      6841793.79      2726639.37      6841955.50
      2726883.66      6842126.95
#Sta/Elev= 30
  4777.8  417.94  4856.8  416.42  4899.3  416.85  4906.2  417.87  4927.6  416.76
  4934.5  417.06  4948.7  415.49  4955.7  415.86  4962.8  414.99  4969.8  415.07
  4977.0  414.30  4991.1  414.05  4997.8  413.30  5074.6  412.08  5074.9  411.58
  5078.4  411.58  5078.6  412.08  5091.5  412.92  5106.3  413.13  5112.4  412.40
  5127.2  412.38  5156.8  413.42  5162.9  413.24  5207.3  415.07  5228.3  415.31
  5264.0  416.63  5270.1  417.20  5284.9  417.46  5299.7  416.92  5302.2  417.32
#Mann=3,-1,0
  4777.8    0.05       0  5074.6    0.05       0  5078.6    0.05       0
Bank Sta=5074.6,5078.6
Exp/Cntr=0.3,0.1

Type RM Length L Ch R = 1,1952,154,154,154
BEGIN DESCRIPTION:
Lacy 156 798
END DESCRIPTION:
XS GIS Cut Line= 3
      2726395.22      6841951.95      2726622.72      6842117.47
      2726816.91      6842295.21
#Sta/Elev= 30
  4713.6  417.13  4791.7  417.19  4806.4  416.97  4892.2  414.11  4913.0  412.37
  4927.7  411.70  4942.4  411.30  4963.3  411.50  4971.8  410.56  4976.0  410.47
  4976.2  409.97  4979.7  409.97  4980.0  410.47  5000.6  410.94  5006.9  411.54
  5013.7  411.17  5027.8  411.02  5035.2  411.60  5056.2  411.87  5092.0  412.98
  5127.1  413.59  5155.5  414.95  5162.3  414.96  5169.7  415.50  5190.6  415.97
  5212.2  416.87  5219.0  416.87  5240.6  417.63  5254.2  418.35  5258.2  418.35
#Mann=3,-1,0
  4713.6    0.05       0  4976.0    0.03       0  4980.0    0.05       0
Bank Sta=4976,4980
Exp/Cntr=0.3,0.1

Type RM Length L Ch R = 1,1798,164,164,164
BEGIN DESCRIPTION:
Lacy 156 799
END DESCRIPTION:
XS GIS Cut Line= 3
      2726327.63      6842093.23      2726540.87      6842241.11
      2726767.12      6842436.44
#Sta/Elev= 30
  4737.5  417.37  4762.9  417.15  4792.6  416.22  4813.6  415.12  4828.4  415.40
  4879.1  413.34  4929.8  410.64  4956.8  409.92  4978.9  410.11  4984.5  409.45
  4984.8  408.95  4988.3  408.95  4988.5  409.45  5015.1  409.96  5056.8  409.58
  5071.1  409.82  5093.0  411.02  5113.8  411.61  5121.5  412.21  5128.1  412.12
  5135.7  412.55  5142.4  412.36  5156.6  413.33  5163.2  412.98  5177.5  413.26
  5199.4  414.32  5220.2  414.52  5248.8  416.11  5277.3  416.70  5295.9  416.38
#Mann=3,-1,0
  4737.5    0.05       0  4984.5    0.04       0  4988.5    0.05       0
Bank Sta=4984.5,4988.5
Exp/Cntr=0.3,0.1

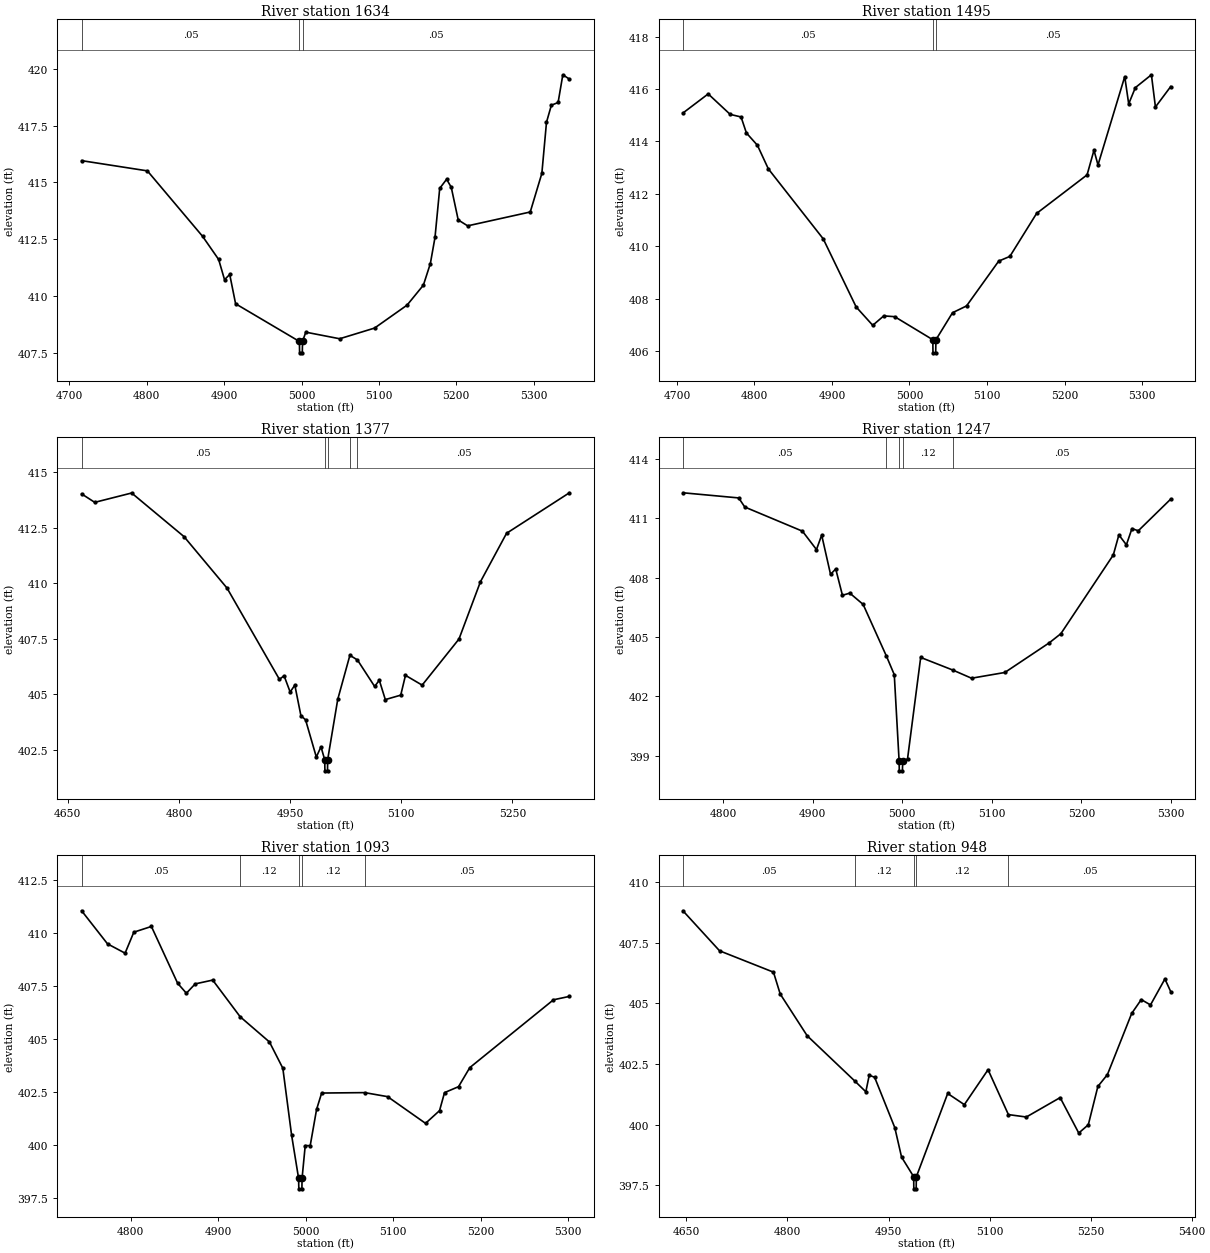
Type RM Length L Ch R = 1,1634,139,139,139
BEGIN DESCRIPTION:
Lacy 156 797
END DESCRIPTION:
XS GIS Cut Line= 3
      2726213.78      6842172.84      2726433.33      6842364.15
      2726715.37      6842552.57
#Sta/Elev= 30
  4715.8  415.96  4800.8  415.51  4872.1  412.63  4892.9  411.61  4900.5  410.72
  4907.2  410.95  4914.8  409.66  4997.3  408.00  4997.5  407.50  5001.0  407.50
  5001.3  408.00  5005.5  408.41  5049.3  408.12  5094.4  408.59  5136.4  409.60
  5157.5  410.48  5166.5  411.43  5172.5  412.58  5178.6  414.74  5187.5  415.14
  5193.5  414.79  5202.5  413.35  5214.7  413.09  5295.6  413.70  5310.6  415.40
  5316.6  417.65  5322.9  418.40  5331.6  418.52  5337.7  419.74  5346.2  419.55
#Mann=3,-1,0
  4715.8    0.05       0  4997.3    0.04       0  5001.3    0.05       0
Bank Sta=4997.3,5001.3
Exp/Cntr=0.3,0.1

Type RM Length L Ch R = 1,1495,118,118,118
BEGIN DESCRIPTION:
Lacy 156 796
END DESCRIPTION:
XS GIS Cut Line= 3
      2726158.47      6842262.50      2726369.89      6842486.05
      2726680.02      6842571.23
#Sta/Elev= 30
  4707.7  415.08  4740.3  415.81  4768.6  415.03  4782.7  414.93  4789.6  414.32
  4803.8  413.85  4817.9  412.95  4888.7  410.28  4931.2  407.68  4952.6  406.98
  4966.8  407.34  4980.9  407.31  5030.1  406.43  5030.3  405.93  5033.8  405.93
  5034.1  406.43  5055.5  407.46  5073.6  407.72  5115.1  409.43  5129.5  409.61
  5164.0  411.25  5229.1  412.72  5238.0  413.66  5243.2  413.10  5277.7  416.47
  5282.8  415.43  5291.4  416.05  5312.1  416.54  5317.3  415.31  5337.0  416.09
#Mann=3,-1,0
  4707.7    0.05       0  5030.1    0.04       0  5034.1    0.05       0
Bank Sta=5030.1,5034.1
Exp/Cntr=0.3,0.1

Type RM Length L Ch R = 1,1377,130,130,130
BEGIN DESCRIPTION:
Lacy 156 807
END DESCRIPTION:
XS GIS Cut Line= 3
      2726107.61      6842315.38      2726309.51      6842578.05
      2726511.66      6842834.95
#Sta/Elev= 30
  4668.7  414.01  4686.4  413.63  4736.2  414.05  4806.9  412.09  4864.9  409.78
  4935.6  405.68  4941.9  405.84  4950.1  405.11  4956.4  405.42  4964.6  404.05
  4970.9  403.86  4985.4  402.19  4991.7  402.65  4996.7  402.07  4997.0  401.57
  5000.5  401.57  5000.7  402.07  5014.3  404.78  5030.7  406.76  5040.9  406.55
  5064.1  405.36  5070.4  405.64  5078.5  404.77  5099.3  404.97  5105.7  405.86
  5128.2  405.42  5177.9  407.49  5206.8  410.06  5242.1  412.24  5326.9  414.06
#Mann=5,-1,0
  4668.7    0.05       0  4996.7    0.04       0  5000.7    0.05       0
  5030.7    0.12       0  5040.9    0.05       0
Bank Sta=4996.7,5000.7
Exp/Cntr=0.3,0.1

Type RM Length L Ch R = 1,1247,154,154,154
BEGIN DESCRIPTION:
Lacy 156 806
END DESCRIPTION:
XS GIS Cut Line= 3
      2726075.63      6842427.21      2726199.40      6842638.76
      2726377.17      6842880.17
#Sta/Elev= 30
  4754.9  412.29  4817.2  412.03  4824.0  411.57  4888.4  410.35  4904.1  409.42
  4909.9  410.15  4919.8  408.17  4925.6  408.44  4933.1  407.11  4941.3  407.22
  4956.2  406.65  4982.3  404.03  4991.0  403.10  4996.4  398.74  4996.6  398.24
  5000.1  398.24  5000.4  398.74  5005.8  398.84  5020.5  403.97  5056.5  403.33
  5077.3  402.92  5114.5  403.21  5164.2  404.71  5177.1  405.17  5235.7  409.15
  5241.9  410.16  5250.3  409.66  5256.5  410.48  5263.6  410.37  5299.8  411.97
#Mann=5,-1,0
  4754.9    0.05       0  4982.3    0.12       0  4996.4    0.07       0
  5000.4    0.12       0  5056.5    0.05       0
Bank Sta=4996.4,5000.4
Exp/Cntr=0.3,0.1

Type RM Length L Ch R = 1,1093,145,145,145
BEGIN DESCRIPTION:
Lacy 156 805
END DESCRIPTION:
XS GIS Cut Line= 3
      2726056.47      6842461.43      2726073.83      6842717.14
      2726220.63      6842980.48
#Sta/Elev= 30
  4743.7  411.07  4773.3  409.51  4793.4  409.07  4803.4  410.06  4823.5  410.33
  4853.5  407.65  4863.5  407.18  4873.6  407.62  4893.6  407.80  4925.0  406.07
  4958.5  404.88  4973.8  403.64  4983.8  400.49  4991.8  398.45  4992.1  397.95
  4995.6  397.95  4995.8  398.45  4999.4  399.99  5005.1  399.99  5012.4  401.70
  5018.2  402.47  5067.4  402.49  5093.6  402.30  5137.0  401.04  5153.0  401.64
  5158.7  402.49  5174.7  402.77  5187.6  403.67  5283.3  406.87  5301.5  407.03
#Mann=5,-1,0
  4743.7    0.05       0  4925.0    0.12       0  4991.8    0.07       0
  4995.8    0.12       0  5067.4    0.05       0
Bank Sta=4991.8,4995.8
Exp/Cntr=0.3,0.1

Type RM Length L Ch R = 1,948,106,106,106
BEGIN DESCRIPTION:
Lacy 156 804
END DESCRIPTION:
XS GIS Cut Line= 3
      2725934.72      6842406.62      2725943.82      6842802.96
      2726188.43      6843020.81
#Sta/Elev= 30
  4644.8  408.81  4699.2  407.16  4779.2  406.28  4789.2  405.38  4829.2  403.66
  4900.4  401.78  4916.3  401.35  4921.3  402.03  4929.3  401.95  4959.3  399.87
  4969.3  398.66  4987.3  397.85  4987.5  397.35  4991.0  397.35  4991.3  397.85
  5037.8  401.28  5062.5  400.82  5097.7  402.26  5127.9  400.41  5154.5  400.31
  5204.7  401.11  5232.3  399.65  5246.5  399.99  5260.7  401.57  5274.9  402.06
  5310.9  404.58  5325.1  405.15  5338.8  404.93  5360.2  406.00  5368.8  405.48
#Mann=5,-1,0
  4644.8    0.05       0  4900.4    0.12       0  4987.3    0.07       0
  4991.3    0.12       0  5127.9    0.05       0
Bank Sta=4987.3,4991.3
Exp/Cntr=0.3,0.1

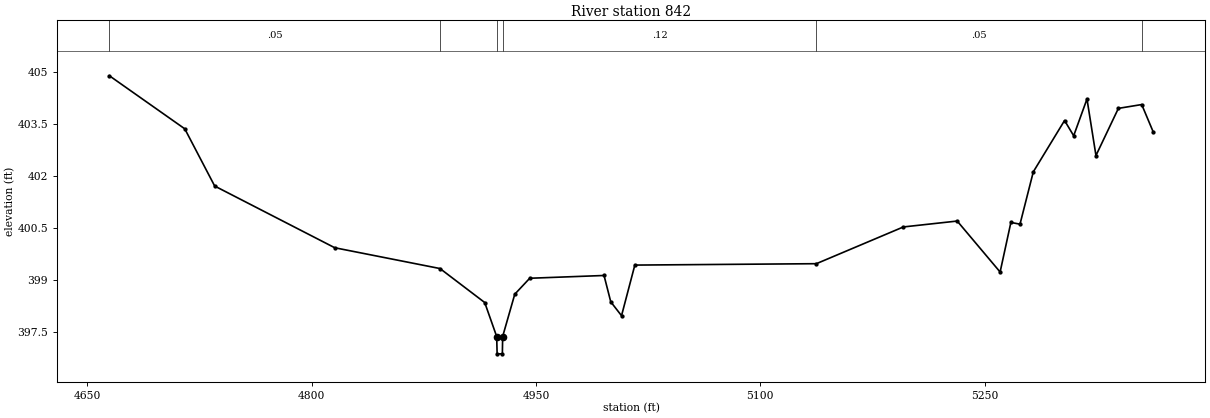
Type RM Length L Ch R = 1,842,0,0,0
BEGIN DESCRIPTION:
Lacy 156 803
END DESCRIPTION:
XS GIS Cut Line= 3
      2725833.59      6842490.80      2725860.57      6842825.01
      2726160.71      6843028.82
#Sta/Elev= 30
  4664.7  404.88  4715.1  403.35  4735.1  401.70  4815.4  399.92  4885.8  399.32
  4915.7  398.34  4923.7  397.36  4924.0  396.86  4927.5  396.86  4927.7  397.36
  4935.8  398.58  4945.8  399.04  4995.5  399.12  5000.0  398.36  5007.2  397.96
  5016.1  399.42  5137.5  399.46  5195.7  400.52  5231.7  400.69  5260.4  399.22
  5267.6  400.65  5273.7  400.60  5282.6  402.11  5303.5  403.59  5309.6  403.15
  5318.5  404.21  5324.5  402.58  5339.5  403.94  5355.1  404.05  5362.8  403.26
#Mann=6,-1,0
  4664.7    0.05       0  4885.8    0.12       0  4923.7    0.07       0
  4927.7    0.12       0  5137.5    0.05       0  5355.1     0.1       0
Bank Sta=4923.7,4927.7
Exp/Cntr=0.3,0.1

Chan Stop Cuts=-1