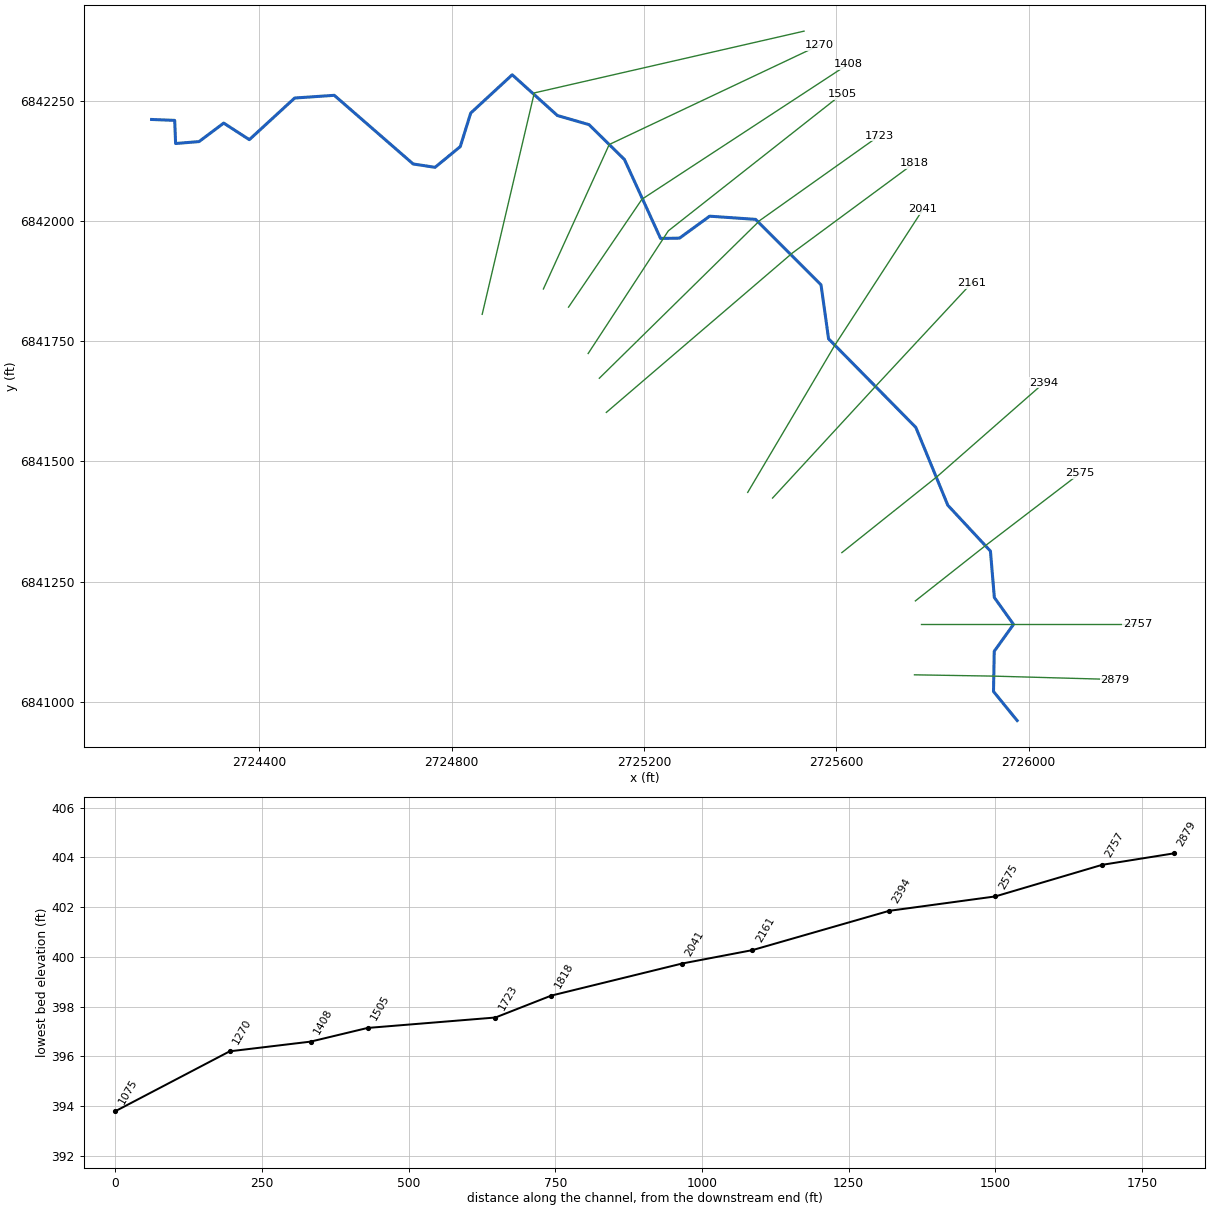
--- Lacy 157.prj (project) ---

Proj Title=Lacy 157 Base Level Engineering
Current Plan=p01
Default Exp/Contr=0.3,0.1
English Units
Geom File=g01
Flow File=f01
Plan File=p01
BEGIN DESCRIPTION:
Lacy 157
END DESCRIPTION:

--- Lacy 157.p01 (plan) ---

Plan Title=Multiple Run
Short Identifier=Multiple
Geom File=g01
Flow File=f01
Subcritical Flow
K Sum by GR= 0
Std Step Tol= 0.01
Critical Tol= 0.01
Num of Std Step Trials= 20
Max Error Tol= 0.3
Flow Tol Ratio= 0.001
Split Flow NTrial= 30
Split Flow Tol= 0.02
Split Flow Ratio= 0.02
Log Output Level= 0
Friction Slope Method= 1
Unsteady Friction Slope Method= 2
Unsteady Bridges Friction Slope Method= 1
Parabolic Critical Depth
Global Vel Dist=  1 , 1 , 1
Global Log Level= 0
CheckData=True
Encroach Param= -1, 0, 0, 0
BEGIN DESCRIPTION:
Multiple Run
END DESCRIPTION:

--- Lacy 157.f01 (steady flow) ---

Flow Title=Multiple
Number of Profiles=7
Profile Names=10-year,25-year,50-year,1pct_min,100-year,1pct_plu,500-year
River Rch & RM= Lacy 157,Reach-1,2879
     333     428     503     293     585    1167     791
Boundary for River Rch & Prof#=Lacy 157,Reach-1,1
Up Type=0
Dn Type=3
Dn Slope=0.005
Boundary for River Rch & Prof#=Lacy 157,Reach-1,2
Up Type=0
Dn Type=3
Dn Slope=0.005
Boundary for River Rch & Prof#=Lacy 157,Reach-1,3
Up Type=0
Dn Type=3
Dn Slope=0.005
Boundary for River Rch & Prof#=Lacy 157,Reach-1,4
Up Type=0
Dn Type=3
Dn Slope=0.005
Boundary for River Rch & Prof#=Lacy 157,Reach-1,5
Up Type=0
Dn Type=3
Dn Slope=0.005
Boundary for River Rch & Prof#=Lacy 157,Reach-1,6
Up Type=0
Dn Type=3
Dn Slope=0.005
Boundary for River Rch & Prof#=Lacy 157,Reach-1,7
Up Type=0
Dn Type=3
Dn Slope=0.005

--- Lacy 157.g01 (geometry) ---

Geom Title=Existing Conditions

River Reach=Lacy 157,Reach-1
Reach XY= 30
      2725976.00      6840961.00      2725926.82      6841021.46
      2725928.36      6841105.12      2725968.44      6841161.00
      2725928.56      6841216.90      2725920.47      6841313.42
      2725831.85      6841408.71      2725765.24      6841570.68
      2725583.86      6841754.83      2725568.14      6841867.17
      2725432.17      6842003.24      2725336.53      6842009.87
      2725273.89      6841964.19      2725234.46      6841963.62
      2725159.37      6842127.71      2725085.70      6842200.23
      2725019.95      6842219.20      2724925.98      6842303.92
      2724839.64      6842224.25      2724817.96      6842154.57
      2724765.51      6842111.48      2724719.97      6842118.45
      2724555.94      6842261.22      2724473.57      6842255.58
      2724379.33      6842168.99      2724326.07      6842203.42
      2724274.64      6842164.98      2724226.00      6842161.00
      2724224.10      6842209.10      2724176.00      6842211.00

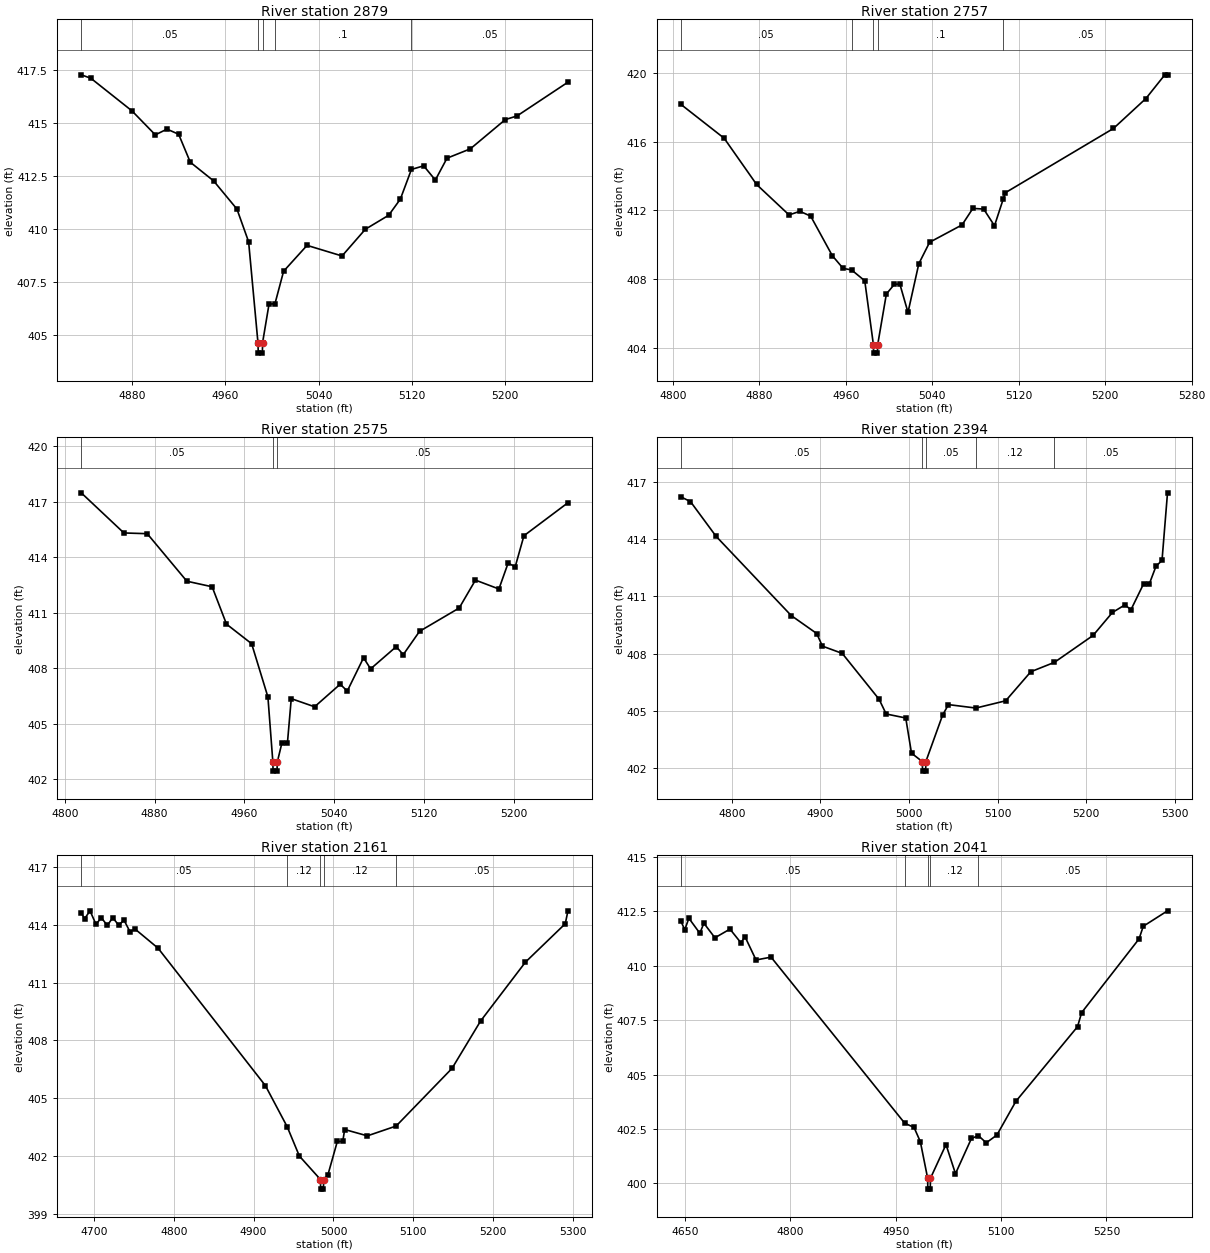
Type RM Length L Ch R = 1,2879,122,122,122
BEGIN DESCRIPTION:
Lacy 157 795
END DESCRIPTION:
XS GIS Cut Line= 3
      2725762.48      6841056.13      2725925.96      6841053.47
      2726179.56      6841046.39
#Sta/Elev= 30
  4836.5  417.28  4844.7  417.12  4880.0  415.58  4900.0  414.45  4910.0  414.72
  4920.0  414.48  4930.0  413.16  4950.0  412.28  4970.0  410.95  4980.0  409.41
  4988.0  404.66  4988.3  404.16  4991.8  404.16  4992.0  404.66  4997.5  406.47
  5002.6  406.49  5010.0  408.02  5030.1  409.24  5060.1  408.74  5080.1  410.00
  5100.1  410.66  5110.1  411.42  5119.6  412.82  5130.1  412.99  5140.1  412.32
  5150.1  413.35  5170.1  413.79  5200.1  415.17  5210.1  415.34  5253.7  416.93
#Mann=5,-1,0
  4836.5    0.05       0  4988.0    0.05       0  4992.0    0.05       0
  5002.6     0.1       0  5119.6    0.05       0
Bank Sta=4988,4992
Exp/Cntr=0.3,0.1

Type RM Length L Ch R = 1,2757,182,182,182
BEGIN DESCRIPTION:
Lacy 157 59
END DESCRIPTION:
XS GIS Cut Line= 3
      2725776.04      6841161.00      2725976.00      6841161.00
      2726226.04      6841161.00
#Sta/Elev= 30
  4807.6  418.17  4847.6  416.20  4877.6  413.51  4907.6  411.74  4917.6  411.95
  4927.6  411.67  4947.6  409.37  4957.6  408.63  4965.4  408.54  4977.6  407.91
  4985.6  404.20  4985.8  403.70  4989.3  403.70  4989.6  404.20  4997.6  407.14
  5005.1  407.71  5010.1  407.71  5017.6  406.07  5027.6  408.90  5037.6  410.15
  5067.6  411.16  5077.6  412.12  5087.6  412.08  5097.6  411.11  5105.7  412.67
  5107.6  413.03  5207.6  416.77  5237.6  418.51  5255.1  419.89  5257.6  419.89
#Mann=5,-1,0
  4807.6    0.05       0  4965.4     0.1       0  4985.6    0.07       0
  4989.6     0.1       0  5105.7    0.05       0
Bank Sta=4985.6,4989.6
Exp/Cntr=0.3,0.1

Type RM Length L Ch R = 1,2575,181,181,181
BEGIN DESCRIPTION:
Lacy 157 792
END DESCRIPTION:
XS GIS Cut Line= 3
      2725764.40      6841209.89      2725908.61      6841323.64
      2726107.02      6841475.45
#Sta/Elev= 30
  4814.6  417.48  4852.6  415.31  4873.4  415.27  4908.7  412.70  4931.2  412.40
  4944.0  410.38  4966.4  409.32  4980.9  406.44  4985.3  402.93  4985.5  402.43
  4989.0  402.43  4989.3  402.93  4993.4  403.96  4998.3  403.96  5001.7  406.35
  5022.5  405.91  5045.3  407.13  5051.6  406.76  5066.1  408.56  5072.4  407.96
  5095.2  409.16  5101.5  408.73  5116.0  409.99  5151.3  411.25  5165.8  412.76
  5186.7  412.28  5194.9  413.68  5201.2  413.48  5209.0  415.16  5248.1  416.94
#Mann=3,-1,0
  4814.6    0.05       0  4985.3    0.05       0  4989.3    0.05       0
Bank Sta=4985.3,4989.3
Exp/Cntr=0.3,0.1

Type RM Length L Ch R = 1,2394,233,233,233
BEGIN DESCRIPTION:
Lacy 157 790
END DESCRIPTION:
XS GIS Cut Line= 3
      2725611.43      6841310.19      2725809.74      6841468.53
      2726031.92      6841663.40
#Sta/Elev= 30
  4742.6  416.20  4753.4  415.95  4782.2  414.14  4867.1  409.99  4895.9  409.05
  4902.3  408.39  4924.7  408.01  4966.3  405.61  4974.3  404.84  4996.4  404.63
  5002.9  402.79  5015.1  402.35  5015.4  401.85  5018.9  401.85  5019.1  402.35
  5038.0  404.78  5044.6  405.33  5075.6  405.15  5109.2  405.53  5137.6  407.05
  5164.2  407.54  5207.9  408.95  5229.7  410.15  5243.9  410.55  5250.6  410.29
  5264.8  411.64  5271.4  411.65  5279.0  412.58  5285.7  412.87  5291.9  416.41
#Mann=5,-1,0
  4742.6    0.05       0  5015.1    0.05       0  5019.1    0.05       0
  5075.6    0.12       0  5164.2    0.05       0
Bank Sta=5015.1,5019.1
Exp/Cntr=0.3,0.1

Type RM Length L Ch R = 1,2161,120,120,120
BEGIN DESCRIPTION:
Lacy 157 791
END DESCRIPTION:
XS GIS Cut Line= 3
      2725467.39      6841423.71      2725687.69      6841662.67
      2725881.10      6841870.62
#Sta/Elev= 30
  4684.3  414.63  4688.5  414.33  4695.3  414.74  4702.7  414.04  4709.5  414.38
  4716.9  413.98  4723.7  414.38  4731.1  414.00  4737.9  414.25  4745.2  413.66
  4752.0  413.78  4780.4  412.80  4914.8  405.65  4942.1  403.51  4957.3  401.99
  4983.7  400.77  4983.9  400.27  4987.4  400.27  4987.7  400.77  4993.0  401.01
  5004.8  402.75  5011.6  402.75  5014.0  403.37  5042.4  403.04  5078.4  403.55
  5148.4  406.55  5184.1  409.01  5240.2  412.07  5290.1  414.07  5293.3  414.71
#Mann=5,-1,0
  4684.3    0.05       0  4942.1    0.12       0  4983.7    0.07       0
  4987.7    0.12       0  5078.4    0.05       0
Bank Sta=4983.7,4987.7
Exp/Cntr=0.3,0.1

Type RM Length L Ch R = 1,2041,223,223,223
BEGIN DESCRIPTION:
Lacy 157 789
END DESCRIPTION:
XS GIS Cut Line= 3
      2725415.70      6841435.49      2725597.67      6841742.82
      2725780.26      6842024.21
#Sta/Elev= 30
  4644.3  412.05  4649.8  411.66  4655.6  412.19  4671.2  411.50  4677.0  411.96
  4692.7  411.29  4714.1  411.69  4729.7  411.06  4735.5  411.34  4751.2  410.27
  4772.6  410.40  4962.9  402.76  4976.1  402.57  4985.1  401.91  4995.5  400.23
  4995.7  399.73  4999.2  399.73  4999.5  400.23  5021.6  401.78  5035.1  400.44
  5057.8  402.06  5067.7  402.19  5078.9  401.86  5094.1  402.22  5121.1  403.77
  5208.8  407.20  5214.7  407.85  5296.4  411.24  5302.4  411.82  5336.9  412.53
#Mann=5,-1,0
  4644.3    0.05       0  4962.9    0.12       0  4995.5    0.07       0
  4999.5    0.12       0  5067.7    0.05       0
Bank Sta=4995.5,4999.5
Exp/Cntr=0.3,0.1

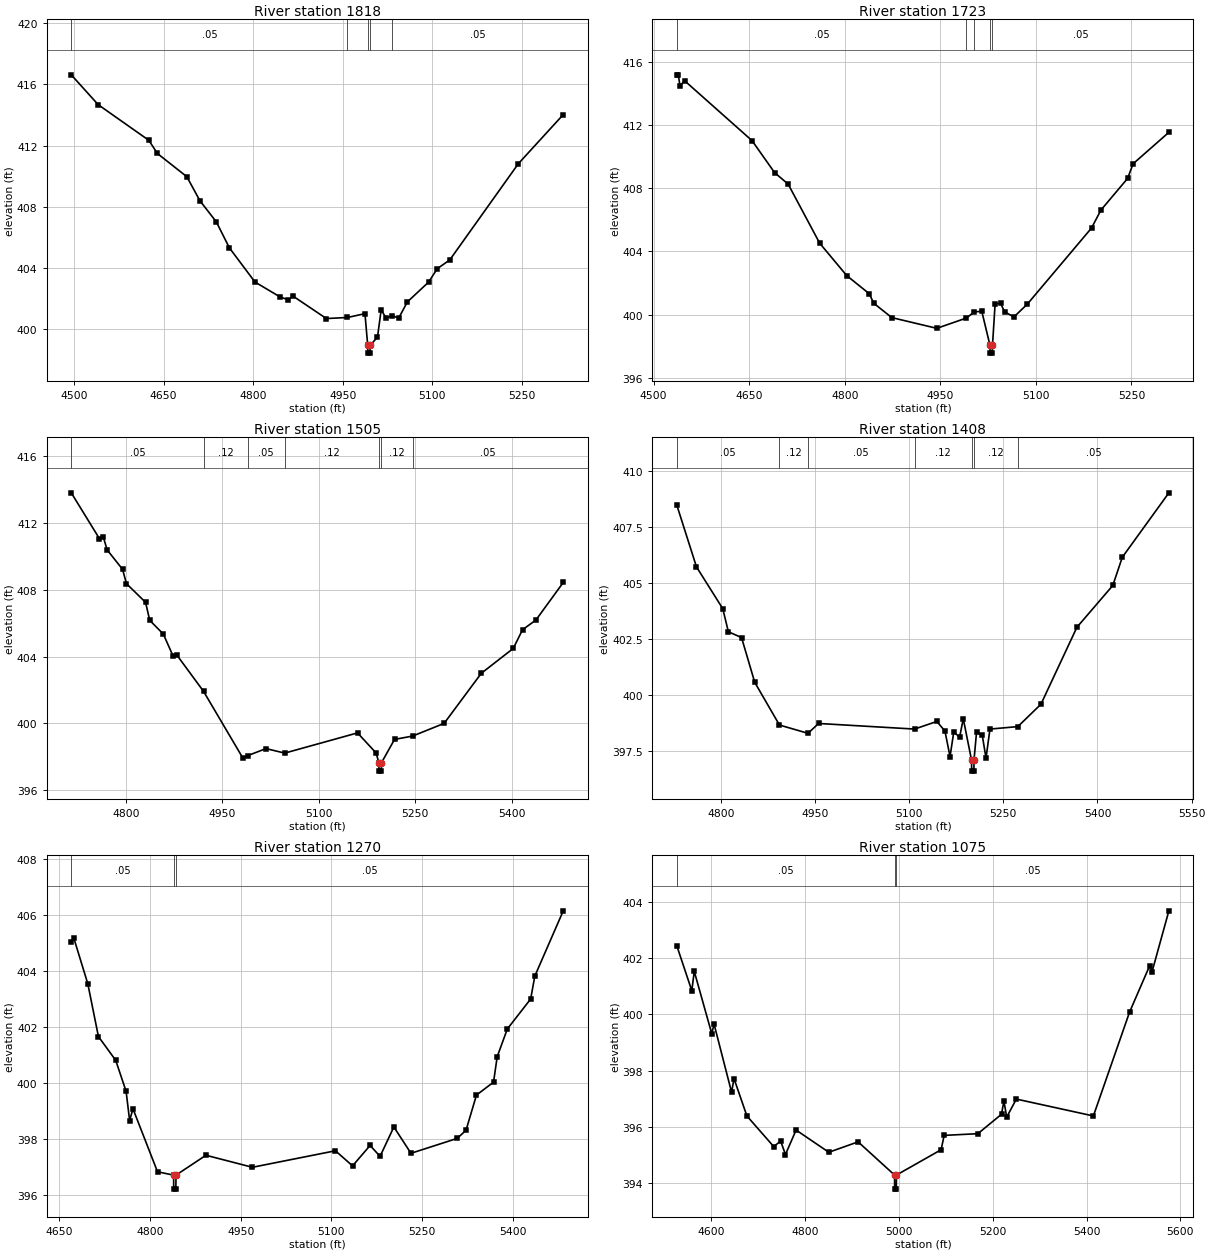
Type RM Length L Ch R = 1,1818,95,95,95
BEGIN DESCRIPTION:
Lacy 157 787
END DESCRIPTION:
XS GIS Cut Line= 3
      2725121.73      6841601.85      2725508.75      6841933.41
      2725762.13      6842120.34
#Sta/Elev= 30
  4495.2  416.63  4540.3  414.68  4625.2  412.35  4639.5  411.49  4688.9  409.97
  4710.8  408.40  4738.3  407.02  4760.2  405.32  4803.0  403.09  4844.8  402.12
  4859.0  401.92  4866.7  402.17  4922.7  400.70  4958.1  400.77  4987.4  401.02
  4992.0  398.94  4992.3  398.44  4995.8  398.44  4996.0  398.94  5008.4  399.49
  5014.6  401.28  5023.0  400.71  5032.6  400.89  5043.9  400.73  5058.5  401.79
  5094.0  403.08  5108.6  403.96  5129.5  404.53  5244.4  410.82  5319.7  414.03
#Mann=5,-1,0
  4495.2    0.05       0  4958.1    0.12       0  4992.0    0.07       0
  4996.0    0.12       0  5032.6    0.05       0
Bank Sta=4992,4996
Exp/Cntr=0.3,0.1

Type RM Length L Ch R = 1,1723,218,218,218
BEGIN DESCRIPTION:
Lacy 157 788
END DESCRIPTION:
XS GIS Cut Line= 3
      2725107.18      6841672.91      2725441.07      6842001.10
      2725688.95      6842176.95
#Sta/Elev= 30
  4536.6  415.18  4538.8  415.18  4541.5  414.47  4548.6  414.81  4654.6  411.01
  4689.9  408.99  4711.2  408.26  4760.7  404.52  4803.1  402.47  4838.5  401.32
  4845.5  400.72  4873.8  399.81  4944.5  399.13  4990.8  399.78  5003.4  400.17
  5015.1  400.21  5027.9  398.06  5028.1  397.56  5031.6  397.56  5031.9  398.06
  5036.0  400.68  5044.6  400.71  5050.8  400.18  5065.5  399.85  5086.5  400.66
  5187.3  405.48  5202.1  406.62  5243.9  408.62  5252.6  409.55  5308.7  411.54
#Mann=5,-1,0
  4536.6    0.05       0  4990.8    0.12       0  5003.4    0.05       0
  5027.9    0.07       0  5031.9    0.05       0
Bank Sta=5027.9,5031.9
Exp/Cntr=0.3,0.1

Type RM Length L Ch R = 1,1505,97,97,97
BEGIN DESCRIPTION:
Lacy 157 786
END DESCRIPTION:
XS GIS Cut Line= 3
      2725083.93      6841724.30      2725250.61      6841979.33
      2725612.03      6842264.10
#Sta/Elev= 30
  4715.3  413.81  4759.0  411.07  4764.9  411.19  4771.1  410.39  4795.0  409.23
  4801.1  408.37  4830.8  407.25  4837.3  406.17  4858.4  405.35  4873.5  404.04
  4879.5  404.09  4920.9  401.92  4982.1  397.92  4989.7  398.07  5018.0  398.49
  5047.1  398.22  5160.3  399.43  5189.1  398.23  5193.5  397.64  5193.8  397.14
  5197.3  397.14  5197.5  397.64  5217.8  399.04  5245.9  399.24  5294.9  400.00
  5352.7  403.00  5402.4  404.49  5416.8  405.61  5437.6  406.19  5480.1  408.44
#Mann=7,-1,0
  4715.3    0.05       0  4920.9    0.12       0  4989.7    0.05       0
  5047.1    0.12       0  5193.5    0.05       0  5197.5    0.12       0
  5245.9    0.05       0
Bank Sta=5193.5,5197.5
Exp/Cntr=0.3,0.1

Type RM Length L Ch R = 1,1408,138,138,138
BEGIN DESCRIPTION:
Lacy 157 785
END DESCRIPTION:
XS GIS Cut Line= 3
      2725043.11      6841820.75      2725195.82      6842045.16
      2725624.41      6842325.73
#Sta/Elev= 30
  4730.0  408.47  4761.2  405.72  4803.1  403.85  4812.0  402.82  4833.0  402.56
  4854.0  400.56  4893.4  398.65  4938.9  398.28  4955.7  398.72  5108.5  398.47
  5144.1  398.81  5157.0  398.38  5165.1  397.24  5171.1  398.35  5180.3  398.10
  5186.2  398.93  5199.3  397.09  5199.6  396.59  5203.1  396.59  5203.3  397.09
  5207.3  398.32  5216.4  398.20  5222.4  397.17  5228.7  398.47  5273.1  398.58
  5309.9  399.58  5367.2  403.02  5424.4  404.89  5439.5  406.15  5513.7  409.03
#Mann=7,-1,0
  4730.0    0.05       0  4893.4    0.12       0  4938.9    0.05       0
  5108.5    0.12       0  5199.3    0.03       0  5203.3    0.12       0
  5273.1    0.05       0
Bank Sta=5199.3,5203.3
Exp/Cntr=0.3,0.1

Type RM Length L Ch R = 1,1270,195,195,195
BEGIN DESCRIPTION:
Lacy 157 794
END DESCRIPTION:
XS GIS Cut Line= 3
      2724990.82      6841858.49      2725127.71      6842158.87
      2725564.74      6842365.48
#Sta/Elev= 30
  4669.9  405.01  4674.2  405.16  4697.3  403.53  4714.8  401.65  4743.4  400.80
  4760.6  399.69  4766.4  398.65  4771.9  399.07  4812.5  396.82  4839.1  396.70
  4839.3  396.20  4842.8  396.20  4843.1  396.70  4892.6  397.41  4969.4  396.98
  5106.7  397.57  5135.0  397.03  5164.0  397.76  5180.5  397.37  5203.3  398.42
  5231.6  397.48  5307.8  398.01  5322.6  398.30  5339.9  399.56  5368.1  400.02
  5374.2  400.93  5390.9  401.92  5429.5  402.99  5436.4  403.81  5483.4  406.14
#Mann=3,-1,0
  4669.9    0.05       0  4839.1    0.03       0  4843.1    0.05       0
Bank Sta=4839.1,4843.1
Exp/Cntr=0.3,0.1

Type RM Length L Ch R = 1,1075,0,0,0
BEGIN DESCRIPTION:
Lacy 157 793
END DESCRIPTION:
XS GIS Cut Line= 3
      2724863.54      6841805.78      2724971.87      6842266.20
      2725532.85      6842394.67
#Sta/Elev= 30
  4527.0  402.43  4558.8  400.84  4564.0  401.53  4601.2  399.32  4606.3  399.65
  4643.6  397.23  4648.7  397.72  4676.2  396.39  4733.5  395.30  4748.1  395.50
  4758.4  395.02  4781.0  395.89  4850.8  395.10  4913.2  395.47  4990.9  394.29
  4991.1  393.79  4994.6  393.79  4994.9  394.29  5090.1  395.19  5096.6  395.70
  5168.4  395.76  5218.8  396.45  5223.9  396.92  5229.9  396.35  5250.4  396.99
  5414.6  396.39  5491.7  400.08  5534.6  401.73  5539.7  401.52  5575.5  403.68
#Mann=3,-1,0
  4527.0    0.05       0  4990.9    0.03       0  4994.9    0.05       0
Bank Sta=4990.9,4994.9
Exp/Cntr=0.3,0.1

Chan Stop Cuts=-1