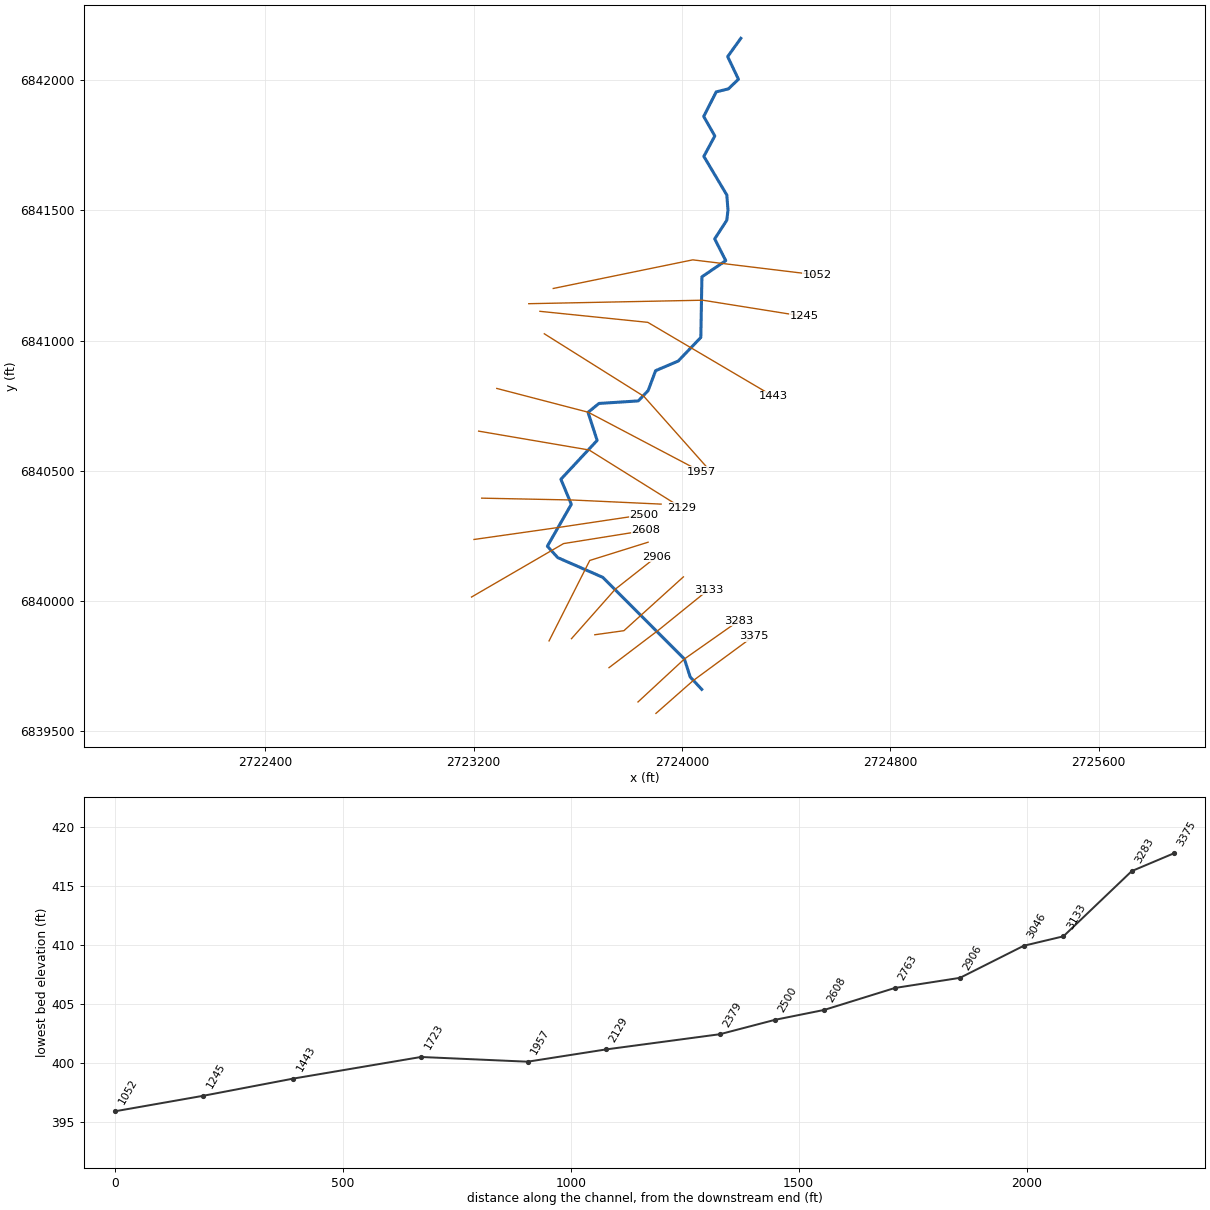
--- Lacy 158.prj (project) ---

Proj Title=Lacy 158 Base Level Engineering
Current Plan=p01
Default Exp/Contr=0.3,0.1
English Units
Geom File=g01
Flow File=f01
Plan File=p01
Y Axis Title=Elevation
X Axis Title(PF)=Main Channel Distance
X Axis Title(XS)=Station
BEGIN DESCRIPTION:
Lacy 158
END DESCRIPTION:
DSS Export Rating Curves= 0
DSS Export Rating Curve Sorted= 0
DSS Export Volume Flow Curves= 0
DXF OffsetX= 0
DXF OffsetY= 0
DXF ScaleX= 1
DXF ScaleY= 10

--- Lacy 158.p01 (plan) ---

Plan Title=Multiple Run
Short Identifier=Multiple
Geom File=g01
Flow File=f01
Subcritical Flow
K Sum by GR= 0
Std Step Tol= 0.01
Critical Tol= 0.01
Num of Std Step Trials= 20
Max Error Tol= 0.3
Flow Tol Ratio= 0.001
Split Flow NTrial= 30
Split Flow Tol= 0.02
Split Flow Ratio= 0.02
Log Output Level= 0
Friction Slope Method= 1
Unsteady Friction Slope Method= 2
Unsteady Bridges Friction Slope Method= 1
Parabolic Critical Depth
Global Vel Dist=  1 , 1 , 1
Global Log Level= 0
CheckData=True
Encroach Param= -1, 0, 0, 0
BEGIN DESCRIPTION:
Multiple Run
END DESCRIPTION:

--- Lacy 158.f01 (steady flow) ---

Flow Title=Multiple
Number of Profiles=7
Profile Names=10-year,25-year,50-year,1pct_min,100-year,1pct_plu,500-year
River Rch & RM= Lacy 158,Reach-1,3375
     280     358     418     243     485     968     651
Boundary for River Rch & Prof#=Lacy 158,Reach-1,1
Up Type=0
Dn Type=3
Dn Slope=0.005
Boundary for River Rch & Prof#=Lacy 158,Reach-1,2
Up Type=0
Dn Type=3
Dn Slope=0.005
Boundary for River Rch & Prof#=Lacy 158,Reach-1,3
Up Type=0
Dn Type=3
Dn Slope=0.005
Boundary for River Rch & Prof#=Lacy 158,Reach-1,4
Up Type=0
Dn Type=3
Dn Slope=0.005
Boundary for River Rch & Prof#=Lacy 158,Reach-1,5
Up Type=0
Dn Type=3
Dn Slope=0.005
Boundary for River Rch & Prof#=Lacy 158,Reach-1,6
Up Type=0
Dn Type=3
Dn Slope=0.005
Boundary for River Rch & Prof#=Lacy 158,Reach-1,7
Up Type=0
Dn Type=3
Dn Slope=0.005

--- Lacy 158.g01 (geometry) ---

Geom Title=Existing Conditions
Program Version=4.10

River Reach=Lacy 158        ,Reach-1
Reach XY= 30
        2724076.        6839661.      2724031.71      6839708.65
      2724009.39      6839777.69      2723696.09      6840091.22
      2723523.14      6840166.83       2723483.2       6840210.7
       2723575.2       6840371.7      2723535.15      6840467.73
      2723674.34      6840617.05      2723639.37       6840724.8
      2723681.45      6840758.94      2723832.47       6840768.7
      2723870.25      6840808.45      2723898.86      6840884.83
      2723985.69      6840921.78      2724072.47      6841012.45
      2724076.69      6841245.17      2724168.24      6841307.36
       2724125.8      6841390.79      2724172.27      6841462.58
      2724176.77      6841500.95      2724172.32      6841559.42
      2724084.07      6841707.69      2724126.22        6841786.
      2724083.55      6841861.03      2724131.62      6841955.38
      2724178.51      6841966.99      2724216.94        6842004.
      2724175.54      6842090.75        2724226.        6842161.

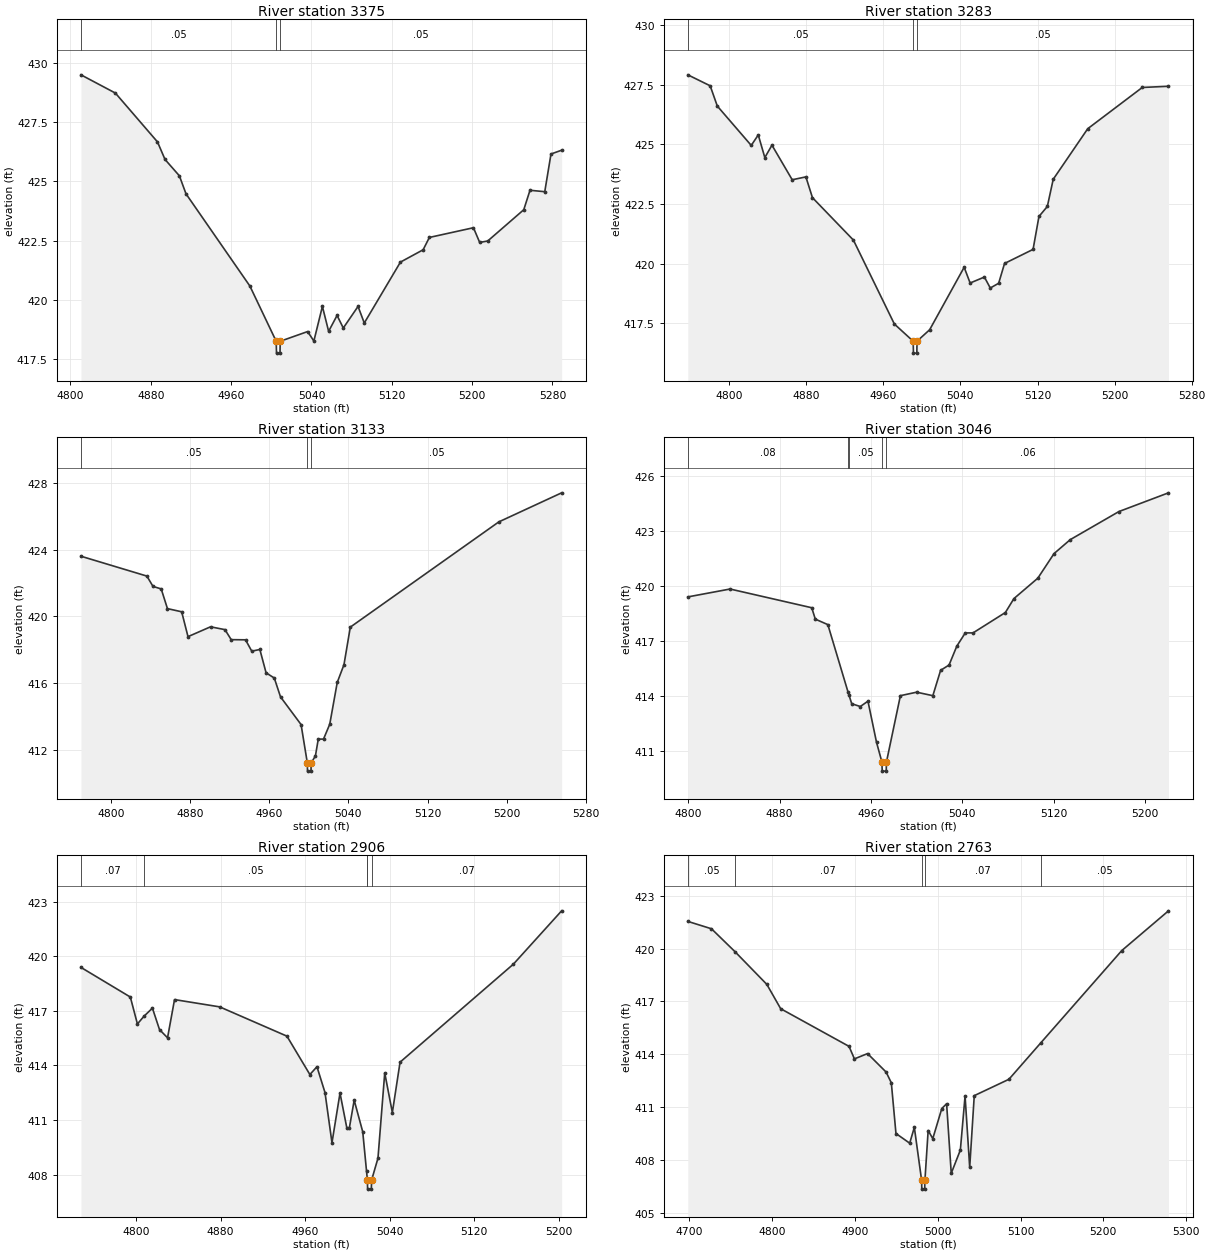
Type RM Length L Ch R = 1 ,3375    ,92,92,92
BEGIN DESCRIPTION:
Lacy 158 784
END DESCRIPTION:
XS GIS Cut Line= 3
      2723900.23      6839568.81      2724042.42      6839694.08
      2724275.26      6839865.45
#Sta/Elev= 30
  4810.5  429.49  4844.8  428.72  4886.7  426.66  4894.2  425.92  4908.5  425.23
  4915.1  424.47  4978.7  420.58  5004.9  418.25  5005.2  417.75  5008.7  417.75
  5008.9  418.25  5036.2  418.66  5042.4  418.26  5050.9  419.72  5057.1  418.67
  5065.5  419.34  5071.7  418.81  5086.4  419.72  5092.6  419.02  5128.6  421.59
  5151.2  422.11  5157.4  422.63  5201.3  423.04  5207.5  422.42  5215.5  422.48
  5251.4   423.8  5257.6  424.62  5272.3  424.56  5278.5  426.15  5289.1  426.31
#Mann= 3 ,-1 , 0
  4810.5     .05       0  5004.9     .04       0  5008.9     .05       0
Bank Sta=5004.9,5008.9
XS Rating Curve= 0 ,0
Exp/Cntr=0.3,0.1

Type RM Length L Ch R = 1 ,3283    ,150,150,150
BEGIN DESCRIPTION:
Lacy 158 783
END DESCRIPTION:
XS GIS Cut Line= 3
      2723831.28      6839612.68      2724009.39      6839777.69
      2724218.81      6839924.76
#Sta/Elev= 30
  4757.2  427.92  4780.4  427.46  4787.8  426.61    4823  424.96  4830.3   425.4
  4837.1  424.45  4844.5  424.97  4865.5  423.52  4879.7  423.64  4886.5  422.77
    4929  420.99  4971.5  417.47    4991  416.75  4991.3  416.25  4994.8  416.25
    4995  416.75  5008.1  417.23  5043.9  419.85  5050.1  419.19  5064.9  419.44
    5071  418.98  5079.7  419.18  5085.8  420.01  5115.4   420.6  5121.5  421.98
  5130.2   422.4  5136.3  423.54  5172.1  425.66  5228.7  427.39  5255.9  427.44
#Mann= 3 ,-1 , 0
  4757.2     .05       0    4991     .05       0    4995     .05       0
Bank Sta=4991,4995
XS Rating Curve= 0 ,0
Exp/Cntr=0.3,0.1

Type RM Length L Ch R = 1 ,3133    ,87,87,87
BEGIN DESCRIPTION:
Lacy 158 776
END DESCRIPTION:
XS GIS Cut Line= 3
      2723719.81      6839744.25      2723911.11      6839889.44
      2724102.47      6840044.25
#Sta/Elev= 30
  4769.4   423.6  4836.1  422.41  4842.3  421.79  4850.6  421.64  4856.9  420.46
  4871.3  420.27  4877.7  418.78  4900.5  419.37  4915.1   419.2  4921.4   418.6
  4935.9  418.59  4942.2  417.91  4950.4  418.01  4956.7  416.61    4965   416.3
  4971.3  415.17  4992.1  413.51  4998.4  411.22  4998.6  410.72  5002.1  410.72
  5002.4  411.22  5006.6  411.63  5009.5  412.64  5014.8  412.64  5021.1  413.53
  5028.7  416.04  5035.5   417.1  5041.9  419.35  5192.2  425.66  5255.7   427.4
#Mann= 3 ,-1 , 0
  4769.4     .05       0  4998.4     .05       0  5002.4     .05       0
Bank Sta=4998.4,5002.4
XS Rating Curve= 0 ,0
Exp/Cntr=0.3,0.1

Type RM Length L Ch R = 1 ,3046    ,140,140,140
BEGIN DESCRIPTION:
Lacy 158 777
END DESCRIPTION:
XS GIS Cut Line= 3
      2723665.43      6839870.72      2723777.13      6839886.32
      2724005.54      6840092.97
#Sta/Elev= 30
  4799.6  419.41  4836.6  419.84  4908.1  418.82  4911.2   418.2  4922.2   417.9
  4939.9  414.22  4940.6  414.08  4943.1  413.59  4950.6  413.44  4957.3  413.73
  4964.8  411.49  4969.5  410.42  4969.8  409.92  4973.3  409.92  4973.5  410.42
  4985.7  414.03  4999.9  414.22  5014.1  414.03  5020.9  415.41  5028.3   415.7
  5035.1  416.73  5042.5  417.45  5049.3  417.45  5077.6  418.56  5085.1  419.32
    5106  420.43  5120.2  421.77  5134.4  422.53    5177  424.06  5220.4  425.08
#Mann= 5 ,-1 , 0
  4799.6     .08       0  4939.9     .07       0  4940.6     .05       0
  4969.5     .04       0  4973.5     .06       0
Bank Sta=4969.5,4973.5
XS Rating Curve= 0 ,0
Exp/Cntr=0.3,0.1

Type RM Length L Ch R = 1 ,2906    ,143,143,143
BEGIN DESCRIPTION:
Lacy 158 780
END DESCRIPTION:
XS GIS Cut Line= 3
      2723575.87      6839855.68      2723744.03      6840045.73
      2723901.84      6840169.96
#Sta/Elev= 30
    4748  419.39  4794.7  417.76  4801.4  416.28  4807.7  416.71  4815.6  417.15
  4822.3  415.97  4829.9  415.52  4836.5  417.62  4879.2  417.22  4942.8  415.61
  4964.5   413.5  4971.2  413.93  4978.8  412.51  4985.4  409.75    4993  412.48
  4999.5  410.55  5001.8  410.55  5006.4  412.09  5014.5  410.35  5018.1  408.18
  5018.9   407.7  5019.1   407.2  5022.6   407.2  5022.9   407.7  5028.9   408.9
  5035.3  413.59  5042.5  411.41  5049.8  414.18    5157  419.57  5202.6   422.5
#Mann= 5 ,-1 , 0
    4748     .07       0  4807.7     .05       0  5018.1     .04       0
  5018.9     .06       0  5022.9     .07       0
Bank Sta=5018.9,5022.9
XS Rating Curve= 0 ,0
Exp/Cntr=0.3,0.1

Type RM Length L Ch R = 1 ,2763    ,155,155,155
BEGIN DESCRIPTION:
Lacy 158 779
END DESCRIPTION:
XS GIS Cut Line= 3
      2723489.74      6839847.17      2723645.97      6840156.01
      2723869.96       6840226.1
#Sta/Elev= 30
    4698  421.55  4726.6  421.13    4755  419.83  4793.5  417.97  4810.2  416.59
  4892.8  414.45  4899.3  413.74  4915.2  414.04  4937.6  412.99  4943.9  412.38
  4949.5   409.5  4966.1  408.95  4971.7  409.85  4980.5  406.84  4980.7  406.34
  4984.2  406.34  4984.5  406.84  4988.4  409.67    4994  409.21  5004.9  410.92
  5010.7  411.19  5016.3  407.24  5027.3  408.56    5033  411.63  5038.6  407.58
  5044.1  411.65    5086  412.58  5124.7  414.66  5222.3  419.89  5278.8  422.15
#Mann= 5 ,-1 , 0
    4698     .05       0    4755     .07       0  4980.5     .04       0
  4984.5     .07       0  5124.7     .05       0
Bank Sta=4980.5,4984.5
XS Rating Curve= 0 ,0
Exp/Cntr=0.3,0.1

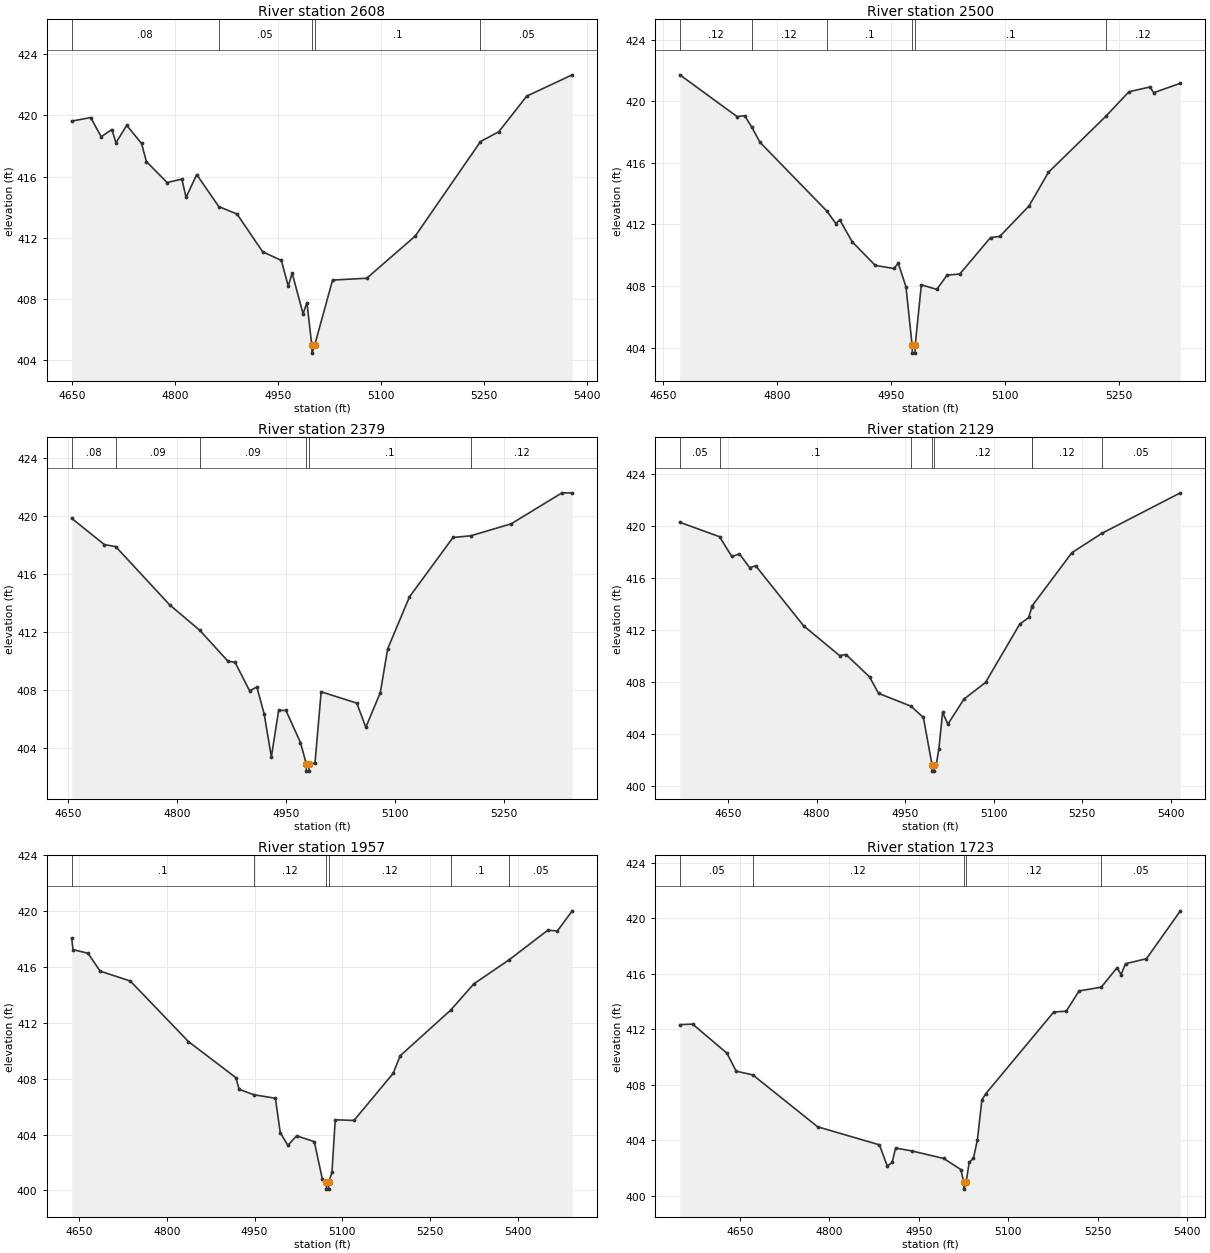
Type RM Length L Ch R = 1 ,2608    ,108,108,108
BEGIN DESCRIPTION:
Lacy 158 778
END DESCRIPTION:
XS GIS Cut Line= 3
      2723192.01      6840015.57       2723545.3      6840220.78
      2723861.41      6840271.38
#Sta/Elev= 30
    4650  419.63  4677.7  419.86  4692.9  418.61  4708.6  419.08  4714.4  418.21
  4730.1  419.35  4751.7  418.17  4758.7  416.99  4788.9  415.62  4810.4  415.84
  4816.5  414.65    4832  416.14  4864.1  414.05  4890.7  413.56    4928   411.1
  4955.3  410.53  4965.2  408.86    4971   409.7  4986.8  407.05  4992.5  407.78
  4999.6  404.98  4999.8  404.48  5003.6  404.98  5029.8  409.25  5079.5  409.37
  5150.1  412.12  5245.1  418.29  5271.9  418.94  5312.5  421.26  5378.7  422.65
#Mann= 5 ,-1 , 0
    4650     .08       0  4864.1     .05       0  4999.6     .04       0
  5003.6      .1       0  5245.1     .05       0
Bank Sta=4999.6,5003.6
XS Rating Curve= 0 ,0
Exp/Cntr=0.3,0.1

Type RM Length L Ch R = 1 ,2500    ,121,121,121
BEGIN DESCRIPTION:
Lacy 158 775
END DESCRIPTION:
XS GIS Cut Line= 3
      2723201.52      6840236.58      2723529.16      6840283.18
      2723852.92       6840331.6
#Sta/Elev= 30
  4672.5  421.72  4747.7  419.01  4757.8  419.06    4767  418.33    4778  417.33
  4865.8  412.87  4877.7  412.06  4882.8   412.3  4899.2  410.87  4929.5  409.34
  4953.6  409.14  4959.8  409.47  4969.9  407.95    4978  404.14  4978.3  403.64
  4981.8  403.64    4982  404.14  4990.1  408.08  5010.4  407.78    5024  408.71
  5040.7  408.78  5081.1  411.15  5093.2  411.22  5131.7   413.2  5157.3  415.39
  5232.8  419.03  5263.1  420.62  5290.7  420.93  5295.7  420.56  5330.8  421.17
#Mann= 6 ,-1 , 0
  4672.5     .12       0    4767     .12       0  4865.8      .1       0
    4978     .09       0    4982      .1       0  5232.8     .12       0
Bank Sta=4978,4982
XS Rating Curve= 0 ,0
Exp/Cntr=0.3,0.1

Type RM Length L Ch R = 1 ,2379    ,250,250,250
BEGIN DESCRIPTION:
Lacy 158 774
END DESCRIPTION:
XS GIS Cut Line= 3
      2723230.91      6840395.29      2723578.13      6840388.22
      2723920.07      6840372.38
#Sta/Elev= 30
  4654.8  419.85  4699.9  418.04  4715.5   417.9  4789.9  413.88  4831.1  412.14
  4869.9  410.01  4879.9  409.92  4899.9  407.96  4909.9  408.22  4919.9  406.38
  4929.9   403.4  4939.9  406.61  4949.9  406.61    4970  404.39    4978  402.92
  4978.2  402.42  4981.7  402.42    4982  402.92    4990  402.98  4998.5  407.89
  5047.6  407.11    5060  405.44    5080  407.84  5090.1  410.85  5120.1  414.43
  5180.1  418.53  5204.7  418.65  5260.2  419.47  5330.3  421.61  5344.4   421.6
#Mann= 6 ,-1 , 0
  4654.8     .08       0  4715.5     .09       0  4831.1     .09       0
    4978     .04       0    4982      .1       0  5204.7     .12       0
Bank Sta=4978,4982
XS Rating Curve= 0 ,0
Exp/Cntr=0.3,0.1

Type RM Length L Ch R = 1 ,2129    ,172,172,172
BEGIN DESCRIPTION:
Lacy 158 773
END DESCRIPTION:
XS GIS Cut Line= 3
      2723219.36      6840652.63      2723643.44      6840580.24
       2723997.5      6840359.03
#Sta/Elev= 30
  4568.3  420.29  4635.6  419.18  4656.2  417.66  4669.3  417.85  4686.6   416.8
  4696.8  416.94  4777.9  412.32  4838.8  410.03  4849.7  410.11  4889.5  408.39
  4904.8  407.12  4959.8  406.13  4980.8  405.26  4995.3  401.63  4995.5  401.13
    4999  401.13  4999.3  401.63  5002.5  401.63    5007  402.85  5013.3  405.65
  5022.3  404.75  5049.4  406.67    5086  407.96  5143.8  412.44  5159.1  412.96
  5164.5  413.77  5165.2  413.87  5232.2  417.95    5283  419.44    5416  422.56
#Mann= 8 ,-1 , 0
  4568.3     .05       0  4635.6      .1       0  4959.8     .12       0
  4995.3     .07       0  4999.3     .12       0  5164.5      .1       0
  5165.2     .12       0    5283     .05       0
Bank Sta=4995.3,4999.3
XS Rating Curve= 0 ,0
Exp/Cntr=0.3,0.1

Type RM Length L Ch R = 1 ,1957    ,234,234,234
BEGIN DESCRIPTION:
Lacy 158 772
END DESCRIPTION:
XS GIS Cut Line= 3
      2723289.02       6840816.6      2723640.06       6840725.2
      2724076.13      6840495.53
#Sta/Elev= 30
  4637.5  418.08  4639.7  417.25  4665.4  416.99  4686.1  415.71  4737.7     415
  4837.1  410.66  4918.1  408.08  4923.7  407.24  4949.2  406.85  4985.7   406.6
    4994  404.14    5007  403.23    5022  403.91  5052.2  403.49    5066   400.8
  5072.8  400.59    5073  400.09  5076.5  400.09  5076.8  400.59  5082.4   401.3
    5088  405.06    5120  405.01  5186.9  408.38  5199.1  409.65  5285.2  412.91
  5324.7  414.79  5385.5  416.53  5451.3  418.64  5467.7  418.59  5493.1  420.03
#Mann= 6 ,-1 , 0
  4637.5      .1       0  4949.2     .12       0  5072.8     .07       0
  5076.8     .12       0  5285.2      .1       0  5385.5     .05       0
Bank Sta=5072.8,5076.8
XS Rating Curve= 0 ,0
Exp/Cntr=0.3,0.1

Type RM Length L Ch R = 1 ,1723    ,280,280,280
BEGIN DESCRIPTION:
Lacy 158 771
END DESCRIPTION:
XS GIS Cut Line= 3
      2723471.47      6841026.48      2723853.48      6840786.45
      2724111.39       6840496.4
#Sta/Elev= 30
  4549.5  412.34  4570.9  412.38  4628.6  410.28  4643.9  408.99  4671.8  408.72
  4780.6  404.98  4884.2  403.68  4897.3  402.15  4905.4  402.41  4911.3  403.45
  4938.7  403.24  4991.8   402.7  5020.8   401.9  5025.5  400.99  5025.8  400.49
  5029.5  400.99  5034.7  402.43  5041.7   402.7  5048.4  404.03    5056  406.92
  5062.6  407.37  5176.4  413.25  5197.3  413.31    5219  414.77  5256.1  415.04
  5282.6  416.44  5289.3  415.95  5296.8  416.73  5331.9  417.09  5388.8  420.54
#Mann= 5 ,-1 , 0
  4549.5     .05       0  4671.8     .12       0  5025.5     .07       0
  5029.5     .12       0  5256.1     .05       0
Bank Sta=5025.5,5029.5
XS Rating Curve= 0 ,0
Exp/Cntr=0.3,0.1

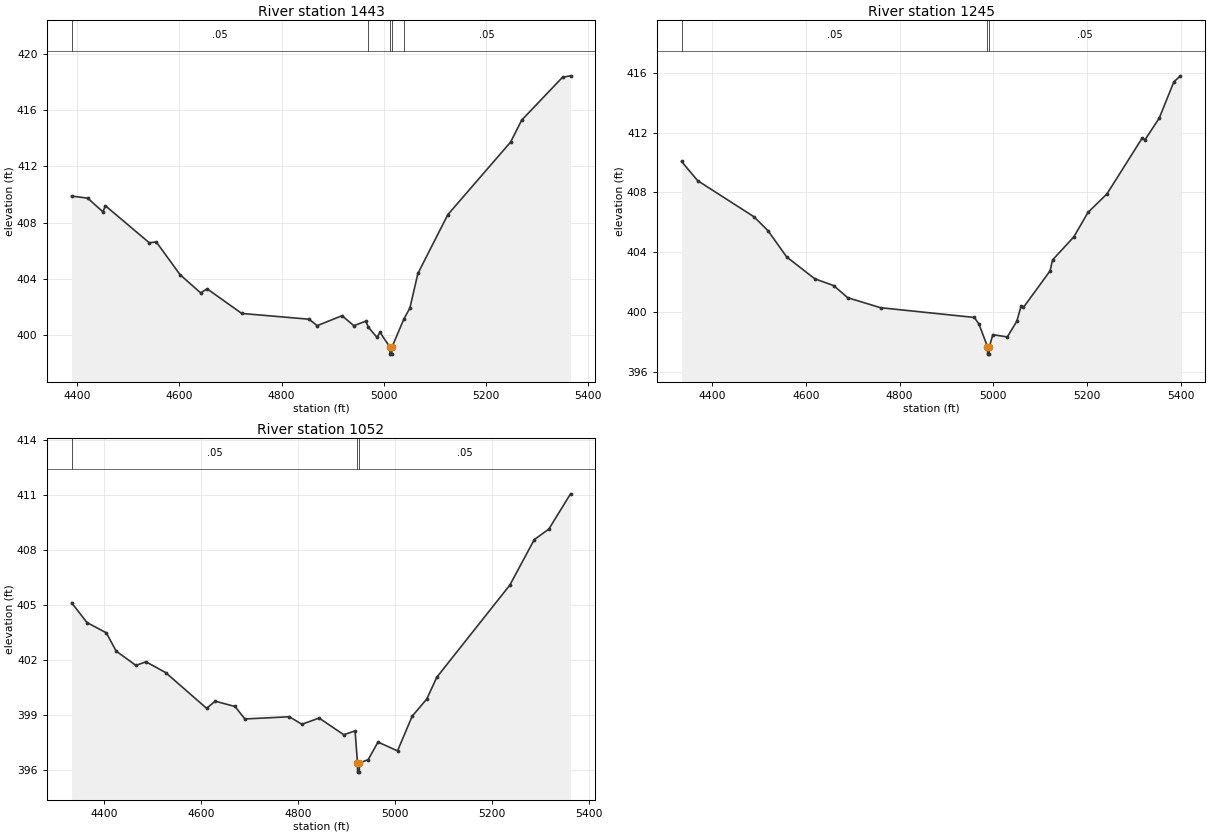
Type RM Length L Ch R = 1 ,1443    ,198,198,198
BEGIN DESCRIPTION:
Lacy 158 769
END DESCRIPTION:
XS GIS Cut Line= 3
      2723454.78      6841112.69       2723868.9      6841070.39
      2724351.21      6840786.16
#Sta/Elev= 30
    4389  409.89  4420.4  409.74  4450.2  408.77  4455.2   409.2    4541  406.57
  4554.7  406.63  4601.3   404.3  4641.5  403.01  4654.1   403.3  4721.9  401.55
  4853.7  401.14  4869.4  400.68  4918.1  401.39  4941.2  400.68  4964.4     401
  4969.7  400.57  4986.5  399.85  4992.3  400.21  5011.8  399.16    5012  398.66
  5015.5  398.66  5015.8  399.16  5038.9  401.14  5050.9  401.94  5066.5  404.39
  5125.1  408.57    5248  413.73  5269.5  415.28  5349.5  418.33  5365.1  418.43
#Mann= 5 ,-1 , 0
    4389     .05       0  4969.7     .12       0  5011.8     .07       0
  5015.8     .12       0  5038.9     .05       0
Bank Sta=5011.8,5015.8
XS Rating Curve= 0 ,0
Exp/Cntr=0.3,0.1

Type RM Length L Ch R = 1 ,1245    ,193,193,193
BEGIN DESCRIPTION:
Lacy 158 770
END DESCRIPTION:
XS GIS Cut Line= 3
      2723411.81        6841142.      2724079.93       6841155.4
      2724470.64      6841093.08
#Sta/Elev= 30
  4335.1  410.07  4369.3  408.79  4489.3  406.38  4519.3  405.45  4559.3  403.69
  4619.3  402.23  4659.4  401.78  4689.4  400.97  4759.4   400.3  4959.4  399.65
  4969.4   399.2  4987.4   397.7  4987.7   397.2  4991.2   397.2  4991.4   397.7
  4998.9   398.5  5029.8  398.35    5050   399.4  5059.1   400.4  5064.1  400.32
  5120.9  402.76  5126.2  403.49  5171.5  405.03  5201.9  406.67  5242.4  407.91
  5317.7  411.65  5323.4  411.52  5353.8  412.97  5384.9  415.39    5399  415.79
#Mann= 3 ,-1 , 0
  4335.1     .05       0  4987.4     .05       0  4991.4     .05       0
Bank Sta=4987.4,4991.4
XS Rating Curve= 0 ,0
Exp/Cntr=0.3,0.1

Type RM Length L Ch R = 1 ,1052    ,0,0,0
BEGIN DESCRIPTION:
Lacy 158 768
END DESCRIPTION:
XS GIS Cut Line= 3
      2723505.92      6841200.47      2724041.42      6841310.36
      2724520.25      6841252.25
#Sta/Elev= 30
  4333.5  405.13  4365.2  404.05    4405  403.49  4425.5  402.49  4466.3  401.71
  4486.7  401.91  4527.5  401.32    4612  399.37  4629.6  399.76  4670.5  399.47
  4690.9  398.79  4782.7  398.91  4808.5   398.5    4844  398.84  4894.8  397.93
  4918.2  398.14  4923.1  396.39  4923.3  395.89  4926.8  395.89  4927.1  396.39
  4945.2  396.57  4965.4  397.53  5005.7  397.05  5035.9  398.94  5066.1  399.88
  5086.8  401.07  5237.3  406.09  5287.7  408.57  5317.9  409.15  5362.5  411.07
#Mann= 3 ,-1 , 0
  4333.5     .05       0  4923.1     .04       0  4927.1     .05       0
Bank Sta=4923.1,4927.1
XS Rating Curve= 0 ,0
Exp/Cntr=0.3,0.1

Chan Stop Cuts=-1
Use User Specified Reach Order=0
Composite Channel Slope=5