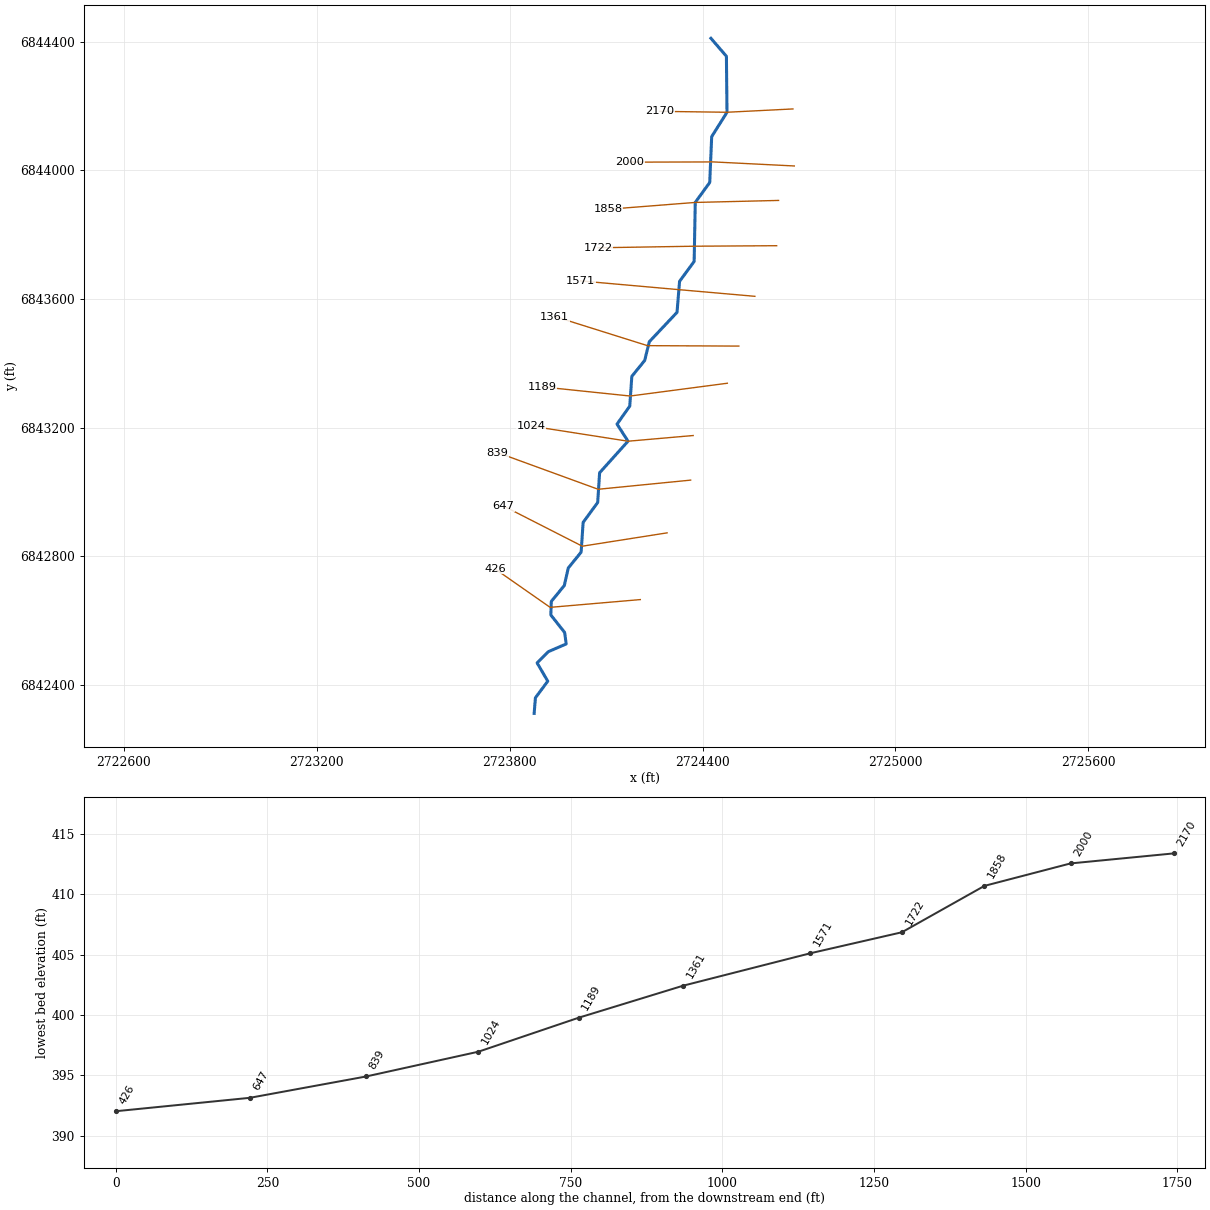
--- Lacy 159.prj (project) ---

Proj Title=Lacy 159 Base Level Engineering
Current Plan=p01
Default Exp/Contr=0.3,0.1
English Units
Geom File=g01
Flow File=f01
Plan File=p01
BEGIN DESCRIPTION:
Lacy 159
END DESCRIPTION:

--- Lacy 159.p01 (plan) ---

Plan Title=Multiple Run
Short Identifier=Multiple
Geom File=g01
Flow File=f01
Subcritical Flow
K Sum by GR= 0
Std Step Tol= 0.01
Critical Tol= 0.01
Num of Std Step Trials= 20
Max Error Tol= 0.3
Flow Tol Ratio= 0.001
Split Flow NTrial= 30
Split Flow Tol= 0.02
Split Flow Ratio= 0.02
Log Output Level= 0
Friction Slope Method= 1
Unsteady Friction Slope Method= 2
Unsteady Bridges Friction Slope Method= 1
Parabolic Critical Depth
Global Vel Dist=  1 , 1 , 1
Global Log Level= 0
CheckData=True
Encroach Param= -1, 0, 0, 0
BEGIN DESCRIPTION:
Multiple Run
END DESCRIPTION:

--- Lacy 159.f01 (steady flow) ---

Flow Title=Multiple
Number of Profiles=7
Profile Names=10-year,25-year,50-year,1pct_min,100-year,1pct_plu,500-year
River Rch & RM= Lacy 159,Reach-1,2170
     111     132     147      82     164     327     200
Boundary for River Rch & Prof#=Lacy 159,Reach-1,1
Up Type=0
Dn Type=3
Dn Slope=0.005
Boundary for River Rch & Prof#=Lacy 159,Reach-1,2
Up Type=0
Dn Type=3
Dn Slope=0.005
Boundary for River Rch & Prof#=Lacy 159,Reach-1,3
Up Type=0
Dn Type=3
Dn Slope=0.005
Boundary for River Rch & Prof#=Lacy 159,Reach-1,4
Up Type=0
Dn Type=3
Dn Slope=0.005
Boundary for River Rch & Prof#=Lacy 159,Reach-1,5
Up Type=0
Dn Type=3
Dn Slope=0.005
Boundary for River Rch & Prof#=Lacy 159,Reach-1,6
Up Type=0
Dn Type=3
Dn Slope=0.005
Boundary for River Rch & Prof#=Lacy 159,Reach-1,7
Up Type=0
Dn Type=3
Dn Slope=0.005

--- Lacy 159.g01 (geometry) ---

Geom Title=Existing Conditions

River Reach=Lacy 159,Reach-1
Reach XY= 30
      2724426.00      6844411.00      2724474.11      6844355.22
      2724475.93      6844181.03      2724428.27      6844105.06
      2724422.21      6843962.57      2724377.22      6843900.49
      2724373.74      6843716.94      2724328.36      6843655.02
      2724320.46      6843558.58      2724234.16      6843467.05
      2724219.86      6843408.83      2724179.82      6843359.41
      2724173.46      6843266.89      2724133.80      6843210.90
      2724167.99      6843157.67      2724079.64      6843059.50
      2724073.64      6842966.98      2724028.35      6842905.03
      2724022.17      6842812.58      2723982.11      6842763.18
      2723969.85      6842708.80      2723929.35      6842659.27
      2723927.85      6842617.09      2723970.74      6842562.85
      2723975.73      6842527.02      2723919.73      6842502.72
      2723885.22      6842467.94      2723918.41      6842411.08
      2723879.98      6842359.64      2723876.00      6842311.00

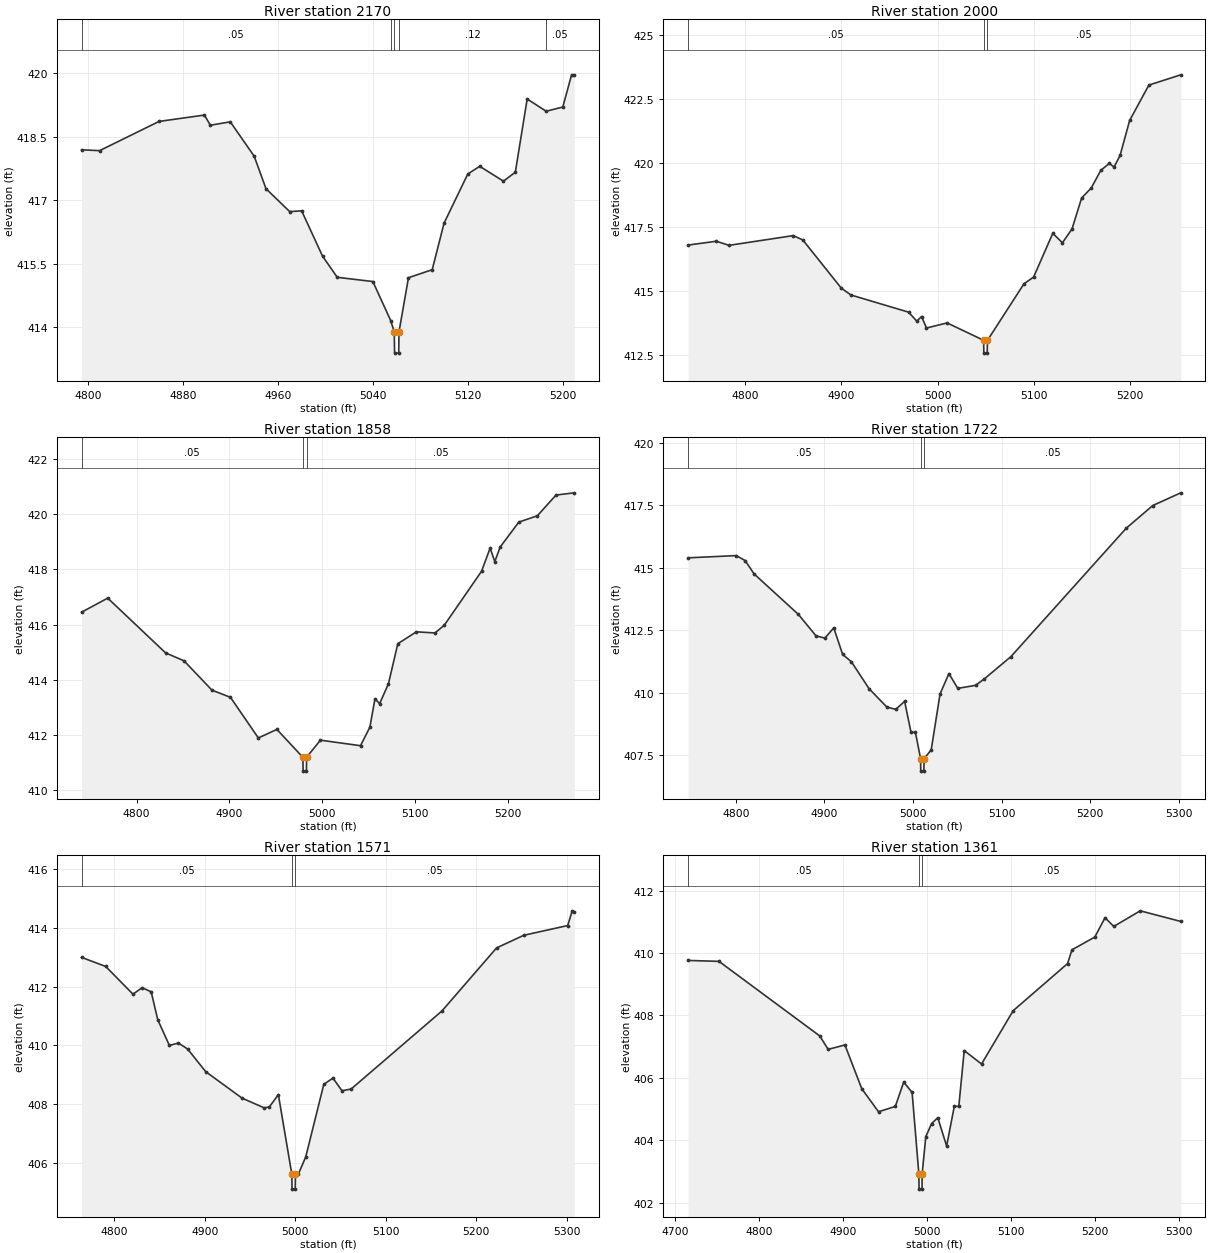
Type RM Length L Ch R = 1,2170,170,170,170
BEGIN DESCRIPTION:
Lacy 159 764
END DESCRIPTION:
XS GIS Cut Line= 3
      2724681.17      6844191.37      2724475.93      6844181.03
      2724266.35      6844183.86
#Sta/Elev= 30
  4794.5  418.19  4809.7  418.17  4859.8  418.86  4898.0  419.01  4903.0  418.77
  4919.8  418.85  4939.9  418.04  4949.9  417.27  4969.9  416.73  4979.9  416.75
  4997.5  415.68  5009.9  415.18  5039.9  415.08  5054.9  414.16  5057.9  413.89
  5058.2  413.39  5061.7  413.39  5061.9  413.89  5069.9  415.17  5089.9  415.36
  5099.9  416.46  5119.9  417.62  5129.9  417.80  5149.9  417.45  5159.9  417.66
  5169.9  419.39  5185.9  419.10  5199.9  419.20  5207.3  419.96  5209.6  419.96
#Mann=5,-1,0
  4794.5    0.05       0  5054.9    0.12       0  5057.9    0.04       0
  5061.9    0.12       0  5185.9    0.05       0
Bank Sta=5057.9,5061.9
Exp/Cntr=0.3,0.1

Type RM Length L Ch R = 1,2000,142,142,142
BEGIN DESCRIPTION:
Lacy 159 763
END DESCRIPTION:
XS GIS Cut Line= 3
      2724685.35      6844013.95      2724433.87      6844026.51
      2724172.76      6844025.81
#Sta/Elev= 30
  4740.3  416.78  4769.7  416.93  4783.0  416.77  4849.8  417.15  4859.8  416.98
  4899.8  415.10  4909.9  414.83  4969.9  414.16  4978.4  413.81  4983.4  413.99
  4988.5  413.54  5010.0  413.74  5048.0  413.06  5048.2  412.56  5051.7  412.56
  5052.0  413.06  5090.0  415.27  5100.0  415.53  5120.0  417.24  5130.0  416.87
  5140.0  417.41  5150.0  418.62  5160.0  419.01  5170.0  419.70  5178.8  419.97
  5183.8  419.83  5190.0  420.28  5200.0  421.65  5220.0  423.03  5253.2  423.43
#Mann=3,-1,0
  4740.3    0.05       0  5048.0    0.04       0  5052.0    0.05       0
Bank Sta=5048,5052
Exp/Cntr=0.3,0.1

Type RM Length L Ch R = 1,1858,136,136,136
BEGIN DESCRIPTION:
Lacy 159 762
END DESCRIPTION:
XS GIS Cut Line= 3
      2724636.44      6843906.74      2724377.22      6843900.49
      2724106.35      6843879.23
#Sta/Elev= 30
  4740.7  416.45  4768.9  416.96  4831.2  414.98  4851.2  414.69  4881.2  413.63
  4901.2  413.37  4931.2  411.90  4951.2  412.21  4979.2  411.20  4979.5  410.70
  4983.0  410.70  4983.2  411.20  4998.1  411.82  5041.3  411.62  5051.4  412.29
  5056.9  413.32  5061.9  413.14  5071.4  413.86  5081.5  415.31  5101.5  415.74
  5121.6  415.70  5131.6  415.98  5171.7  417.93  5181.0  418.77  5186.0  418.28
  5191.8  418.81  5211.9  419.71  5231.9  419.94  5252.0  420.69  5271.7  420.77
#Mann=3,-1,0
  4740.7    0.05       0  4979.2    0.05       0  4983.2    0.05       0
Bank Sta=4979.2,4983.2
Exp/Cntr=0.3,0.1

Type RM Length L Ch R = 1,1722,151,151,151
BEGIN DESCRIPTION:
Lacy 159 761
END DESCRIPTION:
XS GIS Cut Line= 3
      2724630.48      6843765.90      2724376.48      6843764.33
      2724074.32      6843759.42
#Sta/Elev= 30
  4746.0  415.39  4800.5  415.48  4810.5  415.28  4820.5  414.75  4870.5  413.13
  4890.5  412.27  4900.5  412.18  4910.5  412.59  4920.5  411.53  4930.5  411.23
  4950.5  410.15  4970.5  409.42  4980.5  409.33  4990.5  409.65  4997.7  408.41
  5002.7  408.41  5008.5  407.36  5008.7  406.86  5012.2  406.86  5012.5  407.36
  5020.5  407.71  5030.5  409.95  5040.5  410.76  5050.5  410.17  5070.5  410.29
  5080.5  410.55  5110.5  411.44  5240.5  416.57  5270.5  417.48  5302.2  417.99
#Mann=3,-1,0
  4746.0    0.05       0  5008.5    0.04       0  5012.5    0.05       0
Bank Sta=5008.5,5012.5
Exp/Cntr=0.3,0.1

Type RM Length L Ch R = 1,1571,210,210,210
BEGIN DESCRIPTION:
Lacy 159 760
END DESCRIPTION:
XS GIS Cut Line= 3
      2724562.61      6843608.45      2724327.41      6843629.07
      2724020.42      6843656.35
#Sta/Elev= 30
  4763.9  412.99  4790.6  412.68  4820.7  411.74  4830.8  411.96  4840.8  411.82
  4848.1  410.87  4860.9  410.00  4870.9  410.08  4881.0  409.88  4901.0  409.11
  4941.2  408.21  4965.6  407.88  4971.3  407.91  4981.3  408.33  4996.2  405.62
  4996.4  405.12  4999.9  405.12  5000.2  405.62  5003.2  405.62  5011.5  406.21
  5031.5  408.68  5041.6  408.89  5051.6  408.46  5061.7  408.52  5162.0  411.17
  5222.3  413.31  5252.4  413.74  5300.9  414.07  5305.9  414.57  5308.2  414.54
#Mann=3,-1,0
  4763.9    0.05       0  4996.2    0.04       0  5000.2    0.05       0
Bank Sta=4996.2,5000.2
Exp/Cntr=0.3,0.1

Type RM Length L Ch R = 1,1361,172,172,172
BEGIN DESCRIPTION:
Lacy 159 759
END DESCRIPTION:
XS GIS Cut Line= 3
      2724512.90      6843453.60      2724228.50      6843454.96
      2723939.91      6843545.63
#Sta/Elev= 30
  4715.6  409.76  4752.5  409.73  4872.5  407.34  4882.5  406.91  4902.5  407.05
  4922.5  405.65  4942.5  404.91  4962.5  405.08  4972.5  405.86  4982.5  405.53
  4990.5  402.93  4990.8  402.43  4994.3  402.43  4994.5  402.93  4998.8  404.11
  5005.7  404.53  5013.1  404.72  5023.6  403.81  5032.8  405.09  5038.1  405.08
  5044.6  406.87  5065.2  406.44  5102.9  408.15  5167.7  409.66  5172.9  410.10
  5200.1  410.51  5212.3  411.13  5222.7  410.85  5254.2  411.35  5302.5  411.01
#Mann=3,-1,0
  4715.6    0.05       0  4990.5    0.04       0  4994.5    0.05       0
Bank Sta=4990.5,4994.5
Exp/Cntr=0.3,0.1

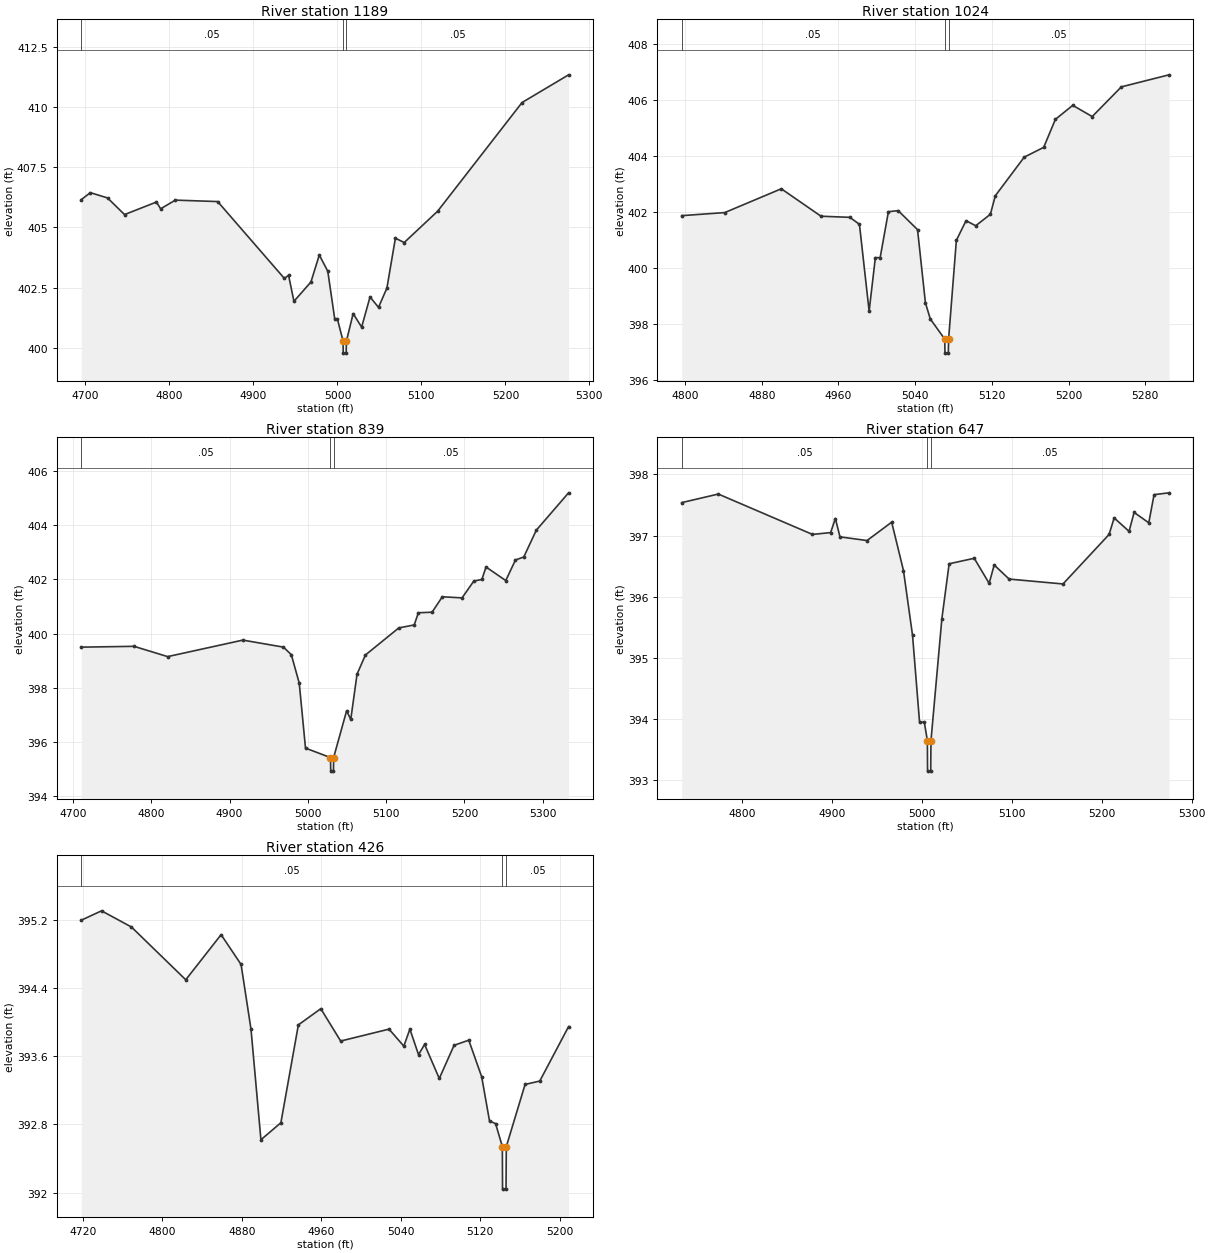
Type RM Length L Ch R = 1,1189,165,165,165
BEGIN DESCRIPTION:
Lacy 159 758
END DESCRIPTION:
XS GIS Cut Line= 3
      2724477.02      6843338.03      2724174.63      6843298.24
      2723900.91      6843326.75
#Sta/Elev= 30
  4695.0  406.15  4705.8  406.44  4726.3  406.22  4746.5  405.53  4784.5  406.05
  4789.5  405.77  4807.0  406.13  4857.4  406.07  4936.8  402.88  4941.8  403.01
  4948.2  401.93  4968.4  402.73  4978.4  403.85  4988.5  403.18  4996.8  401.19
  5000.0  401.19  5006.7  400.28  5006.9  399.78  5010.4  399.78  5010.7  400.28
  5018.7  401.42  5028.8  400.86  5038.8  402.11  5048.9  401.68  5058.9  402.48
  5069.0  404.55  5079.5  404.37  5119.3  405.67  5219.8  410.18  5275.2  411.33
#Mann=3,-1,0
  4695.0    0.05       0  5006.7    0.04       0  5010.7    0.05       0
Bank Sta=5006.7,5010.7
Exp/Cntr=0.3,0.1

Type RM Length L Ch R = 1,1024,185,185,185
BEGIN DESCRIPTION:
Lacy 159 757
END DESCRIPTION:
XS GIS Cut Line= 3
      2724370.72      6843175.37      2724167.99      6843157.67
      2723866.85      6843204.76
#Sta/Elev= 30
  4796.5  401.88  4841.4  401.99  4900.4  402.84  4941.8  401.86  4971.9  401.82
  4981.9  401.57  4992.0  398.47  4998.5  400.38  5003.5  400.38  5012.1  402.02
  5022.3  402.06  5042.5  401.38  5050.7  398.77  5055.8  398.19  5070.9  397.47
  5071.1  396.97  5074.6  396.97  5074.9  397.47  5083.0  401.00  5093.1  401.70
  5103.2  401.52  5118.5  401.93  5123.6  402.59  5153.8  403.97  5174.1  404.32
  5186.3  405.32  5204.4  405.82  5224.7  405.42  5255.1  406.48  5304.8  406.91
#Mann=3,-1,0
  4796.5    0.05       0  5070.9    0.04       0  5074.9    0.05       0
Bank Sta=5070.9,5074.9
Exp/Cntr=0.3,0.1

Type RM Length L Ch R = 1,839,192,192,192
BEGIN DESCRIPTION:
Lacy 159 756
END DESCRIPTION:
XS GIS Cut Line= 3
      2724362.92      6843036.64      2724075.03      6843008.16
      2723762.28      6843122.23
#Sta/Elev= 30
  4710.7  399.50  4778.0  399.53  4821.0  399.15  4917.0  399.76  4968.9  399.50
  4978.9  399.22  4989.0  398.17  4997.0  395.77  5028.9  395.42  5029.2  394.92
  5032.7  394.92  5032.9  395.42  5049.5  397.15  5054.8  396.83  5062.8  398.50
  5073.5  399.21  5116.1  400.21  5135.8  400.32  5141.1  400.77  5158.6  400.79
  5171.7  401.36  5196.9  401.32  5211.9  401.94  5222.2  402.00  5227.5  402.46
  5252.7  401.96  5265.1  402.72  5275.7  402.83  5291.7  403.82  5332.9  405.20
#Mann=3,-1,0
  4710.7    0.05       0  5028.9    0.04       0  5032.9    0.05       0
Bank Sta=5028.9,5032.9
Exp/Cntr=0.3,0.1

Type RM Length L Ch R = 1,647,221,221,221
BEGIN DESCRIPTION:
Lacy 159 755
END DESCRIPTION:
XS GIS Cut Line= 3
      2724289.63      6842872.58      2724025.77      6842831.09
      2723780.96      6842955.93
#Sta/Elev= 30
  4732.9  397.54  4773.6  397.68  4878.3  397.02  4898.5  397.05  4903.8  397.28
  4908.9  396.98  4939.0  396.92  4966.4  397.22  4979.5  396.43  4989.6  395.37
  4997.4  393.95  5002.7  393.95  5006.1  393.65  5006.3  393.15  5009.8  393.15
  5010.1  393.65  5022.2  395.64  5030.3  396.54  5058.2  396.63  5074.8  396.22
  5080.4  396.52  5097.0  396.29  5156.9  396.21  5208.2  397.02  5213.8  397.29
  5230.4  397.07  5236.0  397.38  5252.3  397.21  5258.2  397.67  5274.8  397.70
#Mann=3,-1,0
  4732.9    0.05       0  5006.1    0.04       0  5010.1    0.05       0
Bank Sta=5006.1,5010.1
Exp/Cntr=0.3,0.1

Type RM Length L Ch R = 1,426,0,0,0
BEGIN DESCRIPTION:
Lacy 159 754
END DESCRIPTION:
XS GIS Cut Line= 3
      2724206.28      6842664.99      2723925.72      6842640.82
      2723754.26      6842760.50
#Sta/Elev= 30
  4718.4  395.20  4738.8  395.31  4768.9  395.12  4823.6  394.50  4859.2  395.03
  4879.3  394.68  4889.3  393.92  4899.3  392.62  4919.4  392.82  4937.0  393.97
  4959.6  394.16  4979.6  393.78  5028.3  393.92  5043.2  393.72  5049.3  393.92
  5058.0  393.62  5064.1  393.74  5078.9  393.34  5093.8  393.73  5108.6  393.79
  5121.6  393.36  5129.5  392.84  5135.6  392.81  5142.4  392.54  5142.6  392.04
  5146.1  392.04  5146.4  392.54  5165.3  393.27  5180.1  393.31  5209.1  393.95
#Mann=3,-1,0
  4718.4    0.05       0  5142.4    0.04       0  5146.4    0.05       0
Bank Sta=5142.4,5146.4
Exp/Cntr=0.3,0.1

Chan Stop Cuts=-1