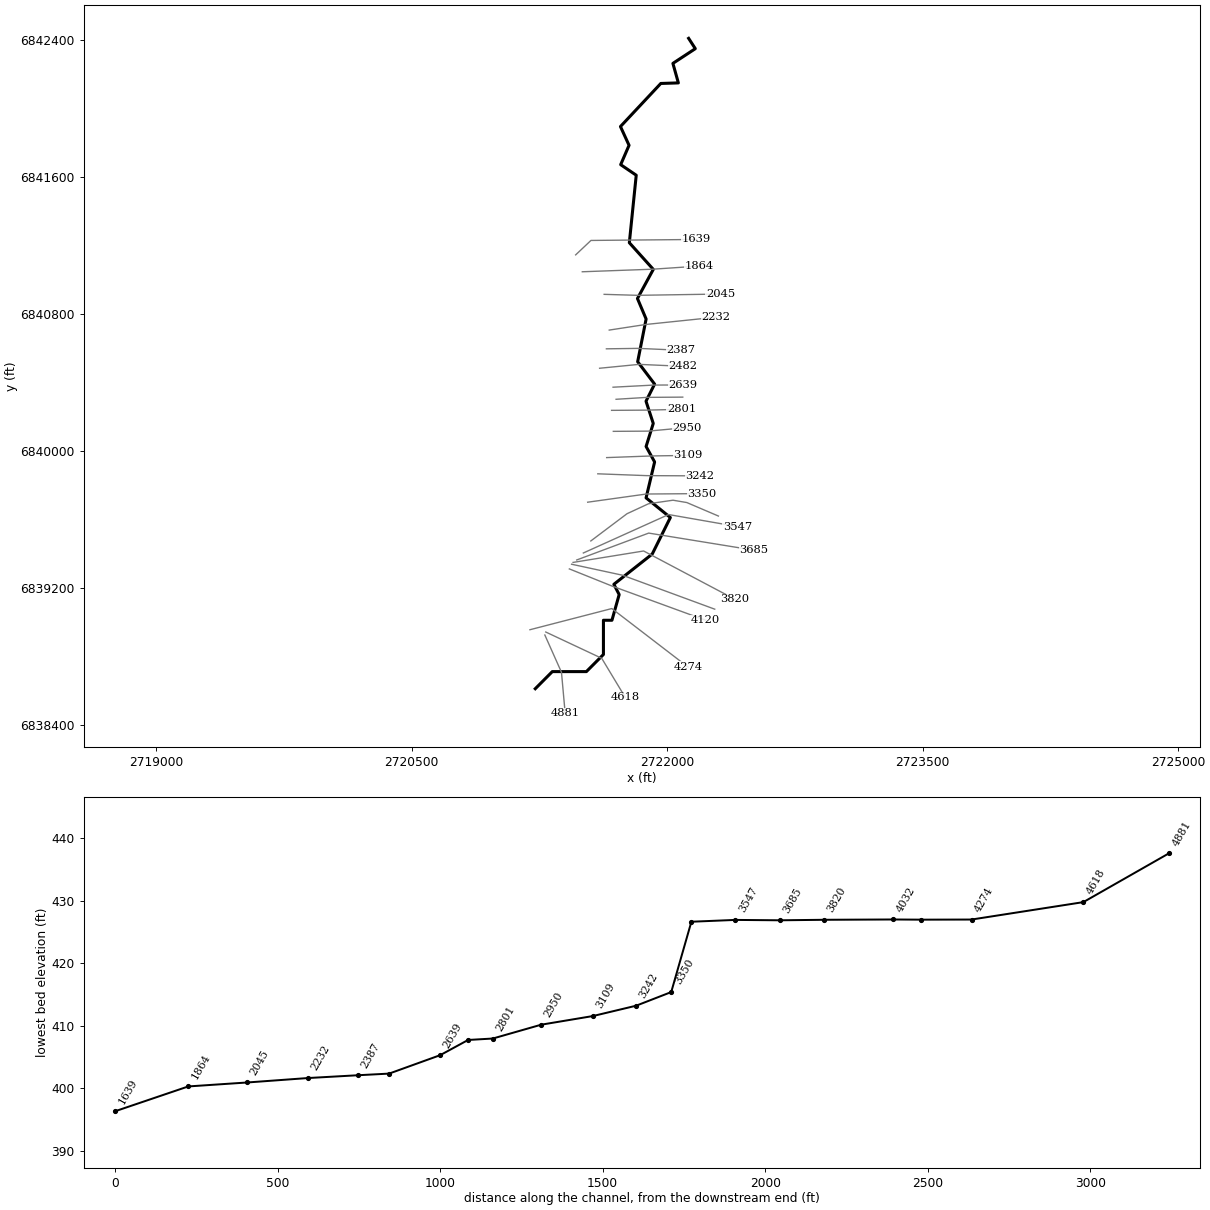
--- Lacy 160.prj (project) ---

Proj Title=Lacy 160 Base Level Engineering
Current Plan=p01
Default Exp/Contr=0.3,0.1
English Units
Geom File=g01
Flow File=f01
Plan File=p01
BEGIN DESCRIPTION:
Lacy 160
END DESCRIPTION:

--- Lacy 160.p01 (plan) ---

Plan Title=Multiple Run
Short Identifier=Multiple
Geom File=g01
Flow File=f01
Subcritical Flow
K Sum by GR= 0
Std Step Tol= 0.01
Critical Tol= 0.01
Num of Std Step Trials= 20
Max Error Tol= 0.3
Flow Tol Ratio= 0.001
Split Flow NTrial= 30
Split Flow Tol= 0.02
Split Flow Ratio= 0.02
Log Output Level= 0
Friction Slope Method= 1
Unsteady Friction Slope Method= 2
Unsteady Bridges Friction Slope Method= 1
Parabolic Critical Depth
Global Vel Dist=  1 , 1 , 1
Global Log Level= 0
CheckData=True
Encroach Param= -1, 0, 0, 0
BEGIN DESCRIPTION:
Multiple Run
END DESCRIPTION:

--- Lacy 160.f01 (steady flow) ---

Flow Title=Multiple
Number of Profiles=7
Profile Names=10-year,25-year,50-year,1pct_min,100-year,1pct_plu,500-year
River Rch & RM= Lacy 160,Reach-1,4881
     218     274     316     182     363     725     477
Boundary for River Rch & Prof#=Lacy 160,Reach-1,1
Up Type=0
Dn Type=3
Dn Slope=0.005
Boundary for River Rch & Prof#=Lacy 160,Reach-1,2
Up Type=0
Dn Type=3
Dn Slope=0.005
Boundary for River Rch & Prof#=Lacy 160,Reach-1,3
Up Type=0
Dn Type=3
Dn Slope=0.005
Boundary for River Rch & Prof#=Lacy 160,Reach-1,4
Up Type=0
Dn Type=3
Dn Slope=0.005
Boundary for River Rch & Prof#=Lacy 160,Reach-1,5
Up Type=0
Dn Type=3
Dn Slope=0.005
Boundary for River Rch & Prof#=Lacy 160,Reach-1,6
Up Type=0
Dn Type=3
Dn Slope=0.005
Boundary for River Rch & Prof#=Lacy 160,Reach-1,7
Up Type=0
Dn Type=3
Dn Slope=0.005

--- Lacy 160.g01 (geometry) ---

Geom Title=Existing Conditions

River Reach=Lacy 160,Reach-1
Reach XY= 30
      2721226.00      6838611.00      2721326.00      6838711.00
      2721526.00      6838711.00      2721626.00      6838811.00
      2721626.00      6839011.00      2721676.00      6839011.00
      2721718.42      6839161.07      2721687.22      6839221.02
      2721912.39      6839397.76      2722018.80      6839611.30
      2721876.31      6839726.04      2721926.40      6839936.00
      2721876.40      6840026.27      2721918.43      6840161.00
      2721875.93      6840290.90      2721926.39      6840390.87
      2721826.94      6840521.48      2721876.50      6840771.17
      2721825.71      6840890.83      2721918.71      6841061.09
      2721778.06      6841216.85      2721818.51      6841611.21
      2721727.22      6841673.01      2721776.38      6841785.99
      2721725.96      6841895.66      2721962.67      6842147.35
      2722065.79      6842150.62      2722033.72      6842264.65
      2722165.28      6842350.59      2722126.00      6842411.00

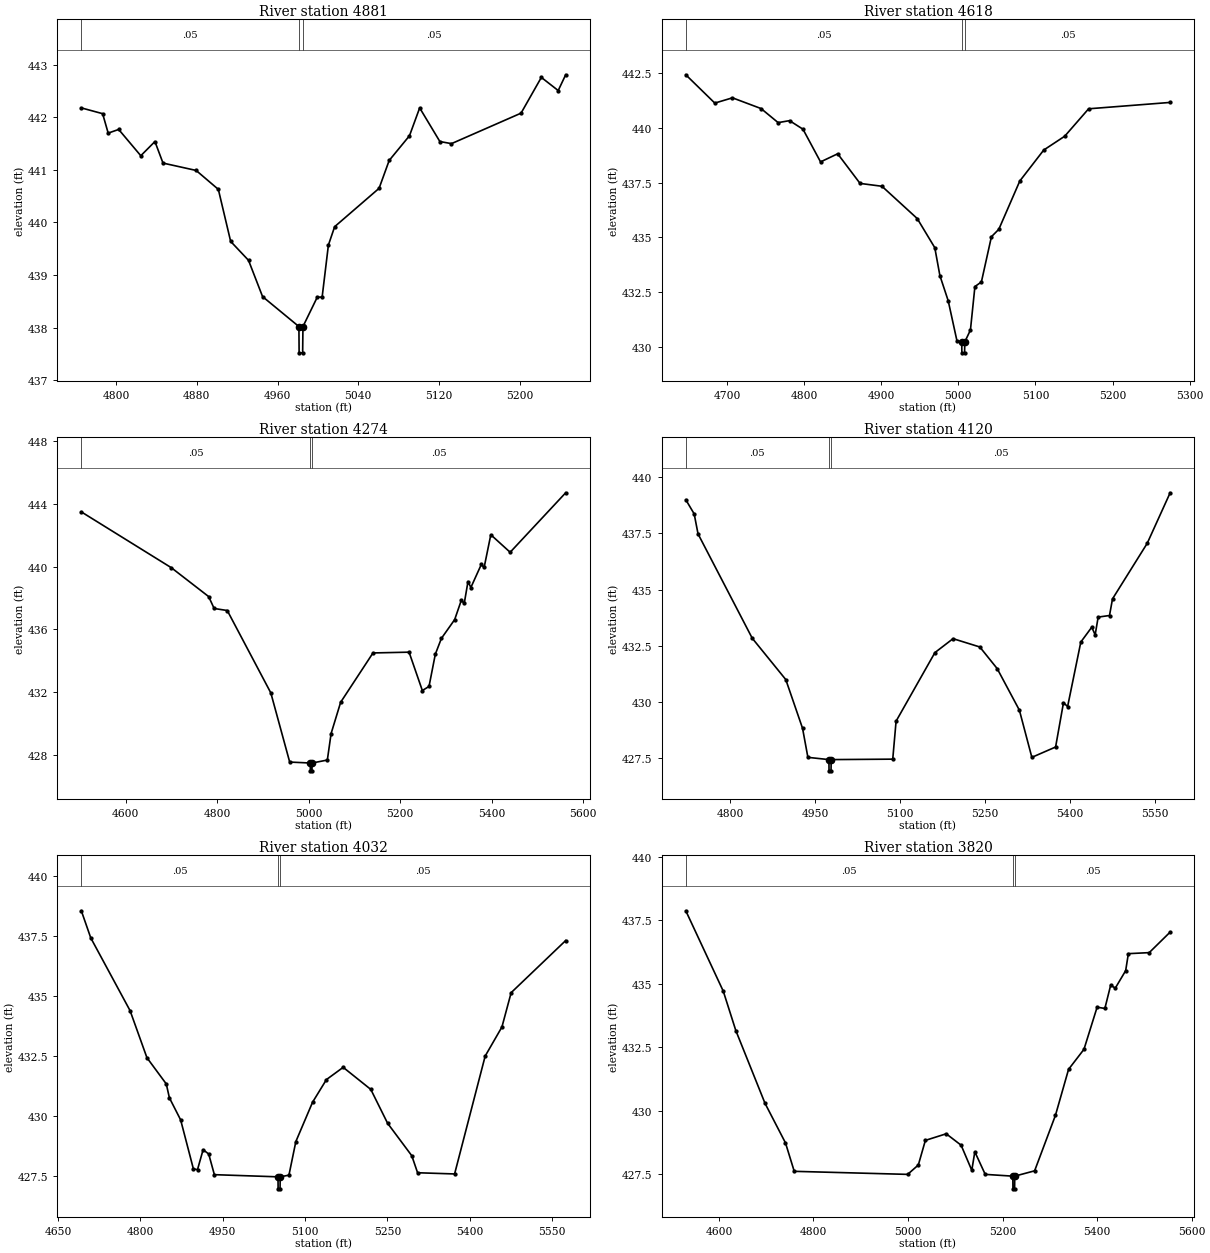
Type RM Length L Ch R = 1,4881,263,263,263
BEGIN DESCRIPTION:
Lacy 160 3441
END DESCRIPTION:
XS GIS Cut Line= 3
      2721282.17      6838924.79      2721379.78      6838707.14
      2721401.51      6838466.95
#Sta/Elev= 30
  4765.7  442.18  4786.8  442.07  4792.3  441.70  4802.7  441.77  4824.6  441.27
  4838.6  441.54  4846.6  441.13  4879.4  440.99  4901.4  440.63  4913.6  439.64
  4931.3  439.28  4945.2  438.59  4981.2  438.02  4981.4  437.52  4984.9  437.52
  4985.2  438.02  4999.4  438.58  5004.2  438.58  5010.4  439.57  5016.6  439.92
  5060.6  440.65  5070.6  441.18  5090.7  441.65  5100.8  442.18  5120.8  441.54
  5132.3  441.50  5201.2  442.08  5221.3  442.76  5238.0  442.51  5245.4  442.81
#Mann=3,-1,0
  4765.7    0.05       0  4981.2    0.04       0  4985.2    0.05       0
Bank Sta=4981.2,4985.2
Exp/Cntr=0.3,0.1

Type RM Length L Ch R = 1,4618,344,344,344
BEGIN DESCRIPTION:
Lacy 160 3440
END DESCRIPTION:
XS GIS Cut Line= 3
      2721287.60      6838942.27      2721615.88      6838788.82
      2721753.39      6838561.67
#Sta/Elev= 30
  4646.7  442.41  4684.3  441.12  4707.2  441.36  4744.3  440.87  4766.4  440.23
  4781.2  440.32  4798.6  439.93  4821.4  438.44  4843.6  438.81  4872.6  437.46
  4901.0  437.33  4946.7  435.86  4969.5  434.53  4976.1  433.26  4986.9  432.11
  4998.2  430.29  5004.4  430.24  5004.6  429.74  5008.1  429.74  5008.4  430.24
  5015.7  430.78  5021.5  432.76  5029.9  432.97  5042.9  435.03  5052.5  435.37
  5079.7  437.57  5110.7  438.98  5137.9  439.61  5168.9  440.86  5274.6  441.15
#Mann=3,-1,0
  4646.7    0.05       0  5004.4    0.04       0  5008.4    0.05       0
Bank Sta=5004.4,5008.4
Exp/Cntr=0.3,0.1

Type RM Length L Ch R = 1,4274,154,154,154
BEGIN DESCRIPTION:
Lacy 160 3439
END DESCRIPTION:
XS GIS Cut Line= 3
      2721194.78      6838955.68      2721675.24      6839079.41
      2722122.49      6838737.67
#Sta/Elev= 30
  4502.7  443.50  4699.7  439.93  4781.1  438.09  4793.1  437.33  4821.8  437.20
  4917.0  431.94  4958.3  427.52  5003.3  427.46  5003.5  426.96  5007.0  426.96
  5007.3  427.46  5040.6  427.65  5048.8  429.34  5069.7  431.34  5140.4  434.49
  5219.3  434.54  5248.3  432.09  5262.9  432.35  5276.7  434.41  5290.0  435.42
  5319.0  436.62  5333.6  437.86  5339.9  437.65  5348.1  439.05  5354.4  438.67
  5377.2  440.14  5383.4  439.95  5398.0  442.04  5440.3  440.92  5561.7  444.72
#Mann=3,-1,0
  4502.7    0.05       0  5003.3    0.04       0  5007.3    0.05       0
Bank Sta=5003.3,5007.3
Exp/Cntr=0.3,0.1

Type RM Length L Ch R = 1,4120,88,88,88
BEGIN DESCRIPTION:
Lacy 160 82
END DESCRIPTION:
XS GIS Cut Line= 3
      2721425.97      6839311.01      2721676.00      6839211.00
      2722225.98      6839011.01
#Sta/Elev= 30
  4721.7  439.00  4736.5  438.37  4743.3  437.48  4838.9  432.84  4898.1  431.00
  4927.7  428.83  4937.1  427.54  4974.2  427.44  4974.4  426.94  4977.9  426.94
  4978.2  427.44  5086.8  427.46  5092.7  429.15  5161.2  432.20  5193.2  432.82
  5240.4  432.45  5271.0  431.49  5310.2  429.64  5332.2  427.54  5374.1  428.00
  5388.0  429.97  5395.3  429.80  5418.6  432.67  5437.9  433.33  5443.9  432.99
  5449.2  433.78  5469.2  433.85  5474.5  434.59  5535.7  437.06  5576.2  439.31
#Mann=3,-1,0
  4721.7    0.05       0  4974.2    0.04       0  4978.2    0.05       0
Bank Sta=4974.2,4978.2
Exp/Cntr=0.3,0.1

Type RM Length L Ch R = 1,4032,212,212,212
BEGIN DESCRIPTION:
Lacy 160 744
END DESCRIPTION:
XS GIS Cut Line= 3
      2721439.14      6839338.37      2721737.38      6839274.29
      2722279.22      6839075.80
#Sta/Elev= 30
  4692.6  438.55  4709.8  437.42  4781.4  434.39  4812.1  432.43  4847.3  431.34
  4853.0  430.76  4873.5  429.84  4896.7  427.80  4904.2  427.77  4914.4  428.60
  4924.6  428.42  4934.9  427.56  5050.8  427.47  5051.0  426.97  5054.5  426.97
  5054.8  427.47  5070.7  427.54  5083.3  428.94  5113.8  430.58  5139.0  431.52
  5169.5  432.03  5219.8  431.11  5250.4  429.70  5294.4  428.35  5305.0  427.64
  5372.4  427.59  5428.1  432.50  5458.6  433.71  5475.4  435.14  5574.7  437.31
#Mann=3,-1,0
  4692.6    0.05       0  5050.8    0.04       0  5054.8    0.05       0
Bank Sta=5050.8,5054.8
Exp/Cntr=0.3,0.1

Type RM Length L Ch R = 1,3820,135,135,135
BEGIN DESCRIPTION:
Lacy 160 743
END DESCRIPTION:
XS GIS Cut Line= 3
      2721447.74      6839348.96      2721861.91      6839415.73
      2722397.30      6839133.80
#Sta/Elev= 30
  4529.9  437.88  4609.2  434.71  4635.7  433.16  4697.5  430.29  4740.8  428.73
  4759.3  427.61  4999.2  427.49  5021.8  427.86  5036.7  428.83  5080.8  429.09
  5112.3  428.64  5134.9  427.65  5141.3  428.38  5163.3  427.49  5221.7  427.42
  5222.0  426.92  5225.5  426.92  5225.7  427.42  5267.8  427.63  5311.9  429.82
  5339.6  431.63  5372.2  432.42  5400.0  434.08  5416.4  434.03  5428.7  434.95
  5438.4  434.83  5460.4  435.52  5466.1  436.19  5510.2  436.23  5554.5  437.04
#Mann=3,-1,0
  4529.9    0.05       0  5221.7    0.03       0  5225.7    0.05       0
Bank Sta=5221.7,5225.7
Exp/Cntr=0.3,0.1

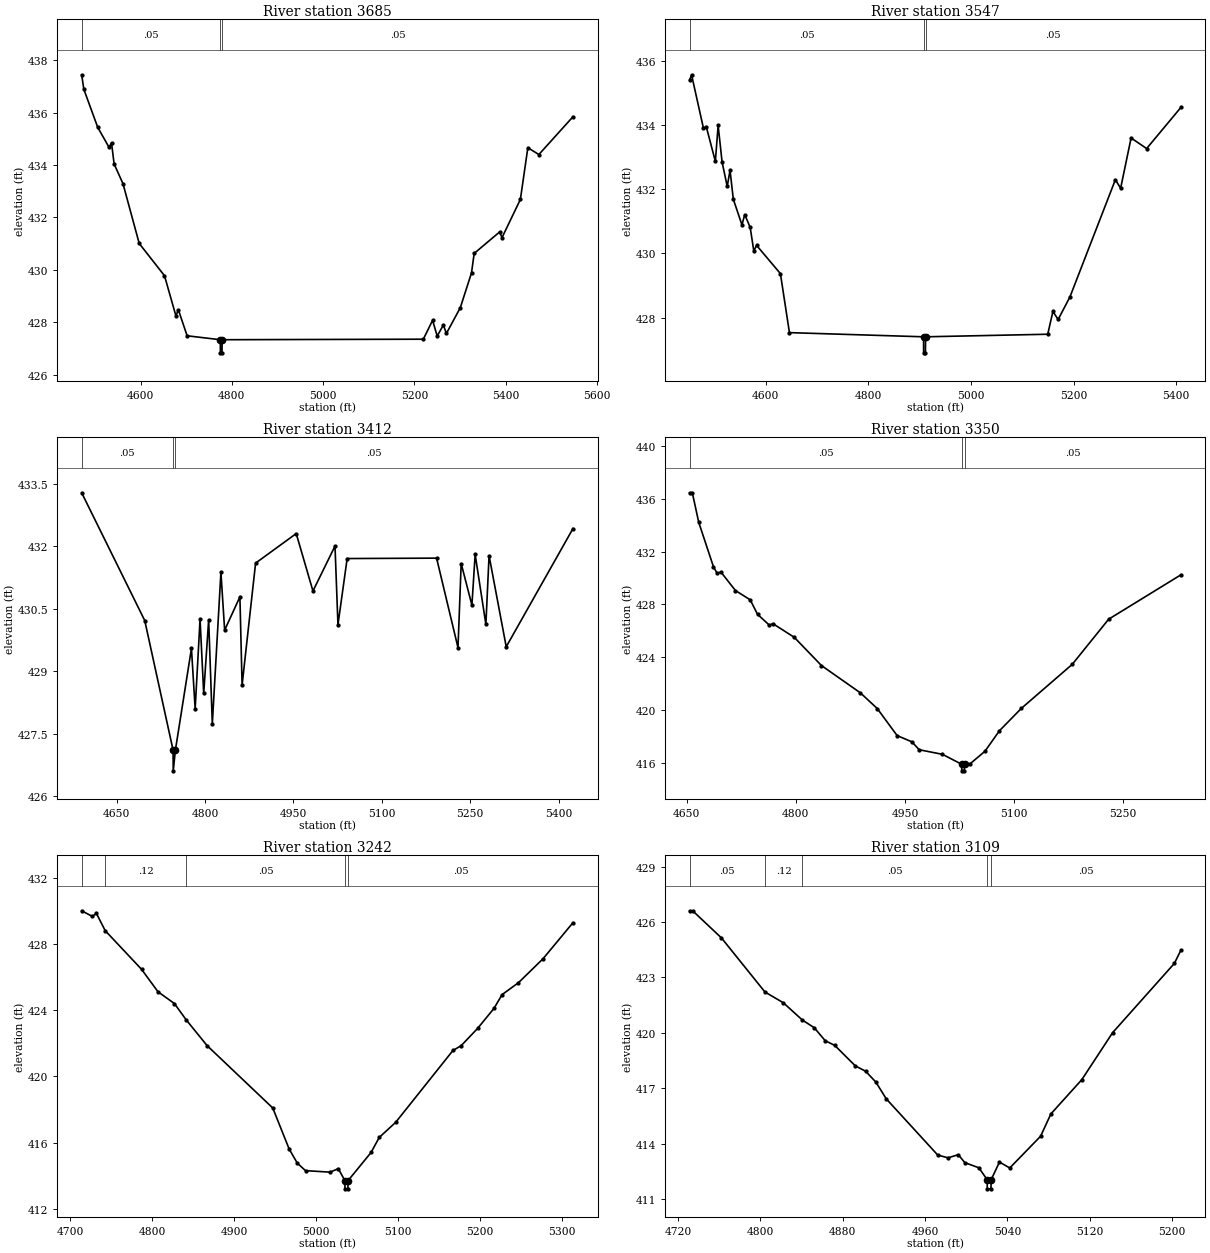
Type RM Length L Ch R = 1,3685,138,138,138
BEGIN DESCRIPTION:
Lacy 160 742
END DESCRIPTION:
XS GIS Cut Line= 3
      2721469.37      6839363.30      2721891.80      6839520.33
      2722509.70      6839420.40
#Sta/Elev= 30
  4471.0  437.44  4475.7  436.89  4506.1  435.44  4531.1  434.67  4536.4  434.85
  4542.1  434.04  4561.5  433.29  4597.1  431.01  4652.5  429.78  4677.5  428.25
  4682.9  428.48  4702.1  427.49  4774.8  427.34  4775.0  426.84  4778.5  426.84
  4778.8  427.34  5219.7  427.36  5240.0  428.08  5250.1  427.48  5263.6  427.90
  5270.3  427.58  5300.7  428.56  5325.3  429.89  5331.1  430.63  5387.0  431.45
  5392.1  431.23  5432.4  432.69  5448.7  434.66  5472.9  434.40  5547.6  435.84
#Mann=3,-1,0
  4471.0    0.05       0  4774.8    0.03       0  4778.8    0.05       0
Bank Sta=4774.8,4778.8
Exp/Cntr=0.3,0.1

Type RM Length L Ch R = 1,3547,135,135,135
BEGIN DESCRIPTION:
Lacy 160 741
END DESCRIPTION:
XS GIS Cut Line= 3
      2721508.15      6839404.06      2722008.28      6839628.68
      2722411.67      6839558.55
#Sta/Elev= 30
  4451.5  435.40  4455.4  435.57  4478.6  433.90  4484.1  433.95  4501.8  432.87
  4507.2  433.99  4514.9  432.85  4524.9  432.09  4530.4  432.59  4536.8  431.69
  4553.6  430.89  4559.1  431.21  4569.7  430.81  4576.7  430.08  4582.2  430.25
  4628.6  429.37  4646.2  427.53  4907.6  427.40  4907.8  426.90  4911.3  426.90
  4911.6  427.40  5149.7  427.48  5159.8  428.19  5170.0  427.94  5192.9  428.64
  5281.6  432.30  5291.8  432.03  5312.2  433.60  5342.5  433.27  5409.2  434.55
#Mann=3,-1,0
  4451.5    0.05       0  4907.6    0.03       0  4911.6    0.05       0
Bank Sta=4907.6,4911.6
Exp/Cntr=0.3,0.1

Type RM Length L Ch R = 1,3412,62,62,62
BEGIN DESCRIPTION:
Lacy 160 735
END DESCRIPTION:
XS GIS Cut Line= 6
      2721552.02      6839474.32      2721764.30      6839633.40
      2721890.75      6839691.75      2722034.24      6839712.41
      2722115.36      6839698.71      2722300.83      6839619.89
#Sta/Elev= 30
  4590.9  433.29  4697.9  430.22  4745.9  427.11  4746.2  426.61  4749.9  427.11
  4777.1  429.55  4783.4  428.10  4791.7  430.25  4797.9  428.47  4806.3  430.24
  4812.5  427.74  4827.1  431.38  4833.4  429.99  4859.3  430.79  4863.0  428.67
  4885.9  431.60  4954.8  432.31  4983.2  430.93  5020.6  432.01  5025.6  430.12
  5041.2  431.71  5192.9  431.72  5229.2  429.57  5234.6  431.59  5252.8  430.59
  5258.3  431.81  5276.5  430.13  5281.9  431.78  5311.0  429.59  5424.2  432.43
#Mann=3,-1,0
  4590.9    0.05       0  4745.9    0.05       0  4749.9    0.05       0
Bank Sta=4745.9,4749.9
Exp/Cntr=0.3,0.1

Type RM Length L Ch R = 1,3350,108,108,108
BEGIN DESCRIPTION:
Lacy 160 734
END DESCRIPTION:
XS GIS Cut Line= 3
      2721533.53      6839700.77      2721877.68      6839748.60
      2722205.22      6839751.02
#Sta/Elev= 30
  4654.1  436.45  4657.9  436.45  4666.7  434.21  4686.9  430.85  4692.0  430.34
  4697.1  430.45  4717.2  429.04  4737.4  428.34  4747.5  427.24  4763.7  426.42
  4768.7  426.53  4797.9  425.50  4835.3  423.36  4888.8  421.29  4912.0  420.10
  4939.3  418.05  4959.5  417.58  4969.6  416.98  5001.6  416.63  5027.9  415.88
  5028.1  415.38  5031.6  415.38  5031.9  415.88  5039.9  415.93  5059.9  416.86
  5079.9  418.42  5109.9  420.11  5179.9  423.45  5229.9  426.87  5329.1  430.23
#Mann=3,-1,0
  4654.1    0.05       0  5027.9    0.05       0  5031.9    0.05       0
Bank Sta=5027.9,5031.9
Exp/Cntr=0.3,0.1

Type RM Length L Ch R = 1,3242,133,133,133
BEGIN DESCRIPTION:
Lacy 160 733
END DESCRIPTION:
XS GIS Cut Line= 3
      2721592.91      6839866.66      2721879.59      6839856.01
      2722192.51      6839854.67
#Sta/Elev= 30
  4713.9  430.02  4726.9  429.68  4731.9  429.86  4742.6  428.82  4787.0  426.48
  4807.1  425.12  4827.1  424.41  4841.7  423.41  4867.1  421.86  4947.2  418.09
  4967.2  415.61  4977.2  414.75  4987.2  414.30  5017.2  414.21  5027.2  414.42
  5035.2  413.70  5035.4  413.20  5038.9  413.20  5039.2  413.70  5067.2  415.40
  5077.2  416.31  5097.2  417.22  5167.2  421.57  5177.2  421.86  5197.2  422.90
  5217.2  424.11  5227.2  424.95  5247.2  425.67  5277.2  427.12  5313.7  429.30
#Mann=5,-1,0
  4713.9    0.05       0  4742.6    0.12       0  4841.7    0.05       0
  5035.2    0.05       0  5039.2    0.05       0
Bank Sta=5035.2,5039.2
Exp/Cntr=0.3,0.1

Type RM Length L Ch R = 1,3109,159,159,159
BEGIN DESCRIPTION:
Lacy 160 737
END DESCRIPTION:
XS GIS Cut Line= 3
      2721644.98      6839961.39      2721913.64      6839971.10
      2722122.28      6839974.23
#Sta/Elev= 30
  4731.1  426.61  4734.1  426.61  4762.1  425.14  4804.4  422.21  4822.2  421.63
  4840.8  420.69  4852.2  420.28  4863.0  419.57  4872.2  419.32  4892.2  418.21
  4902.2  417.92  4912.2  417.33  4922.2  416.43  4972.3  413.38  4982.3  413.23
  4992.3  413.40  4998.6  412.97  5012.3  412.69  5020.3  412.05  5020.5  411.55
  5024.0  411.55  5024.3  412.05  5032.3  413.00  5042.3  412.68  5072.3  414.40
  5082.3  415.61  5112.3  417.46  5142.3  420.01  5202.3  423.76  5208.6  424.47
#Mann=5,-1,0
  4731.1    0.05       0  4804.4    0.12       0  4840.8    0.05       0
  5020.3    0.04       0  5024.3    0.05       0
Bank Sta=5020.3,5024.3
Exp/Cntr=0.3,0.1

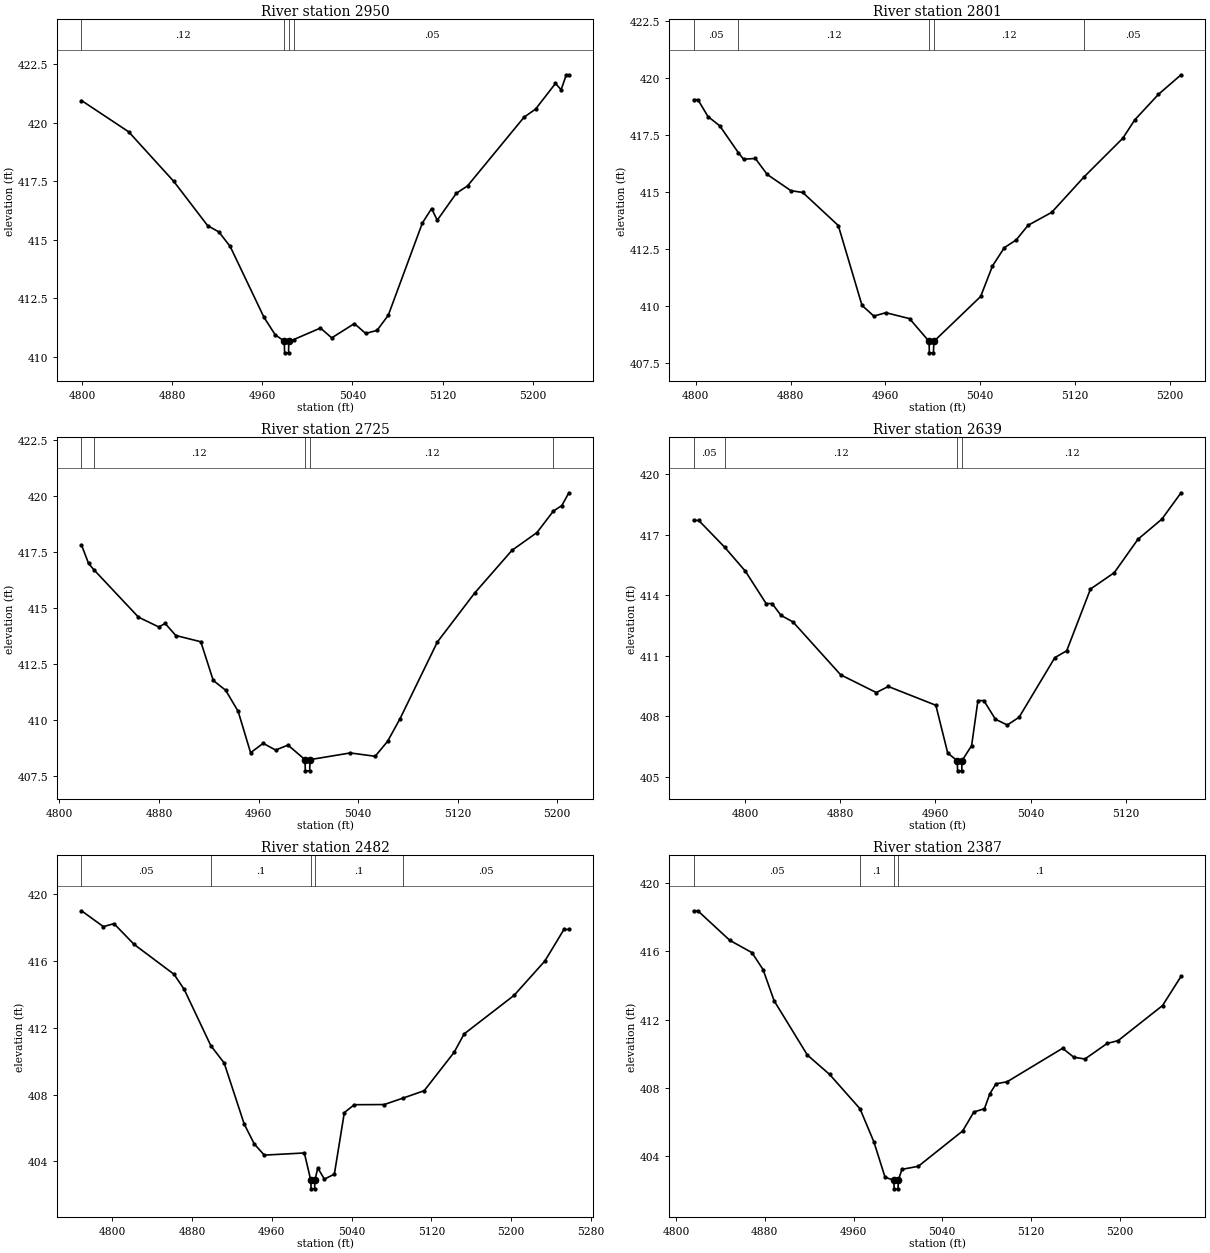
Type RM Length L Ch R = 1,2950,149,149,149
BEGIN DESCRIPTION:
Lacy 160 738
END DESCRIPTION:
XS GIS Cut Line= 3
      2721684.06      6840114.70      2721888.24      6840115.98
      2722115.50      6840136.85
#Sta/Elev= 30
  4799.6  420.96  4841.5  419.62  4881.5  417.50  4911.5  415.61  4921.5  415.34
  4931.5  414.72  4961.5  411.69  4971.5  410.94  4979.5  410.67  4979.8  410.17
  4983.3  410.17  4983.5  410.67  4988.0  410.74  5011.6  411.23  5021.6  410.81
  5041.7  411.42  5051.7  411.00  5061.8  411.13  5071.8  411.78  5102.0  415.72
  5110.2  416.34  5115.2  415.84  5132.1  416.99  5142.1  417.31  5192.3  420.25
  5202.4  420.59  5220.1  421.69  5225.1  421.42  5229.7  422.06  5232.0  422.06
#Mann=4,-1,0
  4799.6    0.12       0  4979.5    0.04       0  4983.5    0.12       0
  4988.0    0.05       0
Bank Sta=4979.5,4983.5
Exp/Cntr=0.3,0.1

Type RM Length L Ch R = 1,2801,76,76,76
BEGIN DESCRIPTION:
Lacy 160 740
END DESCRIPTION:
XS GIS Cut Line= 3
      2721673.85      6840237.41      2721878.04      6840238.70
      2722085.09      6840243.51
#Sta/Elev= 30
  4798.1  419.06  4801.7  419.06  4810.2  418.32  4820.2  417.91  4835.9  416.73
  4840.2  416.45  4850.2  416.48  4860.2  415.78  4880.2  415.07  4890.2  414.99
  4920.2  413.54  4940.2  410.04  4950.2  409.57  4960.3  409.72  4980.3  409.46
  4996.8  408.46  4997.0  407.96  5000.5  407.96  5000.8  408.46  5040.3  410.43
  5050.3  411.77  5060.3  412.57  5070.3  412.91  5080.3  413.55  5100.3  414.12
  5127.5  415.67  5160.3  417.37  5170.3  418.17  5190.3  419.29  5209.4  420.15
#Mann=5,-1,0
  4798.1    0.05       0  4835.9    0.12       0  4996.8    0.07       0
  5000.8    0.12       0  5127.5    0.05       0
Bank Sta=4996.8,5000.8
Exp/Cntr=0.3,0.1

Type RM Length L Ch R = 1,2725,86,86,86
BEGIN DESCRIPTION:
Lacy 160 739
END DESCRIPTION:
XS GIS Cut Line= 3
      2721700.31      6840302.10      2721882.18      6840313.26
      2722091.66      6840314.67
#Sta/Elev= 30
  4817.7  417.83  4823.4  417.00  4827.5  416.73  4863.5  414.60  4879.9  414.16
  4884.9  414.32  4893.5  413.78  4913.6  413.50  4923.6  411.77  4933.6  411.33
  4943.6  410.39  4953.6  408.54  4963.7  408.96  4973.7  408.66  4983.7  408.88
  4997.3  408.23  4997.6  407.73  5001.1  407.73  5001.3  408.23  5033.7  408.53
  5053.7  408.38  5063.7  409.05  5073.7  410.06  5103.7  413.49  5133.7  415.68
  5163.7  417.59  5183.7  418.38  5196.9  419.34  5203.7  419.59  5209.4  420.16
#Mann=5,-1,0
  4817.7    0.05       0  4827.5    0.12       0  4997.3    0.07       0
  5001.3    0.12       0  5196.9    0.05       0
Bank Sta=4997.3,5001.3
Exp/Cntr=0.3,0.1

Type RM Length L Ch R = 1,2639,157,157,157
BEGIN DESCRIPTION:
Lacy 160 732
END DESCRIPTION:
XS GIS Cut Line= 3
      2721682.46      6840372.69      2721921.65      6840385.18
      2722092.24      6840385.71
#Sta/Elev= 30
  4756.5  417.71  4760.8  417.71  4782.5  416.39  4800.1  415.19  4817.5  413.59
  4822.5  413.59  4830.1  413.00  4840.1  412.68  4880.2  410.06  4910.2  409.18
  4920.3  409.48  4960.3  408.55  4970.3  406.18  4978.3  405.80  4978.6  405.30
  4982.1  405.30  4982.3  405.80  4990.4  406.55  4995.7  408.78  5000.7  408.78
  5010.4  407.86  5020.4  407.57  5030.4  407.96  5060.4  410.91  5070.4  411.25
  5090.4  414.31  5110.4  415.12  5130.4  416.78  5150.4  417.77  5166.6  419.08
#Mann=4,-1,0
  4756.5    0.05       0  4782.5    0.12       0  4978.3    0.07       0
  4982.3    0.12       0
Bank Sta=4978.3,4982.3
Exp/Cntr=0.3,0.1

Type RM Length L Ch R = 1,2482,95,95,95
BEGIN DESCRIPTION:
Lacy 160 736
END DESCRIPTION:
XS GIS Cut Line= 3
      2721603.54      6840483.42      2721835.10      6840506.12
      2722090.98      6840494.75
#Sta/Elev= 30
  4769.1  419.02  4791.1  418.07  4801.7  418.25  4821.8  417.01  4862.0  415.21
  4872.1  414.31  4898.8  410.94  4912.2  409.90  4932.3  406.24  4942.4  405.05
  4952.4  404.38  4992.6  404.51  4999.1  402.86  4999.4  402.36  5002.9  402.36
  5003.1  402.86  5006.1  403.61  5012.7  402.94  5022.7  403.24  5032.7  406.93
  5042.7  407.40  5072.7  407.41  5091.7  407.80  5112.8  408.24  5142.8  410.54
  5152.8  411.64  5202.9  413.95  5233.8  416.01  5252.9  417.90  5257.9  417.90
#Mann=5,-1,0
  4769.1    0.05       0  4898.8     0.1       0  4999.1    0.07       0
  5003.1     0.1       0  5091.7    0.05       0
Bank Sta=4999.1,5003.1
Exp/Cntr=0.3,0.1

Type RM Length L Ch R = 1,2387,155,155,155
BEGIN DESCRIPTION:
Lacy 160 731
END DESCRIPTION:
XS GIS Cut Line= 3
      2721643.43      6840596.91      2721831.46      6840599.55
      2722082.66      6840588.19
#Sta/Elev= 30
  4815.8  418.38  4819.6  418.38  4848.4  416.65  4868.4  415.93  4878.4  414.94
  4888.4  413.11  4918.4  409.93  4938.4  408.80  4965.8  406.79  4978.4  404.84
  4988.4  402.78  4996.4  402.60  4996.6  402.10  5000.1  402.10  5000.4  402.60
  5003.6  403.24  5018.4  403.42  5058.4  405.49  5068.5  406.60  5078.0  406.79
  5083.0  407.68  5088.5  408.25  5098.5  408.37  5148.5  410.33  5158.5  409.81
  5168.6  409.70  5188.6  410.61  5198.6  410.78  5238.6  412.83  5255.3  414.54
#Mann=4,-1,0
  4815.8    0.05       0  4965.8     0.1       0  4996.4    0.07       0
  5000.4     0.1       0
Bank Sta=4996.4,5000.4
Exp/Cntr=0.3,0.1

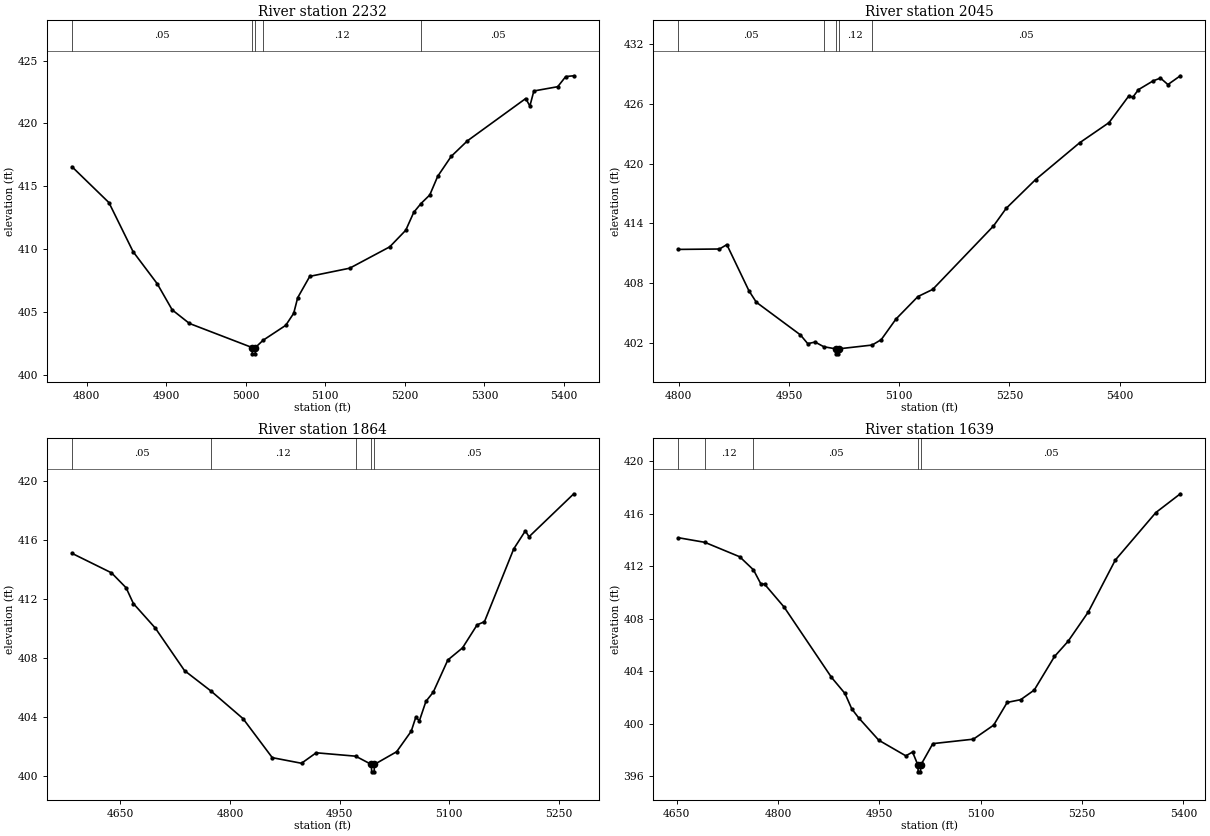
Type RM Length L Ch R = 1,2232,187,187,187
BEGIN DESCRIPTION:
Lacy 160 730
END DESCRIPTION:
XS GIS Cut Line= 4
      2721660.05      6840706.40      2721873.75      6840739.08
      2722155.14      6840768.13      2722286.07      6840781.65
#Sta/Elev= 30
  4781.6  416.55  4828.1  413.69  4858.4  409.79  4888.8  407.23  4907.6  405.15
  4929.2  404.07  5008.1  402.15  5008.4  401.65  5011.9  401.65  5012.1  402.15
  5021.8  402.73  5050.3  403.92  5060.3  404.88  5065.3  406.12  5080.5  407.82
  5130.7  408.47  5181.0  410.17  5201.1  411.49  5211.2  412.92  5220.3  413.62
  5231.3  414.30  5241.3  415.79  5258.2  417.37  5278.6  418.61  5351.9  421.98
  5357.1  421.38  5362.1  422.58  5392.1  422.92  5402.2  423.73  5412.3  423.79
#Mann=5,-1,0
  4781.6    0.05       0  5008.1    0.05       0  5012.1    0.05       0
  5021.8    0.12       0  5220.3    0.05       0
Bank Sta=5008.1,5012.1
Exp/Cntr=0.3,0.1

Type RM Length L Ch R = 1,2045,181,181,181
BEGIN DESCRIPTION:
Lacy 160 729
END DESCRIPTION:
XS GIS Cut Line= 4
      2721630.19      6840915.25      2721827.19      6840909.44
      2722056.28      6840913.03      2722312.95      6840917.06
#Sta/Elev= 30
  4799.7  411.40  4855.5  411.44  4865.5  411.88  4895.5  407.27  4905.6  406.11
  4965.6  402.84  4975.6  401.96  4985.6  402.12  4997.5  401.65  5013.6  401.44
  5013.8  400.94  5017.3  400.94  5017.6  401.44  5063.2  401.82  5075.6  402.36
  5095.6  404.42  5125.6  406.68  5145.6  407.39  5228.3  413.74  5245.6  415.51
  5285.6  418.39  5345.6  422.08  5385.6  424.10  5412.8  426.80  5417.8  426.63
  5425.6  427.40  5445.6  428.28  5455.6  428.56  5465.7  427.91  5482.6  428.79
#Mann=5,-1,0
  4799.7    0.05       0  4997.5    0.12       0  5013.6    0.07       0
  5017.6    0.12       0  5063.2    0.05       0
Bank Sta=5013.6,5017.6
Exp/Cntr=0.3,0.1

Type RM Length L Ch R = 1,1864,225,225,225
BEGIN DESCRIPTION:
Lacy 160 728
END DESCRIPTION:
XS GIS Cut Line= 3
      2721501.97      6841047.12      2721916.19      6841062.17
      2722187.98      6841080.38
#Sta/Elev= 30
  4583.7  415.10  4637.8  413.78  4657.8  412.77  4667.8  411.70  4697.8  410.04
  4737.8  407.16  4774.0  405.78  4817.9  403.91  4857.9  401.27  4897.9  400.89
  4918.0  401.60  4972.0  401.37  4993.6  400.81  4993.9  400.31  4997.4  400.31
  4997.6  400.81  5028.1  401.67  5048.1  403.06  5054.3  404.00  5059.3  403.77
  5068.2  405.08  5078.2  405.70  5098.2  407.88  5118.3  408.70  5138.3  410.26
  5148.3  410.47  5188.4  415.40  5204.3  416.62  5209.3  416.22  5270.6  419.13
#Mann=5,-1,0
  4583.7    0.05       0  4774.0    0.12       0  4972.0    0.05       0
  4993.6    0.05       0  4997.6    0.05       0
Bank Sta=4993.6,4997.6
Exp/Cntr=0.3,0.1

Type RM Length L Ch R = 1,1639,0,0,0
BEGIN DESCRIPTION:
Lacy 160 724
END DESCRIPTION:
XS GIS Cut Line= 3
      2721462.99      6841145.81      2721552.81      6841230.14
      2722172.18      6841235.89
#Sta/Elev= 30
  4652.9  414.19  4691.9  413.84  4743.5  412.74  4763.9  411.74  4774.9  410.66
  4780.2  410.66  4809.3  408.90  4879.3  403.55  4899.3  402.32  4909.3  401.15
  4919.3  400.48  4949.3  398.76  4989.3  397.57  4999.3  397.86  5007.3  396.85
  5007.5  396.35  5011.0  396.35  5011.3  396.85  5029.3  398.50  5089.3  398.84
  5119.3  399.91  5139.3  401.64  5159.3  401.85  5179.3  402.58  5209.3  405.14
  5229.3  406.29  5259.3  408.53  5299.3  412.49  5359.3  416.11  5395.5  417.54
#Mann=5,-1,0
  4652.9    0.05       0  4691.9    0.12       0  4763.9    0.05       0
  5007.3    0.03       0  5011.3    0.05       0
Bank Sta=5007.3,5011.3
Exp/Cntr=0.3,0.1

Chan Stop Cuts=-1