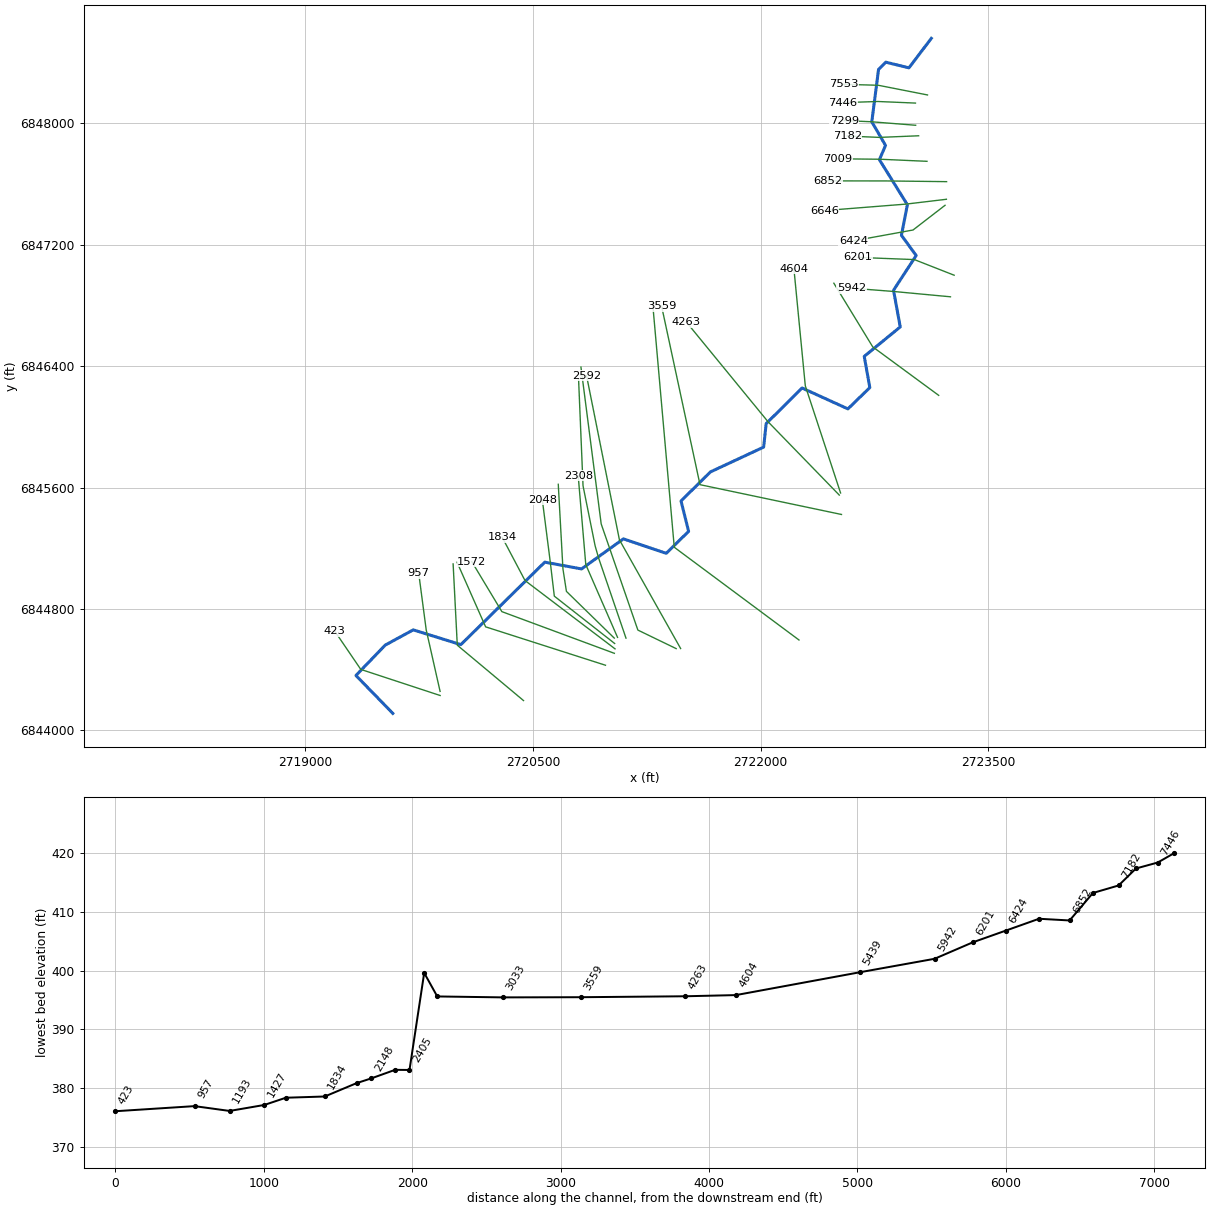
--- Lacy 161.prj (project) ---

Proj Title=Lacy 161 Base Level Engineering
Current Plan=p01
Default Exp/Contr=0.3,0.1
English Units
Geom File=g01
Flow File=f01
Plan File=p01
Y Axis Title=Elevation
X Axis Title(PF)=Main Channel Distance
X Axis Title(XS)=Station
BEGIN DESCRIPTION:
Lacy 161
END DESCRIPTION:
DSS Export Rating Curves= 0
DSS Export Rating Curve Sorted= 0
DSS Export Volume Flow Curves= 0
DXF OffsetX= 0
DXF OffsetY= 0
DXF ScaleX= 1
DXF ScaleY= 10

--- Lacy 161.p01 (plan) ---

Plan Title=Multiple Run
Short Identifier=Multiple
Geom File=g01
Flow File=f01
Subcritical Flow
K Sum by GR= 0
Std Step Tol= 0.01
Critical Tol= 0.01
Num of Std Step Trials= 20
Max Error Tol= 0.3
Flow Tol Ratio= 0.001
Split Flow NTrial= 30
Split Flow Tol= 0.02
Split Flow Ratio= 0.02
Log Output Level= 0
Friction Slope Method= 1
Unsteady Friction Slope Method= 2
Unsteady Bridges Friction Slope Method= 1
Parabolic Critical Depth
Global Vel Dist=  1 , 1 , 1
Global Log Level= 0
CheckData=True
Encroach Param= -1, 0, 0, 0
BEGIN DESCRIPTION:
Multiple Run
END DESCRIPTION:

--- Lacy 161.f01 (steady flow) ---

Flow Title=Multiple
Number of Profiles=7
Profile Names=10-year,25-year,50-year,1pct_min,100-year,1pct_plu,500-year
River Rch & RM= Lacy 161,Reach-1,7553
     178     221     252     144     287     573     370
River Rch & RM= Lacy 161,Reach-1,6201
     351     454     535     313     624    1245     849
River Rch & RM= Lacy 161,Reach-1,3033
     471     621     739     438     873    1742    1215
River Rch & RM= Lacy 161,Reach-1,423
     525     696     833     495     988    1971    1387
Boundary for River Rch & Prof#=Lacy 161,Reach-1,1
Up Type=0
Dn Type=3
Dn Slope=0.005
Boundary for River Rch & Prof#=Lacy 161,Reach-1,2
Up Type=0
Dn Type=3
Dn Slope=0.005
Boundary for River Rch & Prof#=Lacy 161,Reach-1,3
Up Type=0
Dn Type=3
Dn Slope=0.005
Boundary for River Rch & Prof#=Lacy 161,Reach-1,4
Up Type=0
Dn Type=3
Dn Slope=0.005
Boundary for River Rch & Prof#=Lacy 161,Reach-1,5
Up Type=0
Dn Type=3
Dn Slope=0.005
Boundary for River Rch & Prof#=Lacy 161,Reach-1,6
Up Type=0
Dn Type=3
Dn Slope=0.005
Boundary for River Rch & Prof#=Lacy 161,Reach-1,7
Up Type=0
Dn Type=3
Dn Slope=0.005

--- Lacy 161.g01 (geometry) ---

Geom Title=Existing Conditions
Program Version=4.10

River Reach=Lacy 161        ,Reach-1
Reach XY= 30
        2723126.        6848561.      2722978.43       6848366.4
      2722825.65      6848403.78      2722778.05      6848355.55
      2722733.53      6848010.99      2722824.16      6847854.88
      2722783.59      6847761.01      2722968.02      6847464.33
      2722929.08      6847262.64      2723026.07      6847129.12
      2722876.79       6846900.3      2722920.99      6846658.46
      2722683.79      6846464.42      2722720.55      6846258.55
       2722576.1      6846118.31      2722273.71      6846255.94
      2722037.24        6846021.      2722020.59      6845866.26
      2721669.94      6845702.86        2721476.        6845511.
        2721526.        6845311.      2721378.29      6845166.06
      2721096.16      6845261.33      2720820.07      6845063.23
      2720577.63      6845107.87      2720024.36      6844564.14
      2719710.81      6844661.53        2719526.        6844561.
      2719332.98      6844360.79        2719576.        6844111.

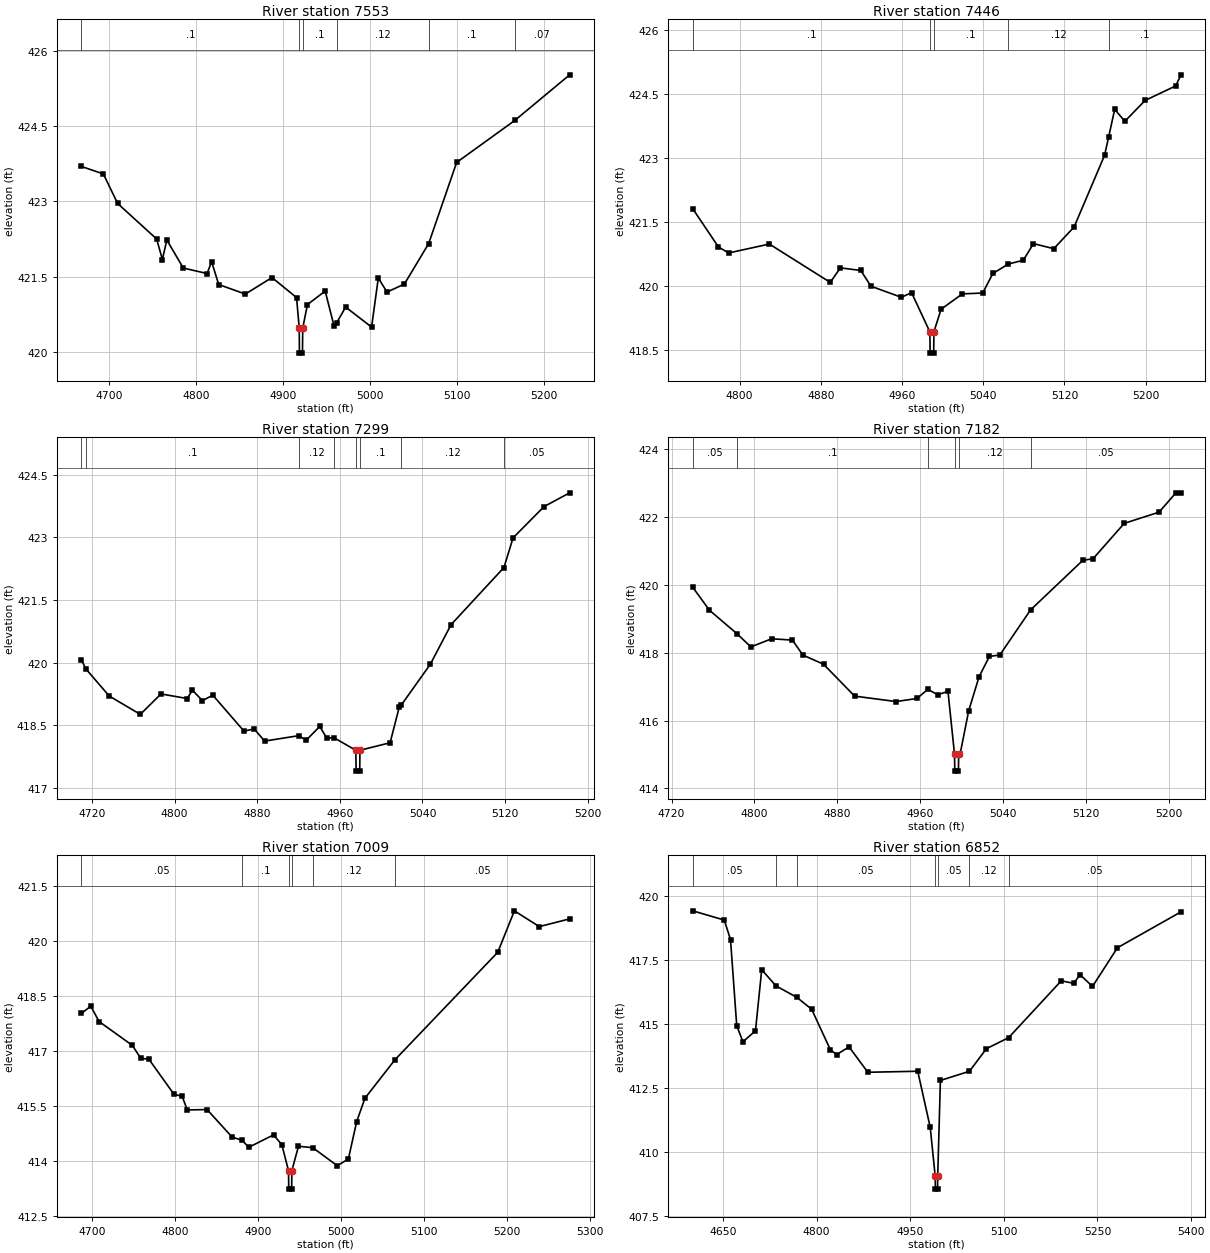
Type RM Length L Ch R = 1 ,7553    ,107,107,107
BEGIN DESCRIPTION:
Lacy 161 703
END DESCRIPTION:
XS GIS Cut Line= 3
      2723100.85      6848187.72      2722776.34      6848251.63
      2722546.27      6848257.94
#Sta/Elev= 30
  4668.5   423.7  4693.8  423.55  4710.2  422.96    4755  422.25  4761.6  421.84
  4766.7  422.23  4785.6  421.67    4813  421.56  4818.1   421.8  4826.3  421.34
  4856.9  421.15  4887.5  421.48  4915.7  421.08  4918.8  420.47    4919  419.97
  4922.5  419.97  4922.8  420.47  4928.2  420.94  4948.6  421.21  4958.8  420.51
  4961.6  420.57  4972.1  420.89  5001.9  420.49  5009.6  421.47  5019.6  421.19
  5039.6  421.35  5067.5  422.16  5099.6  423.78  5166.5  424.62  5229.4  425.53
#Mann= 6 ,-1 , 0
  4668.5      .1       0  4918.8     .07       0  4922.8      .1       0
  4961.6     .12       0  5067.5      .1       0  5166.5     .07       0
Bank Sta=4918.8,4922.8
XS Rating Curve= 0 ,0
Exp/Cntr=0.3,0.1

Type RM Length L Ch R = 1 ,7446    ,147,147,147
BEGIN DESCRIPTION:
Lacy 161 701
END DESCRIPTION:
XS GIS Cut Line= 3
      2723021.42       6848134.2      2722772.92      6848144.68
      2722540.77      6848136.95
#Sta/Elev= 30
  4753.8  421.81  4779.2  420.91  4789.3  420.77  4829.3  420.98  4889.3  420.08
  4899.3  420.42  4919.4  420.36  4929.4  419.99  4959.4  419.73  4969.4  419.84
  4987.4  418.92  4987.7  418.42  4991.2  418.42  4991.4  418.92  4998.5  419.45
  5019.4  419.81  5039.5  419.83  5049.5  420.29  5064.7  420.51  5079.5   420.6
  5089.5  420.99  5109.5  420.87  5129.5  421.38  5159.5  423.06  5163.6   423.5
  5169.5  424.14  5179.5  423.86  5199.5  424.35  5229.6  424.69  5234.8  424.95
#Mann= 5 ,-1 , 0
  4753.8      .1       0  4987.4     .07       0  4991.4      .1       0
  5064.7     .12       0  5163.6      .1       0
Bank Sta=4987.4,4991.4
XS Rating Curve= 0 ,0
Exp/Cntr=0.3,0.1

Type RM Length L Ch R = 1 ,7299    ,117,117,117
BEGIN DESCRIPTION:
Lacy 161 699
END DESCRIPTION:
XS GIS Cut Line= 3
      2723022.88      6847987.87      2722728.74      6848011.22
      2722551.26      6848018.71
#Sta/Elev= 30
  4709.8  420.07  4714.2  419.85  4736.8   419.2  4766.9  418.76  4786.9  419.25
  4812.3  419.14  4817.3  419.34    4827  419.09  4837.1  419.22  4867.2  418.36
  4877.2  418.41  4887.2  418.12  4920.3  418.25  4927.4  418.14  4940.6  418.47
  4947.4  418.19  4954.4   418.2  4975.5   417.9  4975.8   417.4  4979.3   417.4
  4979.5   417.9  5008.7  418.08  5017.6  418.94  5019.7  418.99  5047.6  419.96
  5067.7  420.91  5118.9  422.28  5127.7  422.99  5157.7  423.74  5182.5  424.07
#Mann= 8 ,-1 , 0
  4709.8     .05       0  4714.2      .1       0  4920.3     .12       0
  4954.4      .1       0  4975.5     .07       0  4979.5      .1       0
  5019.7     .12       0  5118.9     .05       0
Bank Sta=4975.5,4979.5
XS Rating Curve= 0 ,0
Exp/Cntr=0.3,0.1

Type RM Length L Ch R = 1 ,7182    ,173,173,173
BEGIN DESCRIPTION:
Lacy 161 698
END DESCRIPTION:
XS GIS Cut Line= 3
      2723042.18      6847918.62      2722784.34      6847907.97
      2722571.29      6847916.96
#Sta/Elev= 30
  4740.4  419.93  4756.6  419.25  4783.1  418.56  4796.6  418.17  4816.6  418.41
  4836.7  418.37  4846.7  417.93  4866.7  417.66  4896.7  416.72  4936.7  416.56
  4956.8  416.65  4967.4  416.92  4976.8  416.76  4986.8  416.86  4993.1  415.01
  4993.4  414.51  4996.9  414.51  4997.1  415.01  4998.5  415.01  5006.8  416.29
  5016.8  417.29  5026.8  417.89  5036.8  417.93  5066.5  419.26  5116.9  420.72
  5126.9  420.77  5156.9  421.81  5190.5  422.14  5206.8  422.71  5211.7  422.71
#Mann= 6 ,-1 , 0
  4740.4     .05       0  4783.1      .1       0  4967.4     .12       0
  4993.1     .07       0  4997.1     .12       0  5066.5     .05       0
Bank Sta=4993.1,4997.1
XS Rating Curve= 0 ,0
Exp/Cntr=0.3,0.1

Type RM Length L Ch R = 1 ,7009    ,157,157,157
BEGIN DESCRIPTION:
Lacy 161 697
END DESCRIPTION:
XS GIS Cut Line= 3
      2723097.39      6847750.31      2722787.69      6847764.01
      2722509.41      6847766.78
#Sta/Elev= 30
  4687.1  418.02  4698.5  418.22  4708.5   417.8  4748.6  417.15  4758.6   416.8
  4768.6  416.77  4798.6  415.82  4808.6  415.76  4814.7  415.39  4838.6   415.4
  4868.7  414.65    4881  414.56  4888.7  414.37  4918.7  414.71  4928.7  414.44
  4936.7  413.73    4937  413.23  4940.5  413.23  4940.7  413.73  4948.7   414.4
  4965.9  414.36  4995.4  413.87  5008.8  414.05  5018.8  415.07  5028.8  415.71
    5065  416.76  5188.8  419.69  5208.8  420.82  5238.8  420.39  5275.4   420.6
#Mann= 6 ,-1 , 0
  4687.1     .05       0    4881      .1       0  4936.7     .07       0
  4940.7      .1       0  4965.9     .12       0    5065     .05       0
Bank Sta=4936.7,4940.7
XS Rating Curve= 0 ,0
Exp/Cntr=0.3,0.1

Type RM Length L Ch R = 1 ,6852    ,206,206,206
BEGIN DESCRIPTION:
Lacy 161 696
END DESCRIPTION:
XS GIS Cut Line= 3
       2723226.6      6847616.25      2722828.46      6847620.92
      2722444.22      6847621.27
#Sta/Elev= 30
  4601.4  419.41    4652  419.05    4662  418.29    4672  414.92    4682   414.3
    4702  414.73    4712  417.11    4735  416.48  4768.5  416.03    4792  415.57
    4822  413.99    4832   413.8    4852   414.1    4882  413.11    4962  413.15
    4982  410.96    4990  409.05  4990.3  408.55  4993.8  408.55    4994  409.05
  4998.3  412.79  5044.9  413.15    5072  414.03  5107.6  414.46    5192  416.68
    5212  416.58    5222  416.92    5242  416.46    5282  417.97  5383.8  419.37
#Mann= 7 ,-1 , 0
  4601.4     .05       0    4735      .1       0  4768.5     .05       0
    4990     .04       0    4994     .05       0  5044.9     .12       0
  5107.6     .05       0
Bank Sta=4990,4994
XS Rating Curve= 0 ,0
Exp/Cntr=0.3,0.1

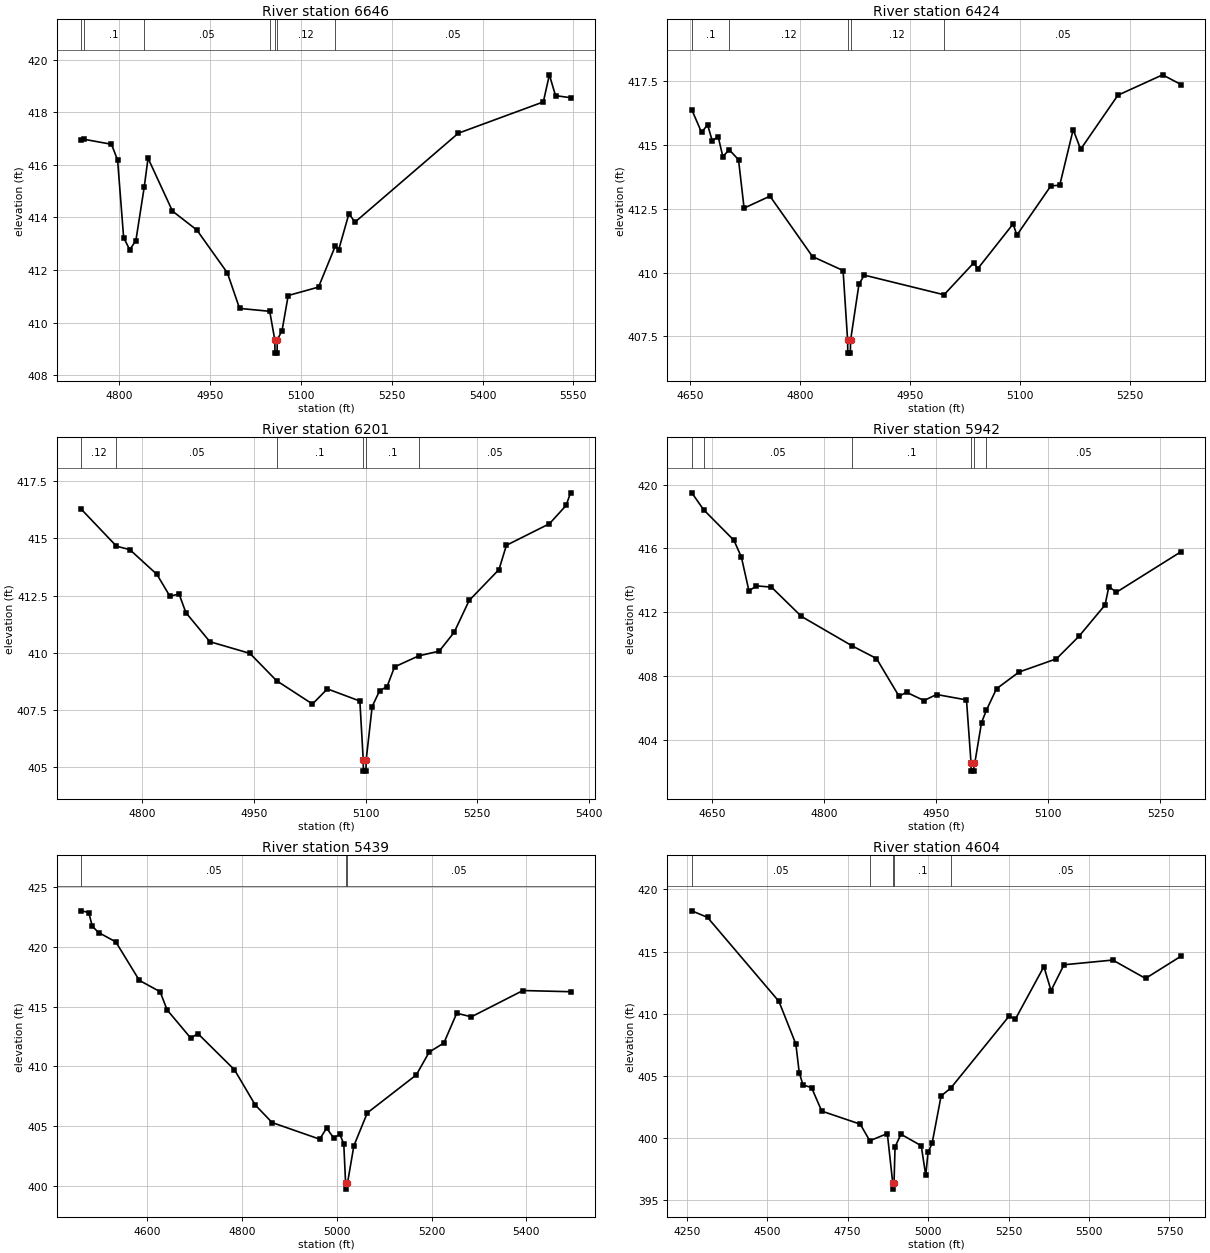
Type RM Length L Ch R = 1 ,6646    ,222,222,222
BEGIN DESCRIPTION:
Lacy 161 695
END DESCRIPTION:
XS GIS Cut Line= 3
      2723225.35      6847500.06      2722960.09      6847468.33
      2722421.24      6847425.59
#Sta/Elev= 30
  4737.5  416.95  4741.8  416.97  4787.2  416.78  4797.3  416.18  4807.3  413.23
  4817.4  412.77  4827.5  413.12  4841.2  415.14  4847.6  416.25  4887.9  414.24
  4928.2  413.52  4978.6  411.89  4998.7  410.54  5048.5  410.43  5056.9  409.34
  5057.2  408.84  5060.7  408.84  5060.9  409.34  5068.9   409.7    5079  411.03
  5129.1  411.35  5157.1  412.93  5162.4  412.77  5179.3  414.14  5189.3  413.82
  5359.9   417.2  5500.3  418.39  5510.3  419.42  5520.4  418.63  5545.2  418.55
#Mann= 7 ,-1 , 0
  4737.5     .05       0  4741.8      .1       0  4841.2     .05       0
  5048.5     .12       0  5056.9     .04       0  5060.9     .12       0
  5157.1     .05       0
Bank Sta=5056.9,5060.9
XS Rating Curve= 0 ,0
Exp/Cntr=0.3,0.1

Type RM Length L Ch R = 1 ,6424    ,223,223,223
BEGIN DESCRIPTION:
Lacy 161 700
END DESCRIPTION:
XS GIS Cut Line= 3
      2723216.44      6847460.38      2723005.44      6847297.47
      2722611.36      6847225.92
#Sta/Elev= 30
  4652.7  416.39    4666   415.5  4674.2   415.8  4680.5  415.18  4688.7  415.33
    4695  414.55  4703.7  414.82  4716.4  414.43    4724  412.53  4759.3     413
  4817.3  410.63    4859  410.08  4865.2  407.34  4865.4  406.84  4868.9  406.84
  4869.2  407.34  4880.7  409.55    4888   409.9  4996.7  409.13  5037.5  410.39
  5042.6  410.15  5090.9  411.91    5096  411.47  5142.3   413.4  5154.5  413.43
  5172.8  415.61    5183  414.84  5233.8  416.96  5294.8  417.76  5319.8  417.38
#Mann= 5 ,-1 , 0
  4652.7      .1       0  4703.7     .12       0  4865.2     .05       0
  4869.2     .12       0  4996.7     .05       0
Bank Sta=4865.2,4869.2
XS Rating Curve= 0 ,0
Exp/Cntr=0.3,0.1

Type RM Length L Ch R = 1 ,6201    ,259,259,259
BEGIN DESCRIPTION:
Lacy 161 694
END DESCRIPTION:
XS GIS Cut Line= 3
      2723276.46      6846999.42      2723013.92      6847102.51
      2722640.06      6847116.99
#Sta/Elev= 30
  4718.8  416.27  4765.9  414.66  4783.8  414.51  4820.1  413.43  4837.5  412.48
  4849.9  412.57    4859  411.76  4891.2  410.49  4944.9  409.98  4980.6  408.79
  5028.8  407.77  5048.8  408.43  5092.4   407.9  5096.9  405.34  5097.1  404.84
  5100.6  404.84  5100.9  405.34  5108.9  407.66  5118.9  408.35  5128.9  408.53
  5138.9  409.39  5171.2  409.87  5198.9  410.08  5218.9   410.9    5239  412.29
    5279  413.64    5289   414.7  5346.7  415.64  5369.1  416.44    5375  416.99
#Mann= 6 ,-1 , 0
  4718.8     .12       0  4765.9     .05       0  4980.6      .1       0
  5096.9     .07       0  5100.9      .1       0  5171.2     .05       0
Bank Sta=5096.9,5100.9
XS Rating Curve= 0 ,0
Exp/Cntr=0.3,0.1

Type RM Length L Ch R = 1 ,5942    ,503,503,503
BEGIN DESCRIPTION:
Lacy 161 693
END DESCRIPTION:
XS GIS Cut Line= 3
      2723252.14      6846857.15      2722874.97      6846892.51
      2722599.82      6846913.86
#Sta/Elev= 30
  4622.6  419.49  4638.4  418.43    4679  416.51    4689  415.45  4699.1  413.33
  4709.1  413.65  4729.2  413.57  4769.4  411.73  4837.7  409.87  4869.8  409.09
    4900  406.72    4910  406.97  4933.4  406.45  4950.2  406.83  4990.3  406.49
  4996.4  402.52  4996.6  402.02  5000.1  402.02  5000.4  402.52  5001.4  402.52
  5010.4  405.06  5016.9  405.84  5030.5  407.19  5060.6  408.24  5110.7  409.07
  5140.8  410.48  5175.8  412.45  5180.9   413.6    5191  413.25  5277.4  415.79
#Mann= 6 ,-1 , 0
  4622.6     .12       0  4638.4     .05       0  4837.7      .1       0
  4996.4     .07       0  5000.4      .1       0  5016.9     .05       0
Bank Sta=4996.4,5000.4
XS Rating Curve= 0 ,0
Exp/Cntr=0.3,0.1

Type RM Length L Ch R = 1 ,5439    ,835,835,835
BEGIN DESCRIPTION:
Lacy 161 3404
END DESCRIPTION:
XS GIS Cut Line= 3
      2723174.46      6846207.44      2722739.62      6846527.21
      2722483.47      6846946.62
#Sta/Elev= 30
  4461.8  423.02  4477.4  422.88  4484.7  421.73  4498.2   421.2  4534.4  420.42
    4584   417.2  4627.8  416.25  4642.5  414.73  4692.6  412.36  4707.3  412.75
  4784.5  409.72  4828.4  406.77  4863.9   405.3  4964.2  403.91  4978.8  404.84
  4993.5  404.02  5006.7  404.32    5015  403.51  5018.8  400.23  5019.1  399.73
  5022.8  400.23  5036.3  403.36  5064.6  406.11  5167.9  409.29  5195.1   411.2
    5226  411.96  5253.1  414.45    5284  414.15  5392.7  416.35    5493  416.25
#Mann= 3 ,-1 , 0
  4461.8     .05       0  5018.8     .05       0  5022.8     .05       0
Bank Sta=5018.8,5022.8
XS Rating Curve= 0 ,0
Exp/Cntr=0.3,0.1

Type RM Length L Ch R = 1 ,4604    ,341,341,341
BEGIN DESCRIPTION:
Lacy 161 667
END DESCRIPTION:
XS GIS Cut Line= 3
      2722527.66        6845564.      2722295.18      6846270.41
      2722220.07      6847042.68
#Sta/Elev= 30
    4266  418.28  4314.8  417.75  4536.6  410.98  4589.2  407.54  4599.7  405.24
  4611.4  404.24  4637.9  404.03  4669.7  402.13  4789.2  401.08  4818.9  399.74
  4873.4  400.32  4890.2  396.34  4890.4  395.84  4894.2  396.34  4897.4  399.24
  4915.6  400.27  4978.7  399.34  4992.8  396.94  4999.8   398.8  5012.5  399.53
  5040.4  403.35  5070.6  403.99  5251.4  409.78  5271.5  409.56  5359.8  413.78
    5382  411.85  5422.2  413.93  5573.7  414.31  5675.5  412.83  5785.6  414.62
#Mann= 5 ,-1 , 0
    4266     .05       0  4818.9      .1       0  4890.2     .07       0
  4894.2      .1       0  5070.6     .05       0
Bank Sta=4890.2,4894.2
XS Rating Curve= 0 ,0
Exp/Cntr=0.3,0.1

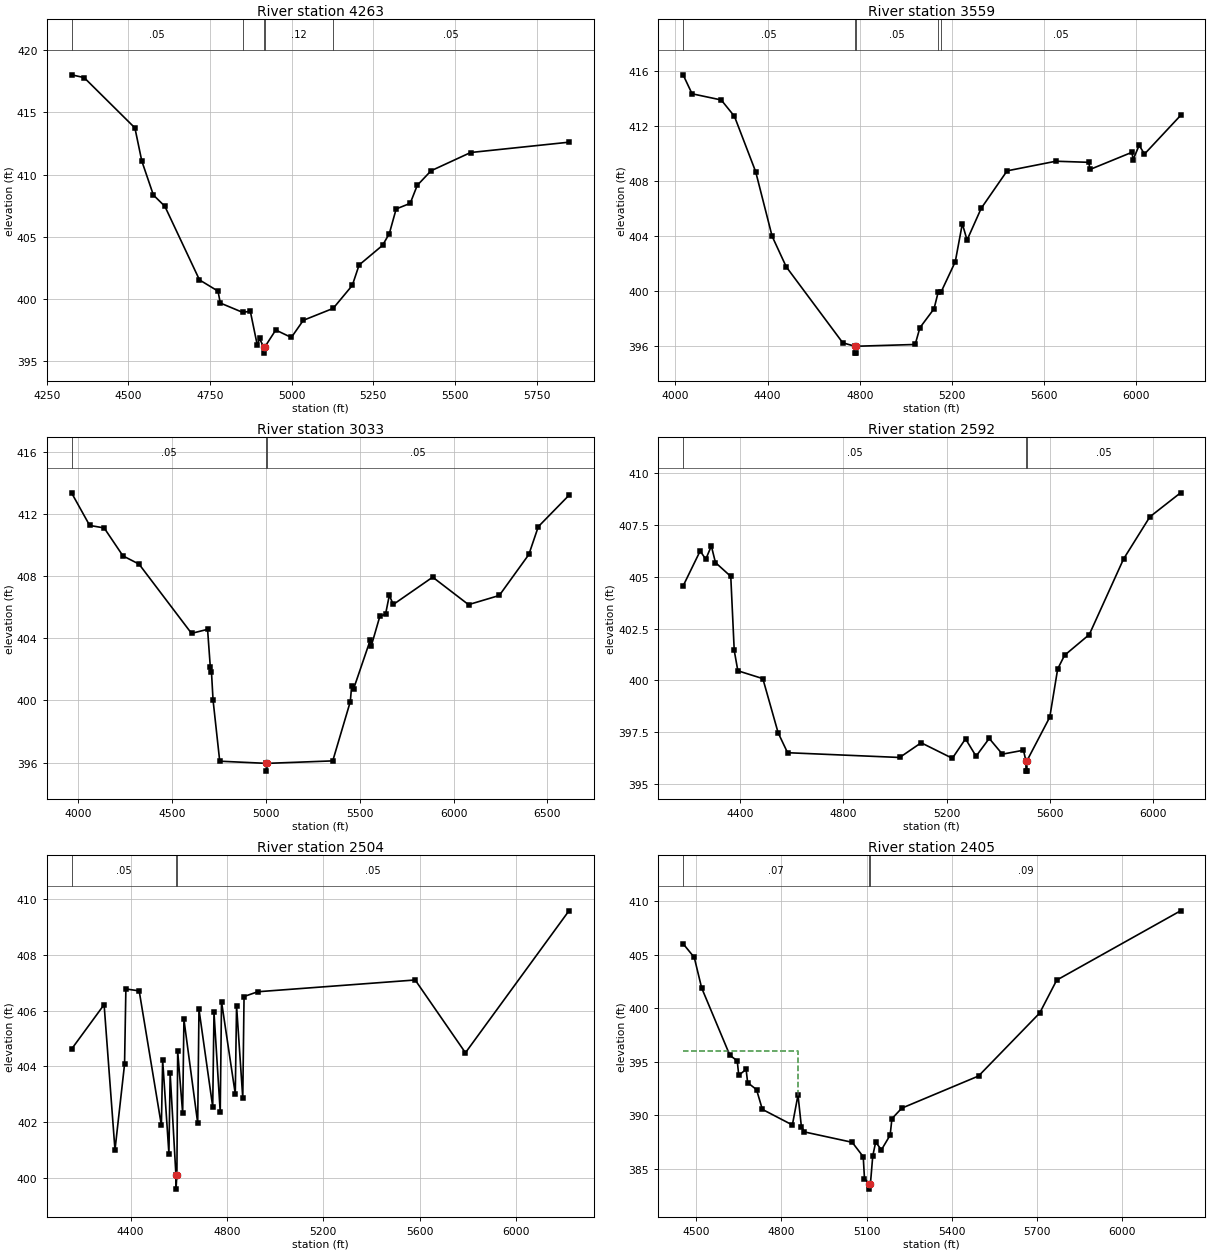
Type RM Length L Ch R = 1 ,4263    ,704,704,704
BEGIN DESCRIPTION:
Lacy 161 666
END DESCRIPTION:
XS GIS Cut Line= 3
      2722519.17      6845549.97      2722049.53       6846033.5
      2721511.49      6846690.29
#Sta/Elev= 30
    4326  418.03  4364.4  417.81    4520  413.76  4541.1   411.1  4576.6  408.36
  4611.8  407.45  4717.8  401.53  4774.4  400.63  4781.6  399.67    4850  398.92
  4873.4  399.01  4894.8  396.28  4901.7  396.82  4913.9  396.14  4914.1  395.64
  4917.9  396.14  4951.3   397.5    4999   396.9  5035.7  398.28  5127.1  399.24
  5185.7  401.09  5206.5  402.73  5278.3  404.31  5299.1  405.26    5320  407.24
    5363  407.69  5384.6  409.14  5426.8  410.31  5548.1  411.78  5849.1  412.61
#Mann= 5 ,-1 , 0
    4326     .05       0    4850     .12       0  4913.9     .07       0
  4917.9     .12       0  5127.1     .05       0
Bank Sta=4913.9,4917.9
XS Rating Curve= 0 ,0
Exp/Cntr=0.3,0.1

Type RM Length L Ch R = 1 ,3559    ,526,526,526
BEGIN DESCRIPTION:
Lacy 161 664
END DESCRIPTION:
XS GIS Cut Line= 3
      2722533.85      6845422.17      2721601.02      6845618.67
      2721347.59      6846796.62
#Sta/Elev= 30
  4033.2  415.74  4071.9  414.36  4198.5  413.91  4255.8  412.72  4347.9  408.69
  4419.3  403.99  4480.7  401.76  4725.9  396.23  4778.8  395.98  4779.1  395.48
  4782.6  395.48  4782.8  395.98    5040  396.11  5060.5  397.33  5121.9  398.71
  5140.1  399.94  5152.4  399.93  5213.9  402.13  5244.6   404.9  5265.1  403.71
  5326.4  406.02  5438.9  408.75  5650.4  409.45  5793.3  409.37  5798.5  408.85
  5980.5   410.1  5985.6  409.56  6011.8  410.61  6034.9  409.97  6191.4  412.78
#Mann= 5 ,-1 , 0
  4033.2     .05       0  4778.8     .03       0  4782.8     .05       0
  5140.1     .12       0  5152.4     .05       0
Bank Sta=4778.8,4782.8
XS Rating Curve= 0 ,0
Exp/Cntr=0.3,0.1

Type RM Length L Ch R = 1 ,3033    ,441,441,441
BEGIN DESCRIPTION:
Lacy 161 680
END DESCRIPTION:
XS GIS Cut Line= 3
      2722253.51      6844594.77      2721431.41      6845206.03
      2721288.08      6846823.65
#Sta/Elev= 30
  3966.3  413.37  4062.8  411.27  4139.9  411.11    4240  409.31  4325.6  408.78
  4605.1  404.32  4690.6  404.58  4705.2  402.14  4711.4  401.83  4719.8  400.02
  4755.3  396.09  5003.8  395.95    5004  395.45  5007.8  395.95  5357.1  396.11
  5450.6  399.93  5457.5   400.9  5467.6  400.73  5557.4  403.91  5562.4  403.52
  5608.1  405.43  5638.2  405.55  5658.3  406.77  5679.3  406.18  5889.2  407.94
    6080  406.17  6243.7  406.76  6401.2   409.4  6451.4  411.19  6614.7  413.21
#Mann= 3 ,-1 , 0
  3966.3     .05       0  5003.8     .03       0  5007.8     .05       0
Bank Sta=5003.8,5007.8
XS Rating Curve= 0 ,0
Exp/Cntr=0.3,0.1

Type RM Length L Ch R = 1 ,2592    ,88,88,88
BEGIN DESCRIPTION:
Lacy 161 662
END DESCRIPTION:
XS GIS Cut Line= 3
      2721473.37      6844538.53      2721069.81      6845255.12
      2720853.13      6846337.53
#Sta/Elev= 30
  4179.7  404.56  4245.7  406.25  4267.3  405.85    4289  406.49  4304.9  405.69
  4364.2  405.02  4377.6  401.44  4391.6  400.46  4488.4  400.08  4547.7  397.46
  4584.2   396.5  5018.3  396.27  5101.5  396.98  5222.3  396.23  5273.3  397.17
  5314.1  396.33  5365.1  397.19    5416  396.43  5497.6  396.62  5507.2  396.11
  5507.5  395.61    5511  395.61  5511.2  396.11  5599.6  398.22  5630.2  400.55
    5657  401.21  5752.6  402.21  5885.2  405.86  5987.2   407.9    6106  409.06
#Mann= 3 ,-1 , 0
  4179.7     .05       0  5507.2     .03       0  5511.2     .05       0
Bank Sta=5507.2,5511.2
XS Rating Curve= 0 ,0
Exp/Cntr=0.3,0.1

Type RM Length L Ch R = 1 ,2504    ,99,99,99
BEGIN DESCRIPTION:
Lacy 161 663
END DESCRIPTION:
XS GIS Cut Line= 4
      2721444.04      6844537.84      2721191.45      6844660.15
      2720949.66      6845359.85       2720816.3      6846393.64
#Sta/Elev= 30
  4155.4  404.62  4290.5  406.21  4335.6  401.02  4375.3  404.08  4380.8  406.77
    4436   406.7  4528.1   401.9  4533.4  404.22  4559.3  400.89  4564.5  403.75
  4588.4  400.12  4588.7  399.62  4592.4  400.12  4595.7  404.55  4616.3  402.34
  4621.6  405.68  4678.7  401.98    4684  406.04    4741  402.56  4746.3  405.93
  4772.2  402.37  4777.5  406.32  4834.6  403.02  4839.9  406.17  4865.7  402.87
    4871   406.5  4928.1  406.67  5580.8  407.09  5789.3  404.49  6218.7  409.56
#Mann= 3 ,-1 , 0
  4155.4     .05       0  4588.4     .05       0  4592.4     .05       0
Bank Sta=4588.4,4592.4
XS Rating Curve= 0 ,0
Exp/Cntr=0.3,0.1

Type RM Length L Ch R = 1 ,2405    ,97,97,97
BEGIN DESCRIPTION:
Lacy 161 661
END DESCRIPTION:
XS GIS Cut Line= 5
      2721113.06      6844607.07      2720933.37      6845132.71
      2720909.93      6845214.27      2720830.03      6845610.78
      2720800.48      6846316.52
#Sta/Elev= 30
  4454.2  406.04  4493.4  404.76  4519.4  401.91  4618.7  395.61  4644.7  395.09
    4650  393.74    4676  394.29  4681.3  393.05  4712.6   392.4  4733.1  390.55
  4838.8  389.09  4858.6  391.89  4870.5  388.94  4881.1  388.44  5049.4  387.47
  5088.3  386.12  5092.6  384.08  5109.6  383.59  5109.9  383.09  5113.6  383.59
  5121.8  386.19    5132  387.48  5152.4  386.77    5183  388.14  5189.3  389.68
  5223.8  390.66  5494.2  393.67  5709.5  399.56  5769.5  402.64  6205.4  409.12
#Mann= 3 ,-1 , 0
  4454.2     .07       0  5109.6     .04       0  5113.6     .09       0
#XS Ineff= 2 , 0
       0    4858     396               0
Permanent Ineff=
       F       F
Bank Sta=5109.6,5113.6
XS Rating Curve= 0 ,0
Exp/Cntr=0.3,0.1

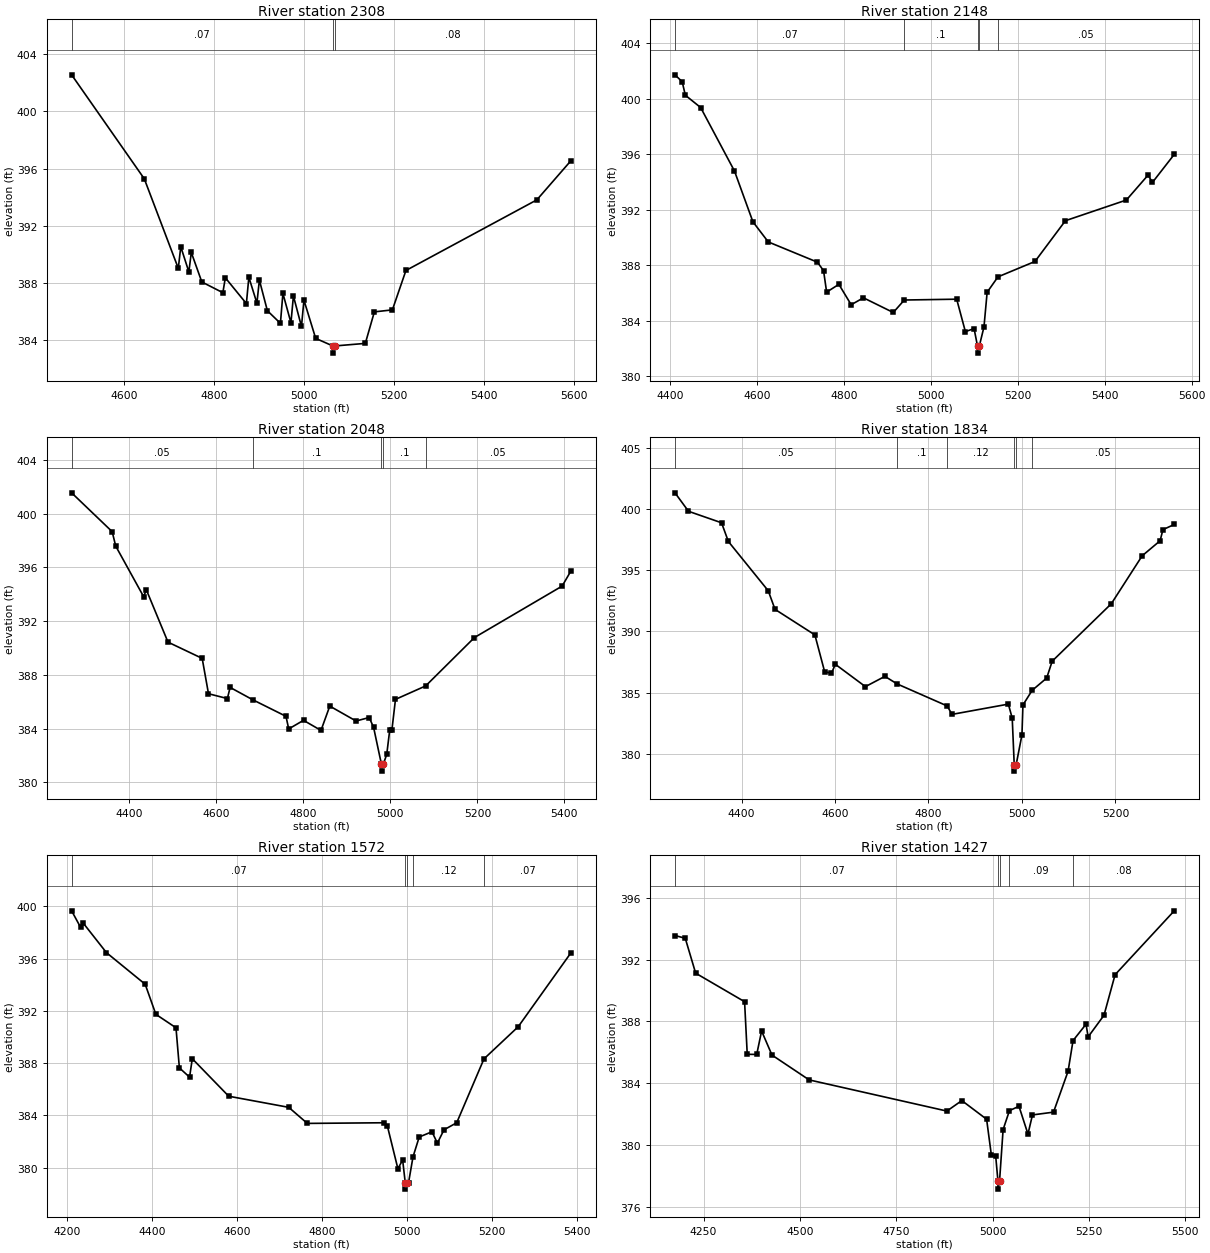
Type RM Length L Ch R = 1 ,2308    ,160,160,160
BEGIN DESCRIPTION:
Lacy 161 657
END DESCRIPTION:
XS GIS Cut Line= 3
      2721057.42      6844612.04      2720848.11      6845091.63
      2720798.09      6845676.42
#Sta/Elev= 30
  4483.9  402.54  4645.5  395.28  4721.1  389.03  4726.6  390.54  4744.6  388.78
    4750  390.14  4773.4  388.08  4820.2  387.33  4825.7  388.37  4872.5  386.57
    4878  388.41  4895.9   386.6  4901.4  388.21  4919.2  386.07  4948.2  385.19
  4953.7  387.28  4971.6  385.23  4977.1   387.1    4995  384.97  5000.5  386.81
  5026.6  384.14  5064.8  383.61    5065  383.11  5068.8  383.61    5137  383.79
  5157.1  385.99  5197.2  386.13  5227.3  388.88  5518.4  393.81  5594.1  396.54
#Mann= 3 ,-1 , 0
  4483.9     .07       0  5064.8     .03       0  5068.8     .08       0
Bank Sta=5064.8,5068.8
XS Rating Curve= 0 ,0
Exp/Cntr=0.3,0.1

Type RM Length L Ch R = 1 ,2148    ,100,100,100
BEGIN DESCRIPTION:
Lacy 161 656
END DESCRIPTION:
XS GIS Cut Line= 4
      2721035.81       6844607.2      2720720.47      6844915.19
      2720697.55      6845062.94       2720666.7      6845621.08
#Sta/Elev= 30
  4410.6  401.73  4427.2  401.23  4434.4  400.26  4469.7  399.37  4547.6  394.79
    4590  391.13  4625.3  389.68  4738.4  388.22  4752.6  387.61  4759.7  386.06
  4787.9  386.62  4816.2  385.15  4844.4  385.65  4913.1  384.59  4938.5  385.49
  5059.1  385.55  5079.1  383.21  5099.1  383.43  5107.1  382.16  5107.4  381.66
  5111.1  382.16  5121.9  383.55  5129.2  386.05  5154.1  387.16  5239.3  388.27
  5309.4  391.21  5449.7   392.7  5499.7   394.5  5509.7  393.97  5559.9  395.99
#Mann= 5 ,-1 , 0
  4410.6     .07       0  4938.5      .1       0  5107.1     .07       0
  5111.1      .1       0  5154.1     .05       0
Bank Sta=5107.1,5111.1
XS Rating Curve= 0 ,0
Exp/Cntr=0.3,0.1

Type RM Length L Ch R = 1 ,2048    ,214,214,214
BEGIN DESCRIPTION:
Lacy 161 659
END DESCRIPTION:
XS GIS Cut Line= 4
      2721038.41      6844571.74      2720640.68      6844883.76
       2720613.9      6845109.65      2720561.25       6845520.9
#Sta/Elev= 30
  4267.3  401.55  4360.5  398.66  4368.6  397.59  4432.7  393.83  4439.1  394.33
  4488.8  390.44  4567.4  389.23  4581.9   386.6  4625.3  386.24  4631.6  387.07
  4683.1  386.16    4760  384.92  4766.3  383.98  4800.3  384.62  4840.5  383.87
  4860.7  385.68  4921.1  384.57  4951.3  384.83  4961.4   384.1  4979.5  381.34
  4979.8  380.84  4983.5  381.34  4991.6  382.08  4998.5   383.9  5003.5   383.9
  5011.7  386.18  5081.1  387.18  5193.2  390.78  5394.8  394.61  5414.9  395.73
#Mann= 5 ,-1 , 0
  4267.3     .05       0  4683.1      .1       0  4979.5     .07       0
  4983.5      .1       0  5081.1     .05       0
Bank Sta=4979.5,4983.5
XS Rating Curve= 0 ,0
Exp/Cntr=0.3,0.1

Type RM Length L Ch R = 1 ,1834    ,262,262,262
BEGIN DESCRIPTION:
Lacy 161 660
END DESCRIPTION:
XS GIS Cut Line= 3
      2721041.03      6844536.28      2720447.63      6844986.55
      2720296.74      6845272.37
#Sta/Elev= 30
  4257.7  401.33  4286.6  399.82  4357.3  398.88  4371.9  397.35  4457.2  393.32
  4471.7   391.8    4557  389.71  4577.8  386.71  4592.4  386.56  4600.7  387.31
  4665.1  385.48  4706.8  386.32    4733   385.7  4840.1   383.9  4850.3  383.21
  4970.9  384.05  4979.2   382.9  4983.5  379.07  4983.7  378.57  4987.5  379.07
    5000  381.54  5002.1  383.98  5021.9  385.18  5052.9  386.18  5064.7  387.56
  5191.2  392.26  5257.2  396.18  5295.6  397.41  5301.6  398.32  5325.8  398.74
#Mann= 6 ,-1 , 0
  4257.7     .05       0    4733      .1       0  4840.1     .12       0
  4983.5     .07       0  4987.5     .12       0  5021.9     .05       0
Bank Sta=4983.5,4987.5
XS Rating Curve= 0 ,0
Exp/Cntr=0.3,0.1

Type RM Length L Ch R = 1 ,1572    ,145,145,145
BEGIN DESCRIPTION:
Lacy 161 658
END DESCRIPTION:
XS GIS Cut Line= 3
      2721036.39      6844506.94      2720294.87      6844781.65
      2720096.55      6845111.33
#Sta/Elev= 30
  4210.3  399.66  4231.5  398.39  4236.9  398.75  4292.3  396.46  4383.5  394.04
  4408.6  391.74    4456  390.71    4464  387.64    4488  386.93  4494.4  388.34
  4580.2  385.47  4721.5  384.62  4765.3  383.39  4946.5  383.44  4953.9  383.17
  4978.5  379.92  4989.7  380.59  4995.8  378.86  4996.1  378.36  4999.8  378.86
  5003.6  378.86  5014.1  380.83  5028.7  382.35  5058.7  382.75  5071.5  381.88
    5087   382.9    5117  383.44  5181.2  388.33  5261.8  390.79  5385.8  396.44
#Mann= 5 ,-1 , 0
  4210.3     .07       0  4995.8     .03       0  4999.8     .05       0
  5014.1     .12       0  5181.2     .07       0
Bank Sta=4995.8,4999.8
XS Rating Curve= 0 ,0
Exp/Cntr=0.3,0.1

Type RM Length L Ch R = 1 ,1427    ,234,234,234
BEGIN DESCRIPTION:
Lacy 161 655
END DESCRIPTION:
XS GIS Cut Line= 3
      2720977.96      6844428.32      2720187.76      6844681.42
      2719999.45      6845107.52
#Sta/Elev= 30
  4175.9  393.57  4202.6  393.39  4229.5  391.13  4356.5  389.28  4363.4  385.87
    4388  385.86  4400.7  387.38  4427.6  385.82  4524.1  384.21  4881.5  382.19
  4920.3  382.87  4984.6  381.66    4997  379.32  5008.1  379.29  5014.1  377.63
  5014.4  377.13  5018.1  377.63  5027.4  380.99  5043.9  382.22  5068.6   382.5
  5091.9   380.7  5103.6  381.94  5158.2  382.12    5196  384.77  5208.9  386.76
  5242.6  387.82  5248.1     387  5289.2   388.4    5318  391.03  5471.5  395.17
#Mann= 5 ,-1 , 0
  4175.9     .07       0  5014.1     .04       0  5018.1     .06       0
  5043.9     .09       0  5208.9     .08       0
Bank Sta=5014.1,5018.1
XS Rating Curve= 0 ,0
Exp/Cntr=0.3,0.1

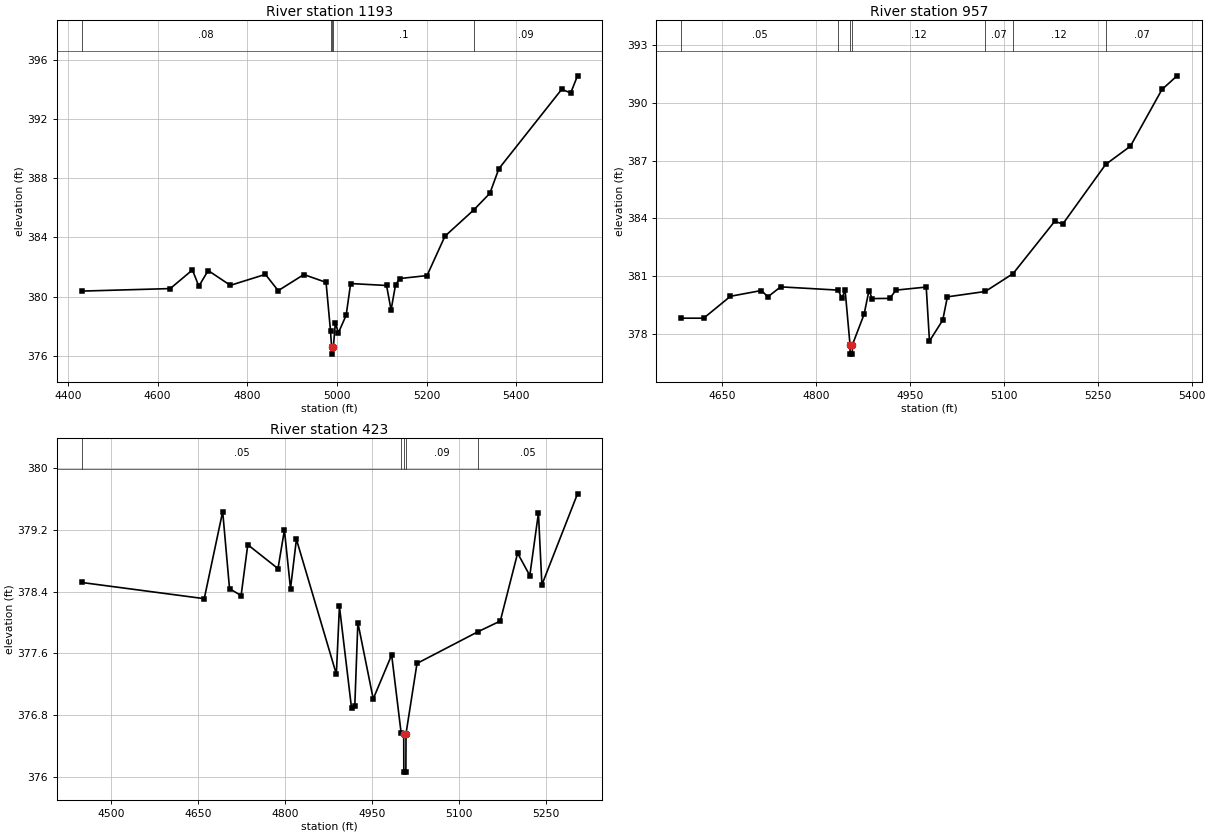
Type RM Length L Ch R = 1 ,1193    ,236,236,236
BEGIN DESCRIPTION:
Lacy 161 640
END DESCRIPTION:
XS GIS Cut Line= 3
      2720437.71      6844195.39      2720001.03       6844560.5
      2719973.58      6845096.19
#Sta/Elev= 30
  4430.8  380.37  4628.2  380.54  4677.7   381.8    4692   380.7  4712.8  381.76
  4762.3  380.76  4840.4   381.5    4869   380.4  4926.2  381.49  4975.7  380.96
  4985.6  377.68    4988  376.61  4988.3  376.11    4992  376.61  4996.5  378.24
  5003.1  377.54  5020.5  378.74  5030.5  380.88  5110.6  380.75  5120.7  379.09
  5130.7  380.81  5140.7  381.22  5200.9  381.42  5240.8  384.08  5305.2  385.86
    5341  386.98    5361  388.64  5501.2  394.01  5521.2  393.76  5536.4  394.92
#Mann= 5 ,-1 , 0
  4430.8     .08       0  4985.6      .1       0    4988     .04       0
    4992      .1       0  5305.2     .09       0
Bank Sta=4988,4992
XS Rating Curve= 0 ,0
Exp/Cntr=0.3,0.1

Type RM Length L Ch R = 1 ,957     ,534,534,534
BEGIN DESCRIPTION:
Lacy 161 675
END DESCRIPTION:
XS GIS Cut Line= 3
      2719887.56      6844256.08      2719796.14       6844661.4
      2719746.79      6845034.85
#Sta/Elev= 30
  4584.5   378.8  4620.3   378.8  4663.1  379.94  4712.6  380.24  4722.8  379.91
  4743.3  380.43  4835.4  380.26  4841.1  379.83  4846.3  380.26  4854.1  377.43
  4854.3  376.93  4857.8  376.93  4858.1  377.43  4876.6     379  4884.4  380.24
  4889.5  379.82  4917.6  379.83  4927.6  380.26  4975.9  380.42  4981.1  377.61
  5002.3   378.7  5009.7  379.91  5070.3  380.19  5114.7  381.12  5181.2  383.84
  5194.1   383.7  5262.6   386.8  5302.2  387.75  5352.6   390.7  5376.7  391.41
#Mann= 7 ,-1 , 0
  4584.5     .05       0  4835.4     .12       0  4854.1     .07       0
  4858.1     .12       0  5070.3     .07       0  5114.7     .12       0
  5262.6     .07       0
Bank Sta=4854.1,4858.1
XS Rating Curve= 0 ,0
Exp/Cntr=0.3,0.1

Type RM Length L Ch R = 1 ,423     ,0,0,0
BEGIN DESCRIPTION:
Lacy 161 676
END DESCRIPTION:
XS GIS Cut Line= 3
       2719888.2      6844228.76      2719364.95      6844400.78
      2719193.59      6844652.48
#Sta/Elev= 30
  4449.2  378.52  4660.6  378.31  4692.4  379.44  4704.2  378.44  4724.2  378.35
  4735.7  379.01  4787.8   378.7  4798.9   379.2  4809.4  378.44  4819.6  379.08
  4888.5  377.33  4893.8  378.21  4914.7  376.89  4920.3  376.92  4925.6     378
  4952.1  377.01  4983.9  377.58  5000.2  376.57  5004.7  376.56  5004.9  376.06
  5008.4  376.06  5008.7  376.56  5027.6  377.47  5132.5  377.88  5171.3  378.02
  5201.2   378.9  5222.2  378.61  5237.1  379.42  5243.1  378.49  5304.5  379.67
#Mann= 5 ,-1 , 0
  4449.2     .05       0  5000.2     .09       0  5004.7     .04       0
  5008.7     .09       0  5132.5     .05       0
Bank Sta=5004.7,5008.7
XS Rating Curve= 0 ,0
Exp/Cntr=0.3,0.1

Chan Stop Cuts=-1
Use User Specified Reach Order=0
Composite Channel Slope=5