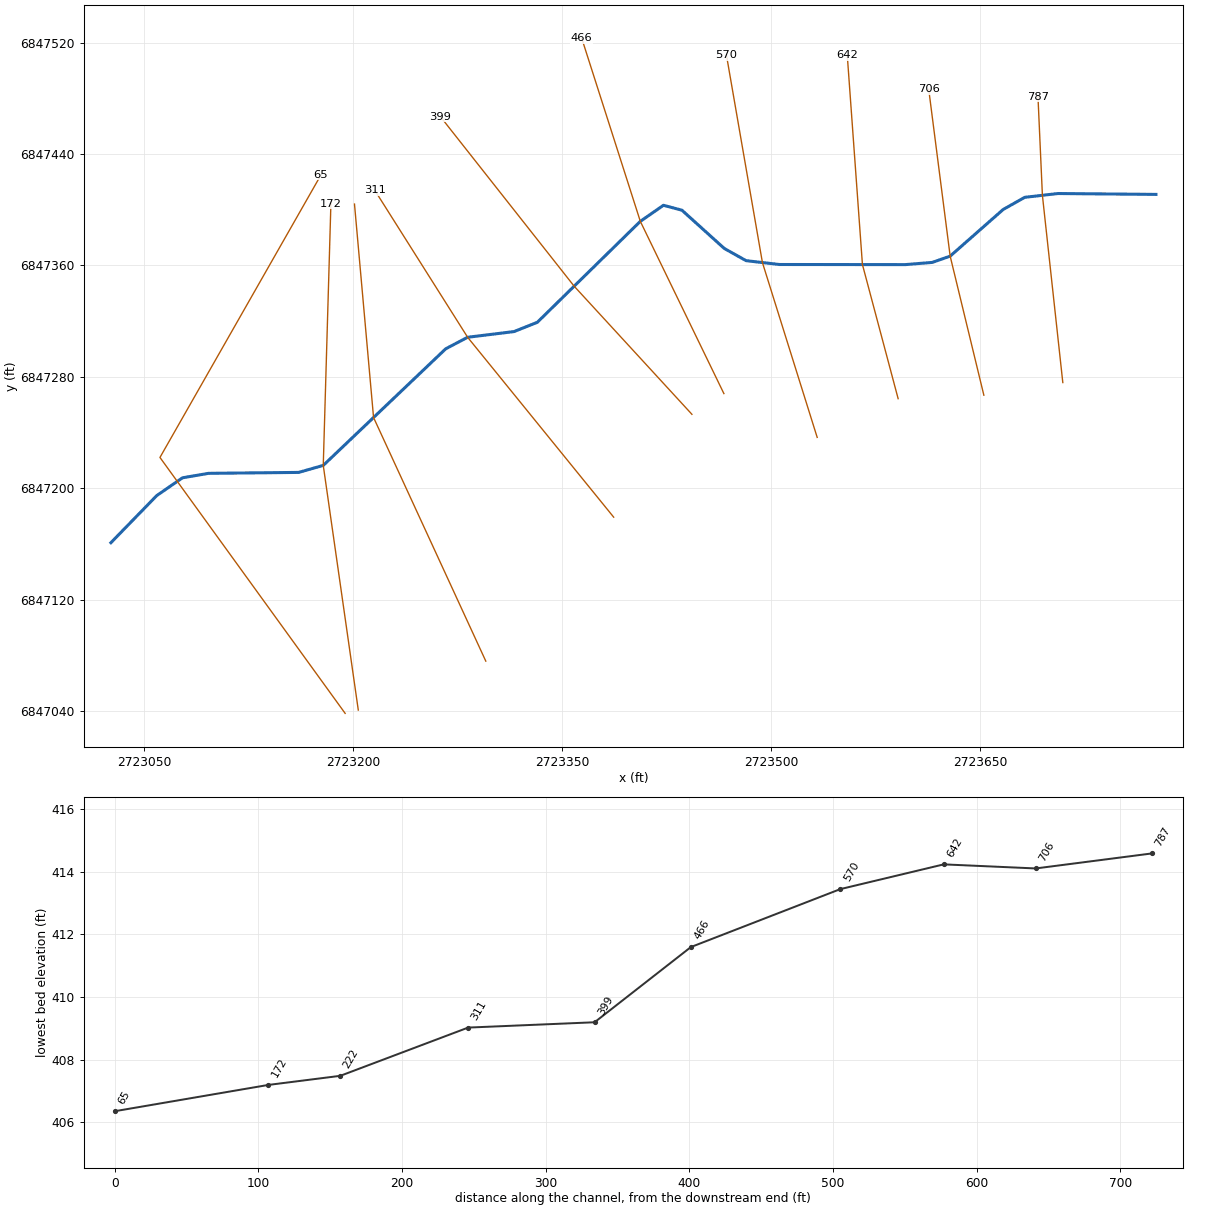
--- Lacy 162.prj (project) ---

Proj Title=Lacy 162 Base Level Engineering
Current Plan=p01
Default Exp/Contr=0.3,0.1
English Units
Geom File=g01
Flow File=f01
Plan File=p01
BEGIN DESCRIPTION:
Lacy 162
END DESCRIPTION:

--- Lacy 162.p01 (plan) ---

Plan Title=Multiple Run
Short Identifier=Multiple
Geom File=g01
Flow File=f01
Subcritical Flow
K Sum by GR= 0
Std Step Tol= 0.01
Critical Tol= 0.01
Num of Std Step Trials= 20
Max Error Tol= 0.3
Flow Tol Ratio= 0.001
Split Flow NTrial= 30
Split Flow Tol= 0.02
Split Flow Ratio= 0.02
Log Output Level= 0
Friction Slope Method= 1
Unsteady Friction Slope Method= 2
Unsteady Bridges Friction Slope Method= 1
Parabolic Critical Depth
Global Vel Dist=  1 , 1 , 1
Global Log Level= 0
CheckData=True
Encroach Param= -1, 0, 0, 0
BEGIN DESCRIPTION:
Multiple Run
END DESCRIPTION:

--- Lacy 162.f01 (steady flow) ---

Flow Title=Multiple
Number of Profiles=7
Profile Names=10-year,25-year,50-year,1pct_min,100-year,1pct_plu,500-year
River Rch & RM= Lacy 162,Reach-1,787
     174     215     246     140     280     559     361
Boundary for River Rch & Prof#=Lacy 162,Reach-1,1
Up Type=0
Dn Type=3
Dn Slope=0.005
Boundary for River Rch & Prof#=Lacy 162,Reach-1,2
Up Type=0
Dn Type=3
Dn Slope=0.005
Boundary for River Rch & Prof#=Lacy 162,Reach-1,3
Up Type=0
Dn Type=3
Dn Slope=0.005
Boundary for River Rch & Prof#=Lacy 162,Reach-1,4
Up Type=0
Dn Type=3
Dn Slope=0.005
Boundary for River Rch & Prof#=Lacy 162,Reach-1,5
Up Type=0
Dn Type=3
Dn Slope=0.005
Boundary for River Rch & Prof#=Lacy 162,Reach-1,6
Up Type=0
Dn Type=3
Dn Slope=0.005
Boundary for River Rch & Prof#=Lacy 162,Reach-1,7
Up Type=0
Dn Type=3
Dn Slope=0.005

--- Lacy 162.g01 (geometry) ---

Geom Title=Existing Conditions

River Reach=Lacy 162,Reach-1
Reach XY= 23
      2723776.00      6847411.00      2723705.74      6847411.63
      2723681.87      6847408.90      2723666.35      6847400.14
      2723628.35      6847366.70      2723615.50      6847362.19
      2723596.14      6847360.61      2723505.83      6847360.69
      2723481.86      6847363.46      2723466.20      6847372.23
      2723435.85      6847399.66      2723422.59      6847403.19
      2723405.98      6847391.67      2723332.05      6847319.20
      2723315.36      6847312.56      2723282.05      6847308.46
      2723266.33      6847300.20      2723178.43      6847216.51
      2723160.80      6847211.48      2723096.08      6847210.81
      2723077.41      6847207.61      2723058.95      6847194.87
      2723026.00      6847161.00

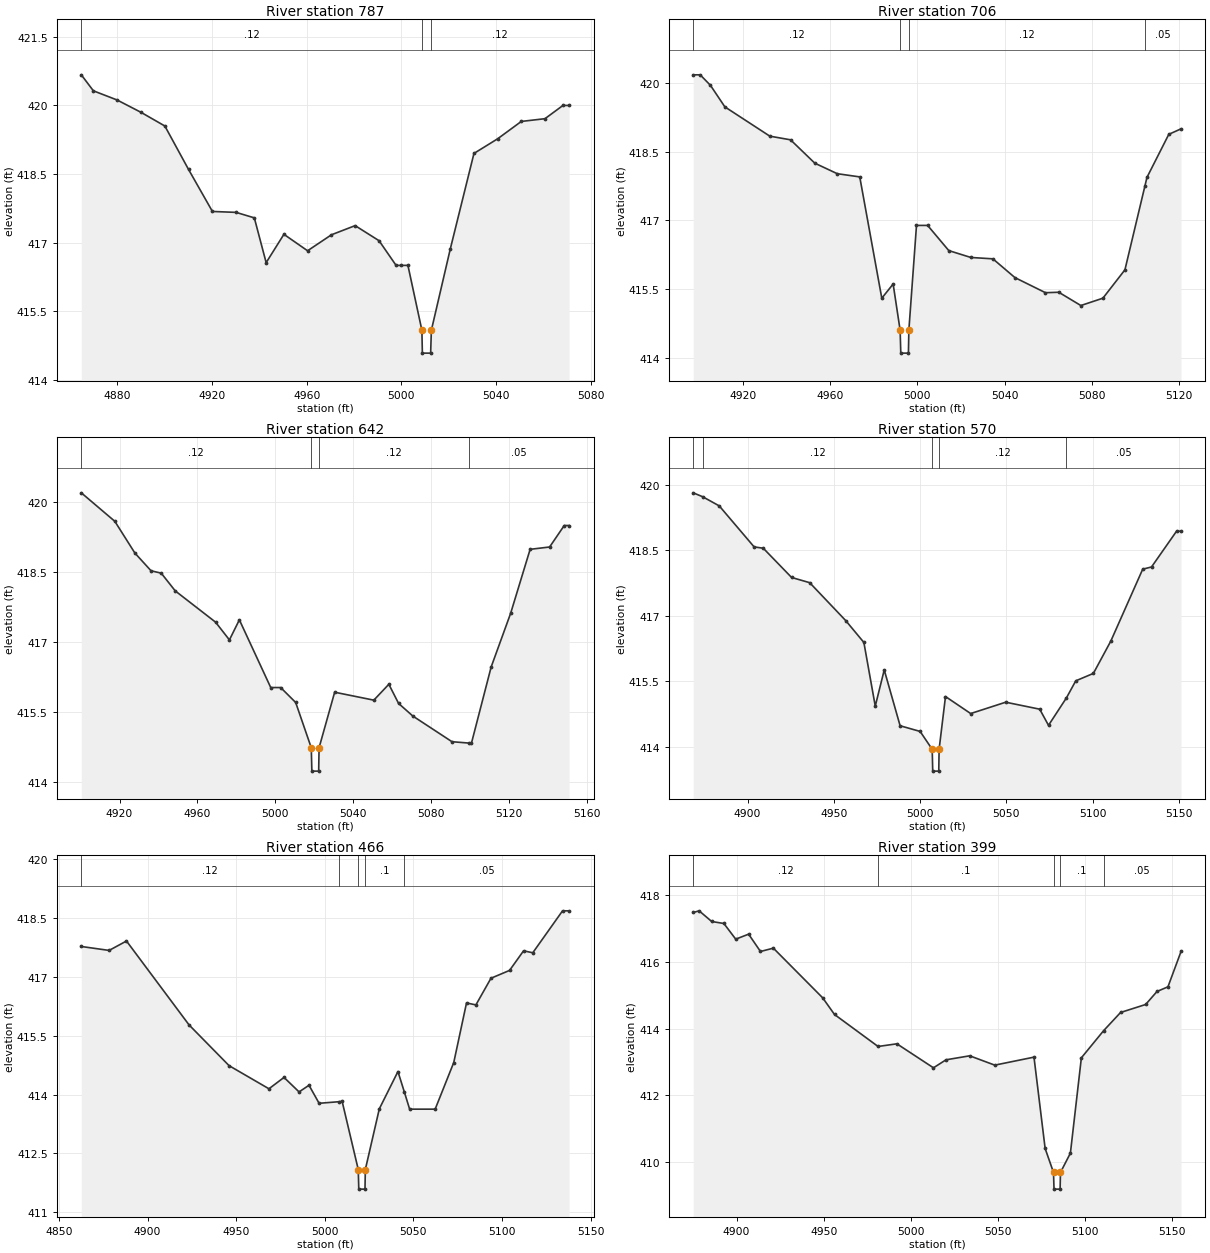
Type RM Length L Ch R = 1,787,81,81,81
BEGIN DESCRIPTION:
Lacy 162 714
END DESCRIPTION:
XS GIS Cut Line= 3
      2723709.20      6847275.95      2723694.55      6847410.35
      2723691.37      6847481.18
#Sta/Elev= 29
  4864.8  420.67  4869.9  420.32  4879.9  420.12  4890.0  419.85  4900.1  419.55
  4910.1  418.60  4920.2  417.68  4930.2  417.66  4937.9  417.54  4942.9  416.56
  4950.4  417.18  4960.4  416.82  4970.5  417.17  4980.5  417.37  4990.6  417.04
  4997.8  416.50  5000.0  416.50  5002.8  416.50  5008.7  415.08  5008.9  414.58
  5012.4  414.58  5012.7  415.08  5020.7  416.86  5030.7  418.95  5040.7  419.27
  5050.7  419.65  5060.7  419.71  5068.3  420.00  5070.9  420.00
#Mann=3,-1,0
  4864.8    0.12       0  5008.7    0.07       0  5012.7    0.12       0
Bank Sta=5008.7,5012.7
Exp/Cntr=0.3,0.1

Type RM Length L Ch R = 1,706,64,64,64
BEGIN DESCRIPTION:
Lacy 162 713
END DESCRIPTION:
XS GIS Cut Line= 3
      2723652.53      6847266.89      2723628.35      6847366.70
      2723612.95      6847486.52
#Sta/Elev= 30
  4897.3  420.18  4900.5  420.18  4905.2  419.95  4911.8  419.48  4932.4  418.84
  4941.9  418.76  4953.0  418.25  4963.3  418.02  4973.6  417.95  4983.7  415.30
  4988.9  415.61  4992.1  414.60  4992.4  414.10  4995.9  414.10  4996.1  414.60
  4999.6  416.89  5004.7  416.89  5014.4  416.34  5024.5  416.19  5034.6  416.16
  5044.7  415.75  5058.7  415.42  5064.8  415.43  5074.9  415.14  5085.0  415.30
  5095.1  415.92  5104.3  417.76  5105.2  417.94  5115.2  418.88  5120.8  419.00
#Mann=4,-1,0
  4897.3    0.12       0  4992.1    0.07       0  4996.1    0.12       0
  5104.3    0.05       0
Bank Sta=4992.1,4996.1
Exp/Cntr=0.3,0.1

Type RM Length L Ch R = 1,642,72,72,72
BEGIN DESCRIPTION:
Lacy 162 712
END DESCRIPTION:
XS GIS Cut Line= 3
      2723591.02      6847264.39      2723565.39      6847360.64
      2723554.50      6847510.94
#Sta/Elev= 30
  4900.4  420.19  4917.6  419.58  4927.9  418.90  4936.2  418.52  4941.4  418.47
  4948.6  418.09  4969.3  417.42  4976.4  417.04  4981.5  417.47  4997.6  416.02
  5002.7  416.02  5010.4  415.70  5018.4  414.73  5018.7  414.23  5022.2  414.23
  5022.4  414.73  5030.4  415.92  5050.5  415.75  5058.2  416.09  5063.2  415.68
  5070.5  415.41  5090.6  414.86  5099.5  414.83  5100.6  414.83  5110.7  416.46
  5120.7  417.61  5130.7  418.98  5140.7  419.03  5148.2  419.49  5150.7  419.49
#Mann=4,-1,0
  4900.4    0.12       0  5018.4    0.07       0  5022.4    0.12       0
  5099.5    0.05       0
Bank Sta=5018.4,5022.4
Exp/Cntr=0.3,0.1

Type RM Length L Ch R = 1,570,104,104,104
BEGIN DESCRIPTION:
Lacy 162 711
END DESCRIPTION:
XS GIS Cut Line= 3
      2723532.92      6847236.61      2723493.61      6847362.10
      2723467.77      6847511.07
#Sta/Elev= 30
  4868.5  419.82  4874.0  419.73  4883.6  419.52  4903.8  418.58  4909.1  418.55
  4925.5  417.88  4936.0  417.76  4956.9  416.89  4967.4  416.39  4974.0  414.93
  4979.2  415.76  4988.4  414.48  5000.0  414.35  5007.0  413.94  5007.3  413.44
  5010.8  413.44  5011.0  413.94  5014.7  415.15  5029.3  414.76  5049.6  415.02
  5069.3  414.86  5074.4  414.49  5084.8  415.12  5090.2  415.51  5100.4  415.68
  5110.5  416.42  5129.0  418.07  5134.1  418.12  5148.6  418.94  5151.2  418.94
#Mann=5,-1,0
  4868.5     0.1       0  4874.0    0.12       0  5007.0    0.07       0
  5011.0    0.12       0  5084.8    0.05       0
Bank Sta=5007,5011
Exp/Cntr=0.3,0.1

Type RM Length L Ch R = 1,466,67,67,67
BEGIN DESCRIPTION:
Lacy 162 710
END DESCRIPTION:
XS GIS Cut Line= 3
      2723465.96      6847268.05      2723405.98      6847391.67
      2723363.95      6847523.01
#Sta/Elev= 30
  4862.6  417.78  4878.3  417.68  4888.1  417.92  4923.4  415.78  4946.0  414.74
  4968.5  414.15  4977.0  414.44  4985.5  414.07  4991.1  414.24  4996.8  413.78
  5008.0  413.82  5009.8  413.83  5018.9  412.09  5019.2  411.59  5022.7  411.59
  5022.9  412.09  5030.8  413.64  5041.3  414.59  5044.9  414.07  5047.9  413.63
  5062.3  413.63  5072.8  414.82  5080.0  416.34  5085.3  416.29  5093.8  416.97
  5104.3  417.17  5112.2  417.67  5117.4  417.62  5134.2  418.69  5137.9  418.69
#Mann=5,-1,0
  4862.6    0.12       0  5008.0     0.1       0  5018.9    0.07       0
  5022.9     0.1       0  5044.9    0.05       0
Bank Sta=5018.9,5022.9
Exp/Cntr=0.3,0.1

Type RM Length L Ch R = 1,399,88,88,88
BEGIN DESCRIPTION:
Lacy 162 709
END DESCRIPTION:
XS GIS Cut Line= 3
      2723443.02      6847253.17      2723358.50      6847345.12
      2723262.44      6847466.90
#Sta/Elev= 30
  4875.1  417.49  4878.5  417.54  4885.7  417.22  4892.7  417.16  4899.5  416.69
  4906.9  416.84  4913.7  416.32  4921.1  416.42  4949.4  414.93  4956.2  414.43
  4981.2  413.47  4992.0  413.55  5013.0  412.83  5020.2  413.07  5033.8  413.19
  5048.2  412.91  5070.7  413.15  5077.1  410.41  5081.9  409.69  5082.2  409.19
  5085.7  409.19  5085.9  409.69  5091.6  410.27  5097.9  413.13  5110.6  413.94
  5120.4  414.49  5134.8  414.73  5141.3  415.12  5147.6  415.26  5155.1  416.32
#Mann=5,-1,0
  4875.1    0.12       0  4981.2     0.1       0  5081.9    0.07       0
  5085.9     0.1       0  5110.6    0.05       0
Bank Sta=5081.9,5085.9
Exp/Cntr=0.3,0.1

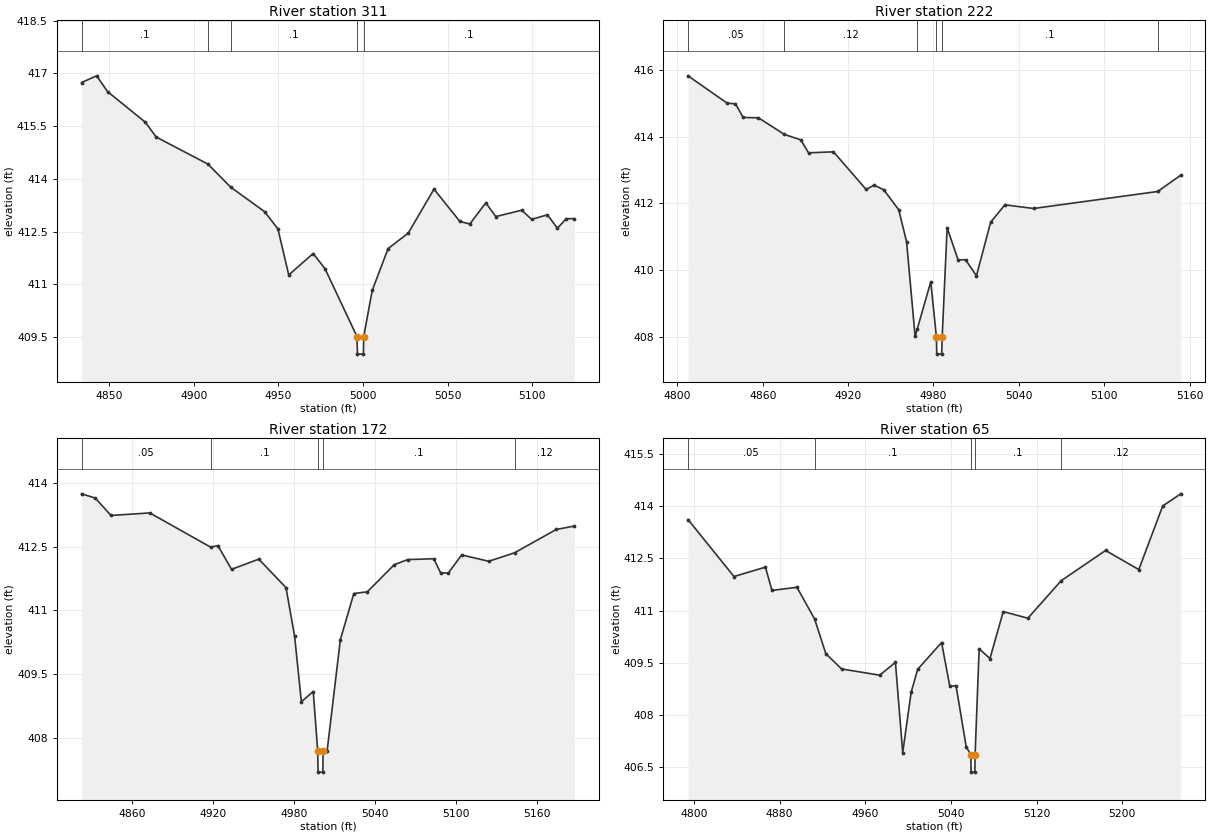
Type RM Length L Ch R = 1,311,89,89,89
BEGIN DESCRIPTION:
Lacy 162 708
END DESCRIPTION:
XS GIS Cut Line= 3
      2723386.87      6847179.35      2723282.05      6847308.46
      2723215.40      6847413.97
#Sta/Elev= 30
  4833.7  416.74  4842.6  416.93  4849.1  416.48  4871.4  415.61  4877.8  415.19
  4908.4  414.42  4921.7  413.77  4941.8  413.07  4949.7  412.58  4956.1  411.27
  4970.5  411.88  4977.5  411.45  4996.4  409.52  4996.7  409.02  5000.2  409.02
  5000.4  409.52  5005.4  410.83  5014.8  412.02  5026.7  412.46  5041.9  413.71
  5057.2  412.79  5063.1  412.72  5072.5  413.32  5078.4  412.93  5093.7  413.11
  5099.6  412.85  5108.9  412.98  5114.8  412.60  5120.1  412.87  5124.8  412.87
#Mann=5,-1,0
  4833.7     0.1       0  4908.4    0.12       0  4921.7     0.1       0
  4996.4    0.07       0  5000.4     0.1       0
Bank Sta=4996.4,5000.4
Exp/Cntr=0.3,0.1

Type RM Length L Ch R = 1,222,50,50,50
BEGIN DESCRIPTION:
Lacy 162 707
END DESCRIPTION:
XS GIS Cut Line= 3
      2723295.08      6847076.04      2723214.53      6847250.88
      2723200.84      6847404.07
#Sta/Elev= 30
  4807.5  415.83  4835.0  415.01  4840.8  414.99  4846.3  414.58  4857.0  414.57
  4875.3  414.07  4886.7  413.91  4892.2  413.52  4909.7  413.55  4932.7  412.42
  4938.2  412.55  4945.1  412.41  4955.6  411.81  4961.1  410.85  4967.1  408.01
  4968.5  408.22  4978.1  409.65  4982.1  407.98  4982.3  407.48  4985.8  407.48
  4986.1  407.98  4989.6  411.27  4997.3  410.31  5002.6  410.31  5010.2  409.83
  5020.2  411.44  5030.2  411.96  5050.3  411.85  5137.6  412.36  5153.8  412.85
#Mann=6,-1,0
  4807.5    0.05       0  4875.3    0.12       0  4968.5     0.1       0
  4982.1    0.07       0  4986.1     0.1       0  5137.6    0.12       0
Bank Sta=4982.1,4986.1
Exp/Cntr=0.3,0.1

Type RM Length L Ch R = 1,172,107,107,107
BEGIN DESCRIPTION:
Lacy 162 706
END DESCRIPTION:
XS GIS Cut Line= 3
      2723203.57      6847040.91      2723178.43      6847216.51
      2723183.92      6847404.43
#Sta/Elev= 30
  4822.6  413.75  4832.8  413.65  4844.4  413.24  4873.2  413.30  4918.5  412.49
  4923.7  412.53  4933.8  411.97  4954.0  412.21  4974.2  411.54  4980.6  410.39
  4985.6  408.85  4994.4  409.09  4997.7  407.69  4998.0  407.19  5001.5  407.19
  5001.7  407.69  5004.7  407.69  5014.5  410.31  5024.5  411.40  5034.5  411.44
  5054.5  412.08  5064.5  412.20  5083.8  412.22  5088.8  411.89  5094.5  411.88
  5104.5  412.31  5124.5  412.16  5143.7  412.36  5174.6  412.91  5188.0  412.99
#Mann=5,-1,0
  4822.6    0.05       0  4918.5     0.1       0  4997.7    0.07       0
  5001.7     0.1       0  5143.7    0.12       0
Bank Sta=4997.7,5001.7
Exp/Cntr=0.3,0.1

Type RM Length L Ch R = 1,65,0,0,0
BEGIN DESCRIPTION:
Lacy 162 3405
END DESCRIPTION:
XS GIS Cut Line= 3
      2723194.14      6847038.54      2723061.23      6847222.22
      2723176.83      6847425.08
#Sta/Elev= 30
  4794.5  413.62  4837.4  411.98  4866.8  412.25  4872.9  411.58  4896.2  411.67
  4912.7  410.76  4923.2  409.76  4937.9  409.32  4973.5  409.14  4988.2  409.51
  4995.0  406.91  5002.9  408.65  5009.0  409.31  5031.3  410.08  5039.0  408.82
  5044.8  408.84  5054.3  407.08  5058.6  406.85  5058.9  406.35  5062.4  406.35
  5062.6  406.85  5066.4  409.90  5076.5  409.62  5088.9  410.97  5111.9  410.78
  5143.0  411.86  5184.5  412.73  5215.5  412.18  5237.8  414.01  5254.7  414.36
#Mann=5,-1,0
  4794.5    0.05       0  4912.7     0.1       0  5058.6    0.07       0
  5062.6     0.1       0  5143.0    0.12       0
Bank Sta=5058.6,5062.6
Exp/Cntr=0.3,0.1

Chan Stop Cuts=-1