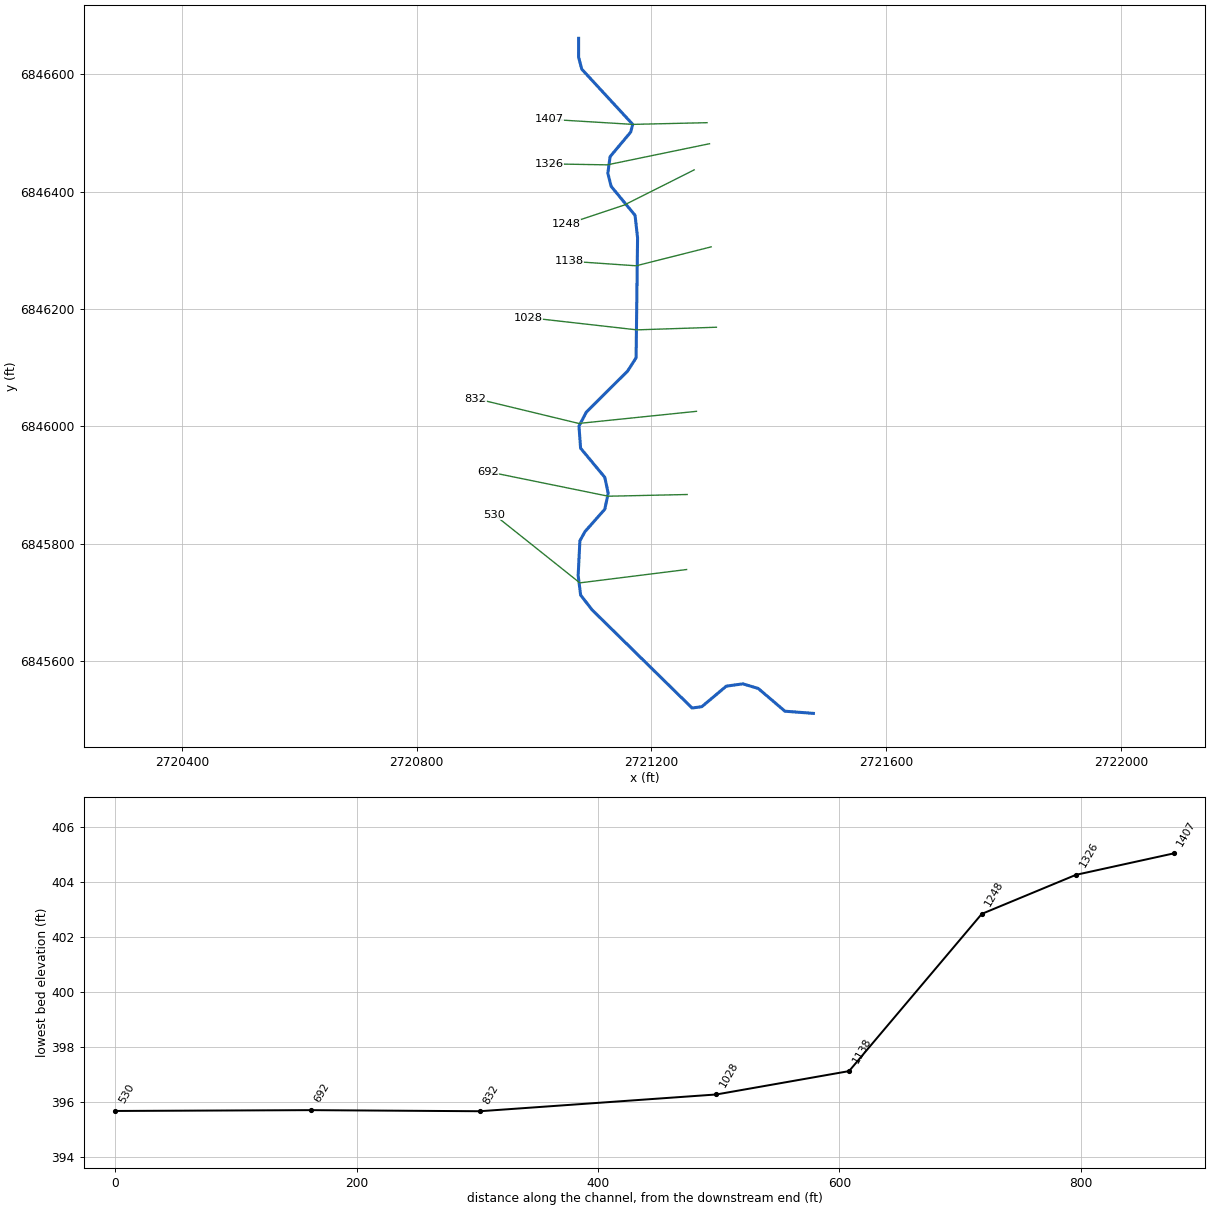
--- Lacy 163.prj (project) ---

Proj Title=Lacy 163 Base Level Engineering
Current Plan=p01
Default Exp/Contr=0.3,0.1
English Units
Geom File=g01
Flow File=f01
Plan File=p01
BEGIN DESCRIPTION:
Lacy 163
END DESCRIPTION:

--- Lacy 163.p01 (plan) ---

Plan Title=Multiple Run
Short Identifier=Multiple
Geom File=g01
Flow File=f01
Subcritical Flow
K Sum by GR= 0
Std Step Tol= 0.01
Critical Tol= 0.01
Num of Std Step Trials= 20
Max Error Tol= 0.3
Flow Tol Ratio= 0.001
Split Flow NTrial= 30
Split Flow Tol= 0.02
Split Flow Ratio= 0.02
Log Output Level= 0
Friction Slope Method= 1
Unsteady Friction Slope Method= 2
Unsteady Bridges Friction Slope Method= 1
Parabolic Critical Depth
Global Vel Dist=  1 , 1 , 1
Global Log Level= 0
CheckData=True
Encroach Param= -1, 0, 0, 0
BEGIN DESCRIPTION:
Multiple Run
END DESCRIPTION:

--- Lacy 163.f01 (steady flow) ---

Flow Title=Multiple
Number of Profiles=7
Profile Names=10-year,25-year,50-year,1pct_min,100-year,1pct_plu,500-year
River Rch & RM= Lacy 163,Reach-1,1407
      97     113     125      69     138     276     167
Boundary for River Rch & Prof#=Lacy 163,Reach-1,1
Up Type=0
Dn Type=3
Dn Slope=0.005
Boundary for River Rch & Prof#=Lacy 163,Reach-1,2
Up Type=0
Dn Type=3
Dn Slope=0.005
Boundary for River Rch & Prof#=Lacy 163,Reach-1,3
Up Type=0
Dn Type=3
Dn Slope=0.005
Boundary for River Rch & Prof#=Lacy 163,Reach-1,4
Up Type=0
Dn Type=3
Dn Slope=0.005
Boundary for River Rch & Prof#=Lacy 163,Reach-1,5
Up Type=0
Dn Type=3
Dn Slope=0.005
Boundary for River Rch & Prof#=Lacy 163,Reach-1,6
Up Type=0
Dn Type=3
Dn Slope=0.005
Boundary for River Rch & Prof#=Lacy 163,Reach-1,7
Up Type=0
Dn Type=3
Dn Slope=0.005

--- Lacy 163.g01 (geometry) ---

Geom Title=Existing Conditions

River Reach=Lacy 163,Reach-1
Reach XY= 30
      2721076.00      6846661.00      2721075.94      6846629.12
      2721081.35      6846608.48      2721168.19      6846514.41
      2721164.61      6846501.13      2721129.62      6846459.37
      2721125.79      6846431.21      2721131.40      6846408.83
      2721172.19      6846359.45      2721176.45      6846321.19
      2721173.93      6846116.86      2721159.53      6846094.25
      2721089.15      6846024.20      2721076.61      6846000.37
      2721079.37      6845962.74      2721120.58      6845913.20
      2721126.39      6845886.00      2721120.62      6845858.82
      2721086.87      6845820.65      2721078.19      6845805.03
      2721075.23      6845745.91      2721079.46      6845712.50
      2721098.84      6845687.48      2721269.27      6845520.15
      2721285.87      6845522.38      2721327.63      6845557.39
      2721355.79      6845561.29      2721382.00      6845553.46
      2721427.49      6845514.69      2721476.00      6845511.00

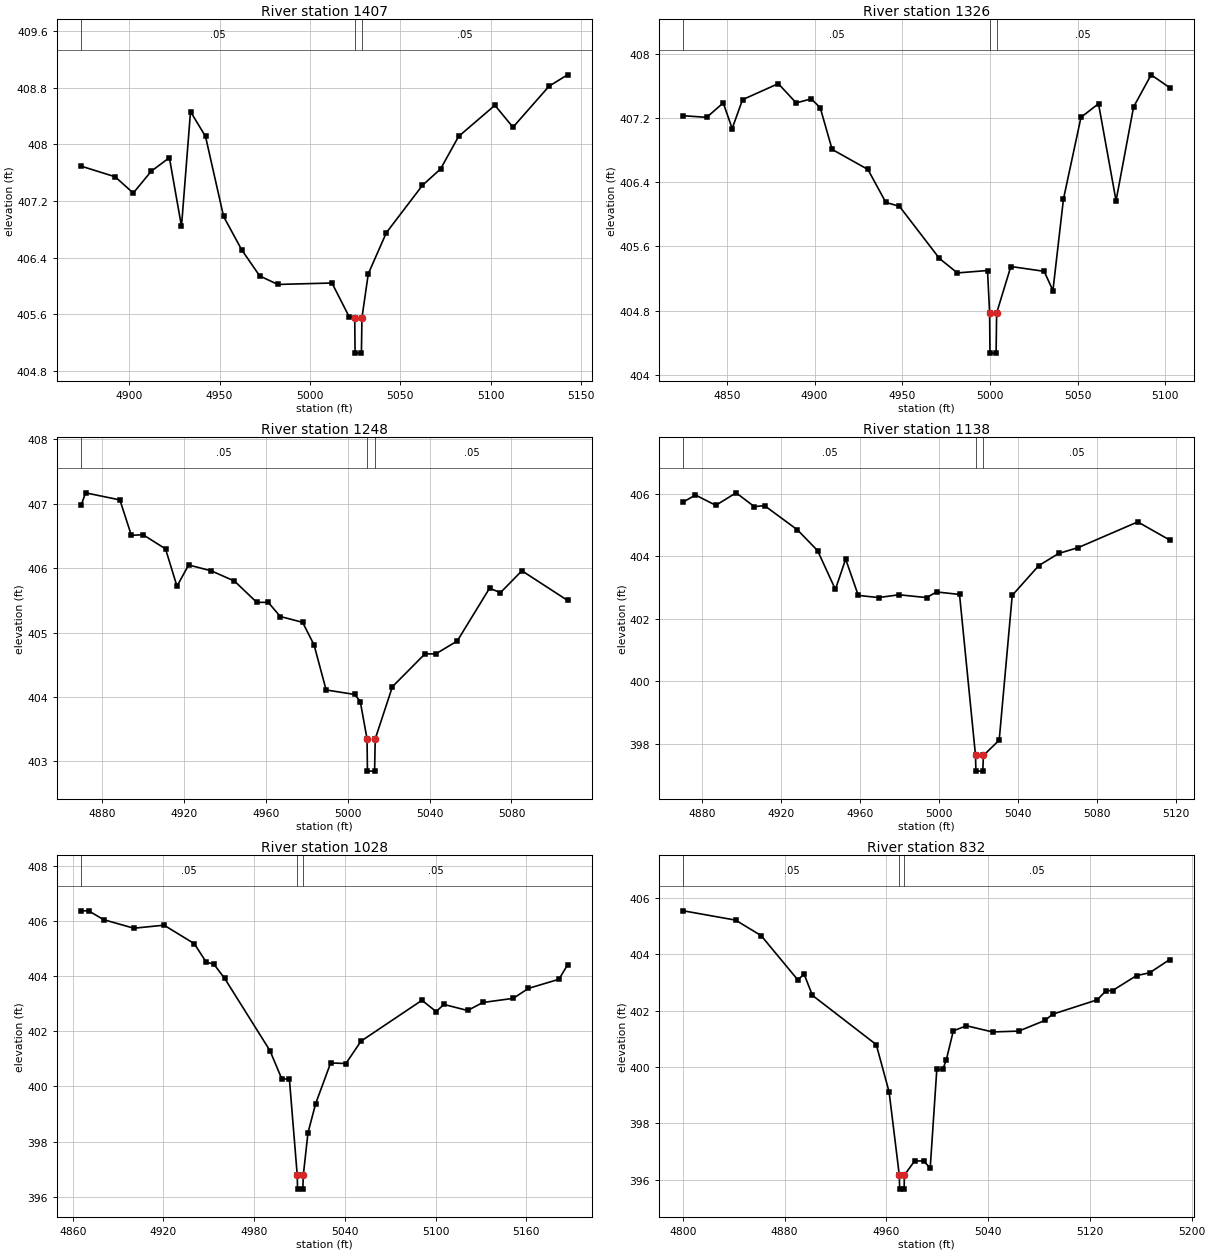
Type RM Length L Ch R = 1,1407,81,81,81
BEGIN DESCRIPTION:
Lacy 163 674
END DESCRIPTION:
XS GIS Cut Line= 3
      2721294.76      6846517.31      2721168.19      6846514.41
      2721025.85      6846523.05
#Sta/Elev= 27
  4873.4  407.69  4892.2  407.54  4902.2  407.31  4912.2  407.62  4922.2  407.81
  4928.9  406.84  4933.9  408.46  4942.2  408.11  4952.2  406.98  4962.2  406.51
  4972.2  406.14  4982.2  406.02  5012.2  406.04  5021.8  405.56  5024.8  405.55
  5025.0  405.05  5028.5  405.05  5028.8  405.55  5032.3  406.17  5042.3  406.75
  5062.3  407.42  5072.3  407.65  5082.3  408.11  5102.4  408.55  5112.4  408.24
  5132.4  408.82  5142.6  408.98
#Mann=3,-1,0
  4873.4    0.05       0  5024.8    0.04       0  5028.8    0.05       0
Bank Sta=5024.8,5028.8
Exp/Cntr=0.3,0.1

Type RM Length L Ch R = 1,1326,78,78,78
BEGIN DESCRIPTION:
Lacy 163 673
END DESCRIPTION:
XS GIS Cut Line= 3
      2721299.00      6846481.46      2721124.77      6846445.46
      2721025.39      6846447.14
#Sta/Elev= 30
  4825.2  407.23  4838.5  407.21  4847.9  407.39  4853.0  407.07  4858.9  407.43
  4879.3  407.63  4889.5  407.39  4898.1  407.44  4903.2  407.33  4910.0  406.81
  4930.4  406.56  4940.6  406.15  4948.4  406.10  4971.2  405.45  4981.4  405.27
  4998.6  405.30  4999.8  404.77  5000.0  404.27  5003.5  404.27  5003.8  404.77
  5011.9  405.35  5030.9  405.29  5035.9  405.05  5041.9  406.19  5051.9  407.21
  5061.9  407.38  5071.9  406.17  5081.9  407.34  5091.9  407.74  5102.5  407.58
#Mann=3,-1,0
  4825.2    0.05       0  4999.8    0.05       0  5003.8    0.05       0
Bank Sta=4999.8,5003.8
Exp/Cntr=0.3,0.1

Type RM Length L Ch R = 1,1248,110,110,110
BEGIN DESCRIPTION:
Lacy 163 672
END DESCRIPTION:
XS GIS Cut Line= 3
      2721272.94      6846436.93      2721153.47      6846376.89
      2721054.83      6846343.96
#Sta/Elev= 30
  4869.7  406.98  4871.8  407.17  4888.6  407.06  4894.2  406.51  4899.9  406.52
  4910.9  406.30  4916.5  405.72  4922.2  406.05  4933.2  405.96  4944.6  405.80
  4955.5  405.47  4961.1  405.47  4967.0  405.25  4977.9  405.16  4983.5  404.81
  4989.4  404.11  5003.4  404.04  5006.1  403.93  5009.4  403.35  5009.6  402.85
  5013.1  402.85  5013.4  403.35  5021.8  404.16  5037.7  404.67  5043.0  404.67
  5053.5  404.87  5069.3  405.69  5074.6  405.62  5085.1  405.96  5107.4  405.50
#Mann=3,-1,0
  4869.7    0.05       0  5009.4    0.04       0  5013.4    0.05       0
Bank Sta=5009.4,5013.4
Exp/Cntr=0.3,0.1

Type RM Length L Ch R = 1,1138,110,110,110
BEGIN DESCRIPTION:
Lacy 163 671
END DESCRIPTION:
XS GIS Cut Line= 3
      2721301.92      6846305.77      2721173.94      6846273.50
      2721059.79      6846281.39
#Sta/Elev= 27
  4870.6  405.74  4876.7  405.96  4887.0  405.63  4897.3  406.03  4906.5  405.59
  4911.7  405.62  4928.3  404.85  4938.6  404.18  4947.6  402.94  4952.8  403.91
  4959.2  402.75  4969.5  402.68  4979.8  402.77  4993.8  402.68  4998.9  402.86
  5010.5  402.78  5018.6  397.63  5018.8  397.13  5022.3  397.13  5022.6  397.63
  5030.6  398.12  5037.2  402.75  5050.6  403.70  5060.7  404.09  5070.7  404.28
  5100.8  405.10  5117.0  404.52
#Mann=3,-1,0
  4870.6    0.05       0  5018.6    0.04       0  5022.6    0.05       0
Bank Sta=5018.6,5022.6
Exp/Cntr=0.3,0.1

Type RM Length L Ch R = 1,1028,196,196,196
BEGIN DESCRIPTION:
Lacy 163 669
END DESCRIPTION:
XS GIS Cut Line= 3
      2721310.76      6846168.83      2721175.35      6846164.35
      2720990.31      6846185.26
#Sta/Elev= 30
  4865.6  406.36  4870.5  406.36  4880.4  406.04  4900.4  405.73  4920.4  405.84
  4940.4  405.17  4948.3  404.50  4953.3  404.43  4960.4  403.92  4990.4  401.30
  4998.3  400.27  5003.3  400.27  5008.5  396.78  5008.7  396.28  5012.2  396.28
  5012.5  396.78  5015.6  398.32  5020.7  399.38  5030.6  400.85  5040.7  400.83
  5050.7  401.64  5091.0  403.12  5100.4  402.71  5105.5  402.97  5121.2  402.75
  5131.3  403.04  5151.4  403.19  5161.4  403.55  5181.6  403.88  5187.3  404.40
#Mann=3,-1,0
  4865.6    0.05       0  5008.5    0.04       0  5012.5    0.05       0
Bank Sta=5008.5,5012.5
Exp/Cntr=0.3,0.1

Type RM Length L Ch R = 1,832,140,140,140
BEGIN DESCRIPTION:
Lacy 163 670
END DESCRIPTION:
XS GIS Cut Line= 3
      2721276.82      6846025.57      2721076.28      6846004.93
      2720900.63      6846047.36
#Sta/Elev= 30
  4800.4  405.55  4841.4  405.22  4861.5  404.67  4890.3  403.10  4895.3  403.30
  4901.8  402.55  4952.0  400.80  4962.1  399.12  4970.1  396.17  4970.4  395.67
  4973.9  395.67  4974.1  396.17  4982.2  396.67  4989.4  396.67  4994.4  396.41
  4999.6  399.92  5004.3  399.92  5007.0  400.25  5012.6  401.29  5022.9  401.47
  5043.4  401.25  5064.0  401.28  5084.6  401.66  5090.7  401.88  5125.7  402.39
  5132.6  402.71  5137.8  402.72  5156.6  403.25  5166.9  403.35  5182.7  403.82
#Mann=3,-1,0
  4800.4    0.05       0  4970.1    0.05       0  4974.1    0.05       0
Bank Sta=4970.1,4974.1
Exp/Cntr=0.3,0.1

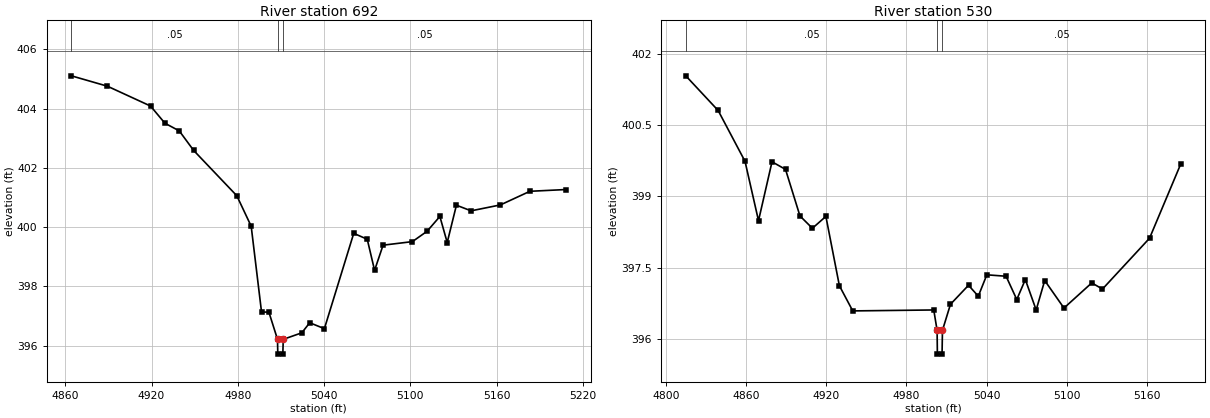
Type RM Length L Ch R = 1,692,162,162,162
BEGIN DESCRIPTION:
Lacy 163 679
END DESCRIPTION:
XS GIS Cut Line= 3
      2721261.01      6845883.87      2721126.59      6845880.94
      2720921.16      6845922.78
#Sta/Elev= 30
  4864.3  405.11  4889.3  404.76  4919.3  404.09  4929.3  403.51  4939.3  403.25
  4949.3  402.59  4979.3  401.06  4989.3  400.03  4996.5  397.13  5001.6  397.13
  5007.6  396.21  5007.8  395.71  5011.3  395.71  5011.6  396.21  5024.5  396.43
  5030.0  396.77  5040.2  396.57  5060.6  399.79  5070.0  399.59  5075.1  398.54
  5081.0  399.39  5101.4  399.51  5111.6  399.86  5120.5  400.36  5125.6  399.48
  5132.0  400.74  5142.2  400.55  5162.6  400.75  5183.1  401.21  5208.4  401.27
#Mann=3,-1,0
  4864.3    0.05       0  5007.6    0.04       0  5011.6    0.05       0
Bank Sta=5007.6,5011.6
Exp/Cntr=0.3,0.1

Type RM Length L Ch R = 1,530,0,0,0
BEGIN DESCRIPTION:
Lacy 163 678
END DESCRIPTION:
XS GIS Cut Line= 3
      2721259.98      6845756.07      2721078.07      6845733.34
      2720931.92      6845849.80
#Sta/Elev= 30
  4814.9  401.54  4839.1  400.81  4859.2  399.74  4869.3  398.49  4879.4  399.73
  4889.5  399.57  4900.3  398.59  4909.6  398.33  4919.7  398.58  4929.8  397.12
  4939.8  396.59  5000.4  396.61  5002.9  396.18  5003.1  395.68  5006.6  395.68
  5006.9  396.18  5012.9  396.73  5026.4  397.13  5033.7  396.90  5040.1  397.35
  5054.5  397.32  5062.5  396.83  5068.9  397.25  5077.0  396.61  5083.4  397.23
  5097.8  396.65  5118.6  397.18  5126.6  397.05  5161.8  398.12  5185.1  399.68
#Mann=3,-1,0
  4814.9    0.05       0  5002.9    0.05       0  5006.9    0.05       0
Bank Sta=5002.9,5006.9
Exp/Cntr=0.3,0.1

Chan Stop Cuts=-1