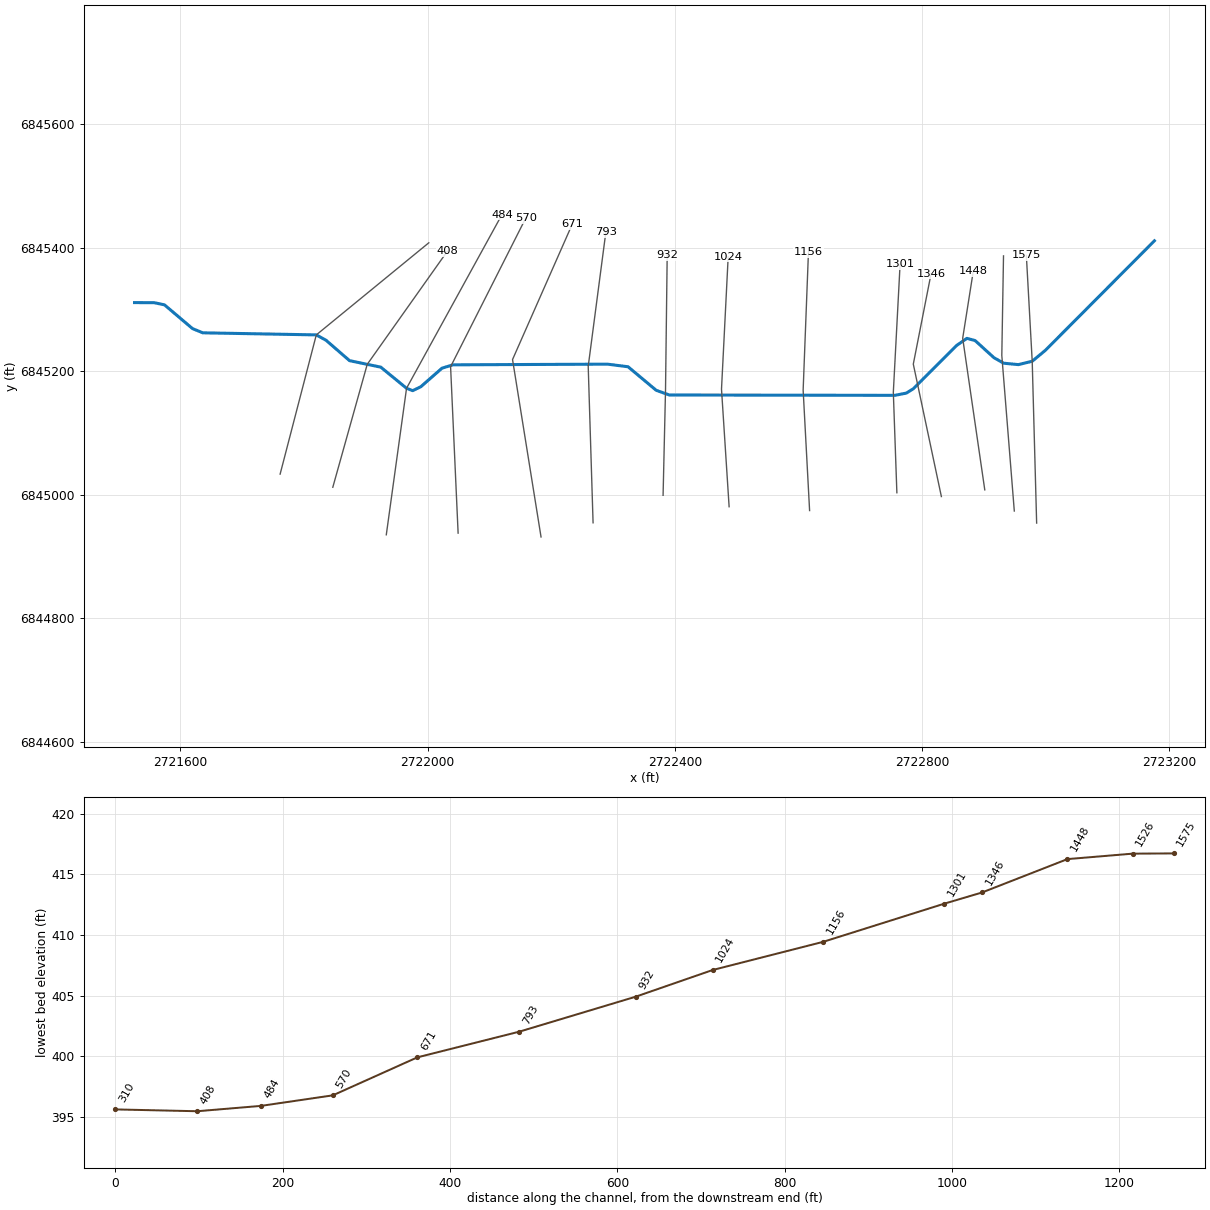
--- Lacy 164.prj (project) ---

Proj Title=Lacy 164 Base Level Engineering
Current Plan=p01
Default Exp/Contr=0.3,0.1
English Units
Geom File=g01
Flow File=f01
Plan File=p01
Y Axis Title=Elevation
X Axis Title(PF)=Main Channel Distance
X Axis Title(XS)=Station
BEGIN DESCRIPTION:
Lacy 164
END DESCRIPTION:
DSS Export Rating Curves= 0
DSS Export Rating Curve Sorted= 0
DSS Export Volume Flow Curves= 0
DXF OffsetX= 0
DXF OffsetY= 0
DXF ScaleX= 1
DXF ScaleY= 10

--- Lacy 164.p01 (plan) ---

Plan Title=Multiple Run
Short Identifier=Multiple
Geom File=g01
Flow File=f01
Subcritical Flow
K Sum by GR= 0
Std Step Tol= 0.01
Critical Tol= 0.01
Num of Std Step Trials= 20
Max Error Tol= 0.3
Flow Tol Ratio= 0.001
Split Flow NTrial= 30
Split Flow Tol= 0.02
Split Flow Ratio= 0.02
Log Output Level= 0
Friction Slope Method= 1
Unsteady Friction Slope Method= 2
Unsteady Bridges Friction Slope Method= 1
Parabolic Critical Depth
Global Vel Dist=  1 , 1 , 1
Global Log Level= 0
CheckData=True
Encroach Param= -1, 0, 0, 0
BEGIN DESCRIPTION:
Multiple Run
END DESCRIPTION:

--- Lacy 164.f01 (steady flow) ---

Flow Title=Multiple
Number of Profiles=7
Profile Names=10-year,25-year,50-year,1pct_min,100-year,1pct_plu,500-year
River Rch & RM= Lacy 164,Reach-1,1575
      76      88      96      53     105     209     124
Boundary for River Rch & Prof#=Lacy 164,Reach-1,1
Up Type=0
Dn Type=3
Dn Slope=0.005
Boundary for River Rch & Prof#=Lacy 164,Reach-1,2
Up Type=0
Dn Type=3
Dn Slope=0.005
Boundary for River Rch & Prof#=Lacy 164,Reach-1,3
Up Type=0
Dn Type=3
Dn Slope=0.005
Boundary for River Rch & Prof#=Lacy 164,Reach-1,4
Up Type=0
Dn Type=3
Dn Slope=0.005
Boundary for River Rch & Prof#=Lacy 164,Reach-1,5
Up Type=0
Dn Type=3
Dn Slope=0.005
Boundary for River Rch & Prof#=Lacy 164,Reach-1,6
Up Type=0
Dn Type=3
Dn Slope=0.005
Boundary for River Rch & Prof#=Lacy 164,Reach-1,7
Up Type=0
Dn Type=3
Dn Slope=0.005

--- Lacy 164.g01 (geometry) ---

Geom Title=Existing Conditions
Program Version=4.10

River Reach=Lacy 164        ,Reach-1
Reach XY= 30
        2723176.        6845411.      2722999.47      6845233.71
      2722978.29      6845216.11      2722955.84      6845210.68
      2722932.05      6845212.99      2722916.32      6845221.93
      2722885.87      6845249.61       2722872.6      6845253.16
      2722855.99      6845241.66       2722785.8      6845171.52
      2722774.54      6845164.56      2722756.02      6845160.97
      2722391.22      6845161.52      2722369.94      6845169.14
      2722324.43      6845207.22      2722291.18      6845211.43
      2722041.16      6845210.34      2722023.55      6845204.98
       2721989.2      6845174.94      2721975.99      6845168.53
      2721966.07      6845172.42      2721924.36      6845206.58
      2721873.83      6845217.09      2721835.67       6845250.2
      2721820.07      6845258.76      2721636.46      6845262.12
      2721619.84      6845268.89      2721574.49      6845307.35
       2721557.8      6845310.88        2721526.        6845311.

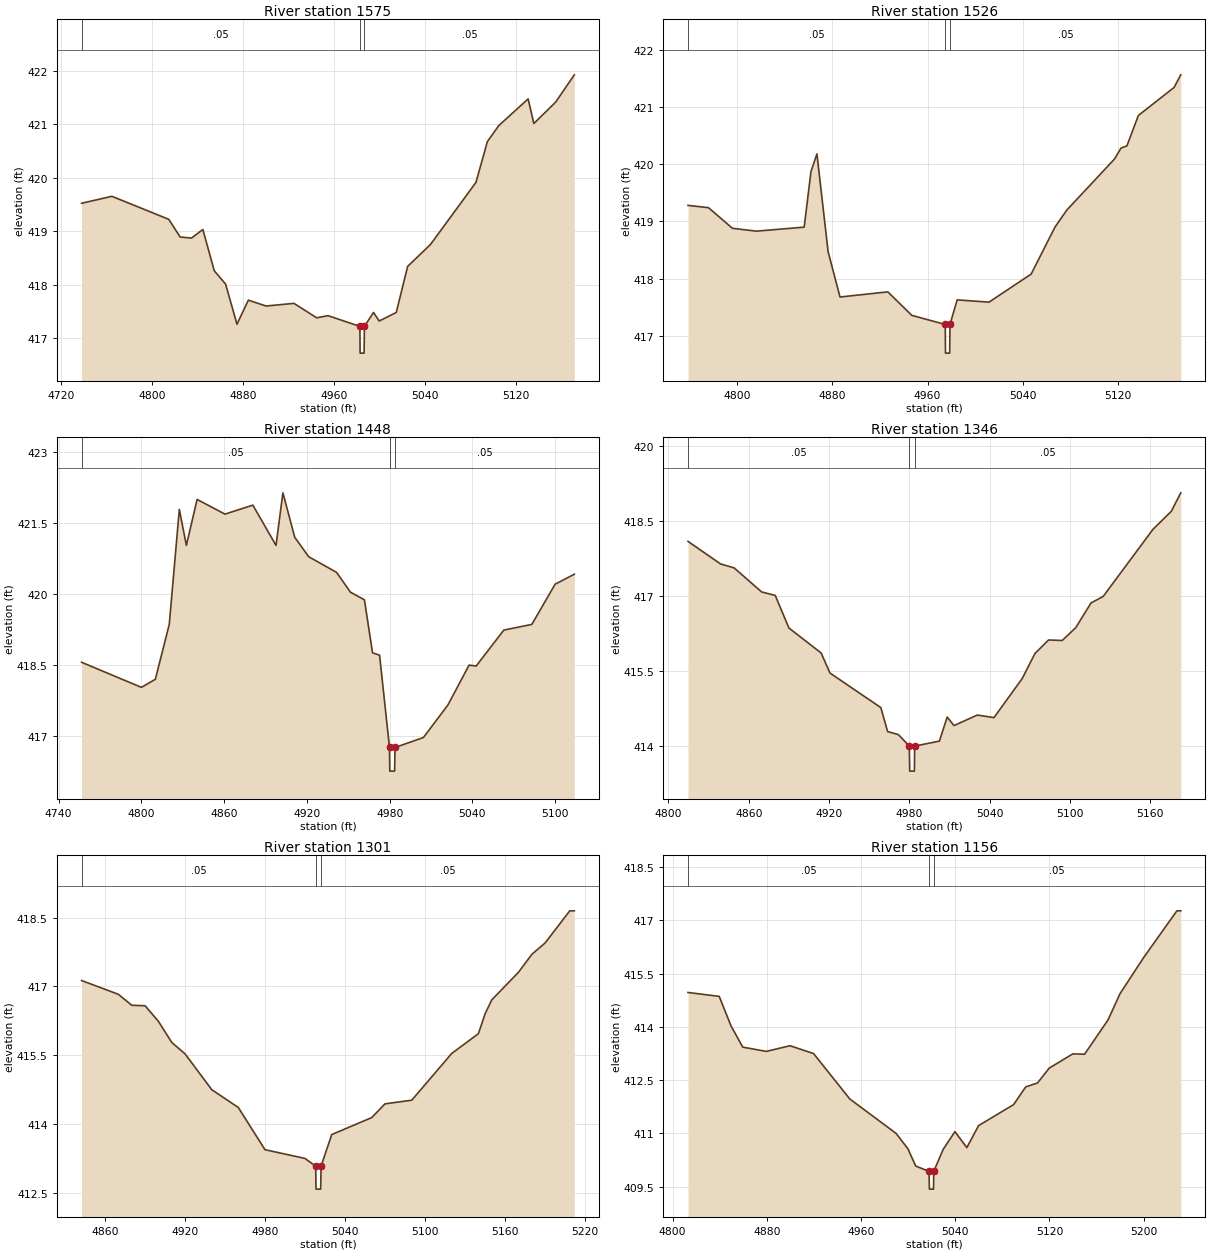
Type RM Length L Ch R = 1 ,1575    ,49,49,49
BEGIN DESCRIPTION:
Lacy 164 715
END DESCRIPTION:
XS GIS Cut Line= 3
      2722985.46      6844954.31      2722978.29      6845216.11
       2722968.8      6845387.35
#Sta/Elev= 30
  4738.1  419.52  4764.8  419.65  4814.8  419.22  4824.8  418.89  4834.8  418.87
  4844.8  419.03  4854.8  418.26  4864.8  418.01  4874.8  417.26  4884.8  417.71
  4900.4   417.6  4924.9  417.65  4944.9  417.38  4954.9  417.42  4982.9  417.22
  4983.1  416.72  4986.6  416.72  4986.9  417.22  4994.9  417.48  4999.9  417.32
  5014.9  417.48  5024.9  418.34    5045  418.75    5085  419.91    5095  420.67
    5105  420.97  5130.9  421.47  5135.9  421.01  5155.1  421.41  5171.5  421.92
#Mann= 3 ,-1 , 0
  4738.1     .05       0  4982.9     .04       0  4986.9     .05       0
Bank Sta=4982.9,4986.9
XS Rating Curve= 0 ,0
Exp/Cntr=0.3,0.1

Type RM Length L Ch R = 1 ,1526    ,78,78,78
BEGIN DESCRIPTION:
Lacy 164 3408
END DESCRIPTION:
XS GIS Cut Line= 3
      2722949.31      6844973.82       2722929.1      6845225.59
      2722931.85      6845386.58
#Sta/Elev= 26
  4758.9  419.28  4776.1  419.24  4796.2  418.88  4816.3  418.83  4856.4   418.9
  4862.1  419.87  4867.1  420.18  4876.5  418.47  4886.5  417.68  4926.6  417.77
  4946.7  417.36  4974.8   417.2    4975   416.7  4978.5   416.7  4978.8   417.2
  4984.8  417.63  5011.5  417.59  5046.9  418.08  5066.9   418.9  5076.9   419.2
  5116.9  420.09  5122.3  420.28  5127.3  420.32  5136.9  420.85  5166.9  421.34
  5172.5  421.56
#Mann= 3 ,-1 , 0
  4758.9     .05       0  4974.8     .04       0  4978.8     .05       0
Bank Sta=4974.8,4978.8
XS Rating Curve= 0 ,0
Exp/Cntr=0.3,0.1

Type RM Length L Ch R = 1 ,1448    ,102,102,102
BEGIN DESCRIPTION:
Lacy 164 3407
END DESCRIPTION:
XS GIS Cut Line= 3
      2722901.54      6845008.06      2722865.82      6845253.34
      2722882.88      6845361.43
#Sta/Elev= 30
  4756.6  418.55    4800  418.02  4810.1  418.19  4820.2  419.35  4827.5  421.78
  4832.6  421.02  4840.4  421.99  4860.6  421.68  4880.8  421.87  4897.6  421.02
  4902.6  422.13  4911.2  421.19  4921.3  420.78  4941.5  420.45  4951.6  420.03
  4961.7  419.87  4967.6  418.75  4972.7   418.7  4979.9  416.75  4980.1  416.25
  4983.6  416.25  4983.9  416.75  5004.5  416.96  5022.3  417.65  5037.6  418.49
  5042.7  418.47  5062.8  419.23  5083.1  419.35    5100   420.2  5113.9  420.41
#Mann= 3 ,-1 , 0
  4756.6     .05       0  4979.9     .04       0  4983.9     .05       0
Bank Sta=4979.9,4983.9
XS Rating Curve= 0 ,0
Exp/Cntr=0.3,0.1

Type RM Length L Ch R = 1 ,1346    ,45,45,45
BEGIN DESCRIPTION:
Lacy 164 3406
END DESCRIPTION:
XS GIS Cut Line= 3
      2722831.33      6844997.23      2722785.91      6845211.49
       2722814.7      6845357.96
#Sta/Elev= 30
  4814.6  418.09  4838.9  417.64  4849.1  417.56  4869.6  417.08  4879.8  417.01
    4890  416.36  4914.1  415.86  4920.7  415.46  4958.7  414.77  4963.8  414.29
  4971.8  414.23    4980     414  4980.3   413.5  4983.8   413.5    4984     414
  5002.5   414.1  5008.3  414.58  5013.4  414.41  5030.8  414.62  5043.3  414.57
  5064.4  415.35  5073.9  415.85  5084.1  416.12  5094.3  416.11  5104.5  416.37
  5115.8  416.86  5124.9  416.99  5162.1  418.33  5175.8  418.69  5182.9  419.06
#Mann= 3 ,-1 , 0
  4814.6     .05       0    4980     .04       0    4984     .05       0
Bank Sta=4980,4984
XS Rating Curve= 0 ,0
Exp/Cntr=0.3,0.1

Type RM Length L Ch R = 1 ,1301    ,145,145,145
BEGIN DESCRIPTION:
Lacy 164 684
END DESCRIPTION:
XS GIS Cut Line= 3
      2722759.34      6845003.37      2722753.59      6845165.85
      2722764.53      6845372.88
#Sta/Elev= 28
  4842.3  417.13  4869.9  416.83    4880  416.59    4890  416.58    4900  416.24
    4910  415.78    4920  415.53    4940  414.75    4960  414.36    4980  413.44
    5010  413.25  5018.1  413.08  5018.3  412.58  5021.8  412.58  5022.1  413.08
  5030.1  413.77  5060.1  414.14  5070.1  414.44  5090.2  414.52  5120.2  415.54
  5140.2  415.97  5145.3  416.41  5150.3  416.71  5170.3  417.31  5180.3   417.7
  5190.3  417.95  5208.8  418.65  5212.2  418.65
#Mann= 3 ,-1 , 0
  4842.3     .05       0  5018.1     .04       0  5022.1     .05       0
Bank Sta=5018.1,5022.1
XS Rating Curve= 0 ,0
Exp/Cntr=0.3,0.1

Type RM Length L Ch R = 1 ,1156    ,132,132,132
BEGIN DESCRIPTION:
Lacy 164 685
END DESCRIPTION:
XS GIS Cut Line= 3
      2722618.13      6844974.56      2722607.69      6845169.43
      2722616.28      6845392.61
#Sta/Elev= 30
  4813.1  414.97  4839.6  414.86  4849.6  414.03  4859.6  413.43  4879.6  413.31
  4899.7  413.47  4919.7  413.25  4950.5  411.97  4989.8     411  4999.8  410.57
  5006.5  410.08  5017.8  409.93  5018.1  409.43  5021.6  409.43  5021.8  409.93
  5029.8  410.55  5039.8  411.05  5049.9   410.6  5059.9  411.22  5089.6  411.81
  5099.9  412.31  5109.9  412.42  5119.9  412.84  5139.9  413.24  5149.9  413.23
  5169.9   414.2  5179.9  414.93    5200  415.95  5228.3  417.27  5231.6  417.27
#Mann= 3 ,-1 , 0
  4813.1     .05       0  5017.8     .04       0  5021.8     .05       0
Bank Sta=5017.8,5021.8
XS Rating Curve= 0 ,0
Exp/Cntr=0.3,0.1

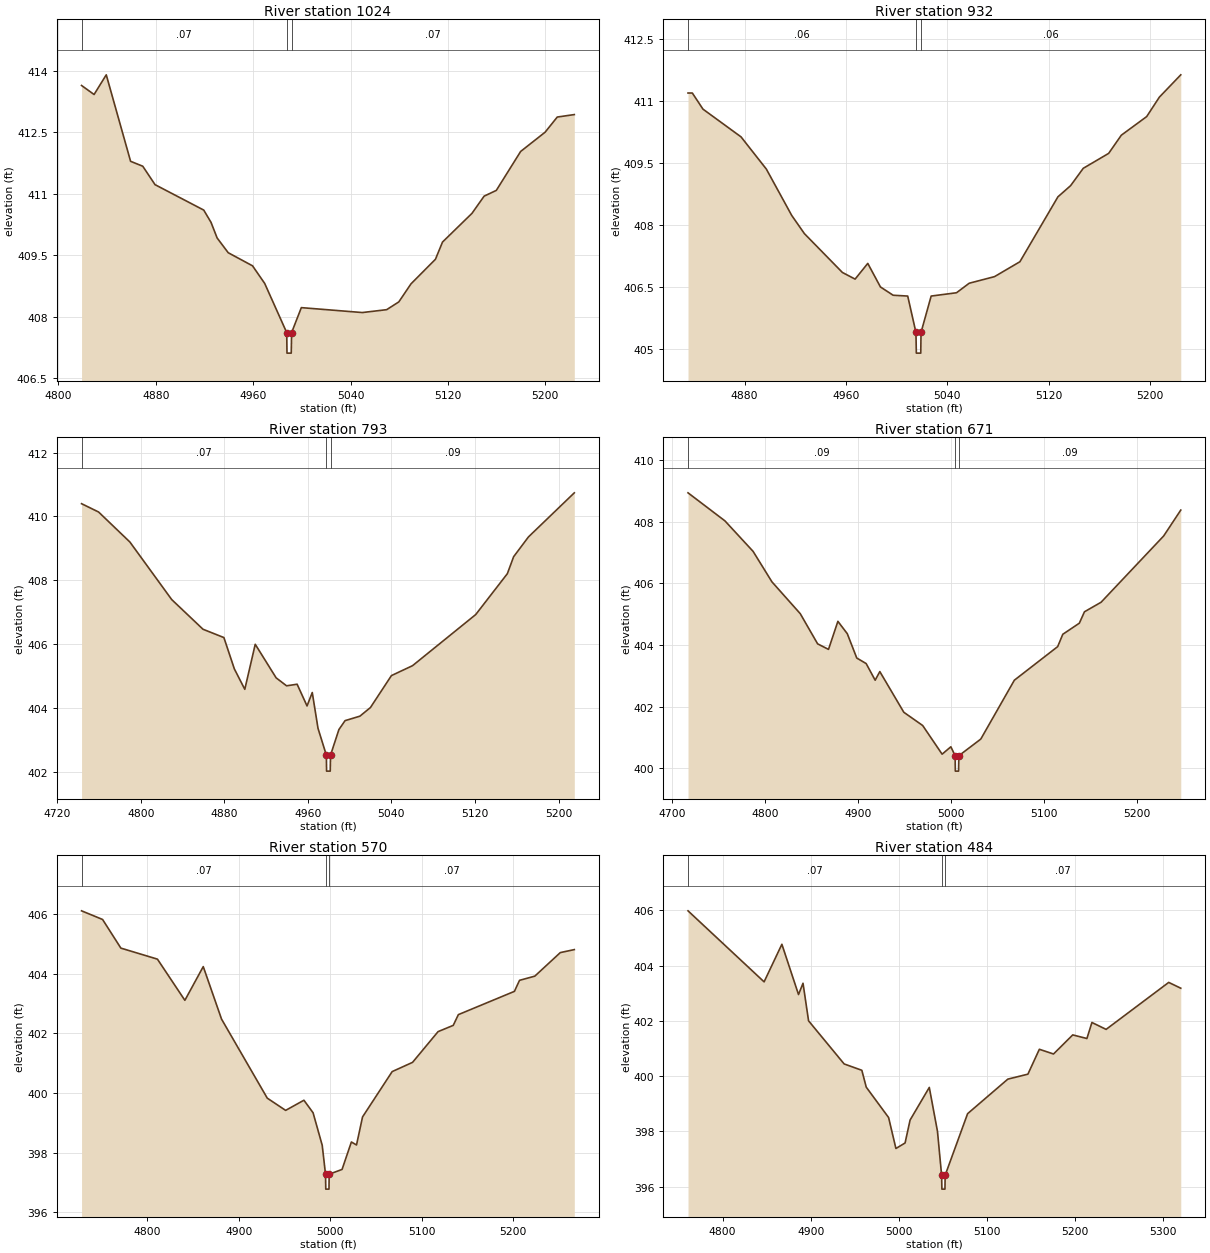
Type RM Length L Ch R = 1 ,1024    ,92,92,92
BEGIN DESCRIPTION:
Lacy 164 686
END DESCRIPTION:
XS GIS Cut Line= 3
      2722487.93      6844980.77      2722475.62        6845171.
      2722486.41        6845385.
#Sta/Elev= 30
    4819  413.64  4829.3  413.42  4839.3   413.9  4859.3  411.79  4869.3  411.67
  4879.4  411.22  4919.4   410.6  4925.4   410.3  4930.4  409.92  4939.5  409.56
  4959.5  409.24  4969.5  408.81  4987.6  407.61  4987.8  407.11  4991.3  407.11
  4991.6  407.61  4999.6  408.22  5049.7   408.1  5069.7  408.17  5079.7  408.36
  5089.7   408.8  5109.8   409.4  5115.6  409.82  5139.8  410.52  5149.8  410.94
  5159.8  411.08  5179.8  412.03  5199.9   412.5  5209.9  412.87  5223.9  412.93
#Mann= 3 ,-1 , 0
    4819     .07       0  4987.6     .03       0  4991.6     .07       0
Bank Sta=4987.6,4991.6
XS Rating Curve= 0 ,0
Exp/Cntr=0.3,0.1

Type RM Length L Ch R = 1 ,932     ,139,139,139
BEGIN DESCRIPTION:
Lacy 164 687
END DESCRIPTION:
XS GIS Cut Line= 3
       2722381.1      6844999.22      2722385.03      6845168.89
      2722387.75      6845387.86
#Sta/Elev= 30
  4835.4   411.2  4838.8   411.2  4847.2  410.81  4877.2  410.14  4897.2  409.36
  4917.2  408.24  4927.2   407.8  4957.2  406.86  4967.2   406.7  4977.2  407.08
  4987.2  406.51  4997.2  406.31  5008.7  406.29  5015.2  405.41  5015.5  404.91
    5019  404.91  5019.2  405.41  5027.2  406.29  5047.2  406.37  5057.2   406.6
  5077.2  406.76  5097.2  407.12  5127.2  408.69  5137.2  408.96  5147.2  409.38
  5167.2  409.74  5177.2  410.18  5197.2  410.63  5207.2   411.1  5224.1  411.64
#Mann= 3 ,-1 , 0
  4835.4     .06       0  5015.2     .05       0  5019.2     .06       0
Bank Sta=5015.2,5019.2
XS Rating Curve= 0 ,0
Exp/Cntr=0.3,0.1

Type RM Length L Ch R = 1 ,793     ,122,122,122
BEGIN DESCRIPTION:
Lacy 164 688
END DESCRIPTION:
XS GIS Cut Line= 3
      2722267.84      6844954.75      2722259.98       6845207.8
      2722288.45      6845424.57
#Sta/Elev= 30
  4743.3   410.4  4759.6  410.14  4789.6   409.2  4829.6   407.4  4859.6  406.47
  4879.6  406.21  4889.6  405.23  4899.6  404.59  4909.6     406  4929.6  404.95
  4939.6   404.7  4949.7  404.75  4959.2  404.07  4964.2  404.49  4969.7  403.37
  4977.7  402.53  4977.9  402.03  4981.4  402.03  4981.7  402.53  4989.7  403.33
  4995.6  403.61  5009.8  403.75  5019.9  404.02    5040  405.02  5060.2  405.33
  5120.7  406.93    5151  408.21    5157  408.74  5171.2  409.36  5215.1  410.74
#Mann= 3 ,-1 , 0
  4743.3     .07       0  4977.7     .05       0  4981.7     .09       0
Bank Sta=4977.7,4981.7
XS Rating Curve= 0 ,0
Exp/Cntr=0.3,0.1

Type RM Length L Ch R = 1 ,671     ,101,101,101
BEGIN DESCRIPTION:
Lacy 164 689
END DESCRIPTION:
XS GIS Cut Line= 3
      2722183.65      6844931.84      2722137.55      6845218.89
      2722234.12      6845437.81
#Sta/Elev= 30
  4717.5  408.94  4757.2  408.03  4787.5  407.04  4807.8  406.05  4838.2  405.02
  4856.9  404.04  4868.6  403.86  4878.7  404.77  4888.8  404.37    4899  403.58
  4909.1   403.4  4918.8  402.86  4923.8  403.14  4949.6  401.82  4969.9  401.39
  4990.8  400.46  5000.2   400.7  5004.8  400.41    5005  399.91  5008.5  399.91
  5008.8  400.41  5032.4  400.95  5068.5  402.86  5115.1  403.95  5120.6  404.35
  5138.4  404.71  5143.9  405.08  5161.8  405.39  5229.1  407.54  5247.5  408.38
#Mann= 3 ,-1 , 0
  4717.5     .09       0  5004.8     .04       0  5008.8     .09       0
Bank Sta=5004.8,5008.8
XS Rating Curve= 0 ,0
Exp/Cntr=0.3,0.1

Type RM Length L Ch R = 1 ,570     ,86,86,86
BEGIN DESCRIPTION:
Lacy 164 690
END DESCRIPTION:
XS GIS Cut Line= 3
       2722049.5      6844938.07      2722037.33      6845207.27
      2722158.91       6845447.7
#Sta/Elev= 30
    4728  406.11    4751  405.82    4771  404.86    4811  404.49    4841  403.11
  4861.1  404.24  4881.1  402.48  4931.1  399.83  4951.2  399.42  4971.2  399.76
  4981.2  399.34  4991.2  398.25  4994.8  397.28  4995.1  396.78  4998.6  396.78
  4998.8  397.28  5012.9  397.44  5023.1  398.36  5028.7  398.26  5035.3   399.2
  5067.7  400.72    5090  401.03  5117.9  402.06  5134.5  402.27  5140.1  402.63
  5201.4  403.41    5207  403.78  5223.7  403.92  5251.6  404.71  5266.9  404.81
#Mann= 3 ,-1 , 0
    4728     .07       0  4994.8     .04       0  4998.8     .07       0
Bank Sta=4994.8,4998.8
XS Rating Curve= 0 ,0
Exp/Cntr=0.3,0.1

Type RM Length L Ch R = 1 ,484     ,76,76,76
BEGIN DESCRIPTION:
Lacy 164 691
END DESCRIPTION:
XS GIS Cut Line= 3
       2721933.3      6844935.37      2721966.07      6845172.42
      2722120.29      6845453.15
#Sta/Elev= 30
  4760.7  405.98  4847.1  403.41  4867.3  404.77  4886.2  402.95  4891.3  403.36
  4897.6     402    4938  400.44  4958.1  400.21  4963.1   399.6  4988.5   398.5
  4996.8  397.38  5007.2  397.58  5012.9  398.41  5034.7  399.59    5044     398
  5048.7  396.41    5049  395.91  5052.5  395.91  5052.7  396.41  5078.2  398.64
  5123.9  399.89  5146.7  400.07  5159.7  400.97  5175.8   400.8  5197.6  401.49
  5213.7  401.36  5219.4  401.94  5235.5  401.69  5306.6  403.39  5320.3  403.18
#Mann= 3 ,-1 , 0
  4760.7     .07       0  5048.7     .04       0  5052.7     .07       0
Bank Sta=5048.7,5052.7
XS Rating Curve= 0 ,0
Exp/Cntr=0.3,0.1

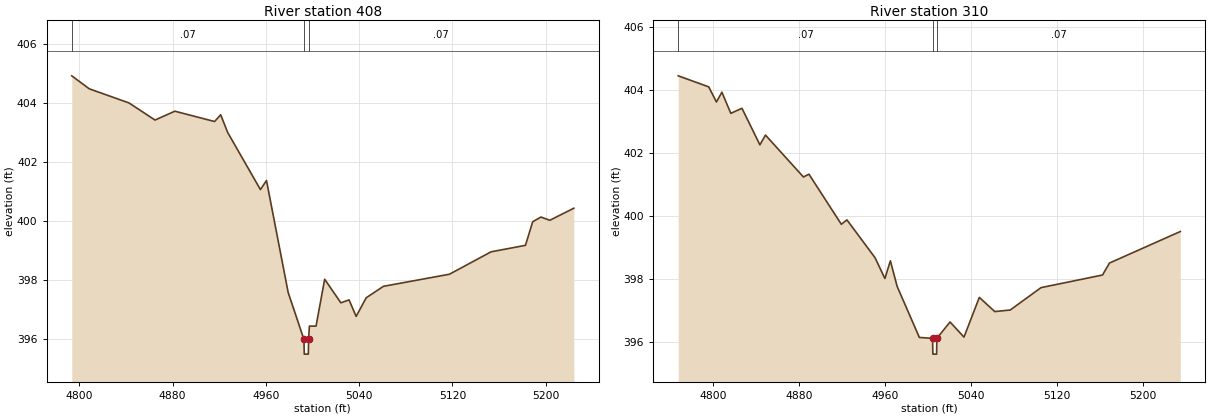
Type RM Length L Ch R = 1 ,408     ,98,98,98
BEGIN DESCRIPTION:
Lacy 164 682
END DESCRIPTION:
XS GIS Cut Line= 3
      2721846.77      6845012.29      2721902.47      6845211.13
        2722032.      6845394.01
#Sta/Elev= 30
  4793.5  404.91  4808.5  404.47  4842.6  403.99  4864.9  403.41  4881.9  403.71
    4916  403.36  4921.2  403.59  4927.2  402.99  4955.3  401.05  4960.5  401.36
  4979.1  397.56  4992.6  395.97  4992.9  395.47  4996.4  395.47  4996.6  395.97
  4997.3  396.42    5003  396.42  5010.4  398.01  5024.3  397.21  5031.3  397.31
  5037.4  396.75    5046  397.38  5060.8  397.77  5117.4  398.18  5153.1  398.94
  5182.6  399.16  5188.8  399.96  5195.9  400.12  5203.5  400.01  5224.1  400.42
#Mann= 3 ,-1 , 0
  4793.5     .07       0  4992.6     .04       0  4996.6     .07       0
Bank Sta=4992.6,4996.6
XS Rating Curve= 0 ,0
Exp/Cntr=0.3,0.1

Type RM Length L Ch R = 1 ,310     ,0,0,0
BEGIN DESCRIPTION:
Lacy 164 683
END DESCRIPTION:
XS GIS Cut Line= 3
      2721761.54      6845033.54      2721820.07      6845258.76
      2722002.06      6845407.75
#Sta/Elev= 30
  4767.3  404.45  4795.7   404.1  4802.9  403.62    4808  403.93  4816.3  403.26
  4826.7  403.42  4843.4  402.26  4848.6  402.57    4884  401.24  4889.1  401.33
  4919.3  399.74  4924.5  399.88  4950.7  398.68  4959.9  398.02    4965  398.58
  4971.3  397.77    4992  396.15  5004.3  396.12  5004.6  395.62  5008.1  395.62
  5008.3  396.12  5020.6  396.64  5033.6  396.16  5047.9  397.42  5062.3  396.97
  5076.7  397.02  5105.4  397.73  5162.7  398.13  5169.2  398.51  5235.2  399.51
#Mann= 3 ,-1 , 0
  4767.3     .07       0  5004.3     .04       0  5008.3     .07       0
Bank Sta=5004.3,5008.3
XS Rating Curve= 0 ,0
Exp/Cntr=0.3,0.1

Chan Stop Cuts=-1
Use User Specified Reach Order=0
Composite Channel Slope=5