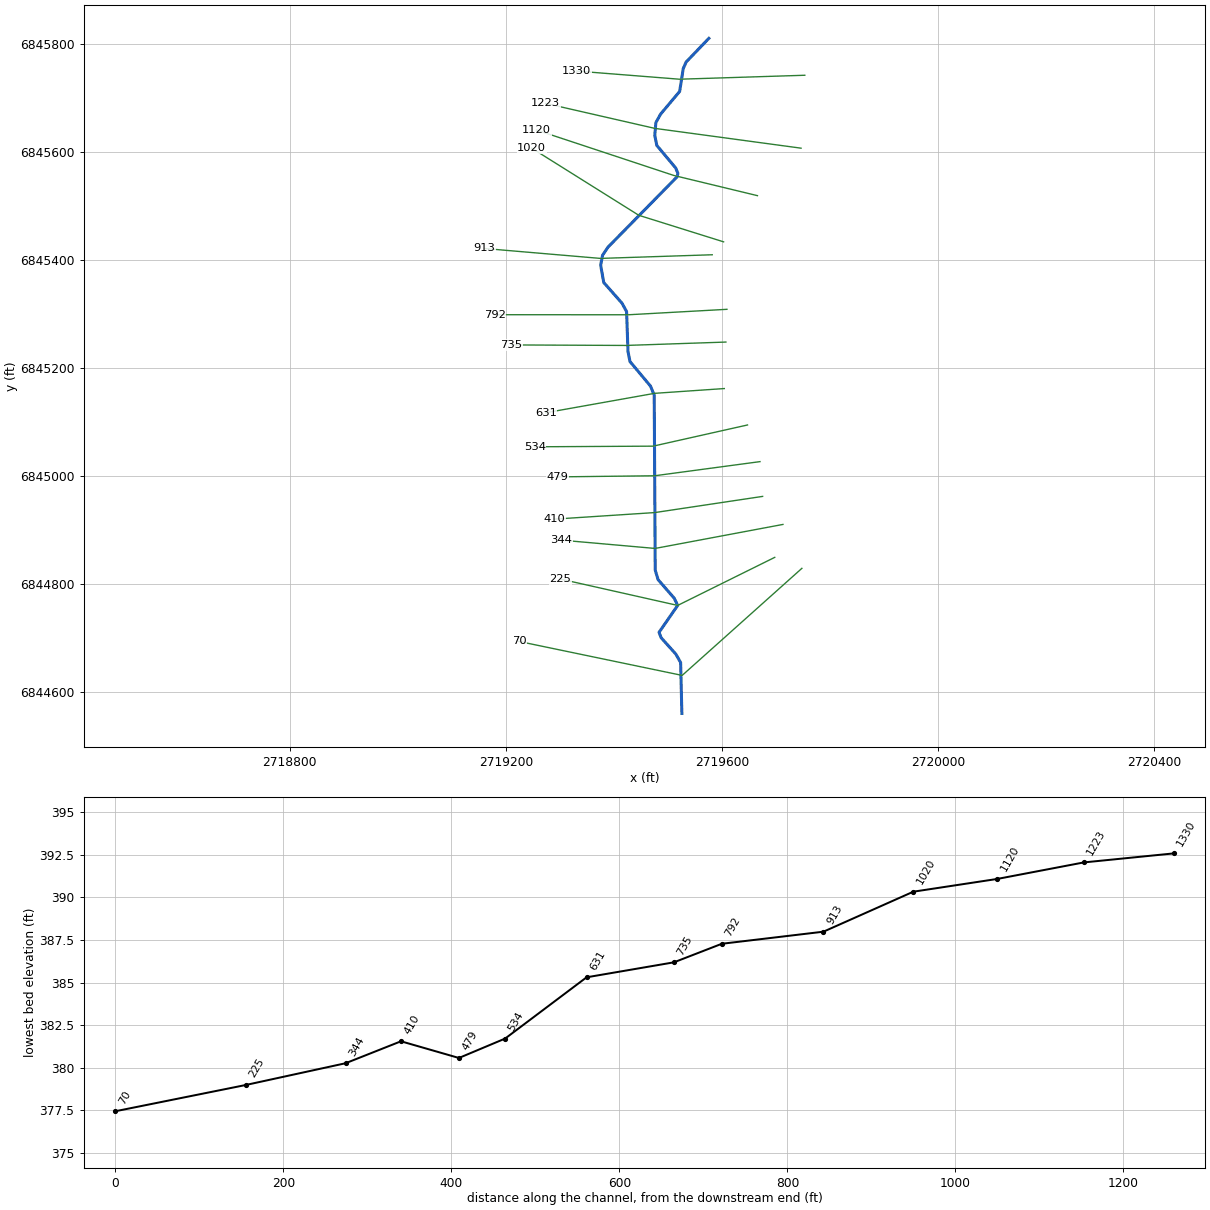
--- Lacy 165.prj (project) ---

Proj Title=Lacy 165 Base Level Engineering
Current Plan=p01
Default Exp/Contr=0.3,0.1
English Units
Geom File=g01
Flow File=f01
Plan File=p01
BEGIN DESCRIPTION:
Lacy 165
END DESCRIPTION:

--- Lacy 165.p01 (plan) ---

Plan Title=Multiple Run
Short Identifier=Multiple
Geom File=g01
Flow File=f01
Subcritical Flow
K Sum by GR= 0
Std Step Tol= 0.01
Critical Tol= 0.01
Num of Std Step Trials= 20
Max Error Tol= 0.3
Flow Tol Ratio= 0.001
Split Flow NTrial= 30
Split Flow Tol= 0.02
Split Flow Ratio= 0.02
Log Output Level= 0
Friction Slope Method= 1
Unsteady Friction Slope Method= 2
Unsteady Bridges Friction Slope Method= 1
Parabolic Critical Depth
Global Vel Dist=  1 , 1 , 1
Global Log Level= 0
CheckData=True
Encroach Param= -1, 0, 0, 0
BEGIN DESCRIPTION:
Multiple Run
END DESCRIPTION:

--- Lacy 165.f01 (steady flow) ---

Flow Title=Multiple
Number of Profiles=7
Profile Names=10-year,25-year,50-year,1pct_min,100-year,1pct_plu,500-year
River Rch & RM= Lacy 165,Reach-1,1330
     111     132     146      82     163     325     199
Boundary for River Rch & Prof#=Lacy 165,Reach-1,1
Up Type=0
Dn Type=3
Dn Slope=0.005
Boundary for River Rch & Prof#=Lacy 165,Reach-1,2
Up Type=0
Dn Type=3
Dn Slope=0.005
Boundary for River Rch & Prof#=Lacy 165,Reach-1,3
Up Type=0
Dn Type=3
Dn Slope=0.005
Boundary for River Rch & Prof#=Lacy 165,Reach-1,4
Up Type=0
Dn Type=3
Dn Slope=0.005
Boundary for River Rch & Prof#=Lacy 165,Reach-1,5
Up Type=0
Dn Type=3
Dn Slope=0.005
Boundary for River Rch & Prof#=Lacy 165,Reach-1,6
Up Type=0
Dn Type=3
Dn Slope=0.005
Boundary for River Rch & Prof#=Lacy 165,Reach-1,7
Up Type=0
Dn Type=3
Dn Slope=0.005

--- Lacy 165.g01 (geometry) ---

Geom Title=Existing Conditions

River Reach=Lacy 165,Reach-1
Reach XY= 30
      2719576.00      6845811.00      2719533.91      6845767.15
      2719528.50      6845754.96      2719521.89      6845712.67
      2719486.50      6845670.55      2719477.83      6845654.88
      2719475.82      6845631.13      2719479.61      6845612.63
      2719514.61      6845570.87      2719518.65      6845560.91
      2719516.85      6845554.27      2719389.12      6845424.22
      2719379.13      6845409.37      2719375.60      6845390.87
      2719381.35      6845358.83      2719415.05      6845320.65
      2719423.62      6845305.03      2719426.24      6845231.10
      2719429.86      6845212.60      2719467.86      6845167.06
      2719474.78      6845150.50      2719476.65      6844826.16
      2719482.00      6844808.55      2719511.93      6844774.16
      2719518.21      6844760.90      2719483.75      6844711.09
      2719487.54      6844701.15      2719514.77      6844670.82
      2719523.67      6844655.23      2719526.00      6844561.00

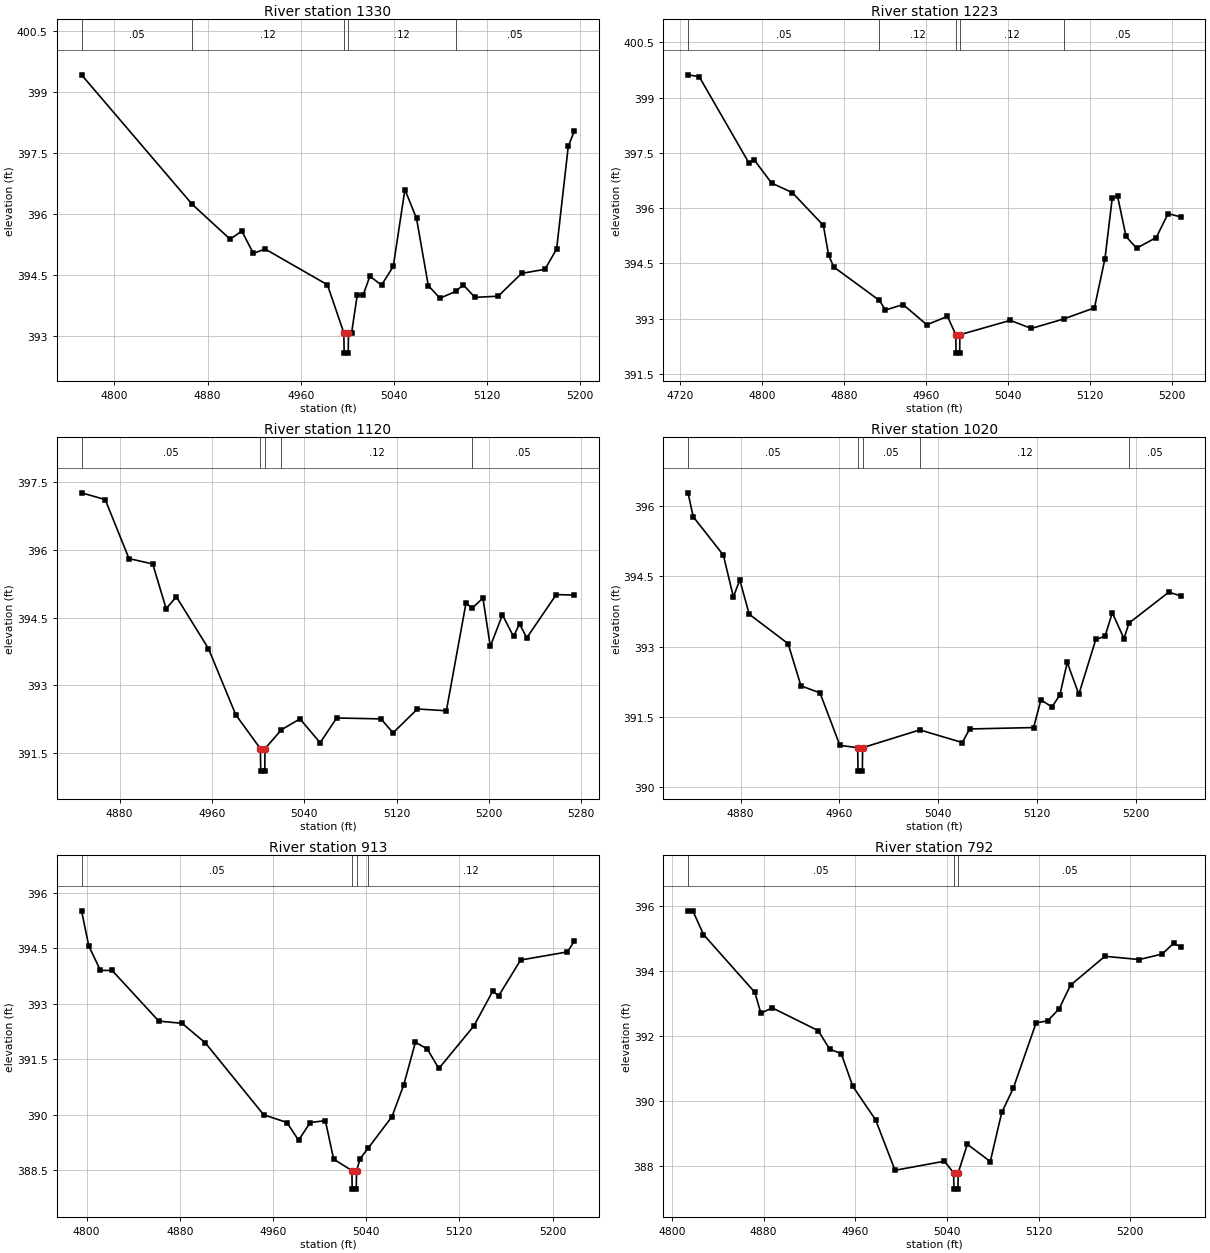
Type RM Length L Ch R = 1,1330,107,107,107
BEGIN DESCRIPTION:
Lacy 165 643
END DESCRIPTION:
XS GIS Cut Line= 3
      2719753.63      6845742.63      2719521.65      6845735.30
      2719330.85      6845750.40
#Sta/Elev= 30
  4771.7  399.43  4866.7  396.25  4899.4  395.39  4909.4  395.59  4919.4  395.04
  4929.4  395.15  4983.0  394.27  4997.1  393.09  4997.4  392.59  5000.9  392.59
  5001.1  393.09  5003.8  393.09  5008.6  394.01  5013.6  394.01  5019.5  394.48
  5029.5  394.26  5039.6  394.72  5049.6  396.61  5059.6  395.90  5069.7  394.25
  5079.7  393.94  5093.5  394.11  5099.7  394.27  5109.8  393.96  5129.8  393.99
  5149.9  394.55  5170.0  394.65  5180.0  395.15  5190.0  397.67  5195.2  398.05
#Mann=5,-1,0
  4771.7    0.05       0  4866.7    0.12       0  4997.1    0.07       0
  5001.1    0.12       0  5093.5    0.05       0
Bank Sta=4997.1,5001.1
Exp/Cntr=0.3,0.1

Type RM Length L Ch R = 1,1223,103,103,103
BEGIN DESCRIPTION:
Lacy 165 649
END DESCRIPTION:
XS GIS Cut Line= 3
      2719746.76      6845607.59      2719475.67      6845644.31
      2719273.95      6845690.47
#Sta/Elev= 30
  4727.7  399.62  4738.6  399.57  4787.2  397.22  4792.2  397.31  4809.2  396.68
  4829.4  396.42  4859.7  395.53  4864.8  394.72  4869.8  394.40  4914.4  393.49
  4920.2  393.23  4937.4  393.38  4960.6  392.83  4980.7  393.06  4988.8  392.56
  4989.1  392.06  4992.6  392.06  4992.8  392.56  5042.0  392.95  5062.5  392.73
  5094.2  392.99  5124.0  393.29  5134.3  394.63  5141.4  396.28  5146.5  396.33
  5154.8  395.23  5165.1  394.91  5184.3  395.20  5195.8  395.85  5208.2  395.76
#Mann=5,-1,0
  4727.7    0.05       0  4914.4    0.12       0  4988.8    0.07       0
  4992.8    0.12       0  5094.2    0.05       0
Bank Sta=4988.8,4992.8
Exp/Cntr=0.3,0.1

Type RM Length L Ch R = 1,1120,100,100,100
BEGIN DESCRIPTION:
Lacy 165 648
END DESCRIPTION:
XS GIS Cut Line= 3
      2719665.94      6845519.69      2719510.85      6845557.15
      2719256.84      6845641.21
#Sta/Elev= 30
  4847.0  397.27  4867.5  397.12  4888.1  395.81  4908.7  395.69  4920.3  394.70
  4929.2  394.96  4957.0  393.81  4980.7  392.34  5002.0  391.59  5002.3  391.09
  5005.8  391.09  5006.0  391.59  5020.3  392.01  5036.3  392.25  5053.8  391.72
  5068.1  392.27  5106.5  392.25  5117.0  391.94  5138.1  392.47  5163.2  392.43
  5180.2  394.82  5185.5  394.71  5194.9  394.93  5201.3  393.86  5211.8  394.56
  5221.4  394.08  5226.6  394.36  5232.9  394.05  5258.4  395.01  5274.1  395.00
#Mann=5,-1,0
  4847.0    0.05       0  5002.0    0.04       0  5006.0    0.05       0
  5020.3    0.12       0  5185.5    0.05       0
Bank Sta=5002,5006
Exp/Cntr=0.3,0.1

Type RM Length L Ch R = 1,1020,107,107,107
BEGIN DESCRIPTION:
Lacy 165 647
END DESCRIPTION:
XS GIS Cut Line= 3
      2719603.26      6845434.17      2719446.24      6845483.33
      2719247.74      6845607.73
#Sta/Elev= 30
  4837.5  396.28  4841.7  395.77  4866.1  394.95  4874.2  394.06  4879.4  394.42
  4887.0  393.69  4918.5  393.06  4928.9  392.16  4944.3  392.01  4960.4  390.89
  4974.8  390.84  4975.1  390.34  4978.6  390.34  4978.8  390.84  5025.1  391.22
  5059.5  390.95  5065.4  391.24  5117.2  391.27  5123.1  391.86  5132.1  391.71
  5138.5  391.97  5144.4  392.66  5153.8  391.98  5167.5  393.15  5175.0  393.22
  5180.9  393.72  5190.3  393.17  5194.4  393.50  5226.6  394.16  5236.3  394.08
#Mann=5,-1,0
  4837.5    0.05       0  4974.8    0.04       0  4978.8    0.05       0
  5025.1    0.12       0  5194.4    0.05       0
Bank Sta=4974.8,4978.8
Exp/Cntr=0.3,0.1

Type RM Length L Ch R = 1,913,121,121,121
BEGIN DESCRIPTION:
Lacy 165 646
END DESCRIPTION:
XS GIS Cut Line= 3
      2719582.22      6845410.24      2719375.14      6845403.48
      2719160.11      6845421.86
#Sta/Elev= 30
  4795.7  395.51  4801.9  394.56  4811.9  393.90  4821.9  393.90  4862.0  392.53
  4882.0  392.47  4902.0  391.94  4952.0  390.00  4972.0  389.79  4982.0  389.31
  4992.0  389.79  5005.0  389.84  5012.1  388.80  5027.8  388.49  5028.0  387.99
  5031.5  387.99  5031.8  388.49  5034.8  388.81  5041.8  389.10  5062.2  389.95
  5072.3  390.81  5082.3  391.96  5092.4  391.78  5102.4  391.25  5132.5  392.40
  5148.7  393.34  5153.7  393.21  5172.6  394.18  5212.8  394.40  5218.7  394.69
#Mann=4,-1,0
  4795.7    0.05       0  5027.8    0.04       0  5031.8    0.05       0
  5041.8    0.12       0
Bank Sta=5027.8,5031.8
Exp/Cntr=0.3,0.1

Type RM Length L Ch R = 1,792,57,57,57
BEGIN DESCRIPTION:
Lacy 165 644
END DESCRIPTION:
XS GIS Cut Line= 3
      2719609.45      6845309.21      2719427.30      6845299.13
      2719179.83      6845299.23
#Sta/Elev= 30
  4814.1  395.85  4818.3  395.85  4827.6  395.12  4872.4  393.34  4877.6  392.70
  4887.7  392.86  4927.7  392.16  4937.7  391.59  4947.8  391.45  4957.8  390.45
  4977.8  389.41  4994.7  387.86  5037.8  388.14  5045.8  387.78  5046.1  387.28
  5049.6  387.28  5049.8  387.78  5057.8  388.66  5077.8  388.13  5087.8  389.64
  5097.8  390.38  5117.8  392.40  5127.8  392.46  5137.8  392.83  5147.8  393.56
  5177.8  394.45  5207.8  394.35  5227.8  394.52  5237.8  394.85  5244.0  394.74
#Mann=3,-1,0
  4814.1    0.05       0  5045.8    0.05       0  5049.8    0.05       0
Bank Sta=5045.8,5049.8
Exp/Cntr=0.3,0.1

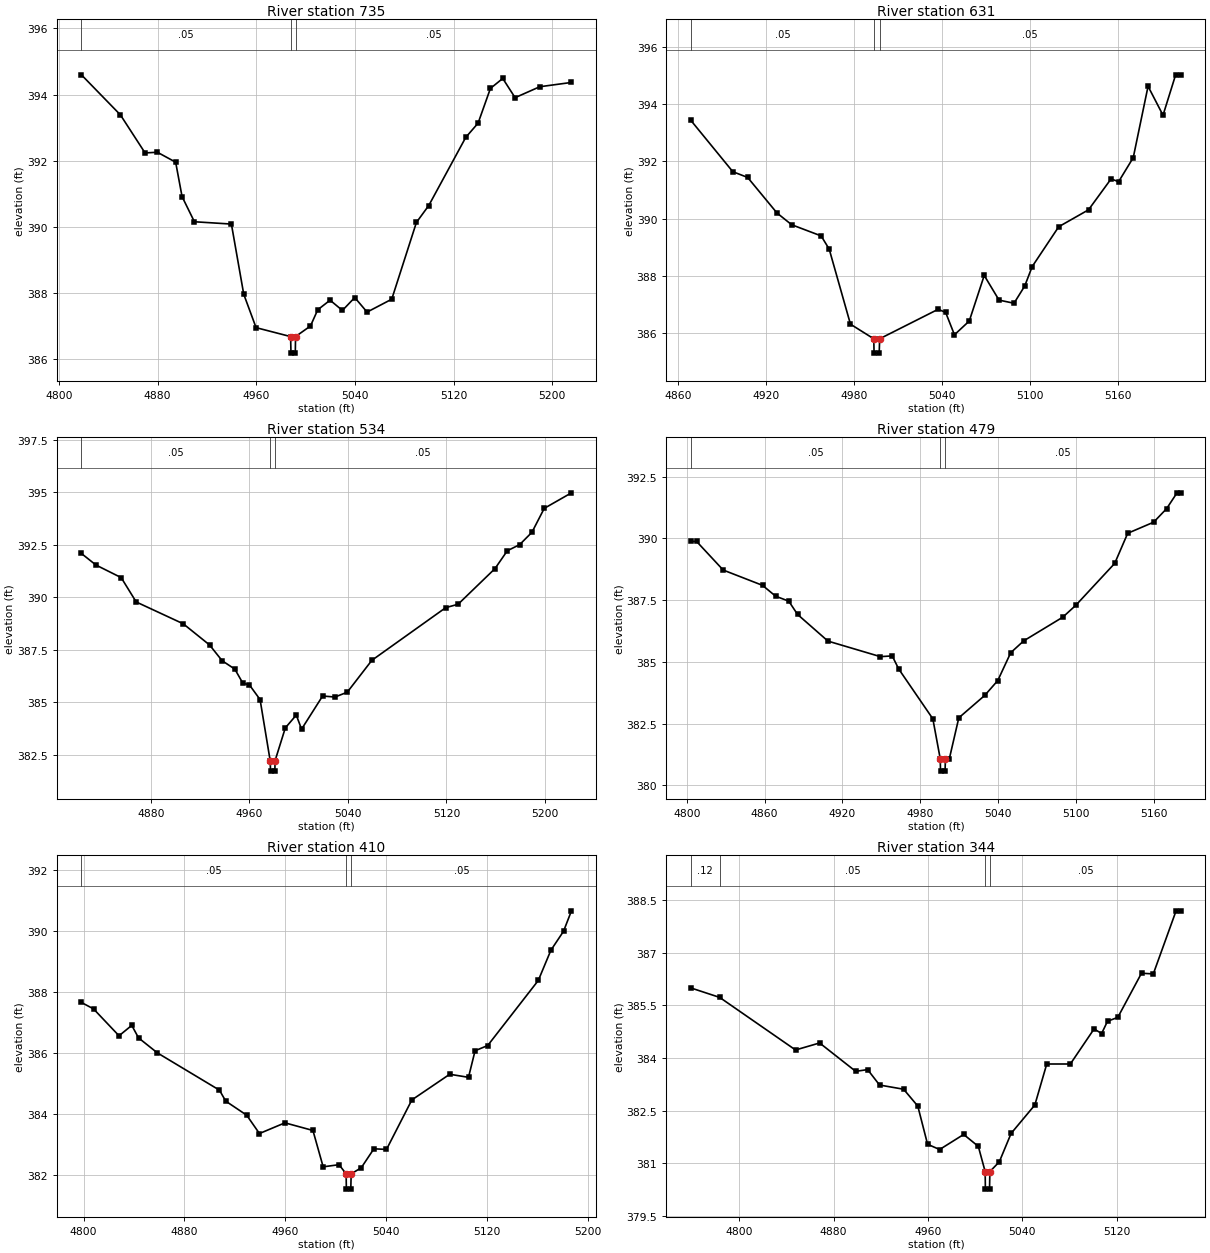
Type RM Length L Ch R = 1,735,104,104,104
BEGIN DESCRIPTION:
Lacy 165 645
END DESCRIPTION:
XS GIS Cut Line= 3
      2719607.54      6845248.57      2719421.98      6845242.31
      2719210.34      6845243.26
#Sta/Elev= 30
  4818.2  394.60  4849.8  393.39  4869.8  392.24  4879.8  392.26  4894.6  391.96
  4899.8  390.92  4909.8  390.16  4939.8  390.09  4949.8  387.97  4959.8  386.96
  4987.8  386.69  4988.1  386.19  4991.6  386.19  4991.8  386.69  5003.9  387.01
  5009.8  387.50  5019.8  387.79  5029.8  387.48  5039.8  387.87  5049.8  387.43
  5069.8  387.82  5089.8  390.14  5099.8  390.65  5129.8  392.71  5139.8  393.14
  5149.8  394.19  5159.8  394.49  5169.8  393.91  5189.8  394.24  5215.5  394.37
#Mann=3,-1,0
  4818.2    0.05       0  4987.8    0.04       0  4991.8    0.05       0
Bank Sta=4987.8,4991.8
Exp/Cntr=0.3,0.1

Type RM Length L Ch R = 1,631,97,97,97
BEGIN DESCRIPTION:
Lacy 165 642
END DESCRIPTION:
XS GIS Cut Line= 3
      2719604.58      6845162.49      2719475.44      6845153.63
      2719273.96      6845117.68
#Sta/Elev= 30
  4868.7  393.43  4897.3  391.64  4907.4  391.44  4927.4  390.20  4937.4  389.79
  4957.5  389.40  4963.0  388.94  4977.5  386.32  4993.4  385.81  4993.6  385.31
  4997.1  385.31  4997.4  385.81  5037.3  386.84  5042.4  386.73  5048.4  385.95
  5058.5  386.43  5068.7  388.02  5078.8  387.16  5089.0  387.05  5096.3  387.65
  5101.4  388.33  5119.5  389.72  5139.8  390.31  5155.2  391.39  5160.3  391.29
  5170.3  392.13  5180.4  394.62  5190.6  393.61  5199.2  395.02  5202.8  395.02
#Mann=3,-1,0
  4868.7    0.05       0  4993.4    0.04       0  4997.4    0.05       0
Bank Sta=4993.4,4997.4
Exp/Cntr=0.3,0.1

Type RM Length L Ch R = 1,534,55,55,55
BEGIN DESCRIPTION:
Lacy 165 641
END DESCRIPTION:
XS GIS Cut Line= 3
      2719647.54      6845095.05      2719472.73      6845055.82
      2719253.89      6845054.66
#Sta/Elev= 30
  4823.5  392.08  4835.3  391.53  4855.8  390.93  4868.0  389.77  4906.2  388.73
  4927.6  387.72  4937.8  386.97  4948.1  386.57  4954.7  385.89  4959.8  385.83
  4968.6  385.12  4976.8  382.21  4977.1  381.71  4980.6  381.71  4980.8  382.21
  4989.1  383.77  4998.0  384.38  5002.3  383.71  5019.4  385.29  5029.4  385.24
  5039.4  385.47  5059.4  386.99  5119.4  389.50  5129.4  389.66  5159.4  391.36
  5169.4  392.21  5179.4  392.50  5189.4  393.09  5199.4  394.23  5221.5  394.97
#Mann=3,-1,0
  4823.5    0.05       0  4976.8    0.04       0  4980.8    0.05       0
Bank Sta=4976.8,4980.8
Exp/Cntr=0.3,0.1

Type RM Length L Ch R = 1,479,69,69,69
BEGIN DESCRIPTION:
Lacy 165 653
END DESCRIPTION:
XS GIS Cut Line= 3
      2719670.69      6845027.18      2719475.64      6845000.99
      2719294.96      6844998.92
#Sta/Elev= 30
  4803.2  389.88  4807.6  389.88  4828.1  388.72  4858.4  388.10  4868.5  387.66
  4878.6  387.46  4885.4  386.92  4908.8  385.84  4949.2  385.21  4958.3  385.24
  4963.3  384.71  4989.6  382.69  4995.3  381.07  4995.5  380.57  4999.0  380.57
  4999.3  381.07  5002.3  381.07  5009.6  382.73  5029.6  383.64  5039.6  384.24
  5049.6  385.37  5059.6  385.85  5089.7  386.81  5099.7  387.29  5129.7  388.99
  5139.7  390.21  5159.7  390.66  5169.7  391.21  5177.7  391.85  5180.7  391.85
#Mann=3,-1,0
  4803.2    0.05       0  4995.3    0.04       0  4999.3    0.05       0
Bank Sta=4995.3,4999.3
Exp/Cntr=0.3,0.1

Type RM Length L Ch R = 1,410,66,66,66
BEGIN DESCRIPTION:
Lacy 165 652
END DESCRIPTION:
XS GIS Cut Line= 3
      2719675.50      6844962.78      2719476.04      6844932.85
      2719289.74      6844920.66
#Sta/Elev= 30
  4798.3  387.66  4807.9  387.45  4828.1  386.57  4838.2  386.91  4843.6  386.50
  4858.5  386.01  4907.7  384.79  4912.7  384.43  4929.3  383.97  4939.4  383.37
  4959.6  383.72  4981.8  383.47  4989.9  382.28  5002.5  382.35  5008.1  382.05
  5008.3  381.55  5011.8  381.55  5012.1  382.05  5020.1  382.25  5030.1  382.87
  5040.1  382.85  5060.2  384.47  5090.2  385.31  5105.1  385.21  5110.3  386.08
  5120.3  386.25  5160.4  388.38  5170.4  389.37  5180.4  389.99  5186.7  390.66
#Mann=3,-1,0
  4798.3    0.05       0  5008.1    0.04       0  5012.1    0.05       0
Bank Sta=5008.1,5012.1
Exp/Cntr=0.3,0.1

Type RM Length L Ch R = 1,344,119,119,119
BEGIN DESCRIPTION:
Lacy 165 654
END DESCRIPTION:
XS GIS Cut Line= 3
      2719713.18      6844910.87      2719476.42      6844866.42
      2719302.70      6844881.80
#Sta/Elev= 30
  4759.1  386.00  4783.5  385.73  4847.8  384.23  4868.2  384.43  4898.8  383.62
  4908.9  383.67  4919.0  383.23  4939.4  383.11  4951.4  382.63  4959.7  381.54
  4969.9  381.39  4990.3  381.82  5002.7  381.48  5008.5  380.76  5008.7  380.26
  5012.2  380.26  5012.5  380.76  5020.5  381.04  5030.5  381.85  5050.6  382.66
  5060.7  383.83  5080.7  383.83  5100.8  384.83  5107.2  384.70  5112.2  385.05
  5120.9  385.16  5141.0  386.42  5151.0  386.40  5170.3  388.20  5174.4  388.20
#Mann=4,-1,0
  4759.1    0.12       0  4783.5    0.05       0  5008.5    0.04       0
  5012.5    0.05       0
Bank Sta=5008.5,5012.5
Exp/Cntr=0.3,0.1

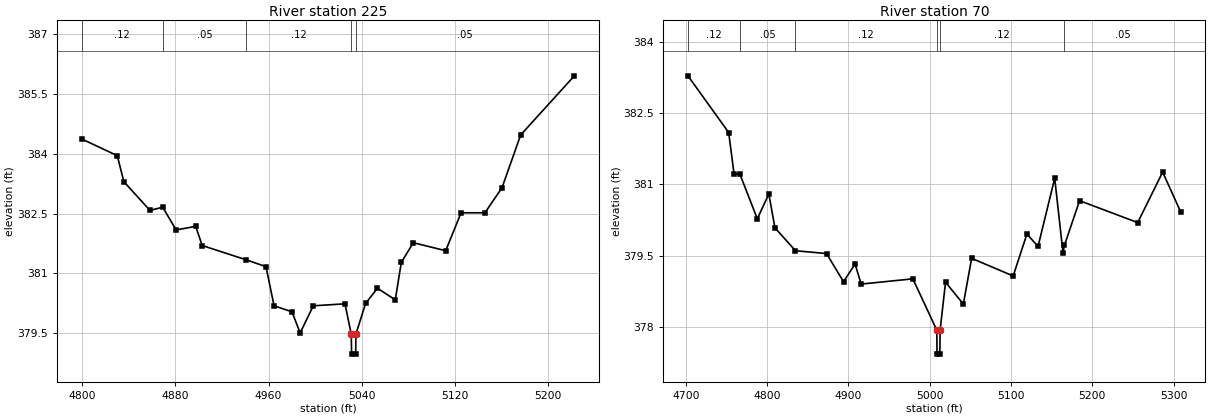
Type RM Length L Ch R = 1,225,155,155,155
BEGIN DESCRIPTION:
Lacy 165 651
END DESCRIPTION:
XS GIS Cut Line= 3
      2719697.99      6844849.90      2719518.21      6844760.90
      2719301.03      6844809.75
#Sta/Elev= 30
  4799.4  384.37  4830.1  383.95  4835.7  383.30  4858.1  382.58  4869.1  382.66
  4880.6  382.09  4897.4  382.18  4903.0  381.70  4941.0  381.34  4957.8  381.17
  4964.7  380.19  4980.1  380.04  4987.1  379.51  4998.4  380.19  5025.6  380.24
  5031.0  379.48  5031.3  378.98  5034.8  378.98  5035.0  379.48  5043.3  380.25
  5053.5  380.63  5068.8  380.34  5074.0  381.28  5084.3  381.77  5112.1  381.57
  5125.3  382.52  5145.8  382.52  5160.5  383.15  5176.5  384.47  5222.6  385.95
#Mann=5,-1,0
  4799.4    0.12       0  4869.1    0.05       0  4941.0    0.12       0
  5031.0    0.07       0  5035.0    0.05       0
Bank Sta=5031,5035
Exp/Cntr=0.3,0.1

Type RM Length L Ch R = 1,70,0,0,0
BEGIN DESCRIPTION:
Lacy 165 650
END DESCRIPTION:
XS GIS Cut Line= 3
      2719748.22      6844829.56      2719526.54      6844631.31
      2719224.12      6844694.27
#Sta/Elev= 30
  4702.6  383.28  4752.7  382.09  4759.4  381.21  4766.2  381.23  4787.9  380.28
  4802.1  380.80  4809.6  380.09  4834.9  379.61  4873.1  379.55  4894.0  378.96
  4908.2  379.33  4915.7  378.91  4979.3  379.02  5008.8  377.94  5009.0  377.44
  5012.5  377.44  5012.8  377.94  5019.5  378.95  5041.4  378.49  5051.6  379.45
  5102.7  379.08  5119.6  379.96  5133.3  379.70  5153.8  381.13  5164.0  379.57
  5165.7  379.72  5184.4  380.66  5255.9  380.20  5286.6  381.26  5308.9  380.42
#Mann=6,-1,0
  4702.6    0.12       0  4766.2    0.05       0  4834.9    0.12       0
  5008.8    0.07       0  5012.8    0.12       0  5165.7    0.05       0
Bank Sta=5008.8,5012.8
Exp/Cntr=0.3,0.1

Chan Stop Cuts=-1