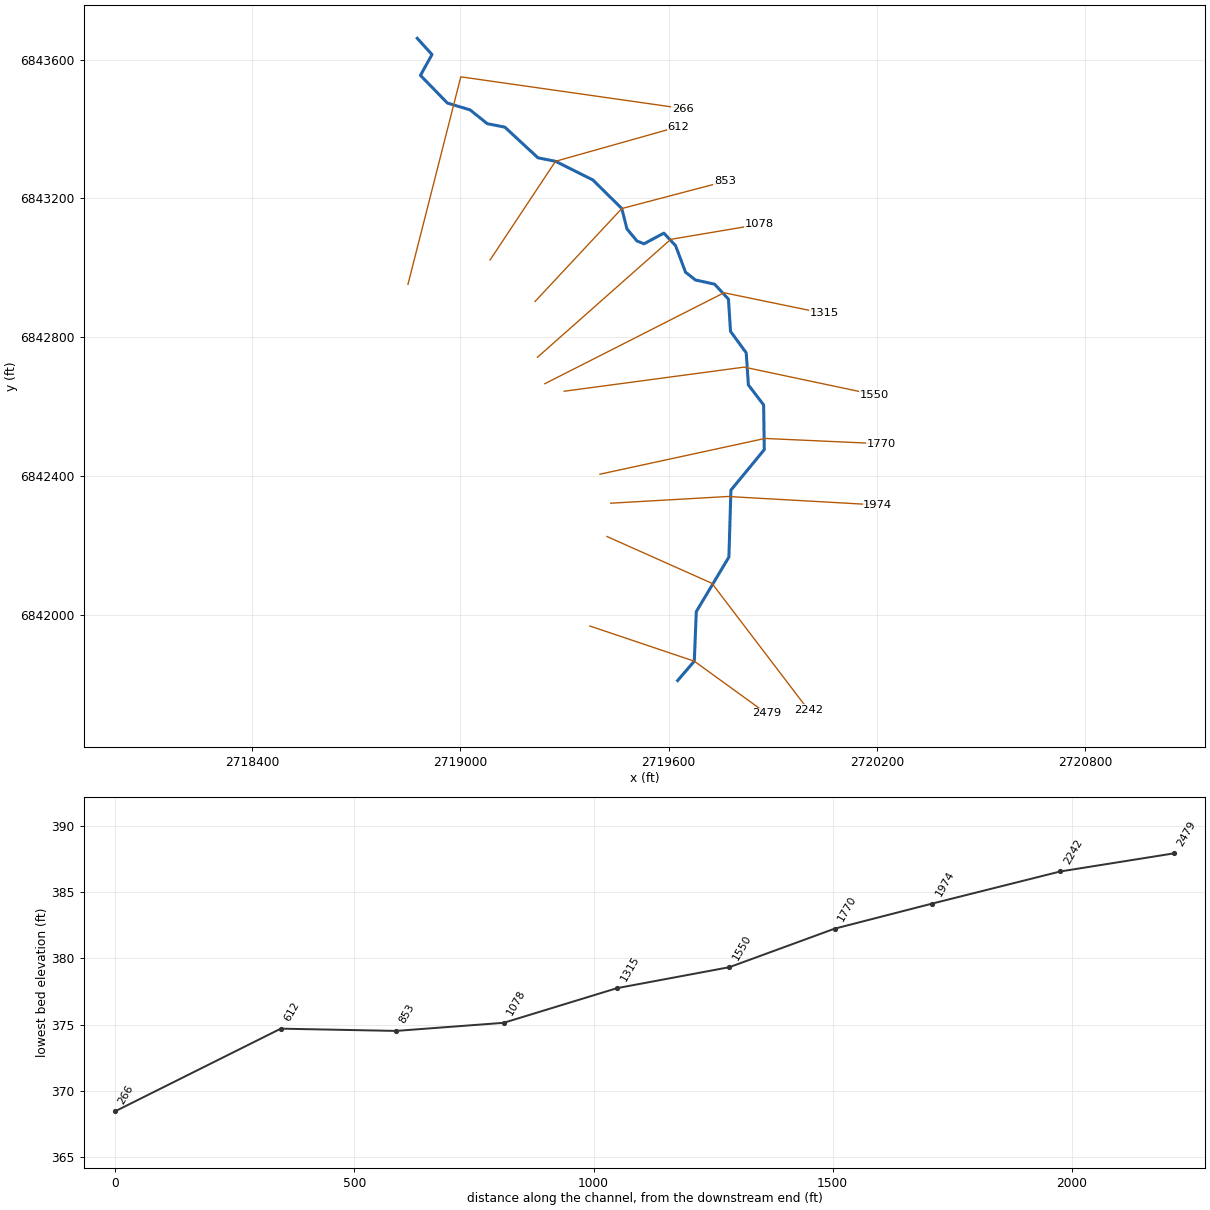
--- Lacy 166.prj (project) ---

Proj Title=Lacy 166 Base Level Engineering
Current Plan=p01
Default Exp/Contr=0.3,0.1
English Units
Geom File=g01
Flow File=f01
Plan File=p01
BEGIN DESCRIPTION:
Lacy 166
END DESCRIPTION:

--- Lacy 166.p01 (plan) ---

Plan Title=Multiple Run
Short Identifier=Multiple
Geom File=g01
Flow File=f01
Subcritical Flow
K Sum by GR= 0
Std Step Tol= 0.01
Critical Tol= 0.01
Num of Std Step Trials= 20
Max Error Tol= 0.3
Flow Tol Ratio= 0.001
Split Flow NTrial= 30
Split Flow Tol= 0.02
Split Flow Ratio= 0.02
Log Output Level= 0
Friction Slope Method= 1
Unsteady Friction Slope Method= 2
Unsteady Bridges Friction Slope Method= 1
Parabolic Critical Depth
Global Vel Dist=  1 , 1 , 1
Global Log Level= 0
CheckData=True
Encroach Param= -1, 0, 0, 0
BEGIN DESCRIPTION:
Multiple Run
END DESCRIPTION:

--- Lacy 166.f01 (steady flow) ---

Flow Title=Multiple
Number of Profiles=7
Profile Names=10-year,25-year,50-year,1pct_min,100-year,1pct_plu,500-year
River Rch & RM= Lacy 166,Reach-1,2479
     378     493     585     345     688    1372     950
Boundary for River Rch & Prof#=Lacy 166,Reach-1,1
Up Type=0
Dn Type=3
Dn Slope=0.005
Boundary for River Rch & Prof#=Lacy 166,Reach-1,2
Up Type=0
Dn Type=3
Dn Slope=0.005
Boundary for River Rch & Prof#=Lacy 166,Reach-1,3
Up Type=0
Dn Type=3
Dn Slope=0.005
Boundary for River Rch & Prof#=Lacy 166,Reach-1,4
Up Type=0
Dn Type=3
Dn Slope=0.005
Boundary for River Rch & Prof#=Lacy 166,Reach-1,5
Up Type=0
Dn Type=3
Dn Slope=0.005
Boundary for River Rch & Prof#=Lacy 166,Reach-1,6
Up Type=0
Dn Type=3
Dn Slope=0.005
Boundary for River Rch & Prof#=Lacy 166,Reach-1,7
Up Type=0
Dn Type=3
Dn Slope=0.005

--- Lacy 166.g01 (geometry) ---

Geom Title=Existing Conditions

River Reach=Lacy 166,Reach-1
Reach XY= 30
      2719626.00      6841811.00      2719674.09      6841866.79
      2719679.75      6842009.44      2719773.76      6842166.93
      2719779.55      6842359.53      2719875.63      6842476.17
      2719873.75      6842605.06      2719829.86      6842662.60
      2719823.65      6842755.03      2719778.36      6842816.98
      2719772.48      6842909.72      2719732.36      6842952.97
      2719677.46      6842964.90      2719648.87      6842987.18
      2719620.13      6843063.81      2719586.31      6843099.88
      2719529.16      6843069.09      2719508.96      6843077.24
      2719479.98      6843112.18      2719465.23      6843170.67
      2719382.07      6843252.87      2719274.27      6843306.81
      2719223.71      6843316.85      2719128.29      6843405.15
      2719077.73      6843415.19      2719028.18      6843454.90
      2718962.73      6843474.62      2718885.19      6843554.32
      2718918.48      6843614.33      2718876.00      6843661.00

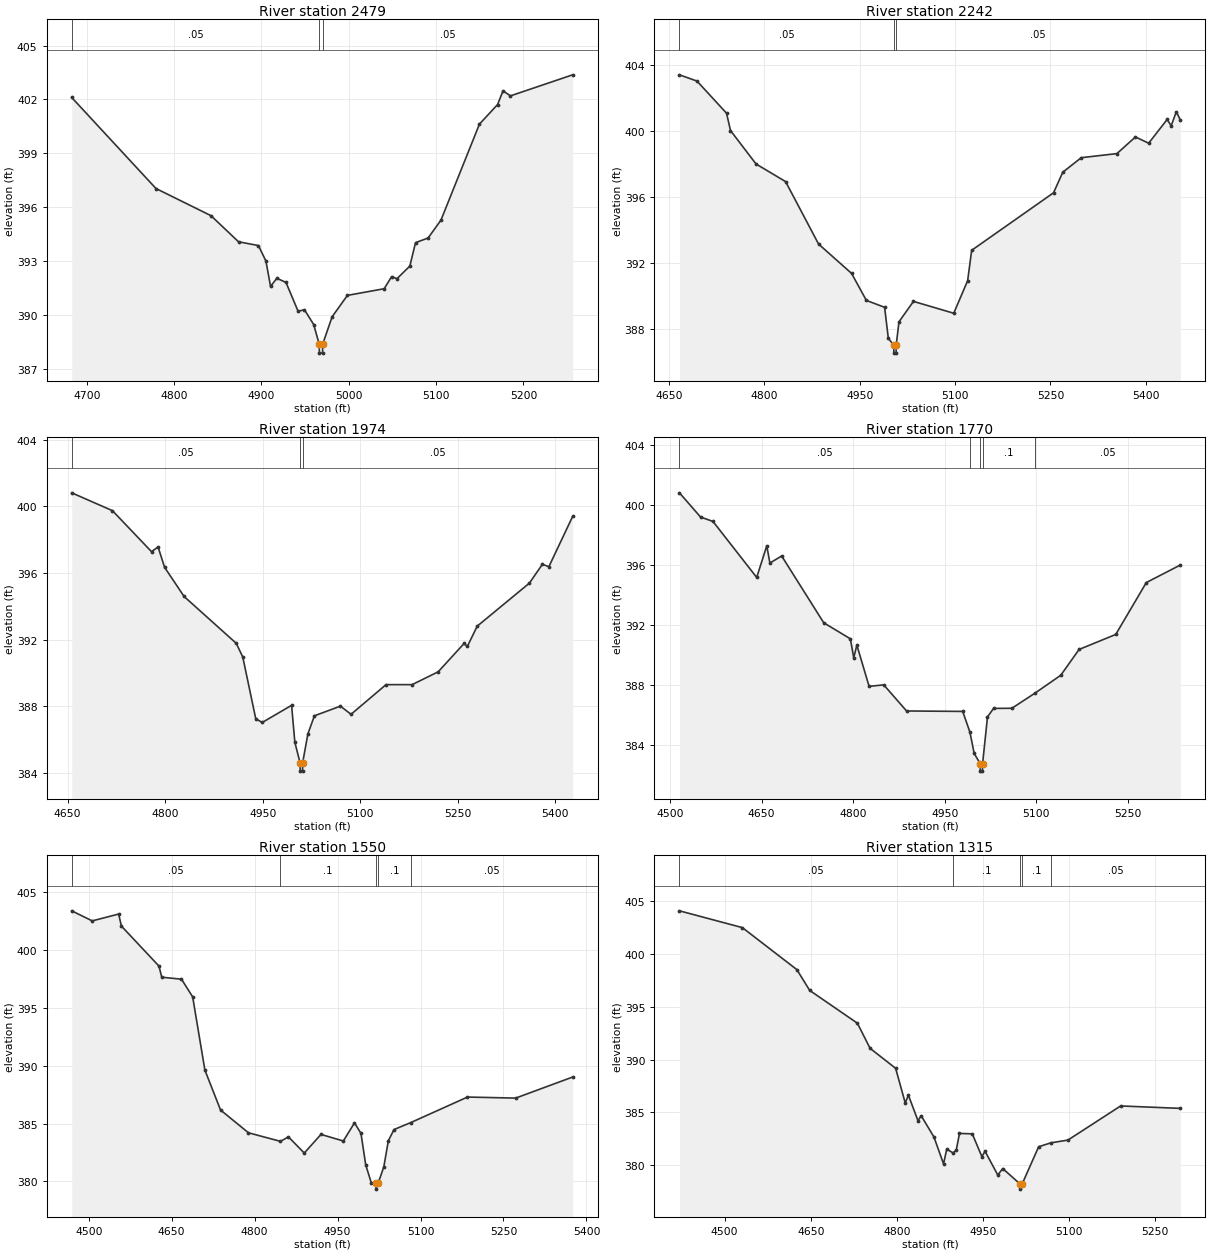
Type RM Length L Ch R = 1,2479,237,237,237
BEGIN DESCRIPTION:
Lacy 166 639
END DESCRIPTION:
XS GIS Cut Line= 3
      2719373.40      6841968.10      2719674.09      6841866.79
      2719881.70      6841716.49
#Sta/Elev= 30
  4682.7  402.11  4779.2  397.05  4842.2  395.54  4873.7  394.09  4896.5  393.88
  4905.1  393.02  4910.4  391.61  4917.6  392.06  4928.1  391.83  4941.9  390.23
  4949.2  390.31  4959.8  389.49  4966.1  388.40  4966.4  387.90  4969.9  387.90
  4970.1  388.40  4980.9  389.92  4998.4  391.11  5040.5  391.48  5049.0  392.15
  5055.2  392.04  5069.9  392.74  5076.4  394.04  5090.8  394.30  5105.5  395.29
  5149.6  400.63  5170.4  401.72  5176.6  402.48  5185.1  402.20  5256.3  403.37
#Mann=3,-1,0
  4682.7    0.05       0  4966.1    0.04       0  4970.1    0.05       0
Bank Sta=4966.1,4970.1
Exp/Cntr=0.3,0.1

Type RM Length L Ch R = 1,2242,268,268,268
BEGIN DESCRIPTION:
Lacy 166 634
END DESCRIPTION:
XS GIS Cut Line= 3
      2719422.70      6842225.90      2719724.80      6842091.15
      2720001.99      6841727.30
#Sta/Elev= 30
  4666.2  403.43  4693.8  403.05  4740.3  401.10  4746.5  400.05  4786.7  398.02
  4833.2  396.95  4885.1  393.16  4937.0  391.38  4960.3  389.74  4989.0  389.32
  4994.9  387.43  5003.3  387.04  5003.6  386.54  5007.1  386.54  5007.3  387.04
  5011.6  388.44  5034.4  389.68  5097.8  388.96  5119.7  390.94  5126.0  392.78
  5254.8  396.27  5269.4  397.52  5298.4  398.40  5354.6  398.65  5383.7  399.66
  5404.5  399.28  5433.6  400.72  5439.9  400.34  5448.1  401.19  5454.4  400.68
#Mann=3,-1,0
  4666.2    0.05       0  5003.3    0.04       0  5007.3    0.05       0
Bank Sta=5003.3,5007.3
Exp/Cntr=0.3,0.1

Type RM Length L Ch R = 1,1974,204,204,204
BEGIN DESCRIPTION:
Lacy 166 633
END DESCRIPTION:
XS GIS Cut Line= 3
      2719433.46      6842321.91      2719770.99      6842341.23
      2720202.42      6842316.86
#Sta/Elev= 30
  4656.4  400.82  4719.0  399.75  4779.1  397.29  4789.2  397.57  4799.2  396.35
  4829.2  394.60  4909.4  391.79  4919.4  390.97  4939.4  387.26  4949.4  387.04
  4994.5  388.07  4999.5  385.85  5007.5  384.62  5007.8  384.12  5011.3  384.12
  5011.5  384.62  5019.5  386.35  5029.6  387.44  5069.6  388.02  5085.9  387.53
  5139.7  389.31  5179.8  389.31  5219.9  390.08  5259.7  391.78  5264.7  391.60
  5279.9  392.82  5360.1  395.40  5380.1  396.53  5390.1  396.39  5426.6  399.40
#Mann=3,-1,0
  4656.4    0.05       0  5007.5    0.04       0  5011.5    0.05       0
Bank Sta=5007.5,5011.5
Exp/Cntr=0.3,0.1

Type RM Length L Ch R = 1,1770,220,220,220
BEGIN DESCRIPTION:
Lacy 166 632
END DESCRIPTION:
XS GIS Cut Line= 3
      2719402.28      6842405.46      2719877.60      6842508.43
      2720211.81      6842493.25
#Sta/Elev= 30
  4515.4  400.78  4549.9  399.17  4570.4  398.87  4642.0  395.14  4658.5  397.25
  4663.6  396.10  4682.9  396.57  4751.8  392.12  4795.5  391.05  4801.0  389.78
  4806.1  390.63  4826.2  387.88  4850.2  387.98  4887.6  386.24  4979.6  386.21
  4991.4  384.83  4998.4  383.41  5008.2  382.73  5008.4  382.23  5011.9  382.23
  5012.2  382.73  5020.2  385.85  5030.2  386.41  5060.2  386.42  5098.5  387.44
  5140.3  388.62  5170.3  390.34  5230.4  391.34  5280.5  394.80  5336.3  395.97
#Mann=5,-1,0
  4515.4    0.05       0  4991.4     0.1       0  5008.2    0.07       0
  5012.2     0.1       0  5098.5    0.05       0
Bank Sta=5008.2,5012.2
Exp/Cntr=0.3,0.1

Type RM Length L Ch R = 1,1550,235,235,235
BEGIN DESCRIPTION:
Lacy 166 631
END DESCRIPTION:
XS GIS Cut Line= 3
      2719299.25      6842644.42      2719817.60      6842713.90
      2720192.03      6842634.73
#Sta/Elev= 30
  4469.3  403.39  4506.4  402.52  4554.1  403.11  4559.2  402.07  4627.1  398.61
  4632.1  397.65  4667.8  397.48  4688.0  395.95  4710.1  389.62  4738.4  386.17
  4788.9  384.20  4846.8  383.46  4861.1  383.85  4889.8  382.45  4920.0  384.06
  4960.4  383.49  4980.6  385.06  4992.3  384.15  5000.9  381.43  5011.1  379.85
  5019.3  379.83  5019.6  379.33  5023.3  379.83  5033.6  381.25  5041.8  383.51
  5052.0  384.48  5082.2  385.08  5184.9  387.29  5272.0  387.20  5375.0  389.02
#Mann=5,-1,0
  4469.3    0.05       0  4846.8     0.1       0  5019.3    0.07       0
  5023.3     0.1       0  5082.2    0.05       0
Bank Sta=5019.3,5023.3
Exp/Cntr=0.3,0.1

Type RM Length L Ch R = 1,1315,237,237,237
BEGIN DESCRIPTION:
Lacy 166 638
END DESCRIPTION:
XS GIS Cut Line= 3
      2719243.58      6842666.14      2719759.70      6842928.13
      2720047.92      6842868.65
#Sta/Elev= 30
  4421.2  404.08  4530.9  402.49  4625.8  398.52  4648.2  396.55  4731.3  393.45
  4753.5  391.07  4798.0  389.18  4814.7  385.91  4820.3  386.63  4836.9  384.23
  4842.6  384.69  4864.8  382.68  4881.5  380.14  4887.1  381.54  4898.2  381.17
  4903.7  381.45  4909.3  383.02  4931.6  382.98  4948.3  380.83  4953.9  381.33
  4976.1  379.08  4984.6  379.70  5014.6  378.25  5014.9  377.75  5018.6  378.25
  5047.3  381.76  5068.6  382.13  5098.3  382.39  5190.2  385.62  5294.3  385.39
#Mann=5,-1,0
  4421.2    0.05       0  4898.2     0.1       0  5014.6    0.07       0
  5018.6     0.1       0  5068.6    0.05       0
Bank Sta=5014.6,5018.6
Exp/Cntr=0.3,0.1

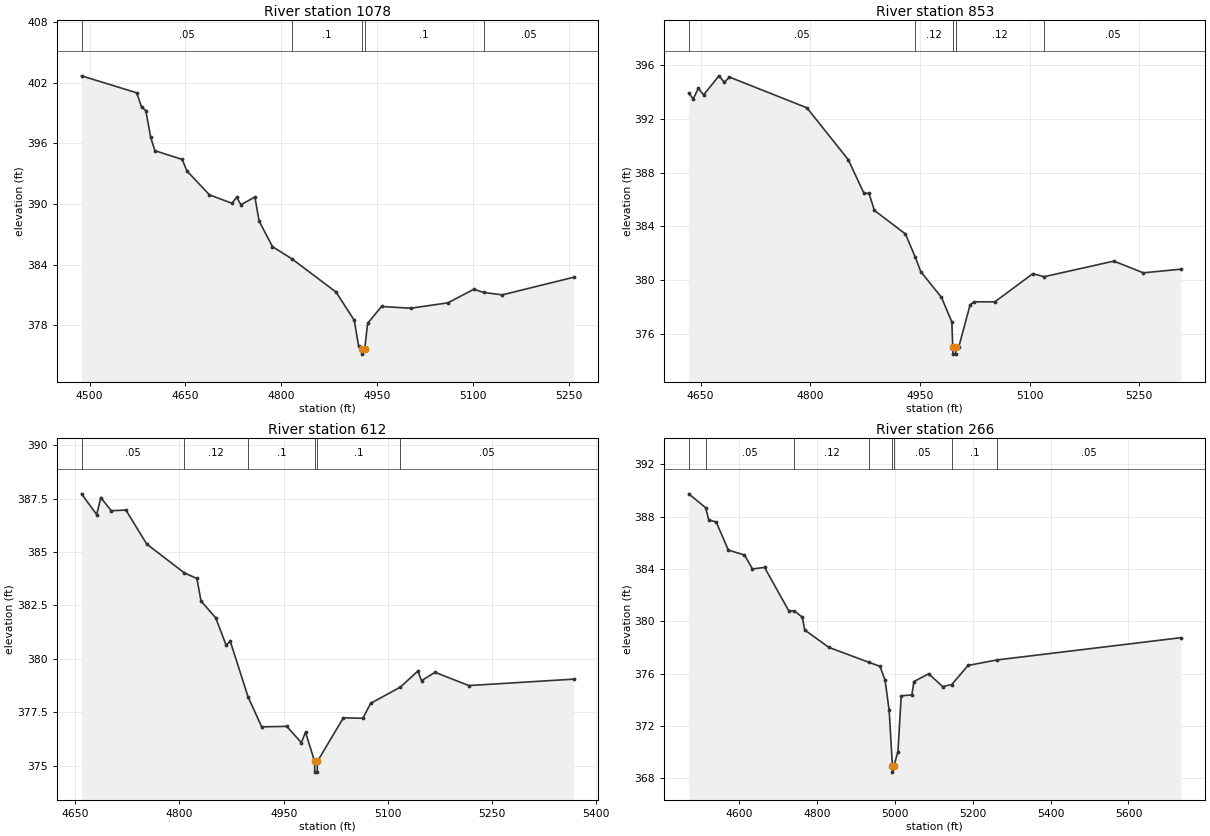
Type RM Length L Ch R = 1,1078,225,225,225
BEGIN DESCRIPTION:
Lacy 166 637
END DESCRIPTION:
XS GIS Cut Line= 3
      2719222.32      6842742.28      2719606.20      6843081.97
      2719860.02      6843124.78
#Sta/Elev= 30
  4487.4  402.66  4573.8  400.98  4581.3  399.57  4588.0  399.23  4595.6  396.58
  4602.2  395.26  4644.9  394.39  4652.4  393.25  4687.6  390.89  4722.7  390.06
  4730.2  390.65  4736.9  389.91  4758.7  390.68  4765.3  388.29  4786.2  385.77
  4816.9  384.55  4885.8  381.27  4914.2  378.48  4920.9  375.97  4926.5  375.64
  4926.7  375.14  4930.5  375.64  4935.1  378.19  4956.9  379.85  5002.4  379.68
  5060.6  380.21  5101.2  381.55  5116.8  381.24  5145.7  381.00  5257.4  382.74
#Mann=5,-1,0
  4487.4    0.05       0  4816.9     0.1       0  4926.5    0.07       0
  4930.5     0.1       0  5116.8    0.05       0
Bank Sta=4926.5,4930.5
Exp/Cntr=0.3,0.1

Type RM Length L Ch R = 1,853,241,241,241
BEGIN DESCRIPTION:
Lacy 166 636
END DESCRIPTION:
XS GIS Cut Line= 3
      2719215.32      6842902.99      2719465.23      6843170.67
      2719761.94      6843248.69
#Sta/Elev= 30
  4633.8  393.89  4640.0  393.46  4646.9  394.24  4654.2  393.76  4675.2  395.17
  4682.5  394.68  4689.4  395.08  4795.4  392.80  4852.0  388.95  4873.5  386.45
  4880.4  386.45  4887.7  385.19  4930.2  383.44  4943.8  381.70  4951.2  380.64
  4979.5  378.74  4993.7  376.91  4994.9  375.03  4995.2  374.53  4998.7  374.53
  4998.9  375.03  5003.0  375.03  5018.6  378.18  5023.8  378.41  5052.5  378.41
  5104.5  380.50  5119.7  380.27  5215.2  381.43  5255.5  380.56  5306.8  380.83
#Mann=5,-1,0
  4633.8    0.05       0  4943.8    0.12       0  4994.9    0.07       0
  4998.9    0.12       0  5119.7    0.05       0
Bank Sta=4994.9,4998.9
Exp/Cntr=0.3,0.1

Type RM Length L Ch R = 1,612,346,346,346
BEGIN DESCRIPTION:
Lacy 166 635
END DESCRIPTION:
XS GIS Cut Line= 3
      2719085.84      6843022.60      2719274.27      6843306.81
      2719628.02      6843406.39
#Sta/Elev= 30
  4659.0  387.72  4680.8  386.75  4686.8  387.54  4701.8  386.93  4722.9  386.96
  4752.9  385.37  4807.1  384.02  4825.1  383.76  4831.1  382.70  4852.2  381.92
  4867.2  380.64  4873.2  380.82  4898.8  378.22  4918.4  376.82  4954.5  376.84
  4975.5  376.08  4981.5  376.57  4994.6  375.20  4994.8  374.70  4998.3  374.70
  4998.6  375.20  5036.0  377.24  5064.1  377.22  5075.3  377.92  5118.2  378.68
  5143.3  379.43  5148.5  378.98  5168.0  379.37  5216.6  378.75  5367.5  379.05
#Mann=6,-1,0
  4659.0    0.05       0  4807.1    0.12       0  4898.8     0.1       0
  4994.6    0.07       0  4998.6     0.1       0  5118.2    0.05       0
Bank Sta=4994.6,4998.6
Exp/Cntr=0.3,0.1

Type RM Length L Ch R = 1,266,0,0,0
BEGIN DESCRIPTION:
Lacy 166 3409
END DESCRIPTION:
XS GIS Cut Line= 3
      2718849.30      6842952.46      2719001.44      6843550.10
      2719641.27      6843458.87
#Sta/Elev= 30
  4471.3  389.74  4514.8  388.68  4522.6  387.76  4542.0  387.58  4573.0  385.44
  4614.3  385.07  4634.9  384.00  4665.9  384.12  4727.8  380.82  4742.5  380.79
  4762.9  380.32  4769.0  379.34  4831.0  378.01  4934.7  376.86  4962.3  376.56
  4975.4  375.48  4985.7  373.20  4994.1  368.98  4994.3  368.48  4998.1  368.98
  5008.3  370.04  5016.7  374.31  5044.1  374.38  5049.2  375.40  5087.1  375.99
  5122.9  375.02  5146.4  375.17  5188.2  376.63  5262.4  377.05  5734.3  378.75
#Mann=8,-1,0
  4471.3    0.12       0  4514.8    0.05       0  4742.5    0.12       0
  4934.7    0.05       0  4994.1    0.03       0  4998.1    0.05       0
  5146.4     0.1       0  5262.4    0.05       0
Bank Sta=4994.1,4998.1
Exp/Cntr=0.3,0.1

Chan Stop Cuts=-1