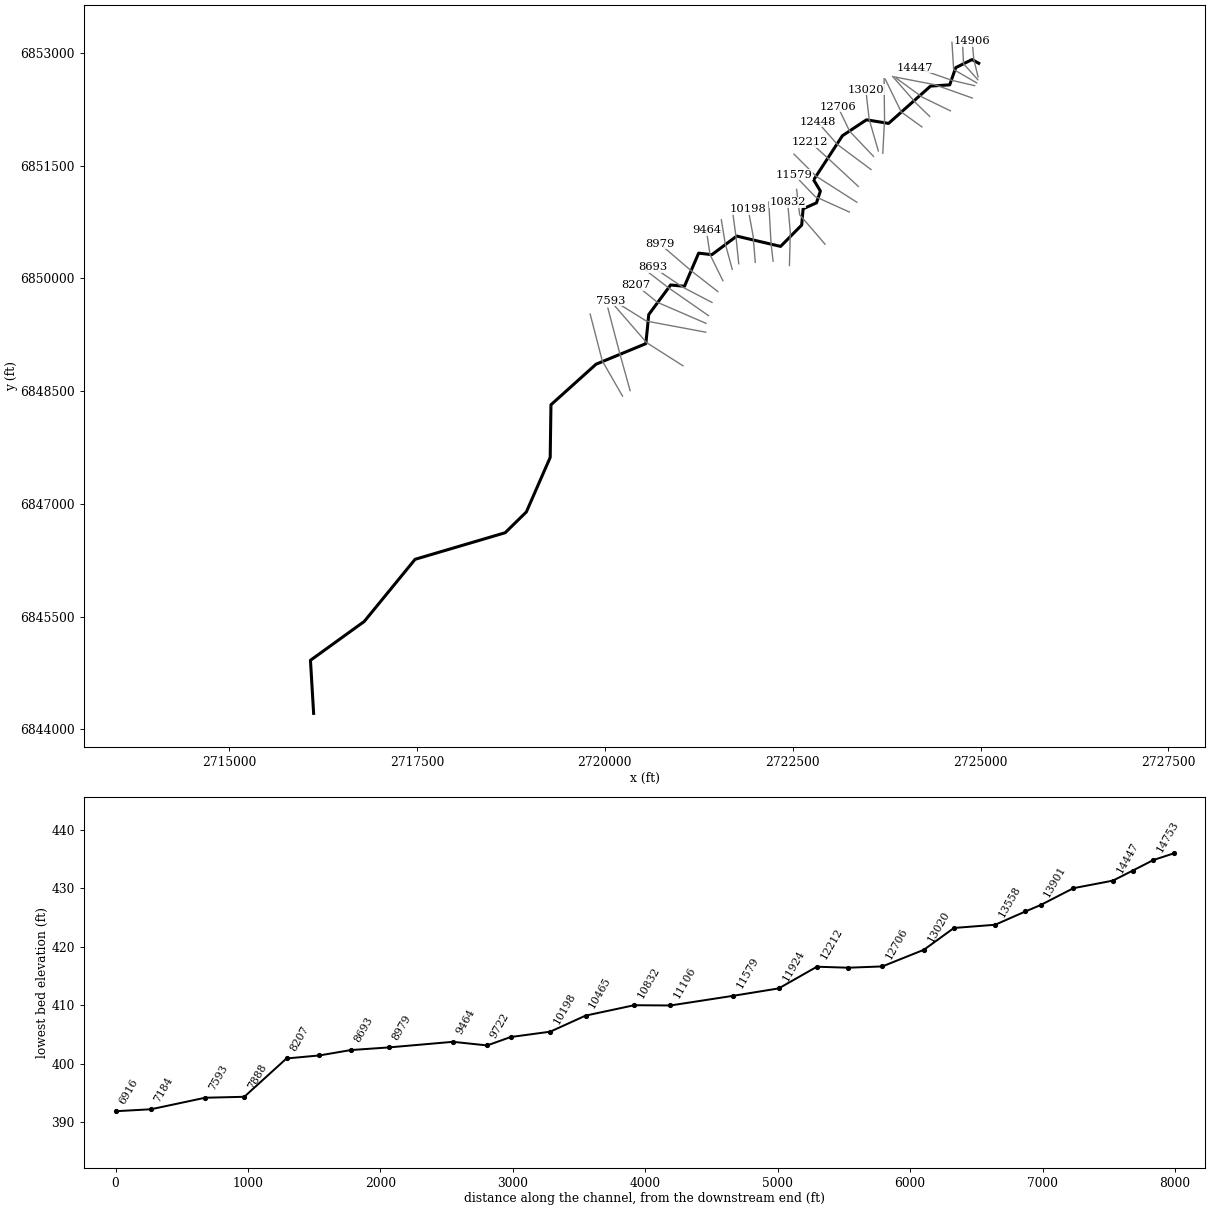
--- Lacy 167.prj (project) ---

Proj Title=Lacy 167 Base Level Engineering
Current Plan=p01
Default Exp/Contr=0.3,0.1
English Units
Geom File=g01
Flow File=f01
Plan File=p01
BEGIN DESCRIPTION:
Lacy 167
END DESCRIPTION:

--- Lacy 167.p01 (plan) ---

Plan Title=Multiple Run
Short Identifier=Multiple
Geom File=g01
Flow File=f01
Subcritical Flow
K Sum by GR= 0
Std Step Tol= 0.01
Critical Tol= 0.01
Num of Std Step Trials= 20
Max Error Tol= 0.3
Flow Tol Ratio= 0.001
Split Flow NTrial= 30
Split Flow Tol= 0.02
Split Flow Ratio= 0.02
Log Output Level= 0
Friction Slope Method= 1
Unsteady Friction Slope Method= 2
Unsteady Bridges Friction Slope Method= 1
Parabolic Critical Depth
Global Vel Dist=  1 , 1 , 1
Global Log Level= 0
CheckData=True
Encroach Param= -1, 0, 0, 0
BEGIN DESCRIPTION:
Multiple Run
END DESCRIPTION:

--- Lacy 167.f01 (steady flow) ---

Flow Title=Multiple
Number of Profiles=7
Profile Names=10-year,25-year,50-year,1pct_min,100-year,1pct_plu,500-year
River Rch & RM= Lacy 167,Reach-1,14906
     248     313     362     208     416     829     547
River Rch & RM= Lacy 167,Reach-1,13247
     445     584     694     410     817    1631    1132
River Rch & RM= Lacy 167,Reach-1,8979
     774    1047    1268     761    1518    3028    2175
River Rch & RM= Lacy 167,Reach-1,2426
     947    1297    1584     958    1912    3814    2785
Boundary for River Rch & Prof#=Lacy 167,Reach-1,1
Up Type=0
Dn Type=3
Dn Slope=0.005
Boundary for River Rch & Prof#=Lacy 167,Reach-1,2
Up Type=0
Dn Type=3
Dn Slope=0.005
Boundary for River Rch & Prof#=Lacy 167,Reach-1,3
Up Type=0
Dn Type=3
Dn Slope=0.005
Boundary for River Rch & Prof#=Lacy 167,Reach-1,4
Up Type=0
Dn Type=3
Dn Slope=0.005
Boundary for River Rch & Prof#=Lacy 167,Reach-1,5
Up Type=0
Dn Type=3
Dn Slope=0.005
Boundary for River Rch & Prof#=Lacy 167,Reach-1,6
Up Type=0
Dn Type=3
Dn Slope=0.005
Boundary for River Rch & Prof#=Lacy 167,Reach-1,7
Up Type=0
Dn Type=3
Dn Slope=0.005

--- Lacy 167.g01 (geometry) ---

Geom Title=Existing Conditions

River Reach=Lacy 167,Reach-1
Reach XY= 30
      2724976.00      6852861.00      2724886.62      6852910.34
      2724669.61      6852803.00      2724589.73      6852574.16
      2724334.50      6852557.53      2723776.00      6852061.00
      2723481.86      6852108.95      2723162.43      6851897.53
      2722779.10      6851309.35      2722868.89      6851161.00
      2722816.83      6851004.01      2722638.96      6850924.63
      2722620.20      6850708.70      2722339.41      6850424.52
      2721755.84      6850561.46      2721424.37      6850314.13
      2721249.10      6850334.98      2721059.77      6849893.79
      2720876.00      6849911.00      2720585.15      6849517.73
      2720546.53      6849130.71      2719884.49      6848857.46
      2719283.80      6848317.21      2719273.74      6847616.94
      2718956.22      6846890.91      2718674.50      6846614.61
      2717476.00      6846261.00      2716799.47      6845434.02
      2716083.81      6844917.19      2716126.00      6844211.00

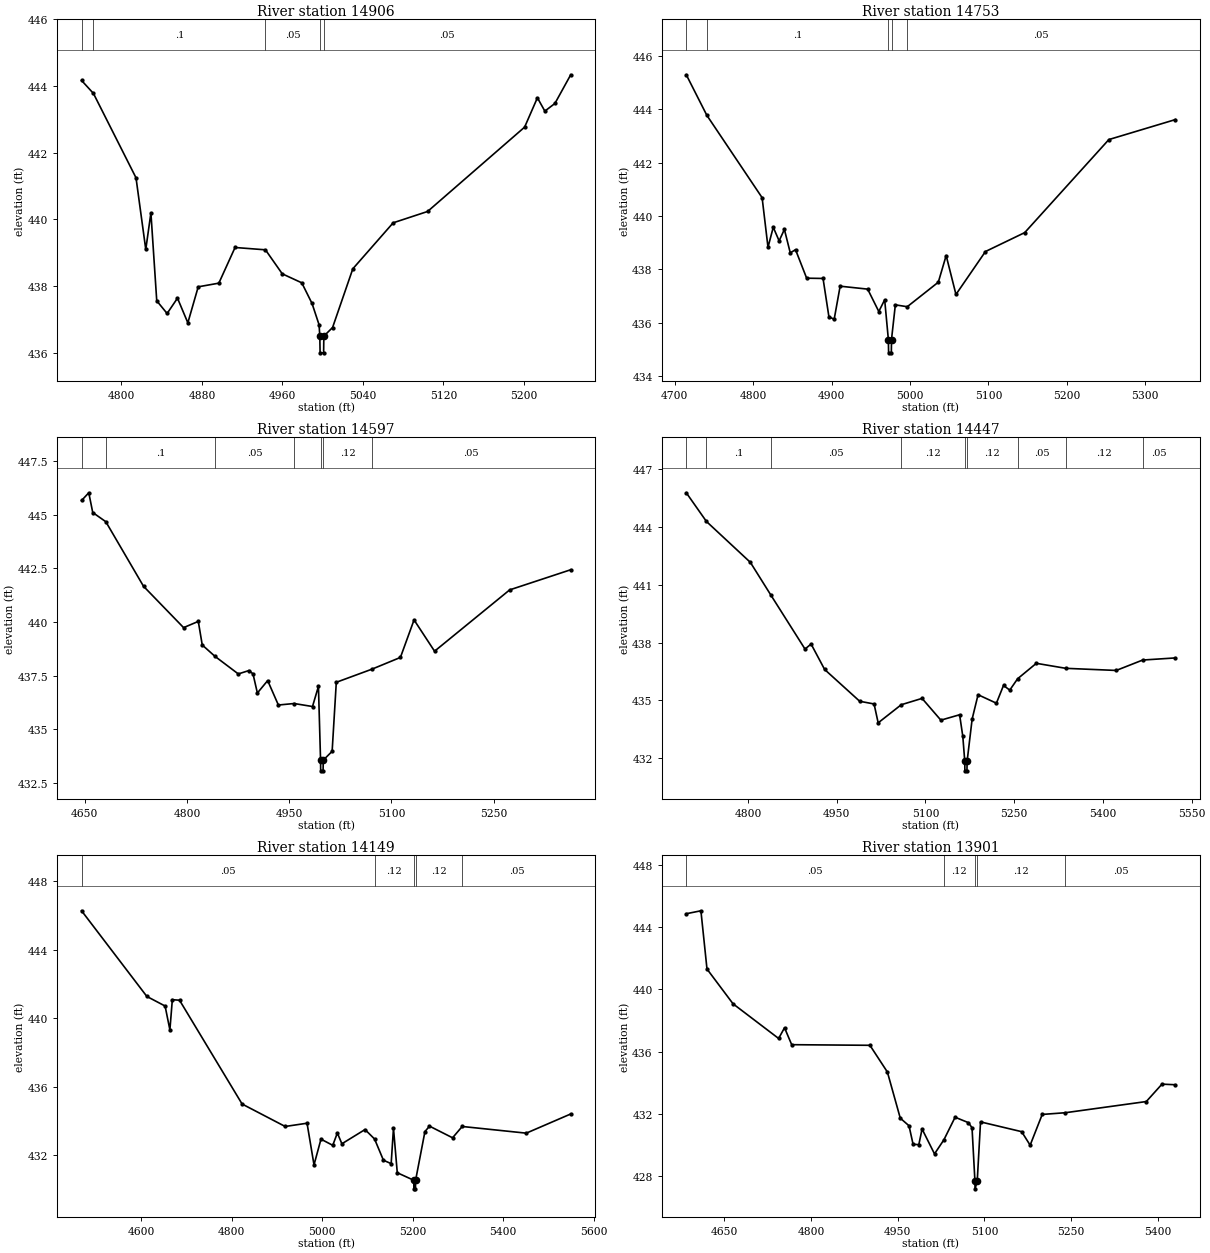
Type RM Length L Ch R = 1,14906,153,153,153
BEGIN DESCRIPTION:
Lacy 167 578
END DESCRIPTION:
XS GIS Cut Line= 3
      2724967.12      6852678.42      2724910.60      6852911.26
      2724887.71      6853156.59
#Sta/Elev= 30
  4760.4  444.17  4772.2  443.78  4814.5  441.25  4824.2  439.10  4829.3  440.20
  4835.1  437.56  4845.4  437.18  4855.7  437.64  4866.0  436.90  4876.3  437.98
  4896.8  438.09  4912.9  439.16  4943.1  439.09  4959.8  438.37  4979.2  438.10
  4989.4  437.48  4996.4  436.84  4997.1  436.50  4997.4  436.00  5000.9  436.00
  5001.1  436.50  5009.8  436.76  5029.9  438.52  5070.0  439.90  5104.2  440.24
  5200.6  442.77  5213.3  443.65  5220.7  443.25  5230.7  443.48  5246.4  444.34
#Mann=5,-1,0
  4760.4    0.05       0  4772.2     0.1       0  4943.1    0.05       0
  4997.1    0.04       0  5001.1    0.05       0
Bank Sta=4997.1,5001.1
Exp/Cntr=0.3,0.1

Type RM Length L Ch R = 1,14753,156,156,156
BEGIN DESCRIPTION:
Lacy 167 577
END DESCRIPTION:
XS GIS Cut Line= 3
      2724963.60      6852641.91      2724773.80      6852854.93
      2724756.86      6853193.00
#Sta/Elev= 30
  4714.7  445.30  4740.9  443.78  4811.4  440.69  4818.9  438.83  4825.6  439.58
  4833.1  439.07  4839.8  439.50  4847.3  438.62  4854.0  438.74  4868.2  437.67
  4889.1  437.66  4896.6  436.22  4903.3  436.13  4910.9  437.37  4946.0  437.26
  4960.2  436.42  4967.7  436.86  4972.4  435.37  4972.7  434.87  4976.2  434.87
  4976.4  435.37  4981.3  436.67  4996.5  436.60  5036.1  437.52  5046.1  438.52
  5058.6  437.06  5096.2  438.67  5146.3  439.38  5253.6  442.87  5338.5  443.62
#Mann=5,-1,0
  4714.7    0.05       0  4740.9     0.1       0  4972.4    0.05       0
  4976.4     0.1       0  4996.5    0.05       0
Bank Sta=4972.4,4976.4
Exp/Cntr=0.3,0.1

Type RM Length L Ch R = 1,14597,150,150,150
BEGIN DESCRIPTION:
Lacy 167 576
END DESCRIPTION:
XS GIS Cut Line= 3
      2724949.14      6852600.04      2724642.28      6852778.14
      2724619.32      6853140.41
#Sta/Elev= 30
  4645.2  445.67  4655.8  446.03  4661.6  445.11  4680.8  444.68  4736.1  441.67
  4794.9  439.74  4816.5  440.03  4822.3  438.93  4841.0  438.40  4875.2  437.58
  4891.0  437.74  4896.8  437.58  4903.2  436.69  4918.3  437.27  4934.0  436.13
  4957.1  436.20  4984.1  436.06  4992.8  437.00  4995.9  433.56  4996.1  433.06
  4999.6  433.06  4999.9  433.56  5012.9  433.97  5019.0  437.19  5071.1  437.80
  5113.1  438.35  5133.1  440.10  5163.2  438.64  5273.4  441.50  5363.0  442.44
#Mann=7,-1,0
  4645.2    0.05       0  4680.8     0.1       0  4841.0    0.05       0
  4957.1    0.12       0  4995.9    0.07       0  4999.9    0.12       0
  5071.1    0.05       0
Bank Sta=4995.9,4999.9
Exp/Cntr=0.3,0.1

Type RM Length L Ch R = 1,14447,298,298,298
BEGIN DESCRIPTION:
Lacy 167 575
END DESCRIPTION:
XS GIS Cut Line= 3
      2724921.38      6852563.03      2724620.12      6852633.93
      2724131.49      6852804.39
#Sta/Elev= 30
  4695.6  445.77  4729.7  444.28  4803.9  442.16  4838.6  440.46  4896.3  437.66
  4906.6  437.92  4929.5  436.60  4988.8  434.95  5013.1  434.81  5020.0  433.83
  5059.0  434.77  5094.2  435.10  5126.0  433.97  5157.7  434.25  5163.1  433.13
  5166.4  431.84  5166.6  431.34  5170.1  431.34  5170.4  431.84  5178.9  434.03
  5188.9  435.29  5219.9  434.85  5231.9  435.77  5242.5  435.53  5255.8  436.12
  5287.4  436.92  5337.2  436.66  5422.5  436.55  5467.2  437.09  5522.6  437.20
#Mann=9,-1,0
  4695.6    0.05       0  4729.7     0.1       0  4838.6    0.05       0
  5059.0    0.12       0  5166.4    0.05       0  5170.4    0.12       0
  5255.8    0.05       0  5337.2    0.12       0  5467.2    0.05       0
Bank Sta=5166.4,5170.4
Exp/Cntr=0.3,0.1

Type RM Length L Ch R = 1,14149,248,248,248
BEGIN DESCRIPTION:
Lacy 167 573
END DESCRIPTION:
XS GIS Cut Line= 3
      2724889.92      6852398.66      2724390.17      6852576.62
      2723849.56      6852680.58
#Sta/Elev= 30
  4468.2  446.28  4612.5  441.28  4652.8  440.72  4663.4  439.33  4668.8  441.09
  4684.7  441.06  4823.0  435.00  4918.2  433.69  4966.5  433.88  4981.9  431.45
  4997.3  432.95  5023.3  432.59  5033.5  433.31  5043.5  432.68  5094.6  433.51
  5115.7  432.96  5135.3  431.72  5152.4  431.52  5157.5  433.59  5165.9  430.99
  5202.4  430.55  5202.6  430.05  5206.1  430.05  5206.4  430.55  5227.0  433.39
  5237.1  433.71  5288.1  433.03  5309.4  433.69  5451.0  433.30  5549.2  434.42
#Mann=5,-1,0
  4468.2    0.05       0  5115.7    0.12       0  5202.4    0.04       0
  5206.4    0.12       0  5309.4    0.05       0
Bank Sta=5202.4,5206.4
Exp/Cntr=0.3,0.1

Type RM Length L Ch R = 1,13901,115,115,115
BEGIN DESCRIPTION:
Lacy 167 574
END DESCRIPTION:
XS GIS Cut Line= 3
      2724598.79      6852228.18      2724226.66      6852409.15
      2723877.12      6852663.35
#Sta/Elev= 30
  4584.3  444.87  4609.6  445.06  4620.1  441.31  4665.2  439.07  4744.0  436.84
  4754.2  437.53  4766.6  436.44  4901.9  436.40  4932.1  434.68  4954.4  431.71
  4969.5  431.22  4976.6  430.02  4986.5  430.01  4992.1  431.01  5013.6  429.41
  5029.9  430.32  5049.2  431.77  5072.3  431.42  5078.5  431.09  5083.5  427.66
  5083.7  427.16  5087.5  427.66  5093.2  431.47  5164.3  430.84  5179.0  429.97
  5199.9  431.95  5239.9  432.06  5379.9  432.78  5407.0  433.90  5430.3  433.86
#Mann=5,-1,0
  4584.3    0.05       0  5029.9    0.12       0  5083.5    0.04       0
  5087.5    0.12       0  5239.9    0.05       0
Bank Sta=5083.5,5087.5
Exp/Cntr=0.3,0.1

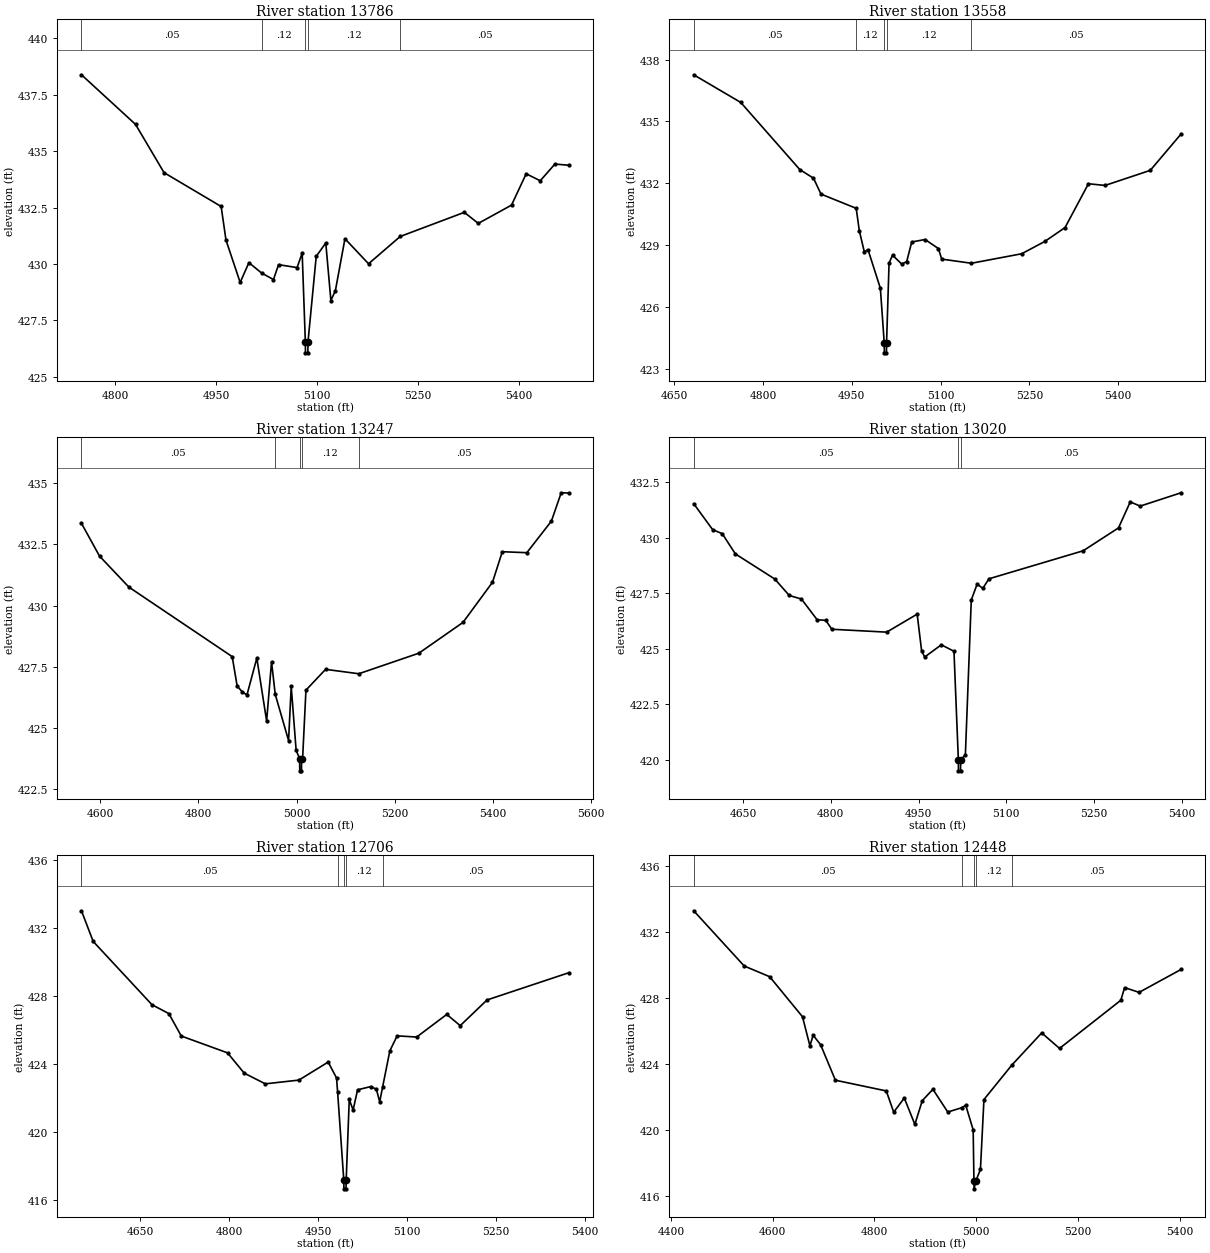
Type RM Length L Ch R = 1,13786,228,228,228
BEGIN DESCRIPTION:
Lacy 167 572
END DESCRIPTION:
XS GIS Cut Line= 3
      2724322.95      6852154.20      2724142.62      6852329.26
      2723830.64      6852685.28
#Sta/Elev= 30
  4749.8  438.39  4830.2  436.19  4872.6  434.05  4957.5  432.55  4964.7  431.06
  4985.8  429.18  4998.8  430.06  5017.6  429.60  5035.3  429.31  5042.9  429.97
  5070.4  429.84  5078.0  430.48  5082.7  426.56  5082.9  426.06  5086.4  426.06
  5086.7  426.56  5098.9  430.34  5113.1  430.93  5120.7  428.38  5127.4  428.82
  5141.6  431.12  5176.7  430.01  5223.8  431.22  5319.1  432.29  5339.9  431.80
  5389.3  432.61  5411.1  434.00  5432.0  433.69  5453.8  434.43  5474.5  434.38
#Mann=5,-1,0
  4749.8    0.05       0  5017.6    0.12       0  5082.7    0.04       0
  5086.7    0.12       0  5223.8    0.05       0
Bank Sta=5082.7,5086.7
Exp/Cntr=0.3,0.1

Type RM Length L Ch R = 1,13558,311,311,311
BEGIN DESCRIPTION:
Lacy 167 571
END DESCRIPTION:
XS GIS Cut Line= 3
      2724220.45      6852014.16      2723944.87      6852212.95
      2723732.93      6852647.75
#Sta/Elev= 30
  4682.9  437.26  4762.4  435.92  4862.1  432.67  4885.3  432.25  4898.0  431.48
  4957.5  430.79  4962.7  429.71  4971.2  428.68  4977.4  428.79  4998.3  426.92
  5004.8  424.29  5005.1  423.79  5008.6  423.79  5008.8  424.29  5013.0  428.14
  5018.9  428.52  5034.4  428.09  5042.8  428.21  5051.3  429.16  5073.9  429.28
  5096.4  428.84  5102.0  428.33  5152.2  428.13  5237.2  428.59  5276.4  429.19
  5310.4  429.86  5349.9  431.98  5378.0  431.90  5454.4  432.63  5506.4  434.39
#Mann=5,-1,0
  4682.9    0.05       0  4957.5    0.12       0  5004.8    0.07       0
  5008.8    0.12       0  5152.2    0.05       0
Bank Sta=5004.8,5008.8
Exp/Cntr=0.3,0.1

Type RM Length L Ch R = 1,13247,227,227,227
BEGIN DESCRIPTION:
Lacy 167 579
END DESCRIPTION:
XS GIS Cut Line= 3
      2723699.38      6851664.30      2723722.49      6852114.25
      2723716.45      6852656.47
#Sta/Elev= 30
  4561.8  433.36  4598.6  432.02  4658.6  430.75  4868.9  427.91  4878.9  426.71
  4888.9  426.48  4898.9  426.34  4919.0  427.85  4939.0  425.28  4949.0  427.70
  4956.5  426.37  4983.7  424.48  4989.1  426.69  4999.1  424.08  5006.2  423.74
  5006.5  423.24  5010.0  423.24  5010.2  423.74  5012.3  423.74  5019.1  426.54
  5059.1  427.39  5126.7  427.21  5249.1  428.05  5339.1  429.31  5399.1  430.95
  5419.1  432.20  5469.1  432.16  5519.1  433.45  5539.1  434.61  5554.6  434.60
#Mann=5,-1,0
  4561.8    0.05       0  4956.5    0.12       0  5006.2    0.07       0
  5010.2    0.12       0  5126.7    0.05       0
Bank Sta=5006.2,5010.2
Exp/Cntr=0.3,0.1

Type RM Length L Ch R = 1,13020,314,314,314
BEGIN DESCRIPTION:
Lacy 167 570
END DESCRIPTION:
XS GIS Cut Line= 3
      2723639.76      6851694.13      2723517.56      6852117.27
      2723473.34      6852507.24
#Sta/Elev= 30
  4565.7  431.53  4598.1  430.36  4614.5  430.18  4636.9  429.27  4704.2  428.14
  4729.0  427.40  4749.8  427.24  4776.6  426.31  4791.4  426.28  4801.8  425.88
  4895.5  425.75  4947.6  426.56  4955.2  424.91  4960.4  424.63  4988.9  425.18
  5010.5  424.89  5018.0  420.01  5018.2  419.51  5021.7  419.51  5022.0  420.01
  5030.0  420.23  5040.1  427.20  5050.1  427.91  5059.8  427.72  5070.3  428.15
  5231.3  429.41  5291.7  430.44  5311.8  431.61  5328.8  431.42  5398.6  432.02
#Mann=3,-1,0
  4565.7    0.05       0  5018.0    0.05       0  5022.0    0.05       0
Bank Sta=5018,5022
Exp/Cntr=0.3,0.1

Type RM Length L Ch R = 1,12706,258,258,258
BEGIN DESCRIPTION:
Lacy 167 569
END DESCRIPTION:
XS GIS Cut Line= 3
      2723575.34      6851622.47      2723259.20      6851955.39
      2723101.82      6852281.60
#Sta/Elev= 30
  4551.4  433.00  4571.1  431.20  4670.2  427.48  4698.6  426.96  4719.6  425.64
  4797.6  424.65  4825.6  423.46  4861.2  422.83  4917.8  423.05  4967.2  424.11
  4981.3  423.17  4983.1  422.33  4993.5  417.16  4993.7  416.66  4997.2  416.66
  4997.5  417.16  5002.7  421.91  5009.2  421.29  5016.7  422.48  5039.0  422.67
  5048.4  422.51  5054.0  421.77  5059.0  422.66  5071.1  424.77  5083.4  425.65
  5116.3  425.58  5167.0  426.91  5189.7  426.25  5234.9  427.76  5372.7  429.36
#Mann=5,-1,0
  4551.4    0.05       0  4983.1    0.12       0  4993.5    0.07       0
  4997.5    0.12       0  5059.0    0.05       0
Bank Sta=4993.5,4997.5
Exp/Cntr=0.3,0.1

Type RM Length L Ch R = 1,12448,236,236,236
BEGIN DESCRIPTION:
Lacy 167 568
END DESCRIPTION:
XS GIS Cut Line= 3
      2723541.98      6851447.64      2723095.86      6851780.14
      2722829.91      6852081.87
#Sta/Elev= 30
  4444.4  433.31  4543.7  429.96  4593.8  429.31  4658.4  426.88  4673.0  425.11
  4679.3  425.76  4693.9  425.19  4723.1  423.03  4823.2  422.38  4837.8  421.09
  4858.6  421.95  4879.4  420.35  4894.0  421.79  4914.9  422.48  4944.1  421.10
  4971.5  421.36  4979.5  421.51  4994.1  420.02  4995.6  416.94  4995.8  416.44
  4999.6  416.94  5008.4  417.62  5015.3  421.86  5070.2  423.95  5128.9  425.90
  5164.0  424.96  5284.5  427.88  5292.0  428.65  5320.5  428.36  5403.0  429.75
#Mann=5,-1,0
  4444.4    0.05       0  4971.5    0.12       0  4995.6    0.07       0
  4999.6    0.12       0  5070.2    0.05       0
Bank Sta=4995.6,4999.6
Exp/Cntr=0.3,0.1

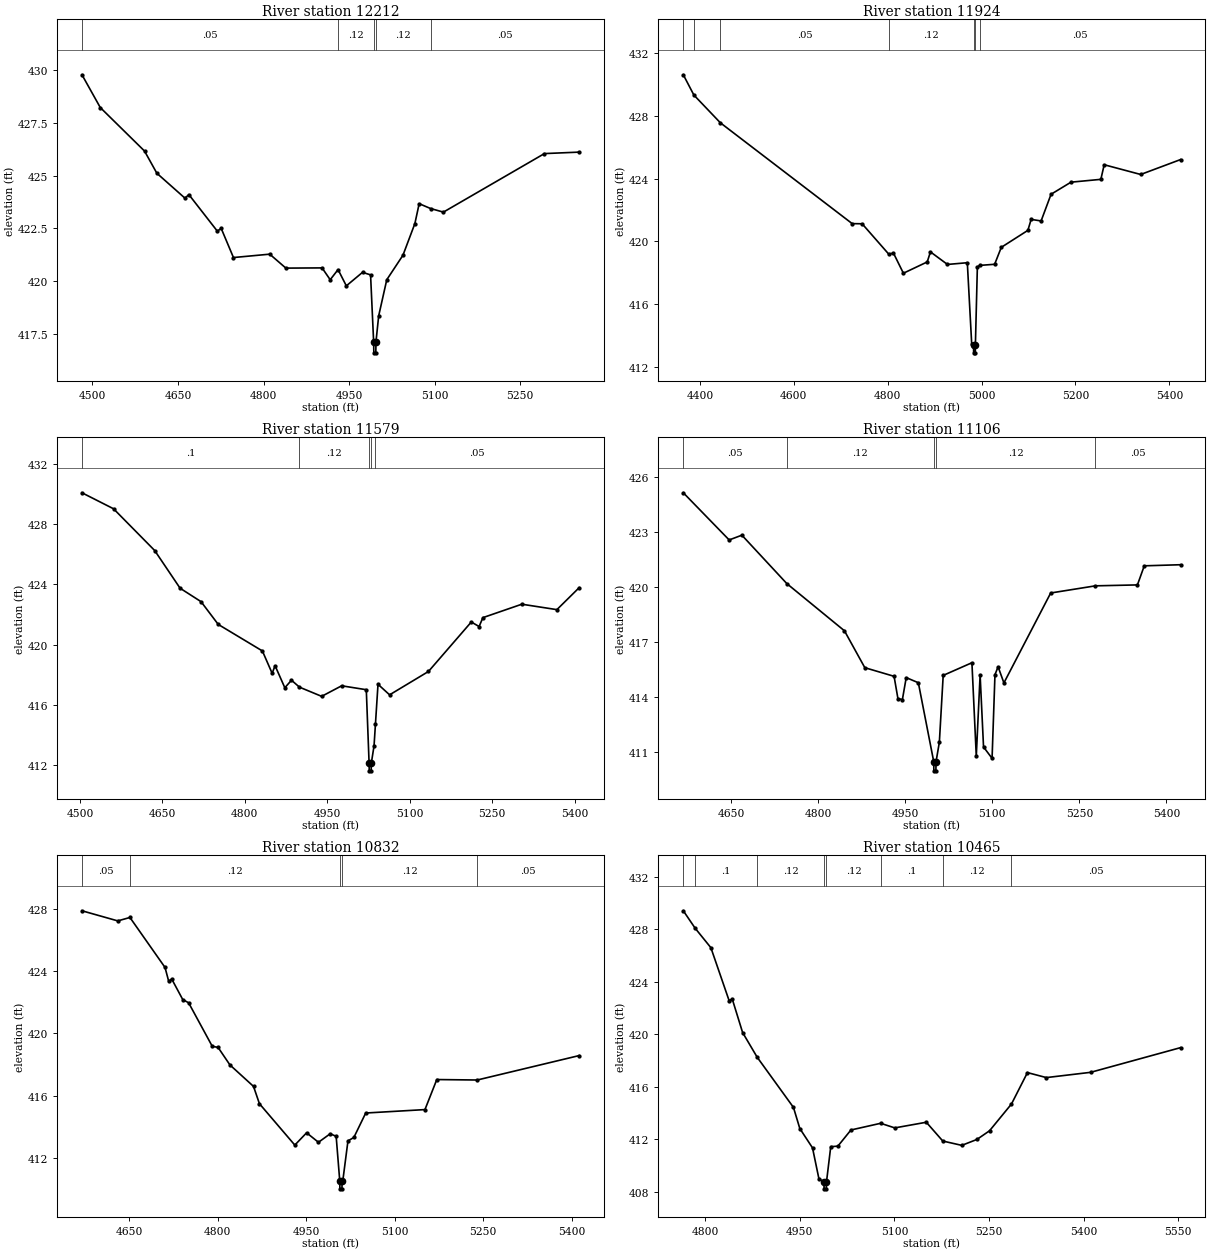
Type RM Length L Ch R = 1,12212,288,288,288
BEGIN DESCRIPTION:
Lacy 167 567
END DESCRIPTION:
XS GIS Cut Line= 3
      2723373.15      6851222.94      2722990.44      6851577.66
      2722731.61      6851813.23
#Sta/Elev= 30
  4481.7  429.77  4513.8  428.22  4591.4  426.16  4613.0  425.11  4662.3  423.93
  4669.1  424.10  4719.0  422.37  4725.8  422.50  4747.3  421.12  4810.9  421.28
  4839.2  420.62  4902.7  420.63  4916.9  420.07  4930.7  420.55  4945.2  419.78
  4973.6  420.42  4987.7  420.30  4993.1  417.11  4993.4  416.61  4996.9  416.61
  4997.1  417.11  5001.9  418.36  5016.1  420.07  5044.5  421.23  5065.4  422.73
  5072.9  423.67  5092.9  423.44  5115.4  423.27  5292.5  426.04  5353.5  426.11
#Mann=5,-1,0
  4481.7    0.05       0  4930.7    0.12       0  4993.1    0.07       0
  4997.1    0.12       0  5092.9    0.05       0
Bank Sta=4993.1,4997.1
Exp/Cntr=0.3,0.1

Type RM Length L Ch R = 1,11924,345,345,345
BEGIN DESCRIPTION:
Lacy 167 565
END DESCRIPTION:
XS GIS Cut Line= 3
      2723353.89      6851012.03      2722812.72      6851357.92
      2722517.27      6851652.39
#Sta/Elev= 30
  4364.5  430.61  4387.0  429.32  4443.5  427.55  4724.3  421.13  4745.5  421.12
  4802.1  419.19  4812.3  419.25  4833.4  417.97  4884.2  418.69  4891.0  419.33
  4927.3  418.53  4969.6  418.64  4978.9  413.48  4982.8  413.40  4983.1  412.90
  4986.6  412.90  4986.8  413.40  4991.0  418.37  4996.2  418.47  5027.8  418.54
  5042.0  419.62  5098.6  420.70  5105.6  421.40  5126.8  421.30  5148.0  423.00
  5190.5  423.77  5254.1  423.95  5261.2  424.88  5339.0  424.26  5423.9  425.21
#Mann=7,-1,0
  4364.5    0.05       0  4387.0    0.12       0  4443.5    0.05       0
  4802.1    0.12       0  4982.8    0.05       0  4986.8    0.12       0
  4996.2    0.05       0
Bank Sta=4982.8,4986.8
Exp/Cntr=0.3,0.1

Type RM Length L Ch R = 1,11579,473,473,473
BEGIN DESCRIPTION:
Lacy 167 566
END DESCRIPTION:
XS GIS Cut Line= 3
      2723253.37      6850882.41      2722799.19      6851087.45
      2722517.02      6851379.62
#Sta/Elev= 30
  4503.8  430.07  4561.2  429.01  4636.1  426.24  4682.3  423.74  4720.4  422.85
  4751.7  421.34  4832.0  419.58  4849.7  418.10  4855.1  418.60  4872.8  417.14
  4884.9  417.64  4899.4  417.18  4939.8  416.57  4976.2  417.27  5021.0  417.01
  5026.1  412.13  5026.4  411.63  5029.9  411.63  5030.1  412.13  5035.1  413.29
  5037.7  414.76  5042.3  417.37  5063.4  416.67  5134.1  418.22  5212.0  421.50
  5226.2  421.20  5233.1  421.79  5303.9  422.68  5367.7  422.32  5408.3  423.78
#Mann=5,-1,0
  4503.8     0.1       0  4899.4    0.12       0  5026.1    0.07       0
  5030.1    0.12       0  5037.7    0.05       0
Bank Sta=5026.1,5030.1
Exp/Cntr=0.3,0.1

Type RM Length L Ch R = 1,11106,274,274,274
BEGIN DESCRIPTION:
Lacy 167 564
END DESCRIPTION:
XS GIS Cut Line= 3
      2722930.71      6850454.06      2722593.33      6850846.27
      2722552.44      6851183.04
#Sta/Elev= 30
  4567.7  425.13  4646.7  422.56  4668.6  422.82  4746.1  420.18  4845.3  417.61
  4880.4  415.60  4930.8  415.13  4937.4  413.92  4945.1  413.86  4951.7  415.06
  4972.6  414.78  4999.1  410.48  4999.3  409.98  5002.8  409.98  5003.1  410.48
  5008.8  411.54  5015.4  415.18  5064.9  415.87  5072.4  410.78  5079.0  415.21
  5084.9  411.28  5099.6  410.66  5104.6  415.22  5110.0  415.65  5120.0  414.77
  5200.6  419.67  5277.7  420.06  5350.0  420.11  5361.8  421.15  5424.3  421.21
#Mann=5,-1,0
  4567.7    0.05       0  4746.1    0.12       0  4999.1    0.07       0
  5003.1    0.12       0  5277.7    0.05       0
Bank Sta=4999.1,5003.1
Exp/Cntr=0.3,0.1

Type RM Length L Ch R = 1,10832,367,367,367
BEGIN DESCRIPTION:
Lacy 167 562
END DESCRIPTION:
XS GIS Cut Line= 3
      2722457.05      6850170.28      2722468.80      6850612.18
      2722433.07      6851011.43
#Sta/Elev= 30
  4570.0  427.88  4630.7  427.23  4651.3  427.45  4710.8  424.24  4717.1  423.34
  4722.1  423.50  4740.8  422.18  4750.8  421.97  4790.8  419.18  4800.8  419.10
  4820.8  417.98  4860.8  416.60  4870.8  415.49  4930.8  412.83  4950.8  413.62
  4970.9  413.01  4990.9  413.56  5000.9  413.39  5007.0  410.52  5007.2  410.02
  5010.7  410.02  5011.0  410.52  5012.1  410.52  5020.9  413.10  5030.9  413.32
  5051.0  414.89  5151.4  415.11  5171.5  417.04  5240.0  417.01  5412.9  418.58
#Mann=5,-1,0
  4570.0    0.05       0  4651.3    0.12       0  5007.0    0.07       0
  5011.0    0.12       0  5240.0    0.05       0
Bank Sta=5007,5011
Exp/Cntr=0.3,0.1

Type RM Length L Ch R = 1,10465,267,267,267
BEGIN DESCRIPTION:
Lacy 167 563
END DESCRIPTION:
XS GIS Cut Line= 3
      2722239.84      6850227.59      2722212.32      6850463.34
      2722181.91      6851013.35
#Sta/Elev= 30
  4765.4  429.41  4784.2  428.08  4809.1  426.60  4838.0  422.57  4843.0  422.69
  4859.4  420.14  4882.5  418.26  4940.0  414.44  4950.1  412.83  4970.2  411.36
  4980.3  409.02  4988.3  408.74  4988.6  408.24  4992.1  408.24  4992.3  408.74
  4999.1  411.45  5010.4  411.49  5031.1  412.72  5078.2  413.23  5100.6  412.88
  5150.6  413.31  5176.7  411.88  5206.8  411.55  5230.8  412.00  5250.8  412.66
  5285.6  414.70  5310.9  417.09  5340.9  416.71  5411.0  417.11  5553.6  418.99
#Mann=8,-1,0
  4765.4    0.05       0  4784.2     0.1       0  4882.5    0.12       0
  4988.3    0.07       0  4992.3    0.12       0  5078.2     0.1       0
  5176.7    0.12       0  5285.6    0.05       0
Bank Sta=4988.3,4992.3
Exp/Cntr=0.3,0.1

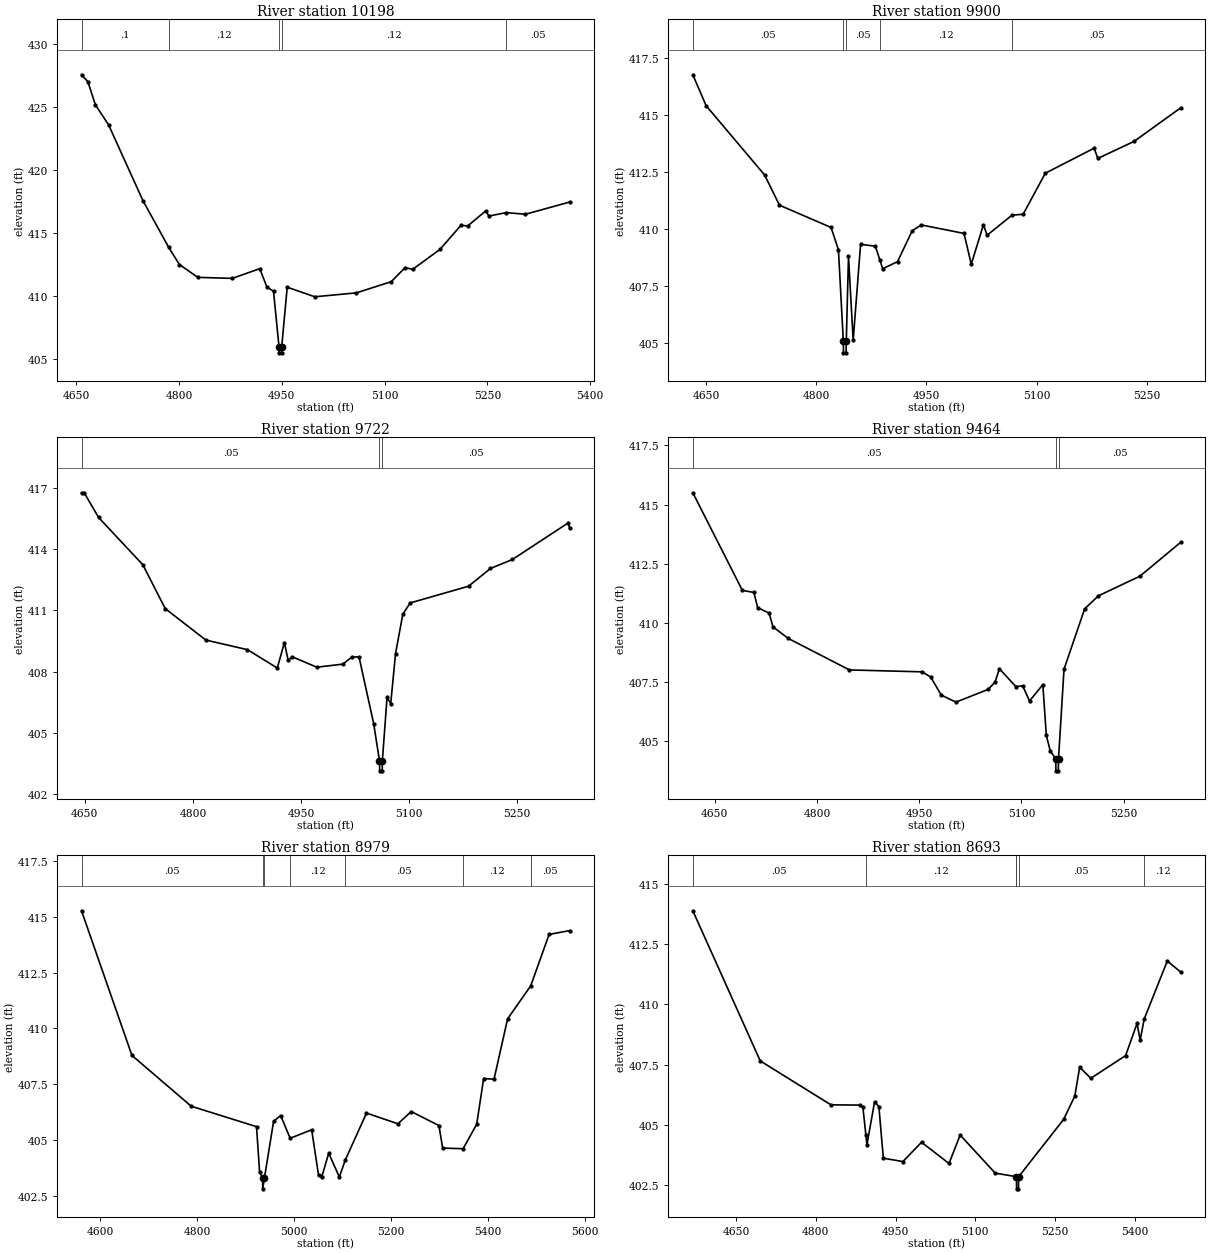
Type RM Length L Ch R = 1,10198,298,298,298
BEGIN DESCRIPTION:
Lacy 167 554
END DESCRIPTION:
XS GIS Cut Line= 3
      2722002.29      6850211.64      2721974.38      6850559.12
      2721909.00      6850917.30
#Sta/Elev= 30
  4657.5  427.56  4666.9  427.00  4677.8  425.17  4697.0  423.59  4747.1  417.58
  4784.6  413.88  4800.4  412.50  4827.4  411.48  4877.6  411.40  4917.7  412.17
  4928.1  410.72  4937.8  410.37  4945.8  405.99  4946.0  405.49  4949.5  405.49
  4949.8  405.99  4957.8  410.70  4998.0  409.94  5058.8  410.25  5109.7  411.14
  5130.0  412.26  5140.8  412.11  5180.8  413.70  5211.3  415.60  5221.5  415.57
  5247.3  416.74  5252.4  416.35  5277.7  416.62  5305.6  416.49  5370.2  417.46
#Mann=5,-1,0
  4657.5     0.1       0  4784.6    0.12       0  4945.8    0.07       0
  4949.8    0.12       0  5277.7    0.05       0
Bank Sta=4945.8,4949.8
Exp/Cntr=0.3,0.1

Type RM Length L Ch R = 1,9900,178,178,178
BEGIN DESCRIPTION:
Lacy 167 553
END DESCRIPTION:
XS GIS Cut Line= 3
      2721782.42      6850193.59      2721745.35      6850556.39
      2721705.37      6850854.23
#Sta/Elev= 30
  4631.6  416.78  4649.8  415.42  4729.5  412.38  4749.6  411.06  4820.0  410.08
  4830.0  409.10  4836.7  405.08  4836.9  404.58  4840.4  404.58  4840.7  405.08
  4843.7  408.81  4850.1  405.13  4860.2  409.34  4880.3  409.26  4886.6  408.64
  4890.3  408.27  4910.5  408.58  4930.6  409.94  4943.1  410.19  5001.1  409.82
  5011.0  408.47  5027.6  410.20  5032.6  409.74  5066.5  410.62  5081.7  410.66
  5111.9  412.46  5178.4  413.56  5183.5  413.11  5233.0  413.86  5296.8  415.34
#Mann=5,-1,0
  4631.6    0.05       0  4836.7    0.07       0  4840.7    0.05       0
  4886.6    0.12       0  5066.5    0.05       0
Bank Sta=4836.7,4840.7
Exp/Cntr=0.3,0.1

Type RM Length L Ch R = 1,9722,258,258,258
BEGIN DESCRIPTION:
Lacy 167 552
END DESCRIPTION:
XS GIS Cut Line= 3
      2721696.04      6850118.85      2721602.08      6850464.74
      2721550.85      6850779.47
#Sta/Elev= 30
  4645.4  416.77  4649.1  416.77  4669.1  415.56  4730.5  413.24  4761.6  411.09
  4817.9  409.55  4875.6  409.08  4917.0  408.18  4926.9  409.43  4932.1  408.55
  4937.8  408.73  4971.9  408.22  5007.8  408.37  5020.3  408.71  5030.4  408.73
  5050.7  405.46  5058.8  403.64  5059.1  403.14  5062.6  403.14  5062.8  403.64
  5069.3  406.74  5074.4  406.44  5081.1  408.89  5091.2  410.82  5101.4  411.37
  5182.4  412.19  5212.8  413.06  5243.2  413.50  5320.5  415.29  5322.7  415.03
#Mann=3,-1,0
  4645.4    0.05       0  5058.8    0.05       0  5062.8    0.05       0
Bank Sta=5058.8,5062.8
Exp/Cntr=0.3,0.1

Type RM Length L Ch R = 1,9464,485,485,485
BEGIN DESCRIPTION:
Lacy 167 551
END DESCRIPTION:
XS GIS Cut Line= 3
      2721571.76      6849967.92      2721400.70      6850314.59
      2721351.26      6850640.79
#Sta/Elev= 30
  4617.7  415.50  4690.4  411.38  4707.3  411.29  4712.9  410.65  4729.7  410.42
  4735.3  409.84  4757.8  409.35  4847.6  408.02  4954.3  407.94  4966.8  407.72
  4982.3  406.96  5003.9  406.66  5051.2  407.20  5061.3  407.51  5067.7  408.07
  5091.7  407.32  5101.8  407.35  5111.9  406.71  5131.4  407.40  5136.5  405.26
  5142.2  404.61  5150.4  404.26  5150.6  403.76  5154.1  403.76  5154.4  404.26
  5162.5  408.05  5192.8  410.60  5213.0  411.15  5274.0  411.98  5334.2  413.42
#Mann=3,-1,0
  4617.7    0.05       0  5150.4    0.04       0  5154.4    0.05       0
Bank Sta=5150.4,5154.4
Exp/Cntr=0.3,0.1

Type RM Length L Ch R = 1,8979,286,286,286
BEGIN DESCRIPTION:
Lacy 167 550
END DESCRIPTION:
XS GIS Cut Line= 3
      2721504.64      6849823.45      2721152.39      6850098.41
      2720727.59      6850462.60
#Sta/Elev= 30
  4561.7  415.28  4665.6  408.79  4787.7  406.51  4922.5  405.59  4928.8  403.56
  4934.9  403.30  4935.2  402.80  4938.9  403.30  4957.7  405.83  4972.2  406.09
  4991.9  405.07  5036.2  405.45  5050.4  403.40  5057.0  403.33  5071.3  404.40
  5093.2  403.33  5105.4  404.09  5149.2  406.20  5214.0  405.72  5241.4  406.27
  5298.5  405.64  5306.2  404.63  5348.4  404.60  5376.4  405.70  5390.7  407.75
  5412.1  407.72  5440.1  410.43  5487.7  411.91  5525.7  414.22  5568.1  414.39
#Mann=7,-1,0
  4561.7    0.05       0  4934.9    0.07       0  4938.9    0.05       0
  4991.9    0.12       0  5105.4    0.05       0  5348.4    0.12       0
  5487.7    0.05       0
Bank Sta=4934.9,4938.9
Exp/Cntr=0.3,0.1

Type RM Length L Ch R = 1,8693,237,237,237
BEGIN DESCRIPTION:
Lacy 167 549
END DESCRIPTION:
XS GIS Cut Line= 3
      2721426.47      6849678.78      2721040.70      6849880.22
      2720639.45      6850150.35
#Sta/Elev= 30
  4568.5  413.87  4695.4  407.65  4828.5  405.83  4882.9  405.82  4888.6  405.73
  4894.2  404.59  4896.2  404.18  4910.6  405.95  4918.7  405.76  4927.1  403.62
  4963.9  403.48  4999.0  404.28  5050.7  403.40  5071.7  404.58  5137.7  403.00
  5175.9  402.86  5177.7  402.85  5177.9  402.35  5181.4  402.35  5181.7  402.85
  5266.6  405.23  5287.6  406.20  5296.6  407.39  5317.6  406.93  5383.1  407.87
  5404.6  409.20  5410.6  408.51  5418.0  409.38  5461.6  411.79  5487.4  411.32
#Mann=6,-1,0
  4568.5    0.05       0  4894.2    0.12       0  5175.9    0.05       0
  5177.7    0.07       0  5181.7    0.05       0  5418.0    0.12       0
Bank Sta=5177.7,5181.7
Exp/Cntr=0.3,0.1

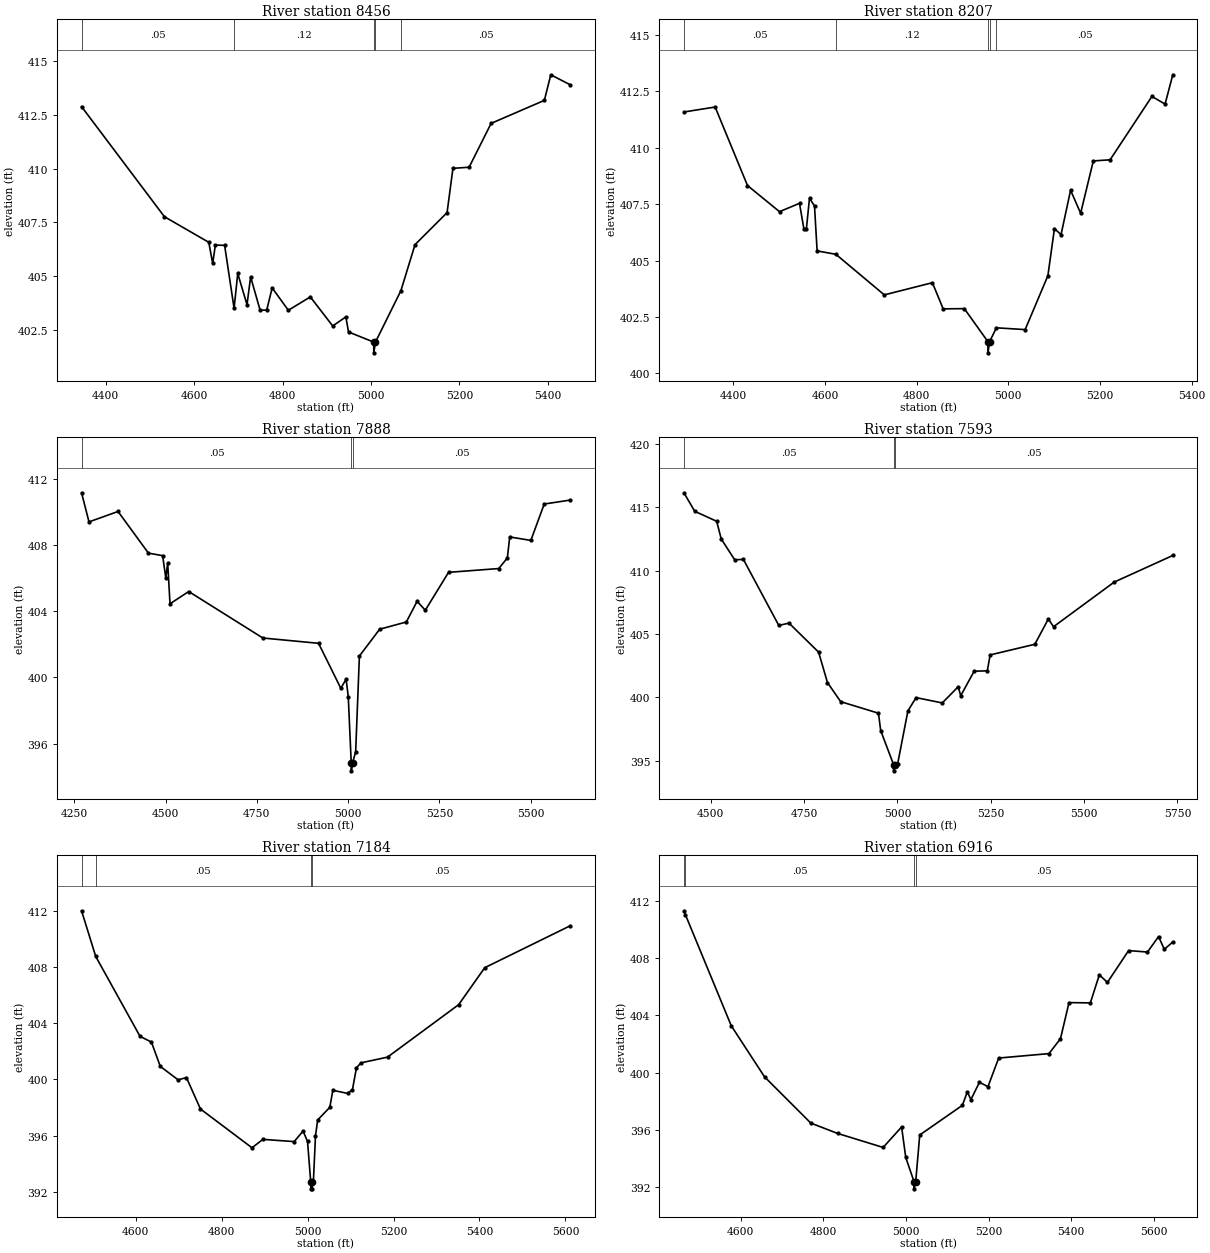
Type RM Length L Ch R = 1,8456,249,249,249
BEGIN DESCRIPTION:
Lacy 167 548
END DESCRIPTION:
XS GIS Cut Line= 3
      2721379.91      6849503.63      2720844.74      6849875.66
      2720485.83      6850153.08
#Sta/Elev= 30
  4345.5  412.88  4532.9  407.76  4633.2  406.57  4642.0  405.59  4648.1  406.44
  4669.0  406.43  4690.4  403.50  4698.7  405.12  4719.6  403.67  4727.8  404.96
  4749.3  403.41  4764.2  403.42  4776.5  404.45  4813.1  403.41  4862.8  404.03
  4913.4  402.68  4943.1  403.10  4949.2  402.40  5006.1  401.93  5006.3  401.43
  5010.1  401.93  5067.6  404.32  5099.5  406.46  5172.0  407.95  5185.3  410.01
  5221.8  410.06  5271.6  412.10  5392.0  413.17  5406.5  414.36  5450.9  413.89
#Mann=5,-1,0
  4345.5    0.05       0  4690.4    0.12       0  5006.1    0.07       0
  5010.1    0.12       0  5067.6    0.05       0
Bank Sta=5006.1,5010.1
Exp/Cntr=0.3,0.1

Type RM Length L Ch R = 1,8207,319,319,319
BEGIN DESCRIPTION:
Lacy 167 543
END DESCRIPTION:
XS GIS Cut Line= 3
      2721347.43      6849400.70      2720700.58      6849680.09
      2720420.11      6849908.31
#Sta/Elev= 30
  4292.5  411.59  4360.6  411.81  4431.1  408.33  4501.0  407.17  4544.6  407.54
  4554.1  406.41  4559.5  406.39  4566.4  407.77  4577.3  407.42  4583.0  405.43
  4623.9  405.28  4729.5  403.48  4834.4  404.02  4857.9  402.86  4904.1  402.87
  4955.3  401.41  4955.6  400.91  4959.3  401.41  4974.0  402.02  5036.7  401.94
  5086.3  404.33  5100.6  406.42  5115.0  406.15  5135.8  408.12  5157.7  407.10
  5185.4  409.42  5222.0  409.47  5313.2  412.28  5341.9  411.94  5358.7  413.24
#Mann=5,-1,0
  4292.5    0.05       0  4623.9    0.12       0  4955.3    0.04       0
  4959.3    0.12       0  4974.0    0.05       0
Bank Sta=4955.3,4959.3
Exp/Cntr=0.3,0.1

Type RM Length L Ch R = 1,7888,295,295,295
BEGIN DESCRIPTION:
Lacy 167 544
END DESCRIPTION:
XS GIS Cut Line= 3
      2721344.31      6849282.87      2720553.63      6849430.77
      2720099.34      6849713.54
#Sta/Elev= 30
  4269.7  411.16  4290.1  409.40  4369.7  410.03  4453.0  407.51  4491.8  407.36
  4500.6  406.01  4505.7  406.91  4512.1  404.45  4563.4  405.19  4766.5  402.38
  4919.1  402.06  4980.1  399.34  4994.6  399.89  5000.5  398.84  5008.6  394.85
  5008.9  394.35  5012.6  394.85  5020.8  395.51  5031.0  401.29  5086.5  402.91
  5159.7  403.35  5189.1  404.60  5211.6  404.06  5275.3  406.35  5412.9  406.58
  5436.4  407.22  5442.9  408.49  5500.8  408.28  5537.4  410.48  5609.2  410.72
#Mann=3,-1,0
  4269.7    0.05       0  5008.6    0.04       0  5012.6    0.05       0
Bank Sta=5008.6,5012.6
Exp/Cntr=0.3,0.1

Type RM Length L Ch R = 1,7593,409,409,409
BEGIN DESCRIPTION:
Lacy 167 545
END DESCRIPTION:
XS GIS Cut Line= 3
      2721040.35      6848835.96      2720557.37      6849143.38
      2720074.45      6849700.23
#Sta/Elev= 30
  4427.9  416.14  4456.8  414.68  4515.6  413.89  4527.9  412.49  4563.9  410.85
  4587.2  410.88  4682.0  405.67  4709.5  405.85  4788.7  403.56  4812.4  401.16
  4847.9  399.65  4949.1  398.74  4955.0  397.37  4989.4  394.69  4989.6  394.19
  4993.4  394.69  5000.4  394.73  5027.9  398.92  5049.8  399.97  5120.0  399.55
  5162.7  400.83  5169.4  400.12  5205.5  402.06  5240.6  402.08  5248.2  403.34
  5367.9  404.18  5404.0  406.17  5418.2  405.57  5580.6  409.09  5737.5  411.19
#Mann=3,-1,0
  4427.9    0.05       0  4989.4    0.05       0  4993.4    0.05       0
Bank Sta=4989.4,4993.4
Exp/Cntr=0.3,0.1

Type RM Length L Ch R = 1,7184,268,268,268
BEGIN DESCRIPTION:
Lacy 167 546
END DESCRIPTION:
XS GIS Cut Line= 3
      2720337.21      6848504.43      2720192.97      6849024.10
      2720041.49      6849602.48
#Sta/Elev= 30
  4474.3  412.00  4507.3  408.75  4610.3  403.07  4636.8  402.66  4657.5  400.93
  4699.1  399.97  4718.2  400.14  4750.9  397.90  4870.8  395.14  4896.2  395.74
  4968.9  395.58  4989.6  396.33  5000.0  395.59  5007.4  392.72  5007.7  392.22
  5011.2  392.22  5011.4  392.72  5013.6  392.72  5018.5  395.99  5023.6  397.12
  5051.8  398.02  5058.9  399.23  5093.1  399.01  5104.5  399.28  5113.8  400.83
  5124.1  401.18  5186.1  401.59  5351.5  405.32  5412.2  407.95  5611.5  410.94
#Mann=4,-1,0
  4474.3    0.12       0  4507.3    0.05       0  5007.4    0.04       0
  5011.4    0.05       0
Bank Sta=5007.4,5011.4
Exp/Cntr=0.3,0.1

Type RM Length L Ch R = 1,6916,357,357,357
BEGIN DESCRIPTION:
Lacy 167 547
END DESCRIPTION:
XS GIS Cut Line= 3
      2720236.05      6848432.85      2719966.71      6848901.09
      2719805.38      6849524.27
#Sta/Elev= 30
  4462.2  411.29  4465.9  411.01  4576.9  403.26  4657.4  399.70  4769.5  396.47
  4834.2  395.75  4944.6  394.77  4989.4  396.20  4999.4  394.07  5019.5  392.38
  5019.7  391.88  5023.5  392.38  5033.3  395.64  5136.6  397.71  5148.5  398.65
  5157.2  398.11  5177.9  399.32  5198.5  399.01  5224.5  401.01  5346.3  401.32
  5374.1  402.36  5394.8  404.88  5446.5  404.86  5468.2  406.82  5487.8  406.29
  5539.1  408.51  5584.8  408.41  5611.7  409.49  5625.5  408.60  5646.1  409.11
#Mann=4,-1,0
  4462.2    0.12       0  4465.9    0.05       0  5019.5    0.04       0
  5023.5    0.05       0
Bank Sta=5019.5,5023.5
Exp/Cntr=0.3,0.1