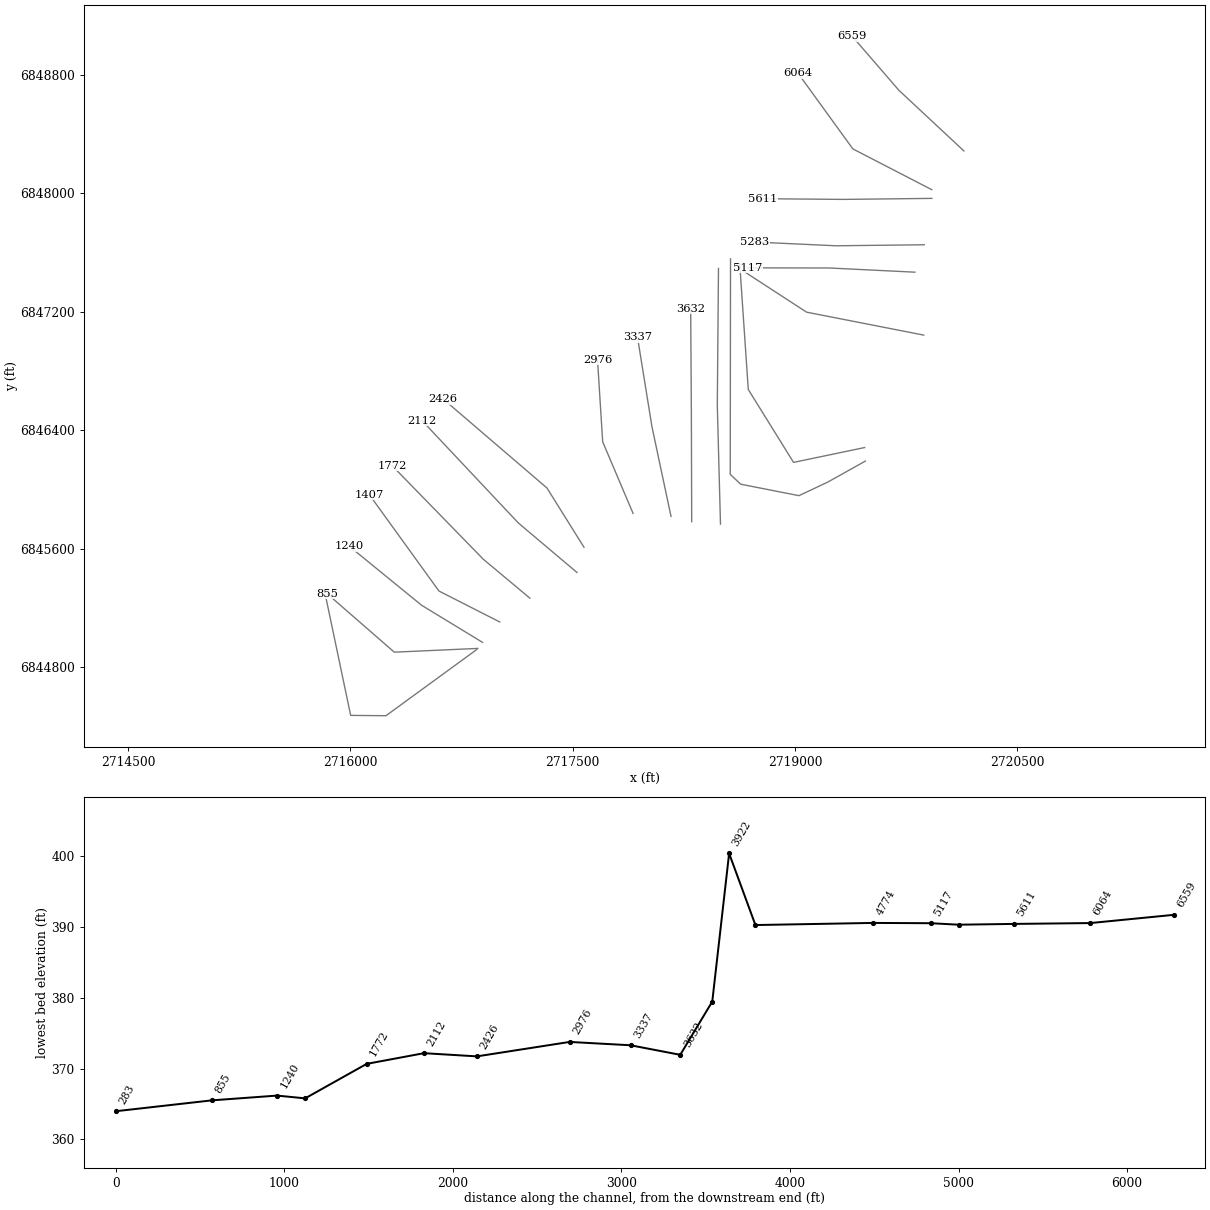
HEC-RAS study Lacy 167.prj: Lacy 167 Base Level Engineering

--- Lacy 167.g01 (geometry) --- (continued)

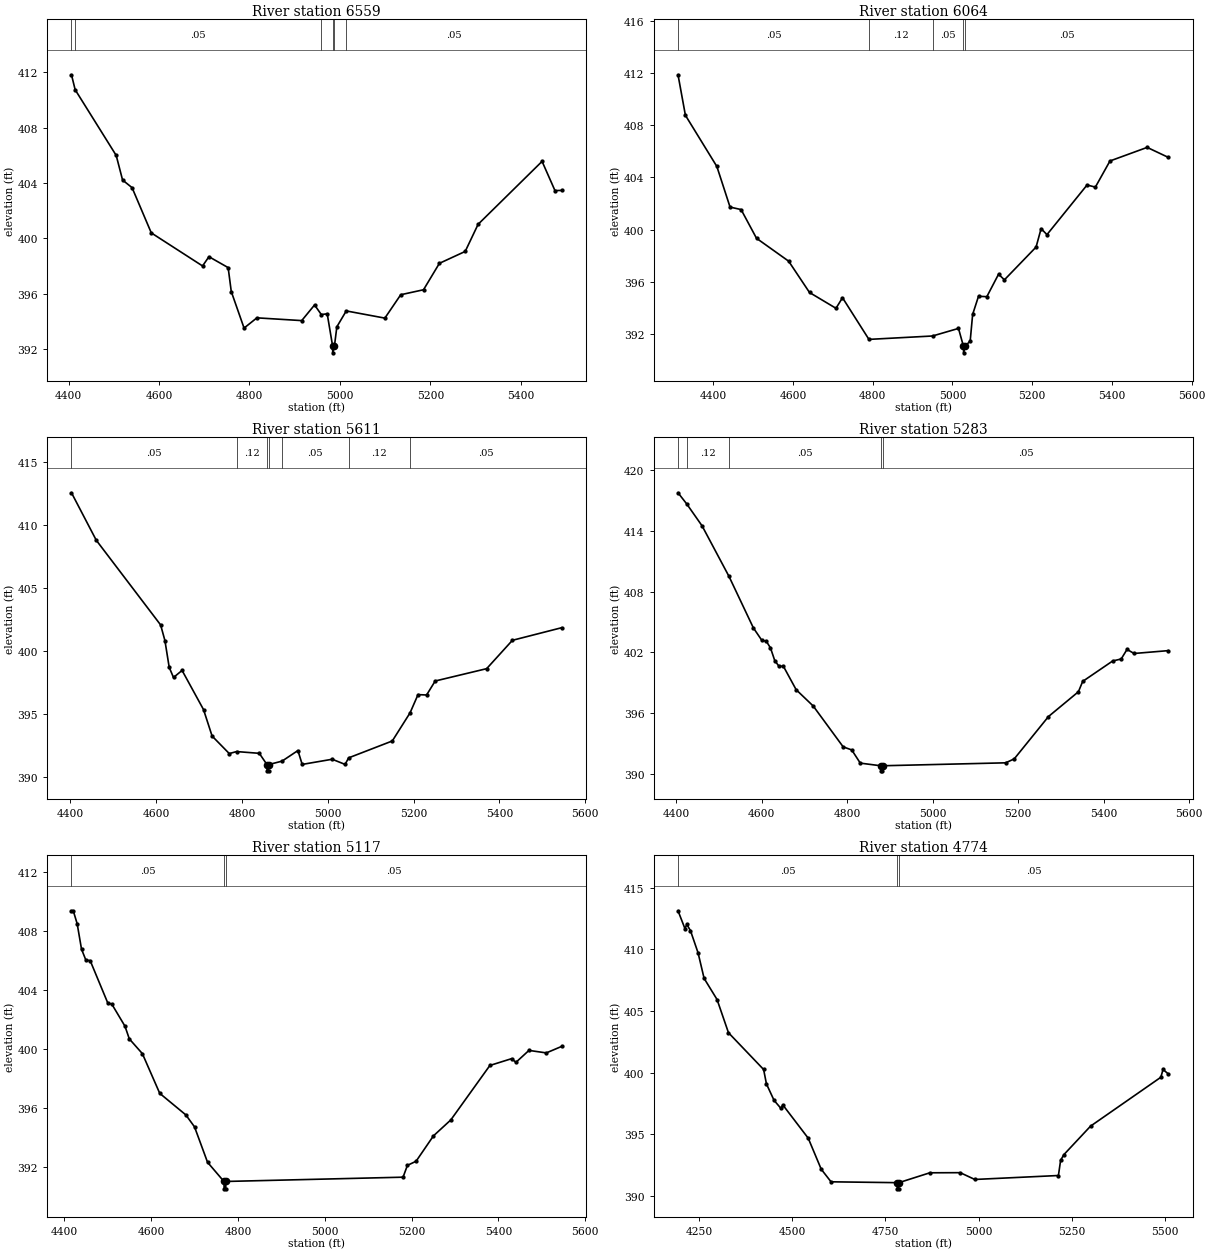
Type RM Length L Ch R = 1,6559,495,495,495
BEGIN DESCRIPTION:
Lacy 167 535
END DESCRIPTION:
XS GIS Cut Line= 3
      2720139.61      6848285.13      2719701.27      6848694.05
      2719384.38      6849060.73
#Sta/Elev= 30
  4406.3  411.83  4414.4  410.75  4505.2  406.00  4519.3  404.22  4540.3  403.67
  4582.8  400.40  4696.2  398.01  4710.3  398.68  4752.8  397.89  4759.7  396.16
  4788.0  393.52  4816.4  394.26  4915.5  394.06  4943.9  395.19  4958.8  394.50
  4971.9  394.55  4983.8  392.23  4984.1  391.73  4987.9  392.23  4993.2  393.61
  5014.0  394.76  5099.4  394.24  5134.5  395.93  5184.9  396.29  5220.0  398.20
  5277.1  399.06  5305.6  401.02  5447.1  405.57  5475.6  403.46  5490.4  403.47
#Mann=6,-1,0
  4406.3    0.12       0  4414.4    0.05       0  4958.8    0.12       0
  4983.8    0.07       0  4987.9    0.12       0  5014.0    0.05       0
Bank Sta=4983.8,4987.9
Exp/Cntr=0.3,0.1

Type RM Length L Ch R = 1,6064,453,453,453
BEGIN DESCRIPTION:
Lacy 167 534
END DESCRIPTION:
XS GIS Cut Line= 3
      2719922.44      6848023.78      2719390.25      6848298.92
      2719020.51      6848809.26
#Sta/Elev= 30
  4311.8  411.86  4330.3  408.76  4409.2  404.84  4442.3  401.73  4470.0  401.54
  4508.7  399.34  4589.2  397.59  4641.6  395.19  4708.0  393.98  4724.3  394.79
  4790.6  391.60  4950.1  391.86  5015.2  392.44  5027.7  391.07  5028.1  390.57
  5032.1  391.07  5044.6  391.49  5050.7  393.51  5065.4  394.90  5086.3  394.87
  5115.7  396.59  5130.4  396.16  5209.8  398.67  5222.4  400.08  5237.1  399.62
  5337.6  403.42  5358.5  403.26  5395.1  405.26  5488.4  406.30  5541.1  405.54
#Mann=5,-1,0
  4311.8    0.05       0  4790.6    0.12       0  4950.1    0.05       0
  5027.7    0.04       0  5032.1    0.05       0
Bank Sta=5027.7,5032.1
Exp/Cntr=0.3,0.1

Type RM Length L Ch R = 1,5611,328,328,328
BEGIN DESCRIPTION:
Lacy 167 533
END DESCRIPTION:
XS GIS Cut Line= 3
      2719923.76      6847964.94      2719327.66      6847958.05
      2718781.22      6847962.71
#Sta/Elev= 30
  4402.5  412.52  4460.3  408.75  4610.3  402.03  4620.3  400.79  4630.3  398.66
  4640.3  397.86  4660.3  398.42  4710.3  395.31  4730.3  393.21  4770.3  391.82
  4787.3  391.98  4840.3  391.84  4858.1  390.95  4858.5  390.45  4862.1  390.45
  4862.5  390.95  4893.3  391.22  4930.3  392.06  4940.3  390.96  5010.3  391.37
  5040.3  390.96  5048.5  391.48  5150.3  392.82  5191.7  395.05  5210.3  396.50
  5230.3  396.47  5250.3  397.58  5370.3  398.56  5430.3  400.81  5545.1  401.81
#Mann=7,-1,0
  4402.5    0.05       0  4787.3    0.12       0  4858.1    0.04       0
  4862.5    0.12       0  4893.3    0.05       0  5048.5    0.12       0
  5191.7    0.05       0
Bank Sta=4858.1,4862.5
Exp/Cntr=0.3,0.1

Type RM Length L Ch R = 1,5283,166,166,166
BEGIN DESCRIPTION:
Lacy 167 532
END DESCRIPTION:
XS GIS Cut Line= 3
      2719872.33      6847652.03      2719276.16      6847645.14
      2718726.26      6847670.50
#Sta/Elev= 30
  4404.0  417.73  4424.4  416.63  4460.3  414.47  4523.3  409.49  4580.3  404.42
  4600.3  403.18  4610.3  403.12  4620.3  402.45  4630.3  401.20  4640.4  400.63
  4650.4  400.65  4680.4  398.33  4720.4  396.72  4790.4  392.70  4810.4  392.40
  4830.4  391.10  4878.1  390.84  4878.6  390.34  4882.2  390.34  4882.6  390.84
  5170.6  391.13  5190.6  391.52  5270.7  395.69  5340.7  398.13  5350.7  399.15
  5420.8  401.16  5440.8  401.36  5454.4  402.30  5470.9  401.90  5550.7  402.18
#Mann=5,-1,0
  4404.0    0.05       0  4424.4    0.12       0  4523.3    0.05       0
  4878.1    0.03       0  4882.6    0.05       0
Bank Sta=4878.1,4882.6
Exp/Cntr=0.3,0.1

Type RM Length L Ch R = 1,5117,343,343,343
BEGIN DESCRIPTION:
Lacy 167 530
END DESCRIPTION:
XS GIS Cut Line= 3
      2719809.07      6847466.99      2719232.63      6847495.20
      2718680.67      6847496.26
#Sta/Elev= 30
  4416.5  409.39  4420.6  409.39  4429.6  408.51  4439.6  406.79  4449.6  406.05
  4459.6  406.01  4499.7  403.17  4509.7  403.05  4539.7  401.57  4549.7  400.71
  4579.8  399.71  4619.8  397.02  4679.9  395.56  4699.9  394.75  4729.9  392.35
  4767.7  391.05  4768.2  390.55  4771.8  390.55  4772.2  391.05  5180.3  391.34
  5190.3  392.14  5210.3  392.42  5250.3  394.14  5290.3  395.22  5380.3  398.91
  5430.3  399.37  5440.3  399.12  5470.3  399.93  5510.3  399.76  5545.6  400.20
#Mann=3,-1,0
  4416.5    0.05       0  4767.7    0.03       0  4772.2    0.05       0
Bank Sta=4767.7,4772.2
Exp/Cntr=0.3,0.1

Type RM Length L Ch R = 1,4774,696,696,696
BEGIN DESCRIPTION:
Lacy 167 531
END DESCRIPTION:
XS GIS Cut Line= 3
      2719868.77      6847042.37      2719077.97      6847197.21
      2718651.48      6847474.82
#Sta/Elev= 30
  4193.9  413.12  4212.4  411.68  4217.5  412.01  4227.3  411.51  4247.7  409.71
  4263.9  407.64  4298.6  405.93  4329.2  403.24  4423.5  400.26  4431.1  399.09
  4451.5  397.76  4469.9  397.11  4475.0  397.39  4543.2  394.69  4578.0  392.18
  4604.3  391.16  4781.7  391.09  4782.1  390.59  4785.7  390.59  4786.2  391.09
  4869.3  391.89  4950.8  391.90  4989.9  391.35  5214.2  391.67  5220.1  392.90
  5228.8  393.36  5300.4  395.67  5488.9  399.63  5494.8  400.26  5508.6  399.91
#Mann=3,-1,0
  4193.9    0.05       0  4781.7    0.03       0  4786.2    0.05       0
Bank Sta=4781.7,4786.2
Exp/Cntr=0.3,0.1

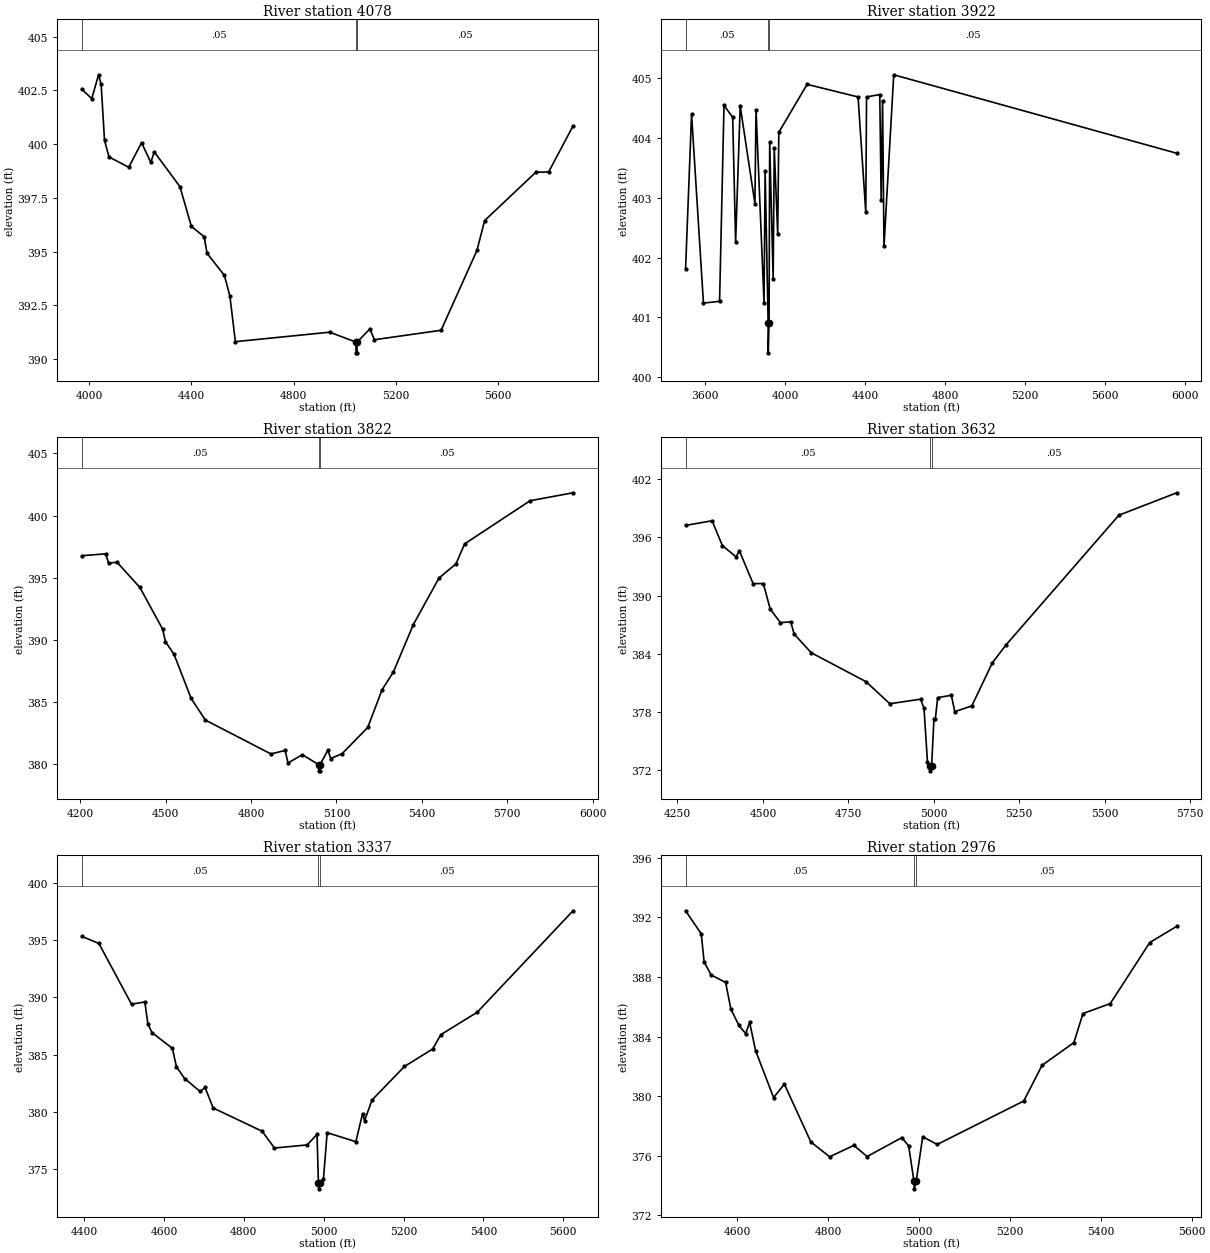
Type RM Length L Ch R = 1,4078,156,156,156
BEGIN DESCRIPTION:
Lacy 167 529
END DESCRIPTION:
XS GIS Cut Line= 4
      2719470.18      6846283.74      2718990.12      6846183.51
      2718684.68      6846675.50      2718626.80      6847526.13
#Sta/Elev= 30
  3971.5  402.55  4010.4  402.11  4037.1  403.22  4047.3  402.77  4060.4  400.17
  4077.9  399.40  4155.3  398.92  4205.3  400.06  4241.4  399.15  4255.3  399.63
  4355.4  398.02  4400.2  396.17  4450.3  395.69  4461.5  394.92  4529.6  393.89
  4551.1  392.92  4572.4  390.81  4941.5  391.25  5044.2  390.79  5044.7  390.29
  5048.4  390.29  5048.8  390.79  5098.4  391.40  5116.7  390.90  5377.3  391.34
  5517.6  395.05  5547.7  396.44  5748.1  398.69  5798.2  398.70  5893.6  400.84
#Mann=3,-1,0
  3971.5    0.05       0  5044.2    0.03       0  5048.8    0.05       0
Bank Sta=5044.2,5048.8
Exp/Cntr=0.3,0.1

Type RM Length L Ch R = 1,3922,100,100,100
BEGIN DESCRIPTION:
Lacy 167 3411
END DESCRIPTION:
XS GIS Cut Line= 6
      2719474.52      6846192.12      2719219.95      6846049.93
      2719026.44      6845958.96      2718633.43      6846036.35
      2718562.99      6846102.86      2718564.88      6847556.70
#Sta/Elev= 30
  3502.9  401.81  3532.9  404.39  3592.3  401.24  3673.0  401.27  3695.1  404.54
  3738.5  404.34  3753.2  402.26  3776.1  404.53  3849.7  402.90  3855.2  404.47
  3895.3  401.25  3900.8  403.44  3915.8  400.91  3916.2  400.41  3920.4  400.91
  3923.6  403.92  3940.9  401.65  3946.4  403.82  3963.7  402.39  3969.2  404.09
  4110.7  404.89  4365.5  404.68  4404.1  402.76  4408.0  404.68  4474.1  404.72
  4481.1  402.96  4488.0  404.62  4495.2  402.19  4543.9  405.05  5959.6  403.74
#Mann=3,-1,0
  3502.9    0.05       0  3915.8    0.05       0  3920.4    0.05       0
Bank Sta=3915.8,3920.4
Exp/Cntr=0.3,0.1

Type RM Length L Ch R = 1,3822,190,190,190
BEGIN DESCRIPTION:
Lacy 167 527
END DESCRIPTION:
XS GIS Cut Line= 3
      2718497.13      6845767.18      2718475.69      6846566.76
      2718483.66      6847491.76
#Sta/Elev= 30
  4205.9  396.78  4289.8  396.93  4299.8  396.19  4329.8  396.25  4409.8  394.23
  4489.8  390.87  4499.8  389.86  4529.8  388.85  4589.9  385.30  4639.9  383.56
  4870.0  380.84  4920.0  381.12  4930.0  380.11  4980.0  380.78  5037.7  379.98
  5038.2  379.48  5041.9  379.48  5042.4  379.98  5070.0  381.14  5080.0  380.47
  5120.0  380.86  5210.0  382.97  5260.0  385.99  5300.0  387.43  5370.0  391.24
  5460.0  394.98  5520.0  396.13  5550.0  397.73  5780.0  401.20  5930.8  401.84
#Mann=3,-1,0
  4205.9    0.05       0  5037.7    0.05       0  5042.4    0.05       0
Bank Sta=5037.7,5042.4
Exp/Cntr=0.3,0.1

Type RM Length L Ch R = 1,3632,295,295,295
BEGIN DESCRIPTION:
Lacy 167 528
END DESCRIPTION:
XS GIS Cut Line= 3
      2718302.87      6845783.45      2718300.65      6846514.22
      2718296.06      6847220.63
#Sta/Elev= 30
  4273.8  397.23  4351.4  397.71  4381.4  395.16  4421.4  394.00  4431.4  394.60
  4471.4  391.24  4501.4  391.24  4521.4  388.61  4551.4  387.22  4581.4  387.30
  4591.4  386.05  4641.4  384.12  4801.4  381.15  4871.4  378.87  4961.4  379.34
  4971.4  378.40  4981.4  372.92  4989.0  372.46  4989.5  371.96  4993.7  372.46
  5000.5  377.34  5004.6  377.34  5011.4  379.50  5051.4  379.74  5061.4  378.05
  5111.4  378.65  5171.4  383.09  5211.4  384.93  5541.4  398.28  5711.0  400.59
#Mann=3,-1,0
  4273.8    0.05       0  4989.0    0.04       0  4993.7    0.05       0
Bank Sta=4989,4993.7
Exp/Cntr=0.3,0.1

Type RM Length L Ch R = 1,3337,361,361,361
BEGIN DESCRIPTION:
Lacy 167 512
END DESCRIPTION:
XS GIS Cut Line= 3
      2718163.28      6845819.14      2718034.72      6846424.03
      2717937.28      6847027.82
#Sta/Elev= 30
  4394.3  395.33  4437.1  394.71  4518.9  389.41  4552.1  389.61  4559.8  387.68
  4570.0  386.94  4621.1  385.56  4631.3  383.96  4651.8  382.93  4690.7  381.80
  4702.9  382.15  4723.3  380.36  4846.0  378.33  4876.7  376.87  4958.5  377.14
  4983.3  378.06  4986.8  373.81  4987.3  373.31  4991.5  373.81  4999.4  374.17
  5008.6  378.21  5080.5  377.42  5097.3  379.87  5102.3  379.26  5121.1  381.06
  5202.1  383.98  5273.0  385.51  5293.3  386.76  5384.4  388.71  5624.3  397.56
#Mann=3,-1,0
  4394.3    0.05       0  4986.8    0.04       0  4991.5    0.05       0
Bank Sta=4986.8,4991.5
Exp/Cntr=0.3,0.1

Type RM Length L Ch R = 1,2976,550,550,550
BEGIN DESCRIPTION:
Lacy 167 511
END DESCRIPTION:
XS GIS Cut Line= 3
      2717907.23      6845839.24      2717702.18      6846322.82
      2717667.37      6846876.97
#Sta/Elev= 30
  4486.9  392.45  4521.4  390.90  4527.7  389.02  4543.1  388.14  4575.0  387.64
  4586.6  385.84  4604.1  384.76  4619.2  384.20  4627.8  384.96  4640.9  383.06
  4680.5  379.91  4704.2  380.81  4762.4  376.93  4803.8  375.93  4857.1  376.70
  4886.2  375.95  4962.6  377.22  4977.6  376.66  4989.3  374.28  4989.9  373.78
  4994.1  374.28  5008.5  377.28  5040.4  376.76  5230.8  379.68  5270.9  382.07
  5341.0  383.60  5361.0  385.55  5421.1  386.22  5507.9  390.32  5567.4  391.41
#Mann=3,-1,0
  4486.9    0.05       0  4989.3    0.04       0  4994.1    0.05       0
Bank Sta=4989.3,4994.1
Exp/Cntr=0.3,0.1

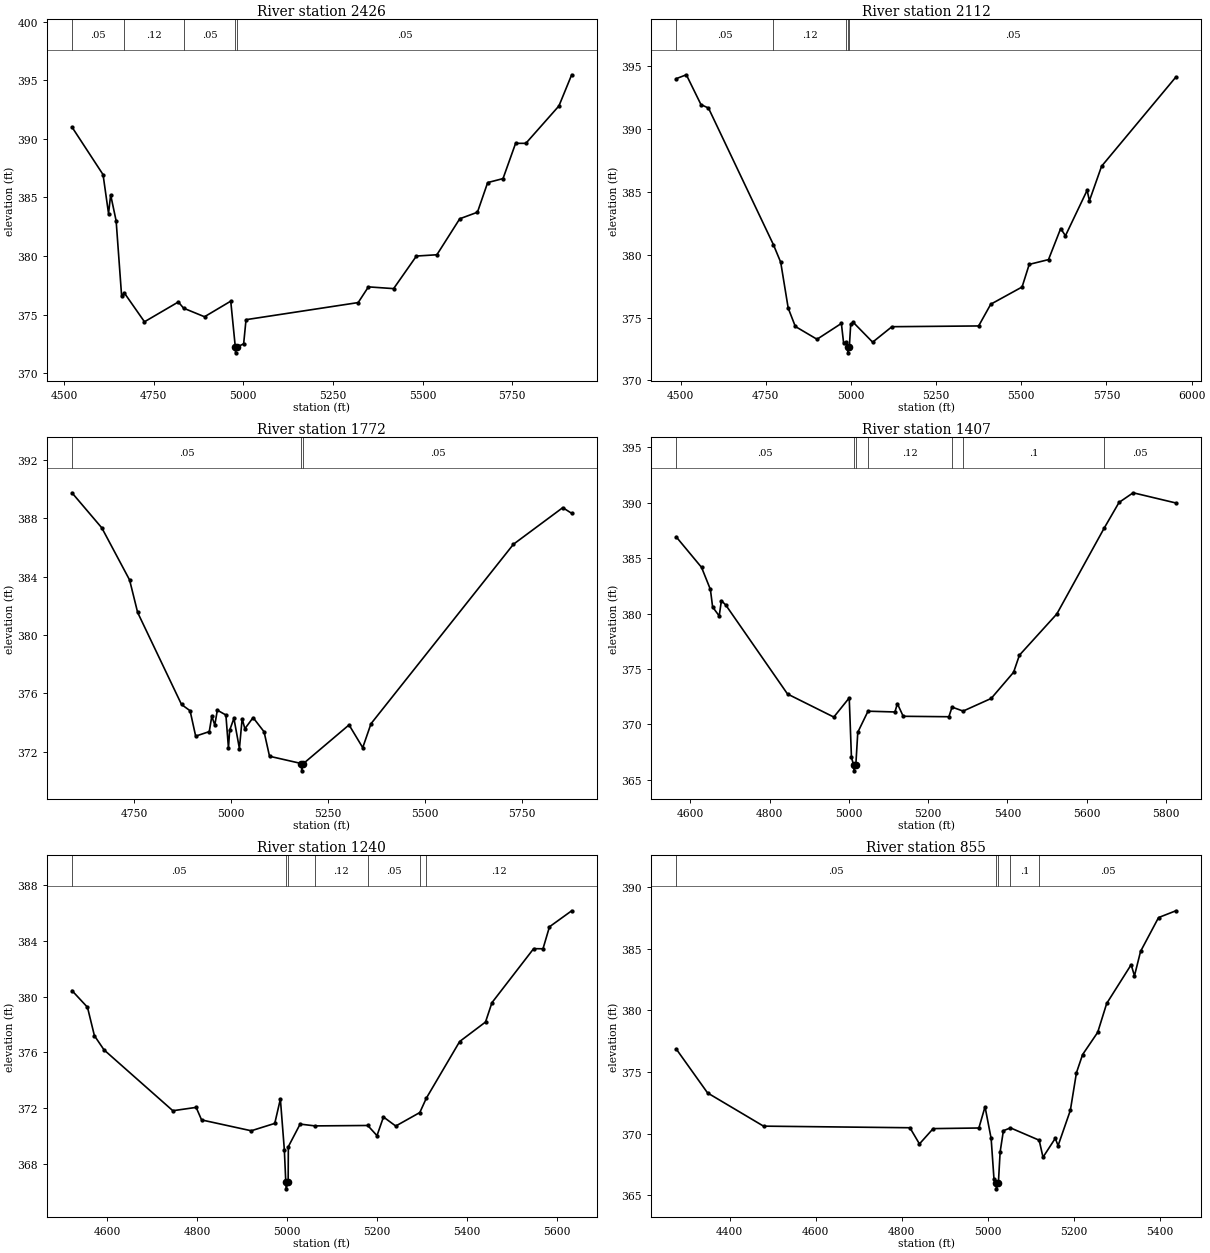
Type RM Length L Ch R = 1,2426,314,314,314
BEGIN DESCRIPTION:
Lacy 167 46
END DESCRIPTION:
XS GIS Cut Line= 3
      2717575.99      6845611.01      2717326.00      6846011.00
      2716626.03      6846610.97
#Sta/Elev= 30
  4522.1  391.01  4608.8  386.95  4624.1  383.63  4630.0  385.22  4645.3  383.00
  4660.6  376.58  4667.9  376.86  4724.3  374.39  4818.7  376.08  4833.5  375.55
  4891.8  374.82  4964.9  376.15  4977.6  372.24  4978.3  371.74  4982.8  372.24
  5000.9  372.51  5007.5  374.57  5320.3  376.03  5348.8  377.37  5419.1  377.22
  5482.7  380.00  5539.8  380.11  5603.5  383.18  5652.9  383.74  5681.4  386.27
  5724.2  386.61  5759.3  389.62  5787.9  389.62  5880.1  392.81  5915.7  395.47
#Mann=5,-1,0
  4522.1    0.05       0  4667.9    0.12       0  4833.5    0.05       0
  4977.6    0.04       0  4982.8    0.05       0
Bank Sta=4977.6,4982.8
Exp/Cntr=0.3,0.1

Type RM Length L Ch R = 1,2112,340,340,340
BEGIN DESCRIPTION:
Lacy 167 510
END DESCRIPTION:
XS GIS Cut Line= 3
      2717528.71      6845440.79      2717133.20      6845774.56
      2716482.73      6846466.08
#Sta/Elev= 30
  4486.8  394.01  4516.7  394.32  4559.6  391.95  4581.7  391.67  4772.1  380.81
  4793.7  379.40  4815.7  375.75  4836.6  374.29  4900.3  373.27  4971.8  374.53
  4978.3  372.98  4985.5  373.03  4990.0  372.69  4990.7  372.19  4995.2  372.69
  4999.2  374.46  5006.9  374.61  5063.6  373.04  5120.2  374.27  5374.7  374.33
  5410.3  376.06  5502.2  377.43  5523.2  379.23  5579.8  379.61  5615.5  382.08
  5629.6  381.51  5693.1  385.12  5700.0  384.30  5735.6  387.04  5953.7  394.14
#Mann=5,-1,0
  4486.8    0.05       0  4772.1    0.12       0  4985.5    0.05       0
  4990.0    0.05       0  4995.2    0.05       0
Bank Sta=4990,4995.2
Exp/Cntr=0.3,0.1

Type RM Length L Ch R = 1,1772,365,365,365
BEGIN DESCRIPTION:
Lacy 167 509
END DESCRIPTION:
XS GIS Cut Line= 3
      2717211.00      6845267.24      2716896.50      6845530.11
      2716282.69      6846160.15
#Sta/Elev= 30
  4589.3  389.75  4666.4  387.34  4738.0  383.77  4758.8  381.54  4872.0  375.23
  4894.1  374.80  4908.5  373.06  4943.6  373.37  4950.1  374.42  4957.9  373.82
  4964.4  374.84  4986.5  374.51  4993.1  372.25  4996.3  373.47  5007.2  374.28
  5021.4  372.21  5028.4  374.25  5035.5  373.57  5056.7  374.33  5085.0  373.36
  5099.1  371.68  5181.4  371.18  5182.1  370.68  5186.6  371.18  5304.3  373.83
  5339.6  372.27  5360.9  373.91  5728.5  386.22  5855.8  388.73  5878.8  388.34
#Mann=3,-1,0
  4589.3    0.05       0  5181.4    0.04       0  5186.6    0.05       0
Bank Sta=5181.4,5186.6
Exp/Cntr=0.3,0.1

Type RM Length L Ch R = 1,1407,167,167,167
BEGIN DESCRIPTION:
Lacy 167 508
END DESCRIPTION:
XS GIS Cut Line= 3
      2717007.66      6845106.65      2716597.41      6845315.39
      2716128.58      6845964.36
#Sta/Elev= 30
  4564.0  386.92  4628.1  384.16  4650.4  382.17  4656.0  380.59  4672.6  379.78
  4678.2  381.16  4689.3  380.76  4845.0  372.74  4961.8  370.66  5000.7  372.39
  5006.3  367.02  5012.0  366.31  5012.8  365.81  5017.3  366.31  5022.3  369.29
  5048.1  371.19  5116.0  371.12  5122.2  371.87  5136.9  370.73  5252.2  370.69
  5260.1  371.56  5288.1  371.20  5358.9  372.34  5415.4  374.70  5430.1  376.24
  5524.5  379.96  5643.8  387.69  5681.5  390.02  5717.1  390.89  5824.9  389.97
#Mann=7,-1,0
  4564.0    0.05       0  5012.0    0.04       0  5017.3    0.05       0
  5048.1    0.12       0  5260.1    0.05       0  5288.1     0.1       0
  5643.8    0.05       0
Bank Sta=5012,5017.3
Exp/Cntr=0.3,0.1

Type RM Length L Ch R = 1,1240,385,385,385
BEGIN DESCRIPTION:
Lacy 167 507
END DESCRIPTION:
XS GIS Cut Line= 3
      2716891.81      6844968.92      2716480.65      6845219.18
      2715992.57      6845617.15
#Sta/Elev= 30
  4521.1  380.44  4555.6  379.24  4571.0  377.20  4592.4  376.18  4745.4  371.81
  4797.2  372.05  4809.3  371.15  4919.7  370.37  4972.0  370.90  4984.5  372.65
  4993.3  369.01  4996.5  366.70  4997.3  366.20  5001.8  366.70  5002.2  369.23
  5028.4  370.85  5061.4  370.72  5178.8  370.75  5199.3  370.02  5213.7  371.36
  5241.0  370.71  5294.5  371.68  5309.0  372.71  5383.1  376.78  5440.6  378.18
  5454.9  379.57  5547.6  383.45  5568.4  383.44  5582.8  385.02  5632.2  386.17
#Mann=7,-1,0
  4521.1    0.05       0  4996.5    0.04       0  5001.8    0.05       0
  5061.4    0.12       0  5178.8    0.05       0  5294.5     0.1       0
  5309.0    0.12       0
Bank Sta=4996.5,5001.8
Exp/Cntr=0.3,0.1

Type RM Length L Ch R = 1,855,572,572,572
BEGIN DESCRIPTION:
Mapping XS 806a11ab
END DESCRIPTION:
XS GIS Cut Line= 3
      2716859.01      6844928.16      2716296.10      6844902.94
      2715844.58      6845295.98
#Sta/Elev= 30
  4275.7  376.87  4348.8  373.30  4478.9  370.61  4819.3  370.48  4841.5  369.17
  4873.4  370.41  4979.7  370.46  4994.0  372.18  5008.2  369.61  5014.8  366.33
  5019.7  366.03  5020.5  365.53  5025.1  366.03  5029.1  368.52  5036.7  370.24
  5053.1  370.47  5119.9  369.47  5128.8  368.09  5157.3  369.62  5163.9  369.03
  5192.4  371.89  5206.6  374.94  5220.9  376.41  5256.0  378.21  5276.9  380.55
  5333.8  383.69  5341.5  382.79  5355.7  384.77  5397.5  387.51  5437.8  388.06
#Mann=5,-1,0
  4275.7    0.05       0  5019.7    0.04       0  5025.1    0.05       0
  5053.1     0.1       0  5119.9    0.05       0
Bank Sta=5019.7,5025.1
Exp/Cntr=0.3,0.1

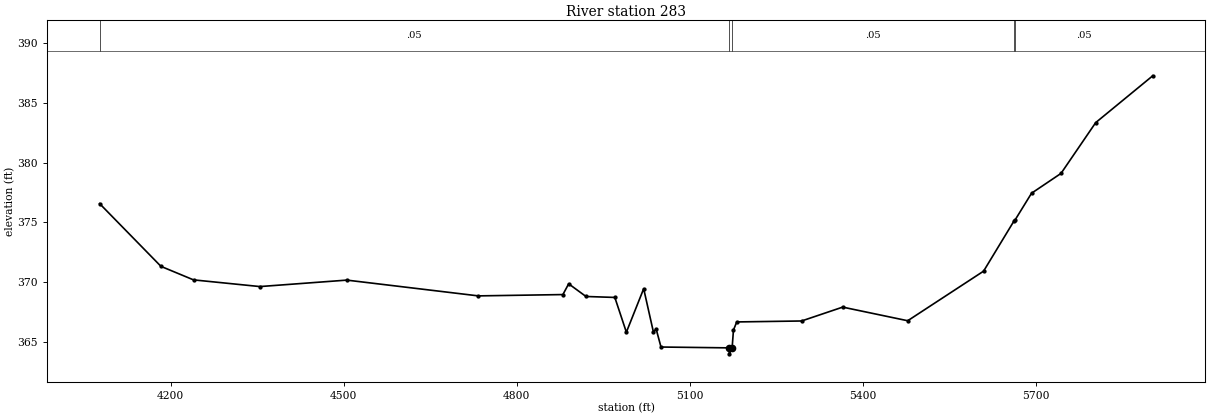
Type RM Length L Ch R = 1,283,0,0,0
BEGIN DESCRIPTION:
Lacy 167 506
END DESCRIPTION:
XS GIS Cut Line= 4
      2716853.24      6844921.24      2716239.93      6844474.08
      2716001.73      6844476.34      2715831.47      6845286.63
#Sta/Elev= 30
  4076.9  376.56  4183.2  371.31  4239.6  370.18  4354.7  369.62  4505.3  370.16
  4733.2  368.84  4879.8  368.95  4889.8  369.85  4919.8  368.79  4969.8  368.71
  4989.8  365.80  5019.8  369.44  5036.5  365.85  5041.5  366.05  5049.8  364.56
  5167.6  364.49  5168.4  363.99  5173.1  364.49  5175.4  365.98  5181.1  366.66
  5293.5  366.74  5364.7  367.90  5477.4  366.76  5608.9  370.91  5661.5  375.10
  5663.7  375.21  5692.0  377.43  5743.1  379.09  5803.2  383.34  5902.1  387.26
#Mann=5,-1,0
  4076.9    0.05       0  5167.6    0.05       0  5173.1    0.05       0
  5661.5     0.1       0  5663.7    0.05       0
Bank Sta=5167.6,5173.1
Exp/Cntr=0.3,0.1

Chan Stop Cuts=-1