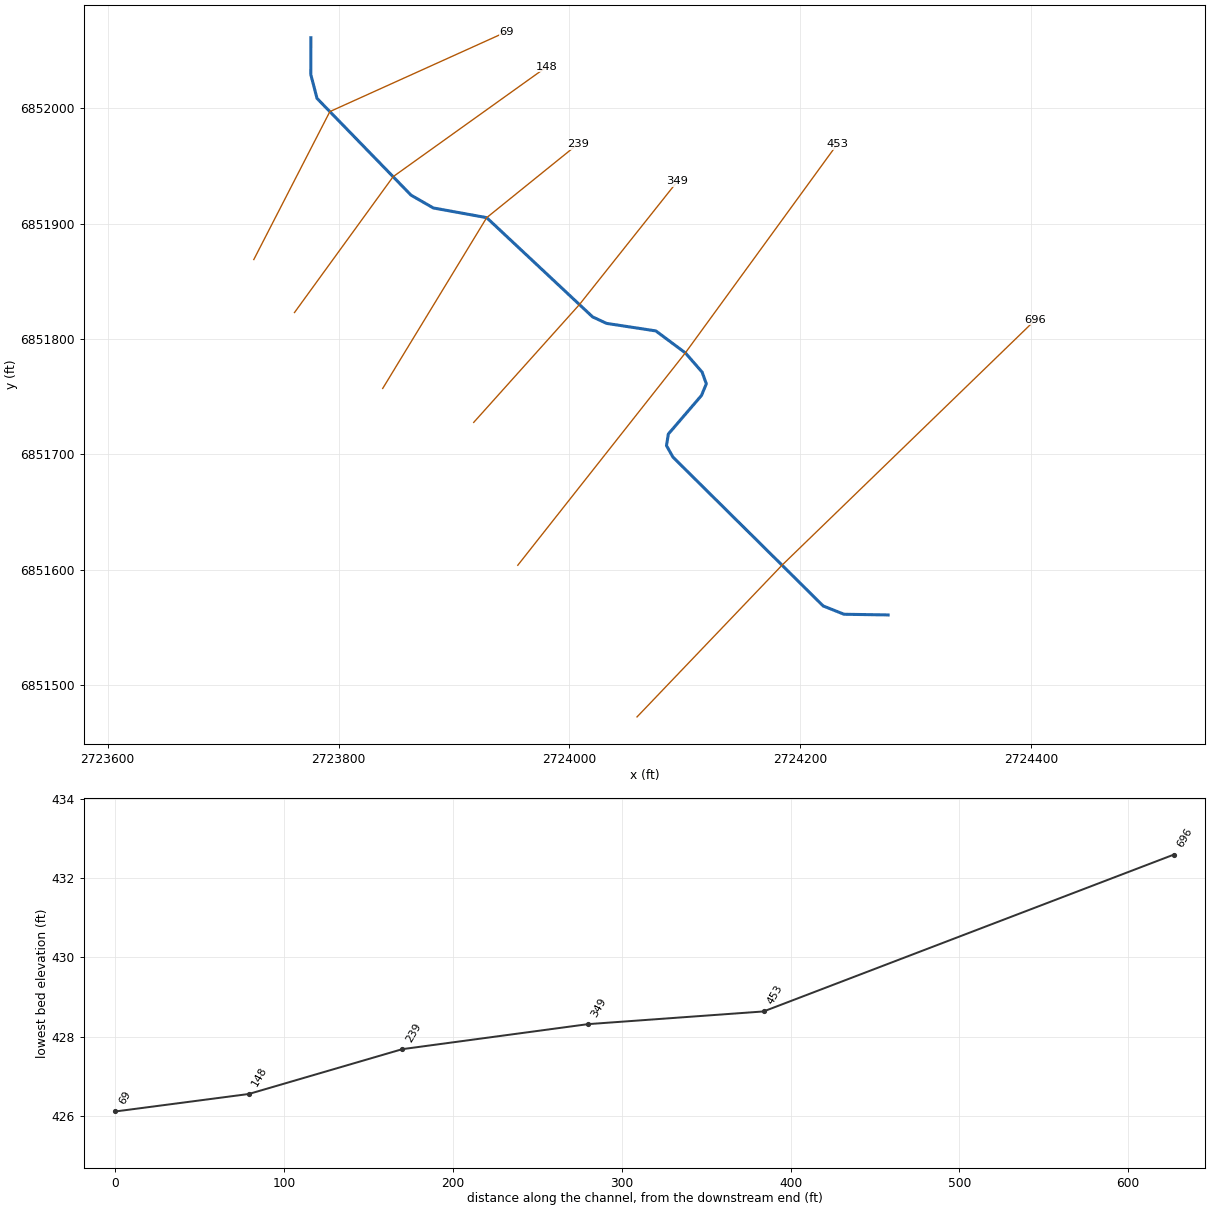
--- Lacy 168.prj (project) ---

Proj Title=Lacy 168 Base Level Engineering
Current Plan=p01
Default Exp/Contr=0.3,0.1
English Units
Geom File=g01
Flow File=f01
Plan File=p01
BEGIN DESCRIPTION:
Lacy 168
END DESCRIPTION:

--- Lacy 168.p01 (plan) ---

Plan Title=Multiple Run
Short Identifier=Multiple
Geom File=g01
Flow File=f01
Subcritical Flow
K Sum by GR= 0
Std Step Tol= 0.01
Critical Tol= 0.01
Num of Std Step Trials= 20
Max Error Tol= 0.3
Flow Tol Ratio= 0.001
Split Flow NTrial= 30
Split Flow Tol= 0.02
Split Flow Ratio= 0.02
Log Output Level= 0
Friction Slope Method= 1
Unsteady Friction Slope Method= 2
Unsteady Bridges Friction Slope Method= 1
Parabolic Critical Depth
Global Vel Dist=  1 , 1 , 1
Global Log Level= 0
CheckData=True
Encroach Param= -1, 0, 0, 0
BEGIN DESCRIPTION:
Multiple Run
END DESCRIPTION:

--- Lacy 168.f01 (steady flow) ---

Flow Title=Multiple
Number of Profiles=7
Profile Names=10-year,25-year,50-year,1pct_min,100-year,1pct_plu,500-year
River Rch & RM= Lacy 168,Reach-1,696
      90     106     117      65     129     257     155
Boundary for River Rch & Prof#=Lacy 168,Reach-1,1
Up Type=0
Dn Type=3
Dn Slope=0.005
Boundary for River Rch & Prof#=Lacy 168,Reach-1,2
Up Type=0
Dn Type=3
Dn Slope=0.005
Boundary for River Rch & Prof#=Lacy 168,Reach-1,3
Up Type=0
Dn Type=3
Dn Slope=0.005
Boundary for River Rch & Prof#=Lacy 168,Reach-1,4
Up Type=0
Dn Type=3
Dn Slope=0.005
Boundary for River Rch & Prof#=Lacy 168,Reach-1,5
Up Type=0
Dn Type=3
Dn Slope=0.005
Boundary for River Rch & Prof#=Lacy 168,Reach-1,6
Up Type=0
Dn Type=3
Dn Slope=0.005
Boundary for River Rch & Prof#=Lacy 168,Reach-1,7
Up Type=0
Dn Type=3
Dn Slope=0.005

--- Lacy 168.g01 (geometry) ---

Geom Title=Existing Conditions

River Reach=Lacy 168,Reach-1
Reach XY= 19
      2724276.00      6851561.00      2724237.84      6851561.59
      2724219.79      6851568.76      2724089.65      6851697.67
      2724084.00      6851707.68      2724085.62      6851717.68
      2724114.35      6851751.13      2724118.53      6851761.21
      2724114.89      6851771.32      2724100.36      6851787.99
      2724074.82      6851807.03      2724032.13      6851813.54
      2724020.00      6851819.18      2723928.28      6851905.13
      2723882.04      6851913.53      2723862.76      6851924.61
      2723781.30      6852008.46      2723775.92      6852029.11
      2723776.00      6852061.00

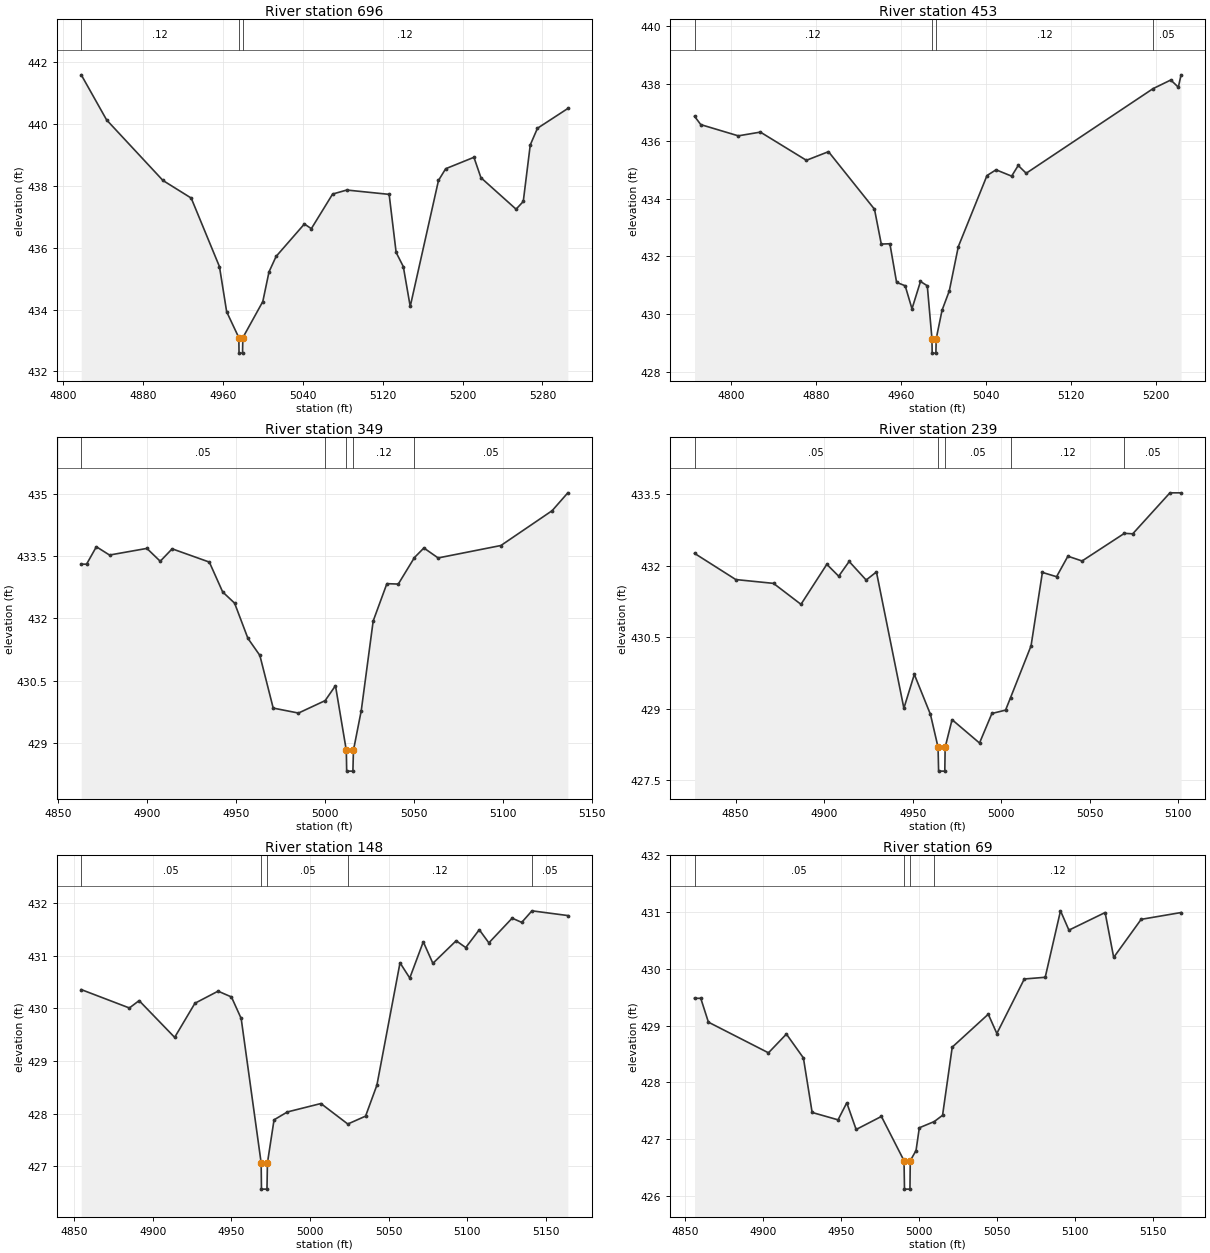
Type RM Length L Ch R = 1,696,243,243,243
BEGIN DESCRIPTION:
Lacy 168 585
END DESCRIPTION:
XS GIS Cut Line= 3
      2724058.51      6851472.67      2724184.11      6851604.10
      2724403.47      6851816.58
#Sta/Elev= 30
  4818.2  441.60  4843.6  440.14  4900.0  438.18  4928.3  437.61  4956.6  435.39
  4963.8  433.93  4976.0  433.09  4976.2  432.59  4979.7  432.59  4980.0  433.09
  5000.0  434.26  5006.2  435.22  5013.3  435.72  5041.6  436.77  5048.6  436.62
  5069.9  437.74  5084.1  437.87  5126.5  437.73  5133.5  435.85  5140.7  435.39
  5147.6  434.10  5175.9  438.18  5183.1  438.56  5211.4  438.93  5218.4  438.27
  5253.6  437.25  5260.8  437.50  5267.8  439.33  5275.0  439.87  5305.4  440.51
#Mann=3,-1,0
  4818.2    0.12       0  4976.0    0.07       0  4980.0    0.12       0
Bank Sta=4976,4980
Exp/Cntr=0.3,0.1

Type RM Length L Ch R = 1,453,104,104,104
BEGIN DESCRIPTION:
Lacy 168 584
END DESCRIPTION:
XS GIS Cut Line= 3
      2723955.22      6851604.05      2724100.36      6851787.99
      2724231.99      6851968.85
#Sta/Elev= 30
  4765.7  436.87  4771.6  436.58  4806.9  436.19  4827.7  436.32  4871.0  435.34
  4891.8  435.64  4935.1  433.64  4941.5  432.43  4949.6  432.44  4955.9  431.10
  4964.0  430.98  4970.4  430.18  4978.4  431.13  4984.8  430.98  4989.2  429.14
  4989.4  428.64  4992.9  428.64  4993.2  429.14  4998.7  430.13  5005.5  430.80
  5014.0  432.34  5041.0  434.81  5049.5  435.01  5064.2  434.79  5070.4  435.16
  5077.9  434.89  5197.3  437.83  5214.0  438.13  5221.1  437.88  5223.7  438.31
#Mann=4,-1,0
  4765.7    0.12       0  4989.2    0.07       0  4993.2    0.12       0
  5197.3    0.05       0
Bank Sta=4989.2,4993.2
Exp/Cntr=0.3,0.1

Type RM Length L Ch R = 1,349,110,110,110
BEGIN DESCRIPTION:
Lacy 168 583
END DESCRIPTION:
XS GIS Cut Line= 3
      2723917.05      6851727.80      2724008.61      6851829.86
      2724093.49      6851936.62
#Sta/Elev= 30
  4862.9  433.31  4865.9  433.31  4871.4  433.73  4878.8  433.53  4899.8  433.69
  4907.3  433.38  4914.0  433.68  4934.9  433.36  4942.4  432.64  4949.1  432.37
  4956.6  431.52  4963.3  431.11  4970.8  429.84  4985.0  429.72  5000.0  430.02
  5005.8  430.38  5011.9  428.82  5012.1  428.32  5015.6  428.32  5015.9  428.82
  5020.3  429.78  5027.0  431.94  5034.7  432.84  5041.1  432.83  5050.2  433.47
  5055.5  433.70  5063.5  433.46  5098.8  433.76  5127.6  434.60  5136.4  435.03
#Mann=5,-1,0
  4862.9    0.05       0  5000.0    0.12       0  5011.9    0.05       0
  5015.9    0.12       0  5050.2    0.05       0
Bank Sta=5011.9,5015.9
Exp/Cntr=0.3,0.1

Type RM Length L Ch R = 1,239,91,91,91
BEGIN DESCRIPTION:
Lacy 168 582
END DESCRIPTION:
XS GIS Cut Line= 3
      2723838.21      6851757.19      2723928.28      6851905.13
      2724007.25      6851968.90
#Sta/Elev= 30
  4826.8  432.26  4850.1  431.71  4871.4  431.63  4886.9  431.19  4901.5  432.03
  4908.2  431.78  4914.1  432.09  4923.7  431.70  4929.5  431.87  4945.0  429.01
  4950.9  429.72  4960.0  428.88  4964.3  428.19  4964.6  427.69  4968.1  427.69
  4968.3  428.19  4972.2  428.77  4987.7  428.28  4994.7  428.90  5002.4  428.97
  5005.2  429.23  5016.8  430.32  5023.2  431.86  5031.2  431.77  5037.6  432.20
  5045.6  432.10  5069.5  432.68  5074.2  432.67  5095.2  433.53  5101.5  433.53
#Mann=5,-1,0
  4826.8    0.05       0  4964.3    0.05       0  4968.3    0.05       0
  5005.2    0.12       0  5069.5    0.05       0
Bank Sta=4964.3,4968.3
Exp/Cntr=0.3,0.1

Type RM Length L Ch R = 1,148,79,79,79
BEGIN DESCRIPTION:
Lacy 168 581
END DESCRIPTION:
XS GIS Cut Line= 3
      2723761.79      6851822.95      2723847.22      6851940.61
      2723980.60      6852036.03
#Sta/Elev= 30
  4854.6  430.36  4885.2  430.01  4891.4  430.15  4914.0  429.45  4926.9  430.10
  4941.6  430.33  4950.1  430.22  4956.3  429.81  4969.0  427.06  4969.2  426.56
  4972.7  426.56  4973.0  427.06  4977.2  427.88  4985.7  428.03  5007.0  428.19
  5024.1  427.80  5035.4  427.95  5042.6  428.54  5057.3  430.87  5063.5  430.58
  5072.1  431.27  5078.2  430.86  5093.0  431.29  5099.1  431.16  5107.7  431.50
  5113.8  431.25  5128.6  431.72  5134.7  431.64  5141.2  431.86  5164.0  431.77
#Mann=5,-1,0
  4854.6    0.05       0  4969.0    0.05       0  4973.0    0.05       0
  5024.1    0.12       0  5141.2    0.05       0
Bank Sta=4969,4973
Exp/Cntr=0.3,0.1

Type RM Length L Ch R = 1,69,0,0,0
BEGIN DESCRIPTION:
Lacy 168 580
END DESCRIPTION:
XS GIS Cut Line= 3
      2723726.55      6851868.85      2723792.43      6851997.01
      2723945.34      6852066.11
#Sta/Elev= 30
  4855.9  429.48  4859.9  429.48  4864.8  429.06  4903.3  428.52  4914.8  428.85
  4925.7  428.43  4931.3  427.47  4947.9  427.34  4953.5  427.64  4959.5  427.17
  4975.7  427.40  4990.2  426.62  4990.5  426.12  4994.0  426.12  4994.2  426.62
  4997.9  426.80  5000.0  427.20  5009.6  427.31  5014.9  427.42  5021.1  428.62
  5044.2  429.20  5049.7  428.86  5067.3  429.82  5080.7  429.85  5090.5  431.02
  5095.9  430.68  5119.1  430.99  5124.6  430.20  5142.2  430.87  5167.8  430.99
#Mann=4,-1,0
  4855.9    0.05       0  4990.2    0.05       0  4994.2    0.05       0
  5009.6    0.12       0
Bank Sta=4990.2,4994.2
Exp/Cntr=0.3,0.1

Chan Stop Cuts=-1