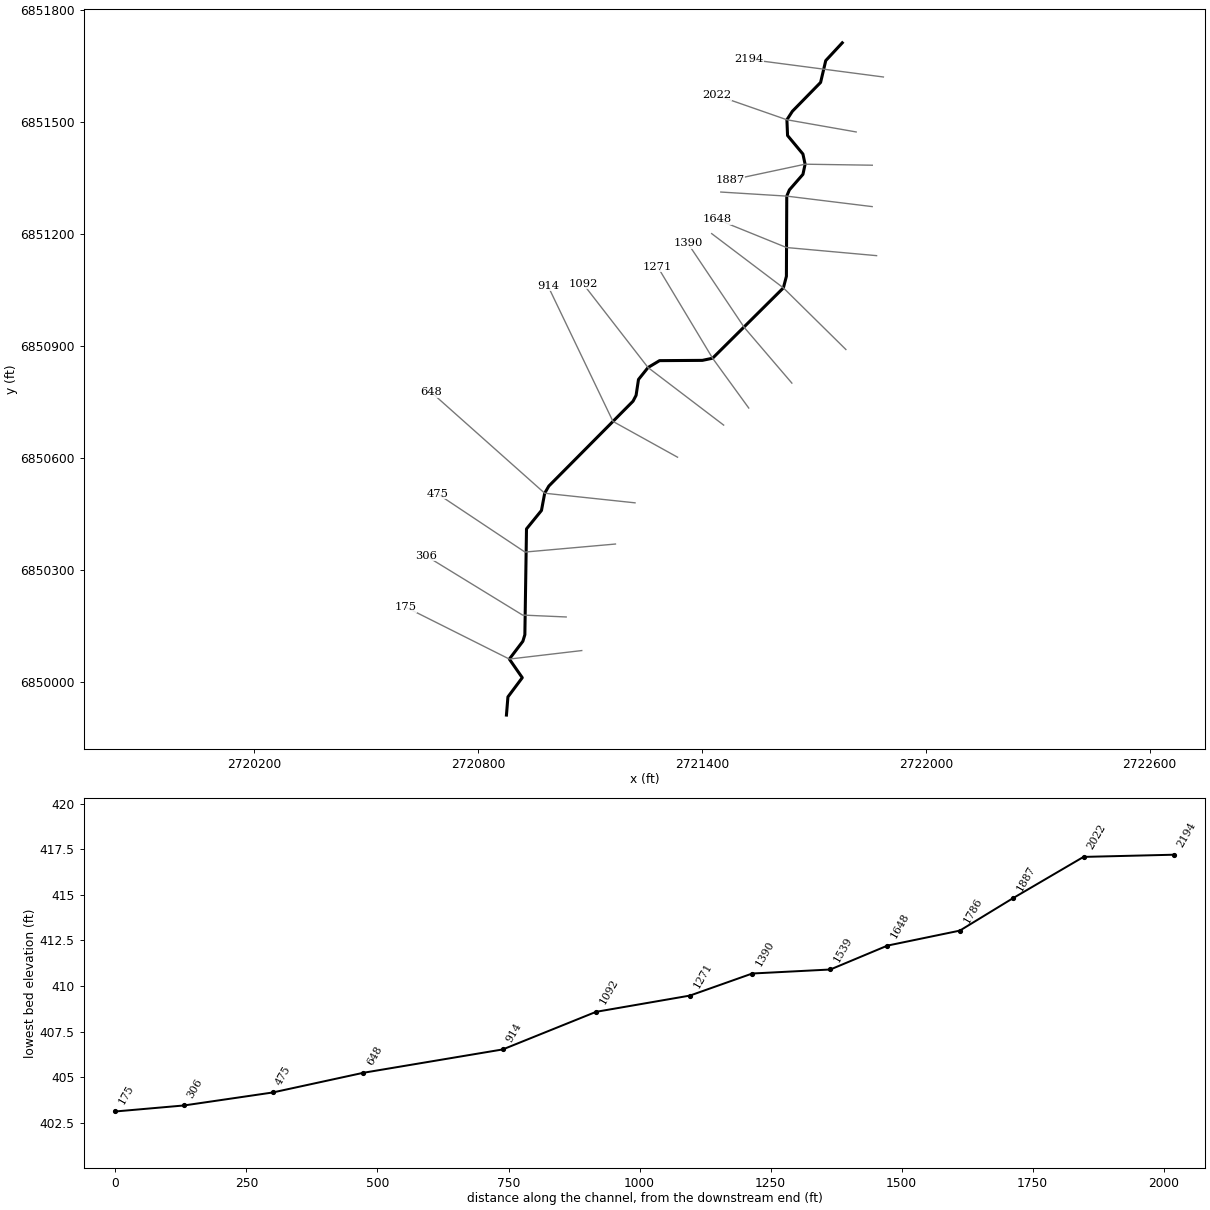
--- Lacy 169.prj (project) ---

Proj Title=Lacy 169 Base Level Engineering
Current Plan=p01
Default Exp/Contr=0.3,0.1
English Units
Geom File=g01
Flow File=f01
Plan File=p01
BEGIN DESCRIPTION:
Lacy 169
END DESCRIPTION:

--- Lacy 169.p01 (plan) ---

Plan Title=Multiple Run
Short Identifier=Multiple
Geom File=g01
Flow File=f01
Subcritical Flow
K Sum by GR= 0
Std Step Tol= 0.01
Critical Tol= 0.01
Num of Std Step Trials= 20
Max Error Tol= 0.3
Flow Tol Ratio= 0.001
Split Flow NTrial= 30
Split Flow Tol= 0.02
Split Flow Ratio= 0.02
Log Output Level= 0
Friction Slope Method= 1
Unsteady Friction Slope Method= 2
Unsteady Bridges Friction Slope Method= 1
Parabolic Critical Depth
Global Vel Dist=  1 , 1 , 1
Global Log Level= 0
CheckData=True
Encroach Param= -1, 0, 0, 0
BEGIN DESCRIPTION:
Multiple Run
END DESCRIPTION:

--- Lacy 169.f01 (steady flow) ---

Flow Title=Multiple
Number of Profiles=7
Profile Names=10-year,25-year,50-year,1pct_min,100-year,1pct_plu,500-year
River Rch & RM= Lacy 169,Reach-1,2194
     200     249     285     163     325     648     420
Boundary for River Rch & Prof#=Lacy 169,Reach-1,1
Up Type=0
Dn Type=3
Dn Slope=0.005
Boundary for River Rch & Prof#=Lacy 169,Reach-1,2
Up Type=0
Dn Type=3
Dn Slope=0.005
Boundary for River Rch & Prof#=Lacy 169,Reach-1,3
Up Type=0
Dn Type=3
Dn Slope=0.005
Boundary for River Rch & Prof#=Lacy 169,Reach-1,4
Up Type=0
Dn Type=3
Dn Slope=0.005
Boundary for River Rch & Prof#=Lacy 169,Reach-1,5
Up Type=0
Dn Type=3
Dn Slope=0.005
Boundary for River Rch & Prof#=Lacy 169,Reach-1,6
Up Type=0
Dn Type=3
Dn Slope=0.005
Boundary for River Rch & Prof#=Lacy 169,Reach-1,7
Up Type=0
Dn Type=3
Dn Slope=0.005

--- Lacy 169.g01 (geometry) ---

Geom Title=Existing Conditions

River Reach=Lacy 169,Reach-1
Reach XY= 30
      2721776.00      6851711.00      2721731.70      6851663.35
      2721717.92      6851604.92      2721642.25      6851527.66
      2721627.63      6851504.96      2721629.37      6851462.74
      2721670.58      6851413.20      2721676.39      6851386.00
      2721670.62      6851358.82      2721634.19      6851317.08
      2721627.24      6851300.50      2721626.30      6851085.88
      2721618.19      6851054.81      2721428.45      6850866.47
      2721401.11      6850860.73      2721286.29      6850860.00
      2721255.45      6850841.55      2721229.87      6850809.60
      2721223.45      6850767.09      2721215.21      6850751.34
      2720989.62      6850524.22      2720978.50      6850504.97
      2720969.86      6850458.83      2720929.75      6850409.45
      2720925.35      6850126.16      2720920.00      6850108.55
      2720883.77      6850060.90      2720918.43      6850011.06
      2720879.98      6849959.64      2720876.00      6849911.00

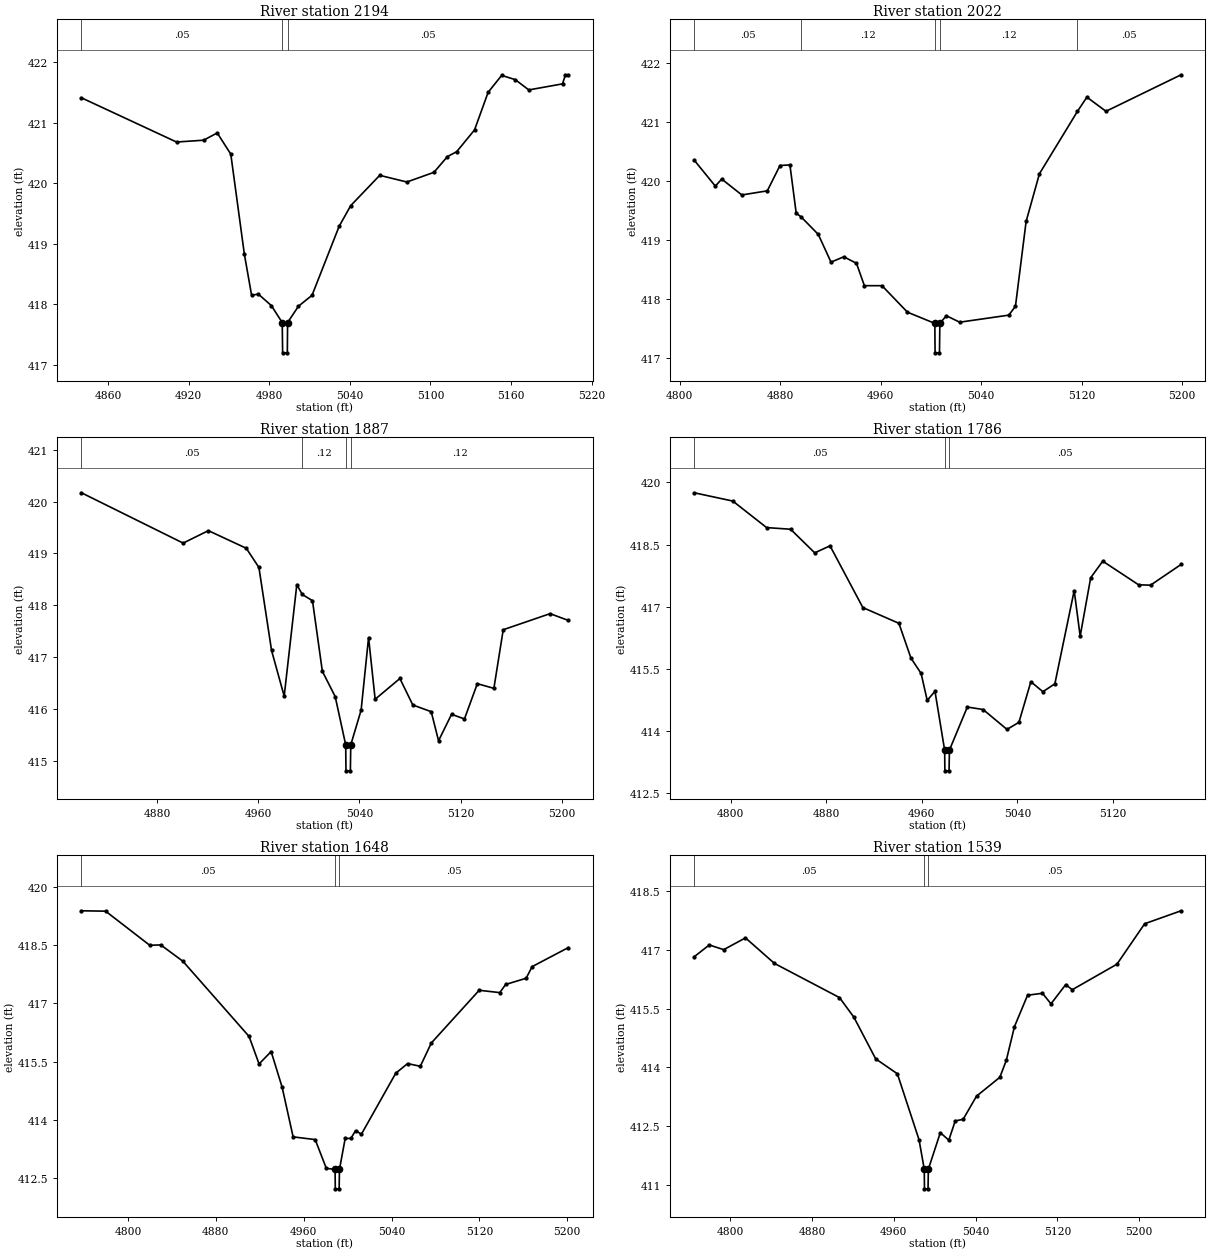
Type RM Length L Ch R = 1,2194,172,172,172
BEGIN DESCRIPTION:
Lacy 169 542
END DESCRIPTION:
XS GIS Cut Line= 2
      2721886.24      6851619.50      2721526.81      6851666.57
#Sta/Elev= 30
  4840.1  421.41  4910.9  420.68  4931.1  420.71  4941.2  420.83  4951.3  420.48
  4961.4  418.83  4966.8  418.15  4971.8  418.17  4981.5  417.98  4989.6  417.70
  4989.9  417.20  4993.4  417.20  4993.6  417.70  5001.7  417.97  5011.8  418.15
  5032.0  419.29  5040.6  419.63  5062.2  420.13  5082.4  420.02  5102.6  420.18
  5112.6  420.44  5119.5  420.52  5132.8  420.88  5142.9  421.50  5153.0  421.78
  5163.1  421.71  5173.2  421.54  5198.3  421.64  5200.5  421.79  5202.6  421.79
#Mann=3,-1,0
  4840.1    0.05       0  4989.6    0.04       0  4993.6    0.05       0
Bank Sta=4989.6,4993.6
Exp/Cntr=0.3,0.1

Type RM Length L Ch R = 1,2022,135,135,135
BEGIN DESCRIPTION:
Lacy 169 541
END DESCRIPTION:
XS GIS Cut Line= 3
      2721813.28      6851472.34      2721627.63      6851504.96
      2721439.50      6851570.45
#Sta/Elev= 30
  4811.5  420.35  4828.3  419.91  4833.4  420.03  4849.4  419.76  4869.7  419.83
  4879.8  420.26  4887.7  420.27  4892.7  419.45  4896.5  419.39  4910.3  419.09
  4920.4  418.62  4930.6  418.71  4940.7  418.60  4947.0  418.22  4961.0  418.22
  4981.3  417.77  5003.1  417.58  5003.3  417.08  5006.8  417.08  5007.1  417.58
  5012.3  417.71  5022.9  417.60  5062.0  417.72  5067.3  417.87  5075.8  419.31
  5086.4  420.12  5116.7  421.18  5124.2  421.42  5139.4  421.18  5199.2  421.80
#Mann=5,-1,0
  4811.5    0.05       0  4896.5    0.12       0  5003.1    0.07       0
  5007.1    0.12       0  5116.7    0.05       0
Bank Sta=5003.1,5007.1
Exp/Cntr=0.3,0.1

Type RM Length L Ch R = 1,1887,101,101,101
BEGIN DESCRIPTION:
Lacy 169 540
END DESCRIPTION:
XS GIS Cut Line= 3
      2721856.47      6851383.30      2721676.39      6851386.00
      2721475.59      6851343.28
#Sta/Elev= 30
  4819.9  420.17  4900.4  419.20  4920.4  419.44  4950.4  419.10  4960.4  418.73
  4970.4  417.13  4980.4  416.25  4990.4  418.40  4994.7  418.21  5002.8  418.09
  5010.6  416.73  5020.8  416.24  5029.1  415.31  5029.3  414.81  5032.8  414.81
  5033.1  415.31  5041.3  415.98  5047.2  417.38  5052.4  416.19  5072.0  416.59
  5082.2  416.08  5096.8  415.95  5102.6  415.39  5112.9  415.90  5123.1  415.81
  5133.3  416.49  5146.4  416.40  5153.8  417.53  5190.9  417.84  5205.3  417.71
#Mann=4,-1,0
  4819.9    0.05       0  4994.7    0.12       0  5029.1    0.07       0
  5033.1    0.12       0
Bank Sta=5029.1,5033.1
Exp/Cntr=0.3,0.1

Type RM Length L Ch R = 1,1786,138,138,138
BEGIN DESCRIPTION:
Lacy 169 539
END DESCRIPTION:
XS GIS Cut Line= 3
      2721856.13      6851272.45      2721627.24      6851300.50
      2721450.48      6851311.46
#Sta/Elev= 30
  4769.4  419.75  4801.7  419.55  4830.0  418.91  4850.1  418.87  4870.3  418.30
  4883.1  418.47  4910.6  416.98  4940.8  416.60  4950.9  415.76  4959.4  415.39
  4964.5  414.74  4971.0  414.96  4979.1  413.54  4979.3  413.04  4982.8  413.04
  4983.1  413.54  4998.1  414.58  5011.3  414.52  5031.3  414.04  5041.3  414.21
  5051.3  415.19  5061.4  414.95  5071.4  415.14  5087.6  417.39  5092.6  416.29
  5101.4  417.70  5111.5  418.10  5141.5  417.53  5151.5  417.52  5177.1  418.02
#Mann=3,-1,0
  4769.4    0.05       0  4979.1    0.04       0  4983.1    0.05       0
Bank Sta=4979.1,4983.1
Exp/Cntr=0.3,0.1

Type RM Length L Ch R = 1,1648,109,109,109
BEGIN DESCRIPTION:
Lacy 169 538
END DESCRIPTION:
XS GIS Cut Line= 3
      2721867.95      6851141.12      2721626.63      6851162.87
      2721440.42      6851238.29
#Sta/Elev= 30
  4757.7  419.39  4779.7  419.38  4819.9  418.50  4829.9  418.51  4850.0  418.09
  4910.3  416.15  4919.4  415.44  4930.4  415.76  4940.4  414.84  4950.4  413.56
  4970.5  413.49  4980.6  412.75  4988.6  412.72  4988.8  412.22  4992.3  412.22
  4992.6  412.72  4997.8  413.52  5003.0  413.52  5007.2  413.72  5012.6  413.63
  5043.8  415.20  5054.6  415.45  5066.2  415.38  5076.2  415.98  5119.8  417.34
  5138.5  417.28  5143.9  417.49  5162.5  417.65  5168.0  417.95  5200.9  418.44
#Mann=3,-1,0
  4757.7    0.05       0  4988.6    0.04       0  4992.6    0.05       0
Bank Sta=4988.6,4992.6
Exp/Cntr=0.3,0.1

Type RM Length L Ch R = 1,1539,149,149,149
BEGIN DESCRIPTION:
Lacy 169 537
END DESCRIPTION:
XS GIS Cut Line= 3
      2721785.69      6850889.83      2721618.19      6851054.81
      2721426.04      6851200.10
#Sta/Elev= 30
  4764.9  416.82  4779.6  417.12  4793.7  417.00  4815.0  417.30  4843.3  416.65
  4906.9  415.78  4921.0  415.28  4942.3  414.22  4963.5  413.84  4984.7  412.16
  4989.8  411.41  4990.0  410.91  4993.5  410.91  4993.8  411.41  5005.5  412.34
  5013.8  412.15  5020.1  412.64  5027.8  412.68  5040.9  413.27  5063.7  413.75
  5070.0  414.18  5078.0  415.04  5090.8  415.84  5105.4  415.89  5113.7  415.62
  5128.1  416.11  5134.5  415.98  5178.2  416.63  5205.3  417.66  5240.9  417.99
#Mann=3,-1,0
  4764.9    0.05       0  4989.8    0.04       0  4993.8    0.05       0
Bank Sta=4989.8,4993.8
Exp/Cntr=0.3,0.1

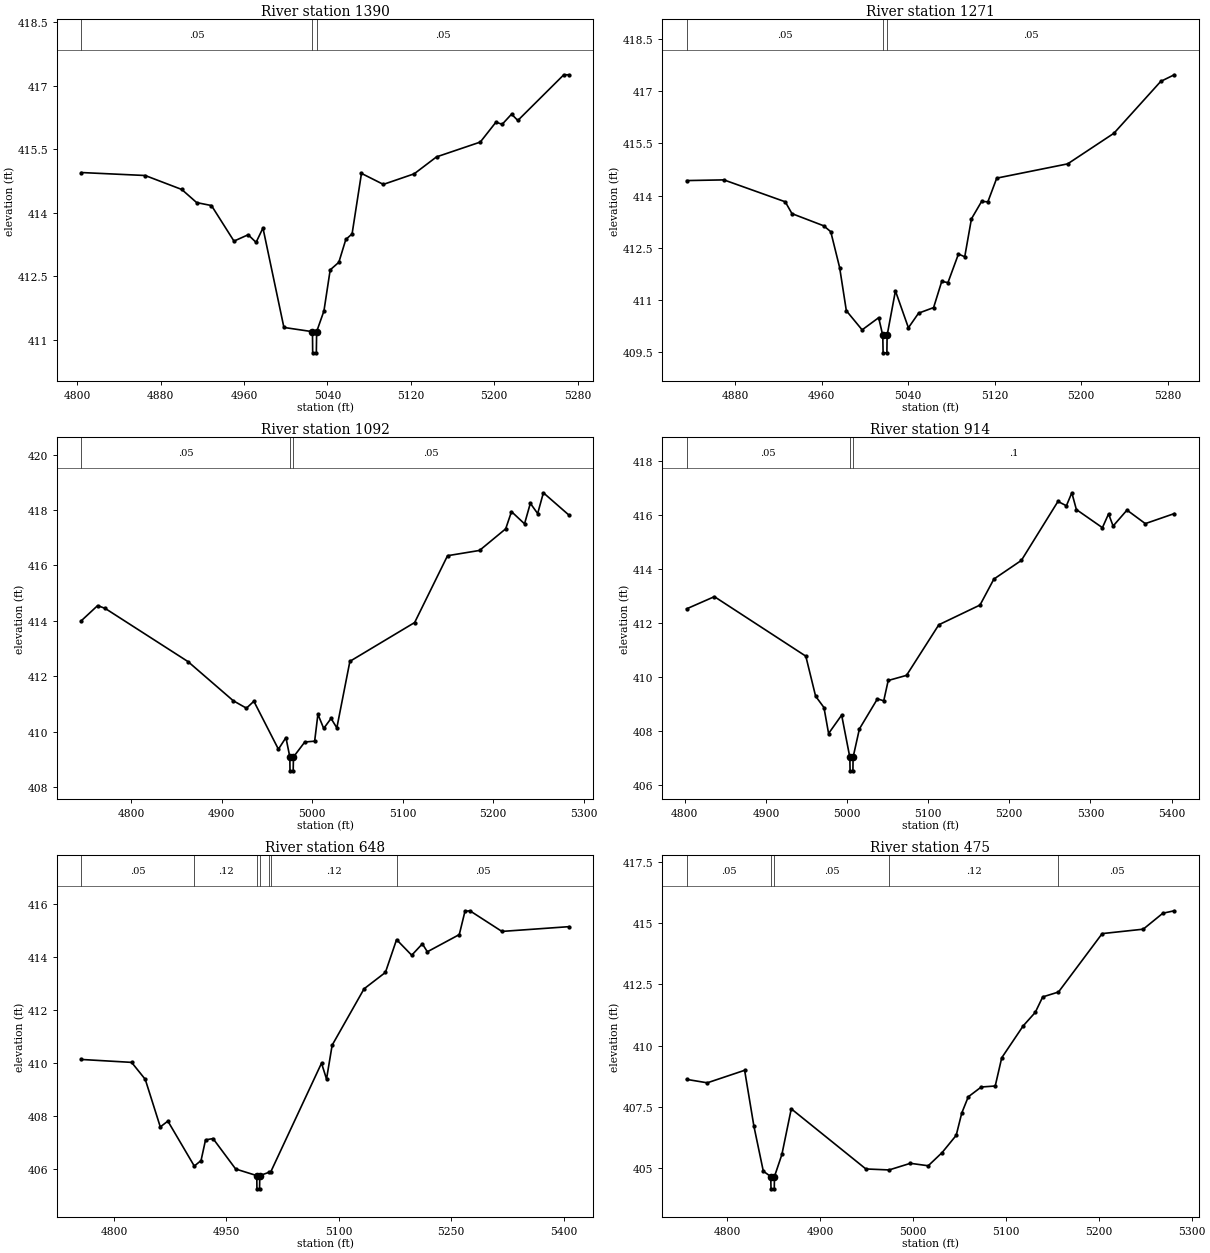
Type RM Length L Ch R = 1,1390,119,119,119
BEGIN DESCRIPTION:
Lacy 169 536
END DESCRIPTION:
XS GIS Cut Line= 3
      2721640.93      6850799.86      2721513.51      6850948.65
      2721361.98      6851174.41
#Sta/Elev= 30
  4804.1  414.95  4865.2  414.88  4900.3  414.55  4914.6  414.24  4928.8  414.17
  4950.4  413.33  4964.0  413.48  4971.6  413.30  4978.2  413.64  4998.3  411.29
  5025.7  411.19  5025.9  410.69  5029.4  410.69  5029.7  411.19  5036.7  411.68
  5042.7  412.65  5051.0  412.83  5057.7  413.37  5063.7  413.50  5072.7  414.93
  5093.7  414.67  5123.3  414.92  5144.7  415.32  5186.7  415.67  5201.7  416.14
  5207.7  416.09  5216.7  416.33  5222.7  416.18  5266.8  417.26  5271.9  417.26
#Mann=3,-1,0
  4804.1    0.05       0  5025.7    0.04       0  5029.7    0.05       0
Bank Sta=5025.7,5029.7
Exp/Cntr=0.3,0.1

Type RM Length L Ch R = 1,1271,179,179,179
BEGIN DESCRIPTION:
Lacy 169 555
END DESCRIPTION:
XS GIS Cut Line= 3
      2721525.33      6850733.15      2721428.45      6850866.47
      2721280.94      6851111.72
#Sta/Elev= 30
  4835.2  414.43  4869.6  414.45  4926.4  413.82  4932.6  413.48  4962.0  413.13
  4968.5  412.96  4976.7  411.93  4982.9  410.69  4997.5  410.14  5012.8  410.49
  5016.6  409.98  5016.9  409.48  5020.4  409.48  5020.6  409.98  5028.3  411.26
  5040.3  410.20  5049.7  410.62  5063.6  410.78  5071.1  411.53  5076.9  411.50
  5086.6  412.32  5092.4  412.24  5098.6  413.33  5108.0  413.83  5113.8  413.82
  5122.0  414.50  5187.6  414.91  5230.4  415.79  5273.7  417.28  5286.2  417.47
#Mann=3,-1,0
  4835.2    0.05       0  5016.6    0.04       0  5020.6    0.05       0
Bank Sta=5016.6,5020.6
Exp/Cntr=0.3,0.1

Type RM Length L Ch R = 1,1092,178,178,178
BEGIN DESCRIPTION:
Lacy 169 556
END DESCRIPTION:
XS GIS Cut Line= 3
      2721458.09      6850687.42      2721255.45      6850841.55
      2721081.48      6851065.65
#Sta/Elev= 30
  4745.4  414.01  4763.2  414.55  4771.5  414.45  4863.0  412.53  4912.9  411.12
  4927.5  410.85  4935.7  411.10  4962.8  409.37  4971.1  409.79  4975.4  409.09
  4975.6  408.59  4979.1  408.59  4979.4  409.09  4991.9  409.63  5002.8  409.66
  5006.4  410.63  5012.8  410.12  5020.9  410.48  5027.3  410.14  5041.7  412.54
  5113.2  413.94  5149.5  416.35  5184.8  416.54  5213.7  417.32  5220.1  417.94
  5234.5  417.50  5240.9  418.24  5249.0  417.87  5255.3  418.62  5283.7  417.81
#Mann=3,-1,0
  4745.4    0.05       0  4975.4    0.04       0  4979.4    0.05       0
Bank Sta=4975.4,4979.4
Exp/Cntr=0.3,0.1

Type RM Length L Ch R = 1,914,266,266,266
BEGIN DESCRIPTION:
Lacy 169 557
END DESCRIPTION:
XS GIS Cut Line= 3
      2721334.52      6850601.42      2721161.49      6850697.26
      2720986.85      6851060.89
#Sta/Elev= 30
  4802.2  412.52  4836.4  412.97  4949.1  410.77  4961.2  409.29  4971.5  408.87
  4977.2  407.91  4993.3  408.59  5003.4  407.03  5003.7  406.53  5007.2  406.53
  5007.4  407.03  5015.2  408.08  5037.4  409.19  5045.2  409.12  5050.7  409.87
  5073.3  410.06  5113.1  411.93  5163.9  412.66  5181.0  413.62  5214.9  414.31
  5260.0  416.49  5270.4  416.33  5277.1  416.81  5282.7  416.19  5314.8  415.52
  5322.4  416.03  5328.0  415.58  5345.1  416.17  5367.7  415.67  5403.4  416.04
#Mann=3,-1,0
  4802.2    0.05       0  5003.4    0.04       0  5007.4     0.1       0
Bank Sta=5003.4,5007.4
Exp/Cntr=0.3,0.1

Type RM Length L Ch R = 1,648,173,173,173
BEGIN DESCRIPTION:
Lacy 169 558
END DESCRIPTION:
XS GIS Cut Line= 3
      2721220.63      6850479.26      2720978.50      6850504.97
      2720674.05      6850775.68
#Sta/Elev= 30
  4756.5  410.14  4823.4  410.03  4841.6  409.39  4861.7  407.59  4871.8  407.81
  4907.1  406.11  4916.1  406.32  4922.1  407.10  4932.1  407.15  4962.3  406.00
  4990.5  405.75  4990.7  405.25  4994.2  405.25  4994.5  405.75  5007.3  405.88
  5009.3  405.90  5076.9  410.00  5083.6  409.40  5091.1  410.68  5133.7  412.81
  5162.2  413.43  5177.1  414.67  5197.3  414.08  5211.5  414.51  5218.2  414.21
  5260.8  414.86  5268.4  415.74  5275.0  415.76  5317.7  414.98  5407.4  415.16
#Mann=7,-1,0
  4756.5    0.05       0  4907.1    0.12       0  4990.5    0.07       0
  4994.5    0.12       0  5007.3     0.1       0  5009.3    0.12       0
  5177.1    0.05       0
Bank Sta=4990.5,4994.5
Exp/Cntr=0.3,0.1

Type RM Length L Ch R = 1,475,169,169,169
BEGIN DESCRIPTION:
Lacy 169 559
END DESCRIPTION:
XS GIS Cut Line= 3
      2721168.15      6850368.94      2720925.60      6850347.44
      2720691.43      6850503.31
#Sta/Elev= 30
  4756.5  408.63  4778.7  408.49  4818.9  409.00  4828.9  406.72  4839.0  404.89
  4847.0  404.67  4847.3  404.17  4850.8  404.17  4851.0  404.67  4859.0  405.57
  4869.1  407.43  4949.4  404.98  4974.4  404.94  4997.3  405.21  5016.5  405.11
  5031.5  405.65  5046.6  406.35  5052.6  407.26  5059.6  407.92  5073.6  408.32
  5088.6  408.36  5095.6  409.51  5118.7  410.81  5131.7  411.36  5139.7  411.99
  5156.7  412.19  5203.7  414.57  5247.9  414.75  5269.0  415.40  5281.3  415.50
#Mann=5,-1,0
  4756.5    0.05       0  4847.0    0.07       0  4851.0    0.05       0
  4974.4    0.12       0  5156.7    0.05       0
Bank Sta=4847,4851
Exp/Cntr=0.3,0.1

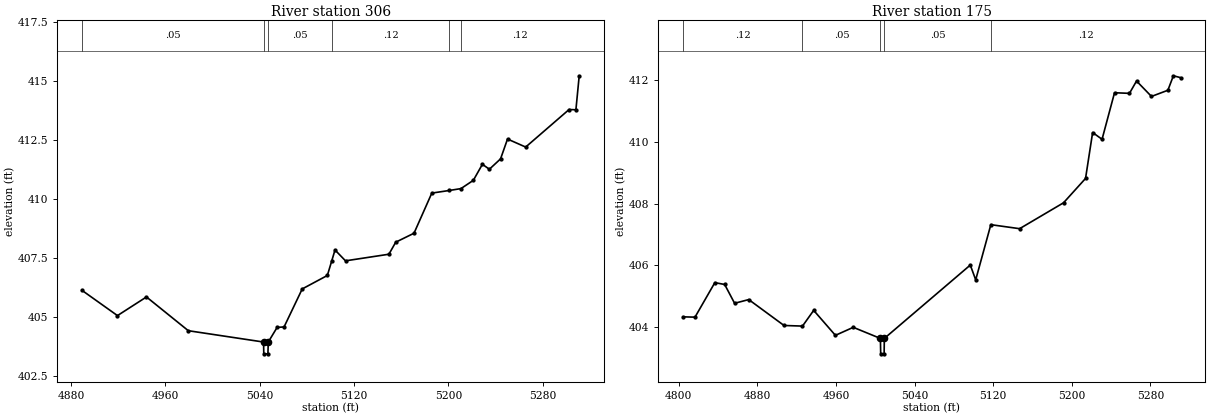
Type RM Length L Ch R = 1,306,131,131,131
BEGIN DESCRIPTION:
Lacy 169 560
END DESCRIPTION:
XS GIS Cut Line= 3
      2721036.10      6850173.64      2720919.22      6850178.72
      2720659.39      6850337.90
#Sta/Elev= 30
  4889.2  406.15  4919.3  405.08  4943.9  405.87  4979.4  404.44  5043.2  403.96
  5043.4  403.46  5046.9  403.46  5047.2  403.96  5054.7  404.58  5060.6  404.60
  5076.0  406.21  5097.3  406.78  5101.1  407.41  5103.8  407.86  5112.7  407.40
  5149.5  407.68  5155.3  408.19  5170.8  408.57  5185.9  410.27  5200.6  410.38
  5210.6  410.46  5221.1  410.81  5228.8  411.49  5234.7  411.28  5244.2  411.72
  5250.1  412.56  5265.5  412.22  5302.3  413.81  5308.1  413.80  5310.9  415.24
#Mann=6,-1,0
  4889.2    0.05       0  5043.2    0.04       0  5047.2    0.05       0
  5101.1    0.12       0  5200.6    0.05       0  5210.6    0.12       0
Bank Sta=5043.2,5047.2
Exp/Cntr=0.3,0.1

Type RM Length L Ch R = 1,175,0,0,0
BEGIN DESCRIPTION:
Lacy 169 561
END DESCRIPTION:
XS GIS Cut Line= 3
      2721077.84      6850083.70      2720883.77      6850060.90
      2720605.95      6850200.00
#Sta/Elev= 30
  4804.6  404.33  4816.5  404.32  4836.7  405.44  4846.7  405.38  4856.8  404.77
  4871.2  404.89  4907.1  404.05  4925.9  404.03  4937.3  404.54  4959.4  403.73
  4977.6  403.99  5005.2  403.63  5005.5  403.13  5009.0  403.13  5009.2  403.63
  5096.7  406.01  5102.2  405.53  5117.6  407.32  5146.9  407.19  5191.6  408.03
  5214.0  408.82  5221.2  410.31  5230.8  410.09  5243.5  411.60  5258.7  411.58
  5265.9  411.98  5281.1  411.48  5297.8  411.68  5303.4  412.15  5310.7  412.09
#Mann=5,-1,0
  4804.6    0.12       0  4925.9    0.05       0  5005.2    0.05       0
  5009.2    0.05       0  5117.6    0.12       0
Bank Sta=5005.2,5009.2
Exp/Cntr=0.3,0.1

Chan Stop Cuts=-1