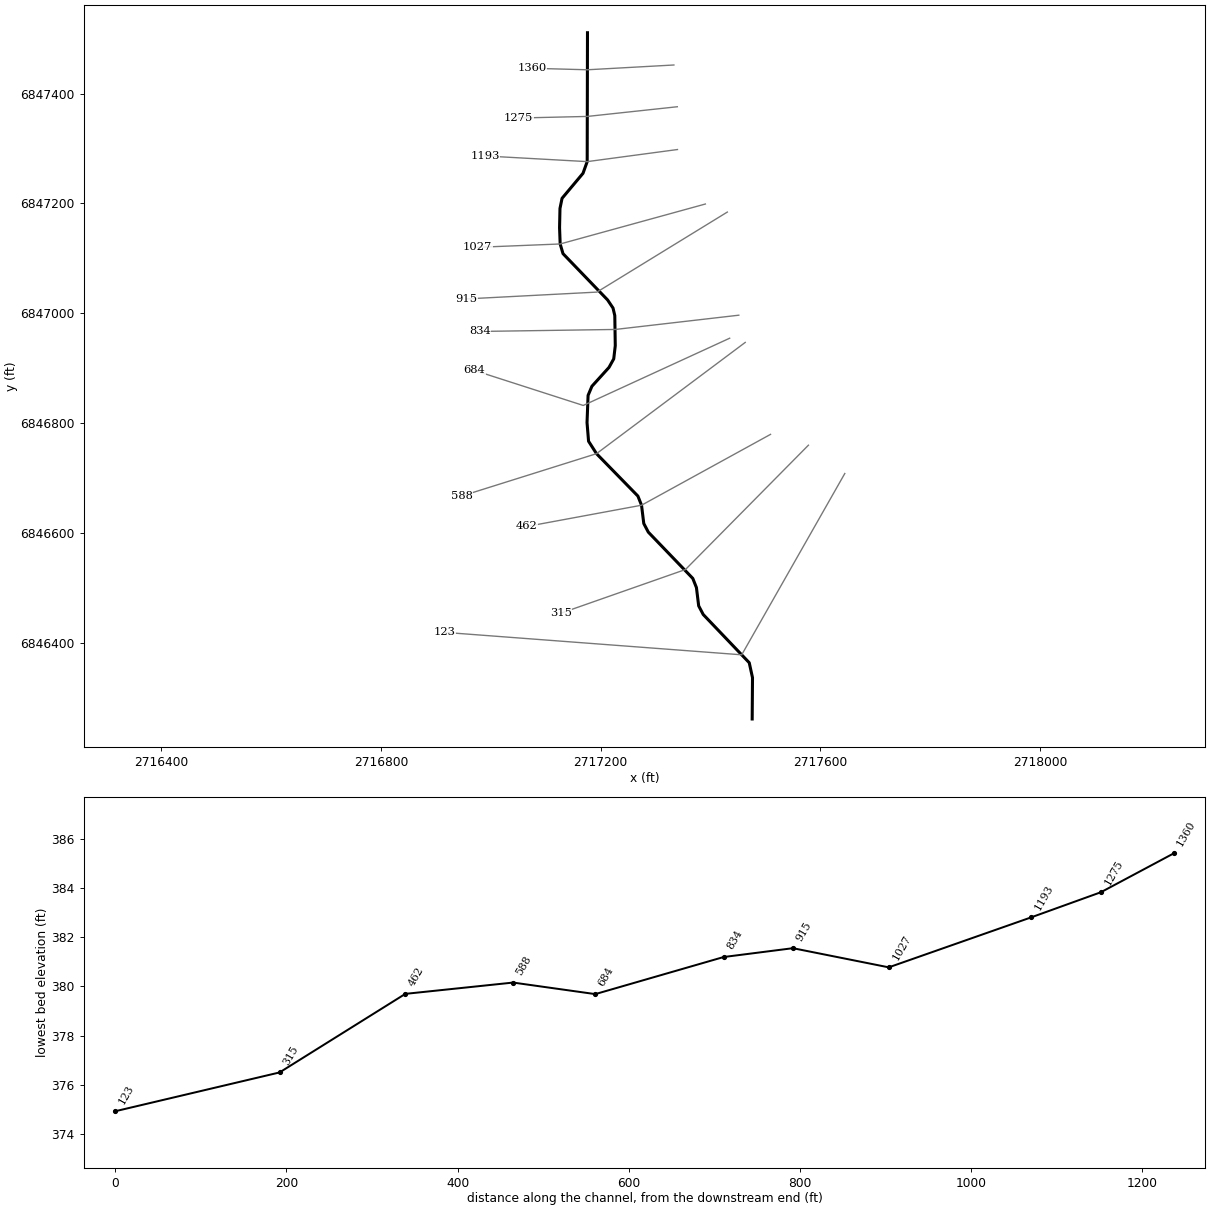
--- Lacy 170.prj (project) ---

Proj Title=Lacy 170 Base Level Engineering
Current Plan=p01
Default Exp/Contr=0.3,0.1
English Units
Geom File=g01
Flow File=f01
Plan File=p01
BEGIN DESCRIPTION:
Lacy 170
END DESCRIPTION:

--- Lacy 170.p01 (plan) ---

Plan Title=Multiple Run
Short Identifier=Multiple
Geom File=g01
Flow File=f01
Subcritical Flow
K Sum by GR= 0
Std Step Tol= 0.01
Critical Tol= 0.01
Num of Std Step Trials= 20
Max Error Tol= 0.3
Flow Tol Ratio= 0.001
Split Flow NTrial= 30
Split Flow Tol= 0.02
Split Flow Ratio= 0.02
Log Output Level= 0
Friction Slope Method= 1
Unsteady Friction Slope Method= 2
Unsteady Bridges Friction Slope Method= 1
Parabolic Critical Depth
Global Vel Dist=  1 , 1 , 1
Global Log Level= 0
CheckData=True
Encroach Param= -1, 0, 0, 0
BEGIN DESCRIPTION:
Multiple Run
END DESCRIPTION:

--- Lacy 170.f01 (steady flow) ---

Flow Title=Multiple
Number of Profiles=7
Profile Names=10-year,25-year,50-year,1pct_min,100-year,1pct_plu,500-year
River Rch & RM= Lacy 170,Reach-1,1360
     224     281     325     187     373     744     489
Boundary for River Rch & Prof#=Lacy 170,Reach-1,1
Up Type=0
Dn Type=3
Dn Slope=0.005
Boundary for River Rch & Prof#=Lacy 170,Reach-1,2
Up Type=0
Dn Type=3
Dn Slope=0.005
Boundary for River Rch & Prof#=Lacy 170,Reach-1,3
Up Type=0
Dn Type=3
Dn Slope=0.005
Boundary for River Rch & Prof#=Lacy 170,Reach-1,4
Up Type=0
Dn Type=3
Dn Slope=0.005
Boundary for River Rch & Prof#=Lacy 170,Reach-1,5
Up Type=0
Dn Type=3
Dn Slope=0.005
Boundary for River Rch & Prof#=Lacy 170,Reach-1,6
Up Type=0
Dn Type=3
Dn Slope=0.005
Boundary for River Rch & Prof#=Lacy 170,Reach-1,7
Up Type=0
Dn Type=3
Dn Slope=0.005

--- Lacy 170.g01 (geometry) ---

Geom Title=Existing Conditions

River Reach=Lacy 170,Reach-1
Reach XY= 30
      2717176.00      6847511.00      2717175.48      6847276.22
      2717167.85      6847254.94      2717129.70      6847209.40
      2717125.90      6847190.90      2717125.15      6847155.95
      2717126.25      6847126.22      2717131.41      6847108.58
      2717212.63      6847024.29      2717222.53      6847009.50
      2717225.75      6846995.78      2717226.61      6846940.96
      2717223.83      6846916.98      2717215.18      6846901.37
      2717184.09      6846867.04      2717177.10      6846850.45
      2717175.18      6846800.93      2717177.97      6846766.89
      2717192.44      6846744.26      2717267.82      6846667.04
      2717274.45      6846650.36      2717278.54      6846617.05
      2717286.80      6846601.33      2717367.82      6846517.04
      2717374.45      6846500.36      2717378.54      6846467.05
      2717386.80      6846451.33      2717470.64      6846363.49
      2717476.59      6846336.24      2717476.00      6846261.00

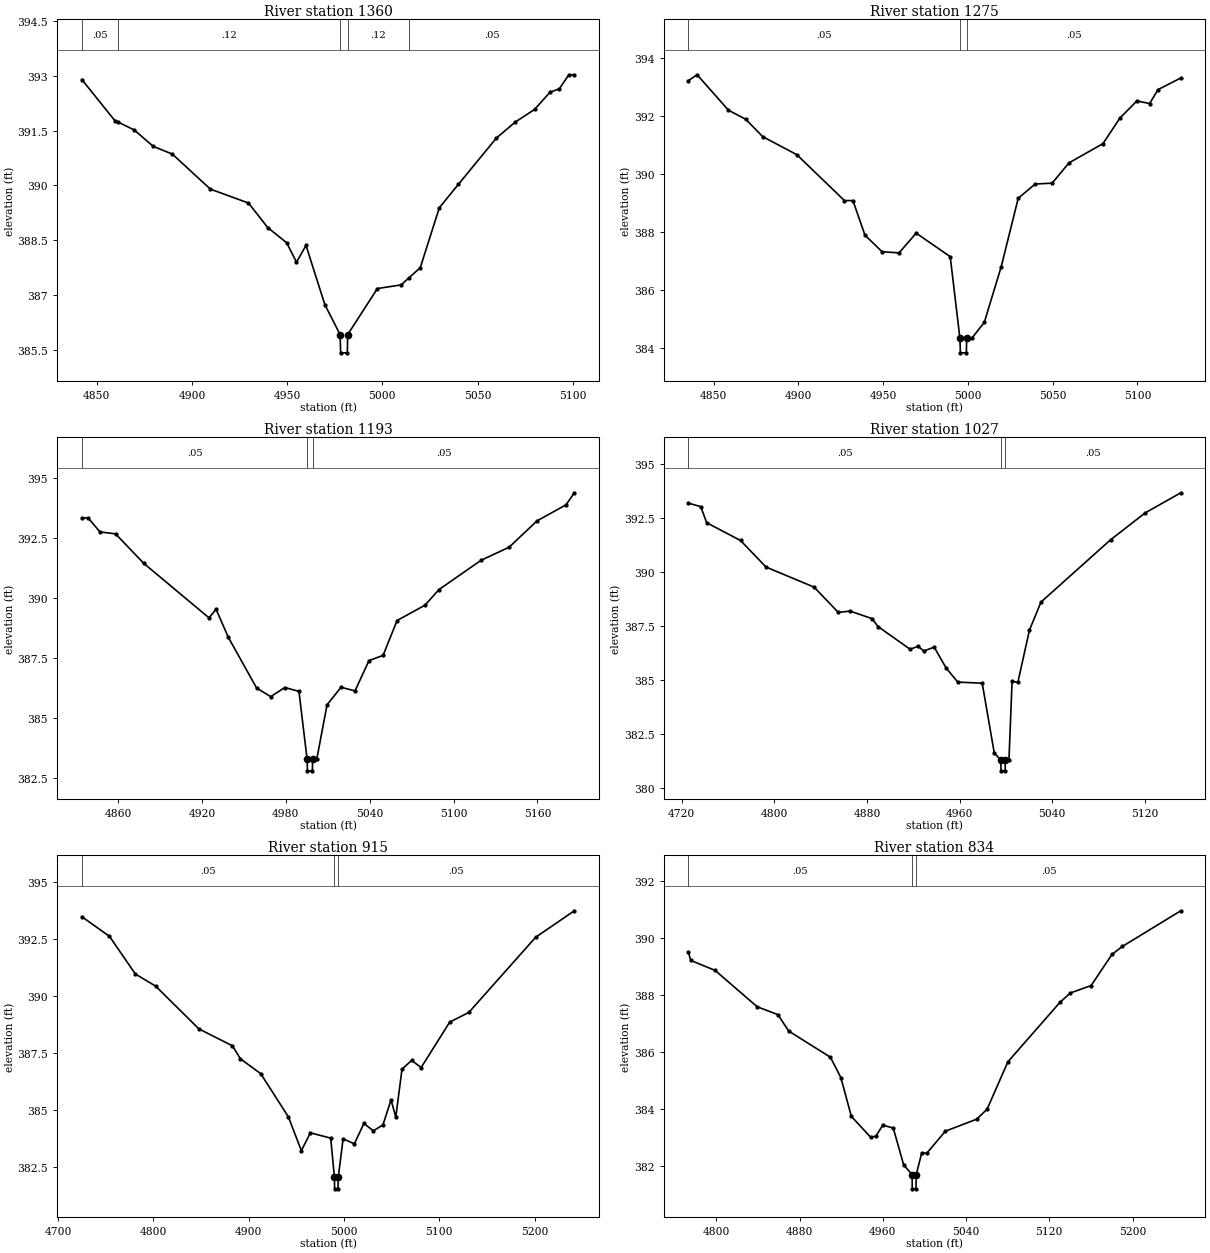
Type RM Length L Ch R = 1,1360,85,85,85
BEGIN DESCRIPTION:
Lacy 170 526
END DESCRIPTION:
XS GIS Cut Line= 3
      2717333.41      6847452.23      2717175.85      6847443.52
      2717075.09      6847446.26
#Sta/Elev= 30
  4842.2  392.90  4859.6  391.77  4861.0  391.74  4869.7  391.52  4879.7  391.07
  4889.7  390.86  4909.7  389.90  4929.7  389.52  4939.8  388.85  4949.8  388.43
  4954.9  387.90  4959.9  388.36  4969.8  386.74  4977.8  385.92  4978.1  385.42
  4981.6  385.42  4981.8  385.92  4997.4  387.18  5009.9  387.28  5013.9  387.47
  5019.9  387.75  5029.9  389.39  5039.9  390.03  5059.9  391.30  5069.9  391.74
  5079.9  392.08  5088.0  392.55  5093.0  392.65  5097.9  393.03  5100.8  393.03
#Mann=5,-1,0
  4842.2    0.05       0  4861.0    0.12       0  4977.8    0.07       0
  4981.8    0.12       0  5013.9    0.05       0
Bank Sta=4977.8,4981.8
Exp/Cntr=0.3,0.1

Type RM Length L Ch R = 1,1275,82,82,82
BEGIN DESCRIPTION:
Lacy 170 525
END DESCRIPTION:
XS GIS Cut Line= 3
      2717339.61      6847376.18      2717175.66      6847358.53
      2717050.09      6847355.63
#Sta/Elev= 30
  4835.1  393.21  4840.3  393.41  4858.8  392.19  4868.9  391.88  4879.0  391.28
  4899.1  390.66  4927.2  389.08  4932.2  389.08  4939.3  387.89  4949.4  387.32
  4959.4  387.28  4969.5  387.96  4989.6  387.15  4995.3  384.34  4995.6  383.84
  4999.1  383.84  4999.3  384.34  5002.3  384.34  5009.7  384.89  5019.7  386.81
  5029.7  389.16  5039.7  389.65  5049.7  389.68  5059.7  390.38  5079.7  391.04
  5089.7  391.92  5099.7  392.51  5107.2  392.42  5112.2  392.90  5125.6  393.30
#Mann=3,-1,0
  4835.1    0.05       0  4995.3    0.04       0  4999.3    0.05       0
Bank Sta=4995.3,4999.3
Exp/Cntr=0.3,0.1

Type RM Length L Ch R = 1,1193,166,166,166
BEGIN DESCRIPTION:
Lacy 170 524
END DESCRIPTION:
XS GIS Cut Line= 3
      2717339.91      6847298.25      2717175.48      6847276.22
      2716989.37      6847286.56
#Sta/Elev= 30
  4834.1  393.34  4838.6  393.34  4847.1  392.76  4858.2  392.68  4878.4  391.45
  4925.1  389.18  4930.1  389.54  4938.9  388.37  4959.1  386.26  4969.2  385.90
  4979.3  386.28  4989.4  386.12  4995.2  383.31  4995.5  382.81  4999.0  382.81
  4999.2  383.31  5002.2  383.31  5009.5  385.56  5019.5  386.29  5029.5  386.14
  5039.5  387.40  5049.6  387.62  5059.6  389.07  5079.6  389.71  5089.6  390.36
  5119.7  391.58  5139.7  392.12  5159.7  393.22  5180.5  393.89  5186.4  394.39
#Mann=3,-1,0
  4834.1    0.05       0  4995.2    0.04       0  4999.2    0.05       0
Bank Sta=4995.2,4999.2
Exp/Cntr=0.3,0.1

Type RM Length L Ch R = 1,1027,112,112,112
BEGIN DESCRIPTION:
Lacy 170 523
END DESCRIPTION:
XS GIS Cut Line= 3
      2717390.72      6847199.00      2717126.25      6847126.22
      2716975.37      6847120.12
#Sta/Elev= 30
  4725.7  393.18  4736.4  393.02  4741.6  392.27  4770.8  391.45  4792.8  390.22
  4834.3  389.29  4855.2  388.12  4865.4  388.18  4884.4  387.83  4889.6  387.46
  4917.3  386.41  4924.0  386.55  4929.1  386.33  4938.0  386.51  4948.4  385.54
  4958.4  384.89  4979.5  384.84  4989.9  381.61  4995.5  381.28  4995.8  380.78
  4999.3  380.78  4999.5  381.28  5002.6  381.28  5005.3  384.92  5010.3  384.88
  5020.3  387.30  5030.3  388.60  5090.3  391.48  5120.3  392.73  5151.0  393.66
#Mann=3,-1,0
  4725.7    0.05       0  4995.5    0.04       0  4999.5    0.05       0
Bank Sta=4995.5,4999.5
Exp/Cntr=0.3,0.1

Type RM Length L Ch R = 1,915,81,81,81
BEGIN DESCRIPTION:
Lacy 170 522
END DESCRIPTION:
XS GIS Cut Line= 3
      2717430.70      6847184.34      2717193.17      6847038.56
      2716955.49      6847026.15
#Sta/Elev= 30
  4725.0  393.47  4754.0  392.61  4781.2  390.96  4802.5  390.43  4847.8  388.56
  4883.0  387.82  4891.4  387.25  4912.7  386.60  4941.7  384.71  4955.3  383.23
  4964.8  384.01  4986.1  383.78  4990.0  382.06  4990.2  381.56  4993.7  381.56
  4994.0  382.06  4999.1  383.75  5010.9  383.53  5020.9  384.42  5030.9  384.10
  5040.9  384.36  5049.4  385.45  5054.4  384.70  5060.9  386.80  5071.0  387.18
  5081.0  386.87  5111.0  388.86  5131.0  389.28  5201.1  392.57  5241.7  393.73
#Mann=3,-1,0
  4725.0    0.05       0  4990.0    0.04       0  4994.0    0.05       0
Bank Sta=4990,4994
Exp/Cntr=0.3,0.1

Type RM Length L Ch R = 1,834,150,150,150
BEGIN DESCRIPTION:
Lacy 170 518
END DESCRIPTION:
XS GIS Cut Line= 3
      2717451.65      6846996.49      2717226.76      6846970.52
      2716979.77      6846966.88
#Sta/Elev= 30
  4773.0  389.49  4775.4  389.20  4798.8  388.85  4839.1  387.58  4859.2  387.30
  4869.4  386.73  4909.6  385.81  4919.6  385.10  4929.7  383.74  4948.2  383.01
  4953.2  383.04  4959.9  383.43  4970.0  383.33  4980.0  382.04  4988.1  381.70
  4988.3  381.20  4991.8  381.20  4992.1  381.70  4997.3  382.45  5002.3  382.45
  5020.1  383.22  5050.2  383.64  5060.2  383.99  5080.2  385.65  5130.2  387.73
  5140.2  388.06  5160.2  388.32  5180.2  389.41  5190.2  389.69  5246.4  390.94
#Mann=3,-1,0
  4773.0    0.05       0  4988.1    0.04       0  4992.1    0.05       0
Bank Sta=4988.1,4992.1
Exp/Cntr=0.3,0.1

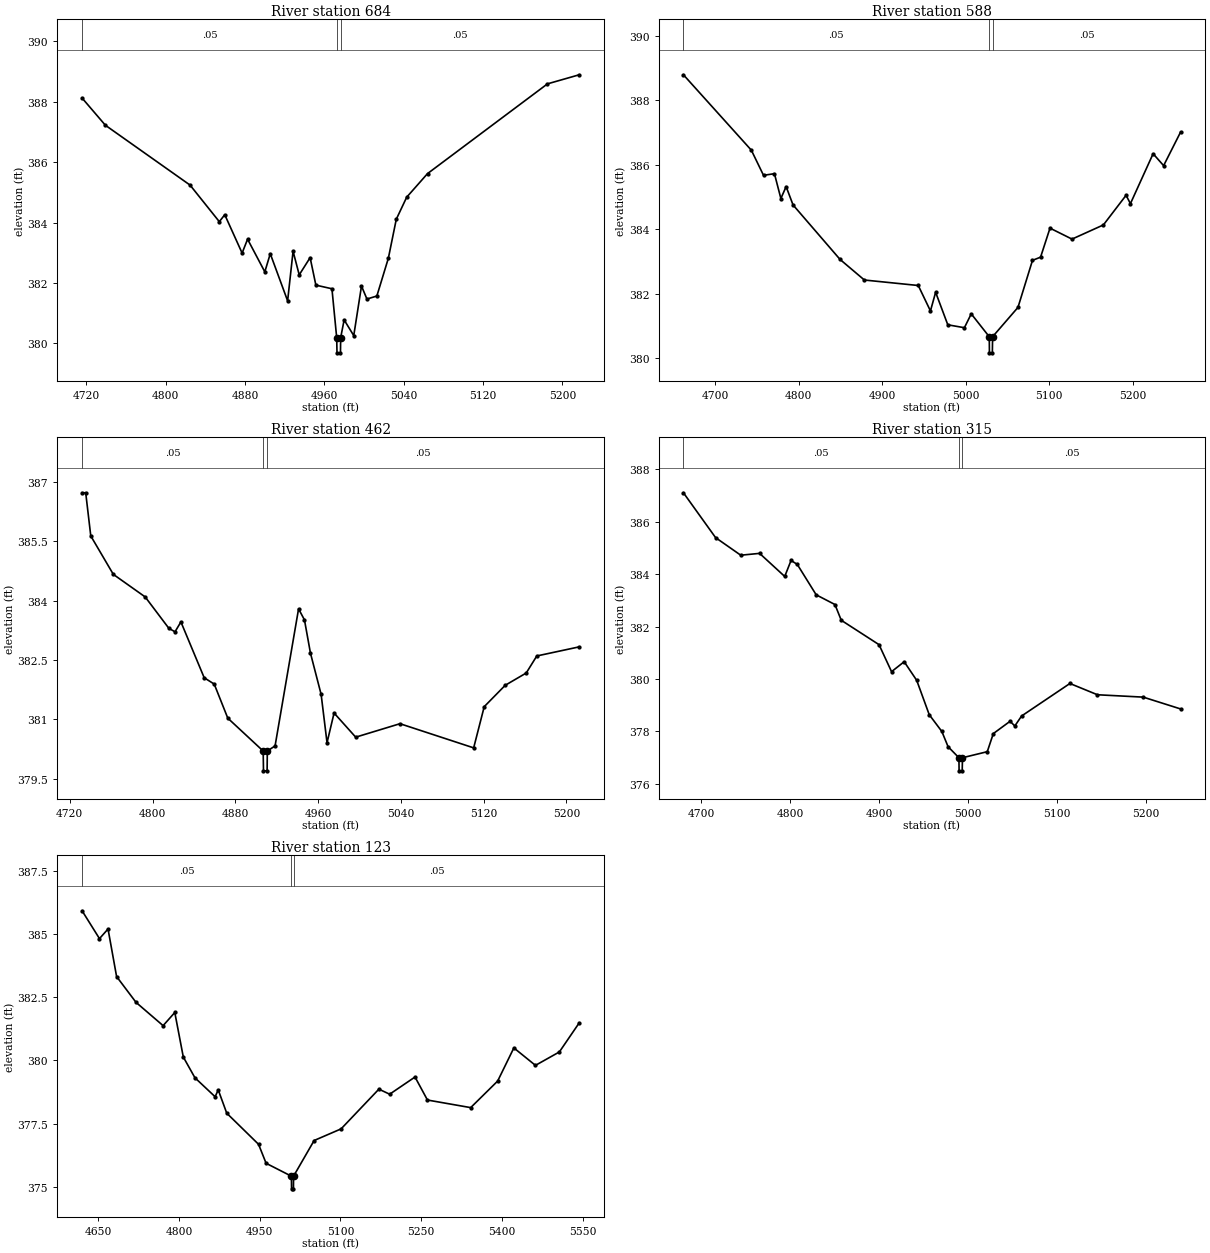
Type RM Length L Ch R = 1,684,96,96,96
BEGIN DESCRIPTION:
Lacy 170 517
END DESCRIPTION:
XS GIS Cut Line= 3
      2717434.98      6846954.56      2717168.30      6846832.09
      2716970.35      6846895.77
#Sta/Elev= 30
  4715.6  388.12  4739.1  387.22  4824.5  385.24  4854.0  384.03  4859.5  384.26
  4877.0  382.99  4882.5  383.45  4899.9  382.37  4905.4  382.97  4922.9  381.41
  4928.4  383.05  4934.6  382.27  4945.6  382.84  4951.4  381.93  4967.6  381.81
  4972.4  380.19  4972.7  379.69  4976.2  379.69  4976.4  380.19  4979.9  380.78
  4989.6  380.26  4997.4  381.90  5002.9  381.47  5012.9  381.57  5024.5  382.82
  5032.5  384.11  5043.0  384.84  5064.0  385.62  5185.0  388.59  5217.0  388.89
#Mann=3,-1,0
  4715.6    0.05       0  4972.4    0.04       0  4976.4    0.05       0
Bank Sta=4972.4,4976.4
Exp/Cntr=0.3,0.1

Type RM Length L Ch R = 1,588,126,126,126
BEGIN DESCRIPTION:
Lacy 170 516
END DESCRIPTION:
XS GIS Cut Line= 3
      2717463.33      6846946.90      2717192.44      6846744.26
      2716946.68      6846667.05
#Sta/Elev= 30
  4661.7  388.79  4743.1  386.45  4757.7  385.67  4770.8  385.72  4778.5  384.95
  4784.8  385.32  4793.1  384.75  4849.4  383.06  4878.6  382.42  4943.2  382.25
  4957.8  381.46  4964.0  382.04  4978.6  381.03  4998.5  380.94  5006.7  381.37
  5028.3  380.66  5028.5  380.16  5032.0  380.16  5032.3  380.66  5062.7  381.57
  5080.1  383.03  5089.8  383.13  5101.1  384.03  5127.5  383.69  5165.1  384.13
  5192.3  385.05  5197.5  384.79  5224.7  386.34  5237.3  385.97  5257.6  387.01
#Mann=3,-1,0
  4661.7    0.05       0  5028.3    0.05       0  5032.3    0.05       0
Bank Sta=5028.3,5032.3
Exp/Cntr=0.3,0.1

Type RM Length L Ch R = 1,462,147,147,147
BEGIN DESCRIPTION:
Lacy 170 515
END DESCRIPTION:
XS GIS Cut Line= 3
      2717509.43      6846779.43      2717274.45      6846650.36
      2717065.69      6846611.71
#Sta/Elev= 30
  4731.9  386.72  4735.4  386.72  4740.3  385.63  4762.1  384.66  4792.9  384.09
  4815.7  383.30  4821.7  383.21  4827.4  383.46  4849.9  382.05  4859.6  381.89
  4872.7  381.03  4906.9  380.20  4907.2  379.70  4910.7  379.70  4910.9  380.20
  4918.4  380.33  4941.1  383.79  4946.8  383.51  4952.6  382.67  4962.9  381.63
  4968.6  380.41  4975.4  381.16  4996.3  380.55  5039.1  380.89  5110.3  380.28
  5120.5  381.32  5140.8  381.86  5161.1  382.17  5171.3  382.60  5212.3  382.83
#Mann=3,-1,0
  4731.9    0.05       0  4906.9    0.05       0  4910.9    0.05       0
Bank Sta=4906.9,4910.9
Exp/Cntr=0.3,0.1

Type RM Length L Ch R = 1,315,192,192,192
BEGIN DESCRIPTION:
Lacy 170 514
END DESCRIPTION:
XS GIS Cut Line= 3
      2717578.46      6846759.72      2717354.51      6846533.26
      2717127.18      6846453.54
#Sta/Elev= 30
  4679.7  387.10  4715.9  385.39  4744.2  384.72  4765.4  384.79  4793.7  383.91
  4800.8  384.52  4807.8  384.37  4829.1  383.21  4850.2  382.84  4857.3  382.24
  4899.8  381.31  4913.9  380.28  4928.1  380.66  4942.2  379.95  4956.3  378.64
  4970.5  378.00  4977.5  377.42  4989.7  377.00  4989.9  376.50  4993.4  376.50
  4993.7  377.00  5021.6  377.23  5028.4  377.92  5047.3  378.39  5052.6  378.21
  5060.2  378.59  5114.6  379.83  5145.6  379.40  5197.1  379.31  5239.1  378.86
#Mann=3,-1,0
  4679.7    0.05       0  4989.7    0.04       0  4993.7    0.05       0
Bank Sta=4989.7,4993.7
Exp/Cntr=0.3,0.1

Type RM Length L Ch R = 1,123,0,0,0
BEGIN DESCRIPTION:
Lacy 170 513
END DESCRIPTION:
XS GIS Cut Line= 3
      2717644.69      6846708.12      2717456.91      6846377.88
      2716914.95      6846418.83
#Sta/Elev= 30
  4620.1  385.91  4652.4  384.81  4668.3  385.19  4684.2  383.31  4720.3  382.29
  4770.6  381.37  4792.3  381.89  4808.1  380.13  4829.7  379.31  4867.2  378.56
  4873.0  378.83  4888.8  377.91  4947.9  376.68  4961.9  375.93  5008.9  375.42
  5009.2  374.92  5012.7  374.92  5012.9  375.42  5051.1  376.83  5101.2  377.29
  5171.4  378.86  5191.4  378.66  5238.5  379.34  5261.6  378.43  5341.9  378.13
  5392.0  379.18  5422.1  380.49  5462.2  379.80  5506.6  380.33  5543.5  381.48
#Mann=3,-1,0
  4620.1    0.05       0  5008.9    0.04       0  5012.9    0.05       0
Bank Sta=5008.9,5012.9
Exp/Cntr=0.3,0.1

Chan Stop Cuts=-1