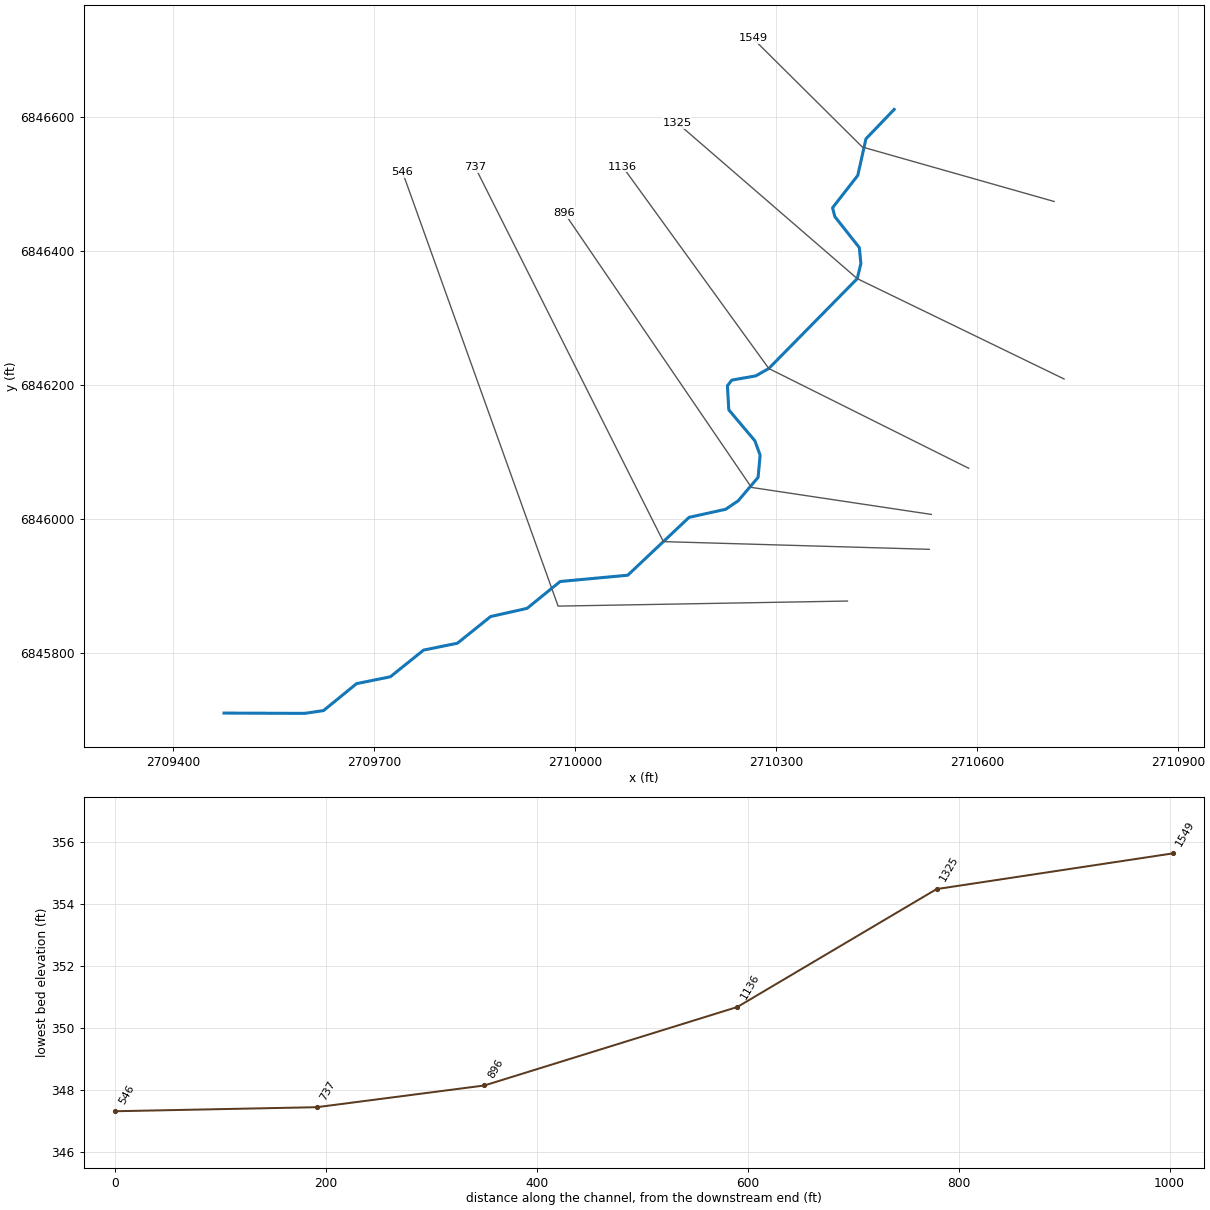
--- Lacy 171.prj (project) ---

Proj Title=Lacy 171 Base Level Engineering
Current Plan=p01
Default Exp/Contr=0.3,0.1
English Units
Geom File=g01
Flow File=f01
Plan File=p01
BEGIN DESCRIPTION:
Lacy 171
END DESCRIPTION:

--- Lacy 171.p01 (plan) ---

Plan Title=Multiple Run
Short Identifier=Multiple
Geom File=g01
Flow File=f01
Subcritical Flow
K Sum by GR= 0
Std Step Tol= 0.01
Critical Tol= 0.01
Num of Std Step Trials= 20
Max Error Tol= 0.3
Flow Tol Ratio= 0.001
Split Flow NTrial= 30
Split Flow Tol= 0.02
Split Flow Ratio= 0.02
Log Output Level= 0
Friction Slope Method= 1
Unsteady Friction Slope Method= 2
Unsteady Bridges Friction Slope Method= 1
Parabolic Critical Depth
Global Vel Dist=  1 , 1 , 1
Global Log Level= 0
CheckData=True
Encroach Param= -1, 0, 0, 0
BEGIN DESCRIPTION:
Multiple Run
END DESCRIPTION:

--- Lacy 171.f01 (steady flow) ---

Flow Title=Multiple
Number of Profiles=7
Profile Names=10-year,25-year,50-year,1pct_min,100-year,1pct_plu,500-year
River Rch & RM= Lacy 171,Reach-1,1549
     205     253     290     165     329     656     422
Boundary for River Rch & Prof#=Lacy 171,Reach-1,1
Up Type=0
Dn Type=3
Dn Slope=0.005
Boundary for River Rch & Prof#=Lacy 171,Reach-1,2
Up Type=0
Dn Type=3
Dn Slope=0.005
Boundary for River Rch & Prof#=Lacy 171,Reach-1,3
Up Type=0
Dn Type=3
Dn Slope=0.005
Boundary for River Rch & Prof#=Lacy 171,Reach-1,4
Up Type=0
Dn Type=3
Dn Slope=0.005
Boundary for River Rch & Prof#=Lacy 171,Reach-1,5
Up Type=0
Dn Type=3
Dn Slope=0.005
Boundary for River Rch & Prof#=Lacy 171,Reach-1,6
Up Type=0
Dn Type=3
Dn Slope=0.005
Boundary for River Rch & Prof#=Lacy 171,Reach-1,7
Up Type=0
Dn Type=3
Dn Slope=0.005

--- Lacy 171.g01 (geometry) ---

Geom Title=Existing Conditions

River Reach=Lacy 171,Reach-1
Reach XY= 30
      2710476.00      6846611.00      2710433.88      6846567.14
      2710421.67      6846512.58      2710384.05      6846464.31
      2710387.51      6846451.08      2710424.02      6846404.95
      2710426.32      6846381.16      2710420.89      6846358.71
      2710288.92      6846224.73      2710269.38      6846213.69
      2710233.74      6846207.46      2710227.18      6846198.99
      2710229.22      6846163.10      2710268.15      6846116.96
      2710275.97      6846095.55      2710272.96      6846062.42
      2710243.22      6846027.49      2710224.63      6846014.89
      2710169.98      6846002.81      2710078.42      6845916.54
      2709977.59      6845907.17      2709928.18      6845867.12
      2709873.80      6845854.92      2709824.28      6845815.16
      2709773.80      6845804.92      2709724.28      6845765.16
      2709673.82      6845754.88      2709624.46      6845714.72
      2709596.18      6845710.56      2709476.00      6845711.00

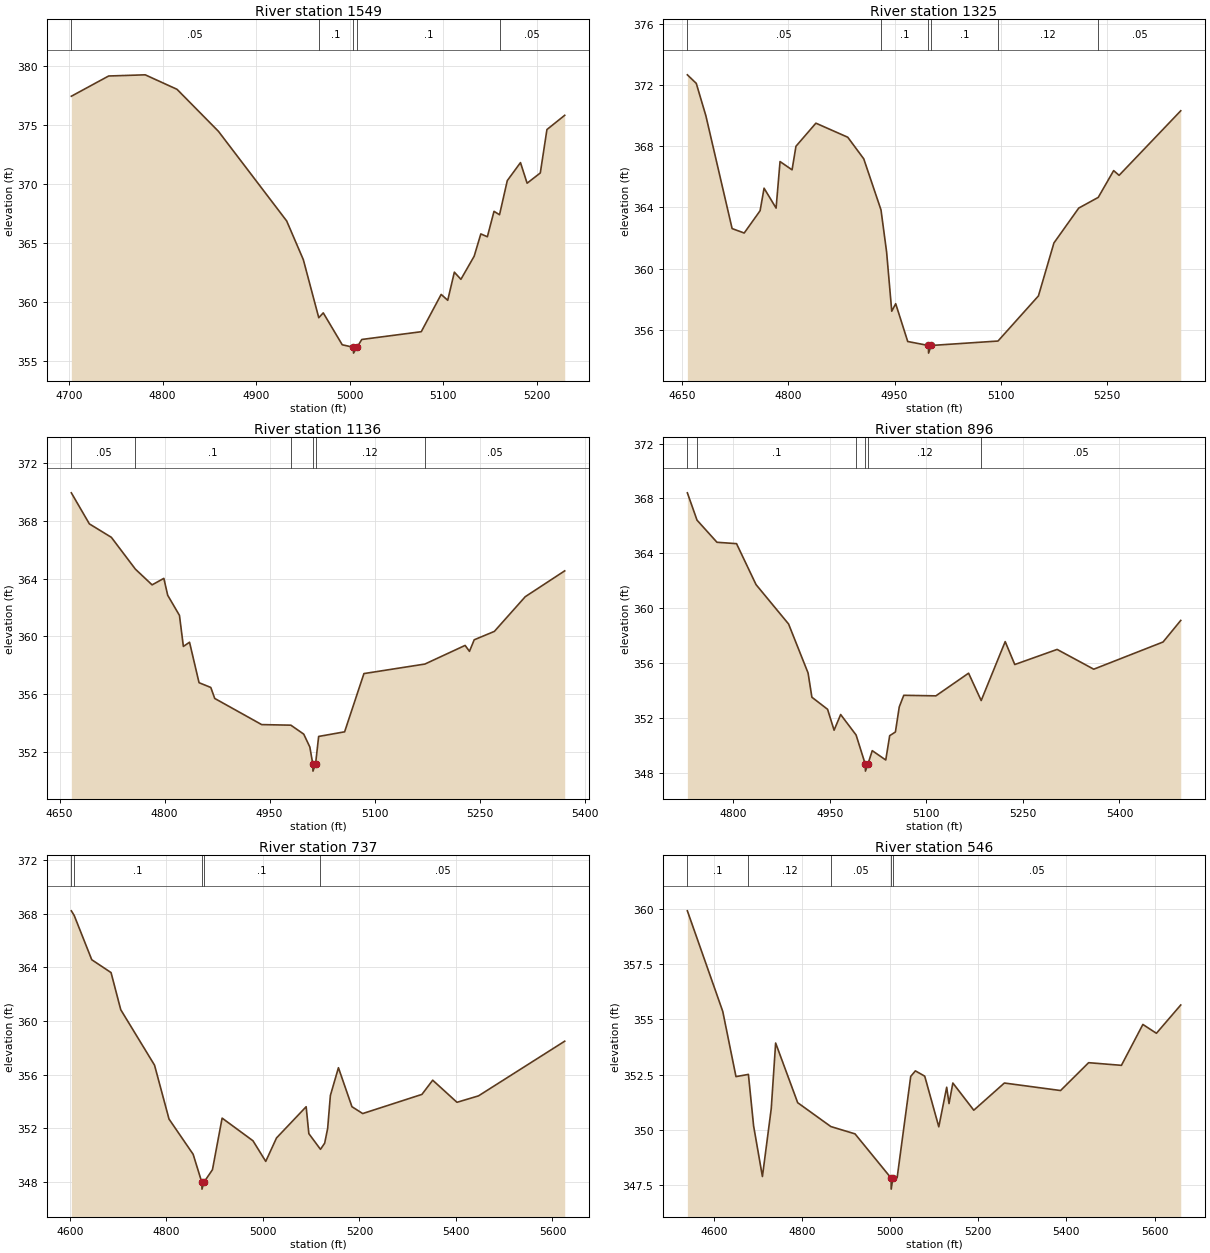
Type RM Length L Ch R = 1,1549,224,224,224
BEGIN DESCRIPTION:
Lacy 171 482
END DESCRIPTION:
XS GIS Cut Line= 3
      2710714.67      6846473.75      2710428.46      6846554.94
      2710265.09      6846716.98
#Sta/Elev= 30
  4702.5  377.46  4742.4  379.18  4781.5  379.28  4815.5  378.05  4859.8  374.48
  4932.8  366.86  4950.6  363.57  4967.1  358.64  4971.9  359.05  4992.2  356.34
  5004.0  356.13  5004.3  355.63  5008.0  356.13  5013.1  356.79  5076.7  357.45
  5098.0  360.62  5105.0  360.12  5112.1  362.51  5119.1  361.90  5133.3  363.87
  5140.4  365.76  5147.4  365.52  5154.5  367.68  5160.4  367.39  5168.7  370.29
  5182.8  371.82  5189.9  370.07  5204.0  370.94  5211.1  374.63  5230.1  375.84
#Mann=5,-1,0
  4702.5    0.05       0  4967.1     0.1       0  5004.0    0.07       0
  5008.0     0.1       0  5160.4    0.05       0
Bank Sta=5004,5008
Exp/Cntr=0.3,0.1

Type RM Length L Ch R = 1,1325,189,189,189
BEGIN DESCRIPTION:
Lacy 171 483
END DESCRIPTION:
XS GIS Cut Line= 3
      2710729.55      6846209.13      2710420.89      6846358.71
      2710152.38      6846590.78
#Sta/Elev= 30
  4657.0  372.67  4669.6  372.11  4683.2  369.99  4720.3  362.62  4737.4  362.33
  4759.9  363.79  4765.5  365.26  4782.5  363.96  4788.1  367.00  4805.1  366.46
  4810.6  368.00  4838.8  369.51  4883.9  368.59  4906.5  367.18  4930.9  363.84
  4938.8  361.10  4946.1  357.22  4951.7  357.71  4968.7  355.24  4997.9  354.98
  4998.2  354.48  5001.9  354.98  5096.4  355.27  5153.6  358.22  5175.5  361.68
  5210.6  363.96  5238.2  364.66  5260.0  366.41  5267.7  366.10  5354.9  370.32
#Mann=6,-1,0
  4657.0    0.05       0  4930.9     0.1       0  4997.9    0.07       0
  5001.9     0.1       0  5096.4    0.12       0  5238.2    0.05       0
Bank Sta=4997.9,5001.9
Exp/Cntr=0.3,0.1

Type RM Length L Ch R = 1,1136,240,240,240
BEGIN DESCRIPTION:
Lacy 171 484
END DESCRIPTION:
XS GIS Cut Line= 3
      2710587.19      6846075.99      2710288.92      6846224.73
      2710070.77      6846525.68
#Sta/Elev= 30
  4666.7  369.94  4692.5  367.79  4723.9  366.86  4758.2  364.66  4782.1  363.57
  4798.9  364.02  4804.4  362.85  4821.2  361.46  4826.8  359.31  4835.6  359.60
  4849.2  356.80  4866.0  356.47  4871.6  355.71  4938.7  353.90  4980.4  353.86
  4998.8  353.24  5007.5  352.35  5011.7  351.18  5012.0  350.68  5015.7  351.18
  5020.1  353.08  5057.2  353.40  5084.8  357.43  5171.9  358.09  5229.4  359.38
  5235.6  358.97  5242.4  359.77  5271.2  360.35  5315.3  362.75  5371.7  364.54
#Mann=6,-1,0
  4666.7    0.05       0  4758.2     0.1       0  4980.4    0.12       0
  5011.7    0.07       0  5015.7    0.12       0  5171.9    0.05       0
Bank Sta=5011.7,5015.7
Exp/Cntr=0.3,0.1

Type RM Length L Ch R = 1,896,159,159,159
BEGIN DESCRIPTION:
Lacy 171 485
END DESCRIPTION:
XS GIS Cut Line= 3
      2710531.52      6846007.17      2710263.02      6846047.44
      2709983.96      6846456.52
#Sta/Elev= 30
  4728.5  368.41  4743.5  366.42  4774.5  364.81  4804.9  364.71  4835.2  361.73
  4885.8  358.86  4916.1  355.29  4922.0  353.53  4946.4  352.65  4956.5  351.13
  4966.7  352.27  4990.7  350.78  5005.0  348.65  5005.2  348.15  5009.0  348.65
  5015.8  349.64  5036.8  348.96  5042.9  350.73  5051.8  351.00  5057.8  352.83
  5064.8  353.67  5114.7  353.63  5165.5  355.28  5185.1  353.29  5222.4  357.58
  5237.3  355.91  5303.1  357.01  5360.0  355.57  5467.7  357.55  5495.2  359.12
#Mann=6,-1,0
  4728.5    0.05       0  4743.5     0.1       0  4990.7    0.12       0
  5005.0    0.07       0  5009.0    0.12       0  5185.1    0.05       0
Bank Sta=5005,5009
Exp/Cntr=0.3,0.1

Type RM Length L Ch R = 1,737,191,191,191
BEGIN DESCRIPTION:
Lacy 171 486
END DESCRIPTION:
XS GIS Cut Line= 3
      2710528.32      6845955.15      2710131.58      6845966.63
      2709850.57      6846525.23
#Sta/Elev= 30
  4603.1  368.22  4609.1  367.87  4645.4  364.57  4685.4  363.61  4705.5  360.84
  4775.5  356.70  4805.5  352.68  4855.5  350.05  4873.5  347.95  4873.8  347.45
  4877.5  347.95  4895.5  348.90  4915.5  352.75  4979.4  351.06  5005.9  349.52
  5028.2  351.27  5089.6  353.60  5095.2  351.59  5119.3  350.42  5128.0  350.88
  5134.2  351.99  5139.8  354.44  5156.5  356.51  5184.5  353.60  5206.8  353.09
  5329.5  354.52  5351.8  355.58  5402.1  353.93  5446.7  354.41  5625.3  358.49
#Mann=5,-1,0
  4603.1    0.05       0  4609.1     0.1       0  4873.5    0.07       0
  4877.5     0.1       0  5119.3    0.05       0
Bank Sta=4873.5,4877.5
Exp/Cntr=0.3,0.1

Type RM Length L Ch R = 1,546,0,0,0
BEGIN DESCRIPTION:
Lacy 171 519
END DESCRIPTION:
XS GIS Cut Line= 3
      2710406.30      6845878.03      2709974.51      6845870.48
      2709742.28      6846517.72
#Sta/Elev= 30
  4540.0  359.91  4620.3  355.36  4650.3  352.41  4678.5  352.51  4690.3  350.18
  4710.3  347.89  4730.3  350.96  4740.3  353.93  4790.3  351.23  4865.6  350.15
  4920.4  349.82  5002.3  347.82  5002.5  347.32  5006.3  347.82  5016.0  347.84
  5046.8  352.42  5057.4  352.67  5078.6  352.43  5110.5  350.14  5128.4  351.93
  5133.7  351.19  5142.4  352.12  5189.9  350.89  5259.3  352.12  5386.8  351.78
  5450.5  353.04  5524.9  352.92  5573.6  354.77  5604.3  354.37  5659.5  355.65
#Mann=5,-1,0
  4540.0     0.1       0  4678.5    0.12       0  4865.6    0.05       0
  5002.3    0.04       0  5006.3    0.05       0
Bank Sta=5002.3,5006.3
Exp/Cntr=0.3,0.1

Chan Stop Cuts=-1