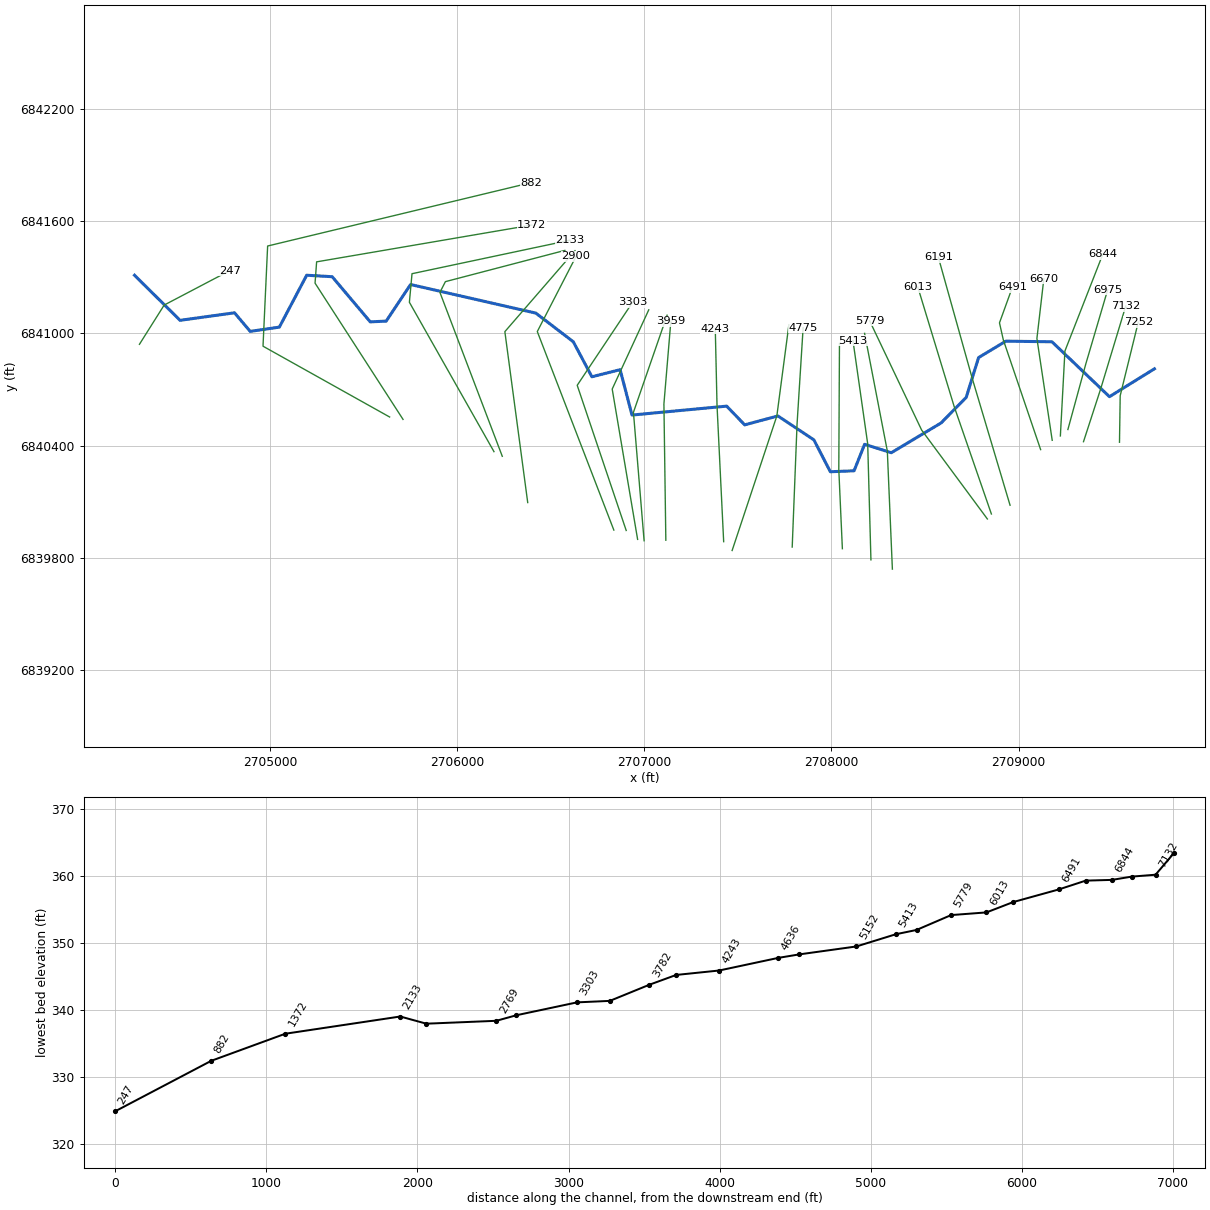
--- Lacy 173.prj (project) ---

Proj Title=Lacy 173 Base Level Engineering
Current Plan=p01
Default Exp/Contr=0.3,0.1
English Units
Geom File=g01
Flow File=f01
Plan File=p01
BEGIN DESCRIPTION:
Lacy 173
END DESCRIPTION:

--- Lacy 173.p01 (plan) ---

Plan Title=Multiple Run
Short Identifier=Multiple
Geom File=g01
Flow File=f01
Subcritical Flow
K Sum by GR= 0
Std Step Tol= 0.01
Critical Tol= 0.01
Num of Std Step Trials= 20
Max Error Tol= 0.3
Flow Tol Ratio= 0.001
Split Flow NTrial= 30
Split Flow Tol= 0.02
Split Flow Ratio= 0.02
Log Output Level= 0
Friction Slope Method= 1
Unsteady Friction Slope Method= 2
Unsteady Bridges Friction Slope Method= 1
Parabolic Critical Depth
Global Vel Dist=  1 , 1 , 1
Global Log Level= 0
CheckData=True
Encroach Param= -1, 0, 0, 0
BEGIN DESCRIPTION:
Multiple Run
END DESCRIPTION:

--- Lacy 173.f01 (steady flow) ---

Flow Title=Multiple
Number of Profiles=7
Profile Names=10-year,25-year,50-year,1pct_min,100-year,1pct_plu,500-year
River Rch & RM= Lacy 173,Reach-1,7252
     568     757     908     540    1078    2151    1520
River Rch & RM= Lacy 173,Reach-1,5550
     754    1019    1233     740    1477    2946    2116
Boundary for River Rch & Prof#=Lacy 173,Reach-1,1
Up Type=0
Dn Type=3
Dn Slope=0.005
Boundary for River Rch & Prof#=Lacy 173,Reach-1,2
Up Type=0
Dn Type=3
Dn Slope=0.005
Boundary for River Rch & Prof#=Lacy 173,Reach-1,3
Up Type=0
Dn Type=3
Dn Slope=0.005
Boundary for River Rch & Prof#=Lacy 173,Reach-1,4
Up Type=0
Dn Type=3
Dn Slope=0.005
Boundary for River Rch & Prof#=Lacy 173,Reach-1,5
Up Type=0
Dn Type=3
Dn Slope=0.005
Boundary for River Rch & Prof#=Lacy 173,Reach-1,6
Up Type=0
Dn Type=3
Dn Slope=0.005
Boundary for River Rch & Prof#=Lacy 173,Reach-1,7
Up Type=0
Dn Type=3
Dn Slope=0.005

--- Lacy 173.g01 (geometry) ---

Geom Title=Existing Conditions

River Reach=Lacy 173,Reach-1
Reach XY= 30
      2709726.00      6840811.00      2709485.63      6840662.08
      2709178.45      6840955.53      2708931.93      6840958.76
      2708786.38      6840871.11      2708720.24      6840658.47
      2708585.98      6840521.69      2708320.01      6840362.64
      2708177.32      6840407.66      2708120.92      6840266.03
      2707994.12      6840261.01      2707906.39      6840431.20
      2707713.99      6840559.15      2707536.48      6840511.56
      2707440.20      6840611.64      2706934.31      6840563.97
      2706870.82      6840806.40      2706719.93      6840768.48
      2706620.71      6840955.52      2706420.50      6841108.65
      2705750.96      6841261.50      2705620.89      6841065.95
      2705535.59      6841061.98      2705332.19      6841303.20
      2705195.88      6841311.11      2705049.87      6841033.81
      2704894.12      6841011.04      2704810.16      6841110.32
      2704519.26      6841070.13      2704276.00      6841311.00

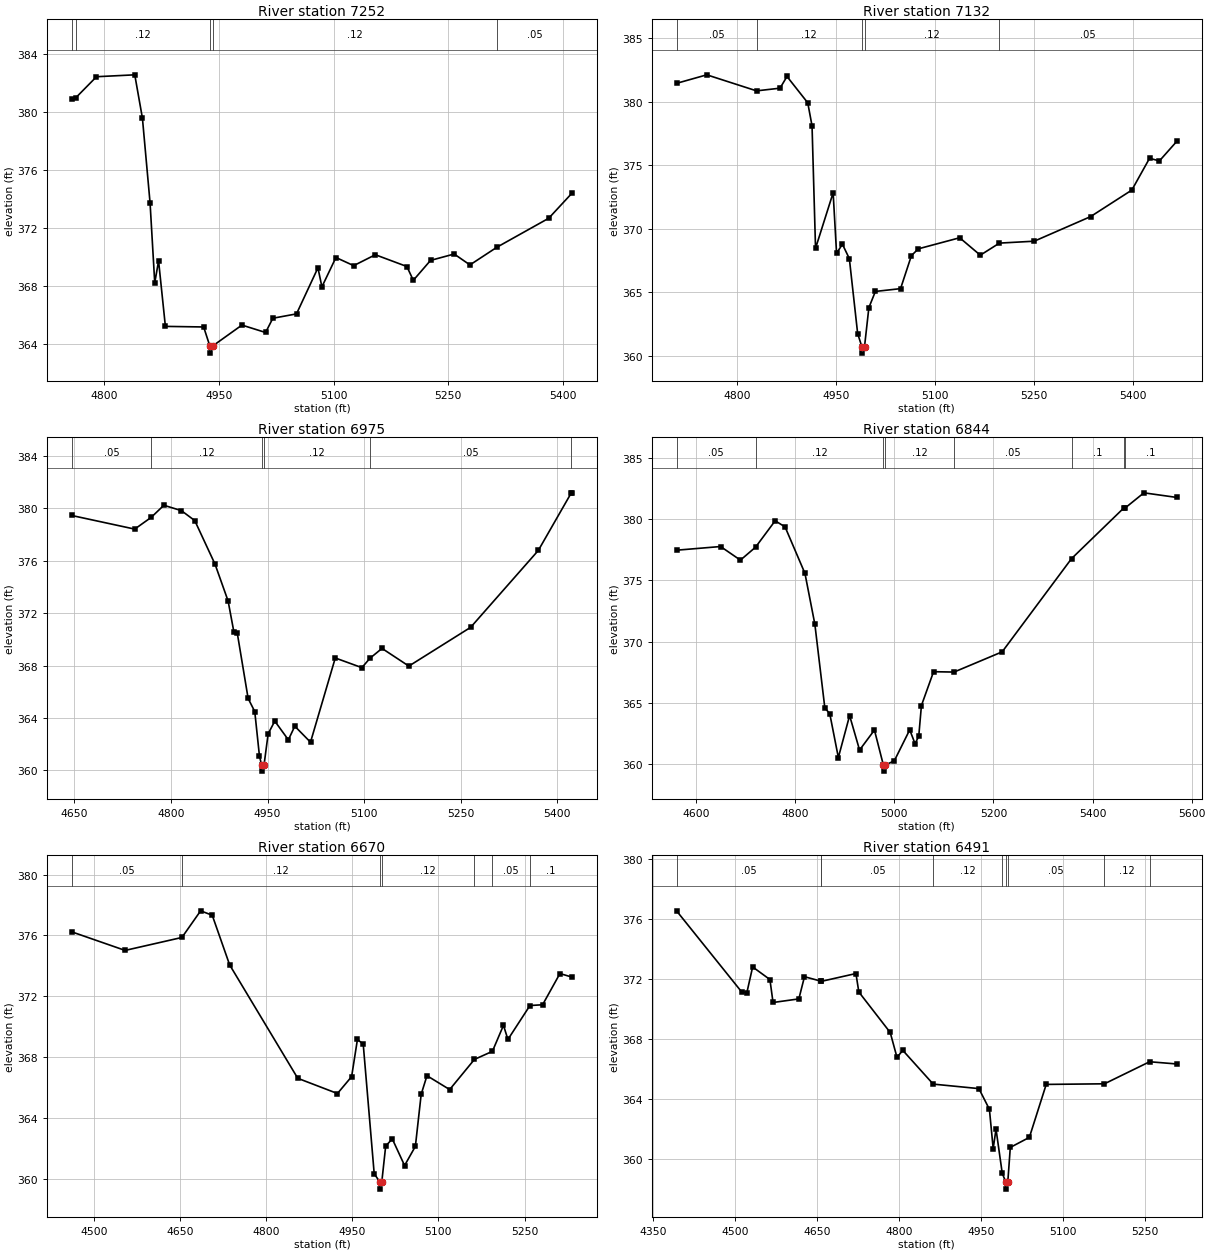
Type RM Length L Ch R = 1,7252,120,120,120
BEGIN DESCRIPTION:
Lacy 173 446
END DESCRIPTION:
XS GIS Cut Line= 3
      2709539.35      6840418.62      2709543.11      6840667.62
      2709639.79      6841060.88
#Sta/Elev= 30
  4757.9  380.89  4763.2  380.97  4790.3  382.42  4840.3  382.55  4850.3  379.57
  4860.3  373.73  4866.4  368.23  4871.4  369.75  4880.3  365.24  4930.3  365.20
  4938.3  363.90  4938.6  363.40  4942.3  363.90  4980.3  365.33  5011.2  364.82
  5020.7  365.80  5051.6  366.10  5079.6  369.27  5084.8  367.96  5103.1  369.98
  5126.3  369.42  5154.6  370.17  5195.8  369.36  5204.2  368.41  5226.7  369.78
  5257.6  370.22  5278.2  369.47  5313.5  370.69  5381.1  372.68  5411.9  374.43
#Mann=5,-1,0
  4757.9    0.05       0  4763.2    0.12       0  4938.3    0.07       0
  4942.3    0.12       0  5313.5    0.05       0
Bank Sta=4938.3,4942.3
Exp/Cntr=0.3,0.1

Type RM Length L Ch R = 1,7132,157,157,157
BEGIN DESCRIPTION:
Lacy 173 445
END DESCRIPTION:
XS GIS Cut Line= 3
      2709347.03      6840421.66      2709438.31      6840702.37
      2709572.86      6841146.77
#Sta/Elev= 30
  4707.7  381.43  4753.6  382.10  4829.1  380.84  4864.7  381.05  4875.3  381.97
  4906.8  379.90  4913.3  378.09  4918.6  368.46  4945.3  372.83  4950.5  368.07
  4959.4  368.78  4969.9  367.65  4982.5  361.76  4988.9  360.72  4989.2  360.22
  4992.9  360.72  4999.5  363.79  5009.4  365.07  5047.6  365.29  5064.1  367.89
  5074.6  368.42  5137.3  369.29  5168.6  367.92  5197.6  368.87  5250.4  369.02
  5335.8  370.95  5398.5  373.04  5425.4  375.54  5440.3  375.33  5467.2  376.90
#Mann=5,-1,0
  4707.7    0.05       0  4829.1    0.12       0  4988.9    0.07       0
  4992.9    0.12       0  5197.6    0.05       0
Bank Sta=4988.9,4992.9
Exp/Cntr=0.3,0.1

Type RM Length L Ch R = 1,6975,131,131,131
BEGIN DESCRIPTION:
Lacy 173 444
END DESCRIPTION:
XS GIS Cut Line= 3
      2709263.60      6840486.60      2709359.58      6840838.03
      2709476.58      6841234.53
#Sta/Elev= 30
  4645.7  379.46  4743.6  378.42  4769.3  379.32  4788.9  380.24  4816.1  379.83
  4836.9  379.07  4868.4  375.74  4888.7  372.93  4897.7  370.56  4902.9  370.49
  4919.8  365.49  4930.1  364.49  4937.4  361.09  4940.6  360.44  4940.8  359.94
  4944.6  360.44  4950.9  362.79  4961.2  363.76  4982.3  362.33  4992.3  363.37
  5016.7  362.15  5055.2  368.58  5096.5  367.84  5109.1  368.56  5127.8  369.31
  5169.5  367.96  5265.5  370.92  5370.6  376.79  5421.9  381.19  5423.4  381.19
#Mann=6,-1,0
  4645.7    0.05       0  4769.3    0.12       0  4940.6    0.07       0
  4944.6    0.12       0  5109.1    0.05       0  5421.9    0.12       0
Bank Sta=4940.6,4944.6
Exp/Cntr=0.3,0.1

Type RM Length L Ch R = 1,6844,174,174,174
BEGIN DESCRIPTION:
Lacy 173 443
END DESCRIPTION:
XS GIS Cut Line= 3
      2709223.42      6840452.28      2709247.72      6840906.07
      2709450.20      6841423.41
#Sta/Elev= 30
  4560.7  377.47  4649.6  377.77  4689.6  376.66  4720.2  377.72  4759.7  379.87
  4779.7  379.37  4819.8  375.58  4839.8  371.43  4859.9  364.61  4869.9  364.13
  4887.2  360.56  4909.9  363.98  4930.0  361.17  4960.0  362.80  4978.0  359.95
  4978.3  359.45  4982.0  359.95  5000.1  360.29  5031.2  362.82  5041.9  361.69
  5049.4  362.29  5054.8  364.80  5079.3  367.56  5120.6  367.53  5217.7  369.18
  5357.6  376.78  5463.8  380.94  5465.7  380.91  5503.7  382.15  5570.7  381.77
#Mann=8,-1,0
  4560.7    0.05       0  4720.2    0.12       0  4978.0    0.07       0
  4982.0    0.12       0  5120.6    0.05       0  5357.6     0.1       0
  5463.8    0.12       0  5465.7     0.1       0
Bank Sta=4978,4982
Exp/Cntr=0.3,0.1

Type RM Length L Ch R = 1,6670,179,179,179
BEGIN DESCRIPTION:
Lacy 173 442
END DESCRIPTION:
XS GIS Cut Line= 3
      2709179.83      6840429.01      2709098.06      6840973.23
      2709135.12      6841292.36
#Sta/Elev= 30
  4461.6  376.24  4554.6  375.02  4653.5  375.87  4686.1  377.62  4706.3  377.33
  4736.6  374.07  4855.2  366.62  4924.3  365.62  4949.0  366.73  4959.1  369.17
  4969.2  368.86  4988.3  360.35  4997.6  359.84  4997.8  359.34  5001.6  359.84
  5008.3  362.17  5019.8  362.64  5041.2  360.89  5060.0  362.15  5070.1  365.57
  5080.2  366.79  5119.7  365.88  5162.8  367.86  5194.1  368.39  5213.4  370.10
  5221.1  369.17  5259.5  371.40  5281.5  371.45  5311.7  373.50  5333.2  373.26
#Mann=7,-1,0
  4461.6    0.05       0  4653.5    0.12       0  4997.6    0.07       0
  5001.6    0.12       0  5162.8     0.1       0  5194.1    0.05       0
  5259.5     0.1       0
Bank Sta=4997.6,5001.6
Exp/Cntr=0.3,0.1

Type RM Length L Ch R = 1,6491,300,300,300
BEGIN DESCRIPTION:
Lacy 173 441
END DESCRIPTION:
XS GIS Cut Line= 4
      2709117.94      6840379.26      2708918.61      6840965.42
      2708898.06      6841056.67      2708967.11      6841247.39
#Sta/Elev= 30
  4393.3  376.57  4512.3  371.17  4521.9  371.11  4532.5  372.83  4564.1  371.99
  4569.8  370.46  4617.0  370.70  4627.3  372.18  4657.5  371.88  4658.3  371.87
  4721.4  372.39  4726.7  371.16  4784.1  368.46  4796.5  366.80  4807.1  367.27
  4862.7  365.02  4946.3  364.72  4965.5  363.34  4972.4  360.72  4977.6  362.02
  4989.0  359.07  4995.2  358.52  4995.4  358.02  4999.2  358.52  5003.7  360.80
  5038.6  361.47  5069.4  365.00  5175.9  365.04  5258.5  366.51  5308.8  366.36
#Mann=9,-1,0
  4393.3    0.05       0  4657.5    0.12       0  4658.3    0.05       0
  4862.7    0.12       0  4989.0    0.05       0  4995.2    0.03       0
  4999.2    0.05       0  5175.9    0.12       0  5258.5     0.1       0
Bank Sta=4995.2,4999.2
Exp/Cntr=0.3,0.1

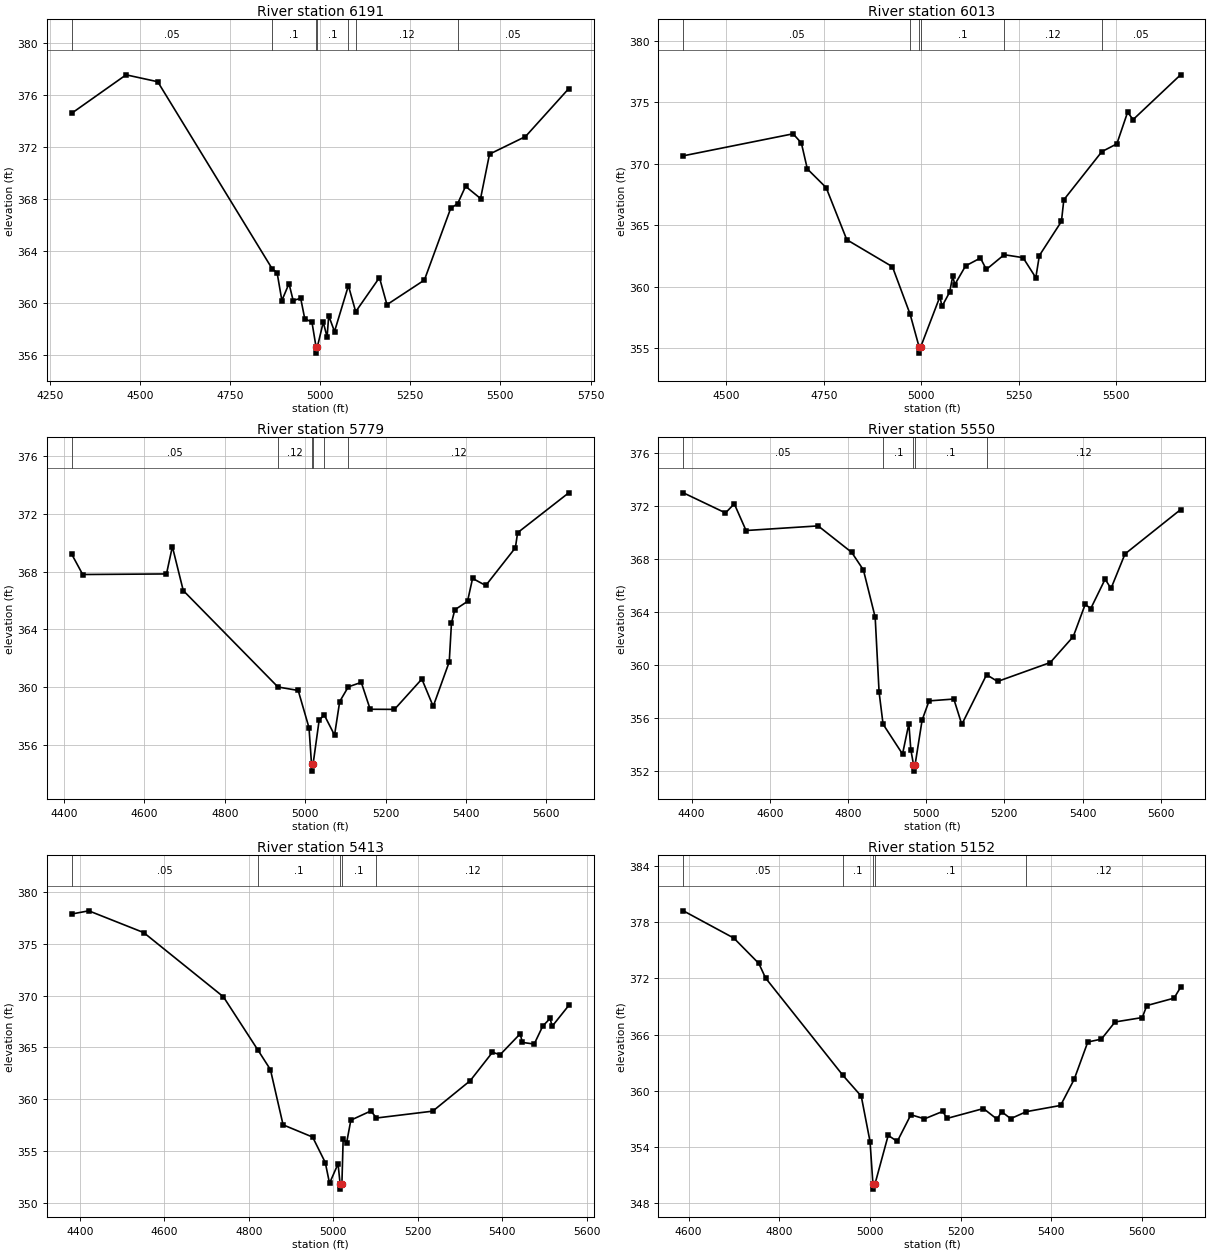
Type RM Length L Ch R = 1,6191,178,178,178
BEGIN DESCRIPTION:
Lacy 173 447
END DESCRIPTION:
XS GIS Cut Line= 3
      2708954.55      6840082.01      2708753.18      6840757.31
      2708571.47      6841406.47
#Sta/Elev= 30
  4310.7  374.56  4462.0  377.52  4549.7  376.99  4867.7  362.60  4880.7  362.34
  4894.0  360.19  4913.8  361.49  4925.3  360.19  4946.2  360.36  4957.4  358.80
  4977.5  358.52  4988.6  356.65  4988.8  356.15  4992.6  356.65  5008.8  358.53
  5019.4  357.38  5023.9  359.02  5040.0  357.81  5078.5  361.33  5098.7  359.33
  5164.6  361.95  5185.4  359.87  5289.2  361.76  5362.2  367.27  5381.5  367.63
  5403.4  368.96  5445.0  368.02  5469.8  371.43  5569.6  372.78  5689.5  376.46
#Mann=7,-1,0
  4310.7    0.05       0  4867.7     0.1       0  4988.6    0.07       0
  4992.6     0.1       0  5078.5    0.05       0  5098.7    0.12       0
  5381.5    0.05       0
Bank Sta=4988.6,4992.6
Exp/Cntr=0.3,0.1

Type RM Length L Ch R = 1,6013,234,234,234
BEGIN DESCRIPTION:
Lacy 173 448
END DESCRIPTION:
XS GIS Cut Line= 3
      2708854.77      6840035.17      2708655.69      6840610.19
      2708461.86      6841247.25
#Sta/Elev= 30
  4390.0  370.66  4671.3  372.45  4692.5  371.70  4707.8  369.59  4756.0  368.07
  4808.9  363.83  4925.9  361.63  4971.3  357.76  4994.3  355.10  4994.5  354.60
  4998.3  355.10  5047.7  359.20  5052.9  358.40  5072.5  359.56  5080.5  360.86
  5085.8  360.18  5113.4  361.70  5151.5  362.34  5166.6  361.41  5212.3  362.61
  5260.7  362.37  5293.4  360.74  5302.5  362.54  5359.1  365.32  5365.2  367.08
  5462.7  371.00  5501.1  371.63  5528.6  374.20  5542.9  373.61  5664.4  377.25
#Mann=6,-1,0
  4390.0    0.05       0  4971.3     0.1       0  4994.3    0.07       0
  4998.3     0.1       0  5212.3    0.12       0  5462.7    0.05       0
Bank Sta=4994.3,4998.3
Exp/Cntr=0.3,0.1

Type RM Length L Ch R = 1,5779,229,229,229
BEGIN DESCRIPTION:
Lacy 173 449
END DESCRIPTION:
XS GIS Cut Line= 3
      2708833.31      6840008.68      2708482.10      6840483.63
      2708204.53      6841066.95
#Sta/Elev= 30
  4418.8  369.23  4446.6  367.80  4655.0  367.84  4669.6  369.73  4696.7  366.69
  4932.2  360.02  4982.6  359.78  5009.5  357.20  5015.7  354.70  5015.9  354.20
  5019.7  354.70  5034.8  357.74  5047.5  358.08  5073.0  356.69  5085.8  359.01
  5107.2  360.03  5139.5  360.34  5161.6  358.48  5222.0  358.47  5290.2  360.57
  5318.4  358.68  5358.3  361.76  5363.8  364.44  5372.1  365.36  5403.7  365.94
  5416.3  367.53  5449.1  367.04  5522.8  369.65  5528.3  370.69  5655.5  373.45
#Mann=6,-1,0
  4418.8    0.05       0  4932.2    0.12       0  5015.7    0.07       0
  5019.7    0.12       0  5047.5     0.1       0  5107.2    0.12       0
Bank Sta=5015.7,5019.7
Exp/Cntr=0.3,0.1

Type RM Length L Ch R = 1,5550,137,137,137
BEGIN DESCRIPTION:
Lacy 173 450
END DESCRIPTION:
XS GIS Cut Line= 3
      2708325.72      6839740.79      2708298.71      6840371.70
      2708177.21      6841000.48
#Sta/Elev= 30
  4378.9  373.02  4486.7  371.50  4509.2  372.19  4539.3  370.17  4723.7  370.52
  4809.5  368.52  4839.5  367.19  4869.6  363.62  4879.6  357.96  4889.8  355.53
  4939.6  353.27  4955.8  355.57  4960.8  353.61  4967.6  352.48  4967.9  351.98
  4971.8  352.48  4989.7  355.84  5007.5  357.29  5070.8  357.43  5091.2  355.51
  5154.6  359.27  5182.8  358.76  5317.5  360.19  5376.3  362.15  5406.9  364.59
  5421.1  364.27  5457.8  366.49  5472.9  365.79  5508.7  368.40  5650.8  371.75
#Mann=5,-1,0
  4378.9    0.05       0  4889.8     0.1       0  4967.6    0.07       0
  4971.8     0.1       0  5154.6    0.12       0
Bank Sta=4967.6,4971.8
Exp/Cntr=0.3,0.1

Type RM Length L Ch R = 1,5413,261,261,261
BEGIN DESCRIPTION:
Lacy 173 451
END DESCRIPTION:
XS GIS Cut Line= 3
      2708211.14      6839790.09      2708193.83      6840410.17
      2708115.06      6840961.95
#Sta/Elev= 30
  4380.2  377.87  4421.1  378.18  4551.2  376.08  4739.9  369.89  4821.4  364.77
  4851.3  362.87  4881.3  357.54  4951.3  356.36  4981.3  353.90  4991.3  351.90
  5011.5  353.78  5016.4  351.84  5016.8  351.34  5020.6  351.84  5023.6  356.15
  5031.7  355.79  5041.8  357.99  5089.3  358.88  5102.5  358.20  5235.8  358.86
  5324.6  361.80  5377.3  364.54  5395.3  364.30  5442.9  366.32  5448.0  365.49
  5476.1  365.33  5496.3  367.06  5513.7  367.80  5518.7  367.05  5557.9  369.05
#Mann=5,-1,0
  4380.2    0.05       0  4821.4     0.1       0  5016.4    0.07       0
  5020.6     0.1       0  5102.5    0.12       0
Bank Sta=5016.4,5020.6
Exp/Cntr=0.3,0.1

Type RM Length L Ch R = 1,5152,377,377,377
BEGIN DESCRIPTION:
Lacy 173 452
END DESCRIPTION:
XS GIS Cut Line= 3
      2708058.50      6839849.79      2708039.39      6840272.91
      2708042.95      6840945.45
#Sta/Elev= 30
  4588.6  379.22  4699.9  376.31  4754.9  373.61  4770.0  372.04  4940.4  361.66
  4980.8  359.44  5000.2  354.58  5006.6  350.02  5006.9  349.52  5010.8  350.02
  5040.2  355.26  5060.2  354.61  5090.2  357.46  5120.2  357.02  5160.2  357.81
  5170.2  357.07  5250.2  358.12  5280.2  356.98  5290.2  357.79  5310.2  357.04
  5344.9  357.79  5420.2  358.45  5450.2  361.24  5480.2  365.22  5510.2  365.53
  5540.3  367.36  5600.3  367.83  5610.3  369.11  5670.3  369.90  5684.7  371.05
#Mann=5,-1,0
  4588.6    0.05       0  4940.4     0.1       0  5006.6    0.07       0
  5010.8     0.1       0  5344.9    0.12       0
Bank Sta=5006.6,5010.8
Exp/Cntr=0.3,0.1

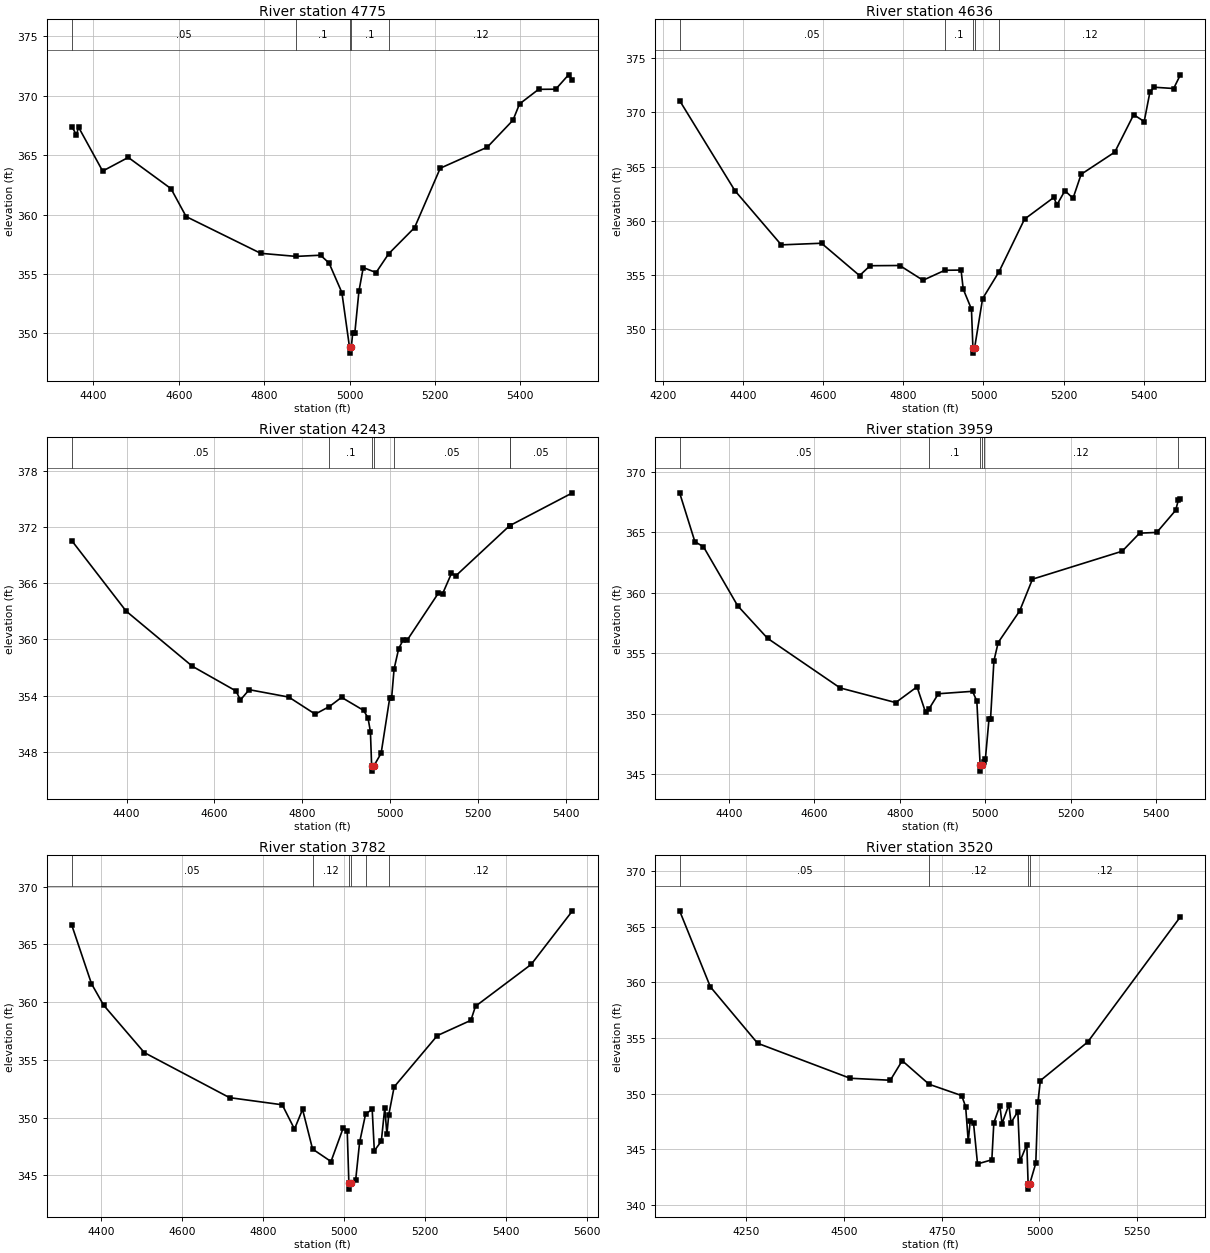
Type RM Length L Ch R = 1,4775,139,139,139
BEGIN DESCRIPTION:
Lacy 173 453
END DESCRIPTION:
XS GIS Cut Line= 3
      2707790.42      6839858.60      2707816.37      6840516.73
      2707848.78      6841030.16
#Sta/Elev= 30
  4349.0  367.41  4360.1  366.72  4365.1  367.35  4421.5  363.66  4481.5  364.81
  4581.6  362.18  4617.1  359.83  4791.7  356.74  4874.7  356.48  4931.9  356.58
  4951.9  355.92  4981.9  353.44  4999.8  348.84  5000.1  348.34  5004.0  348.84
  5007.3  350.05  5012.3  350.05  5021.9  353.56  5032.0  355.54  5062.0  355.12
  5091.5  356.70  5152.2  358.90  5212.3  363.90  5322.5  365.67  5382.7  367.94
  5398.1  369.31  5442.8  370.54  5482.9  370.55  5512.9  371.76  5522.1  371.34
#Mann=5,-1,0
  4349.0    0.05       0  4874.7     0.1       0  4999.8    0.07       0
  5004.0     0.1       0  5091.5    0.12       0
Bank Sta=4999.8,5004
Exp/Cntr=0.3,0.1

Type RM Length L Ch R = 1,4636,393,393,393
BEGIN DESCRIPTION:
Lacy 173 454
END DESCRIPTION:
XS GIS Cut Line= 3
      2707469.37      6839840.08      2707708.26      6840558.85
      2707772.69      6841046.48
#Sta/Elev= 30
  4241.9  371.08  4379.9  362.78  4495.6  357.79  4595.9  357.94  4690.8  354.96
  4717.1  355.87  4791.1  355.89  4849.1  354.53  4903.5  355.45  4944.1  355.47
  4949.4  353.72  4970.0  351.87  4973.6  348.32  4974.0  347.82  4977.9  348.32
  4997.8  352.84  5038.7  355.31  5102.4  360.16  5175.5  362.16  5183.1  361.47
  5203.2  362.78  5223.4  362.08  5243.6  364.29  5327.5  366.33  5374.7  369.78
  5400.9  369.15  5415.1  371.84  5425.1  372.31  5474.4  372.19  5491.2  373.45
#Mann=5,-1,0
  4241.9    0.05       0  4903.5     0.1       0  4973.6    0.07       0
  4977.9     0.1       0  5038.7    0.12       0
Bank Sta=4973.6,4977.9
Exp/Cntr=0.3,0.1

Type RM Length L Ch R = 1,4243,284,284,284
BEGIN DESCRIPTION:
Lacy 173 440
END DESCRIPTION:
XS GIS Cut Line= 3
      2707424.18      6839887.33      2707388.68      6840614.72
      2707379.30      6841026.46
#Sta/Elev= 30
  4275.0  370.56  4398.8  363.03  4549.7  357.13  4649.1  354.49  4659.1  353.53
  4679.1  354.63  4769.3  353.84  4829.3  352.02  4861.7  352.83  4889.4  353.81
  4939.5  352.42  4949.5  351.63  4955.1  350.15  4957.9  346.43  4958.3  345.93
  4962.2  346.43  4979.5  347.84  4998.9  353.70  5003.3  353.70  5009.0  356.85
  5019.5  359.02  5029.5  359.93  5039.5  359.97  5109.6  364.93  5119.6  364.90
  5139.6  367.05  5149.6  366.80  5272.0  372.15  5272.6  372.16  5415.1  375.66
#Mann=7,-1,0
  4275.0    0.05       0  4861.7     0.1       0  4957.9    0.07       0
  4962.2     0.1       0  5009.0    0.05       0  5272.0    0.12       0
  5272.6    0.05       0
Bank Sta=4957.9,4962.2
Exp/Cntr=0.3,0.1

Type RM Length L Ch R = 1,3959,177,177,177
BEGIN DESCRIPTION:
Lacy 173 439
END DESCRIPTION:
XS GIS Cut Line= 3
      2707115.14      6839895.19      2707104.86      6840623.11
      2707142.03      6841066.06
#Sta/Elev= 30
  4284.6  368.25  4320.4  364.21  4340.4  363.80  4420.4  358.93  4490.4  356.24
  4660.4  352.14  4790.5  350.93  4840.5  352.23  4860.5  350.12  4868.4  350.40
  4890.5  351.66  4970.5  351.86  4980.5  351.05  4988.3  345.77  4988.7  345.27
  4992.7  345.77  4996.3  346.00  5000.5  346.26  5009.0  349.57  5012.6  349.57
  5020.5  354.37  5030.5  355.89  5080.7  358.49  5110.8  361.12  5320.9  363.43
  5361.7  364.92  5401.8  364.98  5445.9  366.80  5452.5  367.66  5457.1  367.71
#Mann=6,-1,0
  4284.6    0.05       0  4868.4     0.1       0  4988.3    0.07       0
  4992.7     0.1       0  4996.3    0.12       0  5452.5    0.05       0
Bank Sta=4988.3,4992.7
Exp/Cntr=0.3,0.1

Type RM Length L Ch R = 1,3782,262,262,262
BEGIN DESCRIPTION:
Lacy 173 438
END DESCRIPTION:
XS GIS Cut Line= 3
      2706999.00      6839892.24      2706941.99      6840578.53
      2707121.84      6841097.50
#Sta/Elev= 30
  4327.1  366.68  4376.0  361.59  4406.1  359.73  4506.5  355.63  4717.2  351.73
  4847.6  351.11  4877.8  349.01  4897.8  350.71  4922.5  347.28  4968.1  346.20
  4998.2  349.10  5008.2  348.84  5012.3  344.31  5012.7  343.81  5016.7  344.31
  5029.0  344.58  5038.8  347.86  5053.6  350.31  5069.9  350.72  5075.2  347.13
  5092.5  347.96  5101.0  350.85  5106.3  348.55  5110.7  350.21  5124.2  352.66
  5230.9  357.10  5313.8  358.42  5325.3  359.64  5462.9  363.26  5565.0  367.90
#Mann=6,-1,0
  4327.1    0.05       0  4922.5    0.12       0  5012.3    0.07       0
  5016.7    0.12       0  5053.6     0.1       0  5110.7    0.12       0
Bank Sta=5012.3,5016.7
Exp/Cntr=0.3,0.1

Type RM Length L Ch R = 1,3520,217,217,217
BEGIN DESCRIPTION:
Lacy 173 437
END DESCRIPTION:
XS GIS Cut Line= 3
      2706964.30      6839899.58      2706828.54      6840702.84
      2707023.94      6841126.28
#Sta/Elev= 30
  4079.5  366.45  4158.1  359.61  4279.0  354.53  4515.6  351.38  4618.5  351.20
  4648.9  352.96  4717.6  350.84  4801.0  349.82  4811.2  348.82  4817.8  345.71
  4822.9  347.55  4831.4  347.32  4841.6  343.67  4878.2  344.04  4883.3  347.38
  4898.8  348.90  4904.3  347.30  4921.8  349.00  4927.3  347.38  4944.7  348.38
  4950.2  343.90  4967.7  345.41  4971.0  341.90  4971.4  341.40  4975.4  341.90
  4990.6  343.73  4996.1  349.23  5002.3  351.17  5123.4  354.64  5360.5  365.91
#Mann=4,-1,0
  4079.5    0.05       0  4717.6    0.12       0  4971.0    0.07       0
  4975.4    0.12       0
Bank Sta=4971,4975.4
Exp/Cntr=0.3,0.1

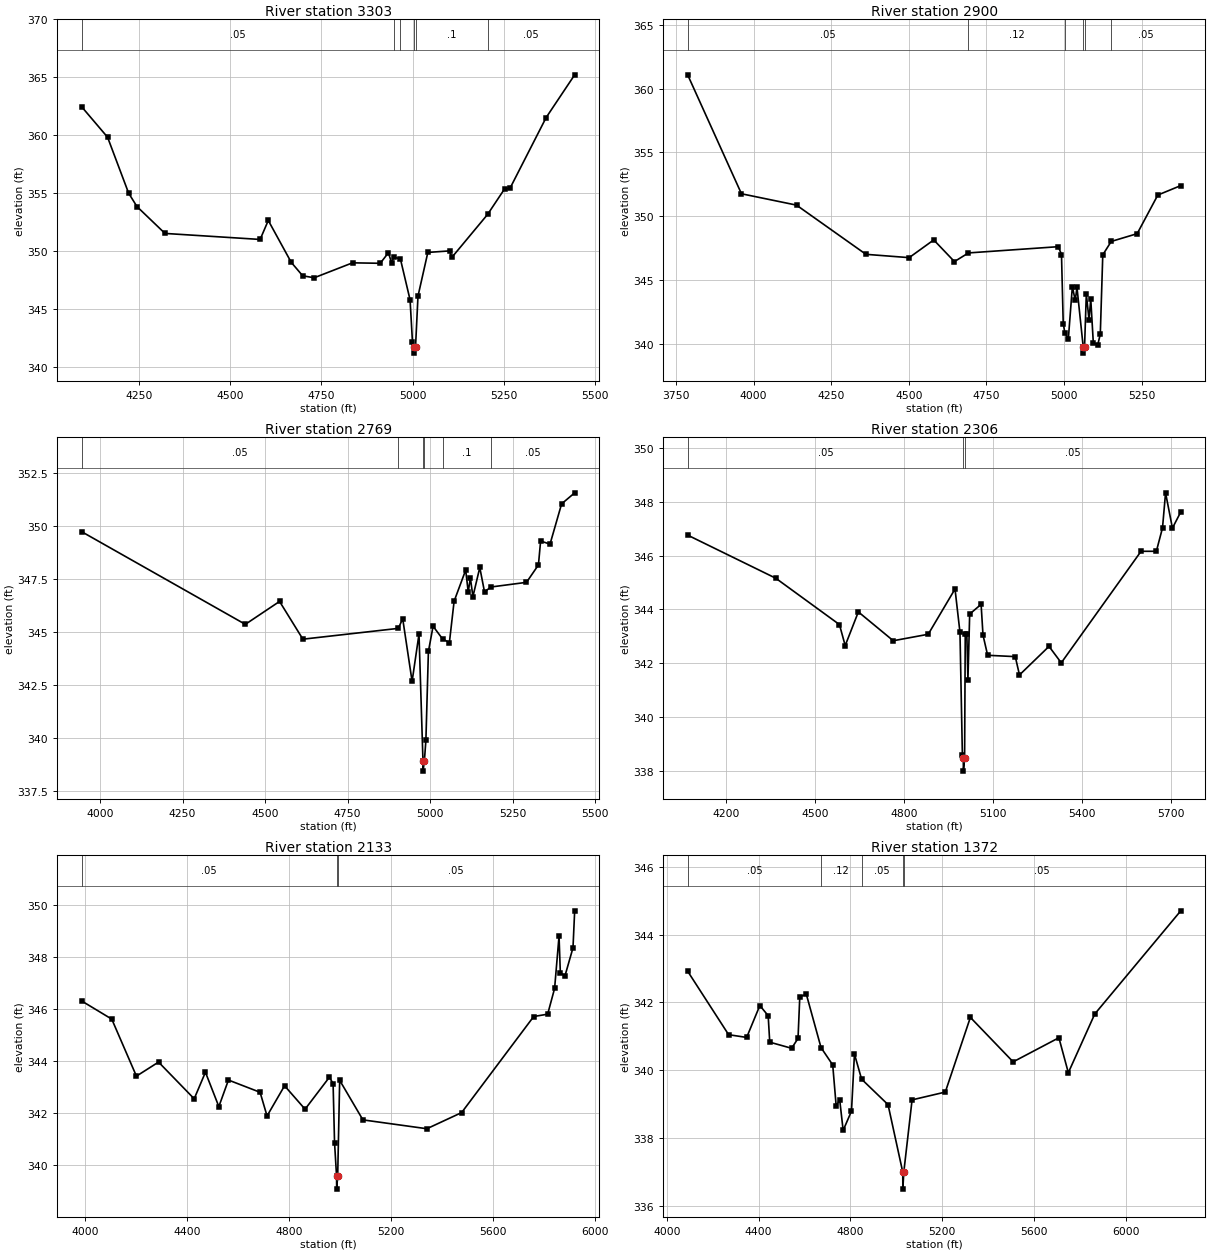
Type RM Length L Ch R = 1,3303,403,403,403
BEGIN DESCRIPTION:
Lacy 173 463
END DESCRIPTION:
XS GIS Cut Line= 3
      2706903.34      6839947.07      2706641.54      6840723.01
      2706937.44      6841166.43
#Sta/Elev= 30
  4092.4  362.47  4163.7  359.83  4221.4  355.00  4244.3  353.84  4321.1  351.52
  4582.0  351.00  4604.3  352.64  4667.3  349.02  4698.7  347.86  4730.2  347.69
  4835.3  348.98  4911.3  348.94  4933.7  349.85  4942.7  348.96  4947.9  349.45
  4966.4  349.34  4993.1  345.78  4999.7  342.12  5003.6  341.68  5004.0  341.18
  5008.0  341.68  5014.8  346.10  5041.8  349.88  5101.3  350.01  5107.9  349.46
  5205.6  353.16  5252.1  355.36  5267.1  355.42  5366.2  361.53  5444.4  365.22
#Mann=6,-1,0
  4092.4    0.05       0  4947.9    0.12       0  4966.4     0.1       0
  5003.6    0.07       0  5008.0     0.1       0  5205.6    0.05       0
Bank Sta=5003.6,5008
Exp/Cntr=0.3,0.1

Type RM Length L Ch R = 1,2900,131,131,131
BEGIN DESCRIPTION:
Lacy 173 465
END DESCRIPTION:
XS GIS Cut Line= 3
      2706837.28      6839949.26      2706428.24      6841010.15
      2706635.03      6841411.39
#Sta/Elev= 30
  3787.7  361.08  3961.0  351.75  4138.3  350.86  4362.0  347.00  4501.2  346.74
  4580.4  348.13  4647.0  346.43  4692.2  347.11  4981.9  347.60  4991.9  346.98
  4997.5  341.57  5003.1  340.80  5014.0  340.38  5026.9  344.46  5036.2  343.39
  5041.8  344.40  5061.8  339.75  5062.2  339.25  5066.2  339.75  5071.9  343.90
  5080.5  341.88  5086.2  343.48  5094.4  340.06  5108.3  339.86  5116.9  340.74
  5124.9  346.96  5152.1  348.01  5235.7  348.62  5302.2  351.65  5376.1  352.39
#Mann=6,-1,0
  3787.7    0.05       0  4692.2    0.12       0  5003.1     0.1       0
  5061.8    0.07       0  5066.2     0.1       0  5152.1    0.05       0
Bank Sta=5061.8,5066.2
Exp/Cntr=0.3,0.1

Type RM Length L Ch R = 1,2769,463,463,463
BEGIN DESCRIPTION:
Lacy 173 464
END DESCRIPTION:
XS GIS Cut Line= 3
      2706377.06      6840096.37      2706254.91      6841009.67
      2706629.92      6841442.47
#Sta/Elev= 30
  3944.1  349.72  4440.3  345.35  4544.0  346.43  4614.7  344.65  4904.0  345.16
  4917.1  345.62  4945.6  342.66  4966.5  344.89  4978.5  338.93  4978.9  338.43
  4982.9  338.93  4987.4  339.88  4995.0  344.07  5009.2  345.26  5038.0  344.66
  5058.6  344.49  5072.9  346.44  5108.0  347.91  5115.6  346.88  5122.2  347.53
  5129.9  346.66  5150.7  348.03  5165.0  346.88  5184.3  347.11  5292.2  347.33
  5328.4  348.15  5335.0  349.28  5363.5  349.13  5398.6  351.03  5438.2  351.55
#Mann=6,-1,0
  3944.1    0.05       0  4904.0    0.12       0  4978.5    0.07       0
  4982.9    0.12       0  5038.0     0.1       0  5184.3    0.05       0
Bank Sta=4978.5,4982.9
Exp/Cntr=0.3,0.1

Type RM Length L Ch R = 1,2306,173,173,173
BEGIN DESCRIPTION:
Lacy 173 3412
END DESCRIPTION:
XS GIS Cut Line= 4
      2706241.15      6840343.53      2705907.87      6841219.38
      2705937.24      6841276.88      2706575.49      6841443.82
#Sta/Elev= 30
  4070.4  346.76  4367.3  345.16  4581.8  343.44  4601.2  342.66  4645.5  343.91
  4763.2  342.84  4880.9  343.08  4971.2  344.76  4987.9  343.15  4996.0  338.61
  4999.1  338.50  4999.5  338.00  5003.5  338.50  5005.7  343.10  5011.0  343.10
  5014.7  341.38  5020.6  343.83  5059.1  344.19  5065.5  343.05  5081.1  342.30
  5174.2  342.25  5188.4  341.57  5287.9  342.63  5329.2  342.02  5598.0  346.16
  5649.6  346.16  5670.3  347.03  5680.6  348.33  5703.7  347.02  5731.8  347.62
#Mann=3,-1,0
  4070.4    0.05       0  4999.1    0.04       0  5003.5    0.05       0
Bank Sta=4999.1,5003.5
Exp/Cntr=0.3,0.1

Type RM Length L Ch R = 1,2133,761,761,761
BEGIN DESCRIPTION:
Lacy 173 3413
END DESCRIPTION:
XS GIS Cut Line= 4
      2706196.74      6840368.39      2705744.74      6841166.59
      2705758.79      6841319.31      2706602.95      6841498.31
#Sta/Elev= 30
  3987.4  346.30  4105.8  345.60  4202.5  343.41  4289.2  343.95  4429.0  342.54
  4473.1  343.56  4525.7  342.24  4563.3  343.26  4687.4  342.79  4714.7  341.88
  4783.4  343.04  4863.8  342.14  4959.3  343.37  4973.7  343.12  4979.4  340.85
  4987.3  339.57  4987.7  339.07  4991.7  339.57  4999.5  343.25  5090.6  341.73
  5341.4  341.39  5477.7  342.01  5760.3  345.70  5815.1  345.79  5842.3  346.78
  5859.7  348.79  5864.8  347.37  5883.2  347.27  5914.4  348.34  5921.0  349.76
#Mann=3,-1,0
  3987.4    0.05       0  4987.3    0.04       0  4991.7    0.05       0
Bank Sta=4987.3,4991.7
Exp/Cntr=0.3,0.1

Type RM Length L Ch R = 1,1372,490,490,490
BEGIN DESCRIPTION:
Lacy 173 3414
END DESCRIPTION:
XS GIS Cut Line= 4
      2705710.79      6840540.68      2705240.64      6841268.79
      2705249.01      6841382.63      2706399.26      6841579.28
#Sta/Elev= 30
  4090.8  342.92  4269.3  341.05  4347.8  340.97  4405.2  341.91  4441.5  341.61
  4448.3  340.83  4543.5  340.65  4571.5  340.94  4579.2  342.17  4607.8  342.24
  4671.7  340.67  4722.6  340.16  4737.8  338.94  4752.9  339.14  4768.1  338.23
  4804.4  338.80  4817.3  340.48  4848.4  339.74  4963.6  338.99  5027.7  337.00
  5028.1  336.50  5032.2  337.00  5068.3  339.13  5213.0  339.36  5322.2  341.56
  5508.5  340.25  5707.8  340.96  5748.9  339.93  5864.0  341.66  6238.6  344.70
#Mann=5,-1,0
  4090.8    0.05       0  4671.7    0.12       0  4848.4    0.05       0
  5027.7    0.04       0  5032.2    0.05       0
Bank Sta=5027.7,5032.2
Exp/Cntr=0.3,0.1

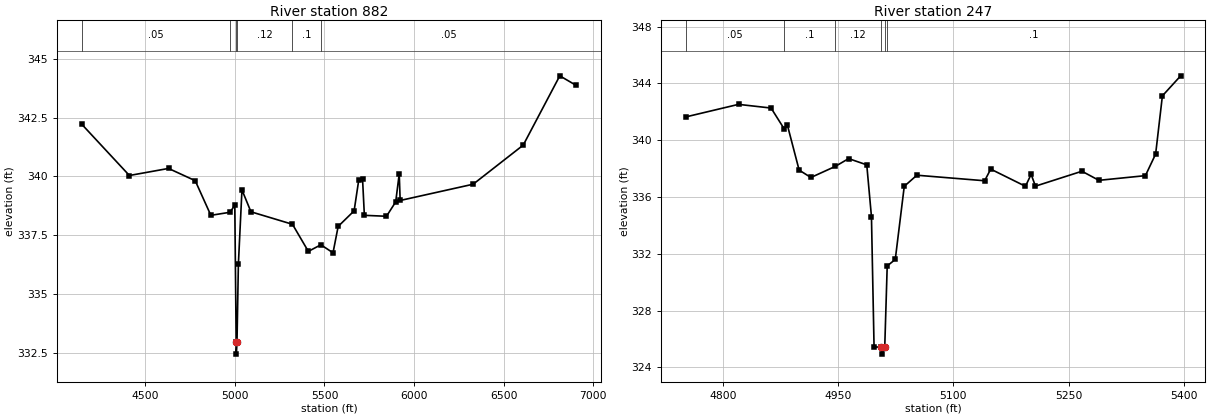
Type RM Length L Ch R = 1,882,635,635,635
BEGIN DESCRIPTION:
Lacy 173 3415
END DESCRIPTION:
XS GIS Cut Line= 4
      2705639.04      6840553.57      2704962.55      6840931.87
      2704987.23      6841467.25      2706395.63      6841806.02
#Sta/Elev= 30
  4145.4  342.22  4411.7  340.04  4630.1  340.34  4779.0  339.82  4866.2  338.35
  4973.2  338.48  4999.7  338.78  5007.5  332.96  5007.9  332.46  5012.0  332.96
  5019.7  336.27  5039.7  339.43  5089.8  338.50  5321.5  337.97  5410.1  336.82
  5480.0  337.10  5547.7  336.76  5576.4  337.88  5665.4  338.54  5691.7  339.87
  5712.5  339.89  5722.6  338.35  5846.0  338.31  5897.4  338.92  5917.1  340.11
  5922.3  338.98  6329.4  339.67  6608.9  341.33  6812.8  344.27  6905.0  343.86
#Mann=6,-1,0
  4145.4    0.05       0  4973.2    0.12       0  5007.5    0.07       0
  5012.0    0.12       0  5321.5     0.1       0  5480.0    0.05       0
Bank Sta=5007.5,5012
Exp/Cntr=0.3,0.1

Type RM Length L Ch R = 1,247,0,0,0
BEGIN DESCRIPTION:
Lacy 173 455
END DESCRIPTION:
XS GIS Cut Line= 3
      2704302.22      6840942.00      2704434.35      6841151.63
      2704784.89      6841335.63
#Sta/Elev= 30
  4752.2  341.65  4820.5  342.53  4862.9  342.27  4880.1  340.79  4884.1  341.07
  4899.4  337.90  4914.7  337.38  4946.4  338.16  4963.8  338.71  4987.4  338.27
  4993.5  334.63  4996.9  325.44  5006.2  325.44  5006.7  324.94  5010.8  325.44
  5014.0  331.15  5024.5  331.61  5036.2  336.76  5052.6  337.54  5140.8  337.15
  5148.7  337.97  5193.9  336.76  5201.3  337.60  5206.9  336.77  5267.4  337.82
  5289.5  337.18  5350.0  337.51  5363.3  339.03  5372.1  343.13  5395.9  344.54
#Mann=6,-1,0
  4752.2    0.05       0  4880.1     0.1       0  4946.4    0.12       0
  5006.2    0.07       0  5010.8    0.12       0  5014.0     0.1       0
Bank Sta=5006.2,5010.8
Exp/Cntr=0.3,0.1

Chan Stop Cuts=-1