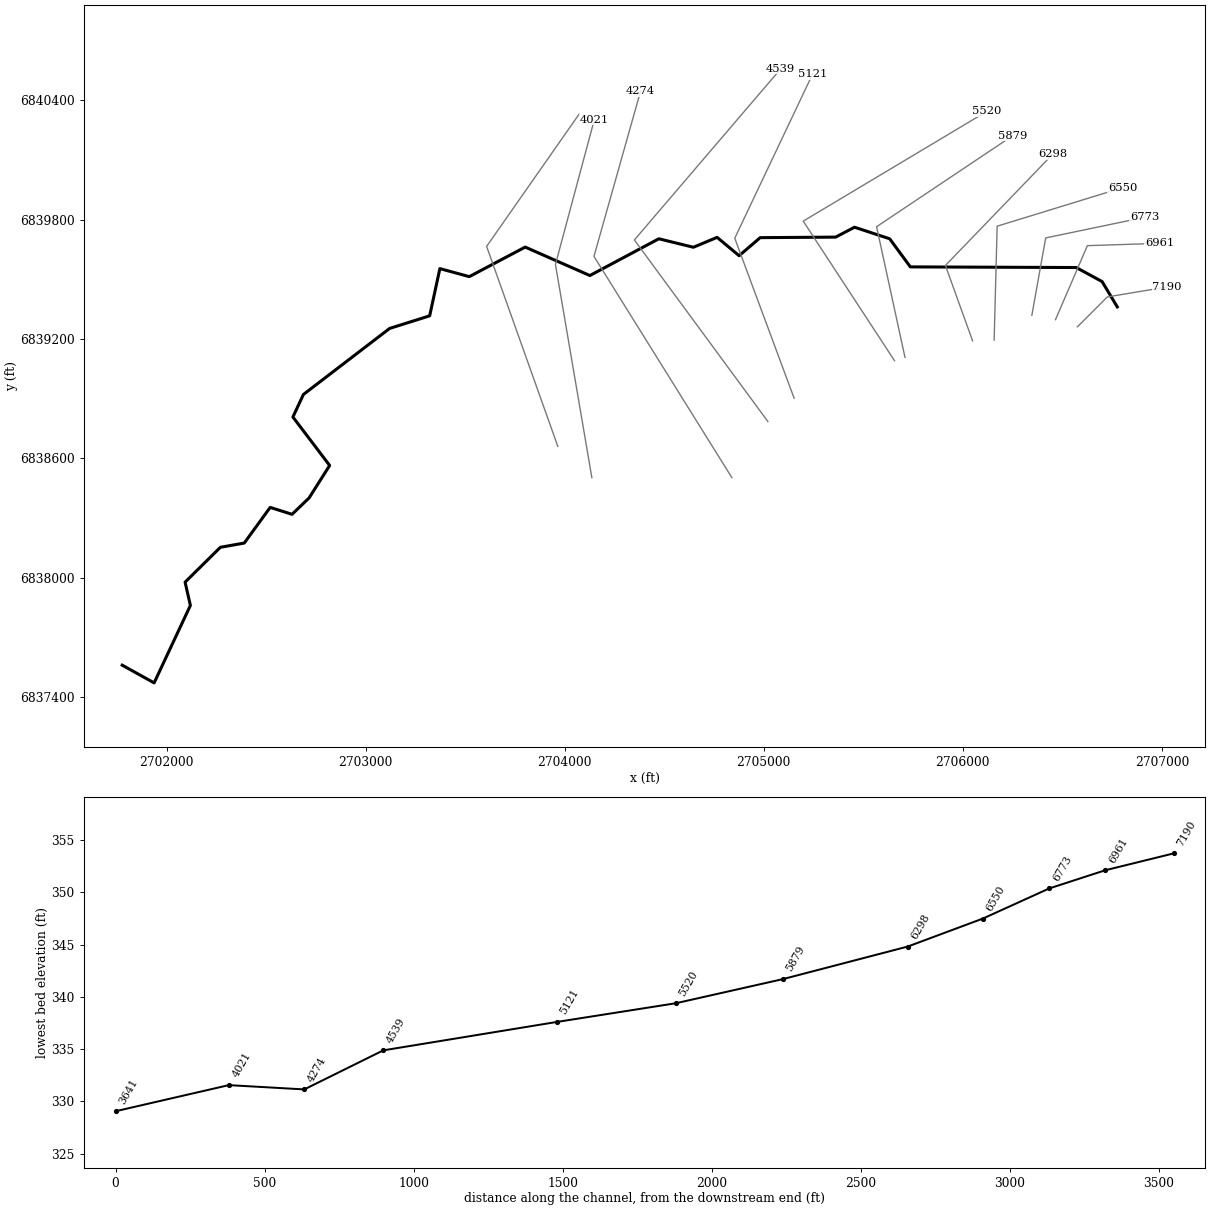
--- Lacy 174.prj (project) ---

Proj Title=Lacy 174 Base Level Engineering
Current Plan=p01
Default Exp/Contr=0.3,0.1
English Units
Geom File=g01
Flow File=f01
Plan File=p01
BEGIN DESCRIPTION:
Lacy 174
END DESCRIPTION:

--- Lacy 174.p01 (plan) ---

Plan Title=Multiple Run
Short Identifier=Multiple
Geom File=g01
Flow File=f01
Subcritical Flow
K Sum by GR= 0
Std Step Tol= 0.01
Critical Tol= 0.01
Num of Std Step Trials= 20
Max Error Tol= 0.3
Flow Tol Ratio= 0.001
Split Flow NTrial= 30
Split Flow Tol= 0.02
Split Flow Ratio= 0.02
Log Output Level= 0
Friction Slope Method= 1
Unsteady Friction Slope Method= 2
Unsteady Bridges Friction Slope Method= 1
Parabolic Critical Depth
Global Vel Dist=  1 , 1 , 1
Global Log Level= 0
CheckData=True
Encroach Param= -1, 0, 0, 0
BEGIN DESCRIPTION:
Multiple Run
END DESCRIPTION:

--- Lacy 174.f01 (steady flow) ---

Flow Title=Multiple
Number of Profiles=7
Profile Names=10-year,25-year,50-year,1pct_min,100-year,1pct_plu,500-year
River Rch & RM= Lacy 174,Reach-1,7190
     341     442     521     306     610    1216     832
Boundary for River Rch & Prof#=Lacy 174,Reach-1,1
Up Type=0
Dn Type=3
Dn Slope=0.005
Boundary for River Rch & Prof#=Lacy 174,Reach-1,2
Up Type=0
Dn Type=3
Dn Slope=0.005
Boundary for River Rch & Prof#=Lacy 174,Reach-1,3
Up Type=0
Dn Type=3
Dn Slope=0.005
Boundary for River Rch & Prof#=Lacy 174,Reach-1,4
Up Type=0
Dn Type=3
Dn Slope=0.005
Boundary for River Rch & Prof#=Lacy 174,Reach-1,5
Up Type=0
Dn Type=3
Dn Slope=0.005
Boundary for River Rch & Prof#=Lacy 174,Reach-1,6
Up Type=0
Dn Type=3
Dn Slope=0.005
Boundary for River Rch & Prof#=Lacy 174,Reach-1,7
Up Type=0
Dn Type=3
Dn Slope=0.005

--- Lacy 174.g01 (geometry) ---

Geom Title=Existing Conditions

River Reach=Lacy 174,Reach-1
Reach XY= 30
      2706776.00      6839361.00      2706699.86      6839488.17
      2706570.07      6839558.76      2705736.28      6839561.99
      2705632.45      6839703.25      2705455.82      6839761.28
      2705360.79      6839711.54      2704981.85      6839708.92
      2704876.00      6839618.10      2704765.38      6839710.39
      2704646.14      6839660.62      2704472.58      6839703.18
      2704126.01      6839518.53      2703801.04      6839661.49
      2703520.10      6839512.98      2703372.29      6839553.32
      2703320.97      6839316.08      2703119.94      6839252.86
      2702686.61      6838921.00      2702633.78      6838807.60
      2702818.39      6838564.33      2702715.22      6838401.28
      2702629.42      6838318.81      2702519.67      6838353.62
      2702389.33      6838174.39      2702269.55      6838153.25
      2702092.08      6837978.05      2702118.65      6837860.97
      2701936.43      6837471.92      2701776.00      6837561.00

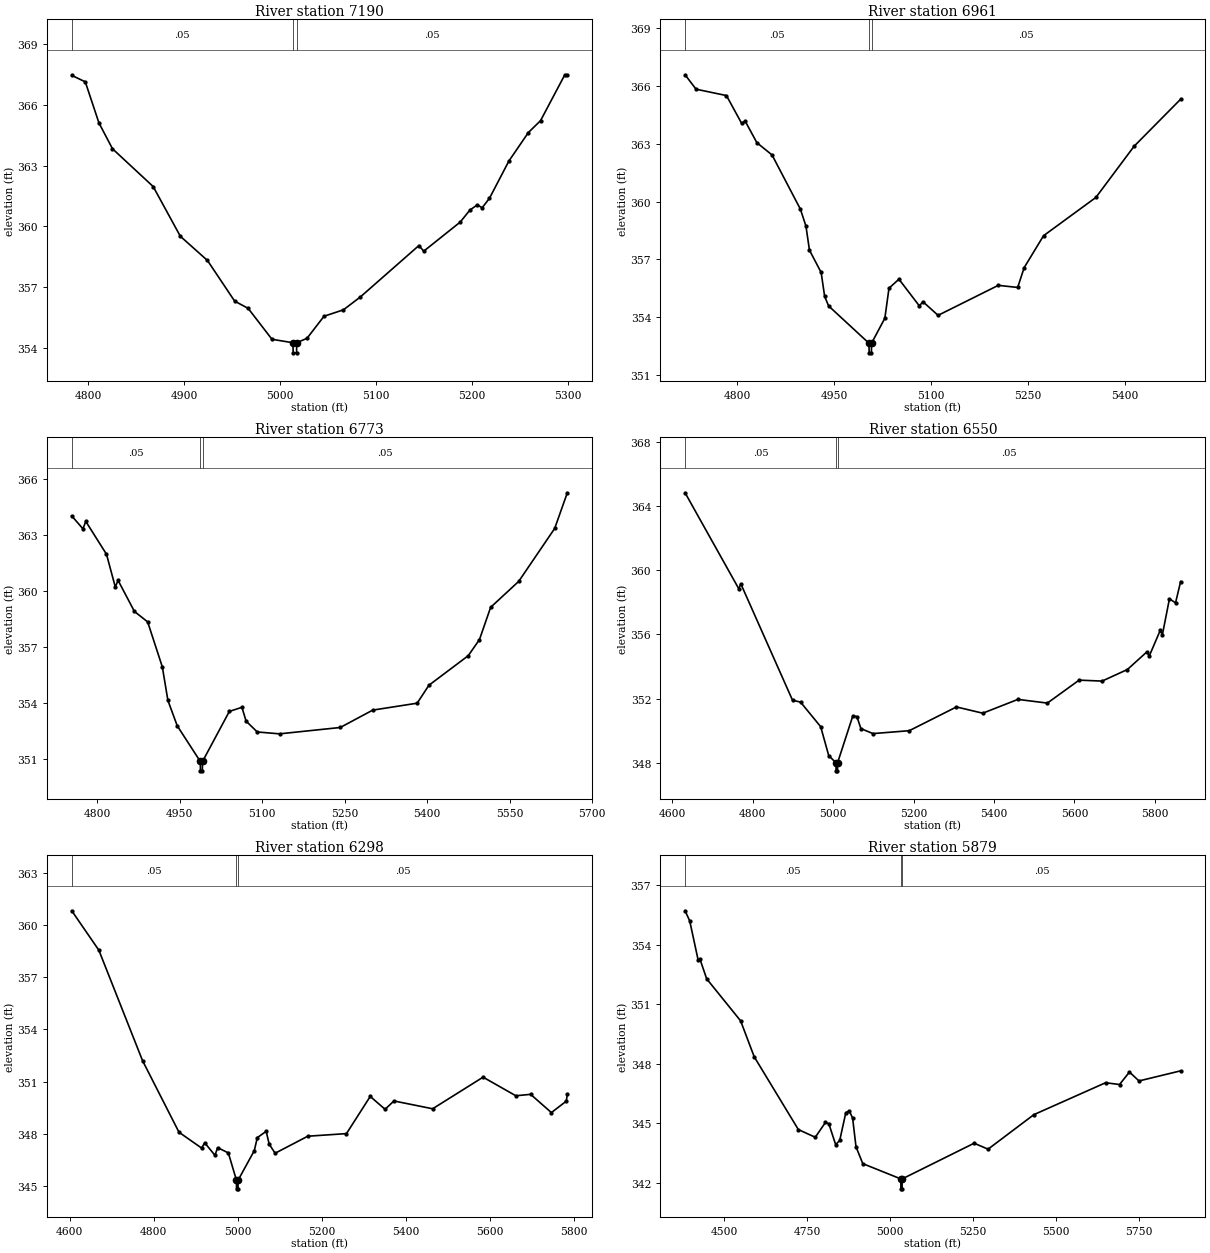
Type RM Length L Ch R = 1,7190,229,229,229
BEGIN DESCRIPTION:
Lacy 174 50
END DESCRIPTION:
XS GIS Cut Line= 3
      2706576.00      6839261.00      2706726.00      6839411.00
      2707026.03      6839461.01
#Sta/Elev= 30
  4782.9  367.47  4797.0  367.15  4811.2  365.12  4825.3  363.84  4867.7  361.97
  4896.0  359.51  4924.3  358.31  4952.6  356.30  4966.7  355.94  4991.5  354.41
  5013.3  354.24  5013.6  353.74  5017.1  353.74  5017.3  354.24  5028.0  354.46
  5045.7  355.55  5066.0  355.87  5083.7  356.51  5144.6  359.05  5149.6  358.77
  5187.6  360.21  5197.8  360.81  5205.4  361.06  5210.5  360.92  5218.1  361.39
  5238.3  363.23  5258.6  364.64  5271.3  365.23  5296.6  367.50  5299.2  367.50
#Mann=3,-1,0
  4782.9    0.05       0  5013.3    0.04       0  5017.3    0.05       0
Bank Sta=5013.3,5017.3
Exp/Cntr=0.3,0.1

Type RM Length L Ch R = 1,6961,188,188,188
BEGIN DESCRIPTION:
Lacy 174 3416
END DESCRIPTION:
XS GIS Cut Line= 3
      2706465.71      6839297.06      2706625.89      6839668.65
      2706988.06      6839680.38
#Sta/Elev= 30
  4719.1  366.59  4736.1  365.84  4783.1  365.51  4806.7  364.06  4812.1  364.18
  4830.2  363.06  4853.7  362.42  4897.6  359.60  4906.2  358.72  4911.6  357.47
  4929.7  356.31  4935.1  355.07  4941.2  354.57  5003.7  352.63  5004.0  352.13
  5007.5  352.13  5007.7  352.63  5028.3  353.93  5034.7  355.49  5050.1  355.96
  5081.7  354.57  5087.2  354.79  5110.7  354.08  5203.9  355.64  5233.9  355.53
  5243.9  356.56  5273.9  358.22  5354.9  360.21  5414.0  362.87  5486.1  365.32
#Mann=3,-1,0
  4719.1    0.05       0  5003.7    0.04       0  5007.7    0.05       0
Bank Sta=5003.7,5007.7
Exp/Cntr=0.3,0.1

Type RM Length L Ch R = 1,6773,223,223,223
BEGIN DESCRIPTION:
Lacy 174 3417
END DESCRIPTION:
XS GIS Cut Line= 3
      2706346.90      6839318.81      2706416.44      6839707.47
      2706912.54      6839810.90
#Sta/Elev= 30
  4753.4  364.03  4773.8  363.34  4778.9  363.74  4816.6  361.98  4832.6  360.23
  4837.7  360.58  4867.4  358.92  4891.5  358.36  4918.2  355.95  4928.3  354.16
  4945.3  352.80  4987.3  350.89  4987.5  350.39  4991.0  350.39  4991.3  350.89
  5040.1  353.57  5063.0  353.79  5070.6  353.05  5090.9  352.47  5131.5  352.37
  5241.9  352.71  5301.0  353.64  5381.8  354.01  5403.2  354.97  5474.7  356.55
  5495.1  357.41  5515.5  359.14  5566.6  360.53  5632.0  363.36  5655.0  365.27
#Mann=3,-1,0
  4753.4    0.05       0  4987.3    0.04       0  4991.3    0.05       0
Bank Sta=4987.3,4991.3
Exp/Cntr=0.3,0.1

Type RM Length L Ch R = 1,6550,252,252,252
BEGIN DESCRIPTION:
Lacy 174 3418
END DESCRIPTION:
XS GIS Cut Line= 3
      2706157.44      6839194.13      2706172.52      6839766.43
      2706802.58      6839959.93
#Sta/Elev= 30
  4632.3  364.82  4765.8  358.84  4770.8  359.15  4899.3  351.90  4919.3  351.78
  4969.3  350.25  4989.3  348.45  5007.3  348.00  5007.6  347.50  5011.1  347.50
  5011.3  348.00  5049.3  350.93  5059.3  350.88  5069.3  350.13  5099.3  349.82
  5189.4  350.00  5306.7  351.48  5372.1  351.09  5459.5  351.95  5532.7  351.72
  5611.6  353.15  5668.7  353.09  5731.5  353.81  5780.5  354.92  5785.7  354.64
  5813.2  356.25  5818.4  355.96  5836.1  358.22  5851.2  357.96  5863.9  359.29
#Mann=3,-1,0
  4632.3    0.05       0  5007.3    0.04       0  5011.3    0.05       0
Bank Sta=5007.3,5011.3
Exp/Cntr=0.3,0.1

Type RM Length L Ch R = 1,6298,419,419,419
BEGIN DESCRIPTION:
Lacy 174 3421
END DESCRIPTION:
XS GIS Cut Line= 3
      2706049.11      6839190.34      2705912.67      6839569.12
      2706451.99      6840128.45
#Sta/Elev= 30
  4605.1  360.83  4669.6  358.56  4773.6  352.20  4860.3  348.08  4914.0  347.17
  4921.7  347.47  4945.9  346.75  4952.4  347.19  4977.8  346.89  4997.1  345.32
  4997.3  344.82  5000.8  344.82  5001.1  345.32  5039.6  347.02  5046.8  347.77
  5067.9  348.13  5075.1  347.39  5089.2  346.87  5166.9  347.85  5259.0  348.00
  5315.6  350.14  5350.9  349.40  5372.0  349.88  5464.1  349.43  5584.2  351.25
  5662.1  350.18  5697.4  350.26  5746.8  349.21  5782.3  349.87  5784.7  350.26
#Mann=3,-1,0
  4605.1    0.05       0  4997.1    0.04       0  5001.1    0.05       0
Bank Sta=4997.1,5001.1
Exp/Cntr=0.3,0.1

Type RM Length L Ch R = 1,5879,359,359,359
BEGIN DESCRIPTION:
Lacy 174 3420
END DESCRIPTION:
XS GIS Cut Line= 3
      2705709.42      6839107.34      2705566.68      6839763.86
      2706250.38      6840220.99
#Sta/Elev= 30
  4381.5  355.72  4395.5  355.21  4421.1  353.22  4426.2  353.29  4446.6  352.29
  4549.0  350.17  4589.9  348.36  4723.0  344.69  4774.1  344.30  4804.8  345.05
  4815.1  344.98  4835.5  343.93  4847.8  344.14  4866.2  345.54  4876.5  345.63
  4886.7  345.27  4896.9  343.82  4917.4  342.97  5032.1  342.20  5032.3  341.70
  5035.8  341.70  5036.1  342.20  5253.1  344.00  5295.1  343.70  5433.2  345.44
  5649.5  347.05  5691.5  346.96  5721.5  347.59  5750.2  347.14  5875.8  347.65
#Mann=3,-1,0
  4381.5    0.05       0  5032.1   0.035       0  5036.1    0.05       0
Bank Sta=5032.1,5036.1
Exp/Cntr=0.3,0.1

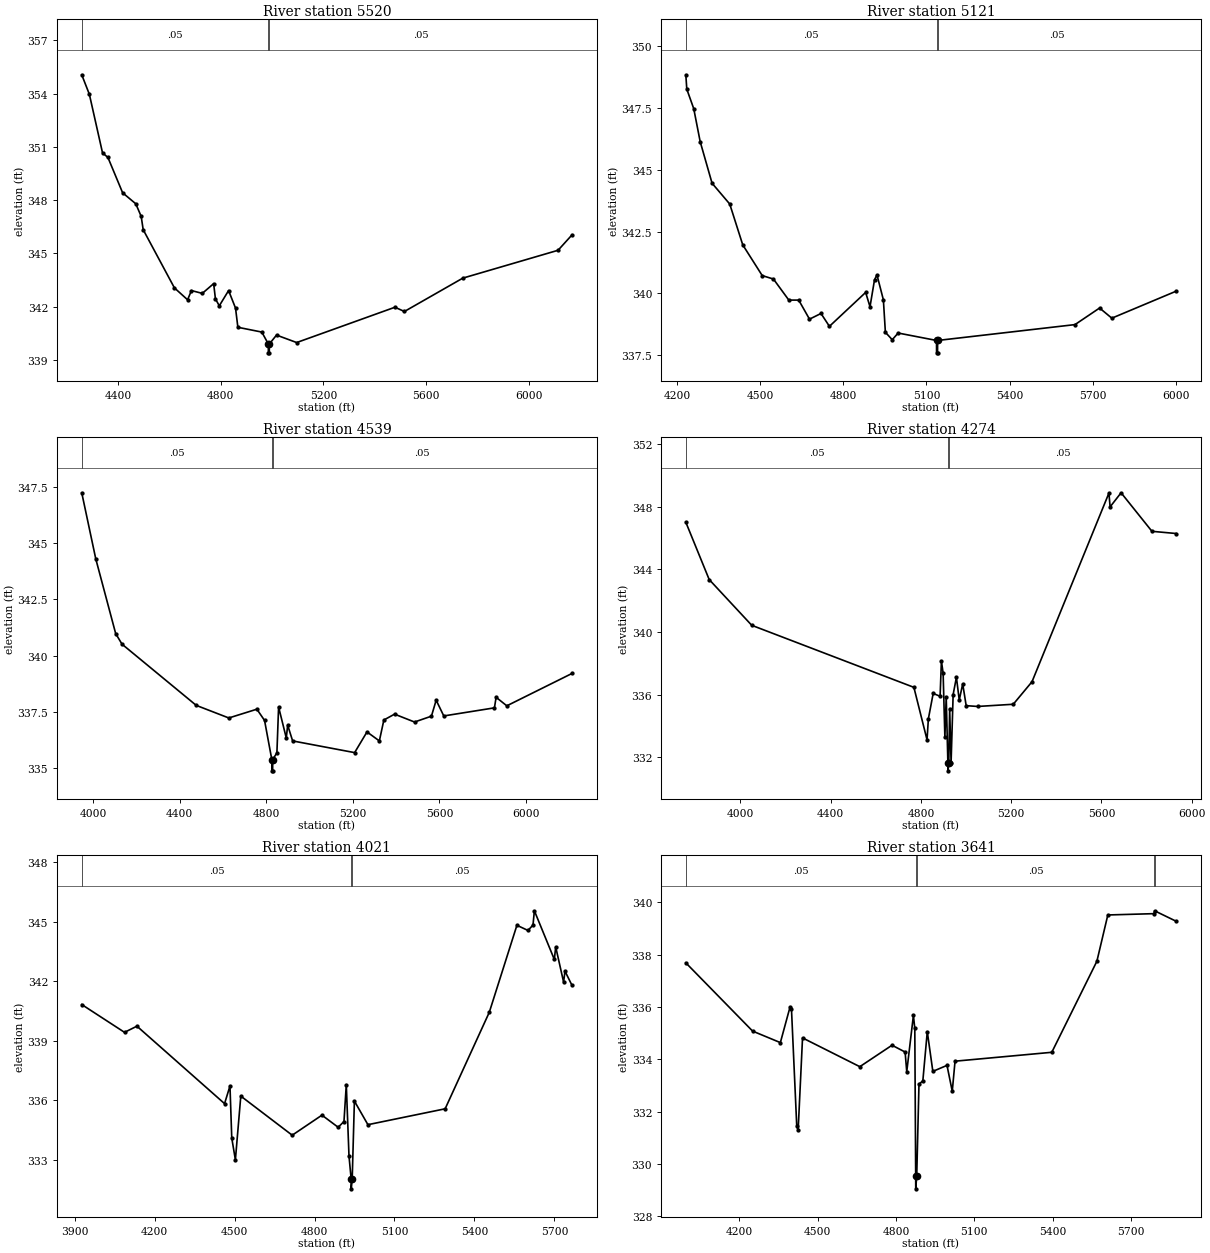
Type RM Length L Ch R = 1,5520,399,399,399
BEGIN DESCRIPTION:
Lacy 174 3419
END DESCRIPTION:
XS GIS Cut Line= 3
      2705656.91      6839090.54      2705198.05      6839791.85
      2706119.79      6840342.71
#Sta/Elev= 30
  4257.9  355.06  4287.6  353.96  4338.9  350.66  4360.0  350.40  4417.3  348.41
  4468.6  347.79  4489.7  347.08  4497.5  346.33  4619.3  343.05  4670.6  342.38
  4685.7  342.90  4727.9  342.74  4772.3  343.29  4779.2  342.43  4794.3  342.04
  4830.5  342.90  4857.6  341.91  4866.7  340.83  4960.1  340.56  4985.4  339.89
  4985.7  339.39  4989.2  339.39  4989.4  339.89  5017.4  340.39  5096.0  339.97
  5479.2  341.96  5516.1  341.72  5743.8  343.60  6115.3  345.17  6169.8  346.04
#Mann=3,-1,0
  4257.9    0.05       0  4985.4    0.04       0  4989.4    0.05       0
Bank Sta=4985.4,4989.4
Exp/Cntr=0.3,0.1

Type RM Length L Ch R = 1,5121,582,582,582
BEGIN DESCRIPTION:
Lacy 174 3422
END DESCRIPTION:
XS GIS Cut Line= 3
      2705152.15      6838902.44      2704854.03      6839706.10
      2705245.17      6840530.66
#Sta/Elev= 30
  4231.5  348.83  4235.0  348.25  4260.1  347.46  4283.3  346.13  4326.2  344.45
  4390.0  343.61  4437.0  341.96  4507.3  340.72  4547.8  340.58  4603.3  339.73
  4639.0  339.73  4677.9  338.96  4719.4  339.19  4749.8  338.67  4880.6  340.04
  4896.3  339.46  4912.6  340.55  4921.4  340.75  4944.6  339.74  4951.8  338.43
  4976.6  338.13  4997.9  338.40  5136.4  338.10  5136.6  337.60  5140.1  337.60
  5140.4  338.10  5636.2  338.74  5725.0  339.41  5769.2  339.00  6001.3  340.09
#Mann=3,-1,0
  4231.5    0.05       0  5136.4    0.04       0  5140.4    0.05       0
Bank Sta=5136.4,5140.4
Exp/Cntr=0.3,0.1

Type RM Length L Ch R = 1,4539,265,265,265
BEGIN DESCRIPTION:
Lacy 174 3423
END DESCRIPTION:
XS GIS Cut Line= 3
      2705020.39      6838785.14      2704349.61      6839697.24
      2705084.94      6840557.10
#Sta/Elev= 30
  3948.6  347.24  4013.4  344.30  4105.3  340.98  4134.6  340.51  4477.2  337.79
  4627.6  337.23  4757.1  337.62  4792.6  337.12  4826.1  335.38  4826.4  334.88
  4829.9  334.88  4830.1  335.38  4849.6  335.68  4857.4  337.72  4892.9  336.34
  4899.3  336.91  4922.2  336.21  5208.4  335.69  5265.5  336.61  5322.6  336.21
  5343.4  337.14  5392.8  337.40  5485.0  337.05  5563.0  337.31  5584.9  338.02
  5620.0  337.32  5853.9  337.68  5861.6  338.15  5911.0  337.77  6212.2  339.21
#Mann=3,-1,0
  3948.6    0.05       0  4826.1    0.04       0  4830.1    0.05       0
Bank Sta=4826.1,4830.1
Exp/Cntr=0.3,0.1

Type RM Length L Ch R = 1,4274,253,253,253
BEGIN DESCRIPTION:
Lacy 174 3424
END DESCRIPTION:
XS GIS Cut Line= 3
      2704839.50      6838503.07      2704146.55      6839614.71
      2704381.02      6840445.84
#Sta/Elev= 30
  3757.7  347.01  3861.3  343.35  4049.9  340.43  4768.7  336.47  4827.0  333.12
  4832.9  334.46  4854.2  336.08  4884.9  335.90  4890.7  338.15  4898.3  337.38
  4906.1  333.27  4912.0  335.86  4919.4  331.64  4919.7  331.14  4923.4  331.64
  4927.3  335.11  4933.6  331.67  4942.7  336.01  4957.2  337.11  4969.8  335.66
  4985.1  336.69  5000.5  335.30  5051.5  335.25  5209.2  335.39  5292.4  336.83
  5633.3  348.87  5638.5  347.99  5687.2  348.89  5824.0  346.43  5931.2  346.29
#Mann=3,-1,0
  3757.7    0.05       0  4919.4    0.04       0  4923.4    0.05       0
Bank Sta=4919.4,4923.4
Exp/Cntr=0.3,0.1

Type RM Length L Ch R = 1,4021,380,380,380
BEGIN DESCRIPTION:
Lacy 174 423
END DESCRIPTION:
XS GIS Cut Line= 3
      2704136.00      6838502.91      2703953.04      6839574.16
      2704148.10      6840300.77
#Sta/Elev= 30
  3926.9  340.83  4087.3  339.43  4133.9  339.74  4462.6  335.84  4482.9  336.73
  4489.6  334.11  4503.2  333.01  4523.5  336.22  4716.3  334.25  4827.9  335.26
  4888.7  334.65  4910.5  334.94  4919.2  336.80  4929.3  333.21  4937.4  332.05
  4937.7  331.55  4941.4  332.05  4949.6  335.97  5000.3  334.78  5290.0  335.58
  5455.6  340.44  5559.2  344.82  5600.6  344.56  5619.5  344.83  5624.7  345.55
  5699.5  343.10  5704.7  343.73  5734.3  341.96  5739.5  342.51  5766.0  341.79
#Mann=3,-1,0
  3926.9    0.05       0  4937.4    0.04       0  4941.4    0.05       0
Bank Sta=4937.4,4941.4
Exp/Cntr=0.3,0.1

Type RM Length L Ch R = 1,3641,0,0,0
BEGIN DESCRIPTION:
Lacy 174 422
END DESCRIPTION:
XS GIS Cut Line= 3
      2703964.95      6838660.09      2703607.21      6839665.02
      2704071.73      6840329.08
#Sta/Elev= 30
  3995.8  337.69  4251.5  335.08  4357.7  334.64  4395.0  336.01  4400.3  335.92
  4420.5  331.44  4425.8  331.29  4442.6  334.82  4661.9  333.72  4785.2  334.54
  4835.3  334.28  4841.6  333.53  4867.1  335.68  4872.4  335.18  4875.8  329.55
  4876.0  329.05  4879.8  329.55  4888.4  333.05  4903.2  333.18  4920.2  335.06
  4941.5  333.54  4995.7  333.77  5015.8  332.78  5026.5  333.93  5396.9  334.27
  5569.5  337.75  5611.4  339.52  5788.6  339.57  5790.3  339.68  5872.9  339.28
#Mann=5,-1,0
  3995.8    0.05       0  4875.8    0.04       0  4879.8    0.05       0
  5788.6    0.12       0  5790.3    0.05       0
Bank Sta=4875.8,4879.8
Exp/Cntr=0.3,0.1

Chan Stop Cuts=-1