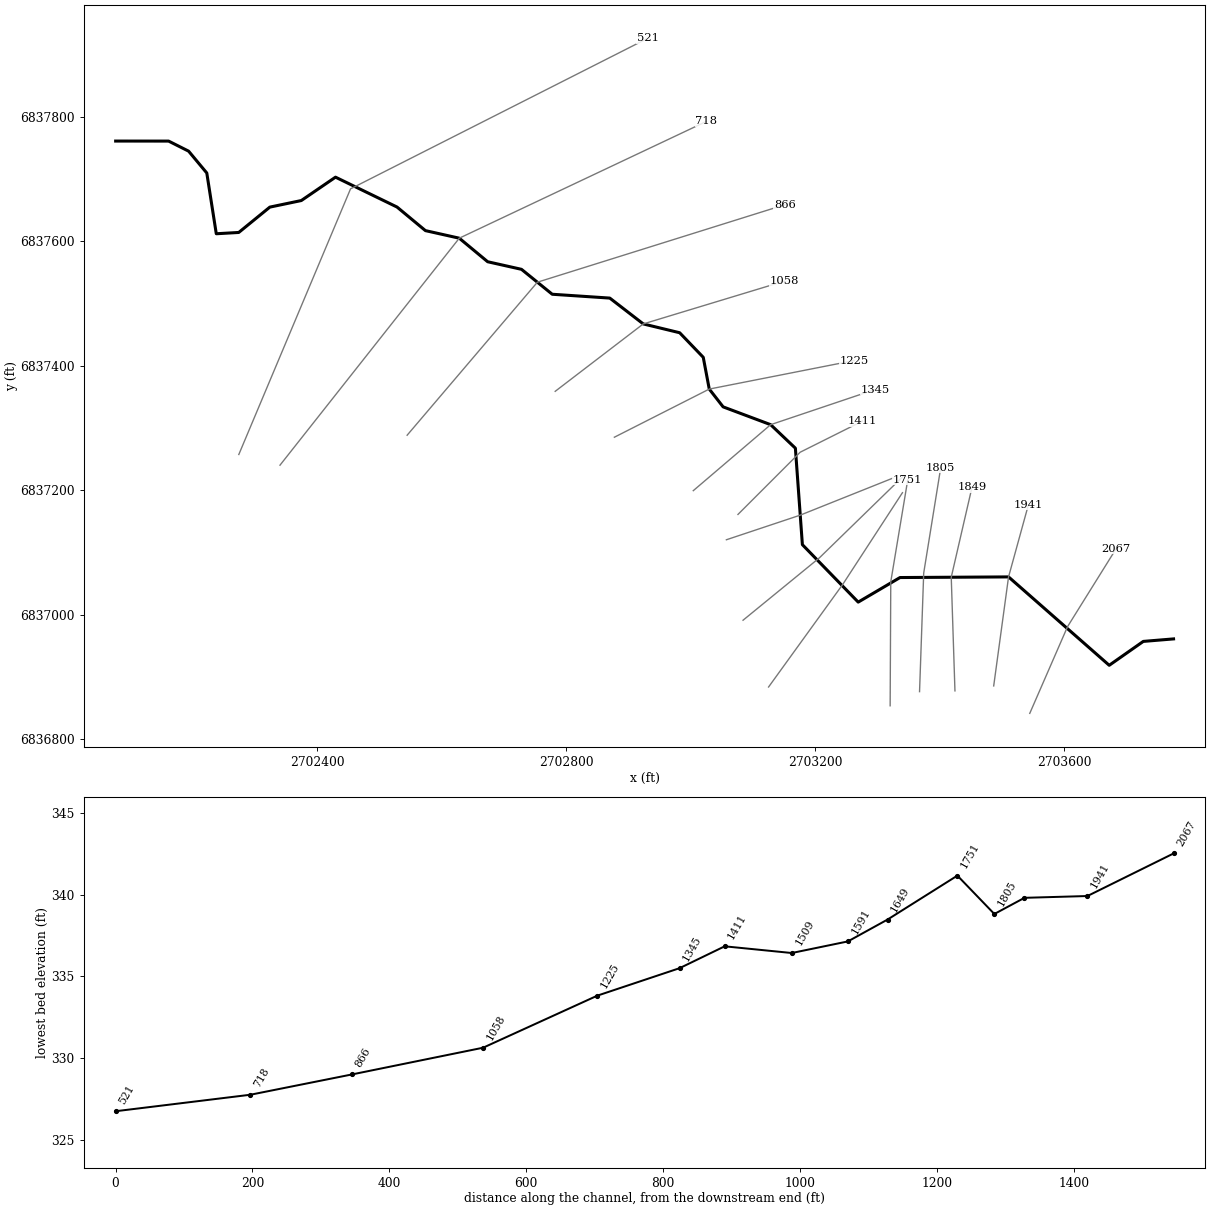
--- Lacy 175.prj (project) ---

Proj Title=Lacy 175 Base Level Engineering
Current Plan=p01
Default Exp/Contr=0.3,0.1
English Units
Geom File=g01
Flow File=f01
Plan File=p01
BEGIN DESCRIPTION:
Lacy 175
END DESCRIPTION:

--- Lacy 175.p01 (plan) ---

Plan Title=Multiple Run
Short Identifier=Multiple
Geom File=g01
Flow File=f01
Subcritical Flow
K Sum by GR= 0
Std Step Tol= 0.01
Critical Tol= 0.01
Num of Std Step Trials= 20
Max Error Tol= 0.3
Flow Tol Ratio= 0.001
Split Flow NTrial= 30
Split Flow Tol= 0.02
Split Flow Ratio= 0.02
Log Output Level= 0
Friction Slope Method= 1
Unsteady Friction Slope Method= 2
Unsteady Bridges Friction Slope Method= 1
Parabolic Critical Depth
Global Vel Dist=  1 , 1 , 1
Global Log Level= 0
CheckData=True
Encroach Param= -1, 0, 0, 0
BEGIN DESCRIPTION:
Multiple Run
END DESCRIPTION:

--- Lacy 175.f01 (steady flow) ---

Flow Title=Multiple
Number of Profiles=7
Profile Names=10-year,25-year,50-year,1pct_min,100-year,1pct_plu,500-year
River Rch & RM= Lacy 175,Reach-1,2067
     283     362     423     246     491     980     661
Boundary for River Rch & Prof#=Lacy 175,Reach-1,1
Up Type=0
Dn Type=3
Dn Slope=0.005
Boundary for River Rch & Prof#=Lacy 175,Reach-1,2
Up Type=0
Dn Type=3
Dn Slope=0.005
Boundary for River Rch & Prof#=Lacy 175,Reach-1,3
Up Type=0
Dn Type=3
Dn Slope=0.005
Boundary for River Rch & Prof#=Lacy 175,Reach-1,4
Up Type=0
Dn Type=3
Dn Slope=0.005
Boundary for River Rch & Prof#=Lacy 175,Reach-1,5
Up Type=0
Dn Type=3
Dn Slope=0.005
Boundary for River Rch & Prof#=Lacy 175,Reach-1,6
Up Type=0
Dn Type=3
Dn Slope=0.005
Boundary for River Rch & Prof#=Lacy 175,Reach-1,7
Up Type=0
Dn Type=3
Dn Slope=0.005

--- Lacy 175.g01 (geometry) ---

Geom Title=Existing Conditions

River Reach=Lacy 175,Reach-1
Reach XY= 30
      2703776.00      6836961.00      2703727.36      6836956.98
      2703672.61      6836918.59      2703510.84      6837060.62
      2703336.43      6837059.61      2703269.24      6837020.12
      2703179.54      6837112.44      2703168.30      6837267.47
      2703128.55      6837305.25      2703052.17      6837333.87
      2703029.90      6837362.46      2703020.24      6837413.51
      2702982.34      6837452.98      2702923.85      6837467.15
      2702870.04      6837508.67      2702777.58      6837514.83
      2702728.18      6837554.88      2702673.80      6837567.08
      2702628.20      6837604.92      2702573.80      6837617.08
      2702528.19      6837654.95      2702429.31      6837702.98
      2702374.36      6837665.42      2702323.77      6837654.85
      2702273.83      6837614.13      2702237.72      6837612.05
      2702222.47      6837709.66      2702193.26      6837744.77
      2702161.12      6837760.95      2702076.00      6837761.00

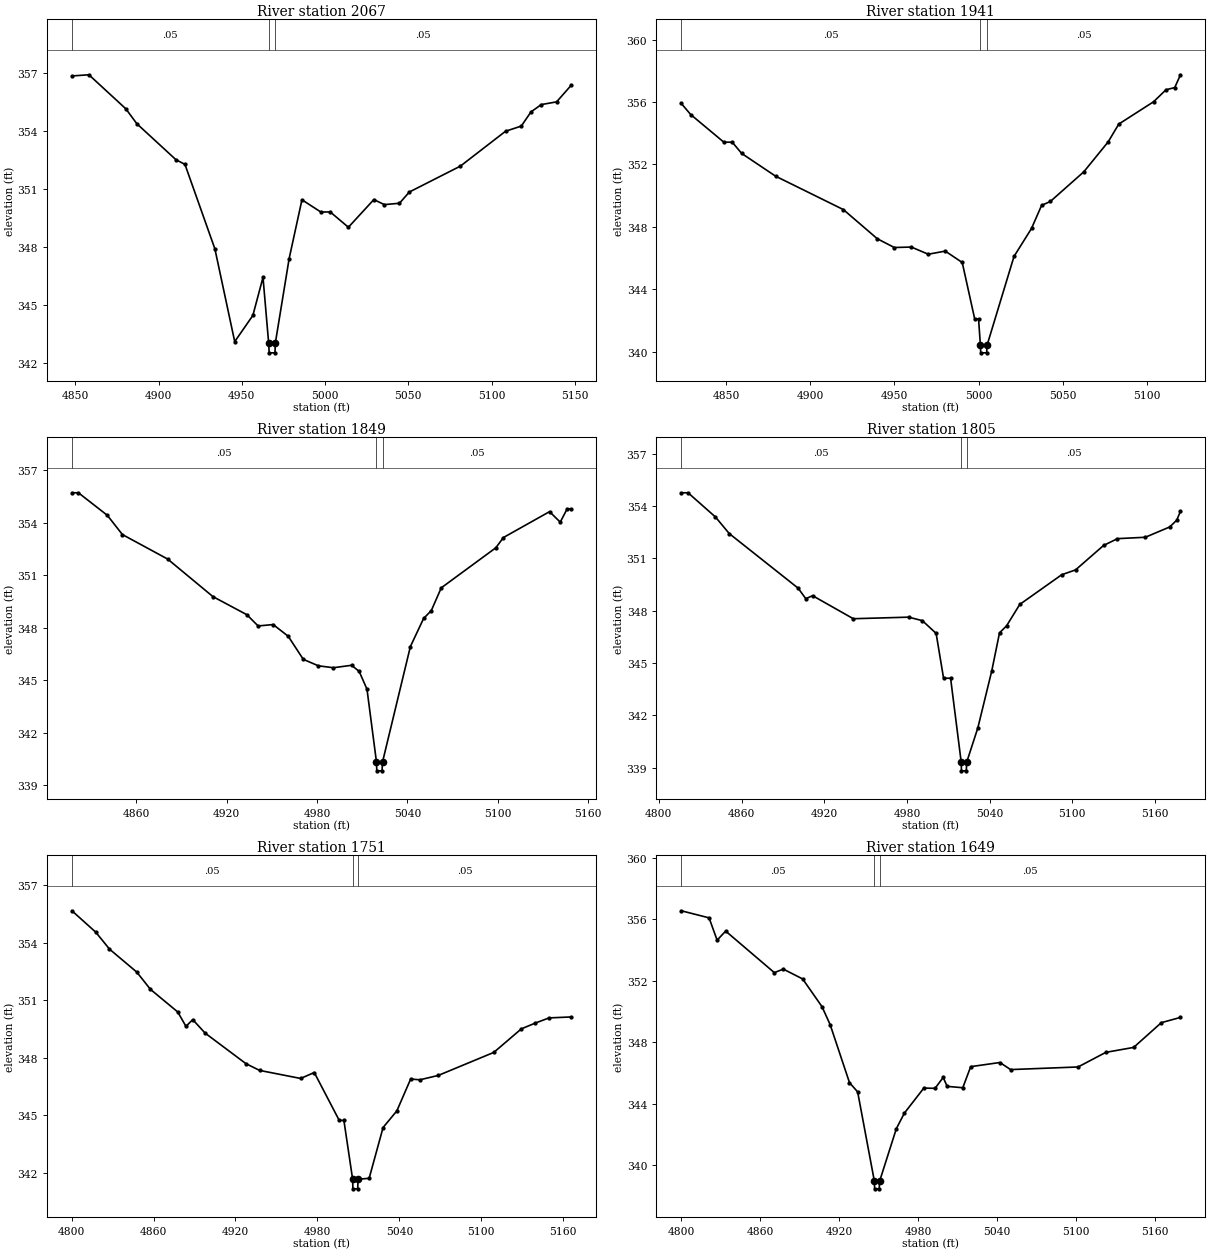
Type RM Length L Ch R = 1,2067,126,126,126
BEGIN DESCRIPTION:
Lacy 175 421
END DESCRIPTION:
XS GIS Cut Line= 3
      2703544.92      6836841.33      2703605.68      6836980.77
      2703683.86      6837106.19
#Sta/Elev= 30
  4847.9  356.84  4858.1  356.90  4880.3  355.14  4886.9  354.37  4910.4  352.51
  4915.8  352.27  4933.8  347.90  4945.7  343.11  4956.6  344.46  4962.7  346.43
  4966.1  343.03  4966.4  342.53  4969.9  342.53  4970.1  343.03  4978.4  347.40
  4986.1  350.44  4997.4  349.81  5003.1  349.81  5014.0  349.02  5029.3  350.45
  5035.6  350.19  5044.7  350.26  5050.6  350.84  5081.3  352.18  5108.4  353.98
  5117.9  354.25  5123.7  354.98  5129.9  355.36  5139.1  355.50  5147.8  356.35
#Mann=3,-1,0
  4847.9    0.05       0  4966.1    0.04       0  4970.1    0.05       0
Bank Sta=4966.1,4970.1
Exp/Cntr=0.3,0.1

Type RM Length L Ch R = 1,1941,92,92,92
BEGIN DESCRIPTION:
Lacy 175 420
END DESCRIPTION:
XS GIS Cut Line= 3
      2703486.97      6836885.44      2703510.84      6837060.62
      2703542.71      6837176.42
#Sta/Elev= 30
  4823.2  355.90  4828.8  355.19  4848.5  353.42  4853.5  353.42  4859.1  352.70
  4879.3  351.24  4919.6  349.10  4939.8  347.23  4949.9  346.67  4960.0  346.70
  4970.1  346.24  4980.2  346.44  4990.3  345.71  4997.7  342.10  5000.0  342.10
  5001.1  340.42  5001.3  339.92  5004.8  339.92  5005.1  340.42  5021.1  346.10
  5031.5  347.89  5037.5  349.37  5042.7  349.62  5062.6  351.52  5077.1  353.44
  5083.4  354.58  5104.1  356.01  5111.5  356.78  5116.7  356.92  5120.1  357.74
#Mann=3,-1,0
  4823.2    0.05       0  5001.1    0.04       0  5005.1    0.05       0
Bank Sta=5001.1,5005.1
Exp/Cntr=0.3,0.1

Type RM Length L Ch R = 1,1849,44,44,44
BEGIN DESCRIPTION:
Lacy 175 419
END DESCRIPTION:
XS GIS Cut Line= 3
      2703424.71      6836877.48      2703418.75      6837060.09
      2703452.17      6837204.98
#Sta/Elev= 30
  4817.3  355.72  4821.6  355.72  4840.8  354.43  4850.8  353.33  4880.8  351.93
  4910.9  349.78  4933.5  348.74  4940.9  348.10  4950.9  348.18  4960.9  347.51
  4970.9  346.19  4980.9  345.82  4990.9  345.71  5003.0  345.85  5008.0  345.50
  5013.2  344.48  5019.5  340.31  5019.7  339.81  5023.2  339.81  5023.5  340.31
  5042.0  346.92  5050.8  348.53  5055.9  348.98  5062.5  350.28  5098.7  352.57
  5103.8  353.16  5134.4  354.64  5141.5  354.04  5146.1  354.80  5148.7  354.80
#Mann=3,-1,0
  4817.3    0.05       0  5019.5    0.04       0  5023.5    0.05       0
Bank Sta=5019.5,5023.5
Exp/Cntr=0.3,0.1

Type RM Length L Ch R = 1,1805,54,54,54
BEGIN DESCRIPTION:
Lacy 175 412
END DESCRIPTION:
XS GIS Cut Line= 3
      2703367.81      6836876.24      2703374.51      6837066.89
      2703401.85      6837236.13
#Sta/Elev= 30
  4816.3  354.76  4821.2  354.76  4841.1  353.37  4851.1  352.42  4901.1  349.29
  4906.6  348.69  4911.6  348.86  4941.1  347.54  4981.2  347.63  4991.2  347.43
  5001.2  346.70  5006.6  344.13  5011.7  344.13  5019.4  339.32  5019.6  338.82
  5023.1  338.82  5023.4  339.32  5031.5  341.29  5041.6  344.56  5047.2  346.73
  5052.3  347.13  5061.9  348.36  5092.3  350.06  5102.4  350.34  5122.7  351.74
  5132.8  352.13  5153.0  352.21  5170.7  352.80  5175.8  353.19  5178.5  353.70
#Mann=3,-1,0
  4816.3    0.05       0  5019.4    0.04       0  5023.4    0.05       0
Bank Sta=5019.4,5023.4
Exp/Cntr=0.3,0.1

Type RM Length L Ch R = 1,1751,102,102,102
BEGIN DESCRIPTION:
Lacy 175 411
END DESCRIPTION:
XS GIS Cut Line= 3
      2703320.58      6836853.53      2703321.57      6837052.70
      2703348.89      6837216.88
#Sta/Elev= 30
  4800.2  355.68  4817.7  354.56  4827.7  353.68  4847.7  352.48  4857.7  351.58
  4877.7  350.40  4883.7  349.65  4888.7  350.00  4897.7  349.30  4927.7  347.70
  4937.7  347.35  4967.7  346.93  4977.7  347.24  4996.0  344.74  4999.4  344.74
  5005.8  341.67  5006.0  341.17  5009.5  341.17  5009.8  341.67  5017.9  341.72
  5028.1  344.37  5038.2  345.24  5048.3  346.90  5055.1  346.86  5068.6  347.09
  5109.2  348.29  5129.4  349.52  5139.6  349.82  5149.7  350.09  5165.8  350.14
#Mann=3,-1,0
  4800.2    0.05       0  5005.8    0.04       0  5009.8    0.05       0
Bank Sta=5005.8,5009.8
Exp/Cntr=0.3,0.1

Type RM Length L Ch R = 1,1649,58,58,58
BEGIN DESCRIPTION:
Lacy 175 410
END DESCRIPTION:
XS GIS Cut Line= 3
      2703125.21      6836883.71      2703244.53      6837048.79
      2703340.34      6837195.96
#Sta/Elev= 30
  4800.0  356.55  4821.1  356.09  4827.2  354.64  4833.7  355.23  4870.7  352.53
  4877.5  352.76  4892.2  352.12  4906.9  350.32  4913.1  349.15  4927.8  345.38
  4934.0  344.78  4946.7  338.98  4946.9  338.48  4950.4  338.48  4950.7  338.98
  4963.4  342.39  4969.5  343.40  4984.3  345.03  4992.8  345.01  4999.0  345.72
  5002.0  345.14  5013.9  345.05  5019.9  346.42  5042.1  346.69  5050.2  346.23
  5101.5  346.40  5122.6  347.35  5143.7  347.67  5164.8  349.28  5179.3  349.62
#Mann=3,-1,0
  4800.0    0.05       0  4946.7    0.04       0  4950.7    0.05       0
Bank Sta=4946.7,4950.7
Exp/Cntr=0.3,0.1

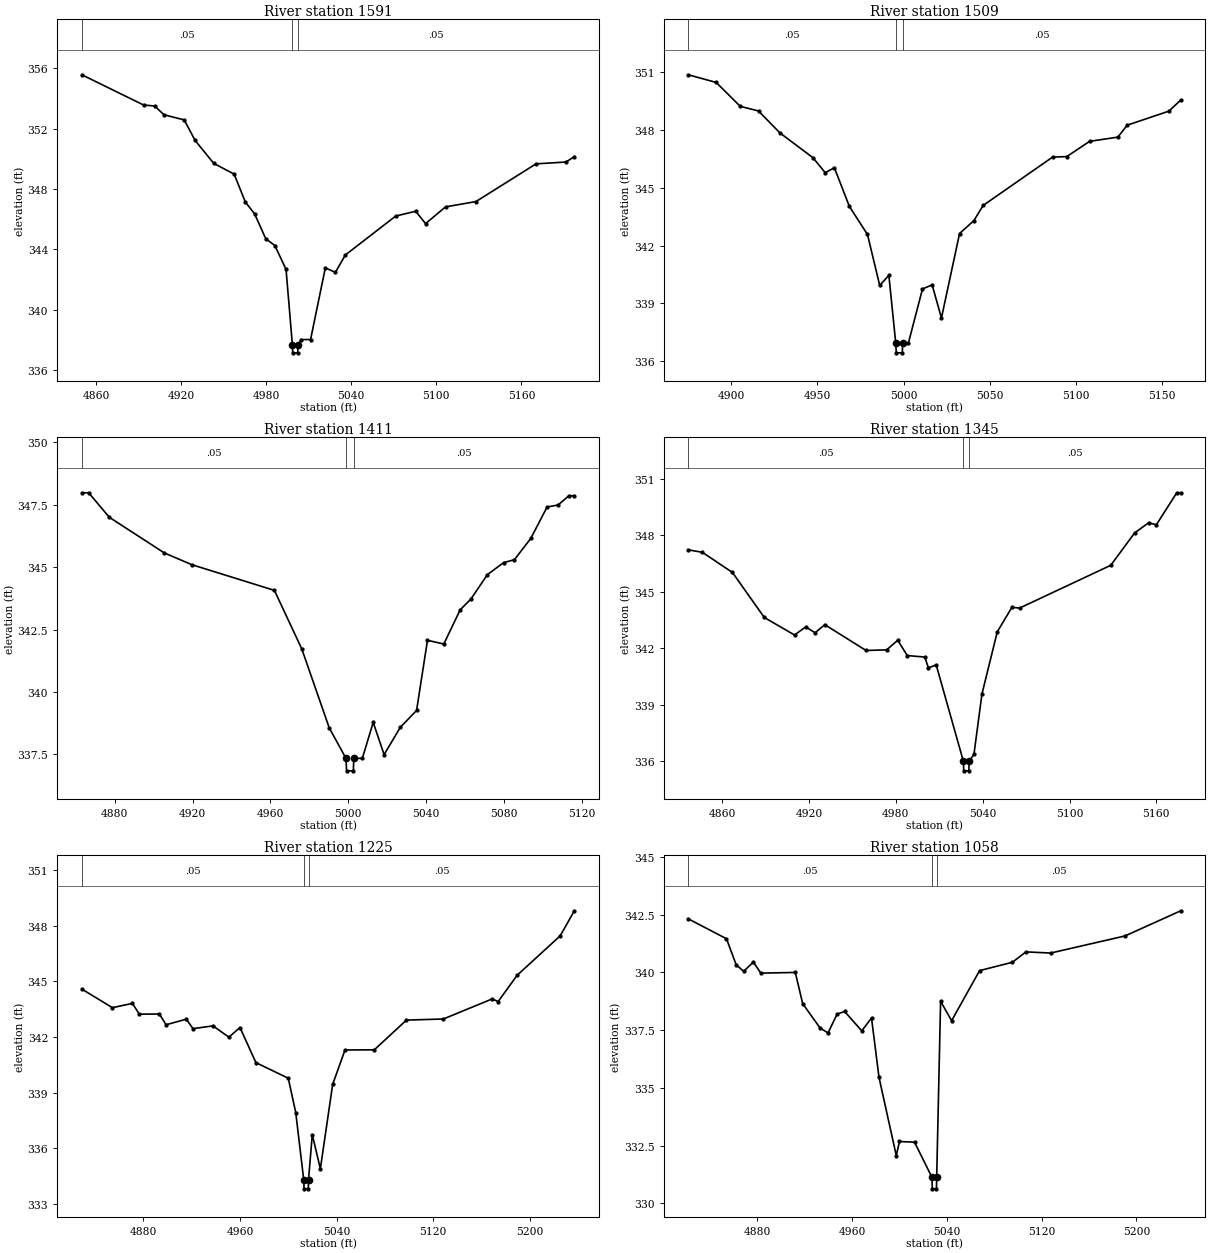
Type RM Length L Ch R = 1,1591,82,82,82
BEGIN DESCRIPTION:
Lacy 175 409
END DESCRIPTION:
XS GIS Cut Line= 3
      2703084.20      6836991.02      2703206.84      6837091.23
      2703342.19      6837223.04
#Sta/Elev= 30
  4850.0  355.56  4893.5  353.56  4901.4  353.49  4907.9  352.91  4922.2  352.57
  4929.8  351.22  4943.0  349.69  4957.4  348.98  4965.3  347.13  4971.8  346.35
  4979.7  344.70  4986.1  344.25  4994.0  342.67  4998.5  337.64  4998.7  337.14
  5002.2  337.14  5002.5  337.64  5004.6  338.02  5011.3  338.02  5021.7  342.77
  5028.8  342.47  5035.8  343.62  5071.3  346.20  5085.4  346.52  5092.4  345.70
  5106.5  346.81  5127.9  347.16  5170.3  349.66  5191.4  349.78  5197.3  350.14
#Mann=3,-1,0
  4850.0    0.05       0  4998.5    0.04       0  5002.5    0.05       0
Bank Sta=4998.5,5002.5
Exp/Cntr=0.3,0.1

Type RM Length L Ch R = 1,1509,98,98,98
BEGIN DESCRIPTION:
Lacy 175 408
END DESCRIPTION:
XS GIS Cut Line= 3
      2703057.41      6837120.31      2703175.90      6837159.80
      2703325.12      6837219.45
#Sta/Elev= 30
  4875.2  350.88  4891.4  350.48  4905.3  349.24  4915.9  349.00  4928.3  347.86
  4947.5  346.57  4954.6  345.79  4959.9  346.05  4968.6  344.04  4979.1  342.58
  4986.2  339.93  4991.5  340.46  4995.5  336.93  4995.8  336.43  4999.3  336.43
  4999.5  336.93  5002.8  336.93  5011.0  339.75  5016.6  339.96  5022.0  338.24
  5032.5  342.63  5040.8  343.30  5046.2  344.09  5086.4  346.60  5094.7  346.63
  5107.9  347.42  5124.3  347.64  5129.7  348.26  5153.9  348.99  5160.8  349.57
#Mann=3,-1,0
  4875.2    0.05       0  4995.5    0.04       0  4999.5    0.05       0
Bank Sta=4995.5,4999.5
Exp/Cntr=0.3,0.1

Type RM Length L Ch R = 1,1411,66,66,66
BEGIN DESCRIPTION:
Lacy 175 69
END DESCRIPTION:
XS GIS Cut Line= 3
      2703076.03      6837161.03      2703176.00      6837261.00
      2703276.01      6837311.01
#Sta/Elev= 29
  4863.1  347.98  4866.6  347.98  4877.2  347.00  4905.5  345.57  4919.6  345.10
  4962.1  344.07  4976.2  341.72  4990.3  338.56  4998.9  337.34  4999.2  336.84
  5002.7  336.84  5002.9  337.34  5007.3  337.34  5012.9  338.78  5018.5  337.49
  5026.8  338.58  5035.2  339.26  5040.8  342.07  5049.2  341.92  5057.6  343.29
  5063.2  343.73  5071.6  344.70  5079.9  345.18  5085.5  345.30  5093.9  346.15
  5102.3  347.41  5107.9  347.49  5113.5  347.86  5116.3  347.86
#Mann=3,-1,0
  4863.1    0.05       0  4998.9    0.04       0  5002.9    0.05       0
Bank Sta=4998.9,5002.9
Exp/Cntr=0.3,0.1

Type RM Length L Ch R = 1,1345,120,120,120
BEGIN DESCRIPTION:
Lacy 175 418
END DESCRIPTION:
XS GIS Cut Line= 3
      2703004.23      6837199.21      2703128.55      6837305.25
      2703296.21      6837361.68
#Sta/Elev= 30
  4836.6  347.23  4846.3  347.10  4867.1  346.03  4889.1  343.64  4910.0  342.71
  4917.7  343.14  4924.2  342.83  4930.9  343.26  4959.4  341.89  4973.6  341.92
  4981.3  342.43  4987.9  341.62  5000.0  341.54  5002.5  340.97  5007.9  341.12
  5026.7  336.00  5026.9  335.50  5030.4  335.50  5030.7  336.00  5034.0  336.39
  5039.5  339.58  5050.1  342.88  5060.2  344.18  5065.5  344.14  5128.5  346.41
  5145.0  348.13  5154.7  348.67  5160.0  348.56  5174.1  350.26  5176.9  350.26
#Mann=3,-1,0
  4836.6    0.05       0  5026.7    0.04       0  5030.7    0.05       0
Bank Sta=5026.7,5030.7
Exp/Cntr=0.3,0.1

Type RM Length L Ch R = 1,1225,167,167,167
BEGIN DESCRIPTION:
Lacy 175 417
END DESCRIPTION:
XS GIS Cut Line= 3
      2702877.41      6837285.09      2703029.90      6837362.46
      2703262.43      6837408.27
#Sta/Elev= 30
  4829.0  344.58  4854.3  343.58  4870.9  343.81  4876.6  343.23  4893.2  343.24
  4898.8  342.66  4915.5  342.96  4921.1  342.45  4937.7  342.60  4950.8  341.99
  4960.0  342.51  4973.2  340.62  5000.0  339.78  5006.2  337.93  5012.8  334.32
  5013.1  333.82  5016.6  333.82  5016.8  334.32  5019.9  336.74  5026.6  334.90
  5036.8  339.45  5047.0  341.30  5071.3  341.31  5097.9  342.91  5128.5  342.97
  5168.9  344.05  5173.9  343.91  5189.7  345.33  5225.3  347.45  5237.0  348.80
#Mann=3,-1,0
  4829.0    0.05       0  5012.8    0.04       0  5016.8    0.05       0
Bank Sta=5012.8,5016.8
Exp/Cntr=0.3,0.1

Type RM Length L Ch R = 1,1058,192,192,192
BEGIN DESCRIPTION:
Lacy 175 416
END DESCRIPTION:
XS GIS Cut Line= 3
      2702782.34      6837358.84      2702923.85      6837467.15
      2703151.04      6837536.01
#Sta/Elev= 30
  4821.8  342.32  4854.0  341.46  4862.2  340.33  4868.5  340.05  4876.7  340.45
  4883.0  339.97  4912.1  340.00  4918.3  338.65  4932.9  337.60  4939.7  337.38
  4947.4  338.20  4953.7  338.31  4968.2  337.47  4976.4  338.03  4982.7  335.46
  4997.3  332.07  5000.0  332.68  5012.7  332.65  5027.4  331.13  5027.7  330.63
  5031.2  330.63  5031.4  331.13  5034.7  338.75  5044.0  337.91  5067.6  340.08
  5095.3  340.44  5106.7  340.89  5127.6  340.84  5190.3  341.58  5237.4  342.67
#Mann=3,-1,0
  4821.8    0.05       0  5027.4    0.04       0  5031.4    0.05       0
Bank Sta=5027.4,5031.4
Exp/Cntr=0.3,0.1

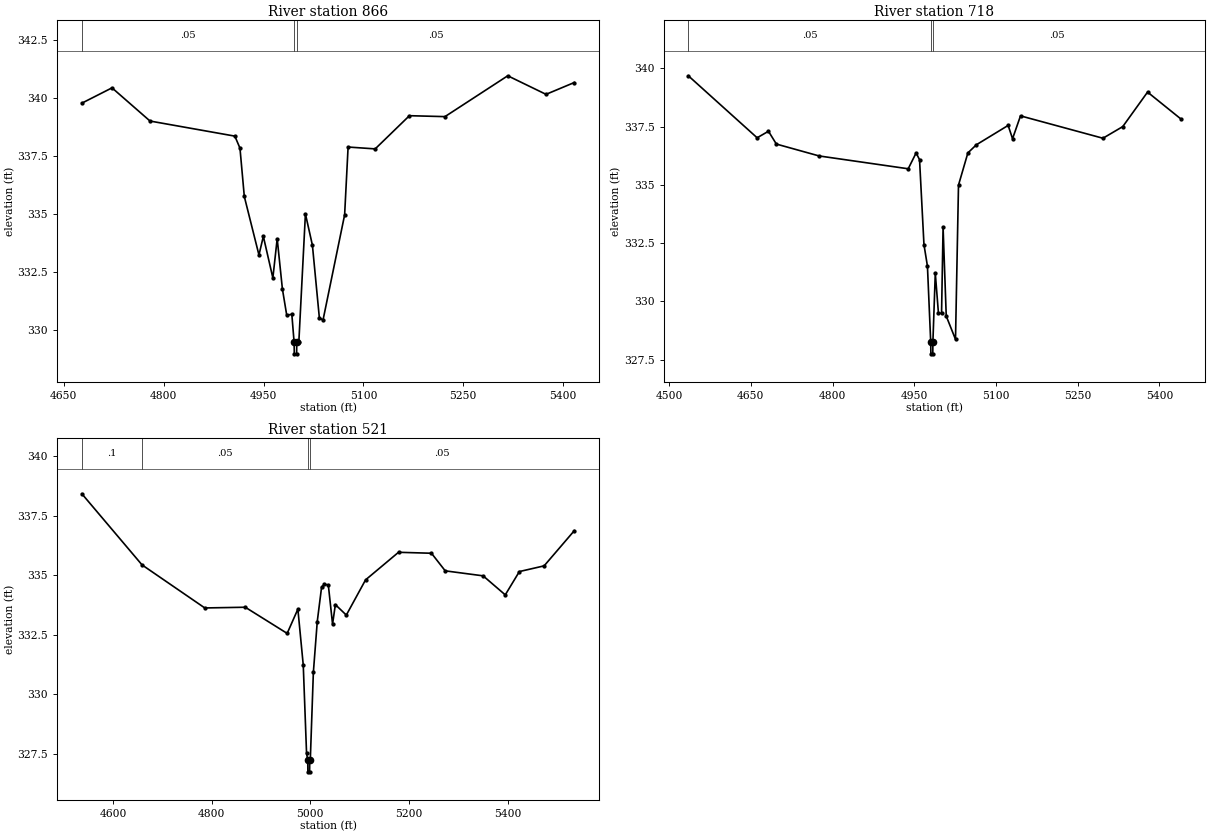
Type RM Length L Ch R = 1,866,148,148,148
BEGIN DESCRIPTION:
Lacy 175 415
END DESCRIPTION:
XS GIS Cut Line= 3
      2702544.40      6837288.31      2702753.71      6837534.19
      2703151.47      6837658.72
#Sta/Elev= 30
  4677.1  339.79  4722.4  340.45  4779.5  339.02  4906.9  338.37  4914.6  337.85
  4921.1  335.77  4943.1  333.25  4949.7  334.05  4964.0  332.26  4970.5  333.95
  4978.3  331.79  4984.8  330.66  4992.5  330.69  4995.9  329.49  4996.2  328.99
  4999.7  328.99  4999.9  329.49  5003.0  329.49  5012.9  335.02  5023.4  333.67
  5033.8  330.55  5039.3  330.44  5071.8  334.98  5077.0  337.90  5117.7  337.82
  5169.1  339.25  5222.5  339.21  5316.8  340.97  5374.3  340.17  5416.8  340.68
#Mann=3,-1,0
  4677.1    0.05       0  4995.9    0.04       0  4999.9    0.05       0
Bank Sta=4995.9,4999.9
Exp/Cntr=0.3,0.1

Type RM Length L Ch R = 1,718,197,197,197
BEGIN DESCRIPTION:
Lacy 175 414
END DESCRIPTION:
XS GIS Cut Line= 3
      2702340.10      6837240.17      2702628.20      6837604.92
      2703025.20      6837792.53
#Sta/Elev= 30
  4535.2  339.68  4661.5  337.02  4682.3  337.30  4696.8  336.75  4775.3  336.24
  4938.8  335.69  4953.3  336.37  4959.6  336.08  4967.7  332.44  4974.1  331.51
  4980.1  328.25  4980.4  327.75  4983.9  327.75  4984.1  328.25  4988.5  331.21
  4994.3  329.49  5000.0  329.49  5002.8  333.18  5008.6  329.37  5025.6  328.37
  5031.1  334.99  5048.3  336.37  5063.9  336.72  5122.2  337.55  5130.3  336.98
  5144.9  337.96  5296.2  337.00  5332.6  337.50  5378.1  338.98  5439.1  337.83
#Mann=3,-1,0
  4535.2    0.05       0  4980.1    0.04       0  4984.1    0.05       0
Bank Sta=4980.1,4984.1
Exp/Cntr=0.3,0.1

Type RM Length L Ch R = 1,521,0,0,0
BEGIN DESCRIPTION:
Lacy 175 413
END DESCRIPTION:
XS GIS Cut Line= 3
      2702273.93      6837257.33      2702453.47      6837684.21
      2702930.90      6837926.07
#Sta/Elev= 30
  4536.9  338.43  4658.9  335.44  4786.1  333.63  4868.2  333.66  4953.1  332.56
  4974.8  333.58  4985.7  331.23  4992.4  327.52  4994.8  327.24  4995.1  326.74
  4998.6  326.74  4998.8  327.24  5000.0  327.24  5006.2  330.92  5014.1  333.06
  5022.9  334.51  5028.5  334.62  5036.5  334.60  5045.1  332.95  5050.8  333.77
  5073.0  333.33  5112.0  334.81  5178.8  335.97  5245.6  335.93  5273.5  335.19
  5350.3  334.98  5395.2  334.18  5423.8  335.16  5474.0  335.40  5535.2  336.88
#Mann=4,-1,0
  4536.9     0.1       0  4658.9    0.05       0  4994.8    0.04       0
  4998.8    0.05       0
Bank Sta=4994.8,4998.8
Exp/Cntr=0.3,0.1

Chan Stop Cuts=-1