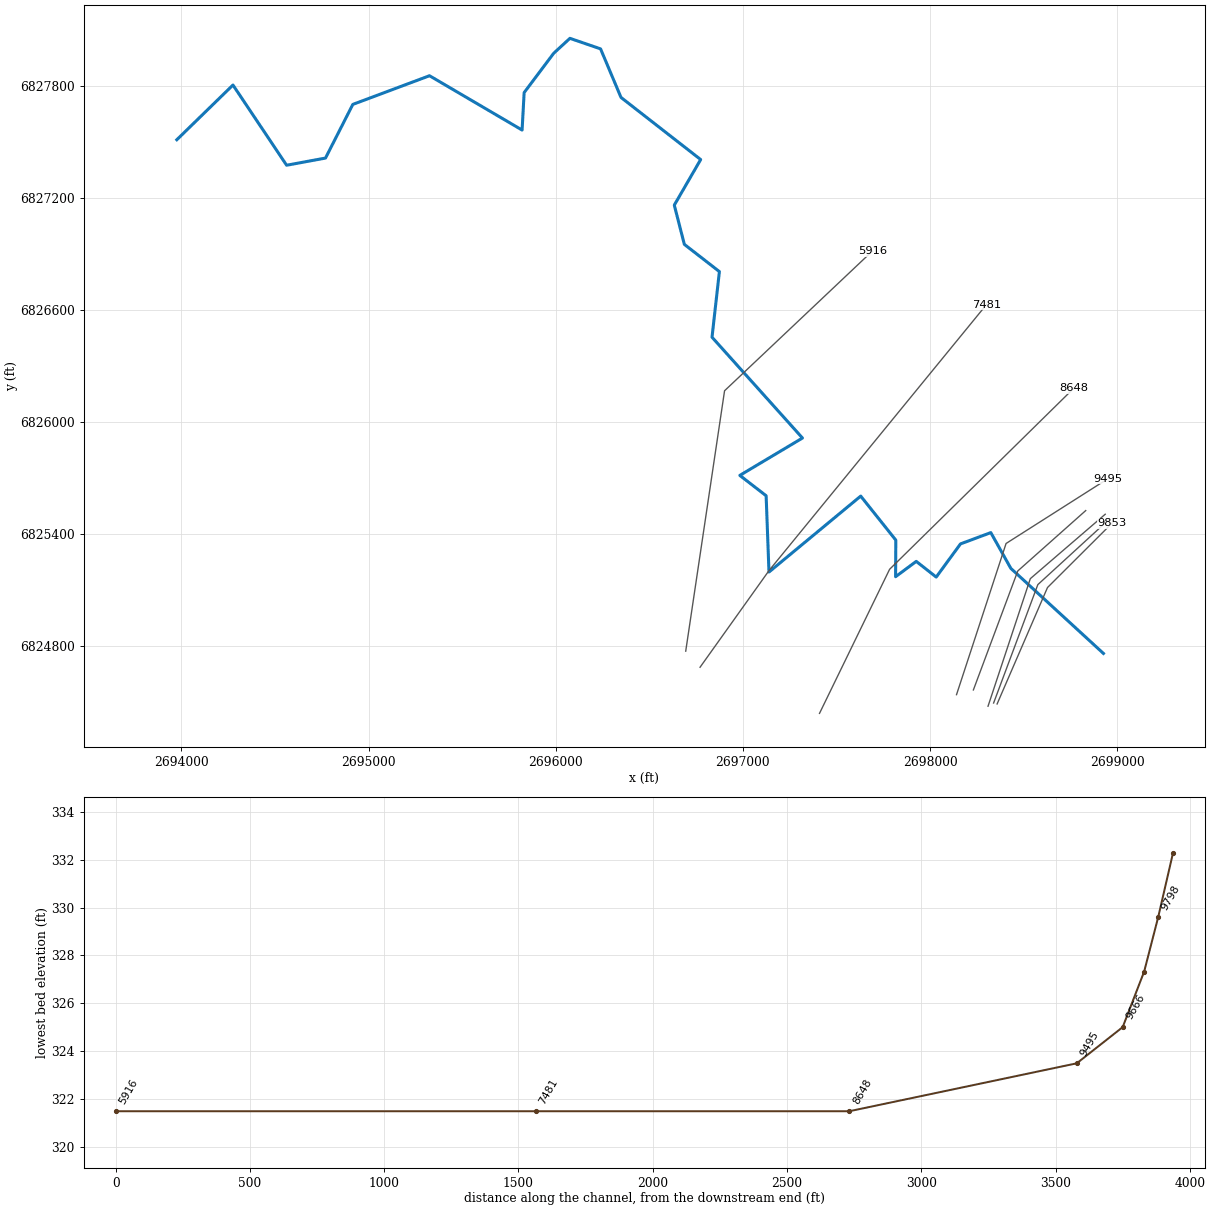
--- Lacy 181.prj (project) ---

Proj Title=Lacy 181 Base Level Engineering
Current Plan=p01
Default Exp/Contr=0.3,0.1
English Units
Geom File=g01
Flow File=f01
Plan File=p01
BEGIN DESCRIPTION:
Lacy 181
END DESCRIPTION:

--- Lacy 181.p01 (plan) ---

Plan Title=Multiple Run
Short Identifier=Multiple
Geom File=g01
Flow File=f01
Subcritical Flow
K Sum by GR= 0
Std Step Tol= 0.01
Critical Tol= 0.01
Num of Std Step Trials= 20
Max Error Tol= 0.3
Flow Tol Ratio= 0.001
Split Flow NTrial= 30
Split Flow Tol= 0.02
Split Flow Ratio= 0.02
Log Output Level= 0
Friction Slope Method= 1
Unsteady Friction Slope Method= 2
Unsteady Bridges Friction Slope Method= 1
Parabolic Critical Depth
Global Vel Dist=  1 , 1 , 1
Global Log Level= 0
CheckData=True
Encroach Param= -1, 0, 0, 0
BEGIN DESCRIPTION:
Multiple Run
END DESCRIPTION:

--- Lacy 181.f01 (steady flow) ---

Flow Title=Multiple
Number of Profiles=7
Profile Names=10-year,25-year,50-year,1pct_min,100-year,1pct_plu,500-year
River Rch & RM= Lacy 181,Reach-1,9853
     368     471     550     318     635    1267     845
Boundary for River Rch & Prof#=Lacy 181,Reach-1,1
Up Type=0
Dn Type=3
Dn Slope=0.005
Boundary for River Rch & Prof#=Lacy 181,Reach-1,2
Up Type=0
Dn Type=3
Dn Slope=0.005
Boundary for River Rch & Prof#=Lacy 181,Reach-1,3
Up Type=0
Dn Type=3
Dn Slope=0.005
Boundary for River Rch & Prof#=Lacy 181,Reach-1,4
Up Type=0
Dn Type=3
Dn Slope=0.005
Boundary for River Rch & Prof#=Lacy 181,Reach-1,5
Up Type=0
Dn Type=3
Dn Slope=0.005
Boundary for River Rch & Prof#=Lacy 181,Reach-1,6
Up Type=0
Dn Type=3
Dn Slope=0.005
Boundary for River Rch & Prof#=Lacy 181,Reach-1,7
Up Type=0
Dn Type=3
Dn Slope=0.005

--- Lacy 181.g01 (geometry) ---

Geom Title=Existing Conditions

River Reach=Lacy 181,Reach-1
Reach XY= 30
      2698926.00      6824761.00      2698431.26      6825216.47
      2698324.38      6825407.88      2698162.43      6825347.53
      2698032.68      6825169.96      2697926.00      6825253.88
      2697815.62      6825171.81      2697816.85      6825367.73
      2697629.35      6825603.42      2697139.34      6825196.85
      2697124.11      6825605.29      2696983.51      6825714.17
      2697318.17      6825914.22      2696835.03      6826453.99
      2696874.46      6826805.15      2696687.23      6826950.98
      2696633.50      6827161.00      2696774.42      6827404.95
      2696348.87      6827737.47      2696239.69      6827997.50
      2696075.99      6828053.91      2695989.63      6827974.27
      2695831.40      6827763.43      2695820.51      6827562.95
      2695325.91      6827853.69      2694916.30      6827700.23
      2694770.35      6827412.98      2694562.62      6827374.53
      2694276.01      6827803.93      2693976.00      6827511.00

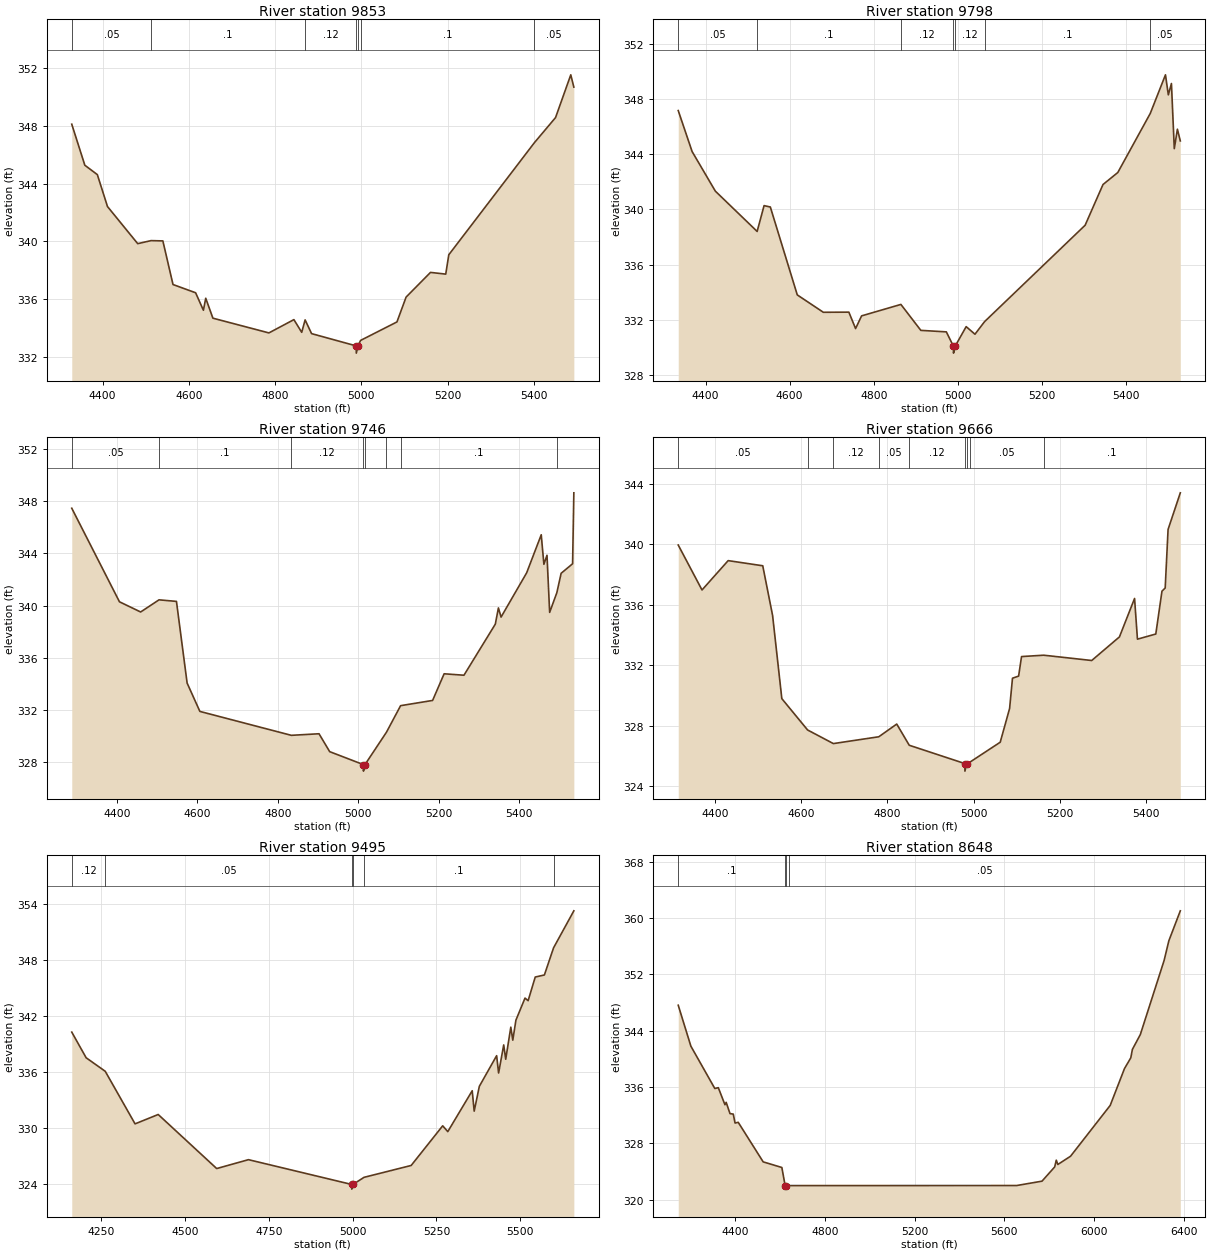
Type RM Length L Ch R = 1,9853,55,55,55
BEGIN DESCRIPTION:
Lacy 181 389
END DESCRIPTION:
XS GIS Cut Line= 3
      2698357.95      6824490.59      2698627.15      6825113.92
      2698970.26      6825456.74
#Sta/Elev= 30
  4328.5  348.11  4358.8  345.27  4387.8  344.62  4411.3  342.41  4481.4  339.84
  4512.3  340.05  4539.7  340.03  4563.2  337.01  4615.6  336.44  4633.7  335.23
  4639.1  336.06  4655.7  334.68  4785.6  333.66  4843.5  334.58  4861.6  333.70
  4869.5  334.56  4884.5  333.61  4988.0  332.76  4988.2  332.26  4992.0  332.76
  4998.1  333.14  5082.4  334.42  5103.6  336.14  5160.2  337.85  5195.5  337.73
  5202.6  339.07  5401.0  346.83  5450.1  348.57  5485.4  351.53  5492.5  350.68
#Mann=7,-1,0
  4328.5    0.05       0  4512.3     0.1       0  4869.5    0.12       0
  4988.0    0.07       0  4992.0    0.12       0  4998.1     0.1       0
  5401.0    0.05       0
Bank Sta=4988,4992
Exp/Cntr=0.3,0.1

Type RM Length L Ch R = 1,9798,52,52,52
BEGIN DESCRIPTION:
Lacy 181 3426
END DESCRIPTION:
XS GIS Cut Line= 3
      2698339.29      6824495.67      2698575.48      6825129.45
      2698957.22      6825479.64
#Sta/Elev= 30
  4334.9  347.17  4367.9  344.20  4423.2  341.33  4522.6  338.41  4539.1  340.28
  4554.0  340.18  4618.1  333.81  4680.1  332.55  4740.8  332.56  4756.8  331.37
  4771.1  332.29  4864.6  333.12  4912.0  331.24  4972.7  331.13  4989.6  330.09
  4989.8  329.59  4993.6  330.09  5019.9  331.51  5040.8  330.96  5063.6  331.87
  5302.9  338.86  5345.4  341.81  5380.6  342.68  5457.8  346.96  5494.0  349.76
  5500.8  348.31  5508.2  349.13  5515.0  344.41  5522.4  345.82  5529.3  344.97
#Mann=7,-1,0
  4334.9    0.05       0  4522.6     0.1       0  4864.6    0.12       0
  4989.6    0.07       0  4993.6    0.12       0  5063.6     0.1       0
  5457.8    0.05       0
Bank Sta=4989.6,4993.6
Exp/Cntr=0.3,0.1

Type RM Length L Ch R = 1,9746,80,80,80
BEGIN DESCRIPTION:
Lacy 181 3425
END DESCRIPTION:
XS GIS Cut Line= 3
      2698309.50      6824478.53      2698535.33      6825161.34
      2698935.43      6825506.21
#Sta/Elev= 30
  4287.8  347.45  4406.3  340.29  4458.9  339.51  4504.6  340.44  4547.9  340.32
  4574.4  334.07  4606.1  331.90  4833.3  330.07  4902.1  330.19  4928.6  328.82
  5012.3  327.83  5012.5  327.33  5016.3  327.83  5069.7  330.31  5104.8  332.34
  5184.3  332.74  5212.9  334.78  5262.2  334.67  5340.1  338.58  5347.8  339.82
  5354.4  339.12  5418.0  342.51  5454.2  345.42  5460.8  343.16  5468.5  343.85
  5475.1  339.48  5493.0  340.99  5503.6  342.47  5532.1  343.20  5535.2  348.63
#Mann=8,-1,0
  4287.8    0.05       0  4504.6     0.1       0  4833.3    0.12       0
  5012.3    0.07       0  5016.3    0.12       0  5069.7    0.05       0
  5104.8     0.1       0  5493.0    0.05       0
Bank Sta=5012.3,5016.3
Exp/Cntr=0.3,0.1

Type RM Length L Ch R = 1,9666,171,171,171
BEGIN DESCRIPTION:
Lacy 181 388
END DESCRIPTION:
XS GIS Cut Line= 3
      2698231.22      6824565.63      2698468.45      6825202.66
      2698831.26      6825525.78
#Sta/Elev= 30
  4314.2  339.95  4369.4  336.98  4430.1  338.92  4510.4  338.58  4533.3  335.29
  4554.7  329.80  4614.5  327.73  4674.3  326.83  4779.8  327.28  4821.5  328.12
  4850.5  326.72  4979.5  325.51  4979.8  325.01  4983.5  325.51  4990.6  325.59
  5061.7  326.92  5083.5  329.15  5090.2  331.15  5104.4  331.29  5111.2  332.58
  5162.8  332.67  5274.1  332.32  5338.5  333.88  5373.6  336.42  5380.3  333.73
  5422.9  334.07  5437.2  336.90  5444.7  337.11  5451.4  340.98  5479.8  343.40
#Mann=9,-1,0
  4314.2    0.05       0  4614.5     0.1       0  4674.3    0.12       0
  4779.8    0.05       0  4850.5    0.12       0  4979.5    0.03       0
  4983.5    0.12       0  4990.6    0.05       0  5162.8     0.1       0
Bank Sta=4979.5,4983.5
Exp/Cntr=0.3,0.1

Type RM Length L Ch R = 1,9495,847,847,847
BEGIN DESCRIPTION:
Lacy 181 3427
END DESCRIPTION:
XS GIS Cut Line= 3
      2698141.13      6824540.35      2698405.86      6825349.71
      2698950.00      6825696.67
#Sta/Elev= 30
  4162.7  340.29  4205.5  337.55  4262.5  336.10  4351.4  330.48  4420.4  331.48
  4594.8  325.70  4689.5  326.65  4997.2  324.00  4997.5  323.50  5001.2  324.00
  5034.0  324.76  5174.6  326.03  5268.6  330.27  5283.8  329.65  5356.6  334.02
  5362.5  331.84  5377.8  334.49  5429.4  337.77  5435.3  335.92  5450.5  338.92
  5456.5  337.39  5471.7  340.82  5477.6  339.43  5486.9  341.57  5514.0  343.93
  5523.3  343.65  5544.5  346.18  5571.8  346.40  5599.1  349.30  5659.6  353.26
#Mann=6,-1,0
  4162.7    0.12       0  4262.5    0.05       0  4997.2    0.03       0
  5001.2    0.05       0  5034.0     0.1       0  5599.1    0.05       0
Bank Sta=4997.2,5001.2
Exp/Cntr=0.3,0.1

Type RM Length L Ch R = 1,8648,1167,1167,1167
BEGIN DESCRIPTION:
Lacy 181 384
END DESCRIPTION:
XS GIS Cut Line= 3
      2697409.26      6824440.23      2697783.70      6825211.55
      2698768.03      6826181.18
#Sta/Elev= 30
  4146.3  347.60  4202.7  341.79  4309.5  335.78  4325.0  335.90  4354.6  333.48
  4360.1  333.82  4377.1  332.22  4391.7  332.15  4399.7  330.88  4413.9  330.98
  4525.1  325.37  4608.4  324.57  4623.1  322.00  4623.4  321.50  4627.1  322.00
  4641.4  322.00  5655.5  322.01  5768.6  322.63  5825.2  324.65  5832.3  325.61
  5839.3  325.00  5895.9  326.17  6072.7  333.38  6136.3  338.60  6164.6  340.14
  6171.7  341.33  6207.1  343.44  6313.1  353.95  6334.3  356.75  6385.4  361.00
#Mann=4,-1,0
  4146.3     0.1       0  4623.1    0.03       0  4627.1     0.1       0
  4641.4    0.05       0
Bank Sta=4623.1,4627.1
Exp/Cntr=0.3,0.1

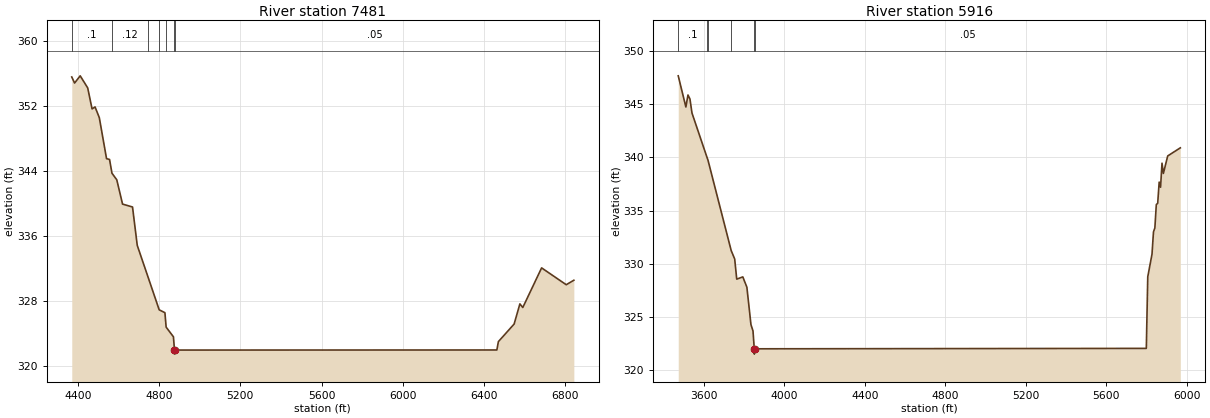
Type RM Length L Ch R = 1,7481,1565,1565,1565
BEGIN DESCRIPTION:
Lacy 181 383
END DESCRIPTION:
XS GIS Cut Line= 3
      2696771.12      6824687.15      2697140.05      6825205.41
      2698301.46      6826628.99
#Sta/Elev= 30
  4369.5  355.60  4383.4  354.85  4411.0  355.74  4447.9  354.26  4469.5  351.67
  4484.3  351.91  4505.2  350.59  4540.8  345.55  4555.6  345.45  4567.5  343.76
  4591.2  342.95  4619.7  339.96  4668.8  339.60  4692.1  334.88  4746.0  330.93
  4800.2  326.95  4828.4  326.60  4834.4  324.82  4870.4  323.63  4875.5  322.00
  4875.7  321.50  4879.5  322.00  6463.6  322.01  6471.2  323.04  6548.7  325.20
  6577.1  327.68  6591.5  327.24  6684.1  332.11  6805.4  330.04  6842.9  330.59
#Mann=7,-1,0
  4369.5     0.1       0  4567.5    0.12       0  4746.0     0.1       0
  4800.2    0.12       0  4834.4    0.05       0  4875.5    0.03       0
  4879.5    0.05       0
Bank Sta=4875.5,4879.5
Exp/Cntr=0.3,0.1

Type RM Length L Ch R = 1,5916,0,0,0
BEGIN DESCRIPTION:
Lacy 181 382
END DESCRIPTION:
XS GIS Cut Line= 3
      2696694.57      6824773.38      2696902.04      6826167.24
      2697691.09      6826914.72
#Sta/Elev= 30
  3471.9  347.66  3509.9  344.73  3520.3  345.86  3530.2  345.48  3540.3  344.16
  3615.9  339.94  3619.6  339.75  3735.1  331.24  3752.6  330.44  3762.7  328.55
  3793.0  328.76  3813.2  327.79  3833.5  324.27  3843.6  323.68  3849.9  322.00
  3850.2  321.50  3853.9  322.00  5799.0  322.04  5806.2  328.77  5827.3  330.90
  5834.6  332.99  5841.5  333.36  5848.7  335.56  5855.6  335.68  5862.9  337.67
  5869.8  337.19  5877.0  339.45  5883.9  338.49  5905.4  340.13  5968.0  340.89
#Mann=6,-1,0
  3471.9     0.1       0  3615.9    0.12       0  3619.6     0.1       0
  3735.1    0.05       0  3849.9    0.03       0  3853.9    0.05       0
Bank Sta=3849.9,3853.9
Exp/Cntr=0.3,0.1

Chan Stop Cuts=-1