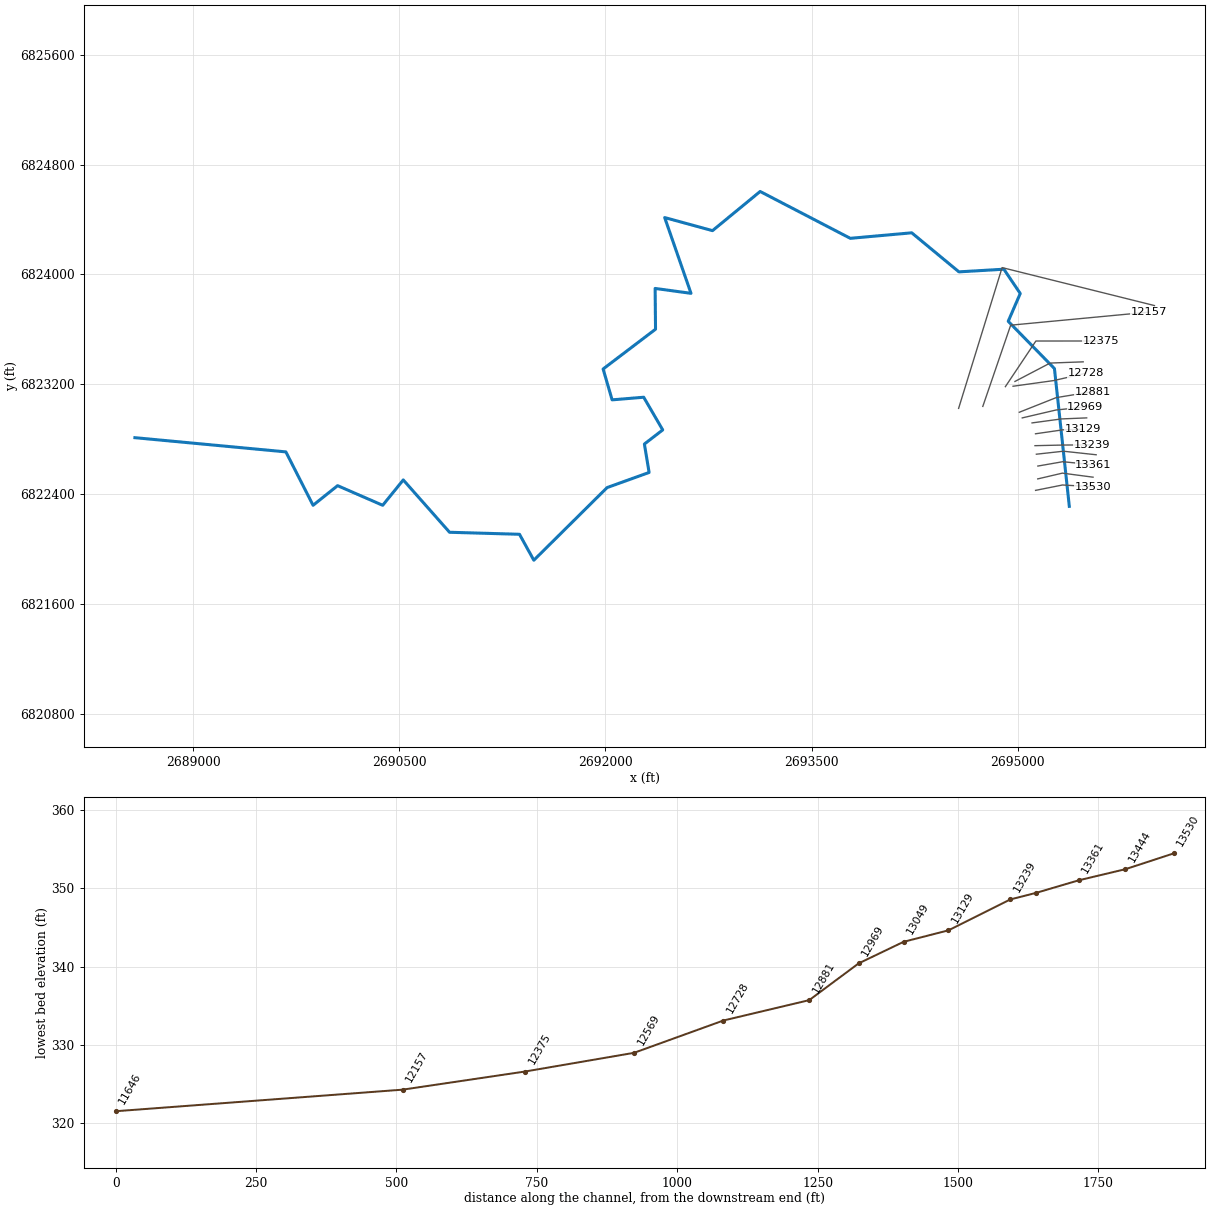
--- Lacy 183.prj (project) ---

Proj Title=Lacy 183 Base Level Engineering
Current Plan=p01
Default Exp/Contr=0.3,0.1
English Units
Geom File=g01
Flow File=f01
Plan File=p01
BEGIN DESCRIPTION:
Lacy 183
END DESCRIPTION:

--- Lacy 183.p01 (plan) ---

Plan Title=Multiple Run
Short Identifier=Multiple
Geom File=g01
Flow File=f01
Subcritical Flow
K Sum by GR= 0
Std Step Tol= 0.01
Critical Tol= 0.01
Num of Std Step Trials= 20
Max Error Tol= 0.3
Flow Tol Ratio= 0.001
Split Flow NTrial= 30
Split Flow Tol= 0.02
Split Flow Ratio= 0.02
Log Output Level= 0
Friction Slope Method= 1
Unsteady Friction Slope Method= 2
Unsteady Bridges Friction Slope Method= 1
Parabolic Critical Depth
Global Vel Dist=  1 , 1 , 1
Global Log Level= 0
CheckData=True
Encroach Param= -1, 0, 0, 0
BEGIN DESCRIPTION:
Multiple Run
END DESCRIPTION:

--- Lacy 183.f01 (steady flow) ---

Flow Title=Multiple
Number of Profiles=7
Profile Names=10-year,25-year,50-year,1pct_min,100-year,1pct_plu,500-year
River Rch & RM= Lacy 183,Reach-1,13530
     350     441     509     291     580    1157     753
Boundary for River Rch & Prof#=Lacy 183,Reach-1,1
Up Type=0
Dn Type=3
Dn Slope=0.005
Boundary for River Rch & Prof#=Lacy 183,Reach-1,2
Up Type=0
Dn Type=3
Dn Slope=0.005
Boundary for River Rch & Prof#=Lacy 183,Reach-1,3
Up Type=0
Dn Type=3
Dn Slope=0.005
Boundary for River Rch & Prof#=Lacy 183,Reach-1,4
Up Type=0
Dn Type=3
Dn Slope=0.005
Boundary for River Rch & Prof#=Lacy 183,Reach-1,5
Up Type=0
Dn Type=3
Dn Slope=0.005
Boundary for River Rch & Prof#=Lacy 183,Reach-1,6
Up Type=0
Dn Type=3
Dn Slope=0.005
Boundary for River Rch & Prof#=Lacy 183,Reach-1,7
Up Type=0
Dn Type=3
Dn Slope=0.005

--- Lacy 183.g01 (geometry) ---

Geom Title=Existing Conditions

River Reach=Lacy 183,Reach-1
Reach XY= 30
      2695376.00      6822311.00      2695267.77      6823314.23
      2694931.39      6823658.56      2695018.91      6823861.00
      2694899.73      6824037.89      2694572.66      6824018.60
      2694229.32      6824302.96      2693782.12      6824262.84
      2693126.21      6824603.99      2692779.45      6824318.79
      2692431.40      6824414.00      2692622.92      6823862.20
      2692361.94      6823897.88      2692364.76      6823600.95
      2691983.33      6823311.10      2692048.84      6823086.52
      2692278.73      6823105.66      2692417.09      6822867.50
      2692283.72      6822764.66      2692318.01      6822557.66
      2692012.32      6822447.50      2691479.14      6821918.50
      2691374.75      6822107.49      2690865.95      6822122.13
      2690529.05      6822503.24      2690379.35      6822318.60
      2690051.00      6822461.59      2689872.64      6822318.59
      2689674.75      6822707.55      2688576.00      6822811.00

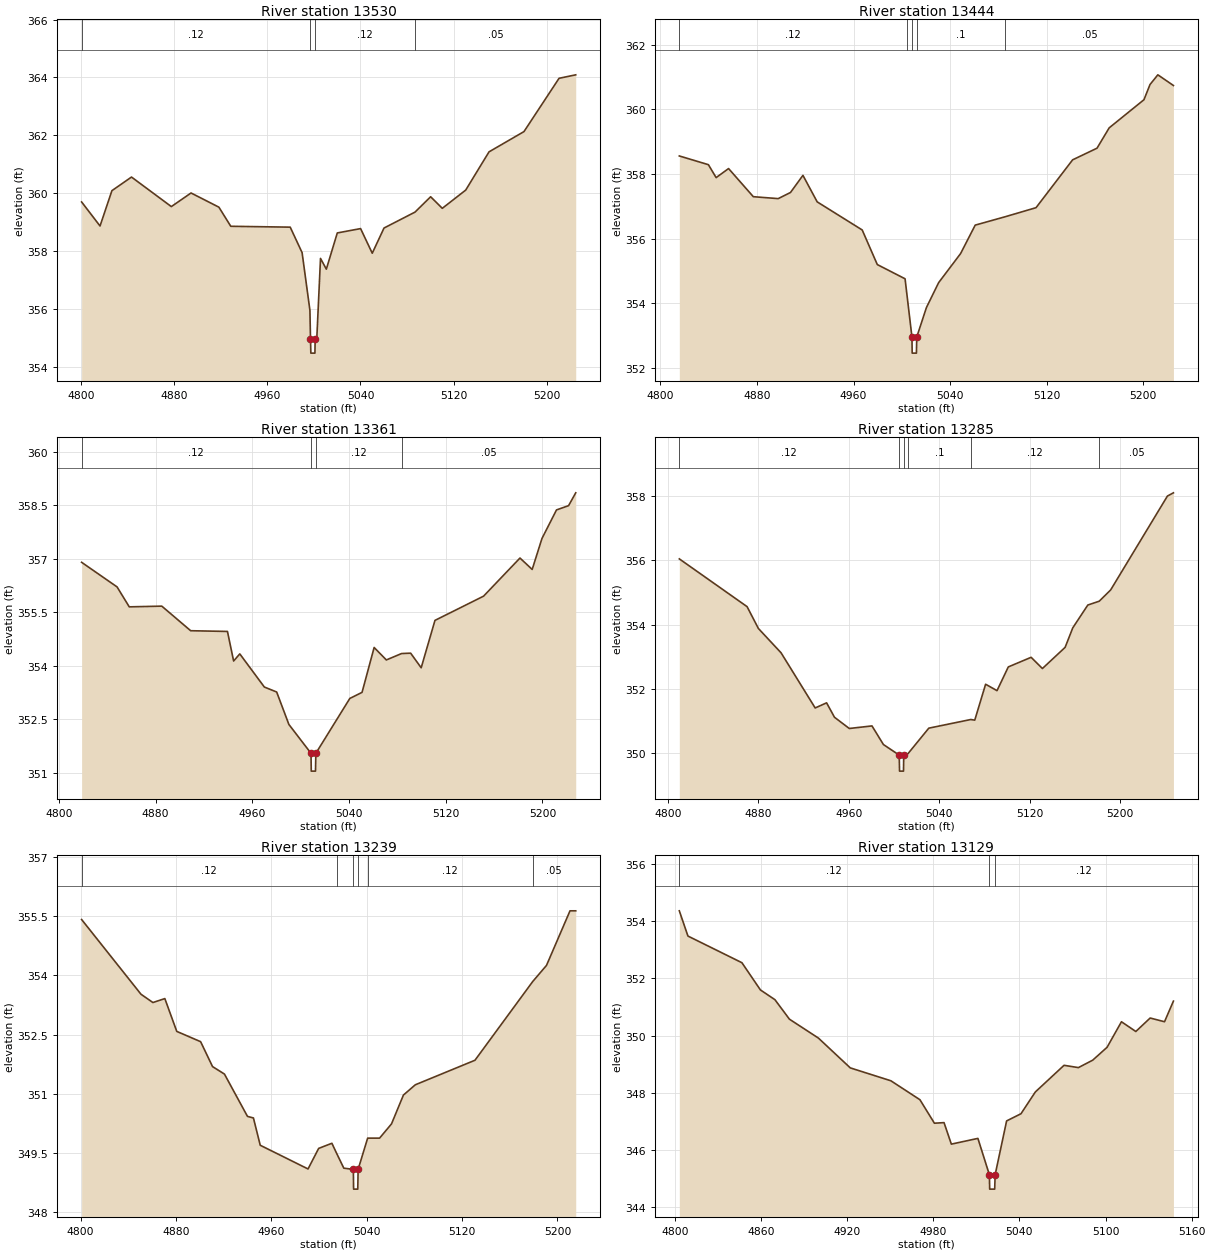
Type RM Length L Ch R = 1,13530,86,86,86
BEGIN DESCRIPTION:
Lacy 183 381
END DESCRIPTION:
XS GIS Cut Line= 3
      2695130.50      6822427.31      2695325.94      6822466.35
      2695550.30      6822454.04
#Sta/Elev= 30
  4800.7  359.70  4816.5  358.87  4826.7  360.09  4843.5  360.56  4877.7  359.54
  4894.6  360.01  4918.5  359.52  4928.7  358.86  4979.7  358.83  4989.9  357.95
  4996.6  355.96  4997.1  354.98  4997.4  354.48  5000.9  354.48  5001.1  354.98
  5002.5  354.98  5005.7  357.75  5010.7  357.38  5020.1  358.63  5040.1  358.78
  5050.1  357.93  5060.2  358.80  5086.8  359.35  5100.2  359.88  5110.2  359.48
  5130.3  360.11  5150.3  361.43  5180.3  362.13  5210.4  363.97  5224.7  364.09
#Mann=4,-1,0
  4800.7    0.12       0  4997.1    0.07       0  5001.1    0.12       0
  5086.8    0.05       0
Bank Sta=4997.1,5001.1
Exp/Cntr=0.3,0.1

Type RM Length L Ch R = 1,13444,83,83,83
BEGIN DESCRIPTION:
Lacy 183 380
END DESCRIPTION:
XS GIS Cut Line= 3
      2695146.28      6822510.79      2695325.73      6822552.80
      2695548.79      6822523.27
#Sta/Elev= 30
  4815.7  358.56  4839.8  358.29  4846.2  357.89  4856.5  358.17  4877.0  357.30
  4897.6  357.24  4907.8  357.43  4918.1  357.96  4929.9  357.14  4967.2  356.27
  4979.7  355.20  5002.7  354.76  5004.6  354.16  5008.4  352.96  5008.6  352.46
  5012.1  352.46  5012.4  352.96  5020.4  353.87  5030.5  354.64  5048.7  355.54
  5060.8  356.42  5085.7  356.68  5111.2  356.96  5141.5  358.44  5161.7  358.80
  5171.8  359.43  5200.6  360.30  5205.6  360.77  5212.1  361.07  5225.0  360.74
#Mann=5,-1,0
  4815.7    0.12       0  5004.6     0.1       0  5008.4    0.07       0
  5012.4     0.1       0  5085.7    0.05       0
Bank Sta=5008.4,5012.4
Exp/Cntr=0.3,0.1

Type RM Length L Ch R = 1,13361,76,76,76
BEGIN DESCRIPTION:
Lacy 183 379
END DESCRIPTION:
XS GIS Cut Line= 3
      2695147.15      6822604.33      2695328.69      6822636.10
      2695551.84      6822613.49
#Sta/Elev= 30
  4818.9  356.90  4848.2  356.21  4858.3  355.65  4885.2  355.67  4909.1  354.98
  4939.5  354.96  4944.6  354.13  4949.7  354.33  4970.0  353.40  4980.2  353.26
  4990.3  352.35  5008.6  351.54  5008.8  351.04  5012.3  351.04  5012.6  351.54
  5040.7  353.08  5050.8  353.25  5060.8  354.51  5070.9  354.16  5083.5  354.34
  5091.0  354.35  5099.7  353.94  5111.1  355.27  5151.3  355.95  5181.4  357.02
  5191.5  356.70  5199.6  357.57  5211.6  358.37  5221.6  358.49  5227.5  358.85
#Mann=4,-1,0
  4818.9    0.12       0  5008.6    0.07       0  5012.6    0.12       0
  5083.5    0.05       0
Bank Sta=5008.6,5012.6
Exp/Cntr=0.3,0.1

Type RM Length L Ch R = 1,13285,46,46,46
BEGIN DESCRIPTION:
Lacy 183 378
END DESCRIPTION:
XS GIS Cut Line= 3
      2695136.40      6822690.67      2695332.86      6822712.39
      2695571.32      6822686.60
#Sta/Elev= 30
  4809.9  356.05  4869.9  354.56  4879.9  353.88  4900.0  353.12  4930.2  351.40
  4940.3  351.56  4947.3  351.11  4960.4  350.76  4980.5  350.84  4990.6  350.26
  5004.6  349.93  5004.9  349.43  5008.4  349.43  5008.6  349.93  5012.5  349.98
  5030.8  350.77  5068.0  351.04  5071.5  351.02  5081.1  352.14  5091.2  351.94
  5101.2  352.68  5121.4  352.98  5131.4  352.63  5151.5  353.29  5158.3  353.90
  5171.6  354.61  5181.7  354.73  5191.8  355.08  5242.1  358.01  5247.4  358.11
#Mann=6,-1,0
  4809.9    0.12       0  5004.6    0.07       0  5008.6    0.12       0
  5012.5     0.1       0  5068.0    0.12       0  5181.7    0.05       0
Bank Sta=5004.6,5008.6
Exp/Cntr=0.3,0.1

Type RM Length L Ch R = 1,13239,110,110,110
BEGIN DESCRIPTION:
Lacy 183 377
END DESCRIPTION:
XS GIS Cut Line= 3
      2695126.19      6822752.79      2695328.91      6822757.33
      2695540.54      6822758.61
#Sta/Elev= 30
  4800.9  355.41  4850.7  353.52  4860.7  353.31  4870.7  353.41  4880.7  352.58
  4900.7  352.32  4910.7  351.69  4920.7  351.50  4940.0  350.43  4945.0  350.39
  4950.7  349.70  4990.8  349.10  4999.7  349.62  5010.8  349.75  5014.7  349.50
  5020.8  349.12  5028.8  349.09  5029.0  348.59  5032.5  348.59  5032.8  349.09
  5040.8  349.88  5050.8  349.88  5060.8  350.24  5070.8  350.97  5080.8  351.23
  5130.8  351.85  5179.2  353.84  5190.8  354.25  5210.5  355.63  5215.3  355.63
#Mann=6,-1,0
  4800.9    0.12       0  5014.7     0.1       0  5028.8    0.07       0
  5032.8     0.1       0  5040.8    0.12       0  5179.2    0.05       0
Bank Sta=5028.8,5032.8
Exp/Cntr=0.3,0.1

Type RM Length L Ch R = 1,13129,80,80,80
BEGIN DESCRIPTION:
Lacy 183 376
END DESCRIPTION:
XS GIS Cut Line= 3
      2695130.09      6822839.46      2695329.37      6822868.17
      2695472.20      6822871.37
#Sta/Elev= 30
  4803.1  354.35  4809.1  353.47  4846.7  352.54  4859.6  351.59  4869.7  351.25
  4879.8  350.57  4900.0  349.91  4922.2  348.87  4950.5  348.42  4970.7  347.76
  4980.8  346.94  4987.5  346.96  4992.6  346.21  5011.1  346.41  5019.1  345.14
  5019.3  344.64  5022.8  344.64  5023.1  345.14  5031.1  347.02  5041.1  347.27
  5051.1  348.03  5071.1  348.96  5081.1  348.88  5091.1  349.14  5101.1  349.59
  5111.1  350.48  5121.1  350.14  5131.1  350.61  5141.1  350.48  5147.3  351.20
#Mann=3,-1,0
  4803.1    0.12       0  5019.1    0.07       0  5023.1    0.12       0
Bank Sta=5019.1,5023.1
Exp/Cntr=0.3,0.1

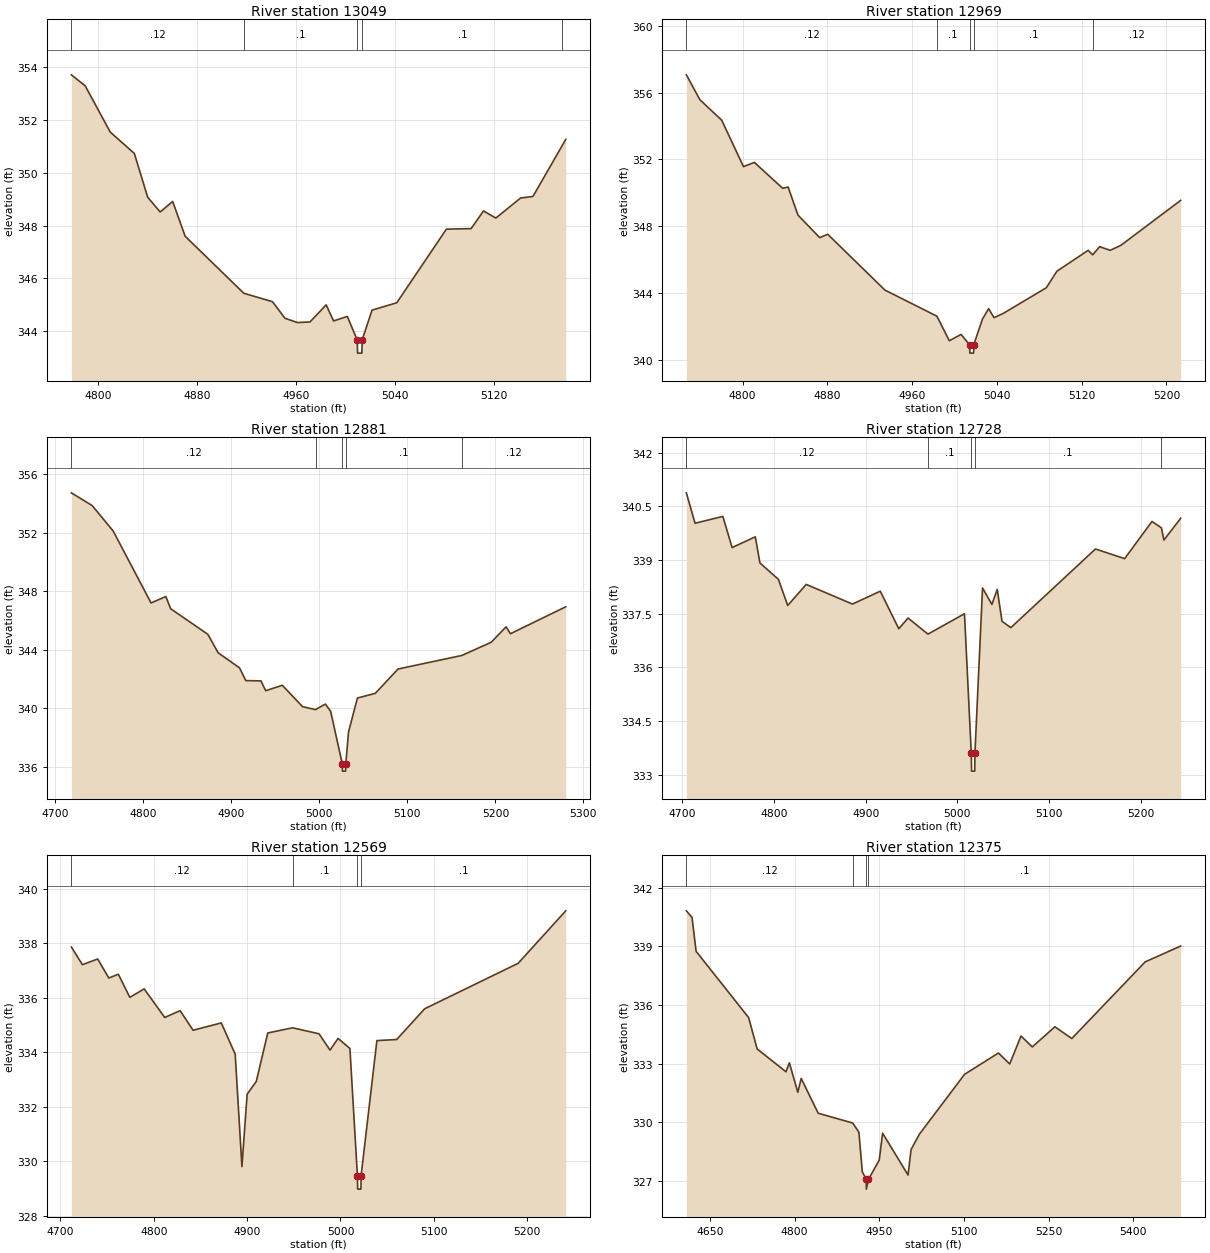
Type RM Length L Ch R = 1,13049,80,80,80
BEGIN DESCRIPTION:
Lacy 183 375
END DESCRIPTION:
XS GIS Cut Line= 3
      2695104.86      6822918.56      2695318.77      6822947.59
      2695502.44      6822955.15
#Sta/Elev= 30
  4778.1  353.72  4789.3  353.30  4809.5  351.55  4829.0  350.74  4839.8  349.08
  4849.9  348.52  4860.0  348.92  4870.1  347.60  4917.5  345.44  4940.7  345.12
  4950.8  344.49  4960.9  344.33  4971.0  344.35  4984.1  345.00  4990.1  344.39
  5001.2  344.56  5009.2  343.67  5009.5  343.17  5013.0  343.17  5013.2  343.67
  5021.2  344.80  5041.2  345.08  5081.3  347.87  5101.3  347.89  5111.3  348.56
  5121.3  348.29  5141.3  349.05  5151.3  349.11  5175.1  351.05  5177.8  351.27
#Mann=5,-1,0
  4778.1    0.12       0  4917.5     0.1       0  5009.2    0.07       0
  5013.2     0.1       0  5175.1    0.05       0
Bank Sta=5009.2,5013.2
Exp/Cntr=0.3,0.1

Type RM Length L Ch R = 1,12969,88,88,88
BEGIN DESCRIPTION:
Lacy 183 374
END DESCRIPTION:
XS GIS Cut Line= 3
      2695033.50      6822955.06      2695279.10      6823012.51
      2695492.13      6823034.52
#Sta/Elev= 30
  4747.0  357.06  4759.8  355.57  4780.4  354.34  4800.9  351.57  4811.2  351.82
  4837.9  350.27  4843.0  350.35  4852.3  348.67  4872.8  347.32  4880.4  347.52
  4934.4  344.18  4983.4  342.62  4995.1  341.15  5006.2  341.53  5014.2  340.91
  5014.5  340.41  5018.0  340.41  5018.2  340.91  5026.3  342.44  5032.2  343.07
  5037.3  342.53  5046.4  342.80  5086.6  344.32  5096.6  345.31  5126.1  346.56
  5130.4  346.29  5136.9  346.78  5146.9  346.56  5157.0  346.86  5213.4  349.55
#Mann=5,-1,0
  4747.0    0.12       0  4983.4     0.1       0  5014.2    0.07       0
  5018.2     0.1       0  5130.4    0.12       0
Bank Sta=5014.2,5018.2
Exp/Cntr=0.3,0.1

Type RM Length L Ch R = 1,12881,153,153,153
BEGIN DESCRIPTION:
Lacy 183 373
END DESCRIPTION:
XS GIS Cut Line= 3
      2695011.93      6822996.12      2695280.02      6823102.58
      2695549.47      6823146.72
#Sta/Elev= 30
  4718.4  354.71  4742.0  353.84  4765.8  352.11  4808.9  347.19  4825.7  347.63
  4831.1  346.80  4873.4  345.05  4885.1  343.79  4909.4  342.76  4916.5  341.89
  4933.7  341.87  4939.1  341.20  4958.0  341.57  4981.0  340.11  4995.7  339.91
  5006.9  340.29  5012.9  339.79  5026.1  336.21  5026.3  335.71  5029.8  335.71
  5030.1  336.21  5033.2  338.38  5043.3  340.70  5063.6  341.02  5089.4  342.68
  5162.1  343.61  5195.3  344.51  5212.1  345.56  5217.1  345.09  5279.9  346.93
#Mann=5,-1,0
  4718.4    0.12       0  4995.7     0.1       0  5026.1    0.07       0
  5030.1     0.1       0  5162.1    0.12       0
Bank Sta=5026.1,5030.1
Exp/Cntr=0.3,0.1

Type RM Length L Ch R = 1,12728,159,159,159
BEGIN DESCRIPTION:
Lacy 183 372
END DESCRIPTION:
XS GIS Cut Line= 3
      2694966.59      6823185.61      2695262.53      6823226.87
      2695496.53      6823280.62
#Sta/Elev= 30
  4704.5  340.88  4714.0  340.03  4744.3  340.22  4754.4  339.35  4779.7  339.65
  4784.7  338.92  4804.9  338.46  4815.0  337.73  4835.2  338.32  4885.6  337.77
  4915.9  338.13  4936.1  337.08  4946.2  337.38  4967.9  336.93  5007.7  337.50
  5015.1  333.60  5015.4  333.10  5018.9  333.10  5019.1  333.60  5027.4  338.22
  5037.6  337.76  5043.4  338.18  5048.6  337.29  5058.2  337.11  5150.5  339.31
  5182.3  339.04  5212.1  340.08  5222.4  339.90  5225.1  339.56  5243.4  340.17
#Mann=5,-1,0
  4704.5    0.12       0  4967.9     0.1       0  5015.1    0.07       0
  5019.1     0.1       0  5222.4    0.12       0
Bank Sta=5015.1,5019.1
Exp/Cntr=0.3,0.1

Type RM Length L Ch R = 1,12569,194,194,194
BEGIN DESCRIPTION:
Lacy 183 371
END DESCRIPTION:
XS GIS Cut Line= 3
      2694980.50      6823220.57      2695236.16      6823354.43
      2695477.01      6823363.29
#Sta/Elev= 30
  4711.7  337.87  4723.5  337.22  4739.9  337.43  4751.8  336.73  4762.0  336.87
  4774.3  336.02  4789.7  336.33  4811.7  335.28  4828.2  335.53  4842.1  334.81
  4872.3  335.08  4887.2  333.93  4894.4  329.80  4900.0  332.46  4909.8  332.93
  4922.1  334.71  4948.7  334.90  4977.0  334.68  4988.8  334.08  4997.4  334.51
  5010.1  334.14  5018.1  329.47  5018.4  328.97  5021.9  328.97  5022.1  329.47
  5039.0  334.43  5060.2  334.47  5090.2  335.60  5190.3  337.27  5241.3  339.20
#Mann=4,-1,0
  4711.7    0.12       0  4948.7     0.1       0  5018.1    0.07       0
  5022.1     0.1       0
Bank Sta=5018.1,5022.1
Exp/Cntr=0.3,0.1

Type RM Length L Ch R = 1,12375,218,218,218
BEGIN DESCRIPTION:
Lacy 183 370
END DESCRIPTION:
XS GIS Cut Line= 3
      2694910.75      6823182.59      2695132.62      6823514.90
      2695608.85      6823515.18
#Sta/Elev= 30
  4608.1  340.81  4618.2  340.47  4625.4  338.74  4718.5  335.35  4733.5  333.75
  4784.6  332.58  4790.6  333.04  4805.6  331.53  4811.6  332.24  4841.7  330.46
  4902.9  329.96  4913.8  329.49  4919.8  327.47  4926.8  327.08  4927.0  326.58
  4930.8  327.08  4949.8  328.06  4955.8  329.44  5000.9  327.30  5006.2  328.60
  5021.0  329.39  5101.0  332.45  5161.0  333.54  5181.0  332.98  5201.0  334.41
  5221.0  333.85  5261.0  334.88  5291.0  334.28  5421.0  338.20  5483.9  339.01
#Mann=4,-1,0
  4608.1    0.12       0  4902.9     0.1       0  4926.8    0.07       0
  4930.8     0.1       0
Bank Sta=4926.8,4930.8
Exp/Cntr=0.3,0.1

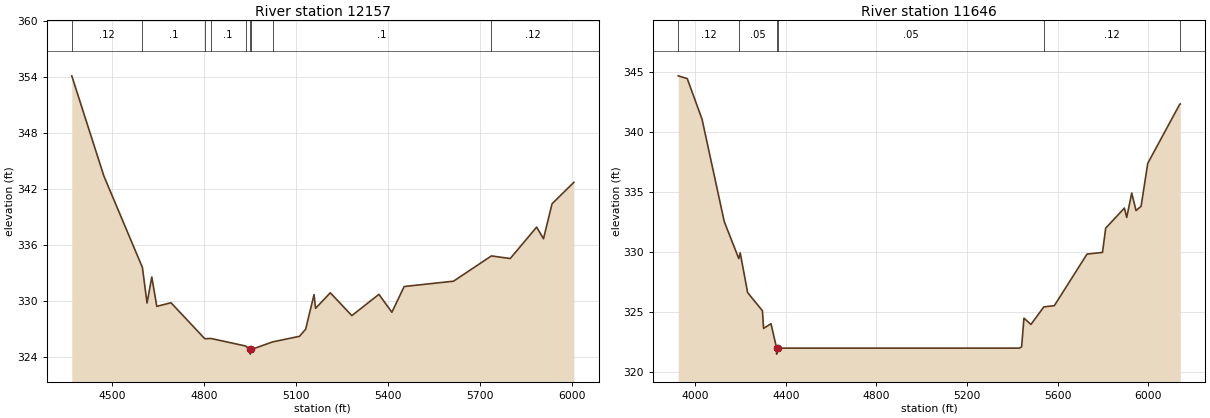
Type RM Length L Ch R = 1,12157,511,511,511
BEGIN DESCRIPTION:
Lacy 183 369
END DESCRIPTION:
XS GIS Cut Line= 3
      2694746.46      6823038.72      2694949.25      6823630.28
      2695956.80      6823725.59
#Sta/Elev= 30
  4368.4  354.10  4473.1  343.36  4598.8  333.55  4613.9  329.74  4629.4  332.53
  4645.7  329.38  4692.0  329.77  4802.3  325.91  4822.1  325.94  4935.3  325.13
  4950.2  324.76  4950.5  324.26  4954.2  324.76  5023.3  325.57  5111.0  326.17
  5131.1  326.93  5158.5  330.64  5163.5  329.17  5211.5  330.84  5281.8  328.39
  5370.1  330.67  5412.4  328.75  5452.5  331.51  5613.3  332.08  5736.9  334.79
  5798.4  334.51  5884.5  337.88  5906.8  336.63  5934.7  340.38  6005.8  342.68
#Mann=9,-1,0
  4368.4    0.12       0  4598.8     0.1       0  4802.3    0.12       0
  4822.1     0.1       0  4935.3    0.05       0  4950.2    0.03       0
  4954.2    0.05       0  5023.3     0.1       0  5736.9    0.12       0
Bank Sta=4950.2,4954.2
Exp/Cntr=0.3,0.1

Type RM Length L Ch R = 1,11646,0,0,0
BEGIN DESCRIPTION:
Lacy 183 368
END DESCRIPTION:
XS GIS Cut Line= 3
      2694570.39      6823024.33      2694886.95      6824049.69
      2695995.47      6823773.22
#Sta/Elev= 30
  3925.6  344.65  3965.4  344.42  4030.7  341.04  4128.6  332.53  4192.8  329.45
  4199.2  329.92  4231.8  326.62  4297.1  325.11  4302.3  323.64  4335.0  324.03
  4359.7  322.00  4359.9  321.50  4363.7  322.00  5431.5  322.00  5440.9  322.11
  5451.2  324.49  5482.1  323.97  5539.0  325.43  5585.2  325.53  5729.5  329.82
  5797.8  329.96  5811.9  331.98  5894.4  333.65  5904.7  332.87  5926.8  334.90
  5945.9  333.44  5968.1  333.80  5997.5  337.37  6138.5  342.28  6141.2  342.31
#Mann=6,-1,0
  3925.6    0.12       0  4192.8    0.05       0  4359.7    0.03       0
  4363.7    0.05       0  5539.0    0.12       0  6138.5     0.1       0
Bank Sta=4359.7,4363.7
Exp/Cntr=0.3,0.1

Chan Stop Cuts=-1