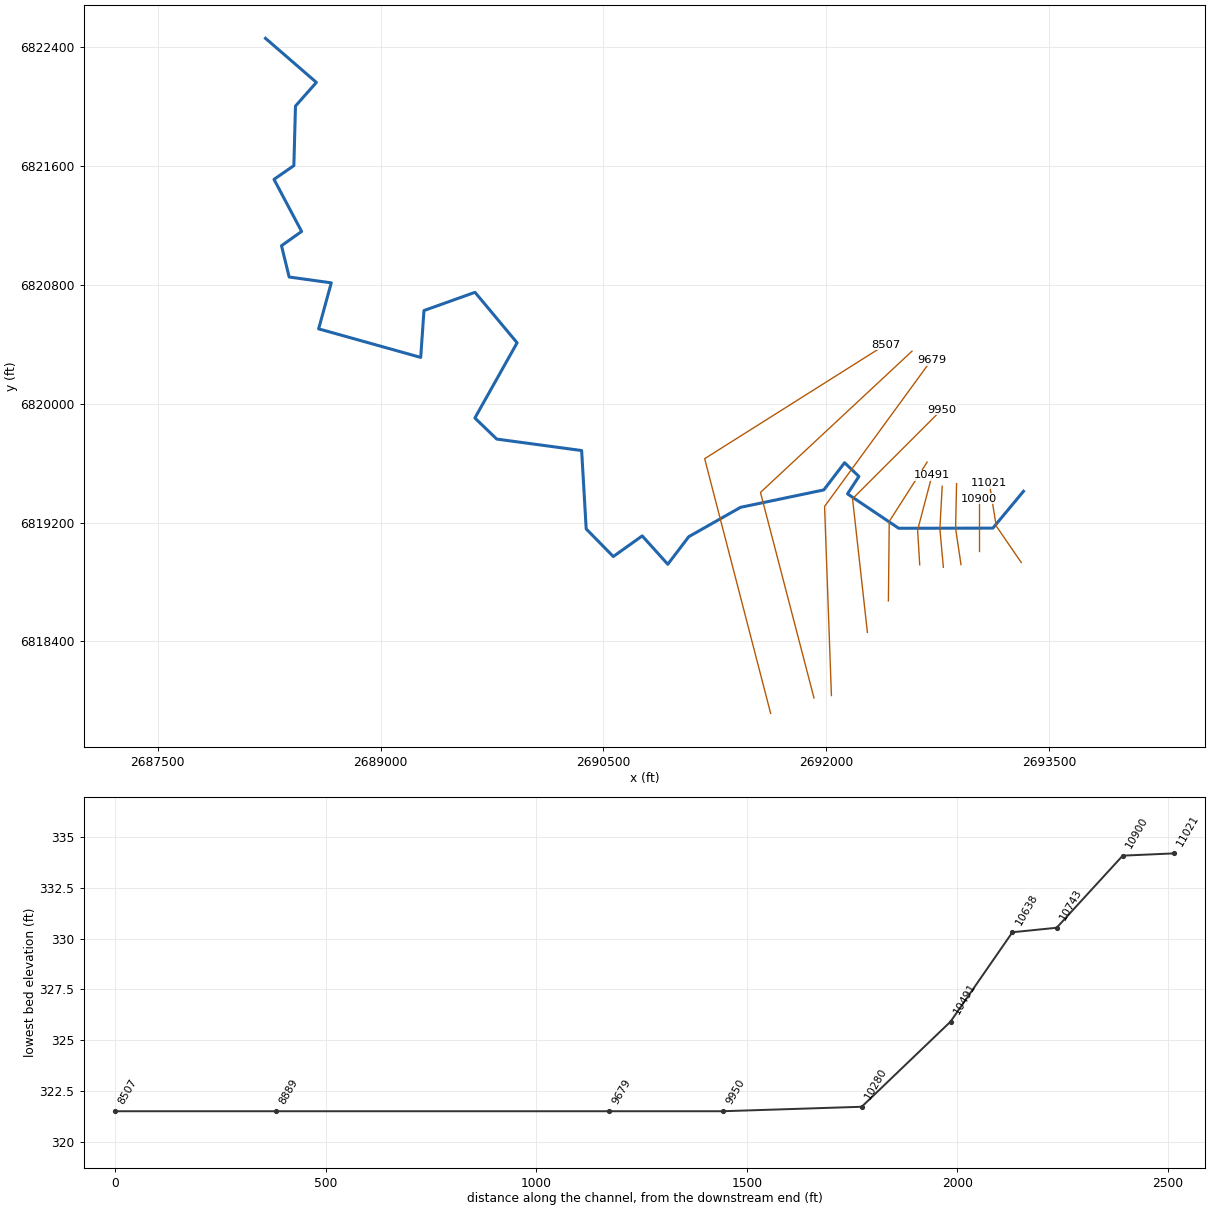
--- Lacy 184.prj (project) ---

Proj Title=Lacy 184 Base Level Engineering
Current Plan=p01
Default Exp/Contr=0.3,0.1
English Units
Geom File=g01
Flow File=f01
Plan File=p01
BEGIN DESCRIPTION:
Lacy 184
END DESCRIPTION:

--- Lacy 184.p01 (plan) ---

Plan Title=Multiple Run
Short Identifier=Multiple
Geom File=g01
Flow File=f01
Subcritical Flow
K Sum by GR= 0
Std Step Tol= 0.01
Critical Tol= 0.01
Num of Std Step Trials= 20
Max Error Tol= 0.3
Flow Tol Ratio= 0.001
Split Flow NTrial= 30
Split Flow Tol= 0.02
Split Flow Ratio= 0.02
Log Output Level= 0
Friction Slope Method= 1
Unsteady Friction Slope Method= 2
Unsteady Bridges Friction Slope Method= 1
Parabolic Critical Depth
Global Vel Dist=  1 , 1 , 1
Global Log Level= 0
CheckData=True
Encroach Param= -1, 0, 0, 0
BEGIN DESCRIPTION:
Multiple Run
END DESCRIPTION:

--- Lacy 184.f01 (steady flow) ---

Flow Title=Multiple
Number of Profiles=7
Profile Names=10-year,25-year,50-year,1pct_min,100-year,1pct_plu,500-year
River Rch & RM= Lacy 184,Reach-1,11021
     404     522     614     357     713    1423     962
Boundary for River Rch & Prof#=Lacy 184,Reach-1,1
Up Type=0
Dn Type=3
Dn Slope=0.005
Boundary for River Rch & Prof#=Lacy 184,Reach-1,2
Up Type=0
Dn Type=3
Dn Slope=0.005
Boundary for River Rch & Prof#=Lacy 184,Reach-1,3
Up Type=0
Dn Type=3
Dn Slope=0.005
Boundary for River Rch & Prof#=Lacy 184,Reach-1,4
Up Type=0
Dn Type=3
Dn Slope=0.005
Boundary for River Rch & Prof#=Lacy 184,Reach-1,5
Up Type=0
Dn Type=3
Dn Slope=0.005
Boundary for River Rch & Prof#=Lacy 184,Reach-1,6
Up Type=0
Dn Type=3
Dn Slope=0.005
Boundary for River Rch & Prof#=Lacy 184,Reach-1,7
Up Type=0
Dn Type=3
Dn Slope=0.005

--- Lacy 184.g01 (geometry) ---

Geom Title=Existing Conditions

River Reach=Lacy 184,Reach-1
Reach XY= 30
      2693326.00      6819411.00      2693120.16      6819163.05
      2692486.43      6819162.04      2692142.01      6819393.87
      2692218.90      6819511.02      2692122.44      6819603.52
      2691982.68      6819420.30      2691422.42      6819303.11
      2691073.70      6819105.20      2690932.80      6818919.77
      2690760.78      6819110.77      2690566.13      6818971.90
      2690383.82      6819157.59      2690353.17      6819685.48
      2689782.03      6819762.62      2689634.89      6819904.49
      2689918.93      6820411.00      2689635.70      6820750.81
      2689292.23      6820628.04      2689270.35      6820312.58
      2688583.48      6820504.91      2688668.51      6820814.62
      2688385.18      6820853.95      2688333.67      6821064.66
      2688469.01      6821160.79      2688283.20      6821511.30
      2688416.83      6821604.05      2688427.66      6822004.95
      2688568.41      6822164.33      2688226.00      6822461.00

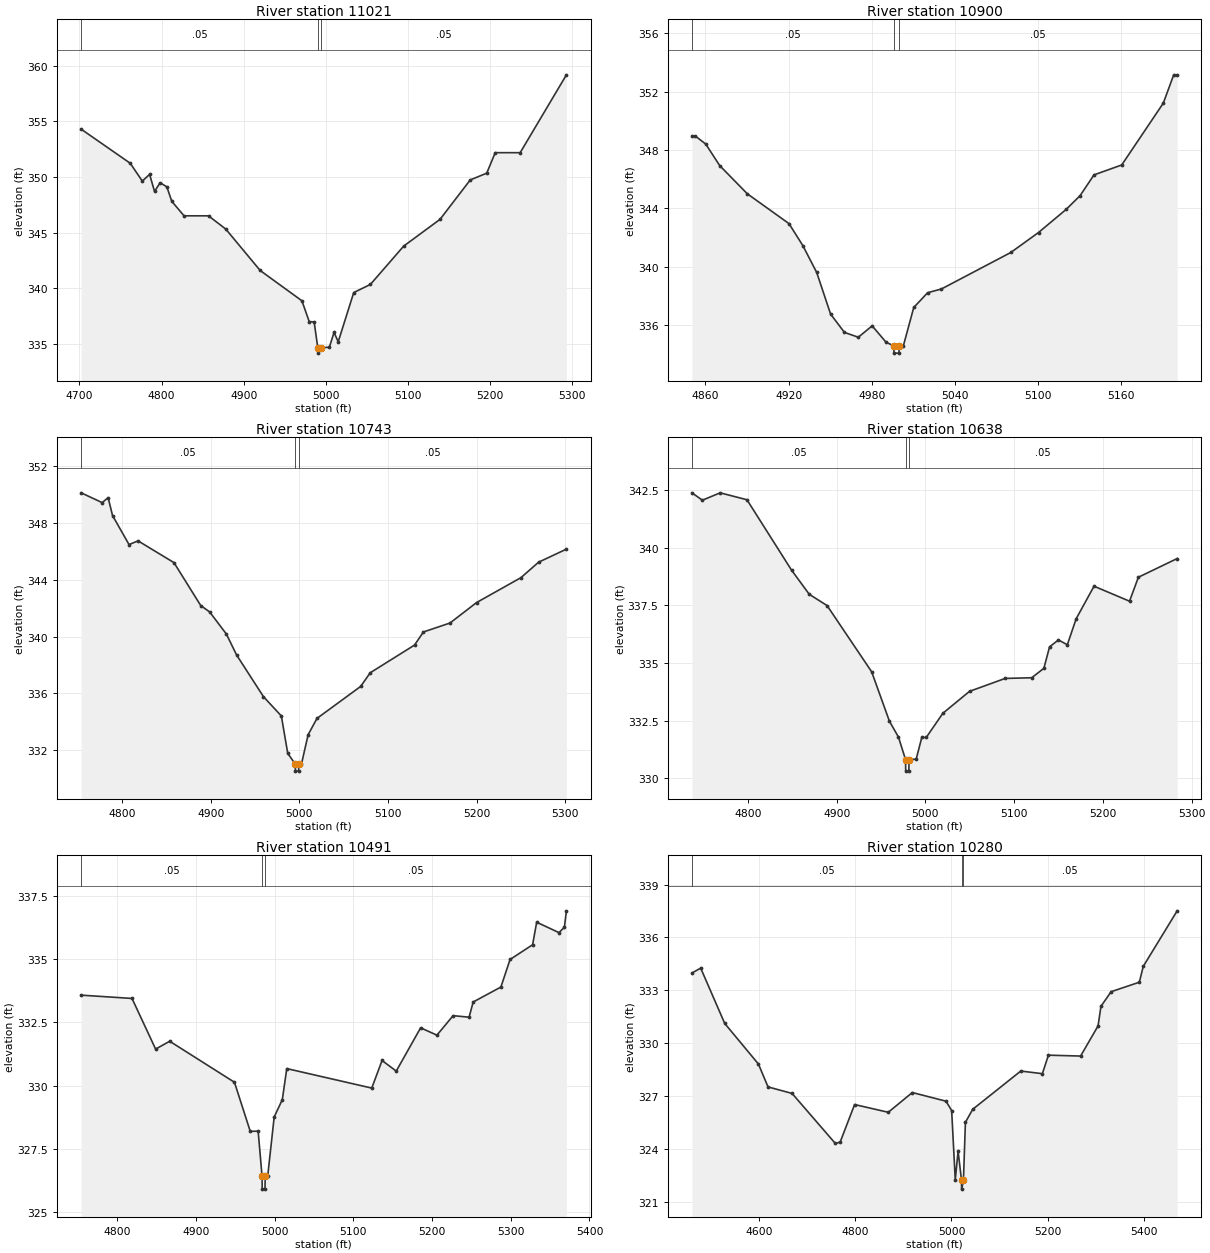
Type RM Length L Ch R = 1,11021,121,121,121
BEGIN DESCRIPTION:
Lacy 184 367
END DESCRIPTION:
XS GIS Cut Line= 3
      2693311.13      6818931.76      2693142.80      6819177.42
      2693096.40      6819466.62
#Sta/Elev= 30
  4702.2  354.30  4761.9  351.24  4776.6  349.64  4785.5  350.24  4791.5  348.71
  4798.3  349.49  4806.5  349.12  4812.5  347.82  4827.4  346.52  4857.2  346.52
  4878.2  345.33  4920.1  341.61  4970.9  338.89  4979.8  337.02  4985.8  336.99
  4990.2  334.69  4990.5  334.19  4994.2  334.69  5004.3  334.71  5010.0  336.05
  5015.1  335.21  5034.0  339.63  5054.3  340.36  5094.8  343.80  5139.0  346.20
  5175.8  349.74  5195.9  350.35  5206.2  352.19  5236.6  352.19  5292.9  359.18
#Mann=3,-1,0
  4702.2    0.05       0  4990.2    0.05       0  4994.2    0.05       0
Bank Sta=4990.2,4994.2
Exp/Cntr=0.3,0.1

Type RM Length L Ch R = 1,10900,157,157,157
BEGIN DESCRIPTION:
Lacy 184 55
END DESCRIPTION:
XS GIS Cut Line= 3
      2693026.00      6819010.95      2693026.00      6819161.00
      2693026.00      6819360.95
#Sta/Elev= 30
  4850.3  348.96  4852.8  348.96  4860.3  348.41  4870.3  346.94  4890.3  345.00
  4920.3  342.96  4930.3  341.45  4940.3  339.61  4950.3  336.76  4960.3  335.50
  4970.3  335.17  4980.3  335.95  4990.3  334.83  4995.8  334.58  4996.1  334.08
  4999.6  334.08  4999.8  334.58  5002.8  334.58  5010.3  337.21  5020.3  338.22
  5030.3  338.48  5080.3  340.98  5100.3  342.35  5120.3  343.94  5130.3  344.88
  5140.3  346.30  5160.3  346.98  5190.3  351.22  5197.8  353.16  5200.3  353.16
#Mann=3,-1,0
  4850.3    0.05       0  4995.8    0.05       0  4999.8    0.05       0
Bank Sta=4995.8,4999.8
Exp/Cntr=0.3,0.1

Type RM Length L Ch R = 1,10743,105,105,105
BEGIN DESCRIPTION:
Lacy 184 366
END DESCRIPTION:
XS GIS Cut Line= 3
      2692905.71      6818917.55      2692869.41      6819160.90
      2692875.91      6819462.39
#Sta/Elev= 30
  4753.8  350.11  4777.5  349.42  4784.2  349.77  4789.2  348.51  4807.8  346.47
  4818.0  346.73  4858.5  345.20  4888.7  342.18  4898.8  341.73  4917.7  340.17
  4929.2  338.70  4959.5  335.77  4979.7  334.41  4986.9  331.78  4995.4  331.03
  4995.6  330.53  4999.1  330.53  4999.4  331.03  5002.4  331.03  5009.9  333.09
  5019.9  334.24  5069.2  336.49  5080.0  337.45  5130.0  339.40  5140.0  340.32
  5170.0  340.95  5200.0  342.39  5250.0  344.14  5270.0  345.23  5301.4  346.15
#Mann=3,-1,0
  4753.8    0.05       0  4995.4    0.05       0  4999.4    0.05       0
Bank Sta=4995.4,4999.4
Exp/Cntr=0.3,0.1

Type RM Length L Ch R = 1,10638,147,147,147
BEGIN DESCRIPTION:
Lacy 184 365
END DESCRIPTION:
XS GIS Cut Line= 3
      2692787.06      6818899.29      2692763.63      6819158.54
      2692779.29      6819444.61
#Sta/Elev= 30
  4736.9  342.38  4748.7  342.06  4768.7  342.38  4798.9  342.08  4849.1  339.03
  4869.1  337.98  4889.2  337.49  4939.4  334.62  4959.5  332.47  4969.6  331.79
  4977.6  330.81  4977.8  330.31  4981.3  330.31  4981.6  330.81  4989.6  330.83
  4995.9  331.77  5000.9  331.77  5019.7  332.82  5049.7  333.77  5089.8  334.33
  5119.8  334.36  5133.5  334.77  5139.9  335.70  5149.9  336.00  5159.9  335.79
  5169.9  336.92  5190.0  338.33  5230.0  337.68  5240.0  338.72  5283.7  339.53
#Mann=3,-1,0
  4736.9    0.05       0  4977.6    0.05       0  4981.6    0.05       0
Bank Sta=4977.6,4981.6
Exp/Cntr=0.3,0.1

Type RM Length L Ch R = 1,10491,211,211,211
BEGIN DESCRIPTION:
Lacy 184 364
END DESCRIPTION:
XS GIS Cut Line= 3
      2692627.91      6818916.53      2692613.88      6819150.00
      2692711.22      6819520.22
#Sta/Elev= 30
  4754.0  333.57  4818.6  333.44  4848.6  331.44  4866.5  331.75  4948.8  330.13
  4968.9  328.19  4978.9  328.20  4983.9  326.41  4984.1  325.91  4987.6  325.91
  4987.9  326.41  4991.0  326.41  4999.3  328.76  5009.6  329.44  5015.3  330.67
  5123.3  329.90  5136.4  330.99  5154.4  330.57  5185.4  332.28  5206.1  331.99
  5226.7  332.76  5247.0  332.70  5252.2  333.30  5287.4  333.89  5299.1  334.98
  5327.7  335.56  5332.9  336.45  5361.2  336.04  5368.1  336.25  5370.7  336.90
#Mann=3,-1,0
  4754.0    0.05       0  4983.9    0.05       0  4987.9    0.05       0
Bank Sta=4983.9,4987.9
Exp/Cntr=0.3,0.1

Type RM Length L Ch R = 1,10280,330,330,330
BEGIN DESCRIPTION:
Lacy 184 363
END DESCRIPTION:
XS GIS Cut Line= 3
      2692417.27      6818672.82      2692422.96      6819208.08
      2692677.77      6819607.31
#Sta/Elev= 30
  4460.4  333.98  4478.6  334.26  4528.6  331.12  4598.6  328.82  4618.6  327.52
  4668.6  327.15  4758.6  324.31  4768.6  324.39  4798.6  326.52  4868.6  326.08
  4918.6  327.20  4988.6  326.71  5000.4  326.18  5007.9  322.25  5013.8  323.88
  5020.9  322.22  5021.1  321.72  5024.9  322.22  5029.0  325.51  5044.2  326.25
  5144.1  328.42  5189.0  328.27  5201.6  329.32  5268.5  329.27  5304.8  330.98
  5310.8  332.09  5331.9  332.92  5390.6  333.46  5398.8  334.36  5469.3  337.51
#Mann=3,-1,0
  4460.4    0.05       0  5020.9    0.05       0  5024.9    0.05       0
Bank Sta=5020.9,5024.9
Exp/Cntr=0.3,0.1

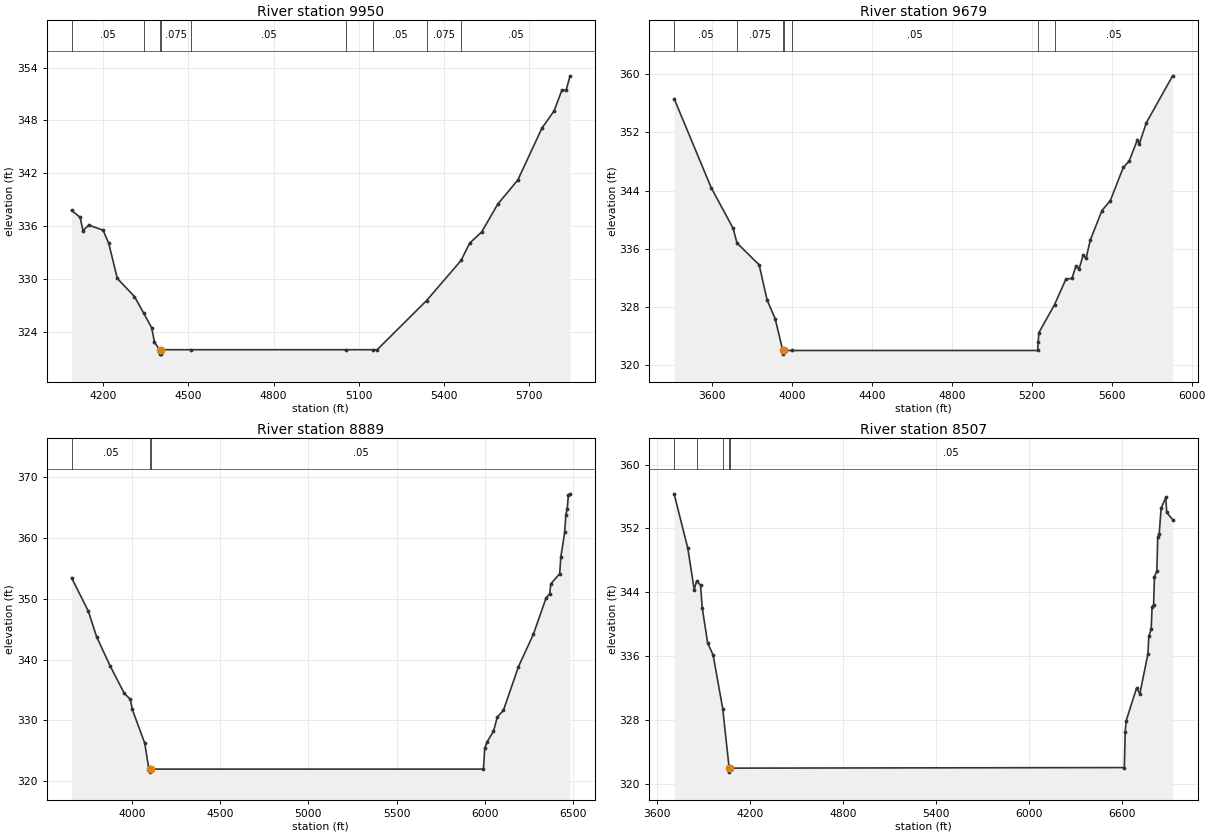
Type RM Length L Ch R = 1,9950,271,271,271
BEGIN DESCRIPTION:
Lacy 184 54
END DESCRIPTION:
XS GIS Cut Line= 3
      2692276.00      6818461.04      2692176.00      6819361.00
      2692775.98      6819960.98
#Sta/Elev= 30
  4089.0  337.80  4119.1  337.01  4129.2  335.50  4149.3  336.13  4199.6  335.56
  4219.8  334.06  4249.9  330.08  4310.3  328.03  4343.3  326.11  4370.7  324.50
  4380.7  322.83  4398.9  322.00  4399.1  321.50  4402.6  321.50  4402.9  322.00
  4507.9  322.00  5056.3  322.00  5148.6  322.00  5164.2  322.00  5338.2  327.58
  5459.6  332.13  5489.5  334.08  5531.9  335.35  5588.5  338.51  5659.2  341.25
  5744.0  347.13  5786.5  349.07  5814.7  351.47  5828.9  351.41  5843.0  353.06
#Mann=9,-1,0
  4089.0    0.05       0  4343.3   0.075       0  4398.9    0.03       0
  4402.9   0.075       0  4507.9    0.05       0  5056.3   0.075       0
  5148.6    0.05       0  5338.2   0.075       0  5459.6    0.05       0
Bank Sta=4398.9,4402.9
Exp/Cntr=0.3,0.1

Type RM Length L Ch R = 1,9679,790,790,790
BEGIN DESCRIPTION:
Lacy 184 362
END DESCRIPTION:
XS GIS Cut Line= 3
      2692033.85      6818035.64      2691987.80      6819309.20
      2692706.67      6820295.05
#Sta/Elev= 30
  3410.1  356.64  3595.6  344.39  3705.6  338.79  3724.6  336.78  3835.7  333.78
  3875.8  328.91  3915.8  326.37  3953.8  322.00  3954.1  321.50  3957.8  322.00
  3999.7  322.00  5229.1  322.00  5231.9  323.11  5235.3  324.45  5313.8  328.30
  5371.2  331.84  5400.6  331.90  5421.4  333.63  5436.1  333.18  5457.0  335.11
  5471.6  334.66  5492.5  337.16  5551.2  341.25  5592.9  342.60  5657.8  347.17
  5687.2  348.05  5728.9  351.00  5737.4  350.35  5772.9  353.30  5904.6  359.77
#Mann=7,-1,0
  3410.1    0.05       0  3724.6   0.075       0  3953.8    0.03       0
  3957.8   0.075       0  3999.7    0.05       0  5231.9   0.075       0
  5313.8    0.05       0
Bank Sta=3953.8,3957.8
Exp/Cntr=0.3,0.1

Type RM Length L Ch R = 1,8889,382,382,382
BEGIN DESCRIPTION:
Lacy 184 361
END DESCRIPTION:
XS GIS Cut Line= 3
      2691916.61      6818019.23      2691556.47      6819403.48
      2692575.97      6820354.44
#Sta/Elev= 30
  3658.4  353.47  3753.2  347.97  3799.8  343.80  3875.7  339.03  3956.7  334.47
  3990.9  333.49  4002.4  331.81  4073.1  326.24  4094.2  322.33  4102.5  322.00
  4102.8  321.50  4106.5  322.00  5992.1  322.00  5999.4  325.43  6013.6  326.52
  6048.8  328.20  6070.3  330.54  6105.4  331.68  6190.4  338.84  6275.5  344.21
  6346.2  350.08  6367.3  350.85  6374.1  352.47  6424.0  354.14  6430.8  356.96
  6452.3  360.93  6459.1  363.84  6466.5  364.72  6473.3  367.06  6482.9  367.27
#Mann=3,-1,0
  3658.4    0.05       0  4102.5    0.03       0  4106.5    0.05       0
Bank Sta=4102.5,4106.5
Exp/Cntr=0.3,0.1

Type RM Length L Ch R = 1,8507,0,0,0
BEGIN DESCRIPTION:
Lacy 184 360
END DESCRIPTION:
XS GIS Cut Line= 3
      2691624.91      6817915.75      2691180.98      6819630.63
      2692398.62      6820398.99
#Sta/Elev= 30
  3713.2  356.33  3801.3  349.53  3842.6  344.35  3858.0  345.41  3883.6  344.89
  3894.2  342.07  3929.3  337.67  3964.8  336.14  4026.3  329.45  4067.8  322.00
  4068.1  321.50  4071.8  322.00  6613.5  322.07  6619.4  326.58  6625.7  327.96
  6692.3  332.01  6713.5  331.31  6765.3  336.28  6771.2  338.48  6786.5  339.41
  6792.4  342.21  6801.8  342.43  6807.7  345.96  6822.9  346.68  6828.9  350.92
  6838.2  351.33  6850.4  354.54  6880.6  355.88  6886.5  354.00  6924.4  353.11
#Mann=5,-1,0
  3713.2    0.05       0  3858.0    0.12       0  4026.3    0.05       0
  4067.8    0.03       0  4071.8    0.05       0
Bank Sta=4067.8,4071.8
Exp/Cntr=0.3,0.1

Chan Stop Cuts=-1