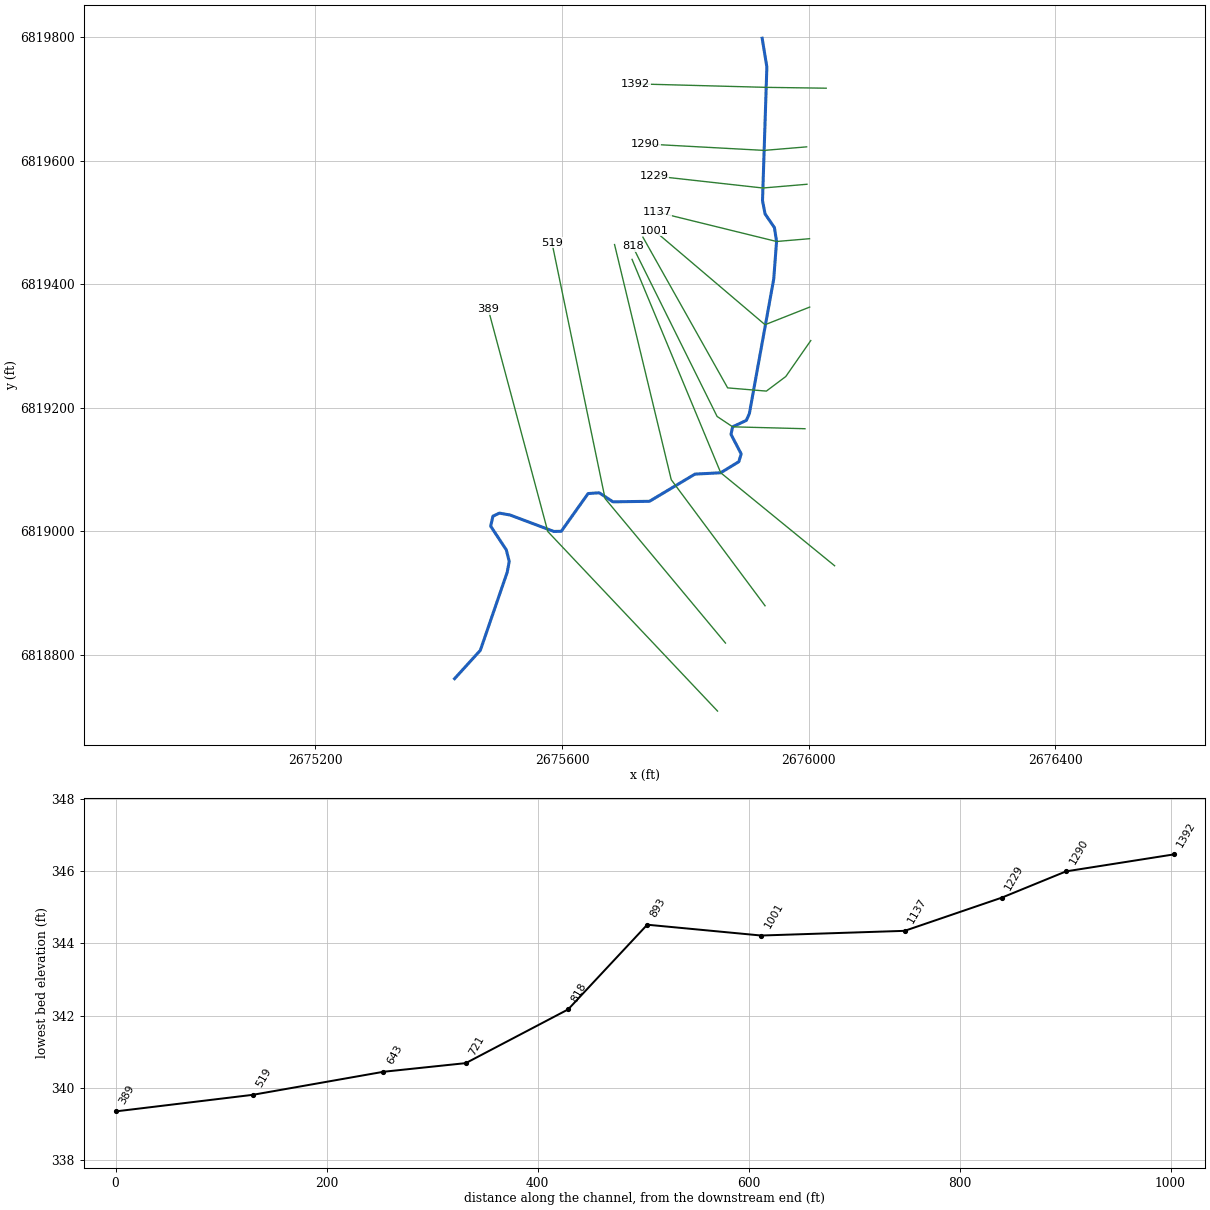
--- Lacy 189.prj (project) ---

Proj Title=Lacy 189 Base Level Engineering
Current Plan=p01
Default Exp/Contr=0.3,0.1
English Units
Geom File=g01
Flow File=f01
Plan File=p01
Y Axis Title=Elevation
X Axis Title(PF)=Main Channel Distance
X Axis Title(XS)=Station
BEGIN DESCRIPTION:
Lacy 189
END DESCRIPTION:
DSS Export Rating Curves= 0
DSS Export Rating Curve Sorted= 0
DSS Export Volume Flow Curves= 0
DXF OffsetX= 0
DXF OffsetY= 0
DXF ScaleX= 1
DXF ScaleY= 10

--- Lacy 189.p01 (plan) ---

Plan Title=Multiple Run
Short Identifier=Multiple
Geom File=g01
Flow File=f01
Subcritical Flow
K Sum by GR= 0
Std Step Tol= 0.01
Critical Tol= 0.01
Num of Std Step Trials= 20
Max Error Tol= 0.3
Flow Tol Ratio= 0.001
Split Flow NTrial= 30
Split Flow Tol= 0.02
Split Flow Ratio= 0.02
Log Output Level= 0
Friction Slope Method= 1
Unsteady Friction Slope Method= 2
Unsteady Bridges Friction Slope Method= 1
Parabolic Critical Depth
Global Vel Dist=  1 , 1 , 1
Global Log Level= 0
CheckData=True
Encroach Param= -1, 0, 0, 0
BEGIN DESCRIPTION:
Multiple Run
END DESCRIPTION:

--- Lacy 189.f01 (steady flow) ---

Flow Title=Multiple
Number of Profiles=7
Profile Names=10-year,25-year,50-year,1pct_min,100-year,1pct_plu,500-year
River Rch & RM= Lacy 189,Reach-1,1392
      92     107     117      64     128     255     151
Boundary for River Rch & Prof#=Lacy 189,Reach-1,1
Up Type=0
Dn Type=3
Dn Slope=0.005
Boundary for River Rch & Prof#=Lacy 189,Reach-1,2
Up Type=0
Dn Type=3
Dn Slope=0.005
Boundary for River Rch & Prof#=Lacy 189,Reach-1,3
Up Type=0
Dn Type=3
Dn Slope=0.005
Boundary for River Rch & Prof#=Lacy 189,Reach-1,4
Up Type=0
Dn Type=3
Dn Slope=0.005
Boundary for River Rch & Prof#=Lacy 189,Reach-1,5
Up Type=0
Dn Type=3
Dn Slope=0.005
Boundary for River Rch & Prof#=Lacy 189,Reach-1,6
Up Type=0
Dn Type=3
Dn Slope=0.005
Boundary for River Rch & Prof#=Lacy 189,Reach-1,7
Up Type=0
Dn Type=3
Dn Slope=0.005

--- Lacy 189.g01 (geometry) ---

Geom Title=Existing Conditions
Program Version=4.10

River Reach=Lacy 189        ,Reach-1
Reach XY= 30
      2675924.54      6819798.82      2675932.17      6819752.23
      2675925.13      6819535.61      2675929.28      6819514.06
      2675944.46      6819491.88      2675947.89      6819469.44
      2675943.33      6819408.73      2675903.81      6819190.47
      2675898.91      6819179.54      2675876.72      6819169.09
      2675874.04      6819156.91      2675890.54      6819125.24
      2675886.77       6819112.6       2675857.4      6819094.64
      2675815.55      6819092.43      2675741.91       6819048.4
      2675682.77      6819047.54       2675660.4      6819062.21
      2675642.42      6819060.95      2675598.92      6818999.82
       2675586.8      6818999.56      2675515.87       6819026.2
      2675498.69      6819029.24      2675488.14      6819024.25
      2675484.45      6819008.15      2675509.75      6818969.78
      2675514.57      6818950.84      2675511.28      6818933.45
      2675467.73      6818806.95        2675426.        6818761.

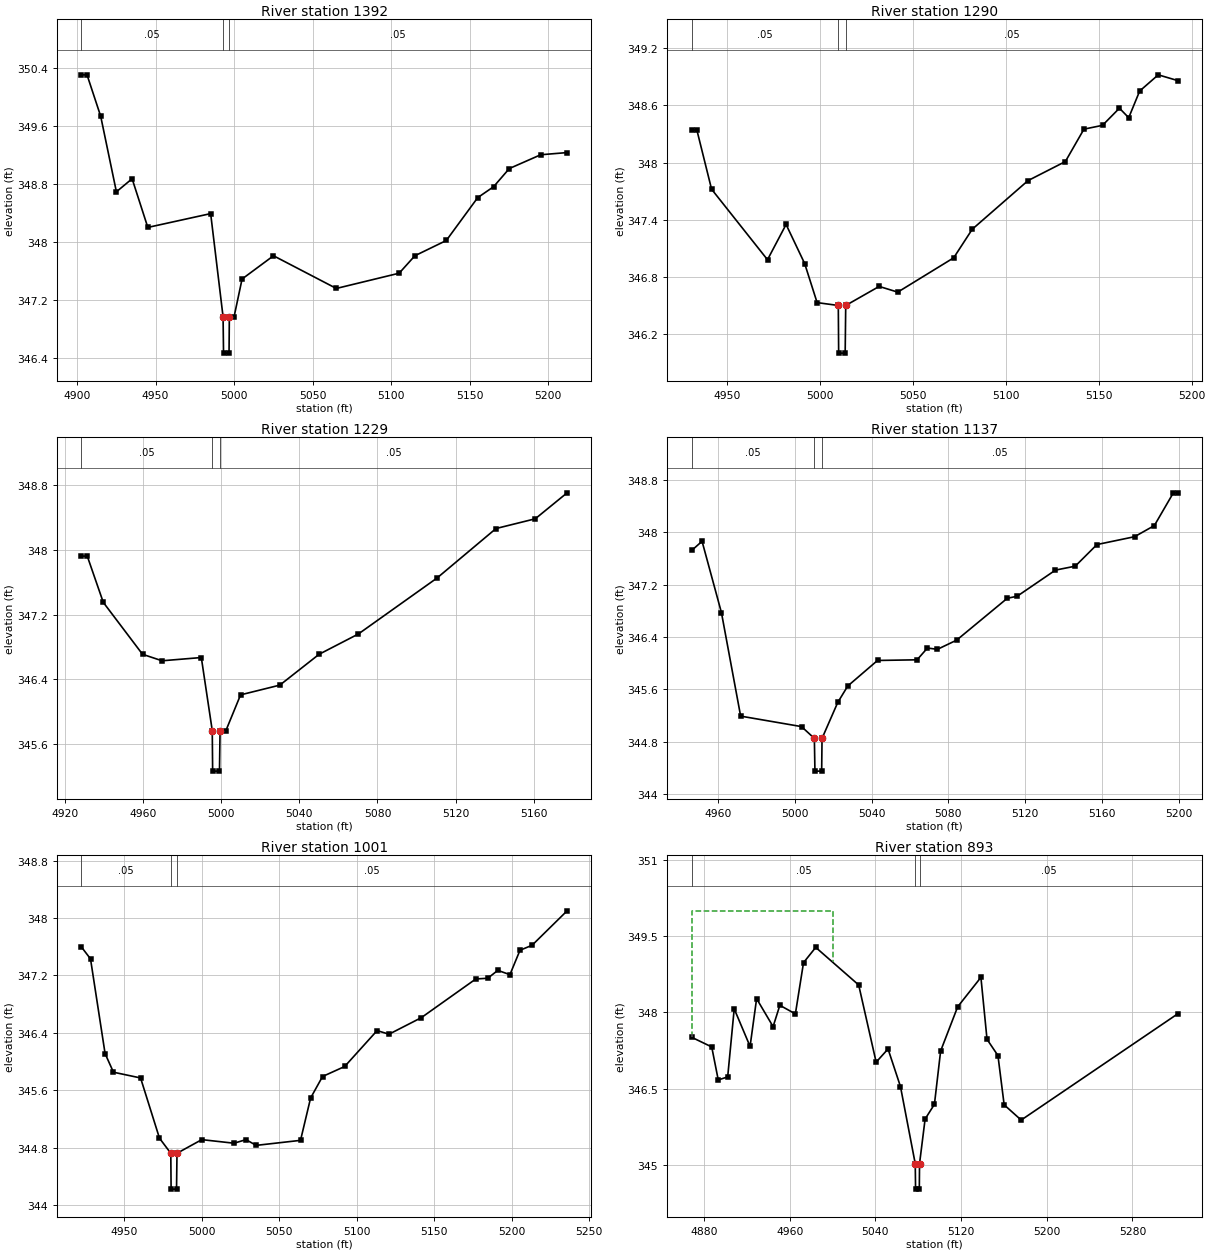
Type RM Length L Ch R = 1 ,1392    ,102,102,102
BEGIN DESCRIPTION:
Lacy 189 3464
END DESCRIPTION:
XS GIS Cut Line= 3
      2676028.38      6819717.84      2675931.09      6819719.21
      2675719.17      6819724.87
#Sta/Elev= 23
  4902.7   350.3  4906.4   350.3  4915.1  349.73  4925.1  348.69  4935.1  348.87
  4945.1   348.2  4985.1  348.39    4993  346.97  4993.3  346.47  4996.8  346.47
    4997  346.97    5000  346.97  5005.1  347.49  5025.1  347.81  5065.1  347.36
  5105.1  347.57  5115.1  347.81  5135.1  348.02  5155.1  348.61  5165.2  348.76
  5175.2  349.01  5195.2   349.2    5212  349.23
#Mann= 3 ,-1 , 0
  4902.7     .05       0    4993     .04       0    4997     .05       0
Bank Sta=4993,4997
XS Rating Curve= 0 ,0
Exp/Cntr=0.3,0.1

Type RM Length L Ch R = 1 ,1290    ,61,61,61
BEGIN DESCRIPTION:
Lacy 189 3463
END DESCRIPTION:
XS GIS Cut Line= 3
      2675996.64      6819622.77      2675927.78      6819617.05
      2675735.66      6819627.47
#Sta/Elev= 24
  4930.9  348.34  4933.7  348.34  4941.6  347.72  4971.7  346.98  4981.7  347.35
  4991.7  346.94  4998.4  346.53  5009.8   346.5    5010     346  5013.5     346
  5013.8   346.5  5031.8   346.7  5041.8  346.64  5071.9     347  5081.9   347.3
  5111.9  347.81    5132  348.01    5142  348.35    5152  348.39  5161.1  348.57
  5166.1  348.47    5172  348.75    5182  348.92  5192.4  348.86
#Mann= 3 ,-1 , 0
  4930.9     .05       0  5009.8     .04       0  5013.8     .05       0
Bank Sta=5009.8,5013.8
XS Rating Curve= 0 ,0
Exp/Cntr=0.3,0.1

Type RM Length L Ch R = 1 ,1229    ,92,92,92
BEGIN DESCRIPTION:
Lacy 189 3462
END DESCRIPTION:
XS GIS Cut Line= 3
      2675997.24      6819562.17       2675925.8      6819556.09
      2675749.78      6819575.66
#Sta/Elev= 19
  4928.3  347.92  4931.4  347.92  4939.6  347.35  4959.7  346.71  4969.7  346.63
  4989.8  346.67  4995.4  345.77  4995.6  345.27  4999.1  345.27  4999.4  345.77
  5002.4  345.77  5009.9  346.21    5030  346.33  5050.1  346.71  5070.2  346.96
  5110.5  347.65  5140.7  348.26  5160.8  348.38  5177.1   348.7
#Mann= 3 ,-1 , 0
  4928.3     .05       0  4995.4     .04       0  4999.4     .05       0
Bank Sta=4995.4,4999.4
XS Rating Curve= 0 ,0
Exp/Cntr=0.3,0.1

Type RM Length L Ch R = 1 ,1137    ,136,136,136
BEGIN DESCRIPTION:
Lacy 189 3461
END DESCRIPTION:
XS GIS Cut Line= 3
       2676001.4      6819473.95      2675947.89      6819469.44
      2675754.25      6819517.04
#Sta/Elev= 25
  4946.3  347.72  4951.7  347.86  4961.8  346.77  4971.8  345.19  5003.5  345.03
  5010.2  344.85  5010.5  344.35    5014  344.35  5014.2  344.85  5022.4   345.4
  5027.6  345.65  5043.1  346.04  5063.7  346.05  5069.1  346.23  5074.3  346.21
  5084.3  346.35  5110.7  346.99  5115.8  347.02  5135.8  347.42  5146.1  347.48
  5157.4  347.81    5177  347.93  5187.3   348.1  5197.2   348.6  5199.4   348.6
#Mann= 3 ,-1 , 0
  4946.3     .05       0  5010.2     .04       0  5014.2     .05       0
Bank Sta=5010.2,5014.2
XS Rating Curve= 0 ,0
Exp/Cntr=0.3,0.1

Type RM Length L Ch R = 1 ,1001    ,108,108,108
BEGIN DESCRIPTION:
Lacy 189 3460
END DESCRIPTION:
XS GIS Cut Line= 3
      2676001.61      6819363.13      2675929.25      6819334.55
      2675749.63      6819487.17
#Sta/Elev= 28
  4922.2   347.6  4928.2  347.43  4937.6  346.11    4943  345.85  4960.5  345.77
  4972.7  344.93    4980  344.72  4980.2  344.22  4983.7  344.22    4984  344.72
    5000  344.91  5020.8  344.86  5028.5  344.91  5035.1  344.83  5063.7   344.9
  5070.2  345.49  5077.9  345.79  5092.2  345.93  5113.1  346.43  5120.8  346.38
  5141.6  346.61  5176.8  347.15  5184.5  347.16    5191  347.27  5198.8  347.21
  5205.3  347.55  5213.1  347.62  5235.7   348.1
#Mann= 3 ,-1 , 0
  4922.2     .05       0    4980     .04       0    4984     .05       0
Bank Sta=4980,4984
XS Rating Curve= 0 ,0
Exp/Cntr=0.3,0.1

Type RM Length L Ch R = 1 ,893     ,75,75,75
BEGIN DESCRIPTION:
Lacy 189 3459
END DESCRIPTION:
XS GIS Cut Line= 5
      2676003.39      6819308.92       2675962.9      6819250.65
      2675931.39      6819226.99      2675868.61      6819232.19
      2675731.24      6819476.45
#Sta/Elev= 30
  4868.5  347.51  4887.2  347.32  4893.3  346.67  4902.1  346.73  4908.2  348.07
    4923  347.33  4929.1  348.27  4944.5  347.72  4950.8  348.14  4965.3  347.97
  4972.9  348.98  4984.3  349.28  5024.4  348.54  5040.7  347.02  5051.8  347.28
  5063.4  346.54  5077.2  345.02  5077.5  344.52    5081  344.52  5081.2  345.02
  5086.4   345.9  5095.1  346.19  5100.9  347.24  5116.8  348.11  5138.5  348.69
  5144.2  347.47  5154.4  347.15  5160.2  346.18  5176.1  345.88  5322.1  347.97
#Mann= 3 ,-1 , 0
  4868.5     .05       0  5077.2     .03       0  5081.2     .05       0
#XS Ineff= 2 , 0
       0    5000     350               0
Permanent Ineff=
       F       F
Bank Sta=5077.2,5081.2
XS Rating Curve= 0 ,0
Exp/Cntr=0.3,0.1

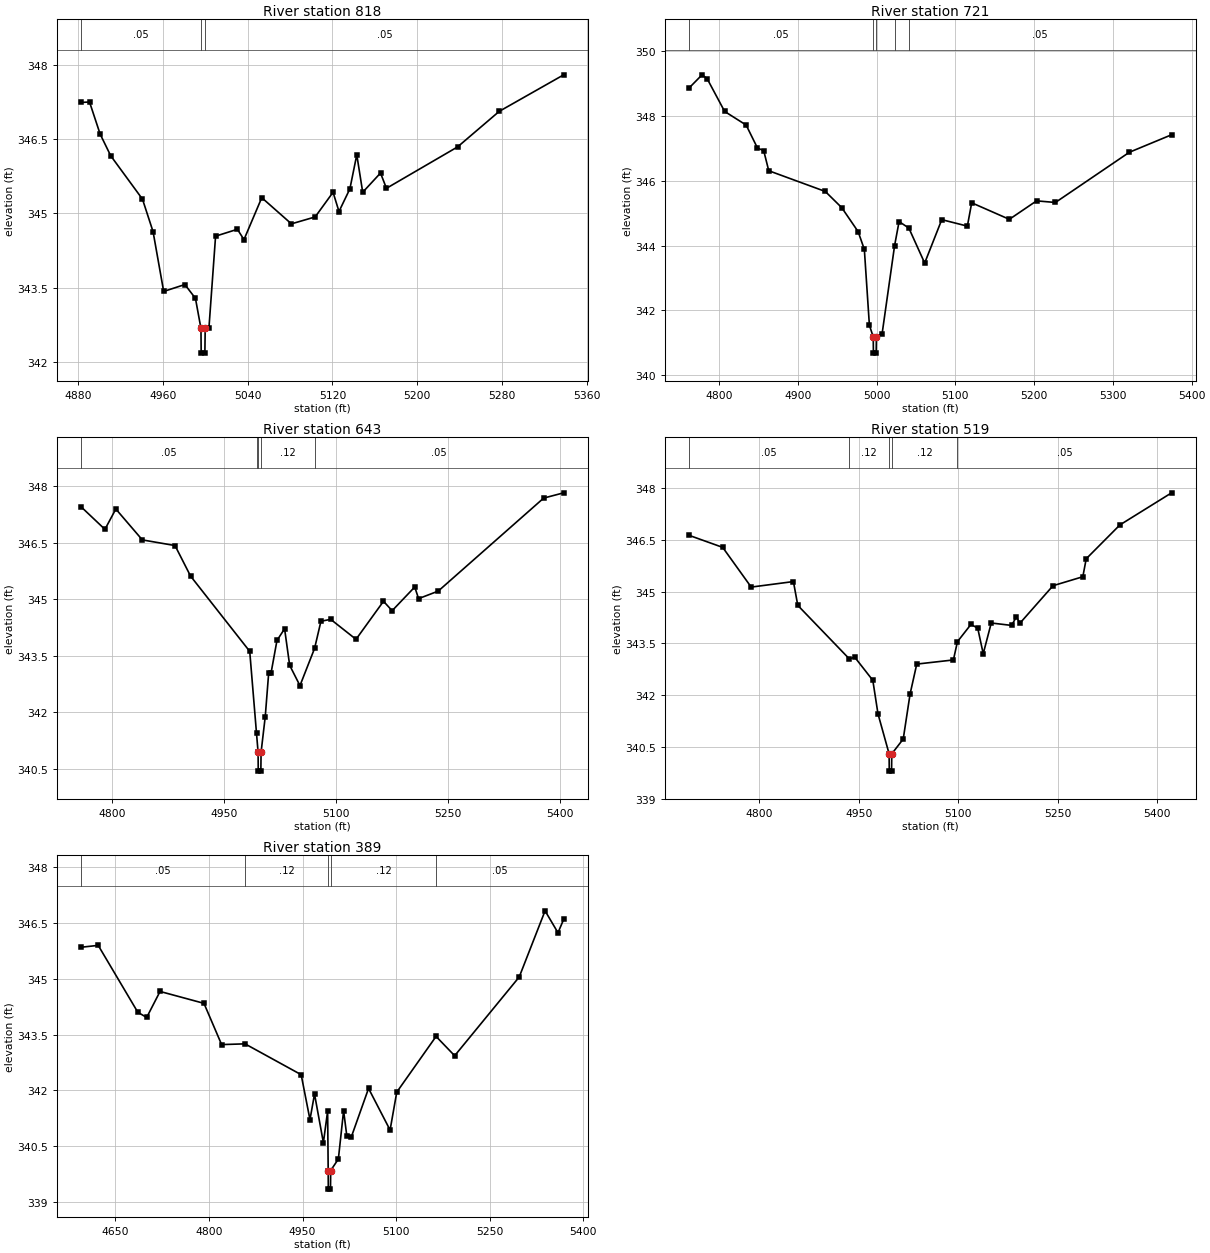
Type RM Length L Ch R = 1 ,818     ,97,97,97
BEGIN DESCRIPTION:
Lacy 189 3458
END DESCRIPTION:
XS GIS Cut Line= 4
      2675993.98      6819166.02      2675876.72      6819169.09
      2675851.52      6819185.88       2675714.6      6819461.79
#Sta/Elev= 30
  4882.7  347.25  4890.7  347.26  4900.7  346.61  4910.7  346.17  4940.7  345.29
  4950.7  344.63  4960.7  343.42  4980.7  343.56  4990.7  343.28  4995.9  342.67
  4996.1  342.17  4999.6  342.17  4999.9  342.67  5003.4  342.67  5009.7  344.54
  5030.3  344.68  5036.5  344.47  5053.3  345.32  5081.3  344.79  5103.7  344.93
  5120.6  345.43  5126.2  345.04  5136.5   345.5    5143  346.19  5148.6  345.43
  5165.4  345.82    5171  345.51  5238.2  346.35  5277.5  347.07  5338.3  347.81
#Mann= 3 ,-1 , 0
  4882.7     .05       0  4995.9     .03       0  4999.9     .05       0
Bank Sta=4995.9,4999.9
XS Rating Curve= 0 ,0
Exp/Cntr=0.3,0.1

Type RM Length L Ch R = 1 ,721     ,78,78,78
BEGIN DESCRIPTION:
Lacy 189 3457
END DESCRIPTION:
XS GIS Cut Line= 3
        2676042.      6818943.95       2675857.4      6819094.64
      2675713.66      6819440.46
#Sta/Elev= 30
  4761.7  348.86  4778.3  349.27  4784.8  349.15    4807  348.14  4834.3  347.72
  4848.7  347.01  4856.6  346.93    4863  346.31  4934.8  345.67  4955.7  345.17
  4976.5  344.43  4984.4  343.88  4990.8  341.54  4995.7  341.18  4995.9  340.68
  4999.4  340.68  4999.7  341.18  5006.9  341.27  5022.8     344  5028.5  344.74
  5040.9  344.54    5061  343.46  5082.7   344.8  5115.2   344.6  5120.7  345.32
  5168.5  344.81  5203.1  345.38    5227  345.33  5320.9  346.88  5374.5  347.42
#Mann= 5 ,-1 , 0
  4761.7     .05       0  4995.7     .03       0  4999.7     .05       0
  5022.8     .12       0  5040.9     .05       0
Bank Sta=4995.7,4999.7
XS Rating Curve= 0 ,0
Exp/Cntr=0.3,0.1

Type RM Length L Ch R = 1 ,643     ,124,124,124
BEGIN DESCRIPTION:
Lacy 189 322
END DESCRIPTION:
XS GIS Cut Line= 3
      2675929.23      6818879.14      2675777.19      6819083.36
       2675685.3      6819464.44
#Sta/Elev= 30
  4757.9  347.46  4789.9  346.86  4804.5   347.4    4840  346.58  4883.8  346.43
  4904.6  345.62  4983.9  343.62    4993  341.44  4995.1  340.94  4995.3  340.44
  4998.8  340.44  4999.1  340.94  5004.7  341.89  5009.3  343.05  5012.5  343.05
  5020.4  343.91  5030.6  344.22  5037.4  343.25  5051.2  342.71  5070.8   343.7
  5079.3  344.42  5092.4  344.47  5126.3  343.94  5163.1  344.95  5174.7   344.7
    5205  345.33  5210.1  345.02  5236.4  345.22  5377.7  347.69  5404.5  347.83
#Mann= 5 ,-1 , 0
  4757.9     .05       0    4993     .12       0  4995.1     .07       0
  4999.1     .12       0  5070.8     .05       0
Bank Sta=4995.1,4999.1
XS Rating Curve= 0 ,0
Exp/Cntr=0.3,0.1

Type RM Length L Ch R = 1 ,519     ,130,130,130
BEGIN DESCRIPTION:
Lacy 189 321
END DESCRIPTION:
XS GIS Cut Line= 3
      2675865.09      6818818.69      2675669.94      6819052.86
      2675583.83      6819467.39
#Sta/Elev= 30
  4693.7  346.63  4744.6  346.28  4787.6  345.13  4851.3  345.29  4857.9   344.6
  4935.7  343.05  4943.8   343.1  4971.1  342.43  4978.9  341.46  4995.7   340.3
  4995.9   339.8  4999.4   339.8  4999.7   340.3    5017  340.73  5027.3  342.03
  5037.4   342.9  5092.7  343.02  5098.8  343.55  5119.2  344.05  5129.4  343.94
  5137.7   343.2  5149.8  344.09  5180.5  344.02  5187.8  344.27  5192.9  344.08
    5243  345.17    5288  345.43  5293.1  345.95  5343.9  346.93  5421.9  347.86
#Mann= 5 ,-1 , 0
  4693.7     .05       0  4935.7     .12       0  4995.7     .07       0
  4999.7     .12       0  5098.8     .05       0
Bank Sta=4995.7,4999.7
XS Rating Curve= 0 ,0
Exp/Cntr=0.3,0.1

Type RM Length L Ch R = 1 ,389     ,0,0,0
BEGIN DESCRIPTION:
Lacy 189 3453
END DESCRIPTION:
XS GIS Cut Line= 3
      2675852.21      6818708.45      2675577.07      6818999.43
      2675480.52      6819359.76
#Sta/Elev= 30
    4595  345.85  4622.5   345.9    4686   344.1  4700.2  343.96  4721.6  344.66
    4792  344.34  4820.3  343.23  4857.8  343.25  4947.8  342.42  4961.9  341.21
  4969.2   341.9  4983.4  340.59  4990.2  341.44  4991.1  339.84  4991.3  339.34
  4994.8  339.34  4995.1  339.84  5007.4  340.15  5015.8  341.45  5020.9  340.78
  5028.1  340.74  5055.8  342.05  5090.3  340.93    5101  341.95    5164  343.45
  5193.8  342.93  5297.3  345.05  5338.7  346.83  5359.4  346.24  5368.5   346.6
#Mann= 5 ,-1 , 0
    4595     .05       0  4857.8     .12       0  4991.1     .07       0
  4995.1     .12       0    5164     .05       0
Bank Sta=4991.1,4995.1
XS Rating Curve= 0 ,0
Exp/Cntr=0.3,0.1

Chan Stop Cuts=-1
Use User Specified Reach Order=0
Composite Channel Slope=5