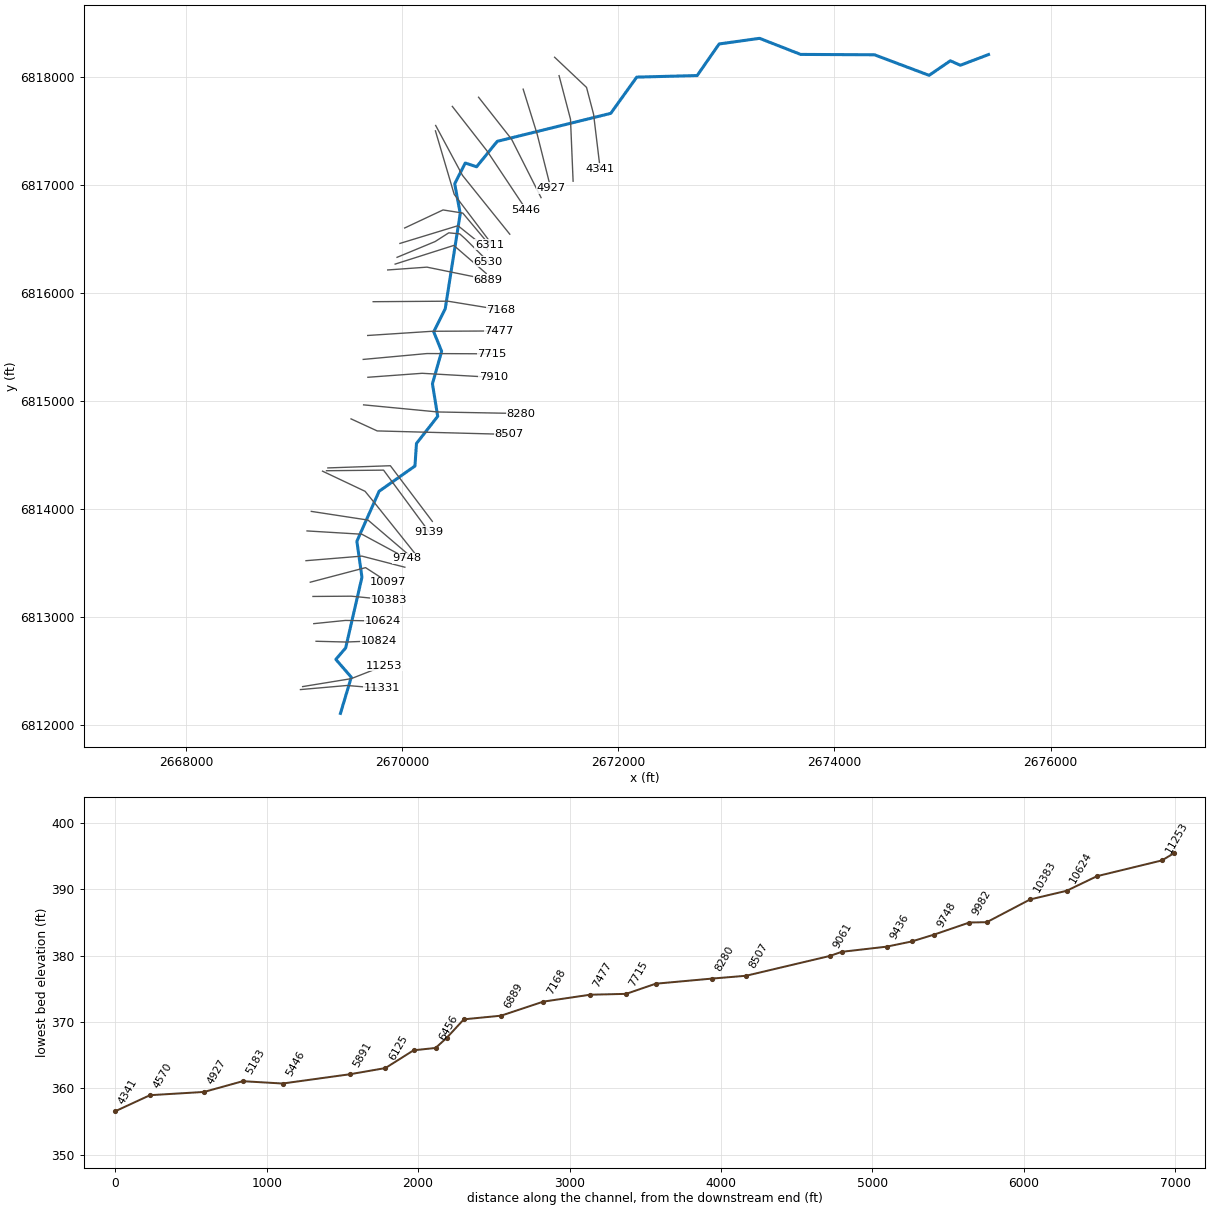
--- Lacy 190.prj (project) ---

Proj Title=Lacy 190 Base Level Engineering
Current Plan=p01
Default Exp/Contr=0.3,0.1
English Units
Geom File=g01
Flow File=f01
Plan File=p01
Y Axis Title=Elevation
X Axis Title(PF)=Main Channel Distance
X Axis Title(XS)=Station
BEGIN DESCRIPTION:
Lacy 190
END DESCRIPTION:
DSS Export Rating Curves= 0
DSS Export Rating Curve Sorted= 0
DSS Export Volume Flow Curves= 0
DXF OffsetX= 0
DXF OffsetY= 0
DXF ScaleX= 1
DXF ScaleY= 10

--- Lacy 190.p01 (plan) ---

Plan Title=Multiple Run
Short Identifier=Multiple
Geom File=g01
Flow File=f01
Subcritical Flow
K Sum by GR= 0
Std Step Tol= 0.01
Critical Tol= 0.01
Num of Std Step Trials= 20
Max Error Tol= 0.3
Flow Tol Ratio= 0.001
Split Flow NTrial= 30
Split Flow Tol= 0.02
Split Flow Ratio= 0.02
Log Output Level= 0
Friction Slope Method= 1
Unsteady Friction Slope Method= 2
Unsteady Bridges Friction Slope Method= 1
Parabolic Critical Depth
Global Vel Dist=  1 , 1 , 1
Global Log Level= 0
CheckData=True
Encroach Param= -1, 0, 0, 0
BEGIN DESCRIPTION:
Multiple Run
END DESCRIPTION:

--- Lacy 190.f01 (steady flow) ---

Flow Title=Multiple
Number of Profiles=7
Profile Names=10-year,25-year,50-year,1pct_min,100-year,1pct_plu,500-year
River Rch & RM= Lacy 190,Reach-1,11331
     171     209     238     135     268     536     341
River Rch & RM= Lacy 190,Reach-1,8507
     330     422     493     286     570    1138     762
River Rch & RM= Lacy 190,Reach-1,6125
     703     951    1152     692    1381    2756    1983
River Rch & RM= Lacy 190,Reach-1,1396
     787    1071    1303     786    1569    3130    2272
Boundary for River Rch & Prof#=Lacy 190,Reach-1,1
Up Type=0
Dn Type=3
Dn Slope=0.005
Boundary for River Rch & Prof#=Lacy 190,Reach-1,2
Up Type=0
Dn Type=3
Dn Slope=0.005
Boundary for River Rch & Prof#=Lacy 190,Reach-1,3
Up Type=0
Dn Type=3
Dn Slope=0.005
Boundary for River Rch & Prof#=Lacy 190,Reach-1,4
Up Type=0
Dn Type=3
Dn Slope=0.005
Boundary for River Rch & Prof#=Lacy 190,Reach-1,5
Up Type=0
Dn Type=3
Dn Slope=0.005
Boundary for River Rch & Prof#=Lacy 190,Reach-1,6
Up Type=0
Dn Type=3
Dn Slope=0.005
Boundary for River Rch & Prof#=Lacy 190,Reach-1,7
Up Type=0
Dn Type=3
Dn Slope=0.005

--- Lacy 190.g01 (geometry) ---

Geom Title=Existing Conditions
Program Version=4.10

River Reach=Lacy 190        ,Reach-1
Reach XY= 30
        2669426.        6812111.      2669526.05      6812445.66
      2669383.08        6812611.      2669473.92      6812716.85
       2669624.8       6813371.5       2669577.8      6813704.89
      2669783.73       6814167.5      2670115.52       6814401.2
      2670129.48      6814609.74        2670326.        6814861.
      2670277.57      6815162.88      2670362.56      6815463.33
      2670289.03       6815643.9       2670395.9      6815857.09
      2670534.72      6816738.89      2670483.53      6817014.32
      2670581.23      6817206.38      2670686.41      6817171.97
       2670877.5      6817407.38      2671928.45      6817666.46
      2672168.93        6818002.      2672728.47      6818016.45
      2672931.84      6818308.95      2673306.01      6818361.06
      2673686.51      6818212.21      2674370.07      6818208.76
        2674876.       6818018.5       2675072.6      6818153.17
      2675165.29      6818111.82        2675426.        6818211.

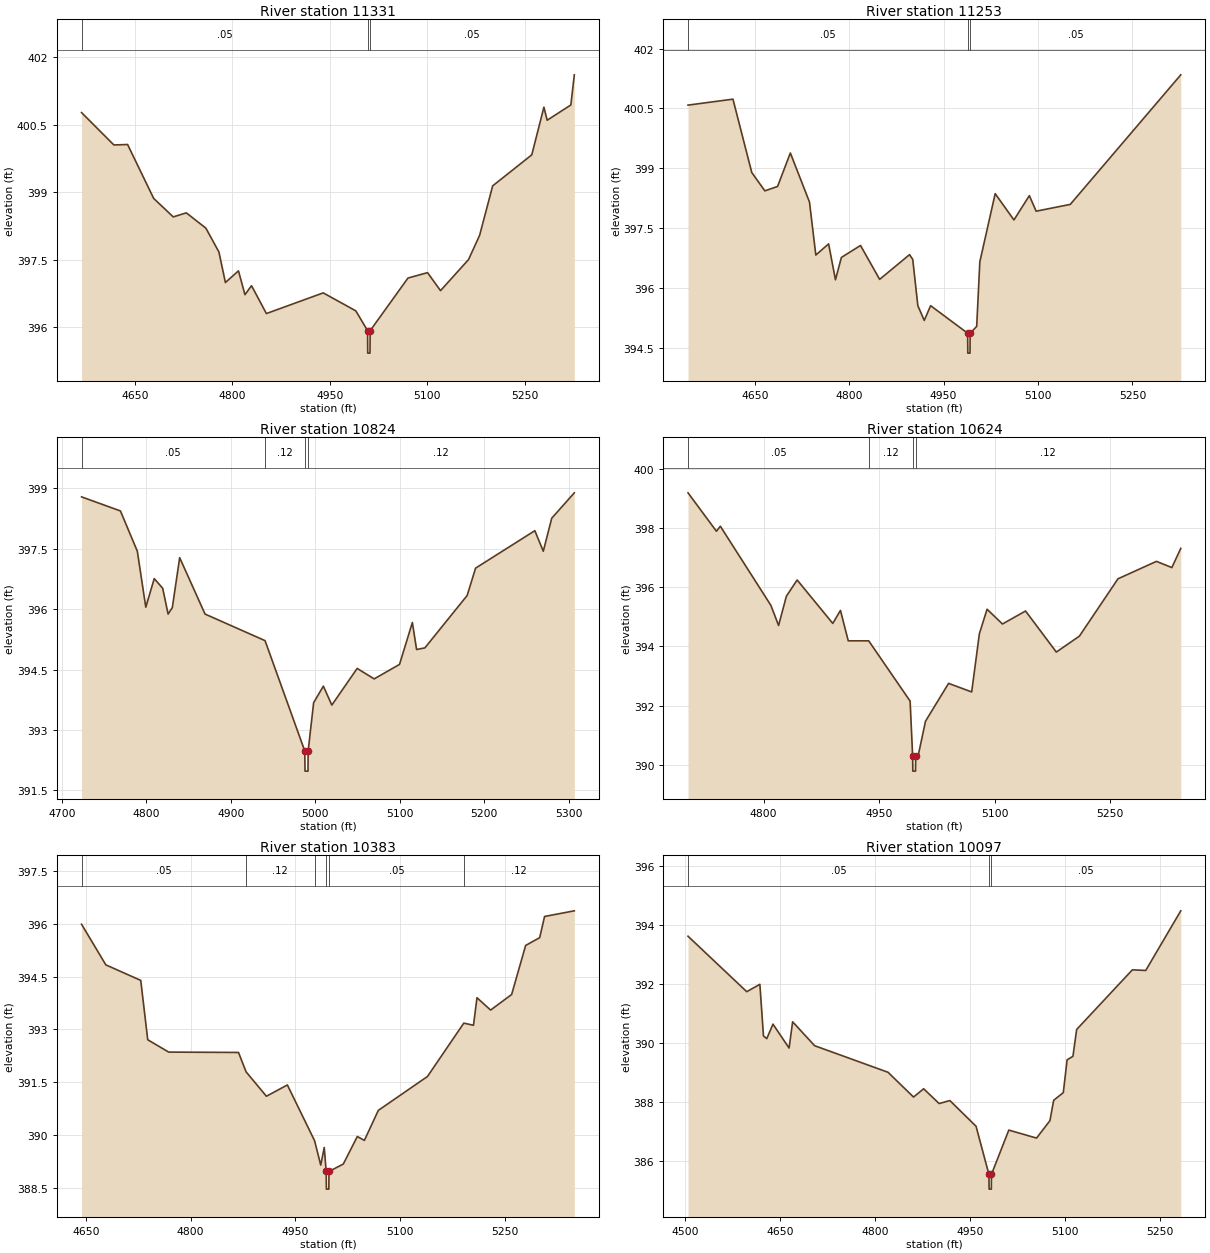
Type RM Length L Ch R = 1 ,11331   ,78,78,78
BEGIN DESCRIPTION:
Lacy 190 317
END DESCRIPTION:
XS GIS Cut Line= 3
      2669055.32       6812331.3      2669486.72      6812369.19
      2669811.26      6812342.46
#Sta/Elev= 30
  4567.6  400.77  4617.4  400.05  4638.5  400.06  4678.7  398.86  4708.8  398.45
  4728.9  398.54    4759   398.2  4779.1  397.67  4789.1  396.99  4809.2  397.25
  4819.2  396.72  4829.3  396.92  4852.2   396.3  4939.7  396.76  4989.9  396.36
    5008  395.92  5008.2  395.42  5011.7  395.42    5012  395.92  5070.2  397.09
  5100.3  397.21  5120.3  396.81  5163.4   397.5  5180.5  398.04  5200.6  399.14
  5260.8  399.83  5279.5  400.89  5284.5   400.6    5321  400.94  5326.3  401.61
#Mann= 3 ,-1 , 0
  4567.6     .05       0    5008     .03       0    5012     .05       0
Bank Sta=5008,5012
XS Rating Curve= 0 ,0
Exp/Cntr=0.3,0.1

Type RM Length L Ch R = 1 ,11253   ,429,429,429
BEGIN DESCRIPTION:
Lacy 190 316
END DESCRIPTION:
XS GIS Cut Line= 3
      2669075.53      6812358.94      2669525.05      6812432.36
      2669829.99      6812551.87
#Sta/Elev= 30
  4543.9  400.58  4615.3  400.73  4645.2  398.89    4666  398.43  4686.2  398.54
  4706.5  399.38  4736.9  398.15    4747  396.82  4767.3   397.1  4778.2   396.2
  4787.6  396.76    4818  397.06  4848.4  396.21  4895.9  396.83    4901  396.71
  4909.1  395.55  4919.3  395.18  4929.4  395.55  4988.2  394.86  4988.5  394.36
    4992  394.36  4992.2  394.86  5002.6  395.03  5007.6  396.65    5032  398.36
  5061.8   397.7  5086.3  398.31  5097.1  397.92  5151.3  398.09  5326.9  401.34
#Mann= 3 ,-1 , 0
  4543.9     .05       0  4988.2     .04       0  4992.2     .05       0
Bank Sta=4988.2,4992.2
XS Rating Curve= 0 ,0
Exp/Cntr=0.3,0.1

Type RM Length L Ch R = 1 ,10824   ,200,200,200
BEGIN DESCRIPTION:
Lacy 190 314
END DESCRIPTION:
XS GIS Cut Line= 3
      2669199.98       6812778.6      2669478.03      6812771.62
      2669782.67      6812783.37
#Sta/Elev= 30
  4723.5  398.79  4769.5  398.44  4789.5  397.44  4799.5  396.05  4809.5  396.76
  4819.5  396.52  4825.9  395.88  4830.9  396.04  4839.6  397.28  4869.6  395.88
  4940.6  395.22  4987.6  392.48  4987.9  391.98  4991.4  391.98  4991.6  392.48
  4998.1  393.68  5009.6  394.09  5019.6  393.62  5049.6  394.53  5069.7  394.27
  5099.7  394.63  5114.9  395.67  5119.9     395  5129.7  395.04  5179.7  396.34
  5189.7  397.02  5259.8  397.95  5269.8  397.44  5279.8  398.26  5306.5  398.89
#Mann= 4 ,-1 , 0
  4723.5     .05       0  4940.6     .12       0  4987.6     .07       0
  4991.6     .12       0
Bank Sta=4987.6,4991.6
XS Rating Curve= 0 ,0
Exp/Cntr=0.3,0.1

Type RM Length L Ch R = 1 ,10624   ,241,241,241
BEGIN DESCRIPTION:
Lacy 190 313
END DESCRIPTION:
XS GIS Cut Line= 3
      2669178.88       6812941.8       2669471.5      6812971.49
      2669817.64        6812966.
#Sta/Elev= 30
  4701.7   399.2  4738.6   397.9  4743.7  398.07  4809.4  395.39  4819.4  394.71
  4829.5   395.7  4843.5  396.25  4889.8  394.78  4899.8  395.22  4909.9  394.19
  4936.5  394.19  4990.3  392.15  4993.6  390.28  4993.8  389.78  4997.3  389.78
  4997.6  390.28  5000.6  390.28  5010.3  391.47  5040.3  392.75  5070.3  392.46
  5080.3  394.43  5090.3  395.26  5110.3  394.76  5140.3   395.2  5180.3  393.81
  5210.3  394.35  5260.4  396.29  5310.4  396.88  5330.4  396.67    5342  397.32
#Mann= 4 ,-1 , 0
  4701.7     .05       0  4936.5     .12       0  4993.6     .07       0
  4997.6     .12       0
Bank Sta=4993.6,4997.6
XS Rating Curve= 0 ,0
Exp/Cntr=0.3,0.1

Type RM Length L Ch R = 1 ,10383   ,286,286,286
BEGIN DESCRIPTION:
Lacy 190 312
END DESCRIPTION:
XS GIS Cut Line= 3
      2669171.19      6813193.59      2669526.19      6813196.07
      2669875.33      6813162.06
#Sta/Elev= 30
  4643.7  395.98  4678.5  394.83  4728.5  394.39  4738.5  392.71  4768.5  392.36
  4868.5  392.35  4879.4   391.8  4908.5  391.11  4938.5  391.43  4977.5  389.85
  4986.3  389.16  4991.3  389.66  4994.1  388.98  4994.4  388.48  4997.9  388.48
  4998.1  388.98  5018.6  389.19  5038.7  389.97  5048.8  389.86  5068.8  390.71
  5139.2  391.67  5191.2  393.18  5205.1  393.12  5210.1   393.9  5229.6  393.55
  5259.7  393.99  5279.8  395.38  5299.9   395.6  5306.9   396.2  5349.5  396.36
#Mann= 6 ,-1 , 0
  4643.7     .05       0  4879.4     .12       0  4977.5     .05       0
  4994.1     .03       0  4998.1     .05       0  5191.2     .12       0
Bank Sta=4994.1,4998.1
XS Rating Curve= 0 ,0
Exp/Cntr=0.3,0.1

Type RM Length L Ch R = 1 ,10097   ,115,115,115
BEGIN DESCRIPTION:
Lacy 190 311
END DESCRIPTION:
XS GIS Cut Line= 3
      2669146.33      6813325.54      2669658.22      6813460.24
      2669867.06      6813325.76
#Sta/Elev= 30
    4505  393.62  4597.7  391.74  4618.4  391.99  4624.1  390.24  4629.3  390.15
  4639.1  390.64  4664.5  389.83  4670.1  390.72  4704.8  389.91  4820.6  389.01
  4860.9  388.17  4876.9  388.45  4901.3  387.95  4918.3  388.05  4959.6  387.18
  4979.9  385.55  4980.2  385.05  4983.7  385.05  4983.9  385.55  5011.3  387.05
  5055.1  386.78  5076.2  387.37  5082.1  388.06  5097.3  388.32  5103.3  389.43
  5112.5  389.55  5118.4  390.46  5206.3  392.48  5227.4  392.46  5282.7  394.48
#Mann= 3 ,-1 , 0
    4505     .05       0  4979.9     .03       0  4983.9     .05       0
Bank Sta=4979.9,4983.9
XS Rating Curve= 0 ,0
Exp/Cntr=0.3,0.1

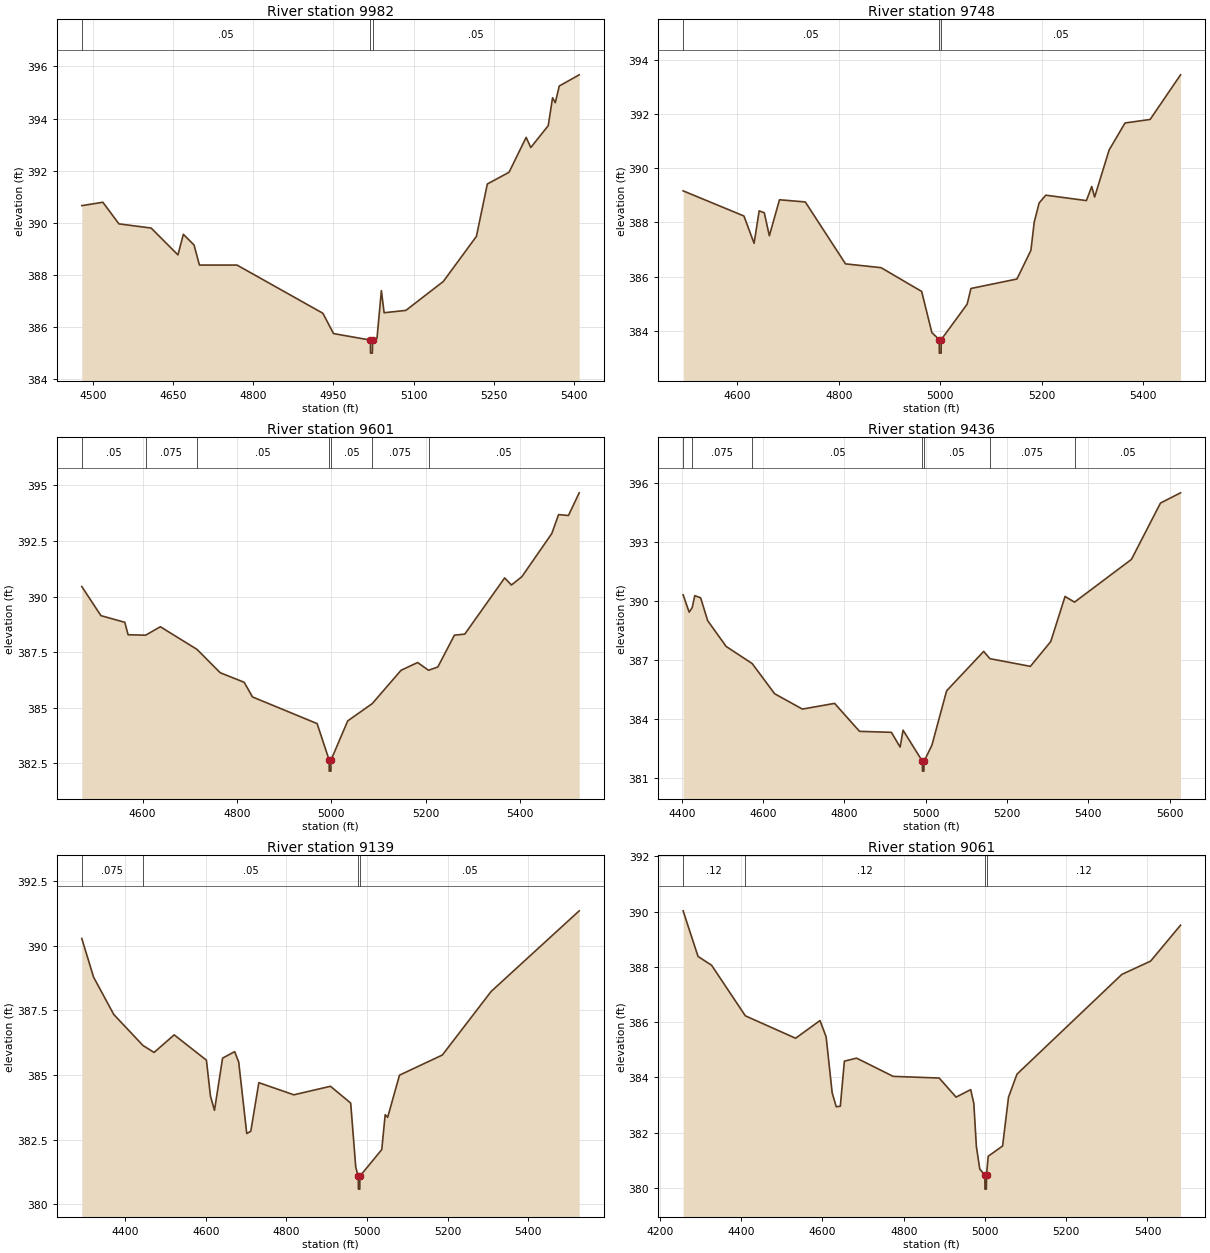
Type RM Length L Ch R = 1 ,9982    ,234,234,234
BEGIN DESCRIPTION:
Lacy 190 310
END DESCRIPTION:
XS GIS Cut Line= 3
      2669106.75      6813524.69      2669624.03      6813567.04
      2670022.07      6813464.26
#Sta/Elev= 30
  4479.6  390.66    4519  390.79  4549.1  389.96  4609.3   389.8  4659.4  388.77
  4669.5  389.56  4689.5  389.15  4699.6  388.38  4769.8  388.38  4930.4  386.53
  4950.4  385.75  5019.3   385.5  5019.5     385    5023     385  5023.3   385.5
  5031.6  385.57  5039.8   387.4  5044.9  386.55  5085.6  386.64  5155.6  387.75
  5217.5  389.48  5237.9  391.49  5278.5  391.94  5310.5  393.28  5319.2  392.89
  5351.8  393.73  5359.9   394.8    5365  394.61  5372.4  395.25  5409.7  395.68
#Mann= 3 ,-1 , 0
  4479.6     .05       0  5019.3     .03       0  5023.3     .05       0
Bank Sta=5019.3,5023.3
XS Rating Curve= 0 ,0
Exp/Cntr=0.3,0.1

Type RM Length L Ch R = 1 ,9748    ,147,147,147
BEGIN DESCRIPTION:
Lacy 190 309
END DESCRIPTION:
XS GIS Cut Line= 3
      2669116.22      6813800.23      2669624.06      6813769.65
      2670040.08      6813545.54
#Sta/Elev= 30
    4493  389.17    4613  388.24    4633  387.23    4643  388.43  4653.1  388.36
  4663.1  387.51  4683.1  388.84    4734  388.76  4813.4  386.47  4883.5  386.33
  4963.6  385.45  4983.7  383.93  4998.2  383.67  4998.5  383.17    5002  383.17
  5002.2  383.67  5053.3  384.98  5060.8  385.56  5151.5  385.91  5179.1  386.97
  5185.7  388.02  5195.3  388.72  5208.4  389.01  5288.6  388.81  5299.1  389.33
  5304.8  388.94  5333.4  390.68  5364.8  391.68  5414.3  391.81  5474.3  393.46
#Mann= 3 ,-1 , 0
    4493     .05       0  4998.2     .03       0  5002.2     .05       0
Bank Sta=4998.2,5002.2
XS Rating Curve= 0 ,0
Exp/Cntr=0.3,0.1

Type RM Length L Ch R = 1 ,9601    ,165,165,165
BEGIN DESCRIPTION:
Lacy 190 308
END DESCRIPTION:
XS GIS Cut Line= 3
      2669155.89      6813981.14      2669680.77      6813900.75
      2670078.47      6813561.24
#Sta/Elev= 30
  4471.3  390.45  4511.9  389.14  4562.5  388.84  4569.4  388.28  4606.5  388.26
  4637.8  388.64  4715.5  387.62  4764.6  386.57  4815.4  386.14    4833  385.48
  4969.9  384.28  4995.4  382.64  4995.6  382.14  4999.1  382.14  4999.4  382.64
  5034.7   384.4  5086.7  385.18  5147.7  386.68  5182.9  387.03    5206  386.68
  5225.7  386.83  5260.8  388.26  5282.8  388.31  5367.3  390.84  5381.6  390.52
  5403.6  390.89  5467.2  392.84  5481.5  393.69  5502.4  393.65  5525.2  394.67
#Mann= 7 ,-1 , 0
  4471.3     .05       0  4606.5    .075       0  4715.5     .05       0
  4995.4     .03       0  4999.4     .05       0  5086.7    .075       0
    5206     .05       0
Bank Sta=4995.4,4999.4
XS Rating Curve= 0 ,0
Exp/Cntr=0.3,0.1

Type RM Length L Ch R = 1 ,9436    ,297,297,297
BEGIN DESCRIPTION:
Lacy 190 318
END DESCRIPTION:
XS GIS Cut Line= 4
      2669260.02      6814353.51       2669653.6      6814167.22
      2669761.66      6814034.98        2670147.      6813552.36
#Sta/Elev= 30
  4403.2  390.31  4418.1  389.43  4425.6  389.67  4431.9  390.27  4446.3  390.16
  4463.6     389  4509.1  387.69  4573.2  386.82  4628.3  385.29  4696.6  384.51
  4775.9   384.8  4837.2  383.38  4915.6  383.33  4937.1  382.58  4944.3  383.44
  4991.9  381.86  4992.1  381.36  4995.6  381.36  4995.9  381.86  5015.2  382.67
  5051.5  385.44  5142.7  387.44  5157.9  387.07  5257.6  386.68  5307.7  387.94
  5342.9  390.23  5366.1  389.94  5506.2  392.11  5577.6  394.97    5627  395.49
#Mann= 7 ,-1 , 0
  4403.2     .05       0  4425.6    .075       0  4573.2     .05       0
  4991.9     .03       0  4995.9     .05       0  5157.9    .075       0
  5366.1     .05       0
Bank Sta=4991.9,4995.9
XS Rating Curve= 0 ,0
Exp/Cntr=0.3,0.1

Type RM Length L Ch R = 1 ,9139    ,78,78,78
BEGIN DESCRIPTION:
Lacy 190 3428
END DESCRIPTION:
XS GIS Cut Line= 3
      2669296.57      6814357.62      2669824.95      6814363.11
      2670243.95      6813794.53
#Sta/Elev= 30
  4292.1  390.28  4321.5  388.78  4371.5  387.34  4443.9  386.14  4471.5  385.87
  4521.5  386.55  4601.5  385.57  4611.5  384.18  4621.5  383.63  4641.6  385.65
  4671.6   385.9  4681.6   385.5  4701.6  382.73  4711.6  382.82  4731.6   384.7
  4818.5  384.23  4909.4  384.56  4959.6  383.91  4972.2  381.42  4978.4  381.08
  4978.7  380.58  4982.2  380.58  4982.4  381.08  5036.7  382.11  5045.2  383.46
  5051.4  383.36  5080.7  384.99  5187.1  385.77  5308.2  388.23  5526.8  391.35
#Mann= 4 ,-1 , 0
  4292.1    .075       0  4443.9     .05       0  4978.4     .03       0
  4982.4     .05       0
Bank Sta=4978.4,4982.4
XS Rating Curve= 0 ,0
Exp/Cntr=0.3,0.1

Type RM Length L Ch R = 1 ,9061    ,554,554,554
BEGIN DESCRIPTION:
Lacy 190 3429
END DESCRIPTION:
XS GIS Cut Line= 3
      2669309.35      6814383.58      2669887.82      6814403.99
      2670276.49      6813888.66
#Sta/Elev= 30
  4257.1  390.03  4293.8  388.38  4327.2  388.06  4410.3  386.23  4533.9  385.42
    4594  386.06  4609.1  385.47    4624  383.44    4634  382.94    4644  382.96
    4654  384.59    4684   384.7  4774.1  384.04  4887.3  383.98  4928.9  383.29
  4964.9  383.56  4972.6  383.06  4978.9   381.5  4987.2  380.69  4999.8  380.46
    5000  379.96  5003.5  379.96  5003.8  380.46    5008  381.15  5043.4  381.52
    5058  383.29  5078.8  384.12  5336.9  387.73  5407.7  388.21  5481.4  389.51
#Mann= 4 ,-1 , 0
  4257.1     .12       0  4410.3     .12       0  4999.8     .03       0
  5003.8     .12       0
Bank Sta=4999.8,5003.8
XS Rating Curve= 0 ,0
Exp/Cntr=0.3,0.1

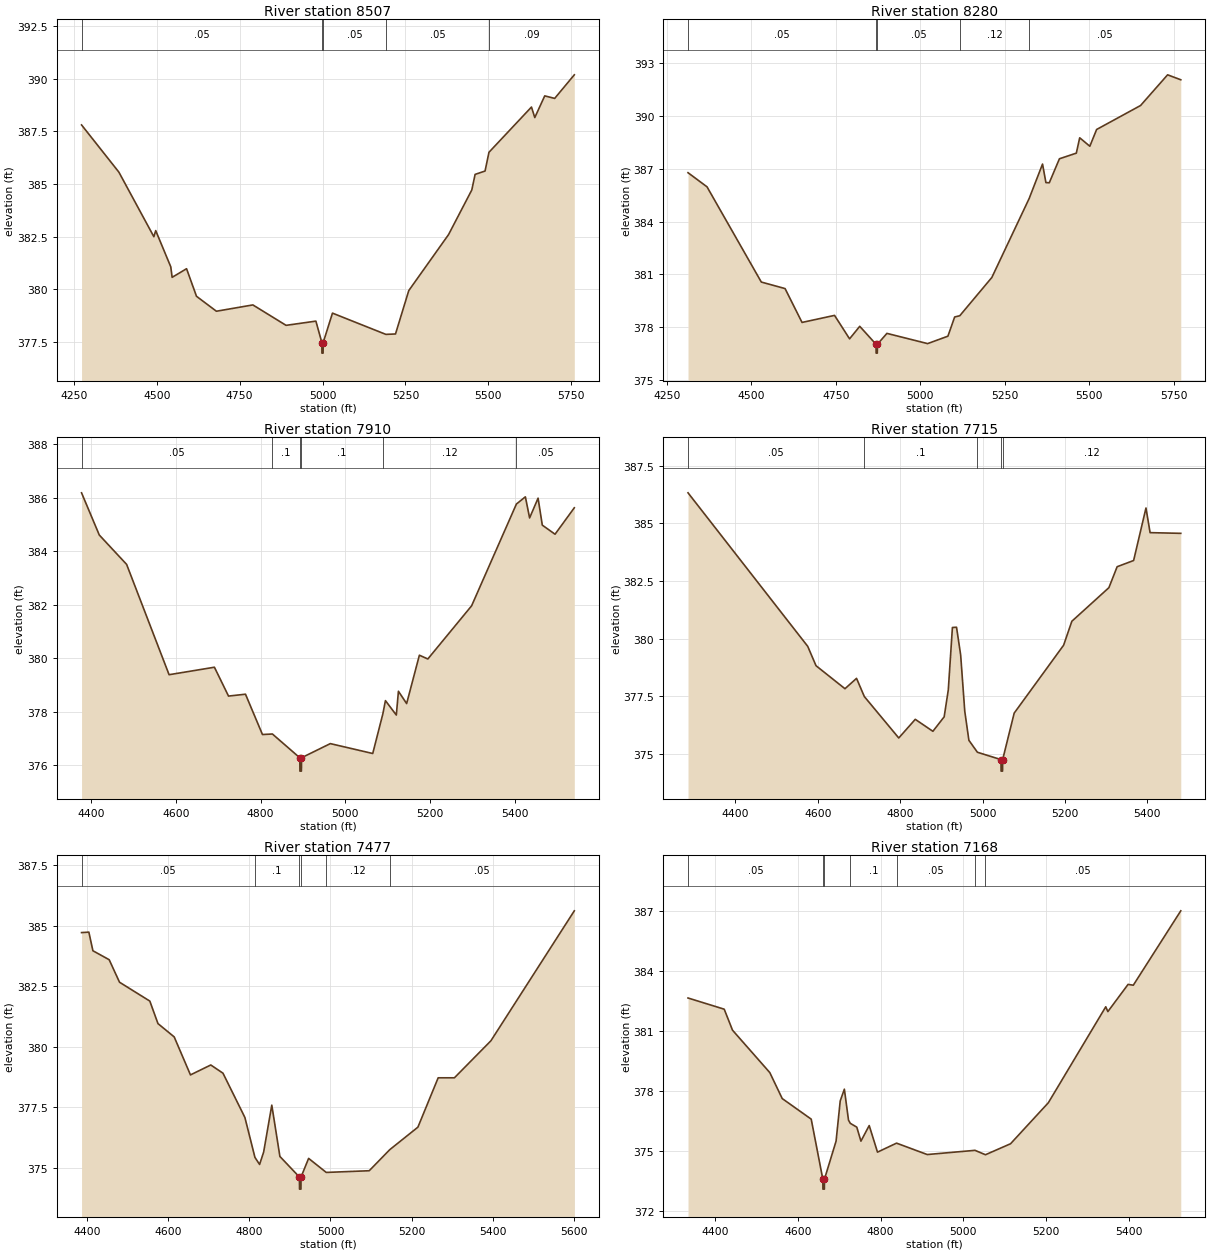
Type RM Length L Ch R = 1 ,8507    ,227,227,227
BEGIN DESCRIPTION:
Lacy 190 295
END DESCRIPTION:
XS GIS Cut Line= 3
      2669523.79      6814837.68      2669765.84      6814726.22
      2670985.14      6814693.87
#Sta/Elev= 30
  4273.2  387.81  4385.7  385.57  4491.3   382.5  4496.9  382.79  4542.3  381.07
  4546.4  380.57  4589.9  380.98  4619.9  379.67  4679.9  378.96  4789.9  379.26
    4890  378.29    4980  378.49    4998  377.47  4998.2  376.97  5001.7  376.97
    5002  377.47    5030  378.87  5191.1  377.86  5220.1  377.88  5260.1  379.94
  5380.1   382.6  5450.2  384.72  5460.2  385.46  5490.2  385.62    5502  386.51
  5630.2  388.66  5640.2  388.16  5670.2  389.19  5700.2  389.07  5759.4  390.19
#Mann= 5 ,-1 , 0
  4273.2     .05       0    4998     .03       0    5002     .05       0
  5191.1     .05       0    5502     .09       0
Bank Sta=4998,5002
XS Rating Curve= 0 ,0
Exp/Cntr=0.3,0.1

Type RM Length L Ch R = 1 ,8280    ,370,370,370
BEGIN DESCRIPTION:
Lacy 190 294
END DESCRIPTION:
XS GIS Cut Line= 3
       2669640.1      6814967.47      2670325.09      6814901.76
      2671095.02      6814887.26
#Sta/Elev= 30
    4313  386.77  4369.2  385.97  4529.9  380.57  4600.2   380.2  4650.4  378.28
  4746.6  378.68  4791.1  377.35  4821.2  378.06  4869.4  377.04  4869.7  376.54
  4873.2  376.54  4873.4  377.04  4901.6  377.66    5022  377.08  5082.1   377.5
  5102.1  378.59  5117.2  378.66  5212.1  380.83  5322.6  385.31  5362.1  387.26
  5372.1  386.21  5382.1   386.2  5412.1  387.56  5462.1  387.88  5472.1  388.75
  5502.1  388.27  5522.1  389.22  5652.2  390.58  5732.2  392.32  5771.2  392.04
#Mann= 5 ,-1 , 0
    4313     .05       0  4869.4     .03       0  4873.4     .05       0
  5117.2     .12       0  5322.6     .05       0
Bank Sta=4869.4,4873.4
XS Rating Curve= 0 ,0
Exp/Cntr=0.3,0.1

Type RM Length L Ch R = 1 ,7910    ,195,195,195
BEGIN DESCRIPTION:
Lacy 190 293
END DESCRIPTION:
XS GIS Cut Line= 3
      2669679.77      6815222.89      2670181.73      6815259.72
      2670841.45      6815222.08
#Sta/Elev= 30
  4376.9  386.19  4418.8  384.61  4483.4  383.51  4583.7  379.38  4690.8  379.66
  4724.1  378.58  4764.2  378.65  4804.3  377.14  4827.8  377.16  4892.5  376.27
  4892.8  375.77  4896.3  375.77  4896.5  376.27  4964.6   376.8  5064.8  376.43
  5088.8  377.92  5094.8  378.41  5120.5  377.87  5125.5  378.76  5144.9   378.3
    5175  380.11    5195  379.97  5298.4  381.96  5404.2  385.77  5425.4  386.04
  5435.4  385.25  5455.4  385.99  5465.4  384.98  5495.5  384.64    5541  385.63
#Mann= 6 ,-1 , 0
  4376.9     .05       0  4827.8      .1       0  4892.5     .07       0
  4896.5      .1       0  5088.8     .12       0  5404.2     .05       0
Bank Sta=4892.5,4896.5
XS Rating Curve= 0 ,0
Exp/Cntr=0.3,0.1

Type RM Length L Ch R = 1 ,7715    ,238,238,238
BEGIN DESCRIPTION:
Lacy 190 292
END DESCRIPTION:
XS GIS Cut Line= 3
       2669636.5       6815388.2      2670226.29      6815442.51
       2670830.5      6815440.01
#Sta/Elev= 30
  4284.8  386.33  4575.5  379.66  4595.6  378.82  4665.9  377.82    4694  378.27
  4712.9  377.48  4796.5  375.68  4836.6  376.49  4879.4  375.97  4906.8   376.6
  4916.8  377.77  4926.8  380.48  4936.8  380.49  4946.8  379.29  4956.8  376.84
  4966.8  375.58  4987.5  375.06  5044.8  374.74    5045  374.24  5048.5  374.24
  5048.8  374.74  5076.8  376.76  5196.8  379.71  5216.8  380.75  5306.8  382.21
  5326.8  383.12  5366.8  383.39  5396.8  385.67  5406.8   384.6  5481.3  384.57
#Mann= 5 ,-1 , 0
  4284.8     .05       0  4712.9      .1       0  4987.5     .12       0
  5044.8     .07       0  5048.8     .12       0
Bank Sta=5044.8,5048.8
XS Rating Curve= 0 ,0
Exp/Cntr=0.3,0.1

Type RM Length L Ch R = 1 ,7477    ,309,309,309
BEGIN DESCRIPTION:
Lacy 190 291
END DESCRIPTION:
XS GIS Cut Line= 3
      2669678.04      6815609.89      2670274.75      6815648.77
      2670891.56      6815651.74
#Sta/Elev= 30
  4386.4  384.71  4404.4  384.73  4414.4  383.96  4454.5  383.59    4480  382.66
  4554.7  381.88  4574.8  380.95  4614.8   380.4  4654.9  378.83    4705  379.24
  4735.1   378.9  4789.1  377.07  4813.9  375.42  4825.3  375.13  4835.3  375.64
  4855.4  377.58  4875.4  375.46  4923.5  374.61  4923.8  374.11  4927.3  374.11
  4927.5  374.61  4946.2  375.38  4989.7   374.8  5095.6  374.87  5146.2  375.74
  5215.6  376.67  5265.6  378.71  5305.6  378.71  5395.6  380.24  5601.2  385.61
#Mann= 6 ,-1 , 0
  4386.4     .05       0  4813.9      .1       0  4923.5     .07       0
  4927.5      .1       0  4989.7     .12       0  5146.2     .05       0
Bank Sta=4923.5,4927.5
XS Rating Curve= 0 ,0
Exp/Cntr=0.3,0.1

Type RM Length L Ch R = 1 ,7168    ,279,279,279
BEGIN DESCRIPTION:
Lacy 190 290
END DESCRIPTION:
XS GIS Cut Line= 3
      2669728.58      6815922.69      2670420.87      6815927.27
      2670911.56      6815847.09
#Sta/Elev= 30
  4335.2  382.63  4422.6  382.07  4442.6  381.02  4532.6   378.9  4562.6   377.6
  4632.6  376.57  4660.6  373.57  4660.9  373.07  4664.4  373.07  4664.6  373.57
  4692.6  375.47  4702.6  377.48  4712.6  378.07  4722.6  376.52    4727  376.36
  4742.6  376.17  4752.6  375.47  4772.6  376.25  4792.6  374.92  4838.6  375.37
  4912.6   374.8    5028  375.01  5053.2  374.79  5113.8  375.34    5205  377.39
  5343.6  382.19  5348.7  381.95  5397.5  383.31  5410.1  383.27  5524.7  386.99
#Mann= 7 ,-1 , 0
  4335.2     .05       0  4660.6     .03       0  4664.6     .05       0
    4727      .1       0  4838.6     .05       0    5028      .1       0
  5053.2     .05       0
Bank Sta=4660.6,4664.6
XS Rating Curve= 0 ,0
Exp/Cntr=0.3,0.1

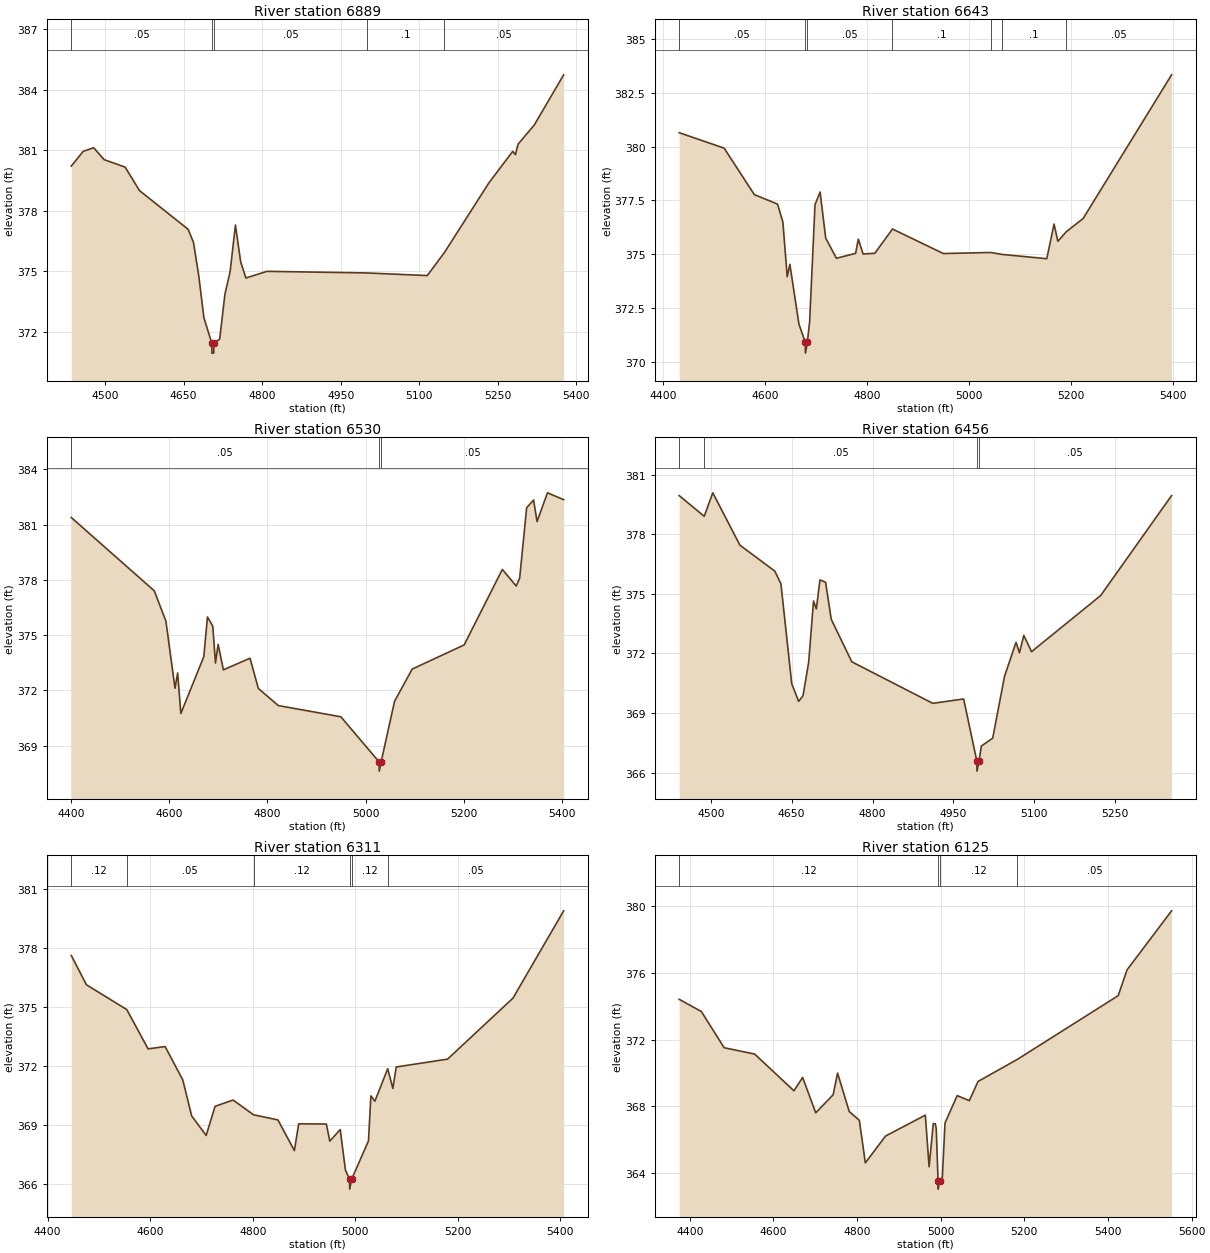
Type RM Length L Ch R = 1 ,6889    ,246,246,246
BEGIN DESCRIPTION:
Lacy 190 289
END DESCRIPTION:
XS GIS Cut Line= 3
      2669863.34      6816216.53      2670226.62      6816242.57
      2670791.21      6816127.55
#Sta/Elev= 30
  4435.4  380.21  4458.1  380.94  4478.2  381.12  4498.2  380.53  4538.3  380.16
  4565.6     379  4658.6  377.08  4668.7  376.44  4678.7  374.81  4688.7   372.7
  4703.7  371.45    4704  370.95  4707.5  370.95  4707.7  371.45  4718.8  371.64
  4728.8  373.86  4738.8  374.99  4748.9  377.29  4758.9  375.47  4768.9  374.67
  4809.2     375  4999.8  374.92  5115.3  374.79    5148  375.93    5233  379.38
  5278.5  380.94  5283.6  380.78  5288.8   381.3  5319.5  382.24  5375.8  384.73
#Mann= 5 ,-1 , 0
  4435.4     .05       0  4703.7     .07       0  4707.7     .05       0
  4999.8      .1       0    5148     .05       0
Bank Sta=4703.7,4707.7
XS Rating Curve= 0 ,0
Exp/Cntr=0.3,0.1

Type RM Length L Ch R = 1 ,6643    ,113,113,113
BEGIN DESCRIPTION:
Lacy 190 3458
END DESCRIPTION:
XS GIS Cut Line= 3
      2669932.15      6816270.78      2670475.22      6816443.56
      2670774.79      6816184.73
#Sta/Elev= 30
  4431.9  380.65  4520.1  379.93  4579.3  377.77  4624.8  377.33  4635.3  376.49
  4643.8  373.95    4649  374.53  4666.8  371.75  4679.3   370.9  4679.5   370.4
  4683.3   370.9  4687.8  371.88  4698.3   377.3  4708.3  377.89  4719.3  375.75
  4740.3  374.81    4778  375.04  4783.2   375.7  4792.7  375.01  4815.5  375.04
  4850.3  376.17  4950.1  375.03  5042.9  375.08    5065  374.99  5152.9  374.79
  5167.2   376.4  5174.6   375.6    5191  376.04  5224.2  376.66  5397.7  383.34
#Mann= 7 ,-1 , 0
  4431.9     .05       0  4679.3     .07       0  4683.3     .05       0
  4850.3      .1       0  5042.9     .05       0    5065      .1       0
    5191     .05       0
Bank Sta=4679.3,4683.3
XS Rating Curve= 0 ,0
Exp/Cntr=0.3,0.1

Type RM Length L Ch R = 1 ,6530    ,74,74,74
BEGIN DESCRIPTION:
Lacy 190 3456
END DESCRIPTION:
XS GIS Cut Line= 6
      2669949.88       6816333.5      2670302.45      6816479.65
      2670428.59      6816560.31      2670530.24      6816550.39
      2670581.21      6816504.74      2670794.55      6816292.88
#Sta/Elev= 30
  4400.9  381.38  4569.9   377.4  4593.6  375.75  4612.1  372.11  4617.5  372.94
    4624  370.74  4670.7  373.82  4678.2  375.98    4689  375.48  4694.5  373.48
  4699.9  374.49  4710.6  373.11  4764.8  373.74  4781.8   372.1  4822.4  371.17
  4949.8  370.56  5027.8  368.11    5028  367.61  5031.8  368.11  5059.1   371.4
    5095  373.15  5200.8  374.46  5278.6  378.56  5306.9  377.66  5313.9  378.09
  5328.1  381.91  5342.2  382.33  5349.3  381.16  5370.5  382.72  5403.5  382.35
#Mann= 3 ,-1 , 0
  4400.9     .05       0  5027.8     .03       0  5031.8     .05       0
Bank Sta=5027.8,5031.8
XS Rating Curve= 0 ,0
Exp/Cntr=0.3,0.1

Type RM Length L Ch R = 1 ,6456    ,145,145,145
BEGIN DESCRIPTION:
Lacy 190 3457
END DESCRIPTION:
XS GIS Cut Line= 3
      2669976.46      6816462.21       2670513.9      6816626.23
      2670787.65      6816407.04
#Sta/Elev= 30
  4441.6  379.94    4488   378.9  4503.9  380.08  4554.1  377.45  4618.9  376.14
  4630.2   375.5  4650.2  370.48    4663  369.59  4671.1  369.87  4681.6  371.56
  4690.6  374.64  4695.8  374.24  4702.5   375.7    4713  375.58  4723.4  373.72
  4761.5  371.58  4911.6  369.49  4968.8  369.71  4993.3  366.58  4993.5  366.08
  4997.3  366.58  5001.6  367.34  5022.7  367.74  5044.6  370.85  5065.9  372.56
  5072.3  372.03  5080.3  372.91  5094.7  372.09  5222.7  374.91  5354.2  379.94
#Mann= 4 ,-1 , 0
  4441.6     .12       0    4488     .05       0  4993.3     .03       0
  4997.3     .05       0
Bank Sta=4993.3,4997.3
XS Rating Curve= 0 ,0
Exp/Cntr=0.3,0.1

Type RM Length L Ch R = 1 ,6311    ,186,186,186
BEGIN DESCRIPTION:
Lacy 190 286
END DESCRIPTION:
XS GIS Cut Line= 4
      2670020.44      6816605.17       2670375.5      6816772.16
      2670558.41      6816743.22      2670804.28      6816449.88
#Sta/Elev= 30
  4446.2  377.61  4475.8  376.12  4554.4  374.86    4596  372.86  4629.2  372.98
  4663.7  371.28    4681  369.45  4709.3  368.46  4726.6  369.94  4761.8  370.26
  4801.6  369.51  4849.2  369.25  4881.3  367.69  4889.7  369.05  4943.7  369.04
  4950.4  368.17  4970.7  368.76  4980.8  366.71  4988.9  366.23  4989.2  365.73
  4992.9  366.23  5025.8  368.18  5030.5  370.47  5038.3   370.2  5063.3  371.85
  5073.4  370.85  5079.9  371.94  5180.1  372.34  5307.6  375.44  5406.5  379.88
#Mann= 6 ,-1 , 0
  4446.2     .12       0  4554.4     .05       0  4801.6     .12       0
  4988.9     .07       0  4992.9     .12       0  5063.3     .05       0
Bank Sta=4988.9,4992.9
XS Rating Curve= 0 ,0
Exp/Cntr=0.3,0.1

Type RM Length L Ch R = 1 ,6125    ,234,234,234
BEGIN DESCRIPTION:
Lacy 190 287
END DESCRIPTION:
XS GIS Cut Line= 3
      2670305.16       6817504.1      2670478.83      6816916.85
      2670819.27      6816465.93
#Sta/Elev= 30
  4374.6  374.42  4427.6  373.69  4482.1  371.52  4555.1  371.14    4649  368.94
  4669.8  369.74  4701.1  367.62  4742.7   368.7  4753.3     370  4781.2   367.7
  4805.4  367.17  4819.7  364.62    4868  366.23  4963.2  367.48  4972.2  364.39
  4982.2  366.97    4987  366.97  4989.3  366.66  4993.6  363.55  4993.8  363.05
  4997.6  363.55  5003.9  363.77  5010.2  367.01  5039.3  368.65  5068.4  368.35
  5089.2   369.5  5183.1  370.82  5424.4  374.64  5445.4  376.18    5552  379.72
#Mann= 4 ,-1 , 0
  4374.6     .12       0  4993.6     .07       0  4997.6     .12       0
  5183.1     .05       0
Bank Sta=4993.6,4997.6
XS Rating Curve= 0 ,0
Exp/Cntr=0.3,0.1

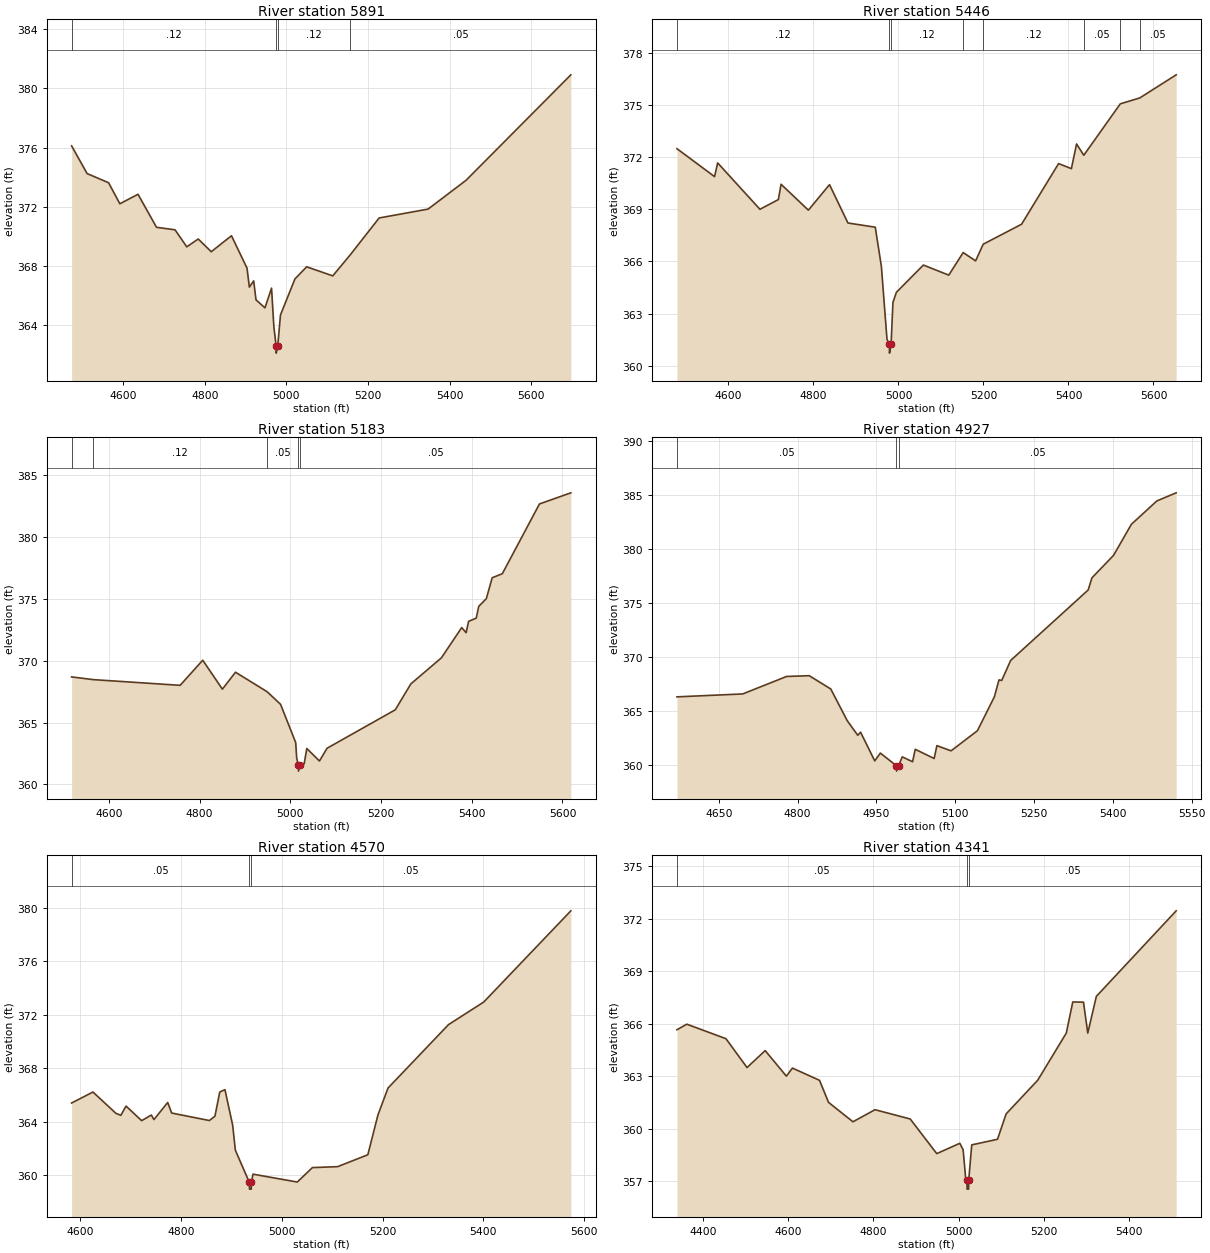
Type RM Length L Ch R = 1 ,5891    ,445,445,445
BEGIN DESCRIPTION:
Lacy 190 274
END DESCRIPTION:
XS GIS Cut Line= 3
      2670307.39      6817554.35      2670555.53      6817092.17
      2670993.65      6816547.48
#Sta/Elev= 30
  4473.7  376.12  4511.6  374.25  4564.3  373.63  4591.9  372.21  4636.4  372.85
  4681.8  370.62  4727.2  370.45  4755.9   369.3    4784  369.83    4816  368.97
  4865.5  370.05  4903.6  367.86  4909.3  366.58  4919.9     367  4925.6  365.72
  4947.5  365.18  4963.7  366.51  4969.4   363.9  4974.9  362.62  4975.2  362.12
  4978.9  362.62  4985.6   364.7    5021  367.13  5049.8  367.95  5113.8  367.34
  5156.9  368.77  5227.4  371.25  5347.4  371.85  5440.2  373.79  5697.3  380.92
#Mann= 4 ,-1 , 0
  4473.7     .12       0  4974.9     .07       0  4978.9     .12       0
  5156.9     .05       0
Bank Sta=4974.9,4978.9
XS Rating Curve= 0 ,0
Exp/Cntr=0.3,0.1

Type RM Length L Ch R = 1 ,5446    ,263,263,263
BEGIN DESCRIPTION:
Lacy 190 275
END DESCRIPTION:
XS GIS Cut Line= 3
      2670461.51      6817730.79      2670782.89      6817318.75
       2671144.5      6816775.91
#Sta/Elev= 30
  4478.7  372.49  4567.2  370.88  4574.5  371.67    4674     369  4717.4  369.56
  4723.7  370.44    4788  368.95  4837.7  370.42  4881.1  368.21  4945.4  367.97
  4959.8  365.71    4973  361.52  4978.6  361.22  4978.9  360.72  4982.6  361.22
    4987  363.64  4995.1  364.22  5058.6  365.79  5118.4  365.21  5152.3  366.51
  5181.5  366.03  5199.4  366.99  5289.7  368.14  5376.8  371.63  5406.9  371.34
  5419.1  372.76  5436.1  372.11    5522  375.07  5567.9  375.41  5653.5  376.74
#Mann= 8 ,-1 , 0
  4478.7     .12       0  4978.6     .07       0  4982.6     .12       0
  5152.3     .05       0  5199.4     .12       0  5436.1     .05       0
    5522     .12       0  5567.9     .05       0
Bank Sta=4978.6,4982.6
XS Rating Curve= 0 ,0
Exp/Cntr=0.3,0.1

Type RM Length L Ch R = 1 ,5183    ,256,256,256
BEGIN DESCRIPTION:
Lacy 190 276
END DESCRIPTION:
XS GIS Cut Line= 3
      2670704.48      6817815.81      2671009.85      6817427.57
      2671283.25      6816886.24
#Sta/Elev= 30
  4518.1  368.69  4565.9  368.47  4757.3  368.01  4807.1  370.04  4850.4   367.7
  4879.3  369.07  4949.1  367.49  4978.7  366.47    5012  363.38  5014.2  362.12
  5017.8  361.57  5018.1  361.07  5021.8  361.57  5030.6  361.66  5036.5   362.9
  5064.4  361.89  5081.1  362.92  5231.5  366.03  5265.9  368.13  5333.1  370.23
  5377.9  372.68  5387.6  372.27  5393.2  373.19  5409.9  373.44  5415.5   374.4
  5432.2  375.02  5445.1  376.71  5467.5  377.04  5549.3  382.68  5618.5  383.58
#Mann= 5 ,-1 , 0
  4518.1     .05       0  4565.9     .12       0  4949.1     .05       0
  5017.8     .03       0  5021.8     .05       0
Bank Sta=5017.8,5021.8
XS Rating Curve= 0 ,0
Exp/Cntr=0.3,0.1

Type RM Length L Ch R = 1 ,4927    ,357,357,357
BEGIN DESCRIPTION:
Lacy 190 277
END DESCRIPTION:
XS GIS Cut Line= 3
      2671117.42      6817890.53      2671246.98      6817474.26
       2671372.3      6816975.43
#Sta/Elev= 30
  4570.3  366.33  4695.5   366.6  4779.1  368.22  4822.1  368.29  4863.1  367.06
  4894.5  364.12  4914.5  362.77  4919.8  363.06  4946.8   360.4  4957.5  361.12
  4988.1  359.95  4988.3  359.45  4992.1  359.95  4999.2  360.77  5018.8  360.32
  5023.9  361.47  5059.9  360.62  5065.1  361.81  5092.1  361.33  5142.2  363.19
  5174.6  366.34  5183.3   367.9  5188.5  367.85  5205.5   369.7  5353.1  376.23
  5360.2  377.35  5401.4  379.44  5435.4  382.32  5483.9  384.48  5520.6  385.23
#Mann= 3 ,-1 , 0
  4570.3     .05       0  4988.1     .04       0  4992.1     .05       0
Bank Sta=4988.1,4992.1
XS Rating Curve= 0 ,0
Exp/Cntr=0.3,0.1

Type RM Length L Ch R = 1 ,4570    ,229,229,229
BEGIN DESCRIPTION:
Lacy 190 273
END DESCRIPTION:
XS GIS Cut Line= 3
      2671449.86      6818015.53      2671555.62      6817612.56
      2671579.83      6817038.19
#Sta/Elev= 30
  4582.4   365.4  4624.8  366.22  4670.3  364.63  4680.1  364.48  4690.5  365.17
  4721.5  364.08  4740.7   364.5  4745.9  364.16  4773.2  365.44  4781.1  364.65
  4855.9  364.09    4867  364.41  4876.6  366.22  4886.9   366.4  4902.2  363.75
  4907.6  361.87  4935.4  359.46  4935.7  358.96  4939.2  358.96  4939.4  359.46
  4942.6  360.08  5030.6  359.49  5060.6  360.57  5110.7  360.64  5170.7  361.53
  5190.8  364.51  5210.8  366.52  5330.9  371.26  5400.9  372.95  5573.9  379.77
#Mann= 3 ,-1 , 0
  4582.4     .05       0  4935.4     .03       0  4939.4     .05       0
Bank Sta=4935.4,4939.4
XS Rating Curve= 0 ,0
Exp/Cntr=0.3,0.1

Type RM Length L Ch R = 1 ,4341    ,230,230,230
BEGIN DESCRIPTION:
Lacy 190 271
END DESCRIPTION:
XS GIS Cut Line= 4
      2671408.57        6818186.      2671704.23      6817906.65
      2671769.24      6817658.75      2671830.05      6817155.25
#Sta/Elev= 30
  4339.5  365.65  4362.6  365.97  4454.4  365.14  4503.8  363.49  4546.3  364.46
    4596     363  4610.2  363.46  4673.7  362.76  4694.8   361.5  4752.1  360.39
  4803.8  361.08  4886.3  360.55  4948.5  358.57  5002.5  359.16  5010.3  358.79
  5016.3  357.16  5019.4  357.04  5019.6  356.54  5023.1  356.54  5023.4  357.04
  5030.5  359.07  5090.9  359.39  5111.1  360.84  5185.3  362.77  5252.1  365.46
  5267.3  367.24  5292.4  367.23  5302.5  365.46  5322.6  367.56  5509.7  372.45
#Mann= 3 ,-1 , 0
  4339.5     .05       0  5019.4     .03       0  5023.4     .05       0
Bank Sta=5019.4,5023.4
XS Rating Curve= 0 ,0
Exp/Cntr=0.3,0.1