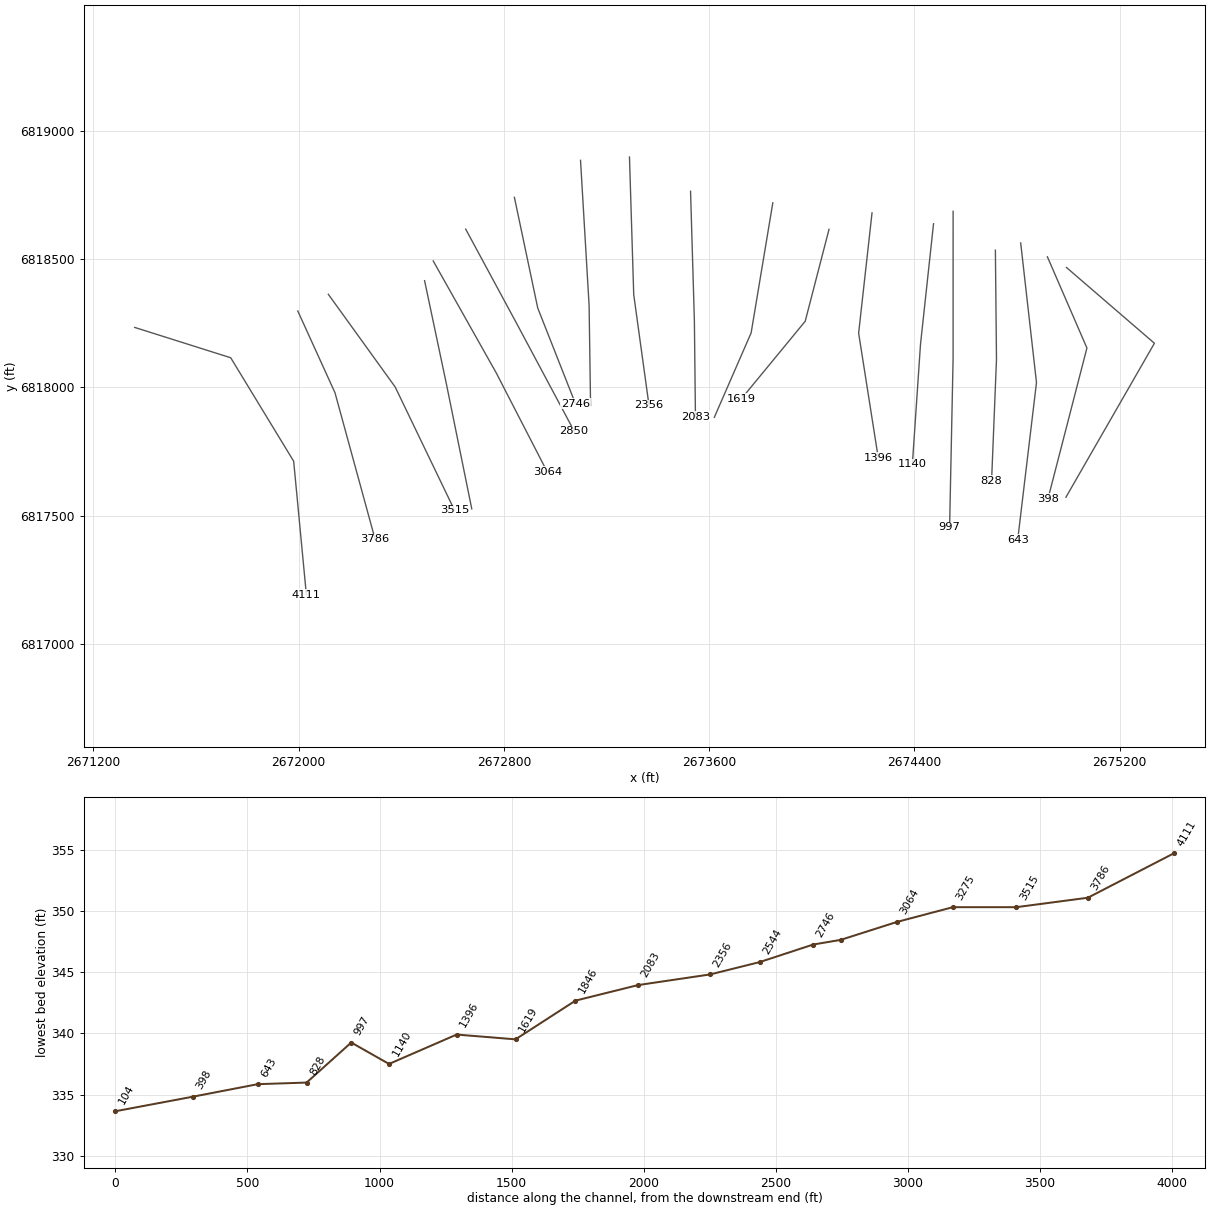
HEC-RAS study Lacy 190.prj: Lacy 190 Base Level Engineering

--- Lacy 190.g01 (geometry) --- (continued)

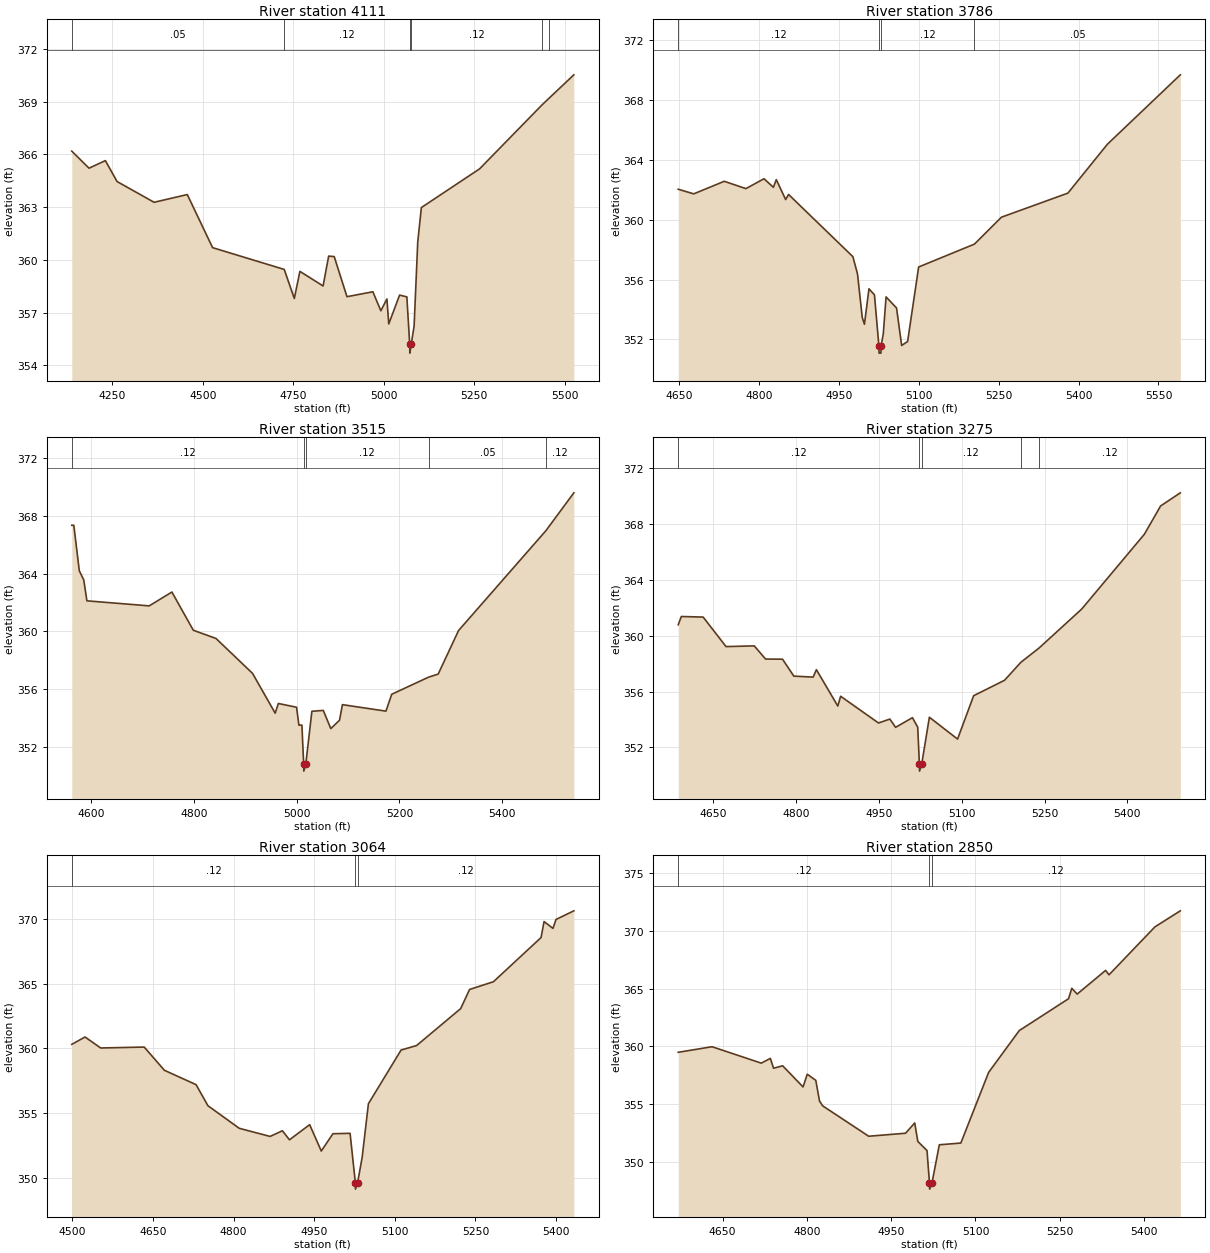
Type RM Length L Ch R = 1 ,4111    ,325,325,325
BEGIN DESCRIPTION:
Lacy 190 270
END DESCRIPTION:
XS GIS Cut Line= 4
      2671360.57      6818233.41      2671734.99      6818115.12
      2671980.41      6817711.76      2672029.91      6817191.63
#Sta/Elev= 30
  4137.6  366.19  4185.2  365.22  4230.5  365.65  4262.8  364.46  4365.1  363.28
  4456.8  363.72  4526.7   360.7  4724.7  359.46  4752.5  357.81    4768  359.35
    4832  358.52  4847.5  360.22  4862.8  360.19    4898  357.91  4969.6  358.19
  4991.6  357.11  5008.4  357.78  5013.5  356.36  5043.4     358  5063.5   357.9
  5071.4   355.2  5071.7   354.7  5075.5   355.2  5083.5  356.23  5093.6  361.03
  5103.6  362.98  5264.4  365.18  5436.1   368.8  5454.9  369.17  5524.9  370.53
#Mann= 6 ,-1 , 0
  4137.6     .05       0  4724.7     .12       0  5071.4     .07       0
  5075.5     .12       0  5436.1     .05       0  5454.9     .12       0
Bank Sta=5071.4,5075.5
XS Rating Curve= 0 ,0
Exp/Cntr=0.3,0.1

Type RM Length L Ch R = 1 ,3786    ,271,271,271
BEGIN DESCRIPTION:
Lacy 190 272
END DESCRIPTION:
XS GIS Cut Line= 3
      2671996.48      6818297.45      2672141.56      6817978.54
      2672298.01      6817407.03
#Sta/Elev= 30
  4648.1  362.04  4677.2  361.73  4734.5  362.57  4775.2  362.08  4809.2  362.74
  4826.8  362.17  4832.3  362.68  4849.8  361.35  4855.3  361.69  4976.1  357.53
  4984.8  356.37  4993.7  353.46  4997.8  353.01  5006.3  355.38  5016.6  354.98
  5024.9  351.58  5025.3  351.08  5028.8  351.08  5029.1  351.58  5033.2  352.37
  5038.4  354.84  5058.1   354.1  5067.7  351.59  5078.9  351.86  5099.6  356.84
  5204.4  358.37  5255.1  360.17  5379.9  361.78  5454.1  365.05    5591  369.69
#Mann= 4 ,-1 , 0
  4648.1     .12       0  5024.9     .07       0  5029.1     .12       0
  5204.4     .05       0
Bank Sta=5024.9,5029.1
XS Rating Curve= 0 ,0
Exp/Cntr=0.3,0.1

Type RM Length L Ch R = 1 ,3515    ,240,240,240
BEGIN DESCRIPTION:
Lacy 190 267
END DESCRIPTION:
XS GIS Cut Line= 3
      2672115.59      6818362.42      2672376.27      6818000.95
      2672607.18      6817521.08
#Sta/Elev= 30
  4561.6  367.36  4565.6  367.36  4576.3   364.2  4584.9  363.58  4591.1  362.12
  4712.5  361.77  4756.7  362.73  4798.4  360.08  4842.6  359.51  4913.8  357.09
  4957.9  354.33  4964.1     355  4999.6  354.74  5004.1   353.5    5010   353.5
  5013.4  350.81  5013.7  350.31  5017.6  350.81  5029.4  354.46  5051.6  354.52
  5066.3  353.26  5083.3  353.84  5088.9  354.92  5173.7  354.47    5185  355.64
    5257  356.83  5275.5  357.04  5315.2  360.06  5485.5  366.99  5539.8  369.61
#Mann= 5 ,-1 , 0
  4561.6     .12       0  5013.4     .07       0  5017.6     .12       0
    5257     .05       0  5485.5     .12       0
Bank Sta=5013.4,5017.6
XS Rating Curve= 0 ,0
Exp/Cntr=0.3,0.1

Type RM Length L Ch R = 1 ,3275    ,211,211,211
BEGIN DESCRIPTION:
Lacy 190 269
END DESCRIPTION:
XS GIS Cut Line= 3
      2672490.74      6818415.62      2672576.02      6818011.82
      2672674.69      6817526.04
#Sta/Elev= 30
  4587.3  360.77  4592.9  361.36  4632.4  361.32  4673.8  359.21  4724.9  359.26
  4745.3  358.32    4776  358.31  4796.4   357.1  4831.4  357.03  4837.3  357.56
    4876  354.96  4881.1  355.66  4949.7  353.75  4970.2  354.03  4980.6  353.44
    5011  354.13  5020.6  353.45  5023.6  350.81  5023.9  350.31  5027.8  350.81
  5041.7  354.16  5092.7   352.6  5121.8   355.7  5177.6   356.8  5207.3  358.09
  5240.2  359.11  5317.2  361.89  5430.7  367.24    5460  369.26  5495.7   370.2
#Mann= 5 ,-1 , 0
  4587.3     .12       0  5023.6     .07       0  5027.8     .12       0
  5207.3     .05       0  5240.2     .12       0
Bank Sta=5023.6,5027.8
XS Rating Curve= 0 ,0
Exp/Cntr=0.3,0.1

Type RM Length L Ch R = 1 ,3064    ,214,214,214
BEGIN DESCRIPTION:
Lacy 190 268
END DESCRIPTION:
XS GIS Cut Line= 3
      2672524.35      6818492.51       2672770.2      6818055.87
      2672968.48      6817670.93
#Sta/Elev= 30
  4498.9  360.32  4523.6  360.89  4552.7  360.04  4633.7  360.11  4671.3  358.31
  4730.2   357.2  4752.2  355.57  4810.5  353.82  4867.9  353.19  4890.8  353.63
  4903.9  352.93  4941.5   354.1  4963.1  352.06  4984.8   353.4  5016.7  353.43
  5026.5  349.61  5026.8  349.11  5030.7  349.61  5039.2  351.58  5050.8  355.72
  5111.6  359.88  5140.5  360.23  5222.5  363.09    5239  364.57  5283.4  365.17
    5372  368.59  5377.6  369.83  5394.2   369.3  5399.8  369.99    5433  370.66
#Mann= 3 ,-1 , 0
  4498.9     .12       0  5026.5     .07       0  5030.7     .12       0
Bank Sta=5026.5,5030.7
XS Rating Curve= 0 ,0
Exp/Cntr=0.3,0.1

Type RM Length L Ch R = 1 ,2850    ,104,104,104
BEGIN DESCRIPTION:
Lacy 190 266
END DESCRIPTION:
XS GIS Cut Line= 3
      2672651.01      6818616.48      2672856.24      6818236.49
      2673073.85      6817829.03
#Sta/Elev= 30
  4570.9  359.49  4631.1  359.97  4718.7  358.55  4734.9  358.96  4740.6  358.11
  4756.8  358.32  4793.1  356.49  4800.6  357.59  4815.8  357.06  4822.4  355.27
  4828.1  354.85    4910  352.22  4975.6  352.48  4991.9  353.37  4997.4  351.77
  5013.8  350.98  5018.2  348.14  5018.5  347.64  5022.5  348.14  5035.7  351.48
    5074  351.63  5123.5  357.75    5178  361.37  5265.8  364.13  5271.5  365.03
  5281.1  364.53  5331.7  366.58  5337.8   366.2  5419.5  370.35  5464.7  371.74
#Mann= 3 ,-1 , 0
  4570.9     .12       0  5018.2     .07       0  5022.5     .12       0
Bank Sta=5018.2,5022.5
XS Rating Curve= 0 ,0
Exp/Cntr=0.3,0.1

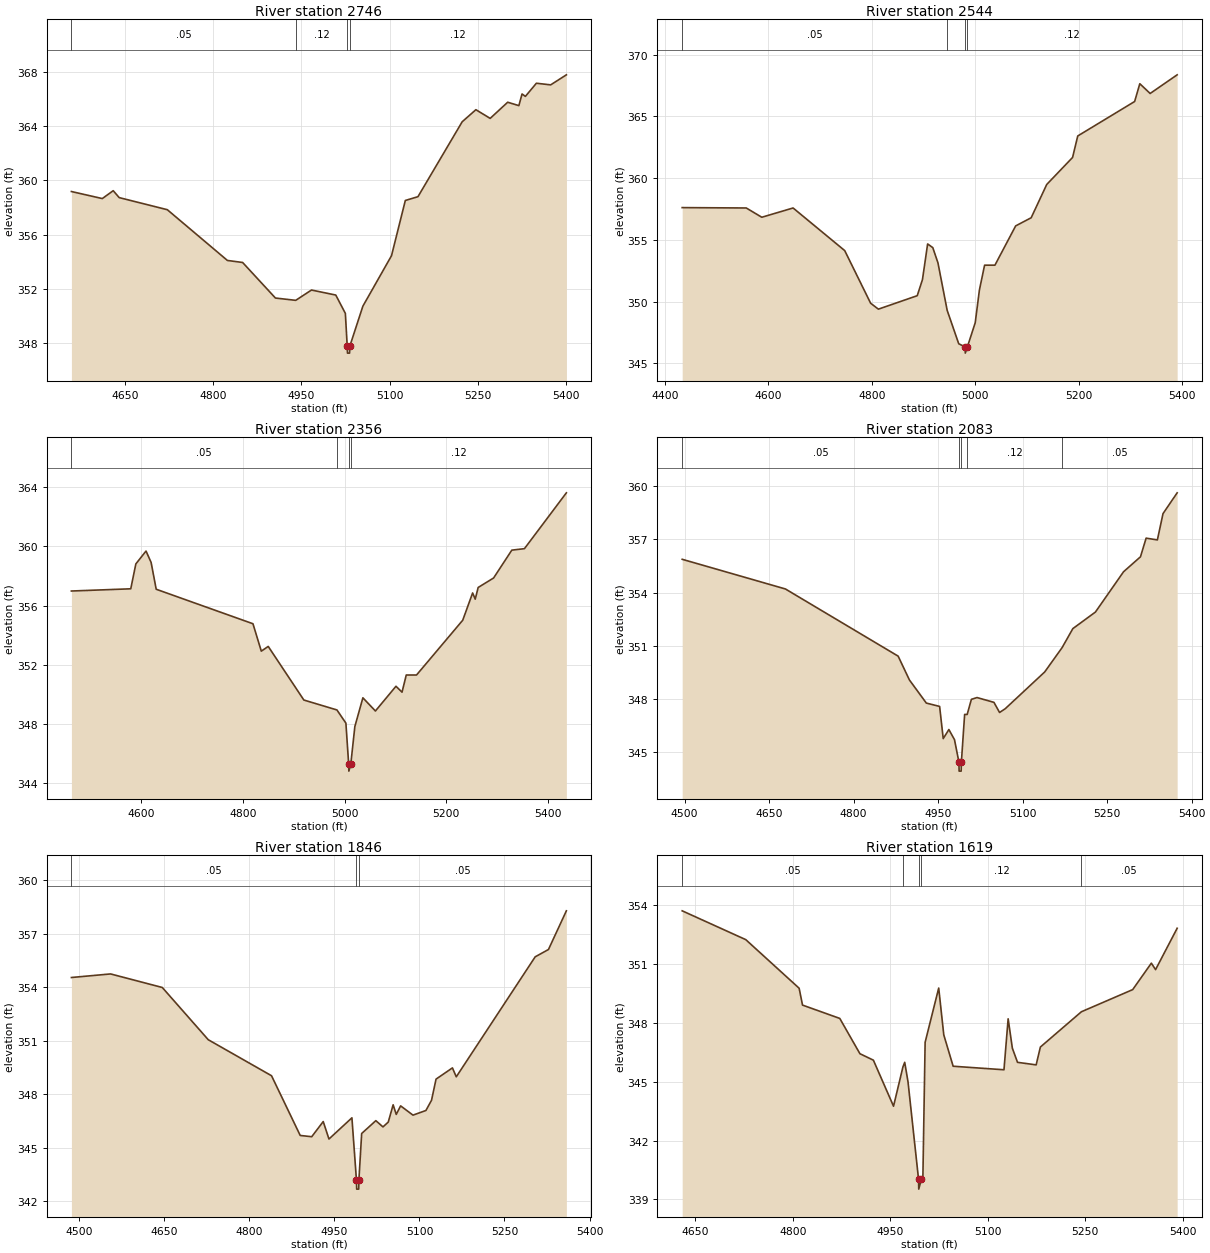
Type RM Length L Ch R = 1 ,2746    ,202,202,202
BEGIN DESCRIPTION:
Lacy 190 249
END DESCRIPTION:
XS GIS Cut Line= 3
      2672840.83      6818740.56      2672931.84      6818308.95
      2673078.79      6817936.16
#Sta/Elev= 30
  4558.9  359.17  4611.4  358.65    4630  359.23  4640.2  358.72    4722  357.83
  4824.2  354.09  4850.1  353.94  4905.9  351.32  4940.4  351.15  4967.2  351.91
  5008.5  351.54  5024.8  350.19    5028  347.76  5028.4  347.26    5032  347.26
  5032.3  347.76  5054.6  350.72  5103.3  354.44  5126.8  358.51  5148.3  358.79
  5223.5  364.31  5246.8   365.2  5271.1  364.56  5300.9  365.75  5319.9   365.5
  5325.3  366.36    5331  366.18  5349.7  367.15    5374  367.03  5400.7  367.77
#Mann= 4 ,-1 , 0
  4558.9     .05       0  4940.4     .12       0    5028     .07       0
  5032.3     .12       0
Bank Sta=5028,5032.3
XS Rating Curve= 0 ,0
Exp/Cntr=0.3,0.1

Type RM Length L Ch R = 1 ,2544    ,188,188,188
BEGIN DESCRIPTION:
Lacy 190 248
END DESCRIPTION:
XS GIS Cut Line= 3
      2673098.62      6818884.65      2673132.06      6818319.14
      2673137.76      6817928.78
#Sta/Elev= 30
  4433.5  357.61  4557.4  357.58  4587.4  356.83  4647.9  357.58  4747.7  354.13
  4797.8  349.87  4812.8  349.39  4887.9  350.48    4898  351.78    4908  354.67
    4918  354.37    4928  353.13  4945.8  349.29  4968.1  346.59  4980.5  346.33
  4980.8  345.83  4984.8  346.33    5000  348.29  5008.1  350.94  5018.1  352.95
  5038.1  352.95  5078.2  356.13  5108.2  356.79  5138.2  359.48  5188.2  361.67
  5198.2  363.41  5308.2   366.2  5318.2  367.64  5338.2  366.85  5390.4  368.36
#Mann= 4 ,-1 , 0
  4433.5     .05       0  4945.8     .12       0  4980.5     .07       0
  4984.8     .12       0
Bank Sta=4980.5,4984.8
XS Rating Curve= 0 ,0
Exp/Cntr=0.3,0.1

Type RM Length L Ch R = 1 ,2356    ,273,273,273
BEGIN DESCRIPTION:
Lacy 190 247
END DESCRIPTION:
XS GIS Cut Line= 3
      2673289.43       6818897.5      2673306.01      6818361.06
       2673365.6      6817929.35
#Sta/Elev= 30
  4463.3  356.98  4579.9  357.13  4589.9  358.81  4609.9  359.68  4619.9  358.91
  4629.9   357.1    4820  354.77  4836.4  352.92    4850  353.24    4920  349.62
    4985  348.95  5002.6  348.06    5008  345.32  5008.4  344.82  5012.3  345.32
  5020.2  347.83    5036  349.77  5060.6  348.88    5101  350.55  5112.9  350.15
  5121.2  351.31  5141.4  351.31  5232.2  355.01  5251.6  356.85  5256.7  356.43
  5262.5  357.22  5292.8  357.86  5328.6  359.74  5353.4  359.84  5435.8  363.61
#Mann= 4 ,-1 , 0
  4463.3     .05       0    4985     .12       0    5008     .07       0
  5012.3     .12       0
Bank Sta=5008,5012.3
XS Rating Curve= 0 ,0
Exp/Cntr=0.3,0.1

Type RM Length L Ch R = 1 ,2083    ,237,237,237
BEGIN DESCRIPTION:
Lacy 190 246
END DESCRIPTION:
XS GIS Cut Line= 3
      2673527.52      6818764.12      2673542.44      6818260.14
      2673546.61      6817885.87
#Sta/Elev= 30
  4495.8  355.87    4679   354.2  4879.1  350.42  4899.1  349.08  4929.1  347.78
  4952.7  347.59  4959.1  345.78  4969.1  346.29  4979.1  345.72    4987  344.45
  4987.3  343.95  4990.9  343.95  4991.3  344.45  4997.1  347.14  5001.6  347.14
  5009.1  347.99  5019.1  348.09  5049.1  347.82  5059.1  347.25  5069.1  347.46
  5139.2  349.53  5170.1   350.9  5189.2  351.97  5229.2   352.9  5279.2  355.17
  5309.2  356.01  5319.2  357.06  5339.2  356.96  5349.2  358.44  5374.3  359.61
#Mann= 5 ,-1 , 0
  4495.8     .05       0    4987     .03       0  4991.3     .05       0
  5001.6     .12       0  5170.1     .05       0
Bank Sta=4987,4991.3
XS Rating Curve= 0 ,0
Exp/Cntr=0.3,0.1

Type RM Length L Ch R = 1 ,1846    ,227,227,227
BEGIN DESCRIPTION:
Lacy 190 245
END DESCRIPTION:
XS GIS Cut Line= 3
       2673848.2      6818719.11      2673763.71      6818212.21
      2673620.16      6817882.94
#Sta/Elev= 30
  4486.1  354.55  4555.2  354.75  4646.4  353.99  4727.5  351.06  4839.1  349.04
  4889.7  345.69    4910  345.62  4930.3  346.47  4940.4  345.49  4980.9  346.68
  4988.9  343.18  4989.3  342.68  4992.9  342.68  4993.2  343.18  4998.1   345.8
  5023.1  346.52  5035.7  346.17    5045  346.44  5053.6  347.41  5059.1  346.87
  5066.8  347.35  5088.6  346.83  5111.4  347.09  5121.3  347.66  5129.3  348.85
  5158.2  349.48    5165  348.98  5304.2  355.71  5327.6  356.12  5359.2  358.29
#Mann= 3 ,-1 , 0
  4486.1     .05       0  4988.9     .03       0  4993.2     .05       0
Bank Sta=4988.9,4993.2
XS Rating Curve= 0 ,0
Exp/Cntr=0.3,0.1

Type RM Length L Ch R = 1 ,1619    ,223,223,223
BEGIN DESCRIPTION:
Lacy 190 244
END DESCRIPTION:
XS GIS Cut Line= 3
      2674067.28      6818615.69      2673974.42      6818257.33
      2673725.82      6817955.28
#Sta/Elev= 30
  4629.8  353.72  4727.6  352.25  4809.7  349.77  4814.9  348.91  4872.2  348.23
  4903.2  346.43  4923.9   346.1  4954.9  343.75  4969.4  345.76  4972.1  345.99
  4977.2  344.99  4993.4  340.02  4993.7  339.52  4997.7  340.02    5000  340.02
  5003.5  347.01  5024.4  349.78  5032.2  347.39  5046.6  345.79  5124.8  345.61
  5131.2  348.21  5137.7  346.71  5145.6  345.99  5174.3  345.86  5180.8  346.77
  5243.9  348.57  5322.8   349.7  5351.5  351.05    5358  350.72  5391.2  352.83
#Mann= 5 ,-1 , 0
  4629.8     .05       0  4969.4     .12       0  4993.4     .07       0
  4997.7     .12       0  5243.9     .05       0
Bank Sta=4993.4,4997.7
XS Rating Curve= 0 ,0
Exp/Cntr=0.3,0.1

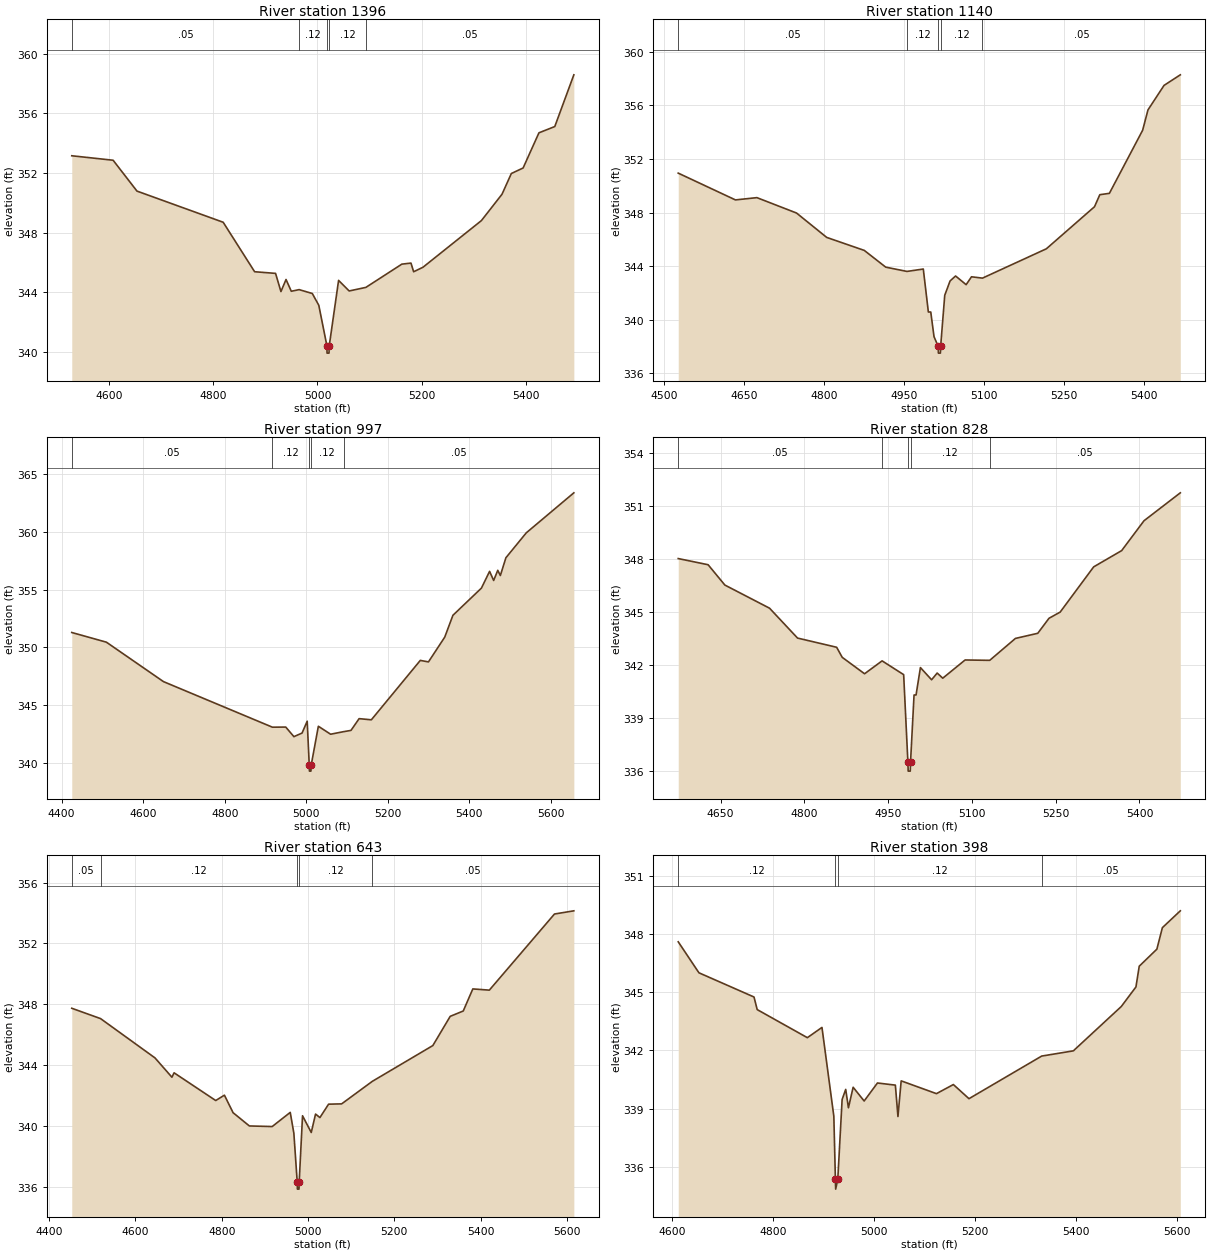
Type RM Length L Ch R = 1 ,1396    ,256,256,256
BEGIN DESCRIPTION:
Lacy 190 243
END DESCRIPTION:
XS GIS Cut Line= 3
      2674234.92      6818679.92      2674182.71      6818211.12
      2674259.23       6817724.8
#Sta/Elev= 30
  4528.3  353.15  4607.7  352.85  4653.5  350.78    4819  348.69  4879.4  345.37
  4919.6  345.26  4929.9  344.04  4939.7  344.85  4949.8  344.06  4964.9  344.17
  4990.1  343.91  5002.6  343.12  5018.1  340.41  5018.5  339.91  5022.2  339.91
  5022.7  340.41  5040.6  344.79  5060.9  344.08    5093  344.32  5162.1  345.88
  5179.6  345.95  5184.7  345.37  5202.6  345.67  5314.8   348.8  5354.4  350.57
  5372.3  351.96  5394.9  352.33  5425.3  354.69  5455.7  355.11  5492.3  358.58
#Mann= 5 ,-1 , 0
  4528.3     .05       0  4964.9     .12       0  5018.1     .07       0
  5022.7     .12       0    5093     .05       0
Bank Sta=5018.1,5022.7
XS Rating Curve= 0 ,0
Exp/Cntr=0.3,0.1

Type RM Length L Ch R = 1 ,1140    ,143,143,143
BEGIN DESCRIPTION:
Lacy 190 242
END DESCRIPTION:
XS GIS Cut Line= 3
      2674474.72      6818637.57      2674423.82      6818167.12
      2674392.21      6817700.59
#Sta/Elev= 30
  4526.8  350.95    4634  348.95  4674.2  349.12  4748.5  347.97    4805  346.15
  4875.4  345.18  4915.6  343.93  4955.5  343.61    4986  343.79  4995.5  340.58
    5000  340.58  5006.1  338.74  5013.9  338.01  5014.3  337.51    5018  337.51
  5018.5  338.01  5026.2  341.83  5036.2   342.9  5046.5  343.27  5066.3  342.62
  5076.3  343.21  5096.9  343.11  5216.6   345.3  5306.8  348.44  5316.8  349.34
  5334.7  349.44    5397  354.15    5407  355.67  5437.1   357.5  5467.6  358.29
#Mann= 5 ,-1 , 0
  4526.8     .05       0  4955.5     .12       0  5013.9     .07       0
  5018.5     .12       0  5096.9     .05       0
Bank Sta=5013.9,5018.5
XS Rating Curve= 0 ,0
Exp/Cntr=0.3,0.1

Type RM Length L Ch R = 1 ,997     ,169,169,169
BEGIN DESCRIPTION:
Lacy 190 241
END DESCRIPTION:
XS GIS Cut Line= 3
        2674551.      6818685.99      2674550.91      6818110.79
      2674537.29      6817454.33
#Sta/Elev= 30
  4424.8  351.28  4509.8  350.44  4649.8  347.02    4917  343.07  4949.8  343.08
  4969.8  342.25  4989.8  342.56  5002.4  343.59  5007.5  339.76  5007.9  339.26
  5011.6  339.26  5012.1  339.76  5029.8  343.15  5059.8  342.46  5091.5  342.68
  5109.8  342.79  5129.8  343.81  5159.8  343.71  5279.9  348.86  5299.9  348.73
  5339.9  350.88  5359.9  352.77  5429.9  355.13  5449.9  356.58  5459.9  355.79
  5469.9  356.67  5476.3  356.22  5489.9  357.76  5539.9  359.92  5656.6  363.39
#Mann= 5 ,-1 , 0
  4424.8     .05       0    4917     .12       0  5007.5     .07       0
  5012.1     .12       0  5091.5     .05       0
Bank Sta=5007.5,5012.1
XS Rating Curve= 0 ,0
Exp/Cntr=0.3,0.1

Type RM Length L Ch R = 1 ,828     ,185,185,185
BEGIN DESCRIPTION:
Lacy 190 237
END DESCRIPTION:
XS GIS Cut Line= 3
      2674715.82      6818534.54      2674720.07      6818108.76
        2674701.      6817636.05
#Sta/Elev= 30
  4574.2  348.02  4627.7  347.67  4657.7  346.52  4737.7  345.21  4787.8  343.52
  4857.8     343  4867.8  342.43  4907.8   341.5  4939.2  342.23  4977.8  341.45
  4985.4  336.49  4985.9  335.99  4989.6  335.99  4990.1  336.49  4996.4   340.3
    5000   340.3  5007.8  341.85  5027.8  341.16  5037.8  341.54  5047.8  341.25
  5087.8  342.28  5131.9  342.26  5177.9   343.5  5217.9  343.79    5238  344.64
    5258  344.99    5318  347.55  5368.1  348.47  5408.1  350.16  5473.1  351.74
#Mann= 5 ,-1 , 0
  4574.2     .05       0  4939.2     .12       0  4985.4     .07       0
  4990.1     .12       0  5131.9     .05       0
Bank Sta=4985.4,4990.1
XS Rating Curve= 0 ,0
Exp/Cntr=0.3,0.1

Type RM Length L Ch R = 1 ,643     ,245,245,245
BEGIN DESCRIPTION:
Lacy 190 240
END DESCRIPTION:
XS GIS Cut Line= 3
      2674814.44      6818562.63        2674876.       6818018.5
      2674802.86      6817406.45
#Sta/Elev= 30
  4452.4  347.74  4519.2  347.06  4645.3  344.48  4684.6  343.21  4689.6   343.5
  4786.1  341.68  4806.3  342.03  4826.4  340.88  4864.1  340.01    4917  339.97
  4958.9   340.9  4967.3  339.53    4975  336.36  4975.5  335.86  4979.2  335.86
  4979.7  336.36  4987.4  340.68  5007.6  339.58  5017.6  340.79  5027.7  340.56
  5047.8  341.44  5078.1  341.46  5149.2  342.94  5289.5  345.29  5329.8  347.21
    5360  347.56  5382.2  349.01  5420.5  348.93  5571.5  353.93  5616.4  354.14
#Mann= 5 ,-1 , 0
  4452.4     .05       0  4519.2     .12       0    4975     .07       0
  4979.7     .12       0  5149.2     .05       0
Bank Sta=4975,4979.7
XS Rating Curve= 0 ,0
Exp/Cntr=0.3,0.1

Type RM Length L Ch R = 1 ,398     ,294,294,294
BEGIN DESCRIPTION:
Lacy 190 239
END DESCRIPTION:
XS GIS Cut Line= 3
      2674918.53      6818508.61       2675072.6      6818153.17
      2674920.97      6817566.03
#Sta/Elev= 30
  4612.6  347.61  4653.6  346.01  4762.6  344.76  4768.9  344.11  4868.2  342.66
  4897.1  343.19  4920.6   338.6  4923.7  335.34  4924.2  334.84  4928.4  335.34
    4937  339.47  4944.1  339.99  4949.5  339.04  4958.8   340.1  4980.6  339.39
  5006.9  340.32  5042.4  340.21  5047.5  338.59  5053.9  340.43  5123.7  339.77
  5157.2  340.24  5188.1  339.51    5332  341.71  5394.7  341.98  5489.6  344.27
  5518.6  345.28  5525.1  346.35    5560  347.23  5570.9  348.34  5606.4  349.21
#Mann= 4 ,-1 , 0
  4612.6     .12       0  4923.7     .07       0  4928.4     .12       0
    5332     .05       0
Bank Sta=4923.7,4928.4
XS Rating Curve= 0 ,0
Exp/Cntr=0.3,0.1

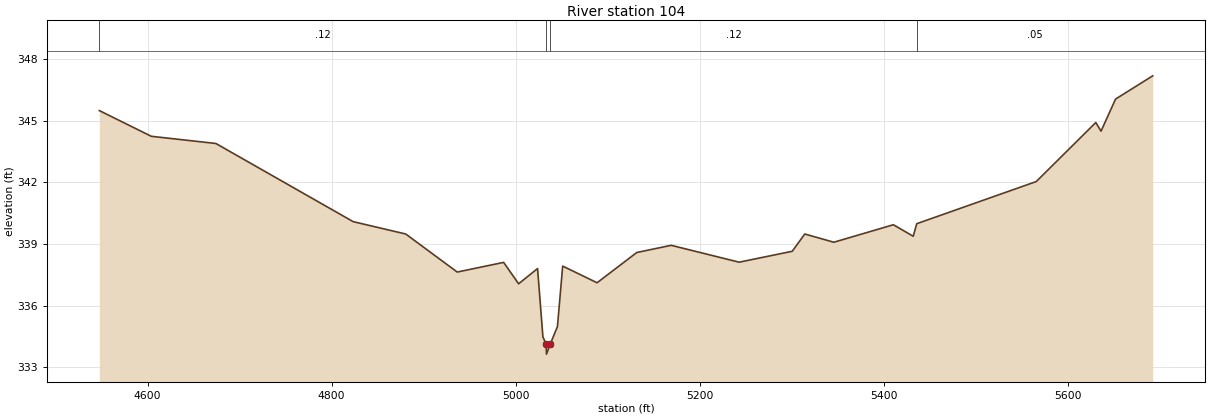
Type RM Length L Ch R = 1 ,104     ,0,0,0
BEGIN DESCRIPTION:
Lacy 190 238
END DESCRIPTION:
XS GIS Cut Line= 3
      2674992.93      6818466.97      2675335.75      6818171.61
       2674990.7      6817571.31
#Sta/Elev= 30
  4547.5  345.49    4604  344.24  4674.2  343.89  4823.4  340.09  4880.5  339.49
  4936.5  337.64  4986.9  338.11  5003.2  337.07  5023.8  337.81  5029.6  334.49
    5033  334.15  5033.5  333.65  5037.7  334.15  5045.4  334.99  5051.1  337.93
  5088.5  337.12  5131.6  338.59    5169  338.94  5242.9  338.12  5300.6  338.65
  5314.2  339.49  5345.8  339.09  5410.5  339.94  5432.1  339.38  5435.9  339.99
  5565.8  342.04  5630.5  344.91  5636.2  344.49    5652  346.05  5692.4  347.18
#Mann= 4 ,-1 , 0
  4547.5     .12       0    5033     .07       0  5037.7     .12       0
  5435.9     .05       0
Bank Sta=5033,5037.7
XS Rating Curve= 0 ,0
Exp/Cntr=0.3,0.1

Chan Stop Cuts=-1
Use User Specified Reach Order=0
Composite Channel Slope=5