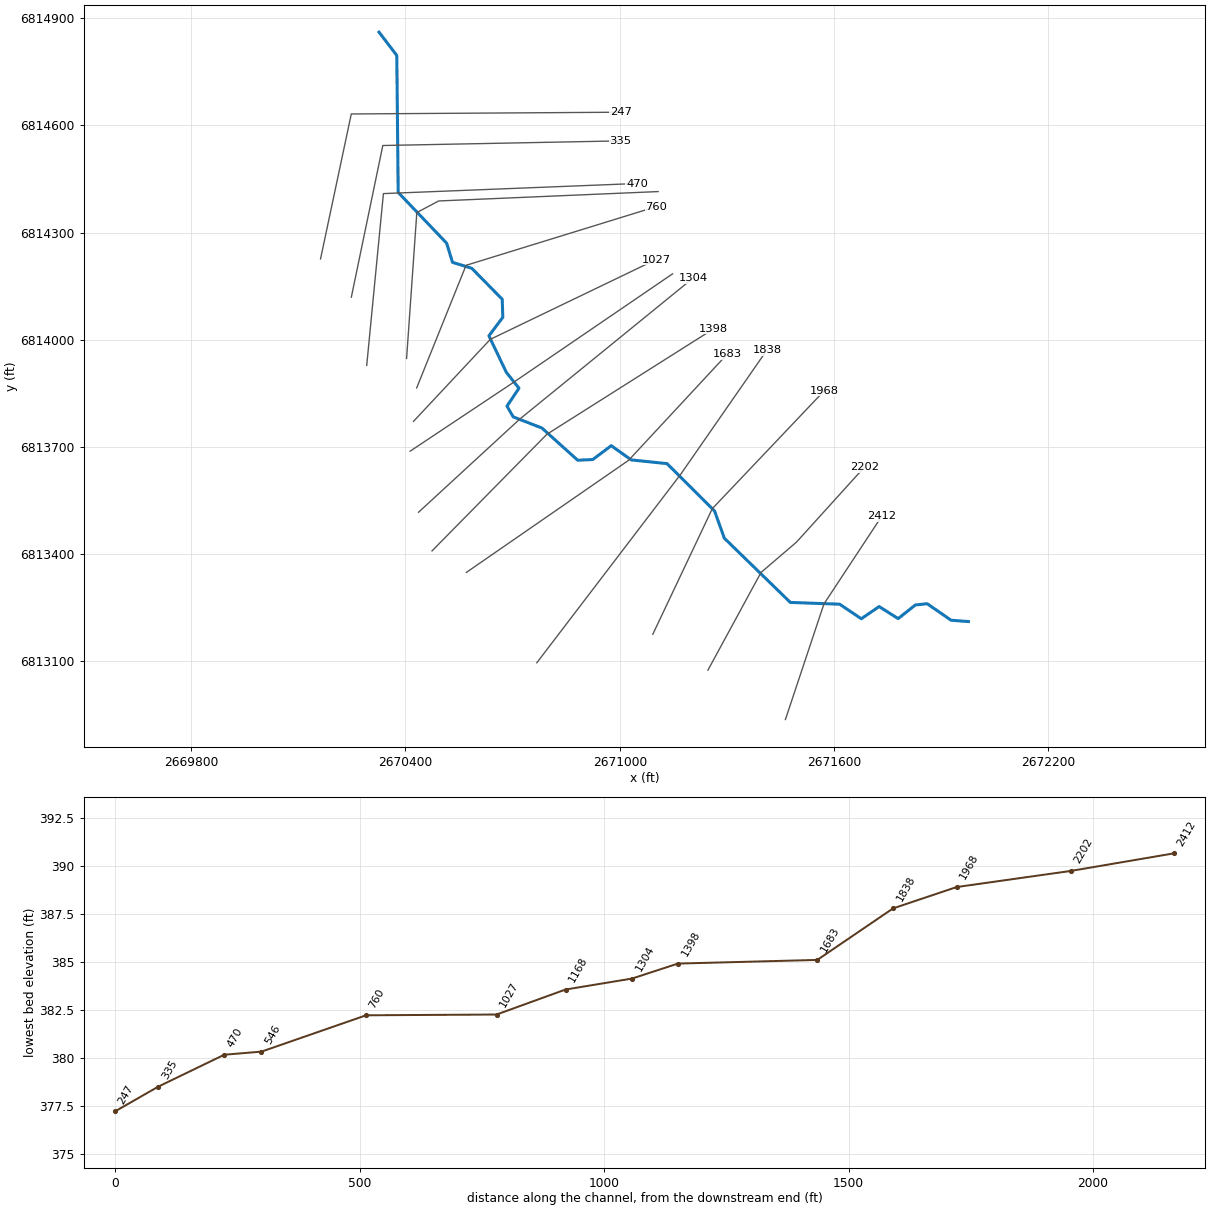
--- Lacy 191.prj (project) ---

Proj Title=Lacy 191 Base Level Engineering
Current Plan=p01
Default Exp/Contr=0.3,0.1
English Units
Geom File=g01
Flow File=f01
Plan File=p01
BEGIN DESCRIPTION:
Lacy 191
END DESCRIPTION:

--- Lacy 191.p01 (plan) ---

Plan Title=Multiple Run
Short Identifier=Multiple
Geom File=g01
Flow File=f01
Subcritical Flow
K Sum by GR= 0
Std Step Tol= 0.01
Critical Tol= 0.01
Num of Std Step Trials= 20
Max Error Tol= 0.3
Flow Tol Ratio= 0.001
Split Flow NTrial= 30
Split Flow Tol= 0.02
Split Flow Ratio= 0.02
Log Output Level= 0
Friction Slope Method= 1
Unsteady Friction Slope Method= 2
Unsteady Bridges Friction Slope Method= 1
Parabolic Critical Depth
Global Vel Dist=  1 , 1 , 1
Global Log Level= 0
CheckData=True
Encroach Param= -1, 0, 0, 0
BEGIN DESCRIPTION:
Multiple Run
END DESCRIPTION:

--- Lacy 191.f01 (steady flow) ---

Flow Title=Multiple
Number of Profiles=7
Profile Names=10-year,25-year,50-year,1pct_min,100-year,1pct_plu,500-year
River Rch & RM= Lacy 191,Reach-1,2412
     165     202     229     129     258     514     326
Boundary for River Rch & Prof#=Lacy 191,Reach-1,1
Up Type=0
Dn Type=3
Dn Slope=0.005
Boundary for River Rch & Prof#=Lacy 191,Reach-1,2
Up Type=0
Dn Type=3
Dn Slope=0.005
Boundary for River Rch & Prof#=Lacy 191,Reach-1,3
Up Type=0
Dn Type=3
Dn Slope=0.005
Boundary for River Rch & Prof#=Lacy 191,Reach-1,4
Up Type=0
Dn Type=3
Dn Slope=0.005
Boundary for River Rch & Prof#=Lacy 191,Reach-1,5
Up Type=0
Dn Type=3
Dn Slope=0.005
Boundary for River Rch & Prof#=Lacy 191,Reach-1,6
Up Type=0
Dn Type=3
Dn Slope=0.005
Boundary for River Rch & Prof#=Lacy 191,Reach-1,7
Up Type=0
Dn Type=3
Dn Slope=0.005

--- Lacy 191.g01 (geometry) ---

Geom Title=Existing Conditions

River Reach=Lacy 191,Reach-1
Reach XY= 30
      2671976.00      6813211.00      2671927.49      6813214.69
      2671860.59      6813260.96      2671827.63      6813257.42
      2671779.23      6813219.30      2671726.00      6813252.97
      2671676.10      6813218.78      2671615.56      6813259.61
      2671477.47      6813264.54      2671292.65      6813444.33
      2671265.22      6813520.68      2671132.17      6813653.14
      2671031.90      6813663.55      2670975.99      6813703.41
      2670924.35      6813664.57      2670882.05      6813662.66
      2670782.00      6813752.82      2670701.64      6813784.01
      2670684.07      6813814.15      2670717.74      6813864.22
      2670682.35      6813908.71      2670633.56      6814011.00
      2670672.43      6814062.65      2670670.89      6814113.30
      2670585.44      6814200.12      2670531.62      6814216.62
      2670515.11      6814270.42      2670379.54      6814412.46
      2670375.64      6814795.85      2670326.00      6814861.00

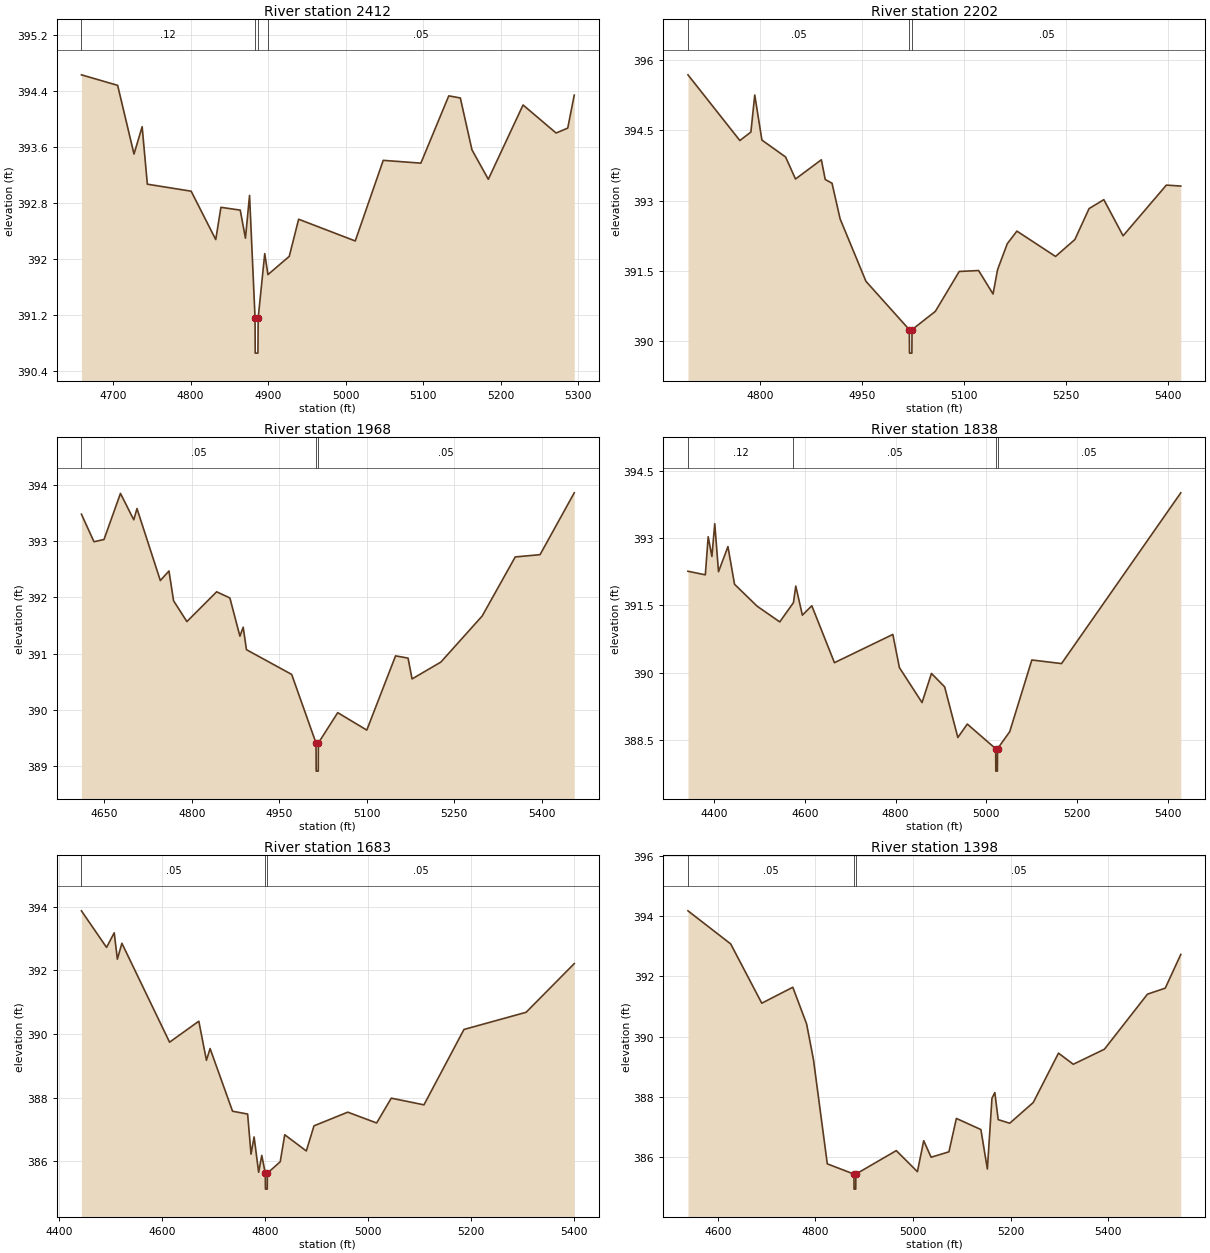
Type RM Length L Ch R = 1,2412,210,210,210
BEGIN DESCRIPTION:
Lacy 191 307
END DESCRIPTION:
XS GIS Cut Line= 3
      2671463.66      6812936.72      2671571.40      6813260.04
      2671733.53      6813506.14
#Sta/Elev= 30
  4659.2  394.63  4705.9  394.48  4727.0  393.50  4737.5  393.89  4744.2  393.07
  4800.7  392.97  4832.4  392.28  4839.1  392.74  4864.0  392.70  4870.7  392.30
  4876.0  392.91  4883.1  391.16  4883.3  390.66  4886.8  390.66  4887.1  391.16
  4895.6  392.08  4899.7  391.78  4927.2  392.04  4939.3  392.57  5012.3  392.26
  5048.4  393.41  5096.9  393.37  5132.9  394.33  5147.8  394.30  5162.8  393.56
  5183.9  393.14  5228.7  394.20  5271.3  393.80  5286.3  393.87  5294.7  394.34
#Mann=4,-1,0
  4659.2    0.12       0  4883.1    0.04       0  4887.1    0.12       0
  4899.7    0.05       0
Bank Sta=4883.1,4887.1
Exp/Cntr=0.3,0.1

Type RM Length L Ch R = 1,2202,234,234,234
BEGIN DESCRIPTION:
Lacy 191 301
END DESCRIPTION:
XS GIS Cut Line= 4
      2671246.75      6813074.88      2671395.18      6813348.21
      2671494.78      6813433.49      2671684.29      6813642.79
#Sta/Elev= 30
  4694.0  395.68  4770.3  394.28  4786.5  394.46  4792.2  395.25  4802.7  394.29
  4837.5  393.93  4852.1  393.46  4890.1  393.87  4895.8  393.45  4905.8  393.37
  4917.7  392.61  4955.7  391.28  5019.4  390.25  5019.7  389.75  5023.2  389.75
  5023.4  390.25  5057.7  390.64  5092.8  391.49  5121.3  391.51  5142.5  391.01
  5149.2  391.53  5163.4  392.08  5177.6  392.35  5234.4  391.81  5262.8  392.17
  5283.7  392.83  5305.4  393.02  5333.7  392.25  5397.3  393.33  5418.5  393.31
#Mann=3,-1,0
  4694.0    0.05       0  5019.4    0.04       0  5023.4    0.05       0
Bank Sta=5019.4,5023.4
Exp/Cntr=0.3,0.1

Type RM Length L Ch R = 1,1968,130,130,130
BEGIN DESCRIPTION:
Lacy 191 298
END DESCRIPTION:
XS GIS Cut Line= 3
      2671092.39      6813175.40      2671258.99      6813527.08
      2671572.53      6813857.29
#Sta/Elev= 30
  4611.0  393.48  4632.5  392.99  4649.7  393.03  4677.9  393.85  4700.7  393.38
  4706.2  393.58  4746.2  392.30  4761.0  392.47  4768.9  391.94  4791.7  391.57
  4842.7  392.10  4865.4  391.99  4882.6  391.31  4888.2  391.47  4893.8  391.07
  4971.3  390.63  5013.0  389.41  5013.3  388.91  5016.8  388.91  5017.0  389.41
  5050.2  389.95  5100.0  389.64  5149.3  390.96  5170.7  390.92  5177.6  390.55
  5227.0  390.85  5297.8  391.67  5354.4  392.72  5396.9  392.76  5455.5  393.86
#Mann=3,-1,0
  4611.0    0.05       0  5013.0    0.04       0  5017.0    0.05       0
Bank Sta=5013,5017
Exp/Cntr=0.3,0.1

Type RM Length L Ch R = 1,1838,155,155,155
BEGIN DESCRIPTION:
Lacy 191 300
END DESCRIPTION:
XS GIS Cut Line= 3
      2670767.72      6813095.62      2671170.89      6813623.88
      2671411.79      6813970.93
#Sta/Elev= 30
  4342.1  392.26  4380.4  392.18  4386.7  393.03  4394.9  392.59  4401.2  393.32
  4409.5  392.25  4430.3  392.81  4444.8  391.97  4494.7  391.48  4544.6  391.13
  4574.8  391.56  4579.9  391.93  4594.5  391.28  4615.3  391.49  4665.2  390.22
  4794.0  390.85  4808.5  390.11  4858.4  389.33  4879.2  389.98  4908.3  389.68
  4937.4  388.55  4958.2  388.85  5020.9  388.30  5021.1  387.80  5024.6  387.80
  5024.9  388.30  5051.8  388.68  5100.6  390.28  5166.1  390.20  5429.1  394.01
#Mann=4,-1,0
  4342.1    0.12       0  4574.8    0.05       0  5020.9    0.04       0
  5024.9    0.05       0
Bank Sta=5020.9,5024.9
Exp/Cntr=0.3,0.1

Type RM Length L Ch R = 1,1683,285,285,285
BEGIN DESCRIPTION:
Lacy 191 299
END DESCRIPTION:
XS GIS Cut Line= 3
      2670570.40      6813348.53      2671024.51      6813662.27
      2671300.33      6813959.16
#Sta/Elev= 30
  4443.2  393.87  4492.0  392.72  4506.9  393.18  4513.0  392.35  4521.8  392.85
  4614.4  389.74  4671.2  390.40  4686.0  389.17  4693.1  389.54  4736.7  387.57
  4766.0  387.48  4772.6  386.22  4778.6  386.76  4787.4  385.65  4793.5  386.18
  4800.3  385.62  4800.6  385.12  4804.1  385.12  4804.3  385.62  4829.3  385.98
  4838.1  386.83  4880.0  386.32  4894.9  387.11  4960.5  387.54  5016.6  387.20
  5045.0  387.98  5108.5  387.77  5186.2  390.14  5306.9  390.68  5400.4  392.21
#Mann=3,-1,0
  4443.2    0.05       0  4800.3    0.04       0  4804.3    0.05       0
Bank Sta=4800.3,4804.3
Exp/Cntr=0.3,0.1

Type RM Length L Ch R = 1,1398,94,94,94
BEGIN DESCRIPTION:
Lacy 191 297
END DESCRIPTION:
XS GIS Cut Line= 3
      2670474.28      6813408.80      2670795.79      6813735.25
      2671262.22      6814030.30
#Sta/Elev= 30
  4538.8  394.18  4626.4  393.08  4690.1  391.11  4753.7  391.64  4782.0  390.42
  4796.1  389.23  4824.4  385.77  4879.0  385.43  4879.2  384.93  4882.7  384.93
  4883.0  385.43  4965.8  386.21  5009.1  385.51  5022.0  386.54  5037.2  385.99
  5073.7  386.17  5089.0  387.28  5139.2  386.91  5152.5  385.60  5161.9  387.95
  5167.8  388.14  5174.7  387.24  5198.3  387.12  5246.6  387.81  5298.3  389.45
  5328.6  389.08  5392.4  389.58  5480.6  391.41  5517.1  391.61  5548.9  392.73
#Mann=3,-1,0
  4538.8    0.05       0  4879.0    0.03       0  4883.0    0.05       0
Bank Sta=4879,4883
Exp/Cntr=0.3,0.1

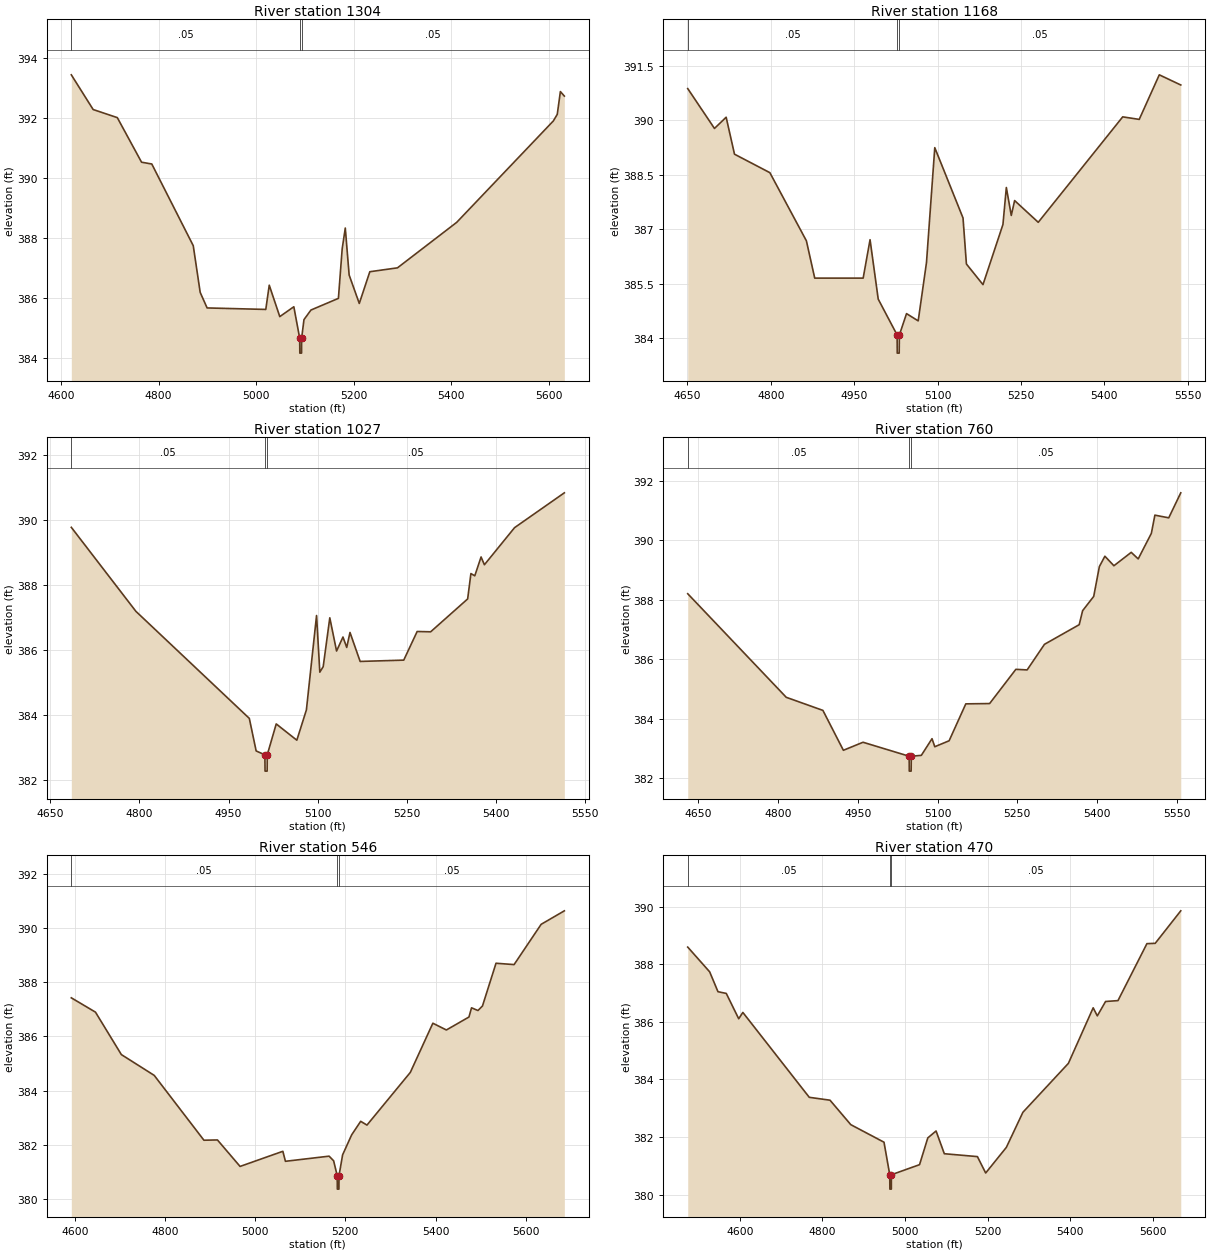
Type RM Length L Ch R = 1,1304,136,136,136
BEGIN DESCRIPTION:
Lacy 191 306
END DESCRIPTION:
XS GIS Cut Line= 3
      2670436.61      6813517.04      2670719.89      6813777.76
      2671205.31      6814172.72
#Sta/Elev= 30
  4621.0  393.45  4665.8  392.29  4715.3  392.02  4765.0  390.53  4786.0  390.47
  4871.0  387.74  4885.2  386.18  4899.4  385.66  5019.7  385.61  5026.8  386.42
  5048.4  385.37  5077.2  385.70  5089.2  384.65  5089.5  384.15  5093.0  384.15
  5093.2  384.65  5098.0  385.27  5112.3  385.59  5168.6  385.98  5176.3  387.63
  5182.7  388.33  5190.6  386.76  5211.4  385.81  5233.0  386.87  5289.7  387.00
  5411.1  388.52  5609.3  391.91  5617.3  392.13  5623.7  392.89  5631.8  392.74
#Mann=3,-1,0
  4621.0    0.05       0  5089.2    0.03       0  5093.2    0.05       0
Bank Sta=5089.2,5093.2
Exp/Cntr=0.3,0.1

Type RM Length L Ch R = 1,1168,141,141,141
BEGIN DESCRIPTION:
Lacy 191 305
END DESCRIPTION:
XS GIS Cut Line= 3
      2670413.07      6813687.98      2670703.91      6813881.61
      2671147.73      6814184.46
#Sta/Elev= 30
  4650.6  390.88  4698.7  389.78  4719.7  390.09  4734.7  389.07  4798.3  388.56
  4864.0  386.68  4879.0  385.65  4966.1  385.65  4978.5  386.71  4993.2  385.07
  5027.2  384.08  5027.4  383.58  5030.9  383.58  5031.2  384.08  5044.1  384.67
  5065.1  384.47  5080.0  386.08  5094.9  389.25  5145.7  387.31  5151.8  386.04
  5181.6  385.47  5217.5  387.13  5223.6  388.15  5232.5  387.38  5238.5  387.79
  5281.0  387.19  5432.9  390.10  5462.6  390.03  5498.7  391.26  5537.3  390.98
#Mann=3,-1,0
  4650.6    0.05       0  5027.2    0.03       0  5031.2    0.05       0
Bank Sta=5027.2,5031.2
Exp/Cntr=0.3,0.1

Type RM Length L Ch R = 1,1027,267,267,267
BEGIN DESCRIPTION:
Lacy 191 304
END DESCRIPTION:
XS GIS Cut Line= 3
      2670422.35      6813771.35      2670637.44      6814001.08
      2671101.84      6814224.61
#Sta/Elev= 30
  4685.3  389.77  4794.0  387.19  4985.0  383.90  4996.5  382.90  5011.2  382.78
  5011.5  382.28  5015.0  382.28  5015.2  382.78  5030.3  383.73  5065.0  383.23
  5081.1  384.16  5098.2  387.06  5103.7  385.32  5109.4  385.49  5120.5  386.99
  5131.9  385.97  5142.7  386.40  5149.0  386.08  5154.5  386.54  5171.6  385.65
  5245.0  385.69  5267.6  386.57  5290.3  386.56  5352.6  387.57  5358.1  388.35
  5364.6  388.28  5375.2  388.86  5380.8  388.62  5431.6  389.76  5515.4  390.83
#Mann=3,-1,0
  4685.3    0.05       0  5011.2    0.03       0  5015.2    0.05       0
Bank Sta=5011.2,5015.2
Exp/Cntr=0.3,0.1

Type RM Length L Ch R = 1,760,214,214,214
BEGIN DESCRIPTION:
Lacy 191 303
END DESCRIPTION:
XS GIS Cut Line= 3
      2670431.31      6813865.01      2670569.58      6814208.31
      2671102.50      6814372.69
#Sta/Elev= 30
  4629.9  388.20  4815.3  384.72  4884.3  384.28  4922.8  382.94  4959.8  383.21
  5046.6  382.74  5046.8  382.24  5050.3  382.24  5050.6  382.74  5069.5  382.77
  5089.6  383.33  5094.8  383.06  5121.8  383.26  5153.2  384.50  5198.0  384.51
  5247.4  385.66  5268.6  385.64  5301.2  386.50  5366.6  387.16  5373.0  387.63
  5393.9  388.11  5404.5  389.11  5414.9  389.46  5431.9  389.14  5464.5  389.59
  5477.6  389.37  5502.4  390.23  5509.0  390.84  5535.1  390.75  5557.7  391.59
#Mann=3,-1,0
  4629.9    0.05       0  5046.6    0.03       0  5050.6    0.05       0
Bank Sta=5046.6,5050.6
Exp/Cntr=0.3,0.1

Type RM Length L Ch R = 1,546,76,76,76
BEGIN DESCRIPTION:
Lacy 191 296
END DESCRIPTION:
XS GIS Cut Line= 4
      2670403.07      6813947.55      2670431.72      6814355.98
      2670492.76      6814388.47      2671107.41      6814414.77
#Sta/Elev= 30
  4592.0  387.43  4645.6  386.90  4703.0  385.33  4775.9  384.56  4886.2  382.16
  4916.2  382.17  4966.4  381.19  5061.3  381.75  5067.0  381.38  5163.9  381.57
  5173.9  381.40  5181.9  380.85  5182.2  380.35  5185.7  380.35  5185.9  380.85
  5193.9  381.62  5214.0  382.36  5234.0  382.86  5247.9  382.72  5344.1  384.67
  5394.1  386.49  5424.1  386.24  5474.2  386.72  5479.9  387.06  5494.2  386.96
  5504.2  387.13  5534.2  388.71  5574.3  388.66  5634.3  390.15  5685.8  390.65
#Mann=3,-1,0
  4592.0    0.05       0  5181.9    0.03       0  5185.9    0.05       0
Bank Sta=5181.9,5185.9
Exp/Cntr=0.3,0.1

Type RM Length L Ch R = 1,470,135,135,135
BEGIN DESCRIPTION:
Lacy 191 3431
END DESCRIPTION:
XS GIS Cut Line= 3
      2670291.45      6813928.18      2670338.20      6814409.12
      2671047.83      6814437.37
#Sta/Elev= 30
  4474.2  388.60  4527.3  387.74  4547.4  387.05  4567.5  386.99  4597.6  386.11
  4607.6  386.33  4768.4  383.38  4818.6  383.28  4868.9  382.43  4949.3  381.82
  4963.2  380.69  4963.5  380.19  4967.0  380.19  4967.2  380.69  5035.3  381.04
  5055.3  381.97  5075.3  382.21  5095.3  381.42  5175.4  381.32  5195.4  380.75
  5245.4  381.64  5285.5  382.86  5395.6  384.56  5455.6  386.49  5465.6  386.21
  5485.6  386.71  5515.6  386.74  5585.7  388.72  5605.7  388.73  5667.6  389.86
#Mann=3,-1,0
  4474.2    0.05       0  4963.2    0.03       0  4967.2    0.05       0
Bank Sta=4963.2,4967.2
Exp/Cntr=0.3,0.1

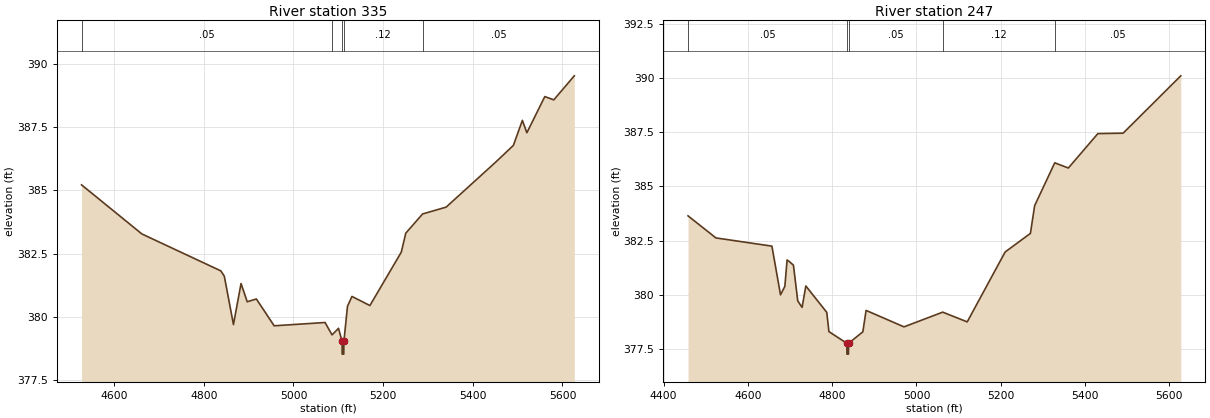
Type RM Length L Ch R = 1,335,88,88,88
BEGIN DESCRIPTION:
Lacy 191 3430
END DESCRIPTION:
XS GIS Cut Line= 3
      2670248.40      6814119.23      2670336.51      6814543.74
      2671001.83      6814556.71
#Sta/Elev= 30
  4527.4  385.22  4662.0  383.28  4838.1  381.82  4845.8  381.61  4866.2  379.70
  4883.1  381.32  4896.9  380.60  4917.3  380.71  4957.0  379.65  5070.5  379.78
  5086.1  379.29  5100.5  379.55  5108.5  379.03  5108.7  378.53  5112.2  378.53
  5112.5  379.03  5120.5  380.42  5130.5  380.81  5170.5  380.45  5240.5  382.56
  5250.5  383.31  5288.0  384.07  5340.5  384.34  5450.5  386.11  5490.5  386.78
  5510.6  387.77  5520.6  387.28  5560.6  388.71  5580.6  388.58  5626.4  389.53
#Mann=5,-1,0
  4527.4    0.05       0  5086.1    0.12       0  5108.5    0.03       0
  5112.5    0.12       0  5288.0    0.05       0
Bank Sta=5108.5,5112.5
Exp/Cntr=0.3,0.1

Type RM Length L Ch R = 1,247,0,0,0
BEGIN DESCRIPTION:
Lacy 191 3435
END DESCRIPTION:
XS GIS Cut Line= 3
      2670162.17      6814226.24      2670248.25      6814632.08
      2671002.77      6814636.98
#Sta/Elev= 30
  4457.8  383.64  4524.0  382.62  4656.9  382.24  4677.3  379.99  4687.6  380.38
  4692.9  381.60  4698.0  381.53  4708.0  381.36  4718.2  379.71  4728.5  379.41
  4737.4  380.40  4787.1  379.18  4792.2  378.29  4834.8  377.75  4835.0  377.25
  4838.5  377.25  4838.8  377.75  4872.7  378.28  4880.4  379.27  4970.4  378.51
  5062.2  379.19  5120.4  378.74  5210.4  381.97  5270.4  382.83  5280.4  384.11
  5328.1  386.09  5360.4  385.85  5430.4  387.44  5490.4  387.46  5627.2  390.11
#Mann=5,-1,0
  4457.8    0.05       0  4834.8    0.03       0  4838.8    0.05       0
  5062.2    0.12       0  5328.1    0.05       0
Bank Sta=4834.8,4838.8
Exp/Cntr=0.3,0.1

Chan Stop Cuts=-1