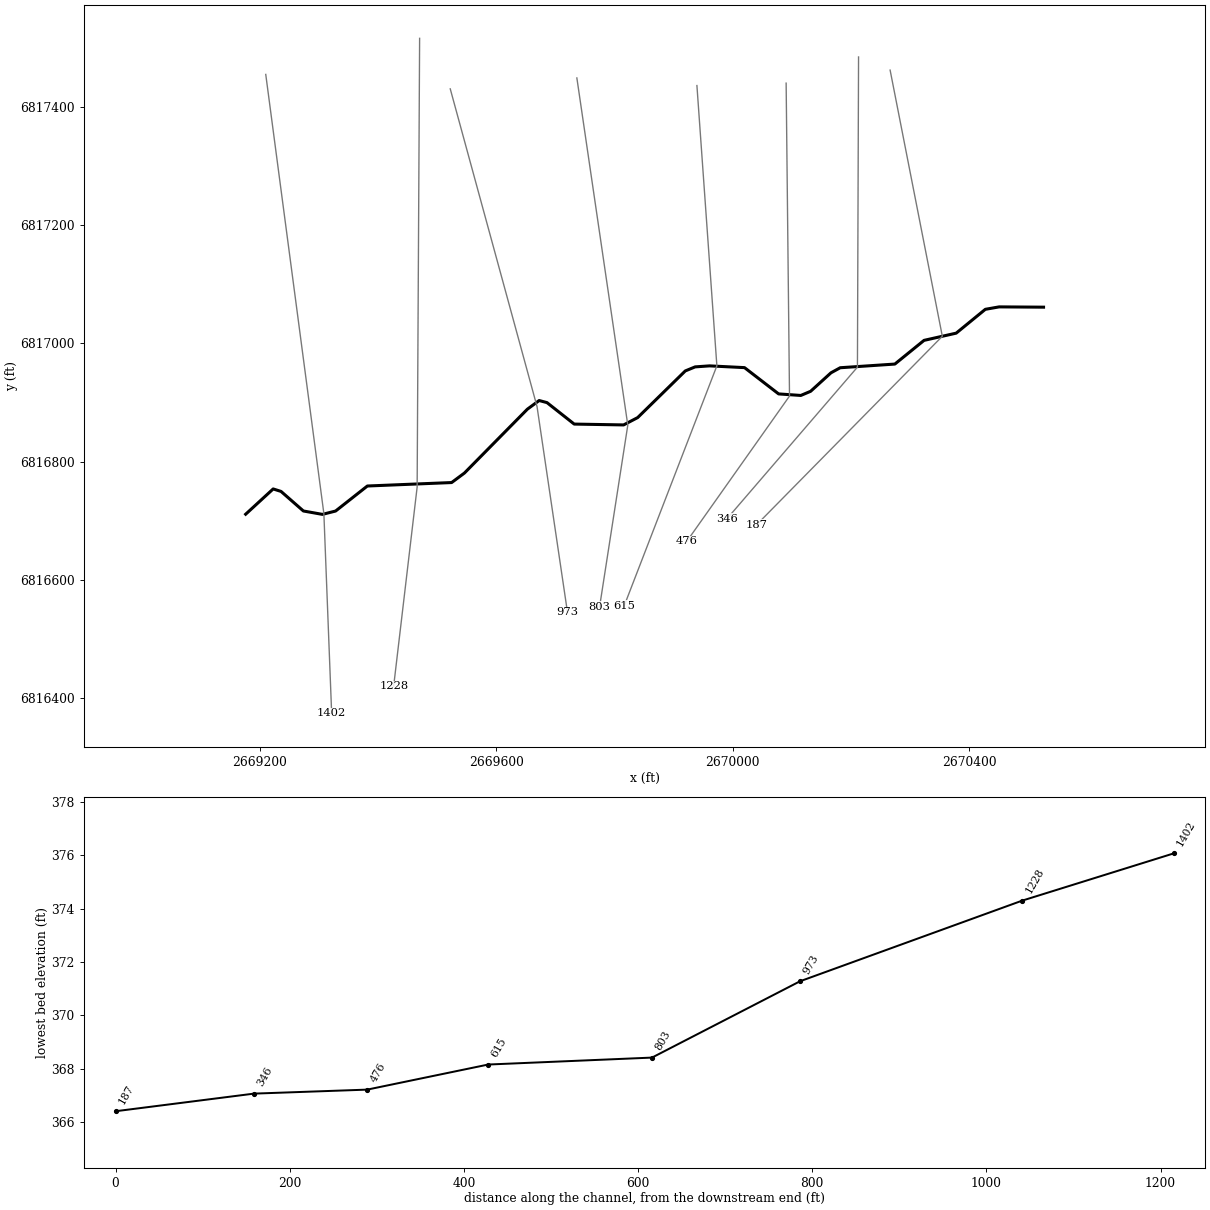
--- Lacy 192.prj (project) ---

Proj Title=Lacy 192 Base Level Engineering
Current Plan=p01
Default Exp/Contr=0.3,0.1
English Units
Geom File=g01
Flow File=f01
Plan File=p01
BEGIN DESCRIPTION:
Lacy 192
END DESCRIPTION:

--- Lacy 192.p01 (plan) ---

Plan Title=Multiple Run
Short Identifier=Multiple
Geom File=g01
Flow File=f01
Subcritical Flow
K Sum by GR= 0
Std Step Tol= 0.01
Critical Tol= 0.01
Num of Std Step Trials= 20
Max Error Tol= 0.3
Flow Tol Ratio= 0.001
Split Flow NTrial= 30
Split Flow Tol= 0.02
Split Flow Ratio= 0.02
Log Output Level= 0
Friction Slope Method= 1
Unsteady Friction Slope Method= 2
Unsteady Bridges Friction Slope Method= 1
Parabolic Critical Depth
Global Vel Dist=  1 , 1 , 1
Global Log Level= 0
CheckData=True
Encroach Param= -1, 0, 0, 0
BEGIN DESCRIPTION:
Multiple Run
END DESCRIPTION:

--- Lacy 192.f01 (steady flow) ---

Flow Title=Multiple
Number of Profiles=7
Profile Names=10-year,25-year,50-year,1pct_min,100-year,1pct_plu,500-year
River Rch & RM= Lacy 192,Reach-1,1402
     289     371     433     252     502    1002     674
Boundary for River Rch & Prof#=Lacy 192,Reach-1,1
Up Type=0
Dn Type=3
Dn Slope=0.005
Boundary for River Rch & Prof#=Lacy 192,Reach-1,2
Up Type=0
Dn Type=3
Dn Slope=0.005
Boundary for River Rch & Prof#=Lacy 192,Reach-1,3
Up Type=0
Dn Type=3
Dn Slope=0.005
Boundary for River Rch & Prof#=Lacy 192,Reach-1,4
Up Type=0
Dn Type=3
Dn Slope=0.005
Boundary for River Rch & Prof#=Lacy 192,Reach-1,5
Up Type=0
Dn Type=3
Dn Slope=0.005
Boundary for River Rch & Prof#=Lacy 192,Reach-1,6
Up Type=0
Dn Type=3
Dn Slope=0.005
Boundary for River Rch & Prof#=Lacy 192,Reach-1,7
Up Type=0
Dn Type=3
Dn Slope=0.005

--- Lacy 192.g01 (geometry) ---

Geom Title=Existing Conditions

River Reach=Lacy 192,Reach-1
Reach XY= 30
      2669176.00      6816711.00      2669222.56      6816753.73
      2669235.83      6816749.56      2669273.68      6816716.48
      2669305.80      6816710.75      2669328.17      6816716.39
      2669381.93      6816758.70      2669524.53      6816764.54
      2669546.16      6816780.61      2669652.64      6816888.55
      2669672.58      6816903.20      2669685.85      6816899.66
      2669731.89      6816863.37      2669815.51      6816861.95
      2669839.29      6816874.37      2669919.84      6816953.22
      2669936.48      6816960.06      2669960.91      6816961.77
      2670020.03      6816958.81      2670077.73      6816914.38
      2670115.31      6816911.77      2670131.92      6816918.81
      2670166.35      6816950.05      2670181.97      6816958.62
      2670274.42      6816964.83      2670323.82      6817004.89
      2670378.19      6817017.09      2670427.50      6817057.37
      2670450.80      6817061.48      2670526.00      6817061.00

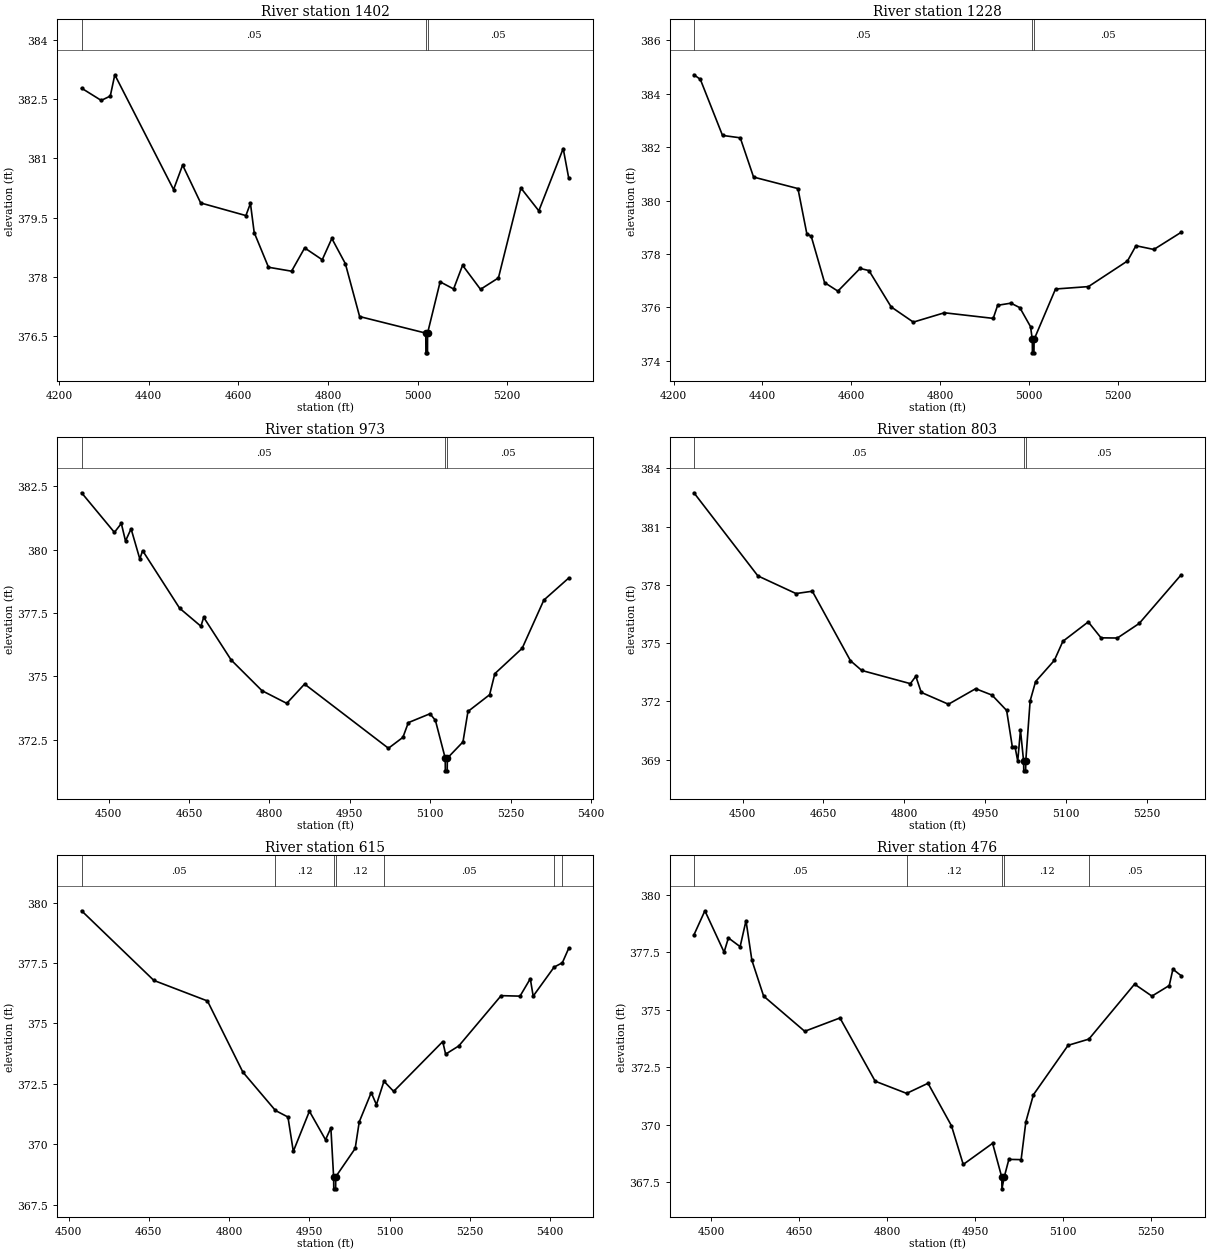
Type RM Length L Ch R = 1,1402,174,174,174
BEGIN DESCRIPTION:
Lacy 192 278
END DESCRIPTION:
XS GIS Cut Line= 3
      2669210.00      6817454.42      2669308.35      6816711.93
      2669321.50      6816374.36
#Sta/Elev= 30
  4250.5  382.78  4294.3  382.47  4314.5  382.58  4324.6  383.12  4455.7  380.21
  4475.9  380.83  4516.2  379.87  4617.1  379.55  4627.2  379.86  4635.6  379.12
  4667.5  378.24  4719.0  378.14  4748.2  378.73  4787.4  378.43  4808.8  378.97
  4839.0  378.33  4870.8  376.99  5018.4  376.57  5018.7  376.07  5022.2  376.07
  5022.4  376.57  5050.4  377.87  5080.5  377.69  5100.5  378.29  5140.5  377.68
  5180.5  377.97  5230.6  380.25  5270.6  379.67  5325.0  381.25  5337.3  380.50
#Mann=3,-1,0
  4250.5    0.05       0  5018.4    0.03       0  5022.4    0.05       0
Bank Sta=5018.4,5022.4
Exp/Cntr=0.3,0.1

Type RM Length L Ch R = 1,1228,255,255,255
BEGIN DESCRIPTION:
Lacy 192 279
END DESCRIPTION:
XS GIS Cut Line= 3
      2669470.33      6817515.43      2669466.15      6816756.90
      2669426.38      6816420.08
#Sta/Elev= 30
  4245.5  384.71  4259.9  384.54  4309.9  382.44  4349.9  382.35  4379.9  380.88
  4479.9  380.45  4499.9  378.76  4509.9  378.66  4539.9  376.93  4569.9  376.61
  4619.9  377.46  4639.9  377.38  4689.9  376.02  4739.9  375.45  4809.9  375.80
  4919.9  375.59  4929.9  376.08  4959.9  376.16  4979.9  375.99  5004.0  375.28
  5008.0  374.80  5008.2  374.30  5011.7  374.30  5012.0  374.80  5060.3  376.69
  5134.5  376.78  5222.5  377.74  5241.6  378.31  5281.9  378.17  5343.2  378.81
#Mann=3,-1,0
  4245.5    0.05       0  5008.0    0.04       0  5012.0    0.05       0
Bank Sta=5008,5012
Exp/Cntr=0.3,0.1

Type RM Length L Ch R = 1,973,170,170,170
BEGIN DESCRIPTION:
Lacy 192 280
END DESCRIPTION:
XS GIS Cut Line= 3
      2669522.16      6817430.01      2669669.01      6816892.89
      2669720.51      6816545.12
#Sta/Elev= 30
  4449.8  382.24  4511.0  380.68  4523.9  381.03  4531.7  380.34  4542.1  380.82
  4558.4  379.63  4563.6  379.96  4632.6  377.69  4672.3  376.98  4677.5  377.33
  4728.7  375.65  4786.2  374.44  4832.4  373.94  4865.6  374.70  5022.0  372.17
  5049.0  372.60  5059.1  373.18  5099.5  373.53  5109.6  373.27  5127.9  371.78
  5128.1  371.28  5131.6  371.28  5131.9  371.78  5161.0  372.42  5170.3  373.62
  5210.7  374.28  5220.4  375.11  5271.4  376.11  5311.8  378.01  5358.2  378.88
#Mann=3,-1,0
  4449.8    0.05       0  5127.9    0.04       0  5131.9    0.05       0
Bank Sta=5127.9,5131.9
Exp/Cntr=0.3,0.1

Type RM Length L Ch R = 1,803,188,188,188
BEGIN DESCRIPTION:
Lacy 192 281
END DESCRIPTION:
XS GIS Cut Line= 3
      2669736.38      6817448.49      2669822.57      6816861.58
      2669774.79      6816554.17
#Sta/Elev= 30
  4409.5  382.74  4528.2  378.46  4599.0  377.55  4629.3  377.67  4700.1  374.09
  4721.0  373.59  4811.3  372.91  4821.4  373.29  4831.5  372.46  4882.0  371.85
  4932.5  372.65  4962.9  372.32  4990.0  371.53  5000.5  369.67  5005.5  369.67
  5010.6  368.92  5015.7  370.52  5021.5  368.92  5021.8  368.42  5025.3  368.42
  5025.5  368.92  5033.6  372.02  5043.8  373.02  5078.6  374.11  5094.4  375.09
  5141.5  376.09  5165.2  375.27  5195.6  375.26  5236.1  376.01  5313.8  378.51
#Mann=3,-1,0
  4409.5    0.05       0  5021.5    0.04       0  5025.5    0.05       0
Bank Sta=5021.5,5025.5
Exp/Cntr=0.3,0.1

Type RM Length L Ch R = 1,615,139,139,139
BEGIN DESCRIPTION:
Lacy 192 282
END DESCRIPTION:
XS GIS Cut Line= 3
      2669939.51      6817435.61      2669973.28      6816961.81
      2669816.36      6816555.89
#Sta/Elev= 30
  4524.3  379.66  4659.3  376.78  4759.5  375.93  4825.6  372.99  4886.5  371.40
  4909.9  371.13  4919.9  369.71  4950.0  371.37  4980.1  370.19  4990.1  370.68
  4995.2  368.66  4995.5  368.16  4999.0  368.16  4999.2  368.66  5035.5  369.83
  5043.1  370.93  5065.5  372.14  5075.2  371.64  5089.3  372.61  5107.4  372.19
  5199.1  374.25  5204.5  373.73  5229.1  374.07  5308.2  376.15  5343.5  376.13
  5362.7  376.85  5368.1  376.13  5407.2  377.33  5422.6  377.51  5434.5  378.11
#Mann=7,-1,0
  4524.3    0.05       0  4886.5    0.12       0  4995.2    0.07       0
  4999.2    0.12       0  5089.3    0.05       0  5407.2    0.12       0
  5422.6    0.05       0
Bank Sta=4995.2,4999.2
Exp/Cntr=0.3,0.1

Type RM Length L Ch R = 1,476,130,130,130
BEGIN DESCRIPTION:
Lacy 192 285
END DESCRIPTION:
XS GIS Cut Line= 3
      2670090.47      6817439.69      2670096.18      6816910.72
      2669922.49      6816665.25
#Sta/Elev= 30
  4471.0  378.26  4489.7  379.31  4522.4  377.51  4529.7  378.13  4549.7  377.75
  4559.7  378.88  4569.7  377.16  4589.7  375.60  4659.7  374.07  4719.7  374.65
  4779.7  371.90  4833.3  371.37  4869.7  371.81  4909.7  369.96  4929.7  368.28
  4979.7  369.20  4995.4  367.72  4995.6  367.22  4999.4  367.72  5007.4  368.50
  5028.3  368.49  5036.4  370.14  5049.2  371.31  5108.3  373.46  5143.7  373.73
  5221.5  376.12  5251.1  375.60  5280.6  376.06  5286.8  376.77  5300.7  376.49
#Mann=5,-1,0
  4471.0    0.05       0  4833.3    0.12       0  4995.4    0.07       0
  4999.4    0.12       0  5143.7    0.05       0
Bank Sta=4995.4,4999.4
Exp/Cntr=0.3,0.1

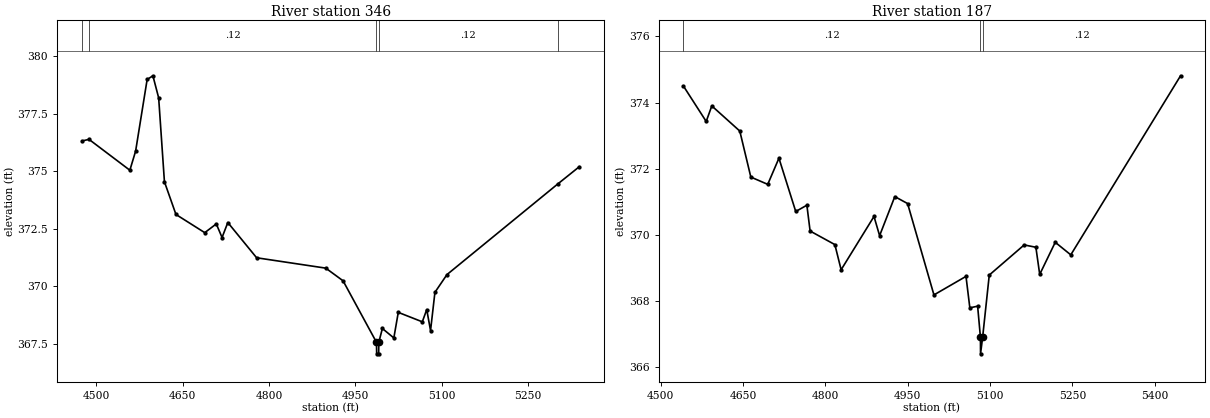
Type RM Length L Ch R = 1,346,159,159,159
BEGIN DESCRIPTION:
Lacy 192 284
END DESCRIPTION:
XS GIS Cut Line= 3
      2670212.99      6817483.94      2670211.10      6816959.65
      2669990.27      6816703.24
#Sta/Elev= 30
  4475.7  376.31  4487.7  376.38  4558.6  375.04  4568.6  375.87  4588.6  378.98
  4598.6  379.14  4608.6  378.18  4618.6  374.54  4638.6  373.12  4688.6  372.33
  4708.6  372.71  4718.6  372.12  4728.6  372.77  4778.6  371.24  4898.6  370.79
  4928.6  370.24  4986.6  367.57  4986.9  367.07  4990.4  367.07  4990.6  367.57
  4996.8  368.17  5016.7  367.76  5024.4  368.87  5066.1  368.46  5073.8  368.99
  5080.4  368.08  5088.0  369.74  5108.9  370.51  5301.0  374.44  5338.4  375.19
#Mann=5,-1,0
  4475.7    0.05       0  4487.7    0.12       0  4986.6    0.07       0
  4990.6    0.12       0  5301.0    0.05       0
Bank Sta=4986.6,4990.6
Exp/Cntr=0.3,0.1

Type RM Length L Ch R = 1,187,0,0,0
BEGIN DESCRIPTION:
Lacy 192 283
END DESCRIPTION:
XS GIS Cut Line= 3
      2670266.39      6817461.73      2670354.73      6817011.82
      2670040.74      6816693.39
#Sta/Elev= 30
  4541.5  374.50  4583.0  373.43  4593.2  373.90  4644.2  373.14  4664.3  371.75
  4695.1  371.53  4715.5  372.32  4746.1  370.71  4766.4  370.90  4772.3  370.12
  4817.4  369.71  4828.8  368.95  4888.7  370.56  4898.9  369.98  4926.6  371.16
  4949.9  370.95  4997.9  368.19  5056.3  368.75  5063.3  367.80  5077.5  367.85
  5082.6  366.91  5082.8  366.41  5086.6  366.91  5098.7  368.79  5162.3  369.70
  5183.6  369.63  5190.6  368.81  5218.9  369.78  5247.2  369.40  5447.2  374.81
#Mann=3,-1,0
  4541.5    0.12       0  5082.6    0.07       0  5086.6    0.12       0
Bank Sta=5082.6,5086.6
Exp/Cntr=0.3,0.1

Chan Stop Cuts=-1