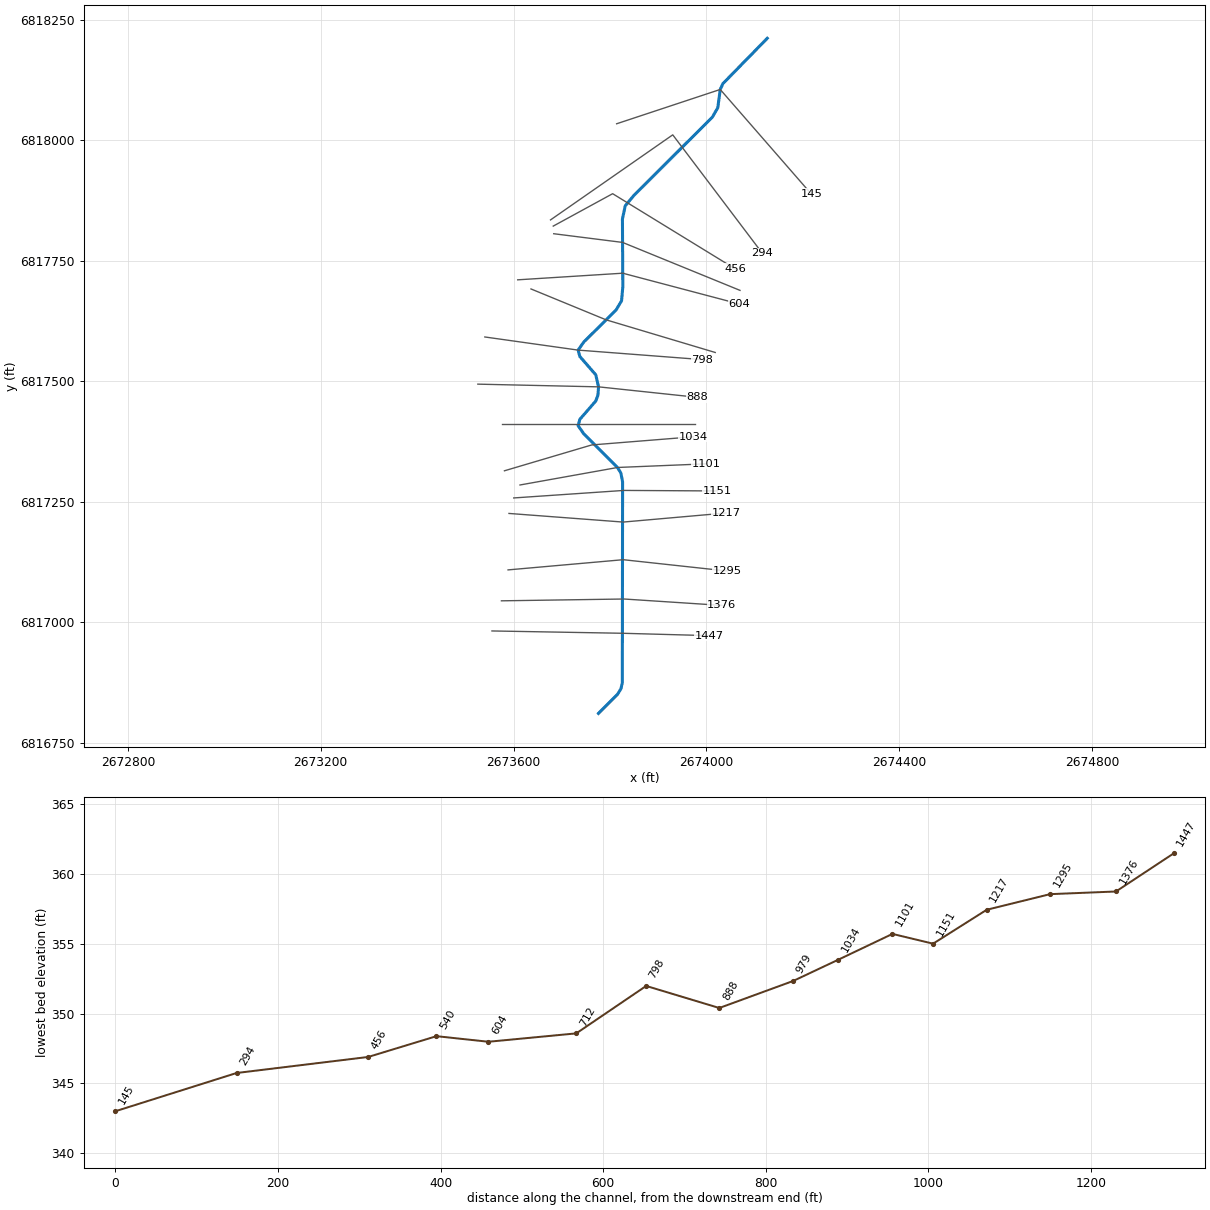
--- Lacy 193.prj (project) ---

Proj Title=Lacy 193 Base Level Engineering
Current Plan=p01
Default Exp/Contr=0.3,0.1
English Units
Geom File=g01
Flow File=f01
Plan File=p01
BEGIN DESCRIPTION:
Lacy 193
END DESCRIPTION:

--- Lacy 193.p01 (plan) ---

Plan Title=Multiple Run
Short Identifier=Multiple
Geom File=g01
Flow File=f01
Subcritical Flow
K Sum by GR= 0
Std Step Tol= 0.01
Critical Tol= 0.01
Num of Std Step Trials= 20
Max Error Tol= 0.3
Flow Tol Ratio= 0.001
Split Flow NTrial= 30
Split Flow Tol= 0.02
Split Flow Ratio= 0.02
Log Output Level= 0
Friction Slope Method= 1
Unsteady Friction Slope Method= 2
Unsteady Bridges Friction Slope Method= 1
Parabolic Critical Depth
Global Vel Dist=  1 , 1 , 1
Global Log Level= 0
CheckData=True
Encroach Param= -1, 0, 0, 0
BEGIN DESCRIPTION:
Multiple Run
END DESCRIPTION:

--- Lacy 193.f01 (steady flow) ---

Flow Title=Multiple
Number of Profiles=7
Profile Names=10-year,25-year,50-year,1pct_min,100-year,1pct_plu,500-year
River Rch & RM= Lacy 193,Reach-1,1447
     152     186     211     120     239     477     305
Boundary for River Rch & Prof#=Lacy 193,Reach-1,1
Up Type=0
Dn Type=3
Dn Slope=0.005
Boundary for River Rch & Prof#=Lacy 193,Reach-1,2
Up Type=0
Dn Type=3
Dn Slope=0.005
Boundary for River Rch & Prof#=Lacy 193,Reach-1,3
Up Type=0
Dn Type=3
Dn Slope=0.005
Boundary for River Rch & Prof#=Lacy 193,Reach-1,4
Up Type=0
Dn Type=3
Dn Slope=0.005
Boundary for River Rch & Prof#=Lacy 193,Reach-1,5
Up Type=0
Dn Type=3
Dn Slope=0.005
Boundary for River Rch & Prof#=Lacy 193,Reach-1,6
Up Type=0
Dn Type=3
Dn Slope=0.005
Boundary for River Rch & Prof#=Lacy 193,Reach-1,7
Up Type=0
Dn Type=3
Dn Slope=0.005

--- Lacy 193.g01 (geometry) ---

Geom Title=Existing Conditions

River Reach=Lacy 193,Reach-1
Reach XY= 28
      2673776.00      6816811.00      2673815.95      6816851.02
      2673822.71      6816862.36      2673825.50      6816874.84
      2673826.03      6817291.02      2673822.44      6817309.54
      2673815.48      6817320.80      2673745.34      6817390.99
      2673733.83      6817407.60      2673737.39      6817420.87
      2673770.31      6817458.71      2673774.85      6817470.80
      2673776.19      6817488.20      2673770.31      6817513.29
      2673737.39      6817551.13      2673733.83      6817564.40
      2673745.34      6817581.01      2673812.57      6817647.68
      2673823.92      6817666.85      2673826.48      6817695.80
      2673825.71      6817836.12      2673831.46      6817863.45
      2673848.86      6817884.53      2674012.37      6818047.79
      2674023.48      6818067.04      2674028.52      6818104.96
      2674034.11      6818117.07      2674126.00      6818211.00

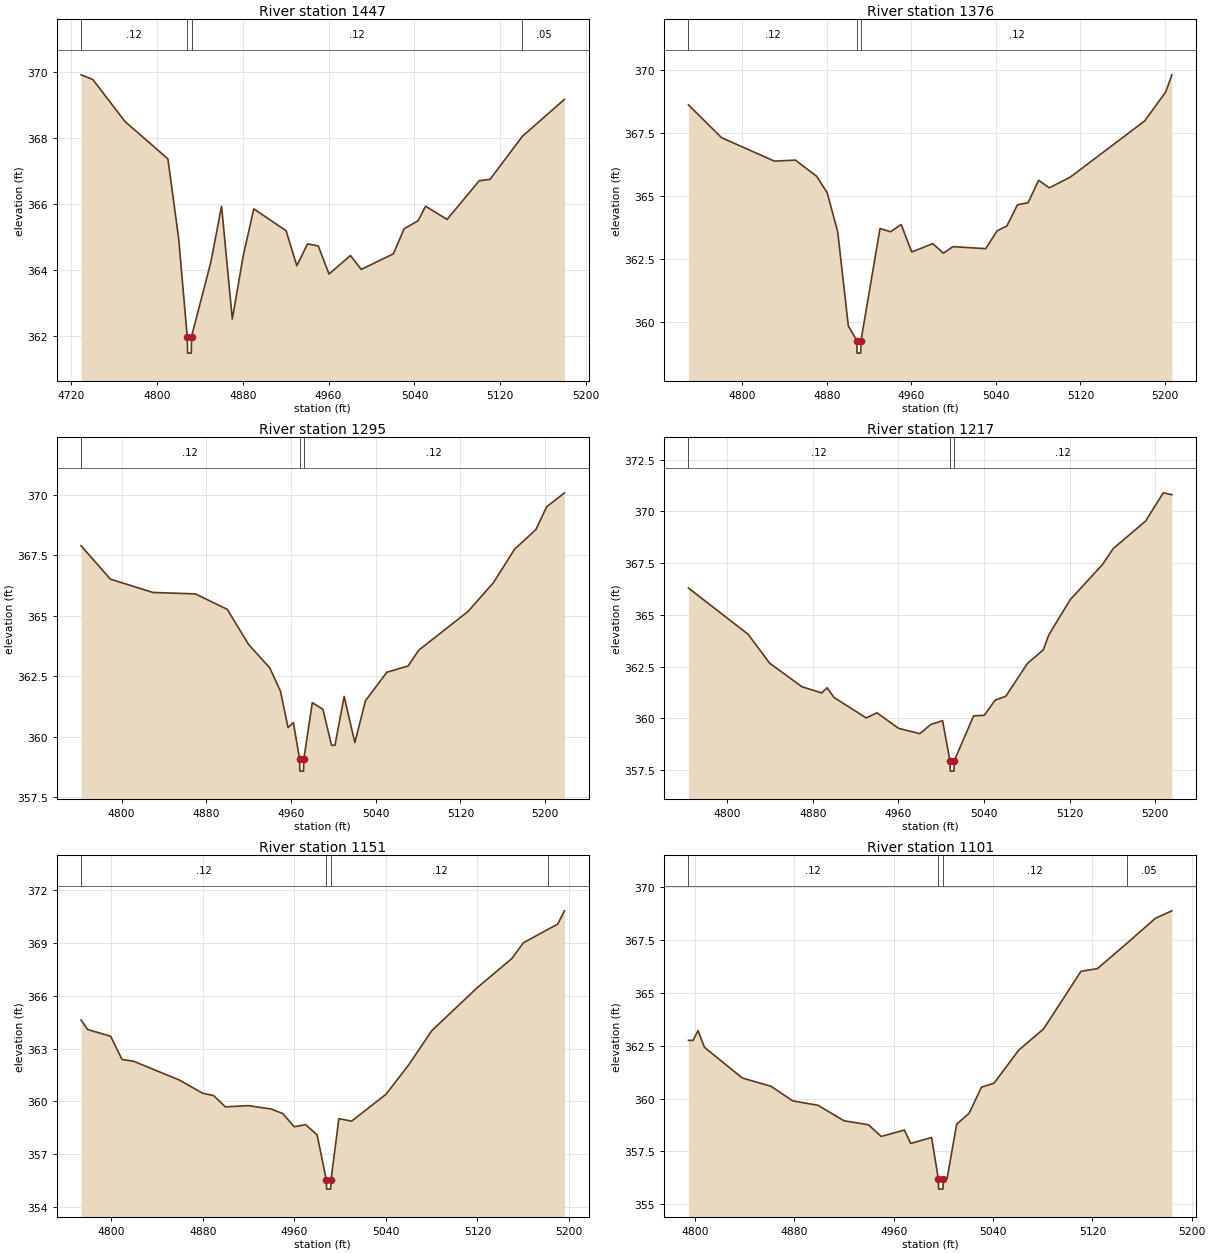
Type RM Length L Ch R = 1,1447,71,71,71
BEGIN DESCRIPTION:
Lacy 193 250
END DESCRIPTION:
XS GIS Cut Line= 3
      2673555.08      6816981.94      2673824.64      6816977.16
      2674005.37      6816972.22
#Sta/Elev= 30
  4729.4  369.90  4740.3  369.76  4770.3  368.49  4810.3  367.36  4820.3  364.96
  4828.3  361.99  4828.6  361.49  4832.1  361.49  4832.3  361.99  4850.3  364.24
  4860.3  365.93  4870.3  362.52  4880.3  364.40  4890.3  365.85  4920.4  365.19
  4930.4  364.13  4940.4  364.79  4950.4  364.73  4960.4  363.88  4980.4  364.44
  4990.4  364.02  5020.4  364.49  5030.4  365.25  5043.4  365.49  5050.4  365.93
  5070.4  365.53  5100.4  366.70  5110.4  366.74  5140.5  368.04  5179.8  369.16
#Mann=4,-1,0
  4729.4    0.12       0  4828.3    0.07       0  4832.3    0.12       0
  5140.5    0.05       0
Bank Sta=4828.3,4832.3
Exp/Cntr=0.3,0.1

Type RM Length L Ch R = 1,1376,81,81,81
BEGIN DESCRIPTION:
Lacy 193 252
END DESCRIPTION:
XS GIS Cut Line= 3
      2673574.75      6817044.43      2673829.12      6817048.19
      2674031.79      6817034.94
#Sta/Elev= 30
  4749.0  368.60  4780.3  367.30  4830.3  366.37  4850.2  366.41  4870.3  365.77
  4880.3  365.12  4890.3  363.56  4900.3  359.84  4908.3  359.26  4908.5  358.76
  4912.0  358.76  4912.3  359.26  4930.3  363.70  4940.3  363.57  4950.3  363.86
  4960.3  362.77  4980.3  363.10  4990.3  362.72  4999.3  362.98  5030.3  362.90
  5041.2  363.61  5050.4  363.80  5060.4  364.64  5070.4  364.72  5080.4  365.61
  5090.5  365.31  5110.5  365.74  5180.7  367.96  5200.7  369.11  5206.5  369.79
#Mann=3,-1,0
  4749.0    0.12       0  4908.3    0.07       0  4912.3    0.12       0
Bank Sta=4908.3,4912.3
Exp/Cntr=0.3,0.1

Type RM Length L Ch R = 1,1295,78,78,78
BEGIN DESCRIPTION:
Lacy 193 251
END DESCRIPTION:
XS GIS Cut Line= 3
      2673588.46      6817108.57      2673827.34      6817129.72
      2674042.85      6817106.27
#Sta/Elev= 30
  4761.7  367.89  4789.4  366.51  4829.5  365.96  4869.7  365.90  4899.8  365.26
  4919.9  363.81  4939.9  362.84  4950.0  361.88  4957.2  360.37  4962.2  360.58
  4968.1  359.07  4968.3  358.57  4971.8  358.57  4972.1  359.07  4980.1  361.40
  4990.1  361.13  4998.3  359.64  5001.5  359.64  5010.2  361.66  5020.3  359.75
  5030.3  361.48  5050.5  362.66  5070.6  362.92  5080.6  363.57  5127.1  365.17
  5151.1  366.36  5171.2  367.75  5191.3  368.56  5201.4  369.50  5218.3  370.08
#Mann=3,-1,0
  4761.7    0.12       0  4968.1    0.07       0  4972.1    0.12       0
Bank Sta=4968.1,4972.1
Exp/Cntr=0.3,0.1

Type RM Length L Ch R = 1,1217,66,66,66
BEGIN DESCRIPTION:
Lacy 193 253
END DESCRIPTION:
XS GIS Cut Line= 3
      2673590.40      6817225.65      2673827.15      6817207.75
      2674040.49      6817226.57
#Sta/Elev= 30
  4763.8  366.30  4819.6  364.06  4839.6  362.67  4869.7  361.53  4888.3  361.23
  4893.3  361.48  4899.8  361.01  4929.9  360.02  4939.9  360.27  4960.0  359.52
  4980.0  359.26  4990.0  359.70  5001.2  359.89  5008.1  357.95  5008.4  357.45
  5011.9  357.45  5012.1  357.95  5030.2  360.12  5040.2  360.15  5050.3  360.88
  5060.3  361.07  5080.4  362.65  5095.3  363.31  5100.5  364.04  5120.5  365.74
  5150.7  367.44  5160.7  368.21  5190.8  369.53  5207.4  370.90  5215.4  370.81
#Mann=3,-1,0
  4763.8    0.12       0  5008.1    0.07       0  5012.1    0.12       0
Bank Sta=5008.1,5012.1
Exp/Cntr=0.3,0.1

Type RM Length L Ch R = 1,1151,50,50,50
BEGIN DESCRIPTION:
Lacy 193 256
END DESCRIPTION:
XS GIS Cut Line= 3
      2673600.24      6817257.78      2673828.73      6817273.39
      2674022.00      6817272.30
#Sta/Elev= 30
  4773.7  364.62  4779.5  364.08  4799.5  363.70  4809.5  362.38  4819.6  362.28
  4859.7  361.21  4879.7  360.47  4889.5  360.33  4899.8  359.69  4919.8  359.76
  4939.8  359.57  4949.9  359.31  4959.9  358.56  4969.9  358.68  4979.9  358.10
  4988.0  355.52  4988.2  355.02  4991.7  355.02  4992.0  355.52  4998.9  359.02
  5010.0  358.88  5040.0  360.40  5060.0  362.08  5080.0  364.01  5120.0  366.47
  5150.0  368.11  5160.0  369.00  5181.6  369.77  5190.0  370.06  5196.0  370.82
#Mann=4,-1,0
  4773.7    0.12       0  4988.0    0.07       0  4992.0    0.12       0
  5181.6    0.05       0
Bank Sta=4988,4992
Exp/Cntr=0.3,0.1

Type RM Length L Ch R = 1,1101,67,67,67
BEGIN DESCRIPTION:
Lacy 193 255
END DESCRIPTION:
XS GIS Cut Line= 3
      2673613.28      6817284.68      2673815.66      6817320.99
      2673999.19      6817328.53
#Sta/Elev= 30
  4794.7  362.75  4798.4  362.75  4802.4  363.21  4807.6  362.42  4838.1  360.97
  4861.2  360.58  4878.7  359.89  4899.1  359.68  4920.0  358.95  4939.7  358.76
  4949.9  358.21  4968.6  358.51  4973.7  357.88  4990.5  358.16  4995.9  356.22
  4996.2  355.72  4999.7  355.72  4999.9  356.22  5003.0  356.22  5010.7  358.79
  5020.7  359.30  5030.7  360.54  5040.7  360.72  5060.7  362.29  5080.7  363.29
  5110.8  366.01  5124.1  366.14  5147.5  367.32  5170.8  368.52  5184.0  368.87
#Mann=4,-1,0
  4794.7    0.12       0  4995.9    0.07       0  4999.9    0.12       0
  5147.5    0.05       0
Bank Sta=4995.9,4999.9
Exp/Cntr=0.3,0.1

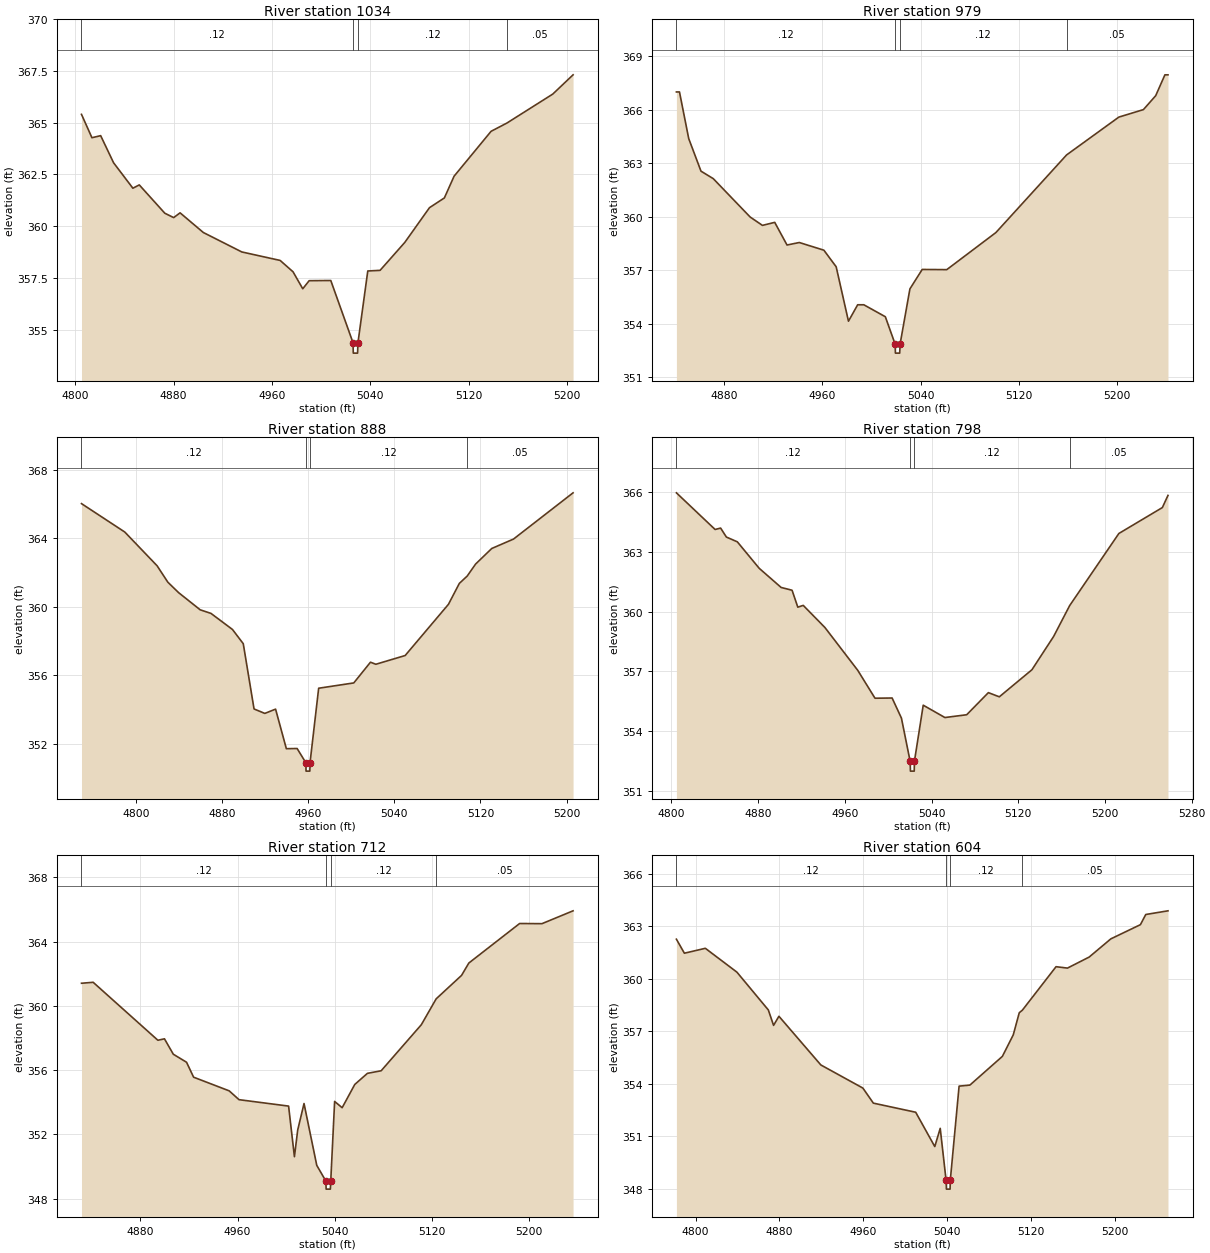
Type RM Length L Ch R = 1,1034,55,55,55
BEGIN DESCRIPTION:
Lacy 193 254
END DESCRIPTION:
XS GIS Cut Line= 3
      2673581.00      6817314.12      2673761.95      6817367.70
      2673972.46      6817384.61
#Sta/Elev= 30
  4805.1  365.40  4813.6  364.27  4820.7  364.37  4831.2  363.06  4846.9  361.83
  4852.1  361.99  4872.9  360.62  4880.1  360.41  4885.3  360.64  4904.2  359.69
  4935.5  358.75  4966.7  358.34  4977.2  357.79  4985.1  356.97  4990.3  357.36
  5007.9  357.37  5026.0  354.36  5026.2  353.86  5029.7  353.86  5030.0  354.36
  5038.0  357.83  5048.0  357.86  5068.1  359.21  5088.2  360.89  5100.3  361.36
  5108.2  362.41  5138.3  364.58  5151.2  364.98  5188.5  366.38  5205.0  367.31
#Mann=4,-1,0
  4805.1    0.12       0  5026.0    0.07       0  5030.0    0.12       0
  5151.2    0.05       0
Bank Sta=5026,5030
Exp/Cntr=0.3,0.1

Type RM Length L Ch R = 1,979,91,91,91
BEGIN DESCRIPTION:
Lacy 193 85
END DESCRIPTION:
XS GIS Cut Line= 3
      2673576.05      6817411.00      2673726.00      6817411.00
      2673976.05      6817411.00
#Sta/Elev= 30
  4841.3  366.99  4843.8  366.99  4851.3  364.38  4861.3  362.55  4871.3  362.13
  4901.3  359.98  4911.3  359.51  4921.3  359.68  4931.3  358.41  4941.3  358.55
  4961.3  358.12  4971.3  357.19  4981.3  354.14  4988.8  355.06  4993.8  355.06
  5011.3  354.39  5019.3  352.85  5019.5  352.35  5023.0  352.35  5023.3  352.85
  5031.3  355.95  5041.3  357.04  5061.3  357.03  5101.3  359.11  5158.8  363.46
  5201.3  365.58  5221.3  366.00  5231.3  366.78  5238.8  367.95  5241.3  367.95
#Mann=4,-1,0
  4841.3    0.12       0  5019.3    0.07       0  5023.3    0.12       0
  5158.8    0.05       0
Bank Sta=5019.3,5023.3
Exp/Cntr=0.3,0.1

Type RM Length L Ch R = 1,888,90,90,90
BEGIN DESCRIPTION:
Lacy 193 263
END DESCRIPTION:
XS GIS Cut Line= 3
      2673525.85      6817493.79      2673776.19      6817488.20
      2673981.04      6817466.46
#Sta/Elev= 30
  4749.6  366.03  4789.8  364.37  4819.8  362.40  4829.8  361.44  4839.8  360.83
  4859.8  359.83  4869.8  359.62  4889.8  358.68  4899.8  357.85  4909.8  354.04
  4919.8  353.78  4929.8  354.03  4939.8  351.72  4949.8  351.73  4957.8  350.91
  4958.1  350.41  4961.6  350.41  4961.8  350.91  4969.8  355.25  5002.4  355.56
  5017.9  356.77  5022.9  356.65  5050.1  357.16  5090.3  360.15  5100.4  361.37
  5107.7  361.80  5115.5  362.50  5130.5  363.41  5150.7  363.96  5206.0  366.66
#Mann=4,-1,0
  4749.6    0.12       0  4957.8    0.07       0  4961.8    0.12       0
  5107.7    0.05       0
Bank Sta=4957.8,4961.8
Exp/Cntr=0.3,0.1

Type RM Length L Ch R = 1,798,86,86,86
BEGIN DESCRIPTION:
Lacy 193 261
END DESCRIPTION:
XS GIS Cut Line= 3
      2673540.34      6817591.64      2673733.83      6817564.40
      2673991.18      6817544.72
#Sta/Elev= 30
  4804.6  365.96  4840.3  364.12  4845.4  364.19  4850.7  363.74  4860.8  363.50
  4881.0  362.17  4901.2  361.21  4911.3  361.07  4916.6  360.22  4921.6  360.31
  4941.6  359.20  4971.9  357.05  4987.8  355.65  5003.6  355.66  5012.2  354.65
  5020.2  352.49  5020.5  351.99  5024.0  351.99  5024.2  352.49  5032.3  355.30
  5052.3  354.68  5072.4  354.82  5092.4  355.93  5102.5  355.72  5132.6  357.08
  5152.6  358.75  5167.4  360.30  5212.8  363.92  5252.9  365.22  5258.1  365.83
#Mann=4,-1,0
  4804.6    0.12       0  5020.2    0.07       0  5024.2    0.12       0
  5167.4    0.05       0
Bank Sta=5020.2,5024.2
Exp/Cntr=0.3,0.1

Type RM Length L Ch R = 1,712,108,108,108
BEGIN DESCRIPTION:
Lacy 193 265
END DESCRIPTION:
XS GIS Cut Line= 3
      2673636.04      6817691.24      2673791.88      6817627.16
      2674018.17      6817559.48
#Sta/Elev= 30
  4831.5  361.41  4841.1  361.47  4894.4  357.86  4899.8  357.95  4907.1  356.99
  4918.0  356.49  4923.8  355.56  4953.1  354.71  4961.2  354.16  5002.0  353.76
  5006.8  350.61  5009.5  352.27  5014.7  353.92  5025.2  350.07  5032.7  349.09
  5032.9  348.59  5036.4  348.59  5036.7  349.09  5039.9  354.05  5046.1  353.66
  5056.5  355.11  5066.9  355.80  5078.2  355.96  5111.3  358.83  5123.5  360.44
  5144.4  361.90  5150.4  362.67  5192.2  365.13  5210.6  365.12  5236.2  365.92
#Mann=4,-1,0
  4831.5    0.12       0  5032.7    0.07       0  5036.7    0.12       0
  5123.5    0.05       0
Bank Sta=5032.7,5036.7
Exp/Cntr=0.3,0.1

Type RM Length L Ch R = 1,604,64,64,64
BEGIN DESCRIPTION:
Lacy 193 260
END DESCRIPTION:
XS GIS Cut Line= 3
      2673608.46      6817710.16      2673826.33      6817723.90
      2674068.71      6817659.87
#Sta/Elev= 30
  4781.7  362.26  4789.3  361.46  4809.3  361.74  4839.4  360.38  4869.4  358.22
  4874.4  357.34  4879.5  357.86  4919.5  355.08  4959.6  353.76  4969.6  352.90
  5010.0  352.38  5028.2  350.42  5033.4  351.46  5039.0  348.49  5039.3  347.99
  5042.8  347.99  5043.0  348.49  5051.4  353.87  5061.7  353.93  5092.7  355.57
  5103.1  356.80  5108.8  358.06  5111.8  358.21  5143.9  360.69  5154.8  360.61
  5175.5  361.24  5196.2  362.28  5224.4  363.09  5229.5  363.67  5250.7  363.88
#Mann=4,-1,0
  4781.7    0.12       0  5039.0    0.07       0  5043.0    0.12       0
  5111.8    0.05       0
Bank Sta=5039,5043
Exp/Cntr=0.3,0.1

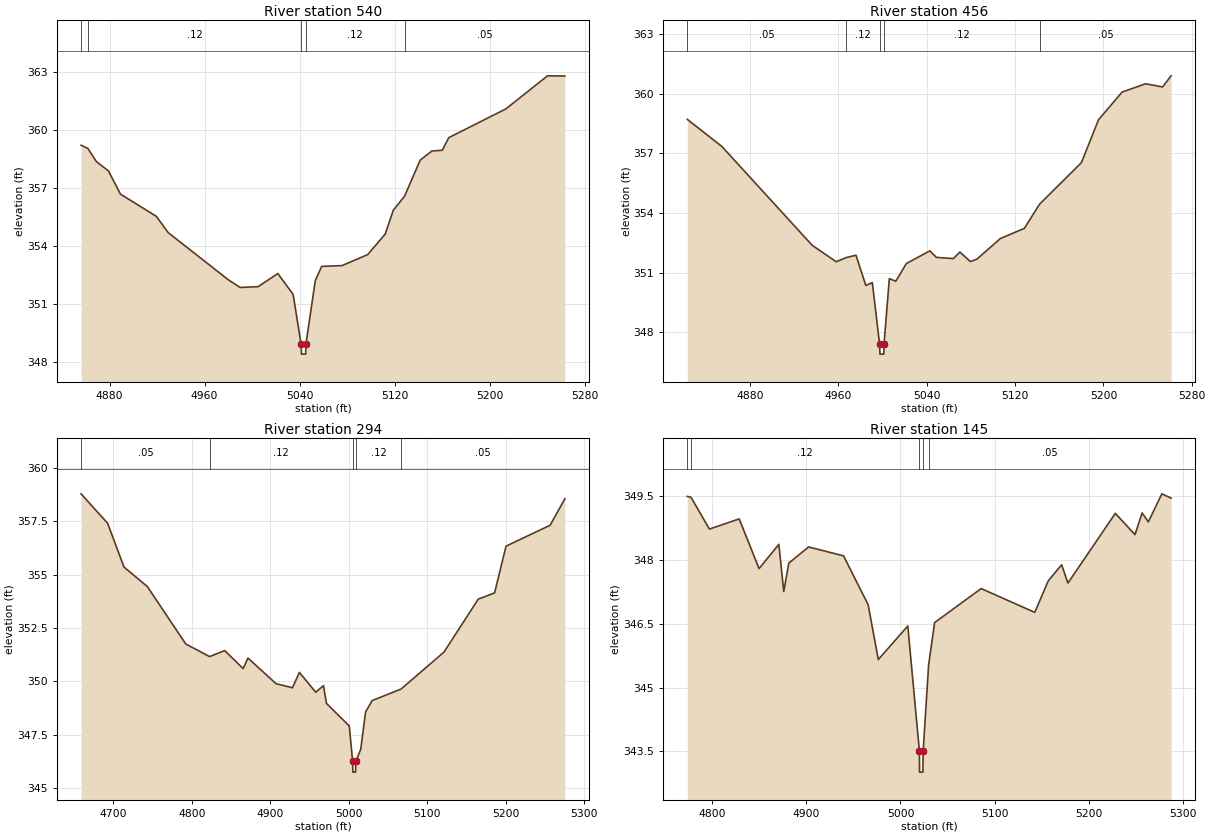
Type RM Length L Ch R = 1,540,84,84,84
BEGIN DESCRIPTION:
Lacy 193 262
END DESCRIPTION:
XS GIS Cut Line= 3
      2673683.21      6817805.77      2673825.97      6817787.75
      2674069.55      6817688.29
#Sta/Elev= 30
  4856.1  359.20  4861.8  359.03  4869.0  358.35  4879.1  357.87  4889.2  356.67
  4919.4  355.52  4929.3  354.68  4979.9  352.24  4989.9  351.84  5005.0  351.88
  5021.6  352.56  5034.5  351.48  5041.2  348.89  5041.5  348.39  5045.0  348.39
  5045.2  348.89  5053.1  352.19  5058.5  352.93  5075.6  352.97  5097.2  353.54
  5111.9  354.60  5118.8  355.84  5128.2  356.56  5141.4  358.43  5151.2  358.90
  5160.0  358.94  5165.4  359.59  5213.5  361.08  5248.5  362.79  5263.1  362.78
#Mann=5,-1,0
  4856.1    0.05       0  4861.8    0.12       0  5041.2    0.07       0
  5045.2    0.12       0  5128.2    0.05       0
Bank Sta=5041.2,5045.2
Exp/Cntr=0.3,0.1

Type RM Length L Ch R = 1,456,162,162,162
BEGIN DESCRIPTION:
Lacy 193 3407
END DESCRIPTION:
XS GIS Cut Line= 3
      2673682.23      6817821.59      2673805.39      6817888.80
      2674059.32      6817733.03
#Sta/Elev= 30
  4823.1  358.72  4854.5  357.35  4936.2  352.38  4958.0  351.55  4967.0  351.76
  4975.9  351.88  4984.8  350.36  4990.7  350.50  4997.3  347.40  4997.6  346.90
  5001.1  346.90  5001.3  347.40  5006.1  350.70  5012.0  350.57  5021.5  351.46
  5042.8  352.10  5048.7  351.77  5064.1  351.71  5070.0  352.04  5079.5  351.56
  5085.4  351.68  5106.7  352.72  5128.4  353.23  5142.2  354.45  5180.1  356.54
  5195.6  358.70  5216.9  360.09  5238.2  360.51  5253.6  360.35  5261.3  360.91
#Mann=5,-1,0
  4823.1    0.05       0  4967.0    0.12       0  4997.3    0.07       0
  5001.3    0.12       0  5142.2    0.05       0
Bank Sta=4997.3,5001.3
Exp/Cntr=0.3,0.1

Type RM Length L Ch R = 1,294,149,149,149
BEGIN DESCRIPTION:
Lacy 193 3408
END DESCRIPTION:
XS GIS Cut Line= 3
      2673676.55      6817834.41      2673930.06      6818010.86
      2674115.72      6817765.45
#Sta/Elev= 30
  4658.8  358.78  4692.6  357.40  4713.5  355.35  4743.2  354.44  4792.2  351.75
  4822.5  351.16  4841.8  351.44  4865.3  350.60  4871.5  351.09  4907.3  349.89
  4928.2  349.70  4937.0  350.42  4957.9  349.49  4967.7  349.80  4971.5  348.97
  5000.6  347.91  5004.9  346.25  5005.1  345.75  5008.6  345.75  5008.9  346.25
  5015.2  346.82  5021.4  348.57  5029.7  349.10  5066.6  349.64  5121.3  351.37
  5165.0  353.85  5185.8  354.14  5200.4  356.33  5256.6  357.31  5275.4  358.55
#Mann=5,-1,0
  4658.8    0.05       0  4822.5    0.12       0  5004.9    0.07       0
  5008.9    0.12       0  5066.6    0.05       0
Bank Sta=5004.9,5008.9
Exp/Cntr=0.3,0.1

Type RM Length L Ch R = 1,145,0,0,0
BEGIN DESCRIPTION:
Lacy 193 257
END DESCRIPTION:
XS GIS Cut Line= 3
      2673813.69      6818033.82      2674028.52      6818104.96
      2674217.26      6817888.35
#Sta/Elev= 30
  4773.7  349.50  4777.6  349.48  4797.2  348.73  4828.8  348.97  4849.9  347.80
  4870.9  348.37  4876.1  347.26  4881.5  347.93  4902.5  348.31  4939.6  348.10
  4965.7  346.95  4976.5  345.66  5007.8  346.45  5020.1  343.51  5020.3  343.01
  5023.8  343.01  5024.1  343.51  5029.9  345.53  5036.3  346.53  5085.7  347.33
  5142.6  346.77  5156.9  347.51  5171.1  347.89  5177.8  347.46  5228.1  349.10
  5249.0  348.60  5256.6  349.11  5263.2  348.90  5277.5  349.56  5287.3  349.46
#Mann=5,-1,0
  4773.7    0.05       0  4777.6    0.12       0  5020.1    0.07       0
  5024.1    0.12       0  5029.9    0.05       0
Bank Sta=5020.1,5024.1
Exp/Cntr=0.3,0.1

Chan Stop Cuts=-1