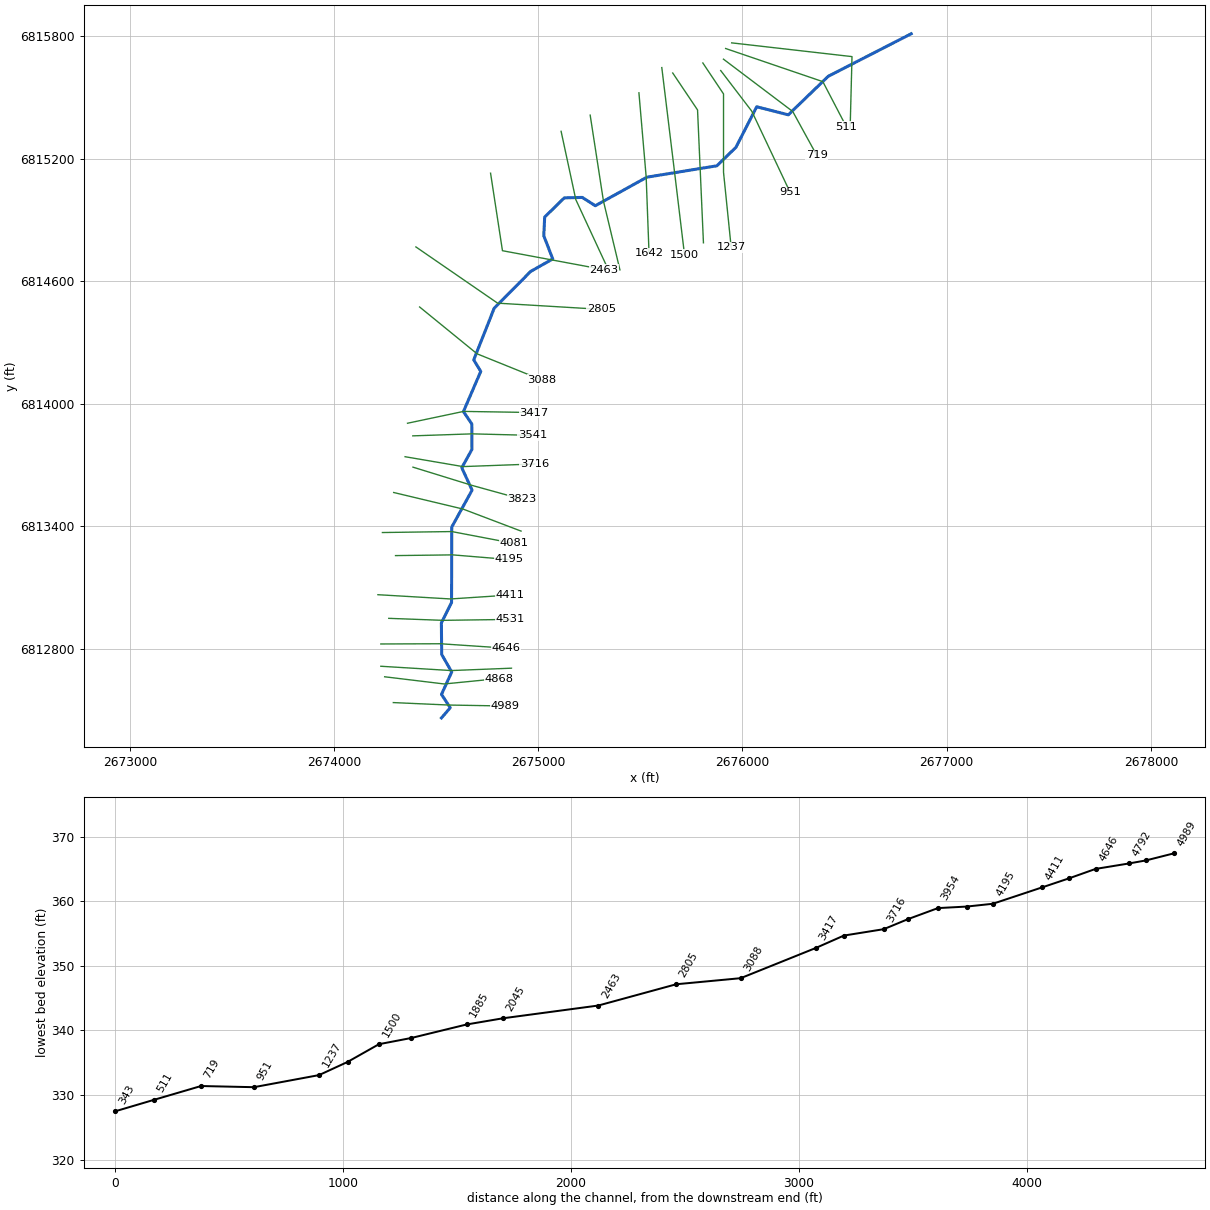
--- Lacy 194.prj (project) ---

Proj Title=Lacy 194 Base Level Engineering
Current Plan=p01
Default Exp/Contr=0.3,0.1
English Units
Geom File=g01
Flow File=f01
Plan File=p01
Y Axis Title=Elevation
X Axis Title(PF)=Main Channel Distance
X Axis Title(XS)=Station
BEGIN DESCRIPTION:
Lacy 194
END DESCRIPTION:
DSS Export Rating Curves= 0
DSS Export Rating Curve Sorted= 0
DSS Export Volume Flow Curves= 0
DXF OffsetX= 0
DXF OffsetY= 0
DXF ScaleX= 1
DXF ScaleY= 10

--- Lacy 194.p01 (plan) ---

Plan Title=Multiple Run
Short Identifier=Multiple
Geom File=g01
Flow File=f01
Subcritical Flow
K Sum by GR= 0
Std Step Tol= 0.01
Critical Tol= 0.01
Num of Std Step Trials= 20
Max Error Tol= 0.3
Flow Tol Ratio= 0.001
Split Flow NTrial= 30
Split Flow Tol= 0.02
Split Flow Ratio= 0.02
Log Output Level= 0
Friction Slope Method= 1
Unsteady Friction Slope Method= 2
Unsteady Bridges Friction Slope Method= 1
Parabolic Critical Depth
Global Vel Dist=  1 , 1 , 1
Global Log Level= 0
CheckData=True
Encroach Param= -1, 0, 0, 0
BEGIN DESCRIPTION:
Multiple Run
END DESCRIPTION:

--- Lacy 194.f01 (steady flow) ---

Flow Title=Multiple
Number of Profiles=7
Profile Names=10-year,25-year,50-year,1pct_min,100-year,1pct_plu,500-year
River Rch & RM= Lacy 194,Reach-1,4989
     257     326     379     219     436     871     578
River Rch & RM= Lacy 194,Reach-1,3088
     444     586     699     414     826    1649    1154
Boundary for River Rch & Prof#=Lacy 194,Reach-1,1
Up Type=0
Dn Type=3
Dn Slope=0.005
Boundary for River Rch & Prof#=Lacy 194,Reach-1,2
Up Type=0
Dn Type=3
Dn Slope=0.005
Boundary for River Rch & Prof#=Lacy 194,Reach-1,3
Up Type=0
Dn Type=3
Dn Slope=0.005
Boundary for River Rch & Prof#=Lacy 194,Reach-1,4
Up Type=0
Dn Type=3
Dn Slope=0.005
Boundary for River Rch & Prof#=Lacy 194,Reach-1,5
Up Type=0
Dn Type=3
Dn Slope=0.005
Boundary for River Rch & Prof#=Lacy 194,Reach-1,6
Up Type=0
Dn Type=3
Dn Slope=0.005
Boundary for River Rch & Prof#=Lacy 194,Reach-1,7
Up Type=0
Dn Type=3
Dn Slope=0.005

--- Lacy 194.g01 (geometry) ---

Geom Title=Existing Conditions
Program Version=4.10

River Reach=Lacy 194        ,Reach-1
Reach XY= 30
        2674526.        6812461.      2674569.05      6812510.88
      2674526.16      6812576.34      2674576.39        6812686.
      2674527.24       6812771.5      2674525.57      6812926.18
      2674575.48      6813026.22      2674576.51      6813395.79
      2674675.92      6813576.39      2674625.61        6813686.
      2674675.48      6813776.22      2674674.63      6813900.56
      2674633.51      6813961.01      2674718.49      6814157.66
      2674684.15      6814214.21      2674784.14      6814467.06
       2674962.8      6814647.36      2675071.01      6814708.45
      2675027.12      6814821.55      2675031.39      6814913.44
      2675127.48      6815007.54      2675215.51      6815009.74
      2675279.32      6814969.05      2675531.93      6815108.75
      2675874.54      6815164.54      2675967.87      6815254.93
      2676069.66      6815453.63      2676224.37      6815414.13
      2676419.94      6815602.86        2676826.        6815811.

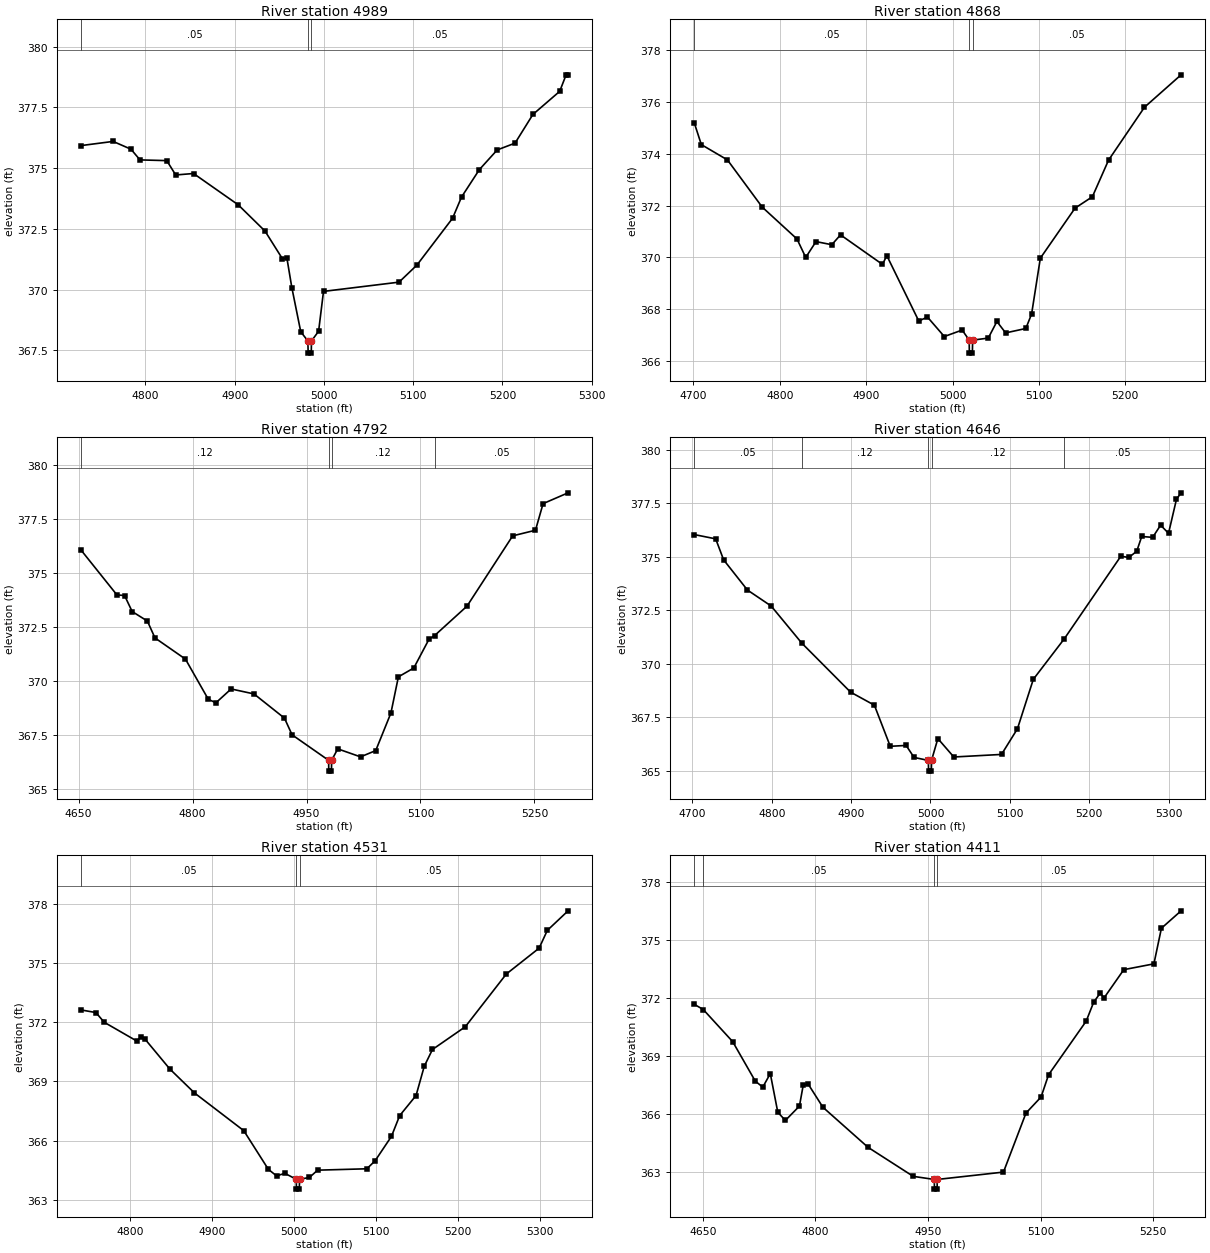
Type RM Length L Ch R = 1 ,4989    ,121,121,121
BEGIN DESCRIPTION:
Lacy 194 228
END DESCRIPTION:
XS GIS Cut Line= 3
      2674290.31      6812536.15      2674561.95      6812524.15
       2674835.4      6812519.44
#Sta/Elev= 30
  4728.1  375.93  4763.8   376.1  4783.8  375.78  4793.9  375.34  4823.9  375.31
  4833.9  374.72  4853.9  374.78    4904  373.49    4934  372.41  4953.5  371.27
  4958.5   371.3    4964  370.09    4974  368.27    4982  367.89  4982.3  367.39
  4985.8  367.39    4986  367.89    4994  368.29  4999.5  369.93  5084.1  370.31
  5104.1  371.01  5144.1  372.94  5154.1  373.81  5174.1  374.94  5194.1  375.75
  5214.1  376.03  5234.1  377.21  5264.1  378.16  5271.3  378.84  5273.5  378.84
#Mann= 3 ,-1 , 0
  4728.1     .05       0    4982     .05       0    4986     .05       0
Bank Sta=4982,4986
XS Rating Curve= 0 ,0
Exp/Cntr=0.3,0.1

Type RM Length L Ch R = 1 ,4868    ,76,76,76
BEGIN DESCRIPTION:
Lacy 194 227
END DESCRIPTION:
XS GIS Cut Line= 3
      2674247.86       6812662.5      2674539.74      6812627.29
      2674808.23      6812653.92
#Sta/Elev= 30
  4700.9  375.19  4709.1  374.35  4739.3  373.76  4779.6  371.94  4819.9  370.71
    4830     370  4841.9  370.61  4860.2  370.49  4870.3  370.87  4918.9  369.73
  4923.9  370.07  4960.9  367.55    4971   367.7  4990.5  366.95  5011.2   367.2
  5019.3  366.81  5019.5  366.31    5023  366.31  5023.3  366.81  5041.4  366.89
  5051.4  367.53  5061.5  367.09  5084.9  367.26  5091.6  367.82  5101.7  369.97
  5141.9   371.9    5162  372.34  5180.7  373.75  5222.3  375.79  5264.7  377.04
#Mann= 3 ,-1 , 0
  4700.9     .05       0  5019.3     .05       0  5023.3     .05       0
Bank Sta=5019.3,5023.3
XS Rating Curve= 0 ,0
Exp/Cntr=0.3,0.1

Type RM Length L Ch R = 1 ,4792    ,146,146,146
BEGIN DESCRIPTION:
Lacy 194 226
END DESCRIPTION:
XS GIS Cut Line= 3
      2674229.15      6812714.04       2674573.6      6812692.97
      2674868.87      6812704.59
#Sta/Elev= 30
  4653.6  376.04  4700.5  373.98  4710.6  373.95  4720.6  373.21  4740.6  372.77
  4750.6  371.99  4790.7  371.01  4820.8  369.15  4830.8  368.99  4850.8  369.63
  4880.9   369.4    4921  368.28    4931  367.51  4979.1  366.33  4979.3  365.83
  4982.8  365.83  4983.1  366.33  4991.1  366.86  5021.1  366.49  5041.1  366.78
  5061.1  368.52  5070.9  370.19  5091.2   370.6  5111.2  371.93  5118.6   372.1
  5161.2  373.46  5221.3  376.71  5251.3  376.97  5261.3   378.2  5294.2   378.7
#Mann= 4 ,-1 , 0
  4653.6     .12       0  4979.1     .07       0  4983.1     .12       0
  5118.6     .05       0
Bank Sta=4979.1,4983.1
XS Rating Curve= 0 ,0
Exp/Cntr=0.3,0.1

Type RM Length L Ch R = 1 ,4646    ,115,115,115
BEGIN DESCRIPTION:
Lacy 194 225
END DESCRIPTION:
XS GIS Cut Line= 3
      2674228.99      6812823.14      2674520.02      6812824.28
      2674841.77      6812802.77
#Sta/Elev= 30
  4702.3  376.04  4729.3  375.84  4739.3  374.86  4769.3  373.45  4799.3   372.7
  4837.8  370.97  4899.3  368.68  4929.3  368.07  4949.3  366.15  4969.3  366.19
  4979.3  365.63  4997.3  365.49  4997.6  364.99  5001.1  364.99  5001.3  365.49
  5009.3  366.51  5029.4  365.65  5089.5  365.77  5109.6  366.97  5129.6  369.28
  5168.8  371.18  5239.9  375.03  5249.9  374.97  5259.9  375.26  5266.2  375.95
    5280  375.91    5290  376.48    5300   376.1    5310  377.69  5315.8  377.99
#Mann= 5 ,-1 , 0
  4702.3     .05       0  4837.8     .12       0  4997.3     .07       0
  5001.3     .12       0  5168.8     .05       0
Bank Sta=4997.3,5001.3
XS Rating Curve= 0 ,0
Exp/Cntr=0.3,0.1

Type RM Length L Ch R = 1 ,4531    ,120,120,120
BEGIN DESCRIPTION:
Lacy 194 224
END DESCRIPTION:
XS GIS Cut Line= 3
      2674268.08      6812948.68      2674532.96      6812938.85
      2674861.26      6812943.41
#Sta/Elev= 30
  4740.7  372.62  4758.6  372.49  4768.6     372  4808.3  371.05  4813.3  371.26
  4818.7  371.13  4848.7  369.63  4878.7  368.42  4938.8  366.51  4968.8  364.55
  4978.8  364.22  4988.8  364.35  5002.8  364.05    5003  363.55  5006.5  363.55
  5006.8  364.05  5018.8  364.14  5028.8  364.51  5088.8  364.58  5098.8  364.98
  5118.8  366.22  5128.8  367.27  5148.8  368.29  5158.8  369.77  5168.8  370.62
  5208.8  371.77  5258.8  374.44  5298.8  375.75  5308.8  376.65  5334.1  377.64
#Mann= 3 ,-1 , 0
  4740.7     .05       0  5002.8     .03       0  5006.8     .05       0
Bank Sta=5002.8,5006.8
XS Rating Curve= 0 ,0
Exp/Cntr=0.3,0.1

Type RM Length L Ch R = 1 ,4411    ,216,216,216
BEGIN DESCRIPTION:
Lacy 194 222
END DESCRIPTION:
XS GIS Cut Line= 3
      2674214.85      6813064.41      2674570.38      6813043.57
       2674862.1      6813062.86
#Sta/Elev= 30
  4638.7  371.68  4650.7  371.41  4689.9  369.75    4720  367.71    4730   367.4
    4740   368.1    4750   366.1  4760.1  365.68  4778.8  366.42  4783.8  367.49
  4790.1  367.58  4810.1  366.36  4870.2  364.29  4930.4  362.79  4958.4  362.63
  4958.7  362.13  4962.2  362.13  4962.4  362.63  5050.6  363.01  5080.6  366.06
  5100.7  366.89  5110.7  368.04  5160.8  370.81  5170.8  371.79  5179.5  372.26
  5184.6  372.01  5210.9  373.47    5251  373.77    5261  375.61  5287.2  376.51
#Mann= 4 ,-1 , 0
  4638.7     .12       0  4650.7     .05       0  4958.4     .03       0
  4962.4     .05       0
Bank Sta=4958.4,4962.4
XS Rating Curve= 0 ,0
Exp/Cntr=0.3,0.1

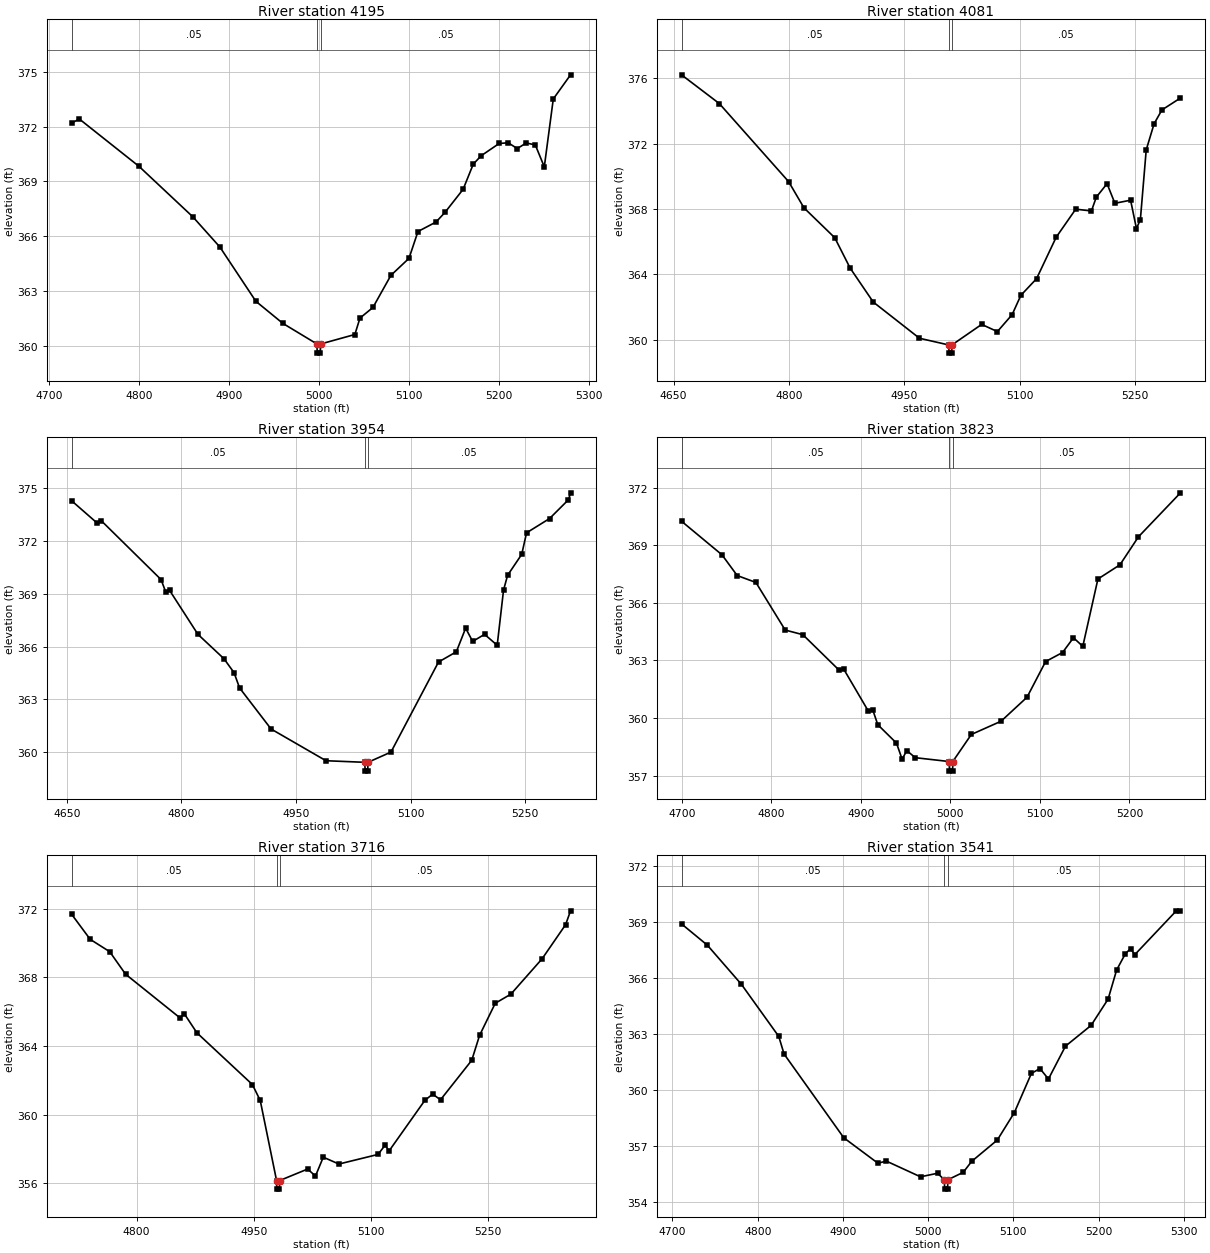
Type RM Length L Ch R = 1 ,4195    ,114,114,114
BEGIN DESCRIPTION:
Lacy 194 223
END DESCRIPTION:
XS GIS Cut Line= 3
      2674301.15      6813255.91      2674581.12       6813259.4
      2674855.09      6813236.79
#Sta/Elev= 30
    4725   372.2  4733.6  372.42  4799.9  369.83  4859.9  367.06  4889.9  365.41
  4929.9  362.44  4959.9  361.23  4997.9   360.1  4998.1   359.6  5001.6   359.6
  5001.9   360.1    5040  360.62  5045.7  361.52  5060.1   362.1  5080.1  363.86
  5100.2  364.79  5110.2  366.26  5130.3  366.78  5140.3  367.31  5160.4  368.57
  5171.7  369.95  5180.5  370.41  5200.5  371.08  5210.6  371.12  5220.6   370.8
  5230.6  371.11  5240.7     371  5250.7   369.8  5260.7  373.52  5279.9  374.84
#Mann= 3 ,-1 , 0
    4725     .05       0  4997.9     .04       0  5001.9     .05       0
Bank Sta=4997.9,5001.9
XS Rating Curve= 0 ,0
Exp/Cntr=0.3,0.1

Type RM Length L Ch R = 1 ,4081    ,127,127,127
BEGIN DESCRIPTION:
Lacy 194 221
END DESCRIPTION:
XS GIS Cut Line= 3
      2674236.88       6813368.8      2674576.43       6813373.6
      2674879.68      6813315.76
#Sta/Elev= 30
  4660.4  376.22  4709.5  374.46  4799.5  369.68  4819.5  368.07  4859.5  366.24
  4879.5  364.38  4909.5   362.3  4969.6  360.08  5007.7  359.67    5008  359.17
  5011.5  359.17  5011.7  359.67  5050.4  360.93  5070.8  360.49    5090  361.53
  5101.3  362.71  5121.7  363.73  5147.2  366.27  5172.6  367.99    5193  367.88
  5199.4  368.73  5213.3  369.55  5223.5  368.35  5243.9  368.54  5251.5   366.8
  5256.6  367.35  5264.2  371.62  5274.4  373.22  5284.6  374.07  5308.7   374.8
#Mann= 3 ,-1 , 0
  4660.4     .05       0  5007.7     .04       0  5011.7     .05       0
Bank Sta=5007.7,5011.7
XS Rating Curve= 0 ,0
Exp/Cntr=0.3,0.1

Type RM Length L Ch R = 1 ,3954    ,131,131,131
BEGIN DESCRIPTION:
Lacy 194 220
END DESCRIPTION:
XS GIS Cut Line= 3
      2674292.18      6813564.83      2674631.36      6813483.89
      2674915.74      6813375.89
#Sta/Elev= 30
  4656.4  374.27  4690.2  372.99  4695.4  373.13  4773.4   369.8  4779.6  369.09
  4784.7  369.18  4821.7  366.69  4855.7  365.31  4868.9  364.52  4876.2  363.65
  4917.4  361.32  4989.3  359.52  5040.2  359.43  5040.4  358.93  5043.9  358.93
  5044.2  359.43  5074.3  360.01  5136.5  365.12  5159.8   365.7    5172  367.04
  5181.2  366.29  5196.8  366.69  5213.3  366.07  5221.6   369.2  5226.9  370.04
  5245.4  371.23  5251.7  372.45  5281.8  373.26  5306.6  374.33  5309.3  374.72
#Mann= 3 ,-1 , 0
  4656.4     .05       0  5040.2     .03       0  5044.2     .05       0
Bank Sta=5040.2,5044.2
XS Rating Curve= 0 ,0
Exp/Cntr=0.3,0.1

Type RM Length L Ch R = 1 ,3823    ,107,107,107
BEGIN DESCRIPTION:
Lacy 194 219
END DESCRIPTION:
XS GIS Cut Line= 3
      2674386.56      6813688.96      2674677.37      6813599.18
      2674921.18      6813531.83
#Sta/Elev= 30
  4699.7  370.25  4744.9   368.5  4761.9  367.42  4782.8  367.06  4815.5  364.58
  4835.2  364.34  4875.5   362.5  4880.8  362.55  4908.2  360.37  4913.4  360.41
  4918.9  359.65  4939.8  358.69  4946.1  357.85  4951.3   358.3  4960.8  357.93
  4998.7  357.73    4999  357.23  5002.5  357.23  5002.7  357.73  5023.4  359.14
  5056.6  359.83  5085.6  361.08  5106.4  362.94  5125.3  363.41  5137.5  364.18
  5147.9  363.73  5164.8  367.24  5189.4  367.98  5210.1  369.44    5257  371.73
#Mann= 3 ,-1 , 0
  4699.7     .05       0  4998.7     .04       0  5002.7     .05       0
Bank Sta=4998.7,5002.7
XS Rating Curve= 0 ,0
Exp/Cntr=0.3,0.1

Type RM Length L Ch R = 1 ,3716    ,175,175,175
BEGIN DESCRIPTION:
Lacy 194 218
END DESCRIPTION:
XS GIS Cut Line= 3
      2674347.91      6813740.08      2674631.25      6813691.69
      2674982.38      6813704.51
#Sta/Elev= 30
  4716.9  371.67  4740.7  370.21  4765.7  369.49    4786  368.18  4855.9  365.63
    4861  365.89  4877.3  364.77  4948.3  361.76  4958.4  360.83  4979.3  356.17
  4979.5  355.67    4983  355.67  4983.3  356.17  5019.1  356.84  5029.1  356.43
  5039.1  357.53  5059.1  357.13  5109.2  357.69  5118.3  358.23  5123.3  357.89
  5169.2  360.84  5179.2   361.2  5189.2  360.87  5229.2  363.17  5239.2  364.62
  5259.3  366.49  5279.3  367.02  5319.3  369.08  5349.3  371.06  5355.7  371.87
#Mann= 3 ,-1 , 0
  4716.9     .05       0  4979.3     .04       0  4983.3     .05       0
Bank Sta=4979.3,4983.3
XS Rating Curve= 0 ,0
Exp/Cntr=0.3,0.1

Type RM Length L Ch R = 1 ,3541    ,124,124,124
BEGIN DESCRIPTION:
Lacy 194 191
END DESCRIPTION:
XS GIS Cut Line= 3
      2674385.73       6813842.2      2674676.64        6813852.
      2674970.87      6813844.55
#Sta/Elev= 30
  4710.6  368.89  4740.9  367.75  4780.9  365.65  4824.7  362.86  4830.9  361.92
    4901  357.43    4941  356.07    4951  356.18    4991  355.34    5011  355.53
    5019  355.18  5019.3  354.68  5022.8  354.68    5023  355.18  5041.1  355.58
  5051.1  356.17  5081.1  357.31  5101.1  358.78  5121.1  360.88  5131.1  361.14
  5141.1  360.58  5161.1  362.34  5191.1  363.45  5211.1  364.86  5221.1  366.42
  5231.1  367.27  5237.4  367.57  5242.4  367.24  5291.1  369.59    5296  369.59
#Mann= 3 ,-1 , 0
  4710.6     .05       0    5019     .03       0    5023     .05       0
Bank Sta=5019,5023
XS Rating Curve= 0 ,0
Exp/Cntr=0.3,0.1

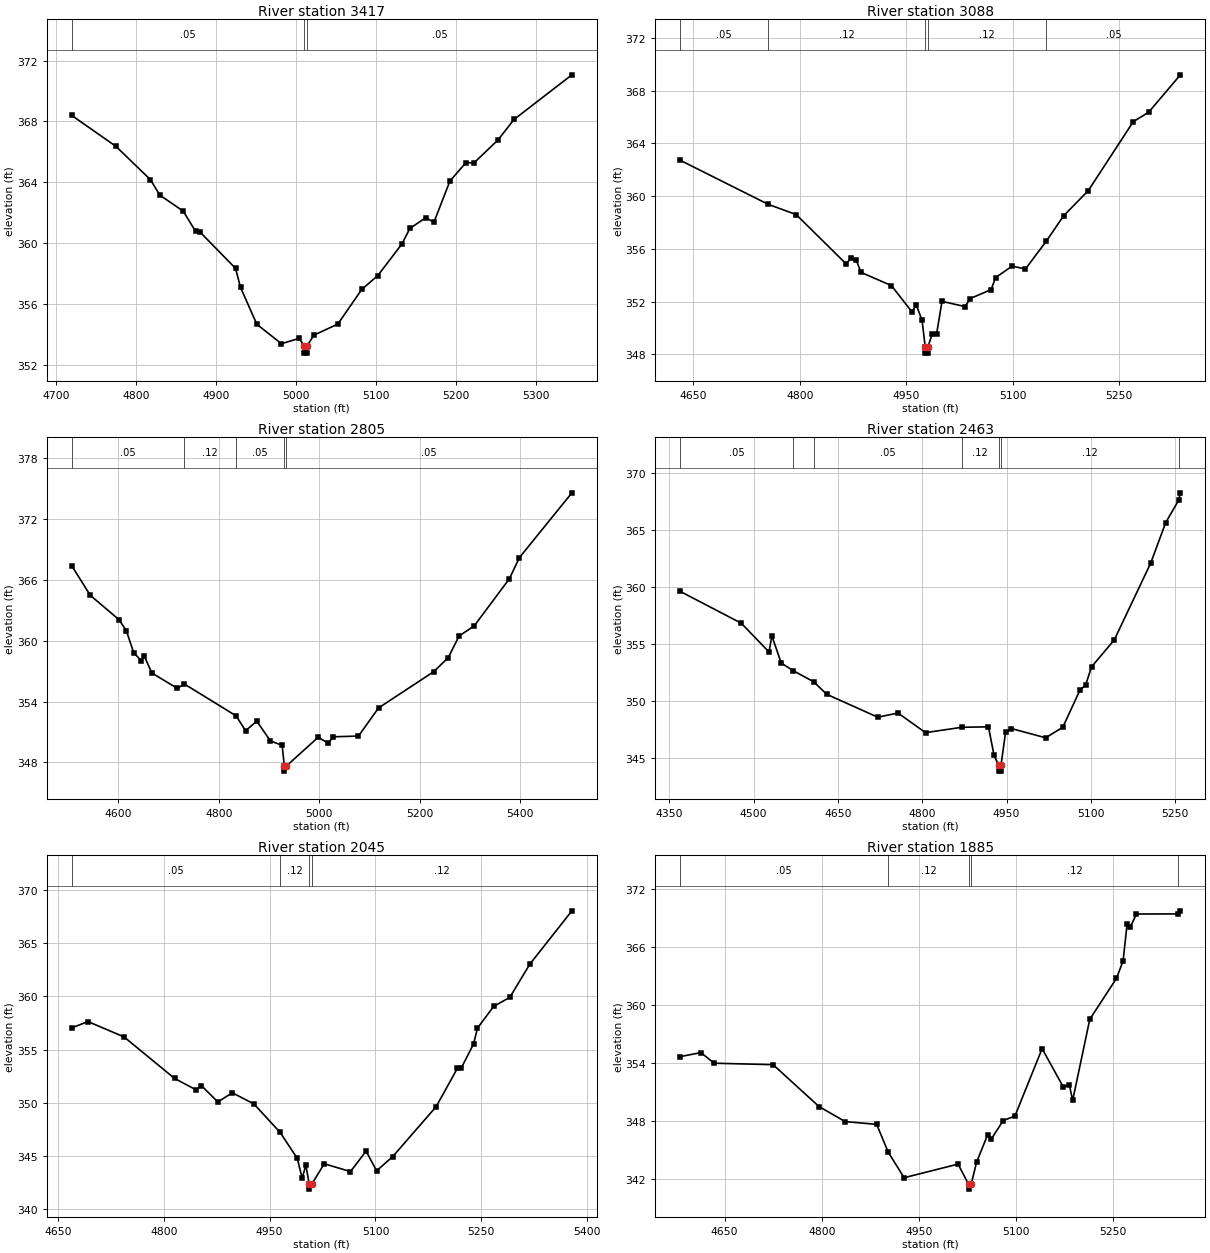
Type RM Length L Ch R = 1 ,3417    ,329,329,329
BEGIN DESCRIPTION:
Lacy 194 192
END DESCRIPTION:
XS GIS Cut Line= 3
      2674359.78      6813903.98      2674634.19      6813961.91
      2674978.29      6813956.41
#Sta/Elev= 30
  4719.9   368.4  4775.2  366.36  4818.2  364.17    4830  363.15  4859.1   362.1
  4874.7  360.76  4879.8  360.74  4924.5  358.33  4930.7  357.08  4951.1  354.65
  4981.8  353.37  5003.8  353.72  5010.2  353.25  5010.4  352.75  5013.9  352.75
  5014.2  353.25  5022.2  353.93  5052.2  354.66  5082.2  356.95  5102.2  357.86
  5132.2  359.93  5142.2  360.96  5162.2  361.67  5172.2  361.36  5192.2  364.08
  5212.2  365.29  5222.2  365.27  5252.2  366.78  5272.2  368.13  5344.5  371.07
#Mann= 3 ,-1 , 0
  4719.9     .05       0  5010.2     .03       0  5014.2     .05       0
Bank Sta=5010.2,5014.2
XS Rating Curve= 0 ,0
Exp/Cntr=0.3,0.1

Type RM Length L Ch R = 1 ,3088    ,283,283,283
BEGIN DESCRIPTION:
Lacy 194 190
END DESCRIPTION:
XS GIS Cut Line= 3
      2674419.08      6814473.28      2674700.46      6814243.89
      2675017.55      6814115.85
#Sta/Elev= 30
  4631.3  362.72  4755.2  359.38  4794.8   358.6  4865.2  354.86  4872.5  355.32
  4879.6  355.13    4886  354.22  4929.1  353.21  4957.8  351.23  4964.3  351.72
  4972.2  350.57  4976.6  348.59  4976.9  348.09  4980.4  348.09  4980.6  348.59
  4986.6  349.54  4992.7  349.55  5000.3  352.02  5032.7  351.62  5040.1  352.23
  5069.6  352.91  5075.8  353.82  5099.1  354.69  5117.9  354.47  5147.4  356.59
  5171.6   358.5  5206.5  360.42  5269.9  365.65  5291.5  366.36  5336.3   369.2
#Mann= 5 ,-1 , 0
  4631.3     .05       0  4755.2     .12       0  4976.6     .07       0
  4980.6     .12       0  5147.4     .05       0
Bank Sta=4976.6,4980.6
XS Rating Curve= 0 ,0
Exp/Cntr=0.3,0.1

Type RM Length L Ch R = 1 ,2805    ,342,342,342
BEGIN DESCRIPTION:
Lacy 194 187
END DESCRIPTION:
XS GIS Cut Line= 3
      2674400.89      6814767.29      2674800.91      6814491.98
      2675310.19      6814461.51
#Sta/Elev= 30
  4506.9  367.37    4544  364.45  4600.8  362.07  4615.6  360.99  4630.5  358.79
  4645.4  358.03  4651.5  358.48  4666.4  356.81  4717.1   355.3  4731.3  355.72
  4834.6  352.58    4853  351.12  4875.4  352.07  4902.4  350.13  4925.9  349.68
  4930.2  347.65  4930.5  347.15  4934.2  347.65  4997.6  350.48  5017.6   349.9
  5027.7  350.53  5077.8   350.6  5117.8  353.37    5228  356.95  5256.6  358.33
  5278.1  360.45  5308.2  361.44  5378.3  366.09  5398.3  368.17  5502.7  374.54
#Mann= 5 ,-1 , 0
  4506.9     .05       0  4731.3     .12       0  4834.6     .05       0
  4930.2     .03       0  4934.2     .05       0
Bank Sta=4930.2,4934.2
XS Rating Curve= 0 ,0
Exp/Cntr=0.3,0.1

Type RM Length L Ch R = 1 ,2463    ,418,418,418
BEGIN DESCRIPTION:
Lacy 194 186
END DESCRIPTION:
XS GIS Cut Line= 3
      2674766.47      6815128.48      2674824.72      6814748.79
      2675321.62      6814656.13
#Sta/Elev= 30
  4369.5   359.6  4478.2  356.81  4527.5  354.29  4532.6  355.71  4549.1  353.33
  4570.4  352.66  4607.1  351.68    4630  350.59    4721  348.58  4756.8  348.95
  4805.8  347.23  4870.7   347.7  4917.7  347.74  4927.6  345.26    4936  344.36
  4936.3  343.86  4939.8  343.86    4940  344.36  4948.2  347.27  4958.4  347.59
  5019.4  346.78  5049.9   347.7  5080.5  350.96  5090.6   351.4    5101  352.99
  5141.5  355.35  5206.4  362.09    5233  365.63  5255.9  367.57  5259.1  368.23
#Mann= 7 ,-1 , 0
  4369.5     .05       0  4570.4     .12       0  4607.1     .05       0
  4870.7     .12       0    4936     .07       0    4940     .12       0
  5255.9     .05       0
Bank Sta=4936,4940
XS Rating Curve= 0 ,0
Exp/Cntr=0.3,0.1

Type RM Length L Ch R = 1 ,2045    ,160,160,160
BEGIN DESCRIPTION:
Lacy 194 188
END DESCRIPTION:
XS GIS Cut Line= 3
      2675111.88      6815333.46      2675183.86      6814999.05
      2675338.12      6814666.45
#Sta/Elev= 30
  4669.6  357.03  4692.6  357.63  4743.7  356.19  4815.3  352.29    4846  351.21
  4853.3  351.62  4876.7  350.08  4897.2  350.94  4927.8  349.89  4964.9  347.22
  4989.2  344.78  4996.2   342.9  5001.3  344.16  5006.1  342.39  5006.4  341.89
  5010.1  342.39  5027.4  344.27  5064.6  343.54  5086.7  345.46  5101.6  343.61
  5124.5  344.95  5185.9  349.63  5216.1  353.24  5221.6  353.27    5239  355.53
  5244.5  357.01  5267.4  359.05  5290.3   359.9  5318.8  363.03  5378.3  368.03
#Mann= 4 ,-1 , 0
  4669.6     .05       0  4964.9     .12       0  5006.1     .07       0
  5010.1     .12       0
Bank Sta=5006.1,5010.1
XS Rating Curve= 0 ,0
Exp/Cntr=0.3,0.1

Type RM Length L Ch R = 1 ,1885    ,243,243,243
BEGIN DESCRIPTION:
Lacy 194 189
END DESCRIPTION:
XS GIS Cut Line= 3
      2675254.22      6815412.76      2675319.27      6814991.61
      2675399.89      6814654.98
#Sta/Elev= 30
  4581.5  354.64  4613.6  355.06  4633.9  353.96  4724.9  353.81  4795.8  349.48
  4836.2  347.92  4884.9  347.63  4902.7  344.75  4927.3  342.11  5010.5  343.52
  5026.8  341.43  5027.1  340.93  5030.8  341.43  5039.1  343.72  5056.3  346.57
  5061.4  346.07  5080.3  348.03  5098.3  348.49  5140.3  355.47  5172.8  351.52
  5182.4  351.68  5187.5  350.12  5213.9  358.51  5255.1  362.74  5265.3  364.55
  5271.6  368.41  5276.7  368.09  5285.9   369.4    5350  369.41  5353.8  369.73
#Mann= 5 ,-1 , 0
  4581.5     .05       0  4902.7     .12       0  5026.8     .07       0
  5030.8     .12       0    5350     .05       0
Bank Sta=5026.8,5030.8
XS Rating Curve= 0 ,0
Exp/Cntr=0.3,0.1

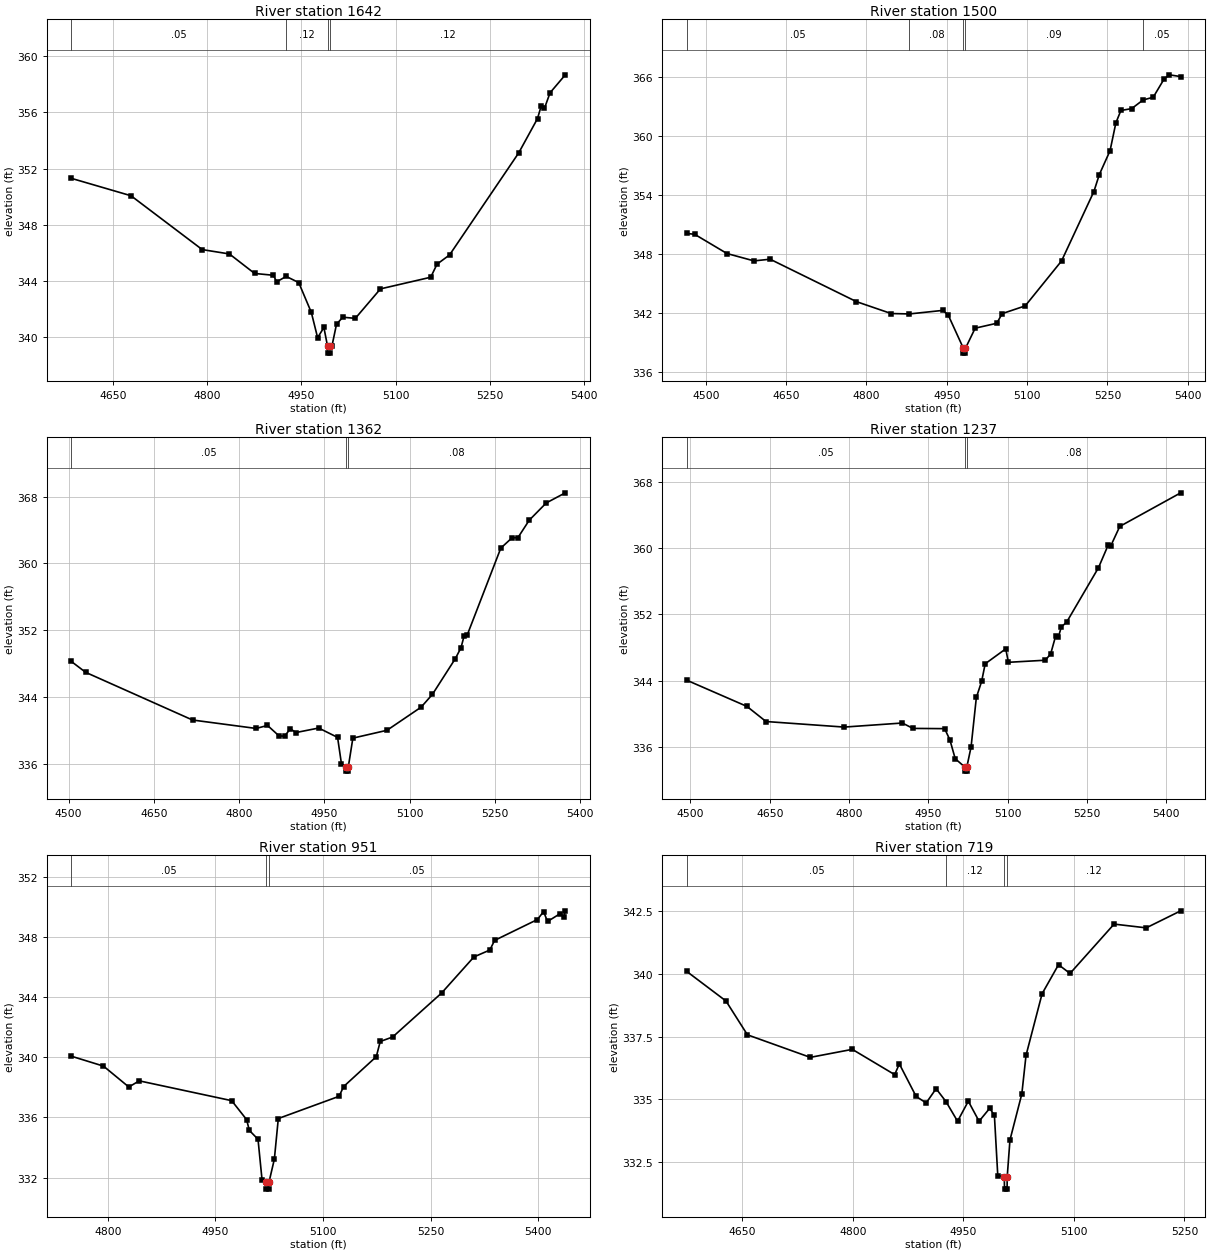
Type RM Length L Ch R = 1 ,1642    ,142,142,142
BEGIN DESCRIPTION:
Lacy 194 185
END DESCRIPTION:
XS GIS Cut Line= 3
      2675492.95      6815521.85      2675528.37      6815110.46
       2675542.4      6814736.74
#Sta/Elev= 30
  4583.5   351.3  4678.5  350.06    4792  346.22  4835.3  345.91  4875.4  344.52
  4905.5  344.39  4910.5  343.92  4925.7  344.31  4945.7  343.87  4965.8  341.74
  4975.8  339.94  4985.8  340.67  4991.6  339.34  4991.9  338.84  4995.4  338.84
  4995.6  339.34  4998.6  339.34  5005.9   340.9  5015.9   341.4  5035.9  341.32
  5075.9  343.42    5156  344.25    5166  345.18    5186  345.84  5296.1  353.11
  5326.1  355.56  5332.1  356.48  5337.1  356.28  5346.1   357.4  5370.4  358.68
#Mann= 4 ,-1 , 0
  4583.5     .05       0  4925.7     .12       0  4991.6     .07       0
  4995.6     .12       0
Bank Sta=4991.6,4995.6
XS Rating Curve= 0 ,0
Exp/Cntr=0.3,0.1

Type RM Length L Ch R = 1 ,1500    ,138,138,138
BEGIN DESCRIPTION:
Lacy 194 184
END DESCRIPTION:
XS GIS Cut Line= 3
      2675604.92      6815645.46      2675669.36        6815117.
      2675716.02      6814730.08
#Sta/Elev= 30
  4464.6  350.06  4479.2  349.98  4539.6  348.02    4590  347.27  4620.2  347.44
  4781.4  343.12  4846.1  341.91  4880.3  341.87  4942.6  342.23  4952.7  341.75
  4980.9  338.38  4981.1  337.88  4984.6  337.88  4984.9  338.38    5003  340.42
  5043.3  340.92  5053.4   341.9  5096.4  342.69  5164.2  347.26  5224.6  354.33
  5234.7  356.05  5254.8  358.49  5265.6  361.31    5275  362.58  5295.1  362.77
  5316.4  363.65  5335.4  363.93  5355.6  365.78  5365.6  366.21  5386.7  366.03
#Mann= 5 ,-1 , 0
  4464.6     .05       0  4880.3     .08       0  4980.9     .06       0
  4984.9     .09       0  5316.4     .05       0
Bank Sta=4980.9,4984.9
XS Rating Curve= 0 ,0
Exp/Cntr=0.3,0.1

Type RM Length L Ch R = 1 ,1362    ,125,125,125
BEGIN DESCRIPTION:
Lacy 194 198
END DESCRIPTION:
XS GIS Cut Line= 3
      2675658.41      6815618.98      2675779.97      6815438.05
      2675808.86      6814787.56
#Sta/Elev= 30
  4504.8  348.26  4529.9  346.96    4718  341.25  4829.9  340.24  4849.9   340.6
    4870  339.36    4880  339.31    4890   340.2    4900  339.75    4940  340.29
  4973.2  339.17  4980.1  335.97  4988.1  335.63  4988.3  335.13  4991.8  335.13
  4992.1  335.63  5000.1  339.08  5060.2  340.02  5120.2  342.79  5140.2  344.33
  5180.3  348.59  5190.3  349.89    5196  351.36    5201  351.37  5260.4  361.83
  5280.4  363.08  5290.4  363.07  5310.4  365.17  5340.4  367.24  5373.9  368.45
#Mann= 3 ,-1 , 0
  4504.8     .05       0  4988.1     .05       0  4992.1     .08       0
Bank Sta=4988.1,4992.1
XS Rating Curve= 0 ,0
Exp/Cntr=0.3,0.1

Type RM Length L Ch R = 1 ,1237    ,286,286,286
BEGIN DESCRIPTION:
Lacy 194 197
END DESCRIPTION:
XS GIS Cut Line= 4
      2675805.93      6815668.03      2675907.17      6815516.57
      2675907.18      6815132.57      2675944.57      6814766.25
#Sta/Elev= 30
    4493  344.06  4606.9   340.9  4642.9  339.08  4790.8  338.41  4900.8   338.9
  4920.8  338.25  4980.8  338.22  4990.8  336.86  5000.8   334.6  5018.8   333.6
    5019   333.1  5022.5   333.1  5022.8   333.6  5030.8  336.01  5040.8  341.98
  5050.8  343.92  5057.5  346.04  5096.4  347.84  5101.4  346.22  5171.3  346.47
  5181.4  347.24  5190.8  349.39  5195.9  349.24  5201.5  350.48  5211.5  351.05
  5271.8  357.62  5290.3  360.37  5295.4   360.3  5312.1   362.6  5427.4  366.65
#Mann= 3 ,-1 , 0
    4493     .05       0  5018.8     .03       0  5022.8     .08       0
Bank Sta=5018.8,5022.8
XS Rating Curve= 0 ,0
Exp/Cntr=0.3,0.1

Type RM Length L Ch R = 1 ,951     ,232,232,232
BEGIN DESCRIPTION:
Lacy 194 196
END DESCRIPTION:
XS GIS Cut Line= 3
      2675893.38      6815630.99      2676045.62      6815431.69
      2676232.68      6815035.86
#Sta/Elev= 30
  4749.2  340.08    4794  339.42  4829.3  338.03  4843.8  338.44  4972.7  337.12
  4993.5  335.86  4997.3  335.14  5009.4  334.55    5015  331.86  5020.9  331.73
  5021.1  331.23  5024.6  331.23  5024.9  331.73  5032.2  333.23  5037.7  335.93
  5122.4  337.41  5128.8  338.06  5174.3  340.05  5179.8  341.06  5197.1  341.36
  5265.4  344.29  5310.4  346.69  5332.6  347.15  5339.2  347.79  5398.9  349.18
  5407.5  349.71    5413  349.05  5430.2  349.56  5435.8  349.37  5437.8  349.76
#Mann= 3 ,-1 , 0
  4749.2     .05       0  5020.9     .03       0  5024.9     .05       0
Bank Sta=5020.9,5024.9
XS Rating Curve= 0 ,0
Exp/Cntr=0.3,0.1

Type RM Length L Ch R = 1 ,719     ,208,208,208
BEGIN DESCRIPTION:
Lacy 194 195
END DESCRIPTION:
XS GIS Cut Line= 3
      2675906.83      6815686.74      2676246.09      6815430.43
      2676363.88       6815215.6
#Sta/Elev= 30
  4574.8   340.1    4628  338.92  4657.1  337.57  4742.4  336.67  4799.4  336.99
  4856.9  335.98  4863.2  336.41    4886  335.11  4899.6  334.85  4913.1  335.42
  4926.6   334.9  4942.2  334.12  4956.8  334.92  4971.4  334.12  4985.9  334.64
  4992.2  334.35  4996.8  331.94  5005.6  331.91  5005.9  331.41  5009.4  331.41
  5009.6  331.91  5013.3  333.37  5029.4  335.21  5035.1  336.75  5056.9  339.21
  5079.2  340.37  5094.8  340.02  5154.6  341.99  5198.2  341.84    5245  342.52
#Mann= 4 ,-1 , 0
  4574.8     .05       0  4926.6     .12       0  5005.6     .07       0
  5009.6     .12       0
Bank Sta=5005.6,5009.6
XS Rating Curve= 0 ,0
Exp/Cntr=0.3,0.1

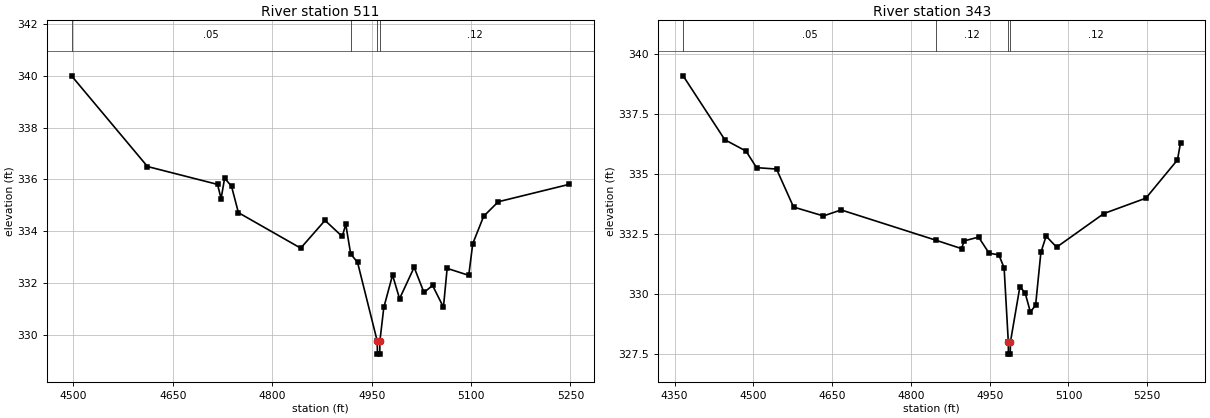
Type RM Length L Ch R = 1 ,511     ,168,168,168
BEGIN DESCRIPTION:
Lacy 194 194
END DESCRIPTION:
XS GIS Cut Line= 3
      2675917.48       6815738.9      2676393.48      6815576.61
      2676507.97      6815356.96
#Sta/Elev= 30
  4497.1     340  4611.7   336.5  4717.4  335.81  4722.8  335.26  4728.1  336.05
  4738.5  335.74  4748.9  334.72  4842.9  333.35  4879.6  334.42  4905.6   333.8
  4910.9  334.27  4918.3  333.13  4928.7   332.8  4958.4  329.76  4958.7  329.26
  4962.2  329.26  4962.4  329.76  4968.3  331.06  4981.5  332.31  4992.1   331.4
  5014.1  332.61  5028.9  331.64  5041.9  331.91  5058.3  331.07  5063.9  332.57
  5096.5   332.3  5102.5  333.52    5119  334.58    5141  335.14  5247.7  335.81
#Mann= 4 ,-1 , 0
  4497.1     .05       0  4918.3     .12       0  4958.4     .07       0
  4962.4     .12       0
Bank Sta=4958.4,4962.4
XS Rating Curve= 0 ,0
Exp/Cntr=0.3,0.1

Type RM Length L Ch R = 1 ,343     ,0,0,0
BEGIN DESCRIPTION:
Lacy 194 3442
END DESCRIPTION:
XS GIS Cut Line= 3
      2675947.07      6815766.51       2676536.3      6815699.19
      2676527.06      6815345.07
#Sta/Elev= 30
  4366.1  339.09  4445.5  336.43  4485.8  335.96  4505.9  335.27    4544  335.21
  4576.4  333.63  4633.3  333.26    4667  333.51  4847.5  332.25  4896.3   331.9
  4901.3  332.22  4928.7  332.38  4948.8  331.71  4967.4  331.64  4977.4   331.1
  4985.4  328.01  4985.6  327.51  4989.1  327.51  4989.4  328.01  5007.4  330.31
  5017.4  330.06  5027.4  329.26  5037.4  329.55  5047.4  331.74  5057.4  332.42
  5077.4  331.96  5167.4  333.36  5247.4     334  5307.5  335.59  5313.4  336.31
#Mann= 4 ,-1 , 0
  4366.1     .05       0  4847.5     .12       0  4985.4     .07       0
  4989.4     .12       0
Bank Sta=4985.4,4989.4
XS Rating Curve= 0 ,0
Exp/Cntr=0.3,0.1

Chan Stop Cuts=-1
Use User Specified Reach Order=0
Composite Channel Slope=5