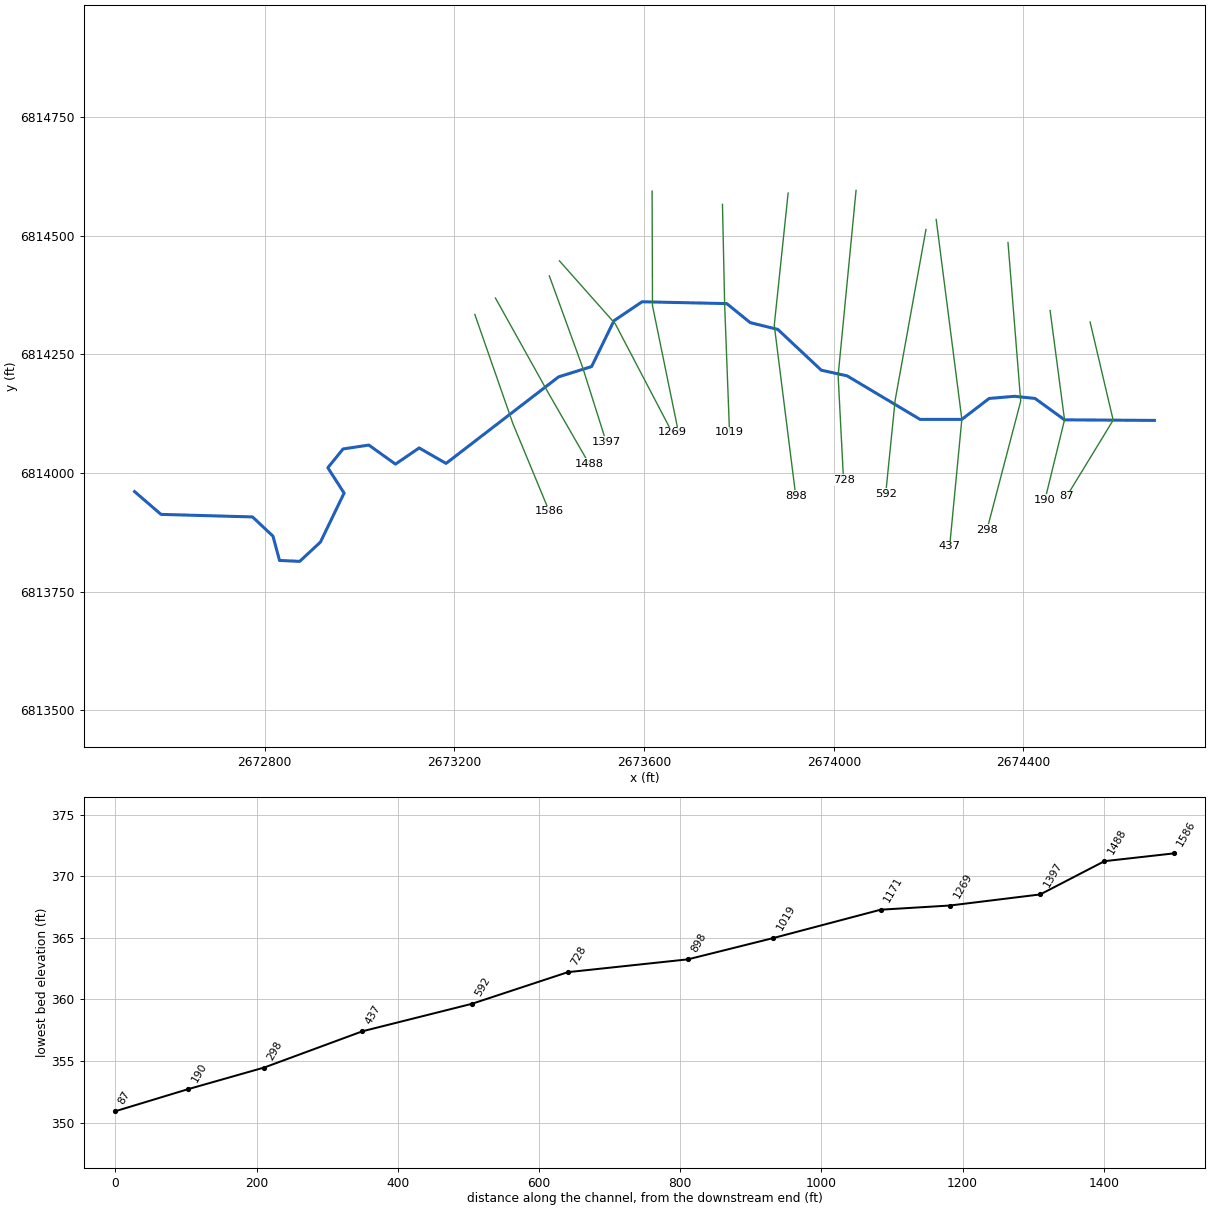
--- Lacy 195.prj (project) ---

Proj Title=Lacy 195 Base Level Engineering
Current Plan=p01
Default Exp/Contr=0.3,0.1
English Units
Geom File=g01
Flow File=f01
Plan File=p01
BEGIN DESCRIPTION:
Lacy 195
END DESCRIPTION:

--- Lacy 195.p01 (plan) ---

Plan Title=Multiple Run
Short Identifier=Multiple
Geom File=g01
Flow File=f01
Subcritical Flow
K Sum by GR= 0
Std Step Tol= 0.01
Critical Tol= 0.01
Num of Std Step Trials= 20
Max Error Tol= 0.3
Flow Tol Ratio= 0.001
Split Flow NTrial= 30
Split Flow Tol= 0.02
Split Flow Ratio= 0.02
Log Output Level= 0
Friction Slope Method= 1
Unsteady Friction Slope Method= 2
Unsteady Bridges Friction Slope Method= 1
Parabolic Critical Depth
Global Vel Dist=  1 , 1 , 1
Global Log Level= 0
CheckData=True
Encroach Param= -1, 0, 0, 0
BEGIN DESCRIPTION:
Multiple Run
END DESCRIPTION:

--- Lacy 195.f01 (steady flow) ---

Flow Title=Multiple
Number of Profiles=7
Profile Names=10-year,25-year,50-year,1pct_min,100-year,1pct_plu,500-year
River Rch & RM= Lacy 195,Reach-1,1586
     157     193     221     126     251     501     323
Boundary for River Rch & Prof#=Lacy 195,Reach-1,1
Up Type=0
Dn Type=3
Dn Slope=0.005
Boundary for River Rch & Prof#=Lacy 195,Reach-1,2
Up Type=0
Dn Type=3
Dn Slope=0.005
Boundary for River Rch & Prof#=Lacy 195,Reach-1,3
Up Type=0
Dn Type=3
Dn Slope=0.005
Boundary for River Rch & Prof#=Lacy 195,Reach-1,4
Up Type=0
Dn Type=3
Dn Slope=0.005
Boundary for River Rch & Prof#=Lacy 195,Reach-1,5
Up Type=0
Dn Type=3
Dn Slope=0.005
Boundary for River Rch & Prof#=Lacy 195,Reach-1,6
Up Type=0
Dn Type=3
Dn Slope=0.005
Boundary for River Rch & Prof#=Lacy 195,Reach-1,7
Up Type=0
Dn Type=3
Dn Slope=0.005

--- Lacy 195.g01 (geometry) ---

Geom Title=Existing Conditions

River Reach=Lacy 195,Reach-1
Reach XY= 30
      2672526.00      6813961.00      2672581.78      6813912.89
      2672774.74      6813907.52      2672817.86      6813866.98
      2672831.66      6813815.76      2672874.21      6813813.86
      2672917.95      6813854.55      2672967.75      6813957.78
      2672933.46      6814011.28      2672965.61      6814050.80
      2673019.87      6814059.03      2673076.09      6814018.81
      2673126.00      6814052.96      2673182.66      6814020.31
      2673419.98      6814202.82      2673489.56      6814224.49
      2673536.63      6814321.04      2673595.88      6814361.09
      2673774.45      6814357.25      2673823.83      6814317.14
      2673882.05      6814302.84      2673973.71      6814216.85
      2674028.19      6814204.90      2674181.97      6814113.14
      2674270.03      6814113.17      2674327.60      6814157.29
      2674381.03      6814161.81      2674424.40      6814157.30
      2674486.50      6814112.21      2674676.00      6814111.00

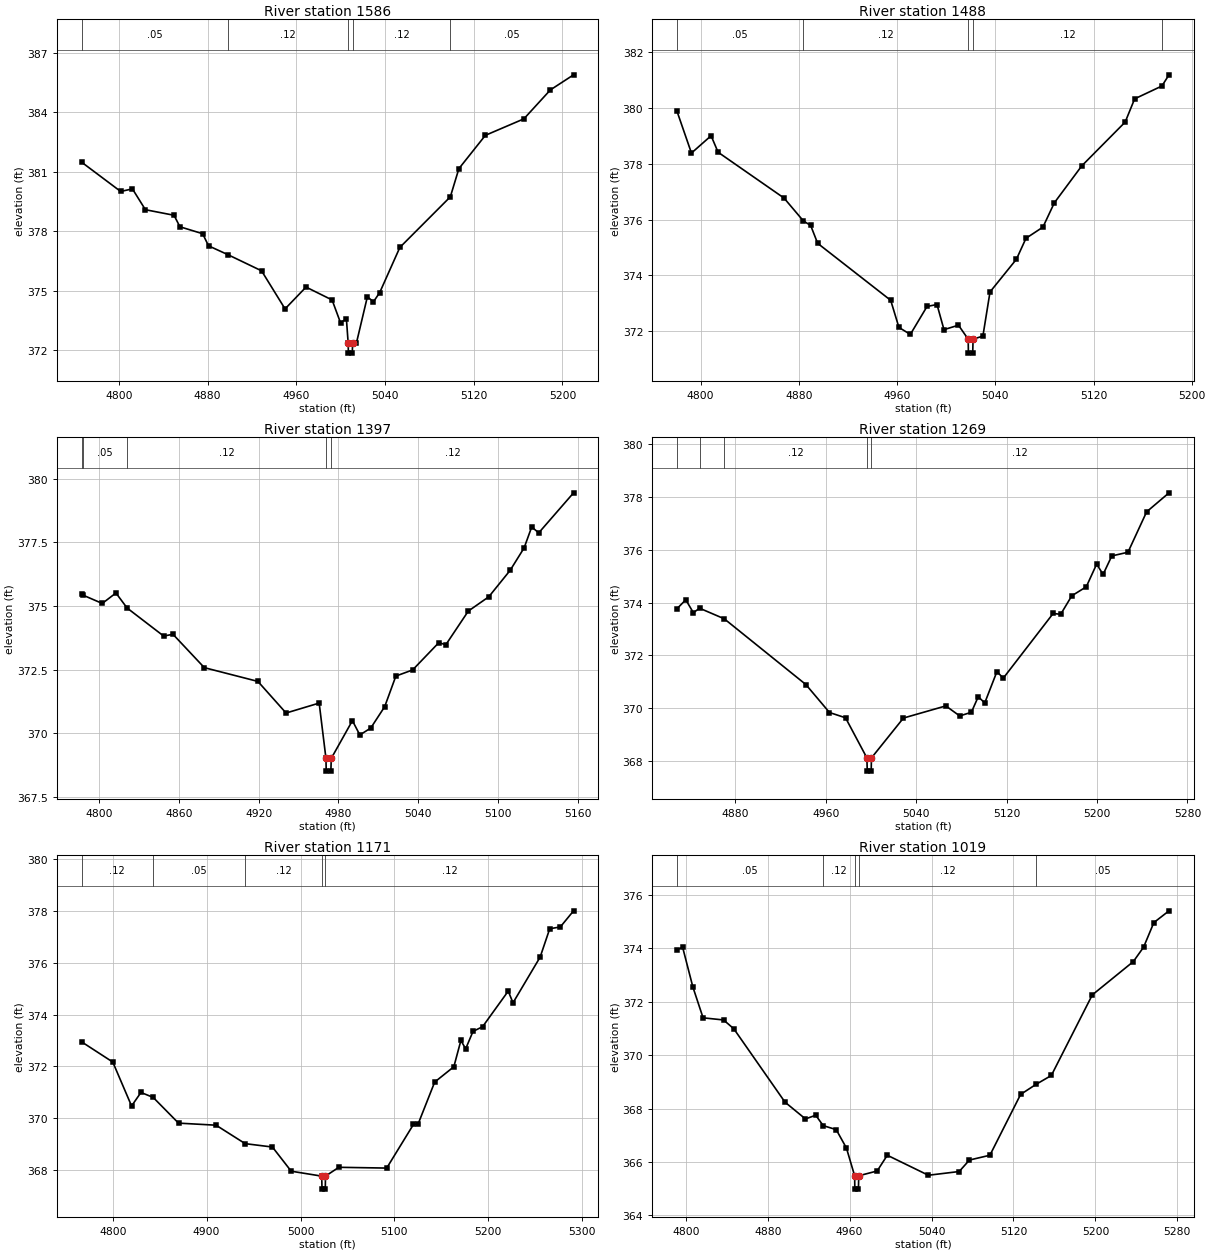
Type RM Length L Ch R = 1,1586,98,98,98
BEGIN DESCRIPTION:
Lacy 195 213
END DESCRIPTION:
XS GIS Cut Line= 3
      2673243.41      6814334.30      2673323.38      6814104.84
      2673400.16      6813919.52
#Sta/Elev= 30
  4766.4  381.48  4801.7  380.00  4812.3  380.13  4824.0  379.08  4849.8  378.80
  4855.1  378.22  4875.6  377.87  4880.9  377.26  4898.5  376.81  4928.7  376.00
  4949.9  374.08  4968.8  375.18  4992.3  374.53  4999.9  373.38  5005.2  373.58
  5006.8  372.35  5007.0  371.85  5010.5  371.85  5010.8  372.35  5014.2  372.35
  5024.1  374.69  5029.6  374.44  5035.2  374.90  5053.4  377.18  5098.9  379.73
  5106.6  381.15  5130.5  382.83  5165.2  383.66  5189.1  385.12  5210.0  385.88
#Mann=5,-1,0
  4766.4    0.05       0  4898.5    0.12       0  5006.8    0.07       0
  5010.8    0.12       0  5098.9    0.05       0
Bank Sta=5006.8,5010.8
Exp/Cntr=0.3,0.1

Type RM Length L Ch R = 1,1488,91,91,91
BEGIN DESCRIPTION:
Lacy 195 214
END DESCRIPTION:
XS GIS Cut Line= 3
      2673286.78      6814368.97      2673396.91      6814171.37
      2673483.97      6814020.05
#Sta/Elev= 30
  4780.7  379.88  4792.5  378.38  4808.5  379.00  4814.2  378.41  4867.9  376.77
  4883.7  375.95  4889.6  375.79  4895.3  375.15  4954.8  373.11  4961.5  372.14
  4970.8  371.89  4984.4  372.89  4992.5  372.96  4998.2  372.06  5010.0  372.22
  5017.9  371.72  5018.1  371.22  5021.6  371.22  5021.9  371.72  5029.9  371.83
  5035.7  373.41  5057.2  374.58  5065.0  375.33  5078.8  375.73  5088.1  376.60
  5110.4  377.92  5145.8  379.49  5153.5  380.32  5175.7  380.78  5181.5  381.18
#Mann=5,-1,0
  4780.7    0.05       0  4883.7    0.12       0  5017.9    0.07       0
  5021.9    0.12       0  5175.7    0.05       0
Bank Sta=5017.9,5021.9
Exp/Cntr=0.3,0.1

Type RM Length L Ch R = 1,1397,128,128,128
BEGIN DESCRIPTION:
Lacy 195 215
END DESCRIPTION:
XS GIS Cut Line= 3
      2673400.41      6814415.66      2673470.78      6814222.33
      2673520.33      6814065.51
#Sta/Elev= 30
  4786.7  375.46  4787.6  375.43  4802.3  375.10  4812.6  375.51  4821.0  374.92
  4848.5  373.82  4855.5  373.89  4879.1  372.58  4919.4  372.04  4940.6  370.80
  4965.5  371.19  4970.6  369.02  4970.8  368.52  4974.3  368.52  4974.6  369.02
  4990.5  370.50  4996.1  369.94  5004.3  370.21  5014.8  371.05  5023.2  372.25
  5035.8  372.49  5055.5  373.56  5060.8  373.48  5077.7  374.80  5093.1  375.36
  5109.2  376.40  5119.7  377.28  5125.4  378.10  5130.7  377.87  5156.9  379.44
#Mann=5,-1,0
  4786.7    0.12       0  4787.6    0.05       0  4821.0    0.12       0
  4970.6    0.07       0  4974.6    0.12       0
Bank Sta=4970.6,4974.6
Exp/Cntr=0.3,0.1

Type RM Length L Ch R = 1,1269,98,98,98
BEGIN DESCRIPTION:
Lacy 195 216
END DESCRIPTION:
XS GIS Cut Line= 3
      2673421.77      6814447.28      2673539.34      6814314.74
      2673658.99      6814086.13
#Sta/Elev= 30
  4828.5  373.77  4836.3  374.11  4843.0  373.62  4848.5  373.79  4870.3  373.39
  4942.5  370.90  4963.4  369.84  4977.6  369.64  4996.5  368.12  4996.8  367.62
  5000.3  367.62  5000.5  368.12  5028.8  369.63  5066.3  370.09  5078.6  369.71
  5088.9  369.85  5095.0  370.44  5100.7  370.20  5111.5  371.39  5117.1  371.14
  5161.2  373.59  5167.9  373.56  5177.7  374.26  5190.5  374.60  5199.7  375.46
  5205.4  375.07  5213.1  375.77  5227.4  375.91  5243.9  377.44  5263.7  378.16
#Mann=5,-1,0
  4828.5    0.12       0  4848.5    0.05       0  4870.3    0.12       0
  4996.5    0.07       0  5000.5    0.12       0
Bank Sta=4996.5,5000.5
Exp/Cntr=0.3,0.1

Type RM Length L Ch R = 1,1171,152,152,152
BEGIN DESCRIPTION:
Lacy 195 217
END DESCRIPTION:
XS GIS Cut Line= 3
      2673617.06      6814594.33      2673617.90      6814352.81
      2673674.64      6814076.08
#Sta/Elev= 30
  4766.8  372.95  4800.1  372.17  4820.1  370.48  4830.1  371.00  4843.1  370.81
  4870.1  369.82  4910.1  369.74  4941.1  369.03  4970.1  368.90  4990.1  367.97
  5022.6  367.78  5022.9  367.28  5026.4  367.28  5026.6  367.78  5040.8  368.12
  5091.8  368.09  5120.3  369.77  5125.4  369.80  5142.9  371.40  5163.3  371.99
  5170.8  373.00  5175.9  372.68  5183.7  373.35  5193.9  373.53  5221.2  374.90
  5226.3  374.45  5255.2  376.21  5265.4  377.30  5276.7  377.37  5290.8  377.99
#Mann=5,-1,0
  4766.8    0.12       0  4843.1    0.05       0  4941.1    0.12       0
  5022.6    0.07       0  5026.6    0.12       0
Bank Sta=5022.6,5026.6
Exp/Cntr=0.3,0.1

Type RM Length L Ch R = 1,1019,121,121,121
BEGIN DESCRIPTION:
Lacy 195 212
END DESCRIPTION:
XS GIS Cut Line= 3
      2673765.41      6814566.46      2673769.98      6814356.12
      2673780.26      6814086.20
#Sta/Elev= 30
  4791.4  373.94  4796.9  374.05  4806.9  372.56  4816.9  371.40  4836.9  371.32
  4846.9  370.99  4896.9  368.24  4916.9  367.61  4926.9  367.75  4934.2  367.36
  4946.9  367.21  4956.9  366.52  4964.9  365.48  4965.1  364.98  4968.6  364.98
  4968.9  365.48  4986.9  365.66  4996.8  366.25  5036.9  365.50  5067.0  365.64
  5077.0  366.07  5097.0  366.25  5127.0  368.53  5142.2  368.91  5157.0  369.24
  5197.0  372.26  5237.1  373.51  5247.1  374.05  5257.1  374.97  5271.9  375.41
#Mann=5,-1,0
  4791.4    0.05       0  4934.2    0.12       0  4964.9    0.07       0
  4968.9    0.12       0  5142.2    0.05       0
Bank Sta=4964.9,4968.9
Exp/Cntr=0.3,0.1

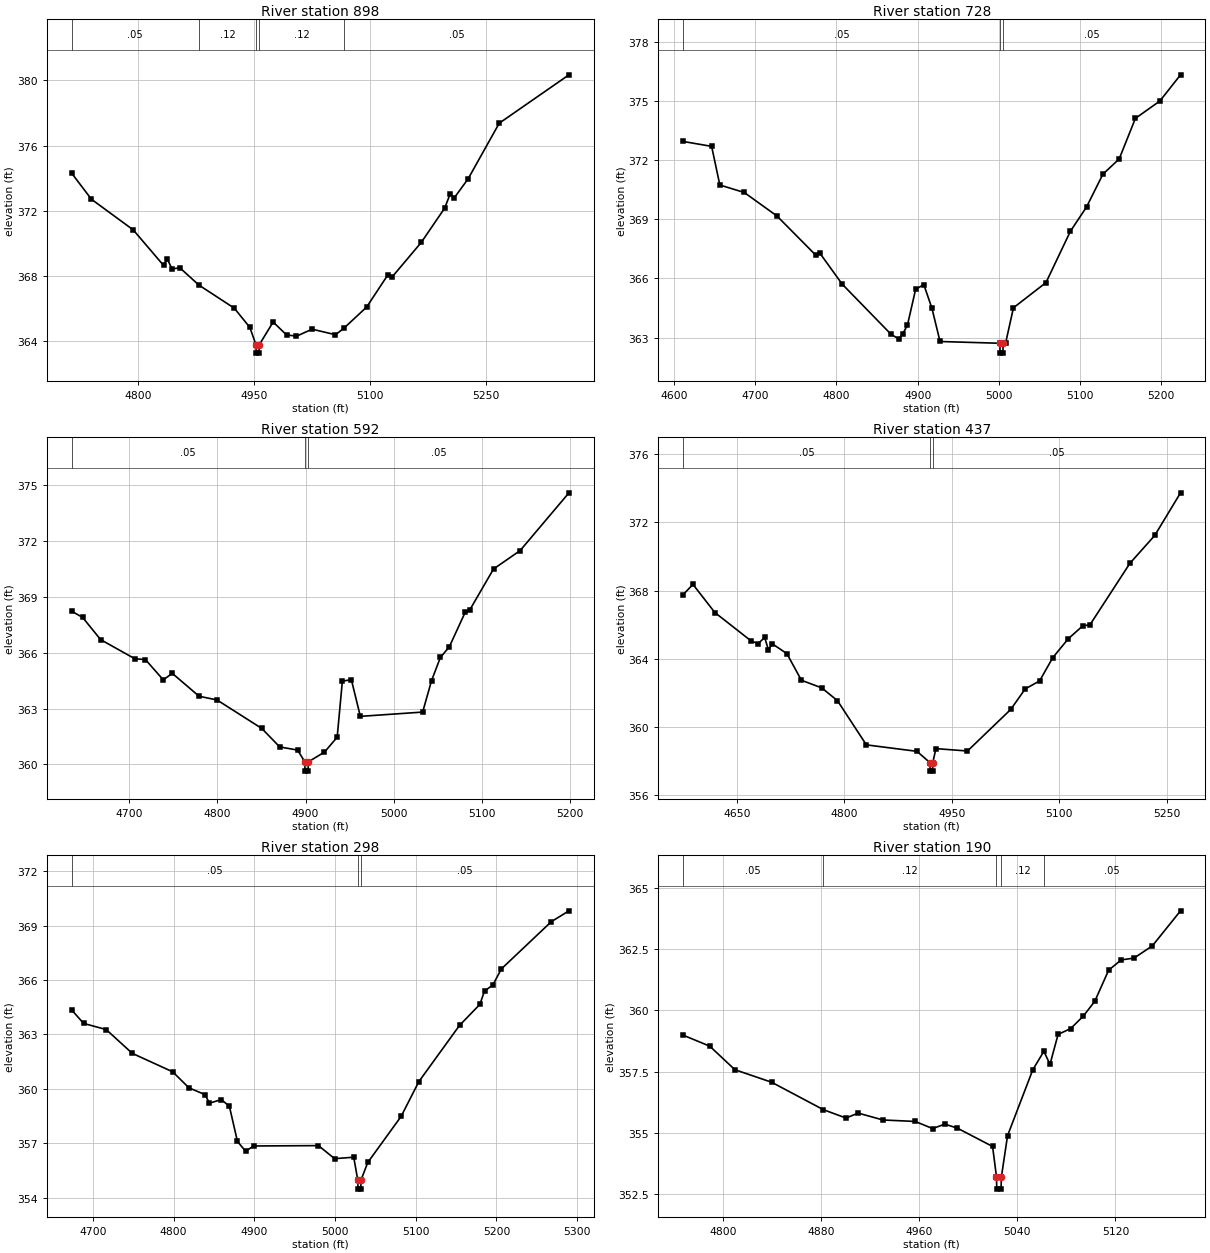
Type RM Length L Ch R = 1,898,170,170,170
BEGIN DESCRIPTION:
Lacy 195 204
END DESCRIPTION:
XS GIS Cut Line= 3
      2673903.82      6814590.22      2673874.60      6814311.64
      2673919.91      6813951.59
#Sta/Elev= 30
  4714.2  374.31  4739.9  372.70  4793.9  370.82  4833.1  368.64  4838.1  369.02
  4844.1  368.42  4854.2  368.49  4878.8  367.43  4924.6  366.01  4944.7  364.83
  4952.7  363.75  4953.0  363.25  4956.5  363.25  4956.7  363.75  4974.8  365.16
  4992.1  364.37  5005.0  364.29  5025.2  364.72  5055.4  364.38  5066.3  364.78
  5095.7  366.08  5123.3  368.07  5128.3  367.91  5166.3  370.05  5196.5  372.15
  5203.7  373.03  5208.7  372.77  5226.8  373.95  5267.1  377.37  5357.2  380.34
#Mann=5,-1,0
  4714.2    0.05       0  4878.8    0.12       0  4952.7    0.07       0
  4956.7    0.12       0  5066.3    0.05       0
Bank Sta=4952.7,4956.7
Exp/Cntr=0.3,0.1

Type RM Length L Ch R = 1,728,136,136,136
BEGIN DESCRIPTION:
Lacy 195 203
END DESCRIPTION:
XS GIS Cut Line= 3
      2674047.04      6814595.97      2674009.22      6814205.47
      2674020.60      6813985.49
#Sta/Elev= 30
  4611.2  372.95  4646.3  372.70  4656.4  370.74  4686.5  370.36  4726.7  369.17
  4774.8  367.17  4779.8  367.27  4807.1  365.71  4867.4  363.16  4876.9  362.93
  4881.9  363.20  4887.5  363.64  4897.5  365.44  4907.6  365.69  4917.6  364.49
  4927.6  362.80  5001.3  362.71  5001.5  362.21  5005.0  362.21  5005.3  362.71
  5008.3  362.71  5018.0  364.51  5058.1  365.79  5088.1  368.39  5108.1  369.63
  5128.2  371.29  5148.2  372.06  5168.2  374.12  5198.3  375.00  5223.8  376.33
#Mann=3,-1,0
  4611.2    0.05       0  5001.3    0.03       0  5005.3    0.05       0
Bank Sta=5001.3,5005.3
Exp/Cntr=0.3,0.1

Type RM Length L Ch R = 1,592,155,155,155
BEGIN DESCRIPTION:
Lacy 195 193
END DESCRIPTION:
XS GIS Cut Line= 3
      2674194.38      6814513.45      2674129.43      6814153.53
      2674109.50      6813955.86
#Sta/Elev= 30
  4634.5  368.23  4647.1  367.89  4667.5  366.70  4706.4  365.67  4718.3  365.63
  4738.6  364.54  4748.8  364.89  4779.2  363.66  4799.6  363.46  4850.4  361.93
  4870.7  360.94  4891.0  360.77  4899.2  360.14  4899.4  359.64  4902.9  359.64
  4903.2  360.14  4921.5  360.66  4935.9  361.46  4941.8  364.47  4952.0  364.55
  4962.2  362.58  5032.9  362.81  5043.0  364.50  5053.0  365.74  5063.1  366.31
  5081.2  368.17  5086.2  368.28  5113.3  370.49  5143.5  371.48  5198.9  374.58
#Mann=3,-1,0
  4634.5    0.05       0  4899.2    0.03       0  4903.2    0.05       0
Bank Sta=4899.2,4903.2
Exp/Cntr=0.3,0.1

Type RM Length L Ch R = 1,437,139,139,139
BEGIN DESCRIPTION:
Lacy 195 202
END DESCRIPTION:
XS GIS Cut Line= 3
      2674215.97      6814534.62      2674270.03      6814113.17
      2674244.30      6813845.20
#Sta/Elev= 30
  4575.1  367.76  4588.8  368.36  4619.4  366.71  4669.5  365.06  4679.6  364.88
  4688.9  365.25  4694.0  364.53  4699.7  364.87  4719.9  364.30  4740.1  362.74
  4768.6  362.29  4790.5  361.54  4830.8  358.95  4901.4  358.57  4919.5  357.91
  4919.8  357.41  4923.3  357.41  4923.5  357.91  4927.8  358.73  4971.9  358.59
  5032.3  361.03  5052.4  362.23  5072.5  362.70  5091.0  364.07  5112.7  365.18
  5132.8  365.93  5142.8  365.99  5198.6  369.60  5233.2  371.23  5269.2  373.73
#Mann=3,-1,0
  4575.1    0.05       0  4919.5    0.04       0  4923.5    0.05       0
Bank Sta=4919.5,4923.5
Exp/Cntr=0.3,0.1

Type RM Length L Ch R = 1,298,108,108,108
BEGIN DESCRIPTION:
Lacy 195 201
END DESCRIPTION:
XS GIS Cut Line= 3
      2674367.34      6814485.98      2674394.10      6814151.50
      2674322.84      6813879.84
#Sta/Elev= 30
  4673.5  364.36  4688.5  363.61  4716.5  363.27  4748.7  361.96  4798.9  360.94
  4818.9  360.06  4839.0  359.68  4844.4  359.21  4859.1  359.41  4869.1  359.04
  4879.1  357.10  4889.2  356.56  4899.2  356.85  4979.5  356.87  4999.5  356.15
  5023.2  356.23  5028.2  354.97  5028.5  354.47  5032.0  354.47  5032.2  354.97
  5040.6  355.94  5081.9  358.48  5103.9  360.40  5154.3  363.50  5179.5  364.66
  5185.3  365.40  5195.7  365.73  5206.0  366.61  5268.0  369.22  5289.9  369.82
#Mann=3,-1,0
  4673.5    0.05       0  5028.2    0.03       0  5032.2    0.05       0
Bank Sta=5028.2,5032.2
Exp/Cntr=0.3,0.1

Type RM Length L Ch R = 1,190,103,103,103
BEGIN DESCRIPTION:
Lacy 195 200
END DESCRIPTION:
XS GIS Cut Line= 3
      2674456.10      6814342.51      2674486.50      6814112.21
      2674445.42      6813944.06
#Sta/Elev= 30
  4767.7  358.99  4789.4  358.54  4809.9  357.58  4839.8  357.07  4882.0  355.95
  4900.4  355.61  4910.4  355.81  4930.6  355.53  4956.9  355.47  4971.0  355.18
  4981.0  355.36  4991.1  355.20  5019.9  354.45  5023.1  353.21  5023.3  352.71
  5026.8  352.71  5027.1  353.21  5032.1  354.89  5052.7  357.58  5061.7  358.33
  5066.7  357.80  5073.3  359.02  5083.6  359.26  5093.9  359.77  5103.2  360.37
  5114.5  361.64  5124.8  362.06  5135.1  362.13  5150.1  362.63  5173.1  364.06
#Mann=5,-1,0
  4767.7    0.05       0  4882.0    0.12       0  5023.1    0.07       0
  5027.1    0.12       0  5061.7    0.05       0
Bank Sta=5023.1,5027.1
Exp/Cntr=0.3,0.1

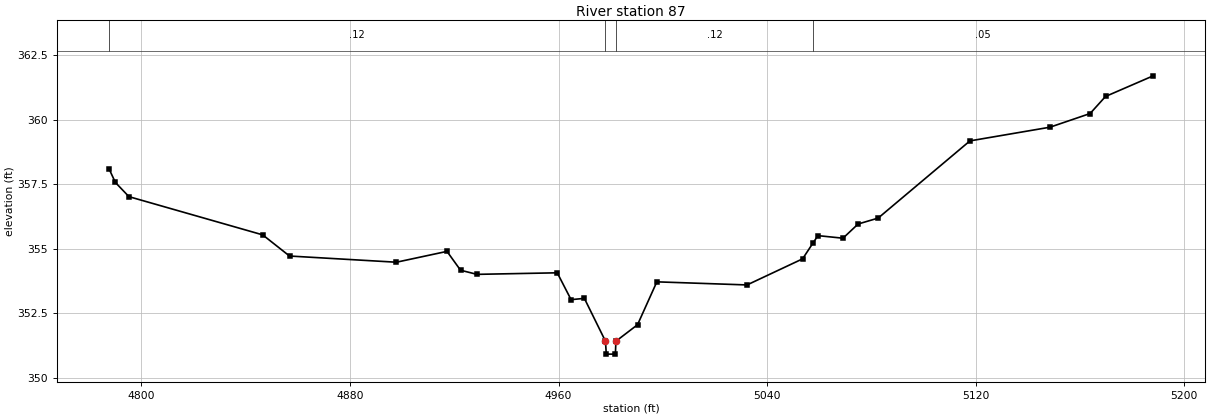
Type RM Length L Ch R = 1,87,0,0,0
BEGIN DESCRIPTION:
Lacy 195 199
END DESCRIPTION:
XS GIS Cut Line= 3
      2674540.43      6814318.32      2674589.03      6814111.56
      2674491.07      6813950.98
#Sta/Elev= 30
  4787.6  358.09  4790.0  357.57  4795.2  357.02  4846.5  355.54  4856.8  354.72
  4897.8  354.48  4917.2  354.90  4922.4  354.17  4928.7  354.01  4959.5  354.07
  4964.8  353.03  4969.9  353.08  4978.0  351.42  4978.3  350.92  4981.8  350.92
  4982.0  351.42  4990.3  352.06  4997.7  353.72  5032.3  353.60  5053.6  354.61
  5057.7  355.24  5059.5  355.51  5069.1  355.41  5074.9  355.96  5082.6  356.19
  5117.8  359.18  5148.5  359.71  5163.9  360.24  5169.8  360.90  5188.1  361.70
#Mann=4,-1,0
  4787.6    0.12       0  4978.0    0.07       0  4982.0    0.12       0
  5057.7    0.05       0
Bank Sta=4978,4982
Exp/Cntr=0.3,0.1

Chan Stop Cuts=-1