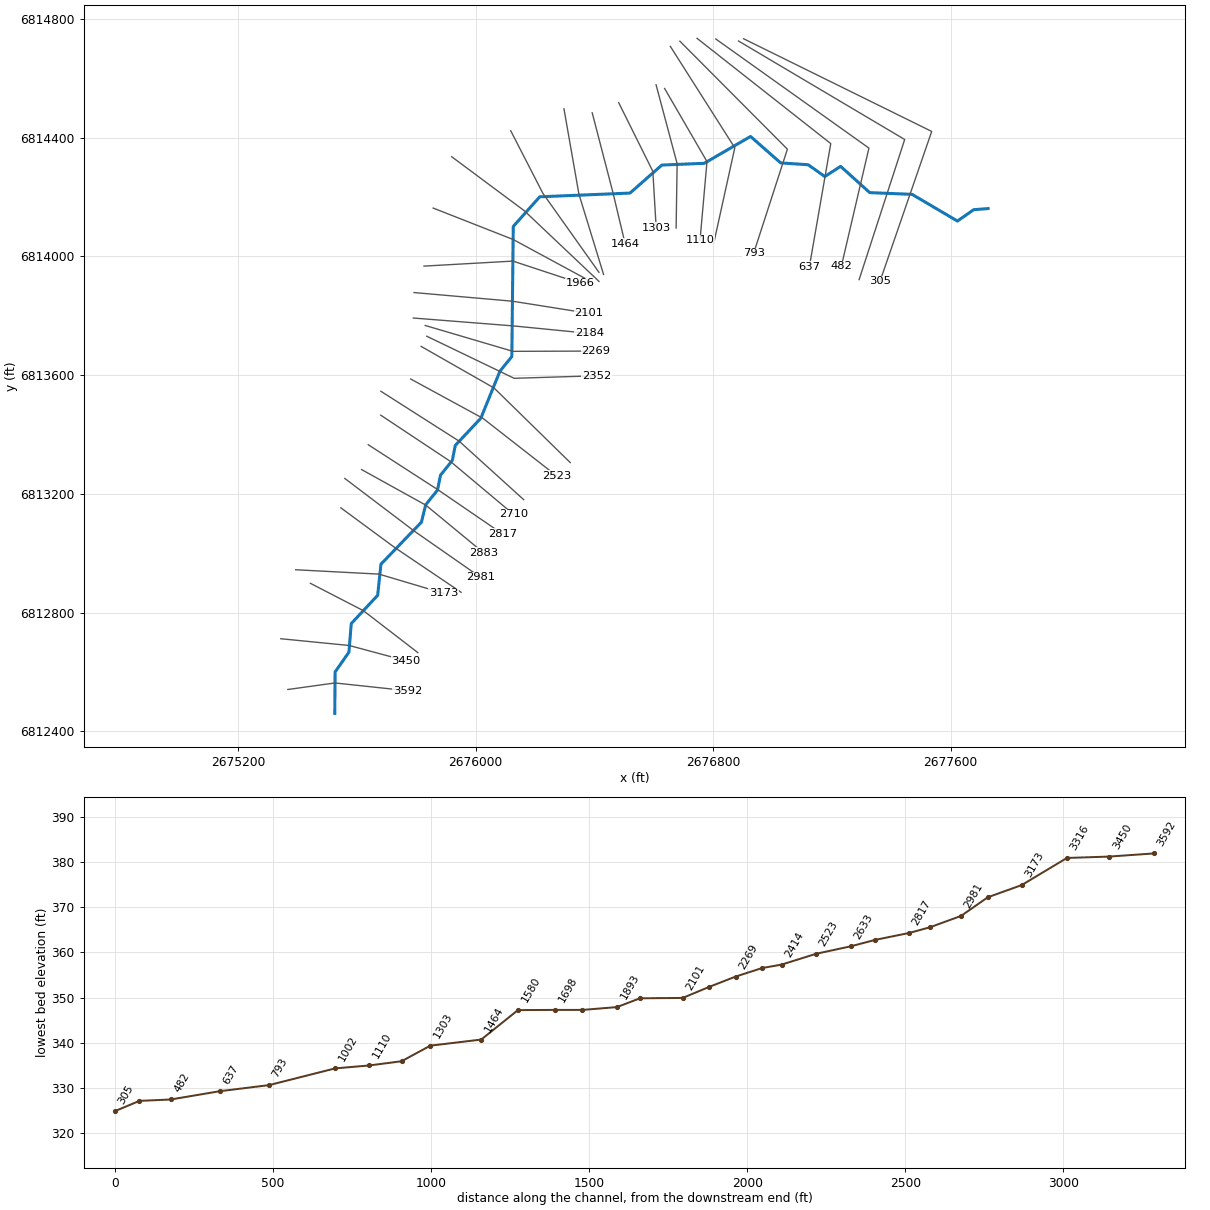
--- Lacy 196.prj (project) ---

Proj Title=Lacy 196 Base Level Engineering
Current Plan=p01
Default Exp/Contr=0.3,0.1
English Units
Geom File=g01
Flow File=f01
Plan File=p01
BEGIN DESCRIPTION:
Lacy 196
END DESCRIPTION:

--- Lacy 196.p01 (plan) ---

Plan Title=Multiple Run
Short Identifier=Multiple
Geom File=g01
Flow File=f01
Subcritical Flow
K Sum by GR= 0
Std Step Tol= 0.01
Critical Tol= 0.01
Num of Std Step Trials= 20
Max Error Tol= 0.3
Flow Tol Ratio= 0.001
Split Flow NTrial= 30
Split Flow Tol= 0.02
Split Flow Ratio= 0.02
Log Output Level= 0
Friction Slope Method= 1
Unsteady Friction Slope Method= 2
Unsteady Bridges Friction Slope Method= 1
Parabolic Critical Depth
Global Vel Dist=  1 , 1 , 1
Global Log Level= 0
CheckData=True
Encroach Param= -1, 0, 0, 0
BEGIN DESCRIPTION:
Multiple Run
END DESCRIPTION:

--- Lacy 196.f01 (steady flow) ---

Flow Title=Multiple
Number of Profiles=7
Profile Names=10-year,25-year,50-year,1pct_min,100-year,1pct_plu,500-year
River Rch & RM= Lacy 196,Reach-1,3592
     202     255     295     170     340     678     449
Boundary for River Rch & Prof#=Lacy 196,Reach-1,1
Up Type=0
Dn Type=3
Dn Slope=0.005
Boundary for River Rch & Prof#=Lacy 196,Reach-1,2
Up Type=0
Dn Type=3
Dn Slope=0.005
Boundary for River Rch & Prof#=Lacy 196,Reach-1,3
Up Type=0
Dn Type=3
Dn Slope=0.005
Boundary for River Rch & Prof#=Lacy 196,Reach-1,4
Up Type=0
Dn Type=3
Dn Slope=0.005
Boundary for River Rch & Prof#=Lacy 196,Reach-1,5
Up Type=0
Dn Type=3
Dn Slope=0.005
Boundary for River Rch & Prof#=Lacy 196,Reach-1,6
Up Type=0
Dn Type=3
Dn Slope=0.005
Boundary for River Rch & Prof#=Lacy 196,Reach-1,7
Up Type=0
Dn Type=3
Dn Slope=0.005

--- Lacy 196.g01 (geometry) ---

Geom Title=Existing Conditions

River Reach=Lacy 196,Reach-1
Reach XY= 30
      2675526.00      6812461.00      2675527.17      6812600.52
      2675573.64      6812666.98      2675581.54      6812763.42
      2675670.46      6812858.58      2675681.52      6812963.43
      2675817.86      6813104.94      2675832.10      6813163.19
      2675871.84      6813212.72      2675882.08      6813263.20
      2675921.81      6813312.74      2675931.85      6813363.29
      2676017.84      6813454.95      2676082.12      6813613.18
      2676122.25      6813662.55      2676127.04      6814100.57
      2676216.17      6814200.53      2676520.14      6814213.07
      2676627.47      6814307.44      2676770.07      6814313.25
      2676926.08      6814403.70      2677027.50      6814314.63
      2677120.11      6814308.45      2677176.10      6814268.80
      2677229.33      6814302.99      2677327.47      6814214.57
      2677470.07      6814208.75      2677622.72      6814118.85
      2677677.36      6814157.00      2677726.00      6814161.00

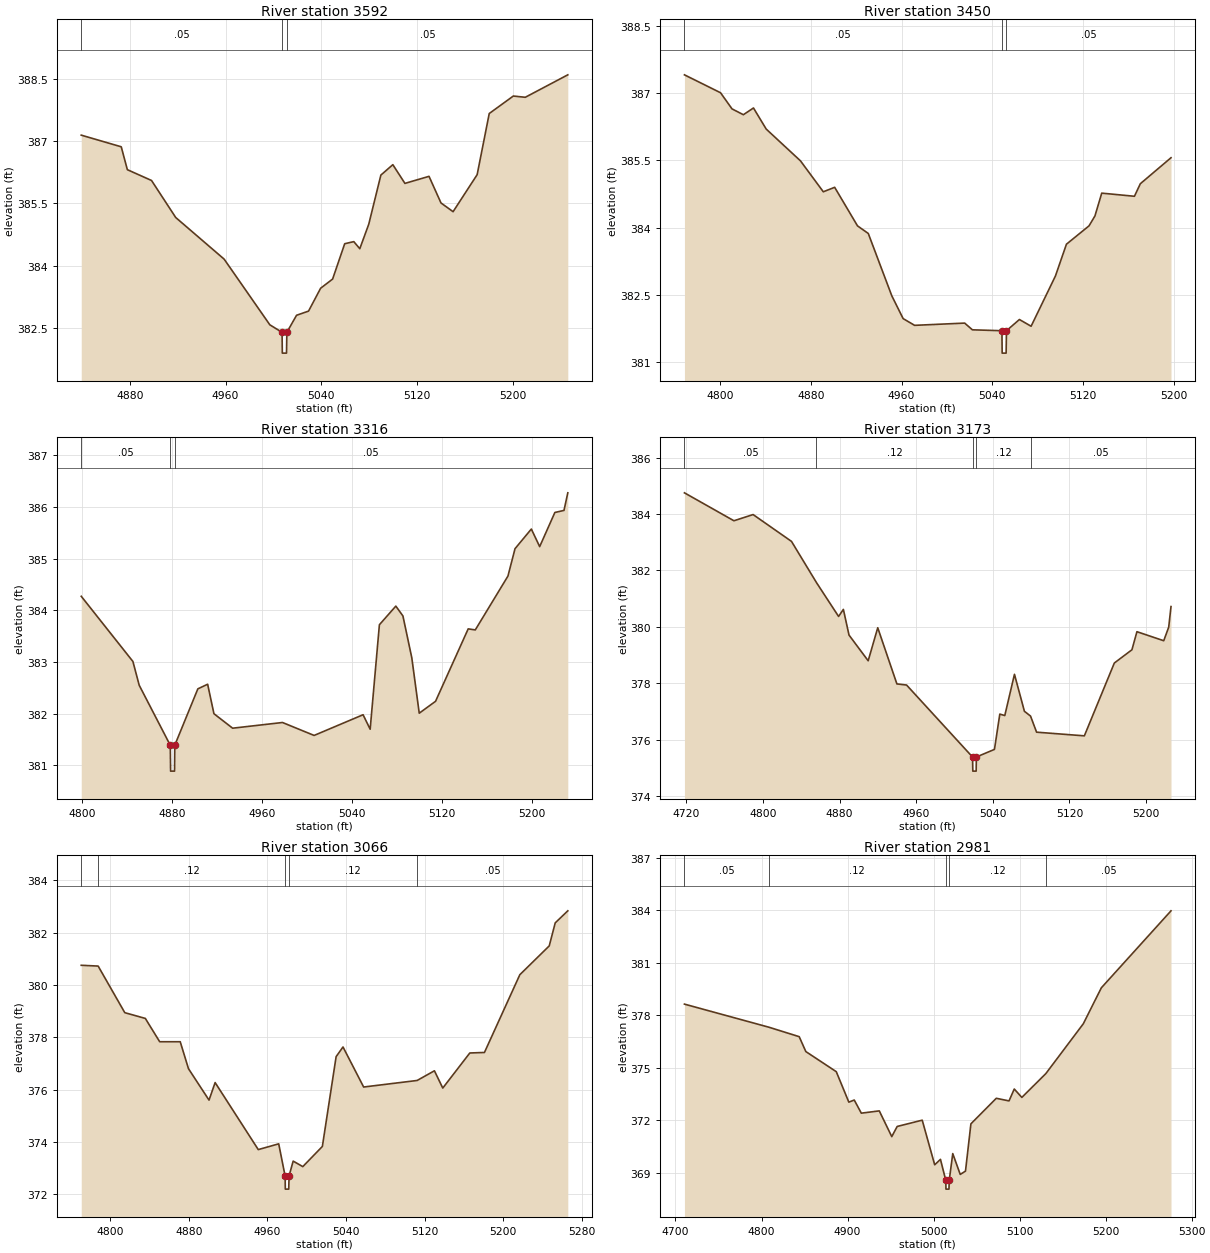
Type RM Length L Ch R = 1,3592,142,142,142
BEGIN DESCRIPTION:
Lacy 196 181
END DESCRIPTION:
XS GIS Cut Line= 3
      2675367.87      6812541.42      2675526.86      6812563.41
      2675771.26      6812537.27
#Sta/Elev= 30
  4839.5  387.14  4872.9  386.86  4878.0  386.31  4898.2  386.05  4918.4  385.16
  4958.8  384.16  4997.0  382.58  5007.2  382.40  5007.4  381.90  5010.9  381.90
  5011.2  382.40  5019.3  382.81  5029.3  382.91  5039.4  383.46  5049.4  383.68
  5059.5  384.53  5067.1  384.58  5072.1  384.41  5079.6  385.00  5089.7  386.18
  5099.7  386.43  5109.8  385.98  5129.9  386.15  5139.9  385.51  5150.0  385.30
  5170.1  386.19  5180.2  387.66  5200.3  388.08  5210.3  388.05  5245.8  388.59
#Mann=3,-1,0
  4839.5    0.05       0  5007.2    0.03       0  5011.2    0.05       0
Bank Sta=5007.2,5011.2
Exp/Cntr=0.3,0.1

Type RM Length L Ch R = 1,3450,134,134,134
BEGIN DESCRIPTION:
Lacy 196 180
END DESCRIPTION:
XS GIS Cut Line= 3
      2675344.32      6812712.35      2675574.41      6812689.62
      2675764.94      6812638.40
#Sta/Elev= 30
  4768.8  387.41  4800.6  387.01  4810.7  386.65  4820.7  386.52  4829.6  386.67
  4840.8  386.20  4871.0  385.49  4891.1  384.80  4901.1  384.90  4921.2  384.04
  4930.7  383.87  4951.4  382.48  4961.4  381.97  4971.5  381.82  5015.6  381.87
  5022.4  381.72  5048.4  381.70  5048.6  381.20  5052.1  381.20  5052.4  381.70
  5063.8  381.95  5074.1  381.80  5095.5  382.92  5105.2  383.63  5125.1  384.04
  5130.3  384.26  5136.3  384.77  5165.1  384.70  5170.3  384.98  5197.3  385.56
#Mann=3,-1,0
  4768.8    0.05       0  5048.4    0.03       0  5052.4    0.05       0
Bank Sta=5048.4,5052.4
Exp/Cntr=0.3,0.1

Type RM Length L Ch R = 1,3316,143,143,143
BEGIN DESCRIPTION:
Lacy 196 179
END DESCRIPTION:
XS GIS Cut Line= 3
      2675443.93      6812898.93      2675622.18      6812806.92
      2675805.81      6812665.61
#Sta/Elev= 30
  4799.4  384.27  4845.3  383.01  4850.9  382.55  4878.5  381.39  4878.8  380.89
  4882.3  380.89  4882.5  381.39  4903.0  382.48  4911.7  382.57  4917.3  382.00
  4933.9  381.72  4978.2  381.83  5006.3  381.58  5049.8  381.98  5056.1  381.70
  5064.3  383.72  5078.9  384.08  5085.2  383.89  5093.1  383.08  5099.7  382.01
  5114.2  382.24  5143.2  383.64  5149.5  383.62  5178.5  384.66  5184.8  385.19
  5199.3  385.57  5206.7  385.23  5220.2  385.89  5228.3  385.93  5231.7  386.27
#Mann=3,-1,0
  4799.4    0.05       0  4878.5    0.03       0  4882.5    0.05       0
Bank Sta=4878.5,4882.5
Exp/Cntr=0.3,0.1

Type RM Length L Ch R = 1,3173,107,107,107
BEGIN DESCRIPTION:
Lacy 196 165
END DESCRIPTION:
XS GIS Cut Line= 3
      2675394.35      6812944.63      2675674.77      6812929.96
      2675892.74      6812865.15
#Sta/Elev= 30
  4717.9  384.75  4769.6  383.76  4789.6  383.98  4829.7  383.03  4855.8  381.57
  4878.9  380.37  4883.9  380.62  4889.8  379.71  4909.8  378.80  4919.8  379.97
  4939.8  377.98  4949.9  377.94  5018.8  375.39  5019.1  374.89  5022.6  374.89
  5022.8  375.39  5041.7  375.66  5047.3  376.91  5052.5  376.86  5062.6  378.32
  5073.0  377.01  5079.4  376.84  5085.7  376.27  5135.6  376.14  5166.9  378.72
  5185.3  379.19  5190.5  379.83  5218.5  379.51  5223.7  379.99  5226.1  380.72
#Mann=5,-1,0
  4717.9    0.05       0  4855.8    0.12       0  5018.8    0.07       0
  5022.8    0.12       0  5079.4    0.05       0
Bank Sta=5018.8,5022.8
Exp/Cntr=0.3,0.1

Type RM Length L Ch R = 1,3066,85,85,85
BEGIN DESCRIPTION:
Lacy 196 171
END DESCRIPTION:
XS GIS Cut Line= 3
      2675546.44      6813153.13      2675727.96      6813019.43
      2675951.43      6812868.70
#Sta/Elev= 30
  4770.6  380.75  4787.8  380.72  4814.9  378.94  4835.8  378.72  4850.4  377.83
  4871.3  377.83  4879.7  376.80  4900.6  375.60  4906.8  376.27  4950.7  373.71
  4971.5  373.93  4978.0  372.70  4978.2  372.20  4981.7  372.20  4982.0  372.70
  4986.2  373.27  4996.0  373.06  5015.9  373.83  5029.9  377.26  5036.9  377.63
  5057.9  376.10  5112.3  376.35  5129.9  376.72  5138.4  376.06  5165.9  377.40
  5180.8  377.42  5216.8  380.39  5246.7  381.49  5252.8  382.37  5265.6  382.83
#Mann=5,-1,0
  4770.6    0.05       0  4787.8    0.12       0  4978.0    0.07       0
  4982.0    0.12       0  5112.3    0.05       0
Bank Sta=4978,4982
Exp/Cntr=0.3,0.1

Type RM Length L Ch R = 1,2981,98,98,98
BEGIN DESCRIPTION:
Lacy 196 173
END DESCRIPTION:
XS GIS Cut Line= 3
      2675559.69      6813252.15      2675792.90      6813075.40
      2676016.80      6812919.25
#Sta/Elev= 30
  4710.4  378.63  4808.6  377.31  4843.8  376.77  4851.5  375.92  4886.9  374.77
  4901.5  373.03  4907.8  373.15  4916.0  372.40  4936.9  372.53  4951.4  371.06
  4957.7  371.64  4986.8  372.00  5001.3  369.45  5008.0  369.76  5014.2  368.56
  5014.4  368.06  5017.9  368.06  5018.2  368.56  5022.3  370.09  5031.0  368.90
  5037.1  369.09  5043.4  371.79  5072.9  373.25  5087.7  373.10  5093.8  373.78
  5102.6  373.30  5130.5  374.66  5174.1  377.51  5195.0  379.56  5276.0  383.96
#Mann=5,-1,0
  4710.4    0.05       0  4808.6    0.12       0  5014.2    0.07       0
  5018.2    0.12       0  5130.5    0.05       0
Bank Sta=5014.2,5018.2
Exp/Cntr=0.3,0.1

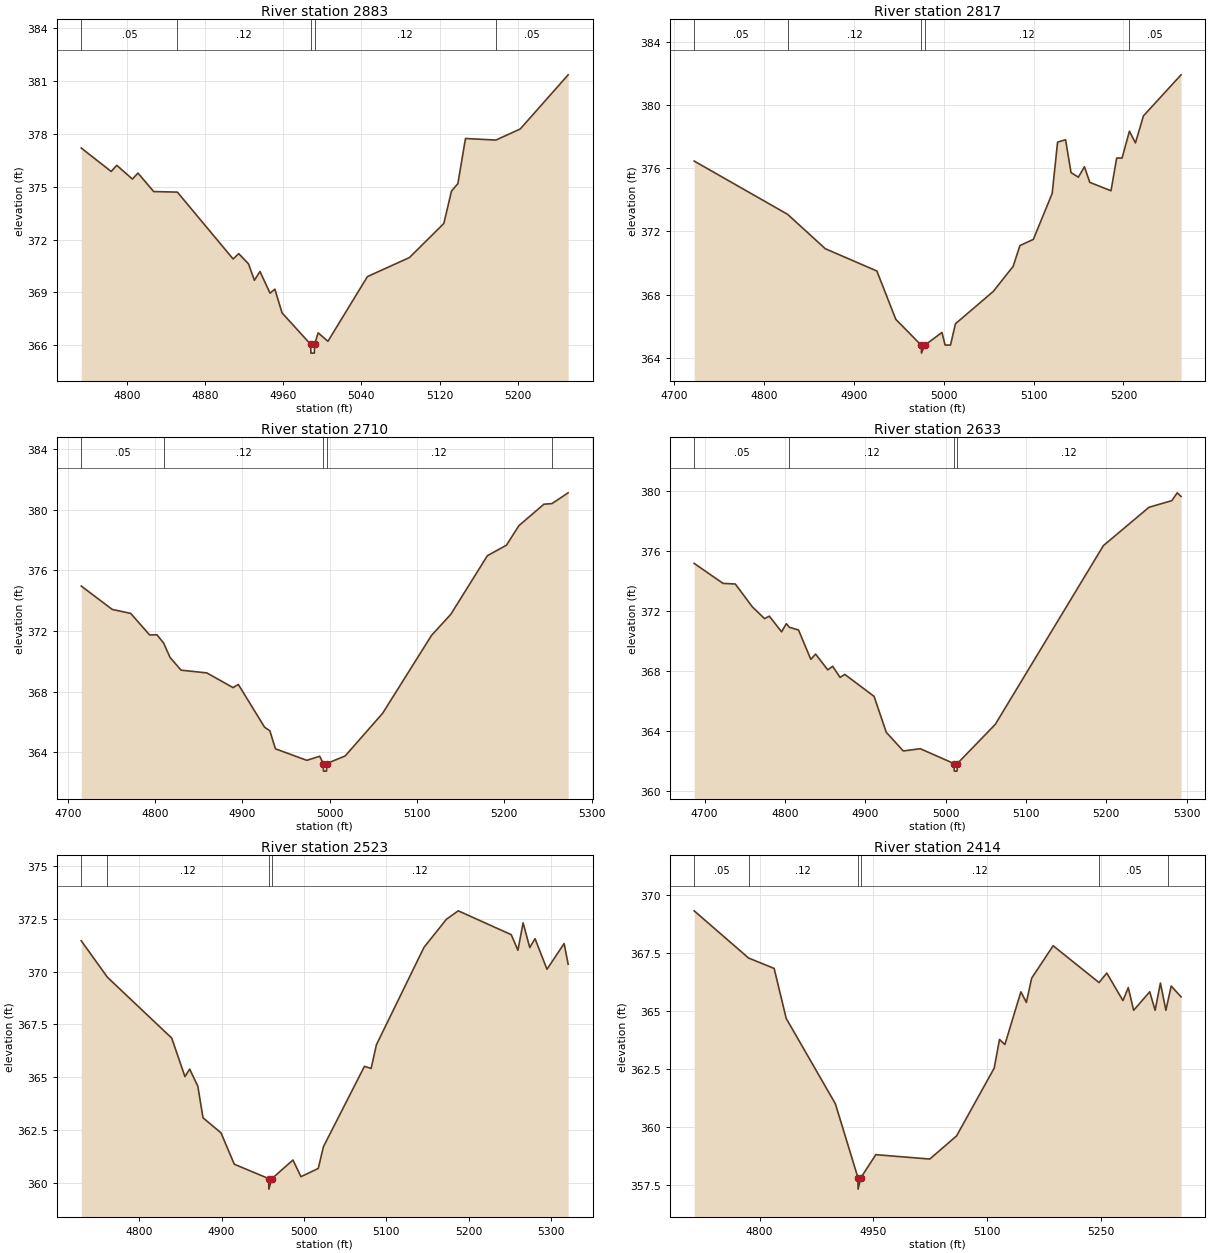
Type RM Length L Ch R = 1,2883,66,66,66
BEGIN DESCRIPTION:
Lacy 196 172
END DESCRIPTION:
XS GIS Cut Line= 3
      2675616.36      6813281.97      2675832.91      6813161.99
      2676026.04      6813002.56
#Sta/Elev= 30
  4753.5  377.19  4784.1  375.86  4789.8  376.21  4805.8  375.43  4811.5  375.77
  4827.6  374.72  4851.8  374.69  4908.8  370.90  4914.6  371.20  4924.6  370.62
  4930.6  369.69  4936.3  370.19  4946.6  368.96  4951.5  369.19  4958.9  367.84
  4988.1  366.06  4988.4  365.56  4991.9  365.56  4992.1  366.06  4995.8  366.71
  5005.8  366.23  5046.2  369.90  5089.2  370.98  5124.3  372.91  5132.2  374.75
  5138.7  375.17  5146.5  377.73  5177.6  377.64  5202.5  378.27  5251.5  381.34
#Mann=5,-1,0
  4753.5    0.05       0  4851.8    0.12       0  4988.1    0.07       0
  4992.1    0.12       0  5177.6    0.05       0
Bank Sta=4988.1,4992.1
Exp/Cntr=0.3,0.1

Type RM Length L Ch R = 1,2817,107,107,107
BEGIN DESCRIPTION:
Lacy 196 175
END DESCRIPTION:
XS GIS Cut Line= 3
      2675638.86      6813365.54      2675875.92      6813212.28
      2676090.37      6813065.61
#Sta/Elev= 30
  4722.1  376.45  4826.1  373.08  4868.1  370.90  4925.5  369.49  4946.6  366.43
  4974.9  364.79  4975.2  364.29  4978.9  364.79  4998.0  365.60  5001.5  364.80
  5007.5  364.80  5013.0  366.15  5055.0  368.19  5077.2  369.78  5084.8  371.10
  5099.7  371.49  5120.7  374.40  5126.7  377.65  5135.6  377.80  5141.7  375.72
  5149.9  375.43  5156.6  376.09  5162.6  375.10  5186.2  374.57  5192.5  376.64
  5198.5  376.64  5206.7  378.34  5213.4  377.60  5222.3  379.31  5264.2  381.91
#Mann=5,-1,0
  4722.1    0.05       0  4826.1    0.12       0  4974.9    0.07       0
  4978.9    0.12       0  5206.7    0.05       0
Bank Sta=4974.9,4978.9
Exp/Cntr=0.3,0.1

Type RM Length L Ch R = 1,2710,77,77,77
BEGIN DESCRIPTION:
Lacy 196 174
END DESCRIPTION:
XS GIS Cut Line= 3
      2675680.73      6813465.20      2675915.70      6813309.26
      2676126.88      6813132.03
#Sta/Elev= 30
  4715.4  374.96  4750.9  373.42  4772.0  373.16  4793.7  371.74  4802.1  371.75
  4809.7  371.21  4817.1  370.26  4829.7  369.42  4859.2  369.24  4889.3  368.27
  4895.3  368.48  4925.4  365.66  4931.4  365.43  4937.8  364.24  4973.8  363.48
  4988.5  363.75  4992.6  363.27  4992.8  362.77  4996.3  362.77  4996.6  363.27
  5017.7  363.77  5060.6  366.58  5116.6  371.71  5138.7  373.10  5180.6  376.96
  5202.4  377.65  5216.7  378.94  5245.3  380.35  5254.5  380.39  5273.1  381.10
#Mann=5,-1,0
  4715.4    0.05       0  4809.7    0.12       0  4992.6    0.07       0
  4996.6    0.12       0  5254.5    0.05       0
Bank Sta=4992.6,4996.6
Exp/Cntr=0.3,0.1

Type RM Length L Ch R = 1,2633,110,110,110
BEGIN DESCRIPTION:
Lacy 196 170
END DESCRIPTION:
XS GIS Cut Line= 3
      2675681.20      6813545.72      2675945.09      6813377.44
      2676162.18      6813180.63
#Sta/Elev= 30
  4687.0  375.16  4723.0  373.83  4738.2  373.79  4759.4  372.27  4774.6  371.49
  4780.6  371.65  4795.8  370.61  4801.7  371.15  4805.6  370.91  4816.9  370.73
  4832.2  368.78  4838.1  369.13  4853.3  368.08  4859.3  368.32  4868.6  367.58
  4874.5  367.78  4910.9  366.32  4926.1  363.93  4947.3  362.69  4968.4  362.84
  5010.5  361.85  5010.7  361.35  5014.2  361.35  5014.5  361.85  5061.8  364.46
  5196.3  376.34  5253.1  378.89  5281.5  379.33  5288.2  379.85  5293.0  379.61
#Mann=4,-1,0
  4687.0    0.05       0  4805.6    0.12       0  5010.5    0.07       0
  5014.5    0.12       0
Bank Sta=5010.5,5014.5
Exp/Cntr=0.3,0.1

Type RM Length L Ch R = 1,2523,109,109,109
BEGIN DESCRIPTION:
Lacy 196 169
END DESCRIPTION:
XS GIS Cut Line= 3
      2675781.70      6813586.90      2676025.01      6813454.51
      2676272.52      6813261.12
#Sta/Elev= 30
  4729.7  371.46  4761.5  369.73  4839.5  366.85  4855.6  365.02  4861.3  365.38
  4871.2  364.57  4877.5  363.07  4899.3  362.36  4915.5  360.87  4957.2  360.19
  4957.4  359.69  4961.2  360.19  4986.7  361.07  4996.4  360.28  5017.4  360.67
  5023.7  361.70  5073.5  365.51  5081.6  365.41  5088.0  366.53  5145.8  371.15
  5173.0  372.48  5187.4  372.88  5251.7  371.75  5259.8  371.01  5266.1  372.31
  5274.2  371.14  5280.6  371.56  5295.1  370.11  5315.9  371.33  5320.8  370.35
#Mann=4,-1,0
  4729.7    0.05       0  4761.5    0.12       0  4957.2    0.07       0
  4961.2    0.12       0
Bank Sta=4957.2,4961.2
Exp/Cntr=0.3,0.1

Type RM Length L Ch R = 1,2414,62,62,62
BEGIN DESCRIPTION:
Lacy 196 166
END DESCRIPTION:
XS GIS Cut Line= 3
      2675816.84      6813696.74      2676062.47      6813556.63
      2676318.91      6813305.52
#Sta/Elev= 30
  4713.7  369.33  4785.4  367.29  4819.1  366.84  4835.0  364.68  4899.8  360.99
  4929.5  357.80  4929.7  357.30  4933.5  357.80  4953.1  358.79  5024.2  358.60
  5059.5  359.60  5109.1  362.53  5116.1  363.77  5123.2  363.55  5144.3  365.83
  5151.5  365.37  5158.5  366.42  5186.8  367.82  5247.3  366.23  5257.5  366.64
  5278.8  365.45  5285.8  366.01  5292.9  365.03  5314.1  365.83  5321.2  365.03
  5328.2  366.21  5335.4  365.03  5338.1  365.44  5342.4  366.08  5355.4  365.61
#Mann=6,-1,0
  4713.7    0.05       0  4785.4    0.12       0  4929.5    0.07       0
  4933.5    0.12       0  5247.3    0.05       0  5338.1    0.12       0
Bank Sta=4929.5,4933.5
Exp/Cntr=0.3,0.1

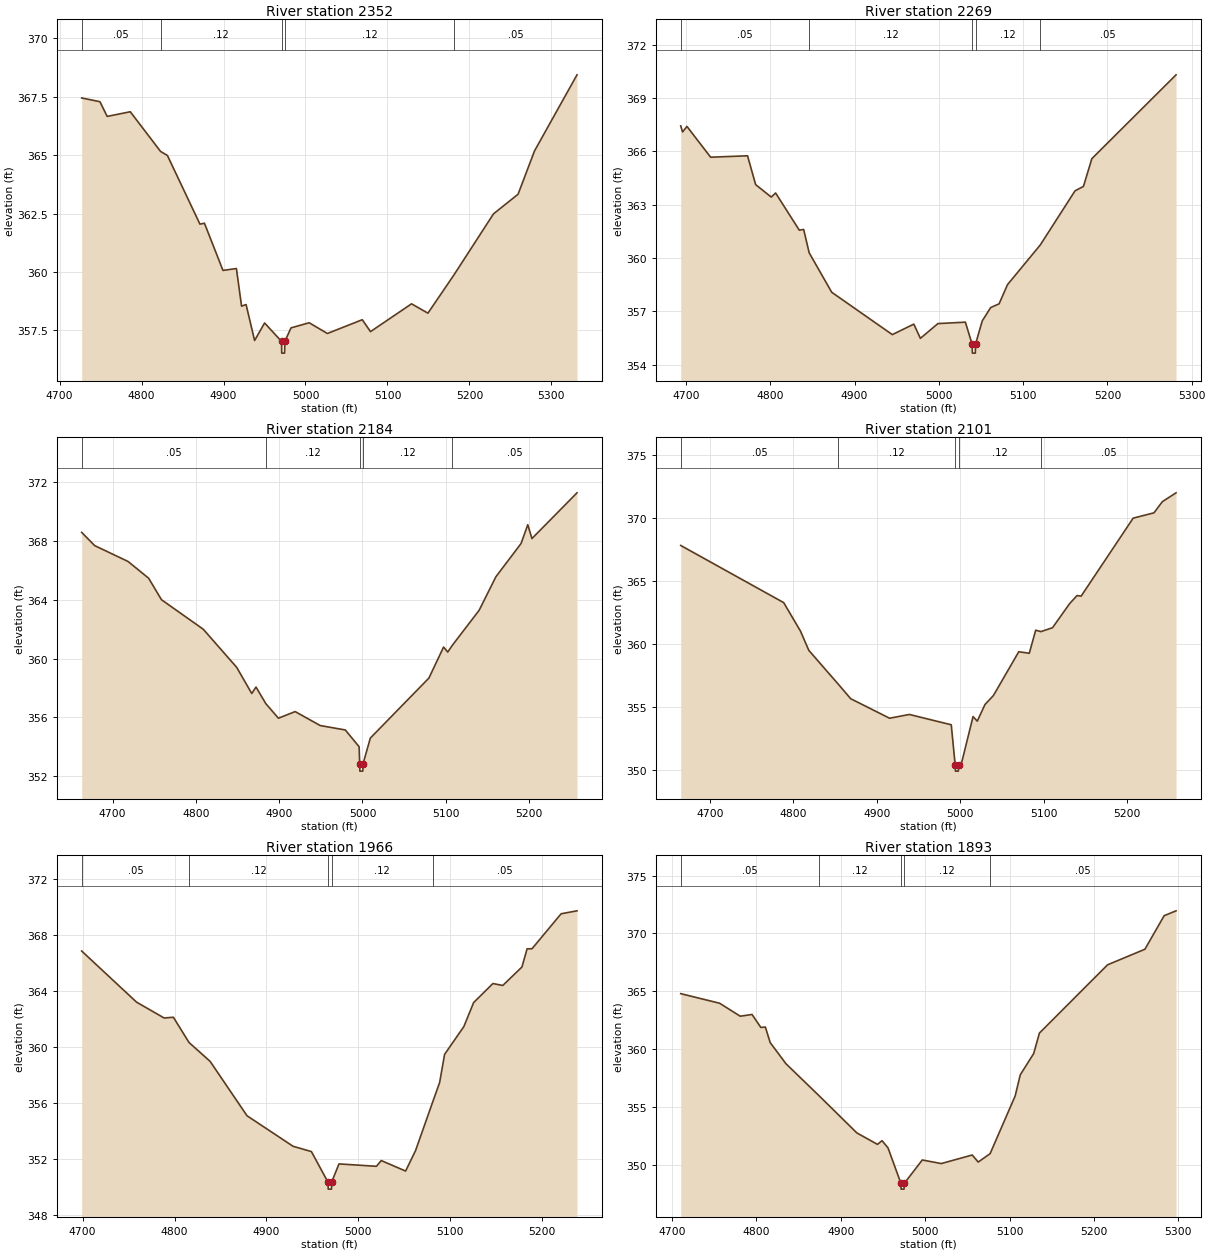
Type RM Length L Ch R = 1,2352,83,83,83
BEGIN DESCRIPTION:
Lacy 196 167
END DESCRIPTION:
XS GIS Cut Line= 3
      2675835.91      6813730.94      2676130.12      6813589.28
      2676407.85      6813597.94
#Sta/Elev= 30
  4726.9  367.45  4749.2  367.29  4758.0  366.66  4786.2  366.86  4823.2  365.16
  4831.5  364.99  4871.2  362.05  4876.7  362.09  4899.3  360.07  4915.7  360.15
  4922.0  358.54  4927.5  358.61  4937.9  357.07  4950.1  357.82  4970.8  357.03
  4971.0  356.53  4974.5  356.53  4974.8  357.03  4982.3  357.61  5004.5  357.83
  5026.7  357.37  5069.3  357.96  5079.3  357.45  5129.4  358.64  5149.4  358.24
  5181.2  359.88  5229.4  362.49  5259.4  363.33  5279.4  365.18  5331.3  368.44
#Mann=5,-1,0
  4726.9    0.05       0  4823.2    0.12       0  4970.8    0.07       0
  4974.8    0.12       0  5181.2    0.05       0
Bank Sta=4970.8,4974.8
Exp/Cntr=0.3,0.1

Type RM Length L Ch R = 1,2269,85,85,85
BEGIN DESCRIPTION:
Lacy 196 168
END DESCRIPTION:
XS GIS Cut Line= 3
      2675830.73      6813767.18      2676125.94      6813680.11
      2676405.95      6813681.02
#Sta/Elev= 30
  4693.7  367.43  4695.9  367.09  4701.1  367.40  4729.2  365.67  4773.0  365.75
  4782.6  364.13  4801.1  363.43  4806.3  363.66  4834.4  361.57  4839.6  361.61
  4846.1  360.30  4872.9  358.08  4944.8  355.70  4970.3  356.29  4978.1  355.49
  4998.9  356.32  5031.5  356.40  5039.5  355.16  5039.8  354.66  5043.3  354.66
  5043.5  355.16  5051.5  356.47  5061.5  357.22  5071.5  357.43  5081.5  358.51
  5120.4  360.74  5161.6  363.78  5171.6  364.03  5181.6  365.59  5281.5  370.30
#Mann=5,-1,0
  4693.7    0.05       0  4846.1    0.12       0  5039.5    0.07       0
  5043.5    0.12       0  5120.4    0.05       0
Bank Sta=5039.5,5043.5
Exp/Cntr=0.3,0.1

Type RM Length L Ch R = 1,2184,83,83,83
BEGIN DESCRIPTION:
Lacy 196 164
END DESCRIPTION:
XS GIS Cut Line= 3
      2675790.48      6813792.28      2676126.27      6813765.83
      2676382.89      6813740.50
#Sta/Elev= 30
  4662.9  368.58  4678.5  367.68  4718.6  366.60  4743.3  365.46  4758.7  364.00
  4808.9  361.99  4849.0  359.40  4867.1  357.62  4872.2  358.06  4884.0  356.93
  4899.1  355.94  4919.2  356.39  4949.3  355.44  4979.4  355.14  4996.0  354.00
  4996.7  352.84  4996.9  352.34  5000.4  352.34  5000.7  352.84  5009.5  354.59
  5079.8  358.67  5097.4  360.78  5102.4  360.44  5107.8  360.89  5140.1  363.28
  5160.2  365.56  5190.4  367.82  5198.5  369.10  5203.5  368.16  5257.6  371.27
#Mann=5,-1,0
  4662.9    0.05       0  4884.0    0.12       0  4996.7    0.07       0
  5000.7    0.12       0  5107.8    0.05       0
Bank Sta=4996.7,5000.7
Exp/Cntr=0.3,0.1

Type RM Length L Ch R = 1,2101,135,135,135
BEGIN DESCRIPTION:
Lacy 196 161
END DESCRIPTION:
XS GIS Cut Line= 3
      2675793.07      6813878.05      2676124.46      6813848.92
      2676382.17      6813808.00
#Sta/Elev= 30
  4665.1  367.84  4788.5  363.30  4808.6  361.04  4818.6  359.51  4854.1  356.81
  4868.8  355.67  4915.4  354.12  4939.1  354.42  4989.3  353.60  4994.0  350.42
  4994.3  349.92  4997.8  349.92  4998.0  350.42  5001.1  350.42  5015.4  354.25
  5020.5  353.89  5029.7  355.21  5039.8  355.92  5070.2  359.40  5082.8  359.28
  5090.5  361.11  5096.8  361.00  5110.7  361.31  5131.0  363.21  5140.0  363.86
  5145.0  363.82  5207.3  370.01  5232.2  370.43  5242.3  371.32  5258.7  372.02
#Mann=5,-1,0
  4665.1    0.05       0  4854.1    0.12       0  4994.0    0.07       0
  4998.0    0.12       0  5096.8    0.05       0
Bank Sta=4994,4998
Exp/Cntr=0.3,0.1

Type RM Length L Ch R = 1,1966,73,73,73
BEGIN DESCRIPTION:
Lacy 196 162
END DESCRIPTION:
XS GIS Cut Line= 3
      2675826.40      6813967.10      2676125.92      6813984.02
      2676352.87      6813909.10
#Sta/Elev= 30
  4699.0  366.84  4758.7  363.19  4788.7  362.06  4798.8  362.11  4815.8  360.31
  4838.8  358.96  4878.9  355.08  4929.0  352.90  4949.0  352.52  4967.0  350.34
  4967.3  349.84  4970.8  349.84  4971.0  350.34  4979.0  351.64  5019.7  351.47
  5025.0  351.88  5051.5  351.13  5062.3  352.59  5081.0  356.07  5088.5  357.45
  5093.9  359.46  5114.9  361.45  5125.5  363.16  5146.5  364.52  5157.2  364.38
  5178.1  365.70  5183.7  367.00  5189.0  367.00  5220.7  369.50  5238.0  369.71
#Mann=5,-1,0
  4699.0    0.05       0  4815.8    0.12       0  4967.0    0.07       0
  4971.0    0.12       0  5081.0    0.05       0
Bank Sta=4967,4971
Exp/Cntr=0.3,0.1

Type RM Length L Ch R = 1,1893,109,109,109
BEGIN DESCRIPTION:
Lacy 196 163
END DESCRIPTION:
XS GIS Cut Line= 3
      2675857.40      6814162.59      2676126.54      6814056.77
      2676388.44      6813915.22
#Sta/Elev= 30
  4710.3  364.79  4756.4  363.96  4780.8  362.84  4794.8  362.99  4805.2  361.87
  4810.6  361.90  4816.3  360.56  4835.0  358.73  4874.7  355.93  4919.0  352.75
  4943.4  351.76  4948.8  352.08  4955.9  351.46  4971.2  348.39  4971.4  347.89
  4974.9  347.89  4975.2  348.39  4996.5  350.41  5019.0  350.10  5055.7  350.84
  5062.8  350.23  5076.9  350.96  5106.6  355.95  5112.6  357.77  5128.5  359.61
  5135.3  361.38  5216.0  367.28  5260.3  368.63  5283.1  371.53  5297.2  371.95
#Mann=5,-1,0
  4710.3    0.05       0  4874.7    0.12       0  4971.2    0.07       0
  4975.2    0.12       0  5076.9    0.05       0
Bank Sta=4971.2,4975.2
Exp/Cntr=0.3,0.1

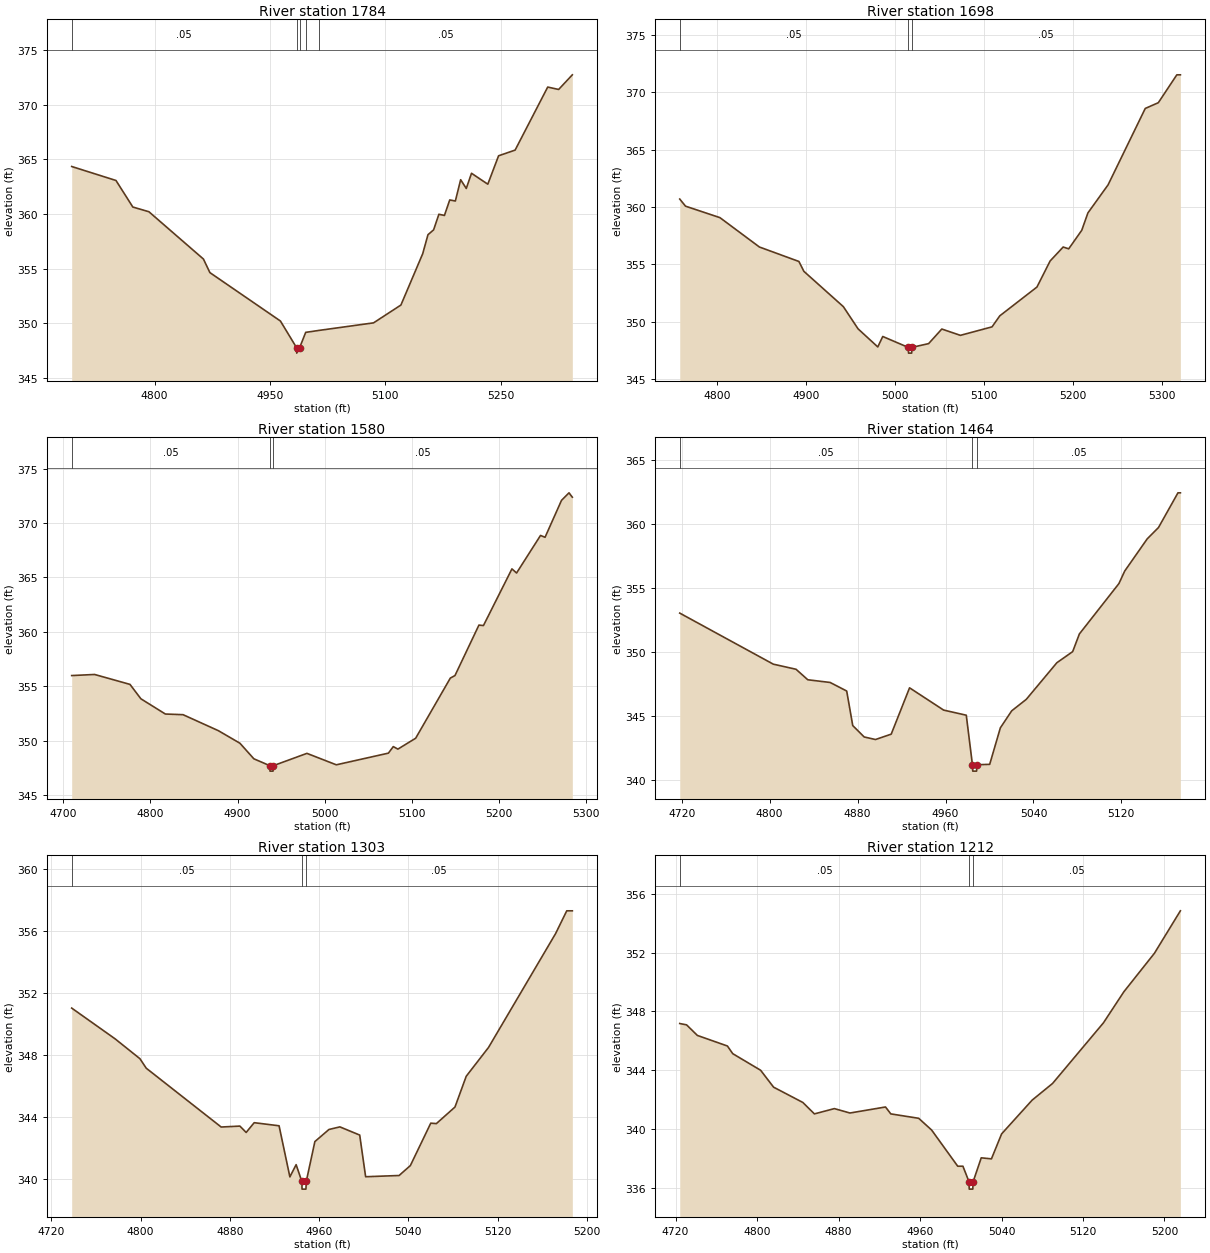
Type RM Length L Ch R = 1,1784,86,86,86
BEGIN DESCRIPTION:
Lacy 196 158
END DESCRIPTION:
XS GIS Cut Line= 3
      2675919.78      6814335.40      2676164.12      6814153.70
      2676415.79      6813915.53
#Sta/Elev= 30
  4692.3  364.35  4749.9  363.07  4771.8  360.64  4792.7  360.21  4863.6  355.88
  4872.0  354.64  4963.7  350.21  4984.7  347.77  4984.9  347.27  4988.7  347.77
  4996.6  349.17  5014.0  349.35  5084.8  350.04  5120.4  351.67  5148.7  356.36
  5155.6  358.11  5162.9  358.55  5169.8  359.98  5177.0  359.87  5183.9  361.29
  5191.2  361.19  5198.1  363.14  5205.4  362.34  5212.2  363.73  5233.4  362.73
  5247.4  365.33  5268.9  365.85  5311.3  371.62  5325.5  371.40  5343.3  372.74
#Mann=5,-1,0
  4692.3    0.05       0  4984.7    0.07       0  4988.7    0.05       0
  4996.6    0.12       0  5014.0    0.05       0
Bank Sta=4984.7,4988.7
Exp/Cntr=0.3,0.1

Type RM Length L Ch R = 1,1698,118,118,118
BEGIN DESCRIPTION:
Lacy 196 160
END DESCRIPTION:
XS GIS Cut Line= 3
      2676118.57      6814422.83      2676226.80      6814212.21
      2676415.62      6813946.21
#Sta/Elev= 30
  4757.9  360.70  4764.4  360.08  4803.1  359.08  4847.5  356.52  4891.9  355.26
  4897.5  354.40  4941.9  351.32  4958.4  349.39  4980.6  347.81  4986.2  348.72
  5014.9  347.77  5015.2  347.27  5018.7  347.27  5018.9  347.77  5037.8  348.10
  5052.6  349.37  5073.5  348.82  5109.1  349.56  5117.8  350.52  5159.6  353.03
  5174.4  355.30  5189.1  356.52  5195.3  356.36  5210.0  357.98  5216.9  359.49
  5239.6  361.94  5281.4  368.60  5296.1  369.10  5316.9  371.53  5320.9  371.53
#Mann=3,-1,0
  4757.9    0.05       0  5014.9    0.03       0  5018.9    0.05       0
Bank Sta=5014.9,5018.9
Exp/Cntr=0.3,0.1

Type RM Length L Ch R = 1,1580,116,116,116
BEGIN DESCRIPTION:
Lacy 196 159
END DESCRIPTION:
XS GIS Cut Line= 3
      2676297.76      6814496.92      2676348.14      6814209.66
      2676431.11      6813939.14
#Sta/Elev= 30
  4709.7  356.00  4736.0  356.10  4776.6  355.19  4789.1  353.87  4817.2  352.47
  4837.5  352.41  4878.1  350.94  4902.8  349.79  4918.8  348.36  4937.1  347.73
  4937.3  347.23  4940.8  347.23  4941.1  347.73  4979.7  348.86  5013.4  347.81
  5073.2  348.88  5078.8  349.48  5084.1  349.25  5104.5  350.25  5144.3  355.77
  5149.6  356.00  5177.1  360.63  5182.3  360.59  5215.0  365.79  5220.3  365.41
  5247.8  368.86  5253.0  368.69  5271.9  372.08  5280.5  372.77  5284.3  372.37
#Mann=3,-1,0
  4709.7    0.05       0  4937.1    0.03       0  4941.1    0.05       0
Bank Sta=4937.1,4941.1
Exp/Cntr=0.3,0.1

Type RM Length L Ch R = 1,1464,161,161,161
BEGIN DESCRIPTION:
Lacy 196 157
END DESCRIPTION:
XS GIS Cut Line= 3
      2676392.89      6814483.36      2676462.70      6814214.76
      2676503.97      6814041.63
#Sta/Elev= 30
  4718.2  353.06  4803.3  349.07  4824.0  348.67  4834.7  347.85  4855.0  347.64
  4870.1  346.97  4875.6  344.27  4886.0  343.38  4896.3  343.18  4910.6  343.60
  4927.3  347.22  4958.3  345.48  4978.9  345.08  4984.5  341.21  4984.8  340.71
  4988.3  340.71  4988.5  341.21  5000.2  341.24  5009.9  344.09  5020.2  345.42
  5033.5  346.32  5061.3  349.18  5075.7  350.05  5081.8  351.43  5117.8  355.37
  5123.0  356.34  5143.5  358.86  5153.8  359.75  5171.5  362.46  5173.7  362.46
#Mann=3,-1,0
  4718.2    0.05       0  4984.5    0.03       0  4988.5    0.05       0
Bank Sta=4984.5,4988.5
Exp/Cntr=0.3,0.1

Type RM Length L Ch R = 1,1303,91,91,91
BEGIN DESCRIPTION:
Lacy 196 3410
END DESCRIPTION:
XS GIS Cut Line= 3
      2676482.10      6814517.49      2676597.03      6814286.29
      2676608.31      6814096.02
#Sta/Elev= 30
  4738.2  351.05  4777.0  349.07  4799.4  347.78  4805.0  347.17  4872.2  343.37
  4889.0  343.43  4894.6  343.02  4901.8  343.65  4924.1  343.45  4933.8  340.15
  4939.4  340.94  4944.5  339.86  4944.7  339.36  4948.2  339.36  4948.5  339.86
  4956.2  342.43  4968.8  343.21  4978.6  343.38  4996.4  342.85  5001.7  340.16
  5031.7  340.24  5041.8  340.88  5060.1  343.62  5065.1  343.59  5081.8  344.66
  5091.9  346.65  5111.9  348.51  5172.0  355.86  5182.0  357.33  5187.0  357.33
#Mann=3,-1,0
  4738.2    0.05       0  4944.5    0.03       0  4948.5    0.05       0
Bank Sta=4944.5,4948.5
Exp/Cntr=0.3,0.1

Type RM Length L Ch R = 1,1212,102,102,102
BEGIN DESCRIPTION:
Lacy 196 3409
END DESCRIPTION:
XS GIS Cut Line= 3
      2676607.97      6814577.69      2676678.87      6814312.04
      2676675.48      6814095.52
#Sta/Elev= 30
  4724.1  347.18  4730.8  347.09  4741.4  346.37  4770.9  345.65  4776.1  345.13
  4803.5  344.00  4816.2  342.85  4844.9  341.81  4856.3  341.03  4875.9  341.39
  4891.2  341.09  4926.1  341.50  4931.3  341.03  4958.7  340.73  4971.4  339.93
  4997.0  337.47  5002.1  337.47  5008.1  336.41  5008.3  335.91  5011.8  335.91
  5012.1  336.41  5020.1  338.04  5030.1  337.97  5040.1  339.67  5070.1  341.97
  5090.1  343.10  5140.1  347.23  5160.1  349.34  5190.1  351.96  5215.6  354.85
#Mann=3,-1,0
  4724.1    0.05       0  5008.1    0.03       0  5012.1    0.05       0
Bank Sta=5008.1,5012.1
Exp/Cntr=0.3,0.1

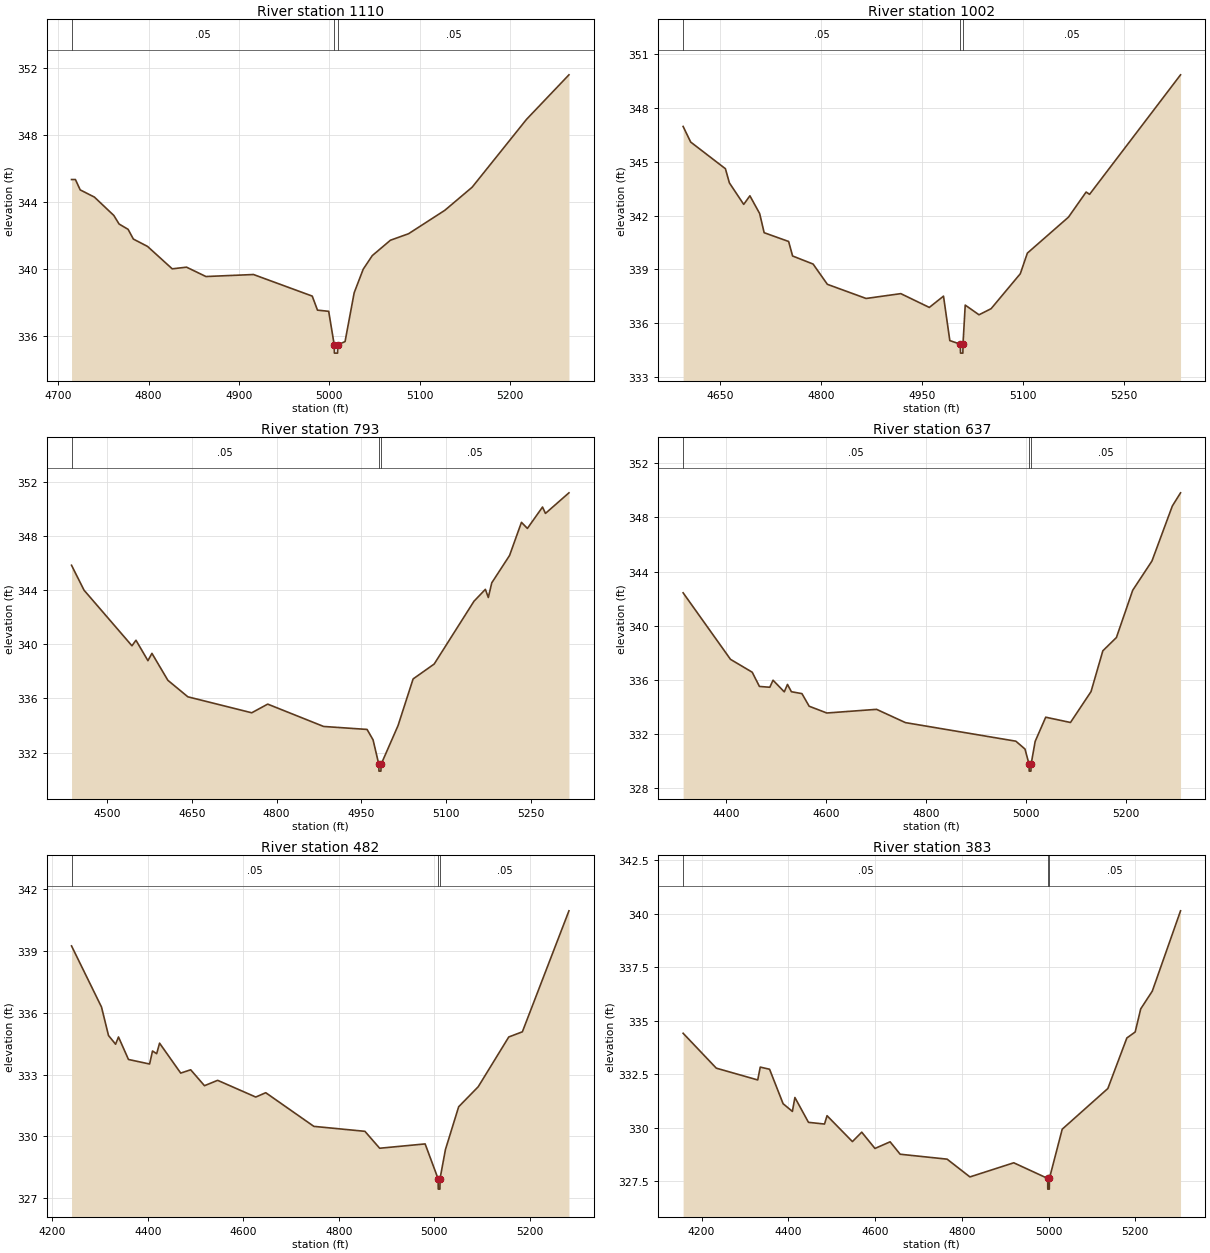
Type RM Length L Ch R = 1,1110,108,108,108
BEGIN DESCRIPTION:
Lacy 196 3411
END DESCRIPTION:
XS GIS Cut Line= 3
      2676636.72      6814565.17      2676779.43      6814319.03
      2676755.91      6814054.29
#Sta/Elev= 30
  4714.8  345.36  4719.1  345.36  4724.4  344.74  4740.1  344.31  4761.6  343.21
  4767.4  342.70  4777.4  342.38  4783.2  341.80  4798.9  341.36  4826.2  340.02
  4842.0  340.12  4863.5  339.56  4916.1  339.68  4981.1  338.39  4986.9  337.55
  4999.3  337.48  5005.4  335.48  5005.6  334.98  5009.1  334.98  5009.4  335.48
  5017.4  335.67  5027.5  338.59  5037.5  340.00  5047.5  340.81  5067.6  341.73
  5087.7  342.12  5127.8  343.52  5158.0  344.90  5218.2  348.96  5265.1  351.62
#Mann=3,-1,0
  4714.8    0.05       0  5005.4    0.03       0  5009.4    0.05       0
Bank Sta=5005.4,5009.4
Exp/Cntr=0.3,0.1

Type RM Length L Ch R = 1,1002,209,209,209
BEGIN DESCRIPTION:
Lacy 196 3414
END DESCRIPTION:
XS GIS Cut Line= 3
      2676655.98      6814707.02      2676873.02      6814365.41
      2676800.91      6814038.29
#Sta/Elev= 30
  4595.0  346.98  4606.2  346.11  4657.9  344.62  4663.8  343.83  4685.1  342.63
  4694.3  343.11  4708.8  342.12  4715.5  341.05  4751.9  340.56  4757.8  339.75
  4788.3  339.30  4809.5  338.17  4867.1  337.38  4918.7  337.65  4961.1  336.88
  4982.2  337.51  4991.6  335.03  5007.2  334.83  5007.5  334.33  5011.0  334.33
  5011.2  334.83  5014.5  337.01  5035.0  336.47  5053.0  336.81  5096.4  338.76
  5106.9  339.91  5168.1  341.92  5194.3  343.32  5199.4  343.19  5334.7  349.86
#Mann=3,-1,0
  4595.0    0.05       0  5007.2    0.03       0  5011.2    0.05       0
Bank Sta=5007.2,5011.2
Exp/Cntr=0.3,0.1

Type RM Length L Ch R = 1,793,156,156,156
BEGIN DESCRIPTION:
Lacy 196 3413
END DESCRIPTION:
XS GIS Cut Line= 3
      2676688.16      6814724.47      2677050.13      6814360.89
      2676936.73      6814010.95
#Sta/Elev= 30
  4436.9  345.84  4459.0  344.00  4543.9  339.89  4551.0  340.30  4572.2  338.79
  4579.3  339.33  4607.5  337.34  4642.9  336.12  4756.0  334.94  4784.3  335.58
  4883.3  333.93  4960.3  333.71  4970.9  332.94  4981.1  331.13  4981.3  330.63
  4984.8  330.63  4985.1  331.13  5015.1  333.99  5041.8  337.44  5079.1  338.54
  5149.6  343.18  5169.8  344.06  5175.0  343.46  5181.1  344.54  5212.6  346.56
  5233.7  349.01  5244.2  348.56  5271.0  350.14  5276.2  349.67  5317.8  351.19
#Mann=3,-1,0
  4436.9    0.05       0  4981.1    0.03       0  4985.1    0.05       0
Bank Sta=4981.1,4985.1
Exp/Cntr=0.3,0.1

Type RM Length L Ch R = 1,637,155,155,155
BEGIN DESCRIPTION:
Lacy 196 3412
END DESCRIPTION:
XS GIS Cut Line= 3
      2676745.93      6814734.12      2677196.21      6814379.66
      2677124.14      6813964.73
#Sta/Elev= 30
  4314.9  342.44  4409.6  337.53  4453.0  336.58  4467.4  335.53  4488.2  335.47
  4494.6  335.99  4517.1  335.13  4523.5  335.68  4531.3  335.14  4552.4  335.00
  4566.8  334.07  4602.1  333.57  4701.5  333.84  4759.3  332.86  4979.9  331.49
  4998.2  330.91  5006.4  329.78  5006.6  329.28  5010.1  329.28  5010.4  329.78
  5018.5  331.47  5039.6  333.26  5089.1  332.87  5130.2  335.15  5153.8  338.16
  5180.9  339.14  5213.5  342.63  5252.0  344.79  5292.6  348.84  5309.1  349.82
#Mann=3,-1,0
  4314.9    0.05       0  5006.4    0.03       0  5010.4    0.05       0
Bank Sta=5006.4,5010.4
Exp/Cntr=0.3,0.1

Type RM Length L Ch R = 1,482,99,99,99
BEGIN DESCRIPTION:
Lacy 196 3415
END DESCRIPTION:
XS GIS Cut Line= 3
      2676809.09      6814731.87      2677324.72      6814364.49
      2677231.72      6813965.92
#Sta/Elev= 30
  4239.9  339.23  4302.7  336.27  4317.4  334.89  4332.2  334.47  4338.3  334.82
  4359.2  333.73  4403.5  333.51  4409.6  334.14  4418.3  334.01  4424.4  334.52
  4468.7  333.07  4489.6  333.23  4518.5  332.46  4546.1  332.72  4626.0  331.91
  4646.9  332.12  4747.7  330.49  4854.7  330.25  4885.6  329.43  4980.9  329.64
  5008.1  327.95  5008.4  327.45  5011.9  327.45  5012.1  327.95  5023.5  329.37
  5051.2  331.44  5092.2  332.41  5156.2  334.82  5184.7  335.07  5282.3  340.93
#Mann=3,-1,0
  4239.9    0.05       0  5008.1    0.03       0  5012.1    0.05       0
Bank Sta=5008.1,5012.1
Exp/Cntr=0.3,0.1

Type RM Length L Ch R = 1,383,78,78,78
BEGIN DESCRIPTION:
Lacy 196 3416
END DESCRIPTION:
XS GIS Cut Line= 3
      2676885.50      6814725.18      2677445.14      6814393.49
      2677291.66      6813921.57
#Sta/Elev= 30
  4157.5  334.42  4234.0  332.79  4329.5  332.24  4335.3  332.84  4356.8  332.74
  4388.0  331.13  4409.4  330.77  4415.2  331.42  4446.5  330.26  4483.5  330.18
  4489.3  330.57  4547.8  329.36  4569.3  329.80  4599.8  329.04  4634.7  329.35
  4657.9  328.77  4766.1  328.54  4818.7  327.71  4919.8  328.37  4998.0  327.64
  4998.2  327.14  5001.7  327.14  5002.0  327.64  5031.5  329.94  5136.7  331.84
  5180.5  334.20  5199.7  334.48  5212.5  335.56  5239.2  336.39  5304.3  340.14
#Mann=3,-1,0
  4157.5    0.05       0  4998.0    0.03       0  5002.0    0.05       0
Bank Sta=4998,5002
Exp/Cntr=0.3,0.1

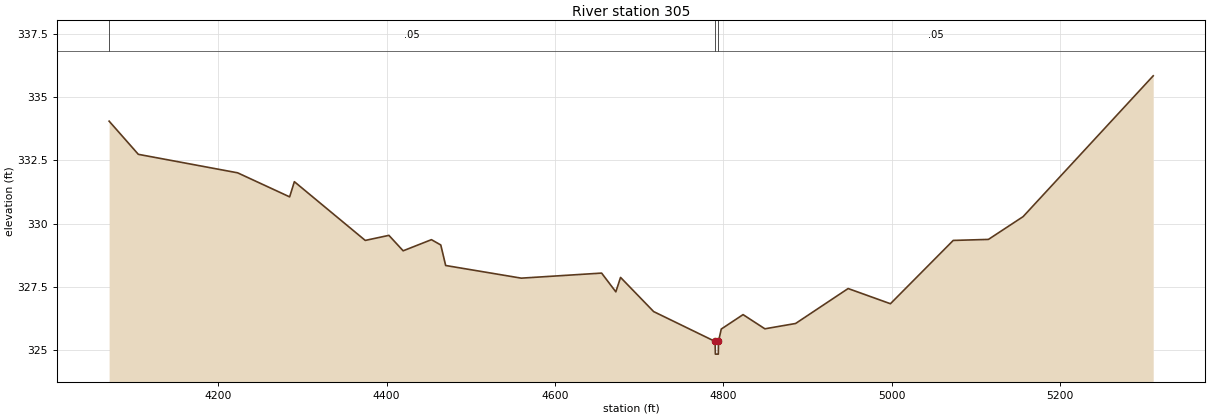
Type RM Length L Ch R = 1,305,0,0,0
BEGIN DESCRIPTION:
Lacy 196 3417
END DESCRIPTION:
XS GIS Cut Line= 3
      2676902.68      6814732.72      2677536.10      6814420.64
      2677361.99      6813915.96
#Sta/Elev= 30
  4070.5  334.05  4105.2  332.74  4223.1  332.01  4284.9  331.06  4290.5  331.66
  4374.7  329.34  4402.8  329.54  4419.7  328.93  4453.3  329.37  4464.4  329.16
  4470.2  328.35  4560.0  327.85  4655.4  328.05  4672.3  327.31  4677.9  327.88
  4717.2  326.53  4790.2  325.35  4790.5  324.85  4794.0  324.85  4794.2  325.35
  4797.5  325.84  4823.4  326.41  4849.3  325.85  4885.8  326.06  4948.2  327.44
  4998.4  326.84  5073.0  329.34  5114.8  329.38  5156.0  330.28  5310.5  335.84
#Mann=3,-1,0
  4070.5    0.05       0  4790.2    0.03       0  4794.2    0.05       0
Bank Sta=4790.2,4794.2
Exp/Cntr=0.3,0.1

Chan Stop Cuts=-1