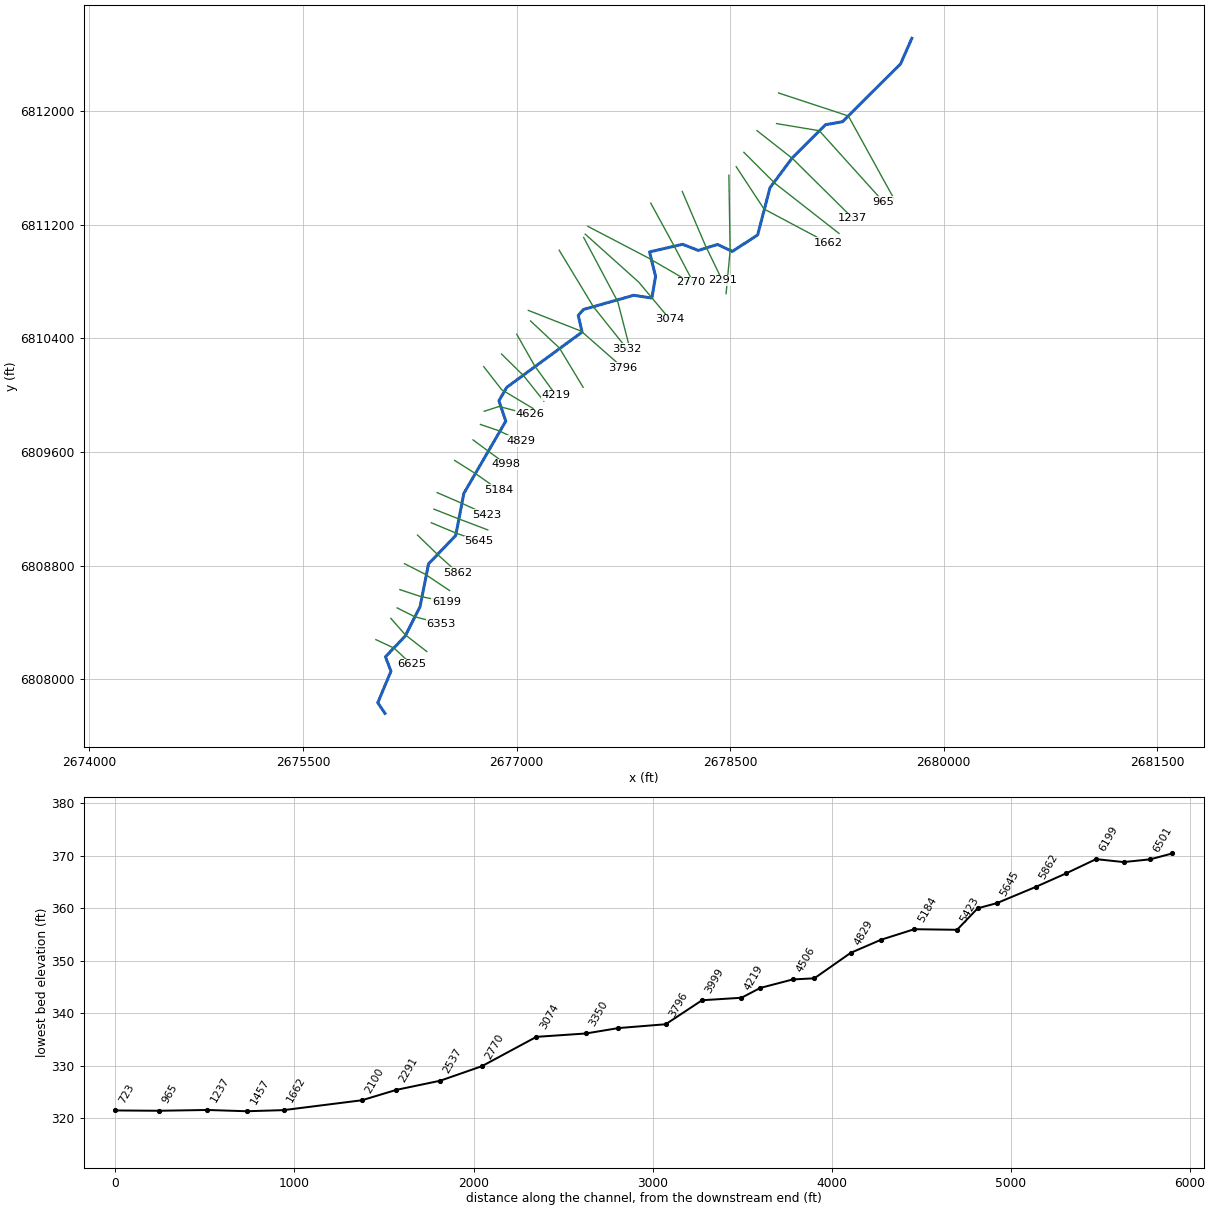
--- Lacy 197.prj (project) ---

Proj Title=Lacy 197 Base Level Engineering
Current Plan=p01
Default Exp/Contr=0.3,0.1
English Units
Geom File=g01
Flow File=f01
Plan File=p01
BEGIN DESCRIPTION:
Lacy 197
END DESCRIPTION:

--- Lacy 197.p01 (plan) ---

Plan Title=Multiple Run
Short Identifier=Multiple
Geom File=g01
Flow File=f01
Subcritical Flow
K Sum by GR= 0
Std Step Tol= 0.01
Critical Tol= 0.01
Num of Std Step Trials= 20
Max Error Tol= 0.3
Flow Tol Ratio= 0.001
Split Flow NTrial= 30
Split Flow Tol= 0.02
Split Flow Ratio= 0.02
Log Output Level= 0
Friction Slope Method= 1
Unsteady Friction Slope Method= 2
Unsteady Bridges Friction Slope Method= 1
Parabolic Critical Depth
Global Vel Dist=  1 , 1 , 1
Global Log Level= 0
CheckData=True
Encroach Param= -1, 0, 0, 0
BEGIN DESCRIPTION:
Multiple Run
END DESCRIPTION:

--- Lacy 197.f01 (steady flow) ---

Flow Title=Multiple
Number of Profiles=7
Profile Names=10-year,25-year,50-year,1pct_min,100-year,1pct_plu,500-year
River Rch & RM= Lacy 197,Reach-1,6625
     150     183     208     118     235     468     298
River Rch & RM= Lacy 197,Reach-1,4506
     454     604     724     432     862    1719    1219
River Rch & RM= Lacy 197,Reach-1,1662
     614     832    1009     609    1214    2423    1755
Boundary for River Rch & Prof#=Lacy 197,Reach-1,1
Up Type=0
Dn Type=3
Dn Slope=0.005
Boundary for River Rch & Prof#=Lacy 197,Reach-1,2
Up Type=0
Dn Type=3
Dn Slope=0.005
Boundary for River Rch & Prof#=Lacy 197,Reach-1,3
Up Type=0
Dn Type=3
Dn Slope=0.005
Boundary for River Rch & Prof#=Lacy 197,Reach-1,4
Up Type=0
Dn Type=3
Dn Slope=0.005
Boundary for River Rch & Prof#=Lacy 197,Reach-1,5
Up Type=0
Dn Type=3
Dn Slope=0.005
Boundary for River Rch & Prof#=Lacy 197,Reach-1,6
Up Type=0
Dn Type=3
Dn Slope=0.005
Boundary for River Rch & Prof#=Lacy 197,Reach-1,7
Up Type=0
Dn Type=3
Dn Slope=0.005

--- Lacy 197.g01 (geometry) ---

Geom Title=Existing Conditions

River Reach=Lacy 197,Reach-1
Reach XY= 30
      2676076.00      6807761.00      2676025.39      6807836.05
      2676117.90      6808057.71      2676079.16      6808159.35
      2676217.86      6808304.94      2676322.25      6808512.55
      2676381.84      6808813.29      2676572.52      6809012.27
      2676629.83      6809309.42      2676924.23      6809817.10
      2676876.00      6809961.00      2676931.44      6810055.49
      2677459.93      6810443.95      2677433.26      6810561.30
      2677469.30      6810602.87      2677822.71      6810702.89
      2677949.97      6810683.51      2677976.23      6810836.07
      2677933.85      6811008.06      2678165.96      6811061.76
      2678276.00      6811018.57      2678410.73      6811060.60
      2678515.38      6811011.60      2678692.92      6811127.42
      2678779.61      6811459.50      2678936.78      6811670.68
      2679169.83      6811903.14      2679289.30      6811924.40
      2679696.39      6812330.84      2679776.00      6812511.00

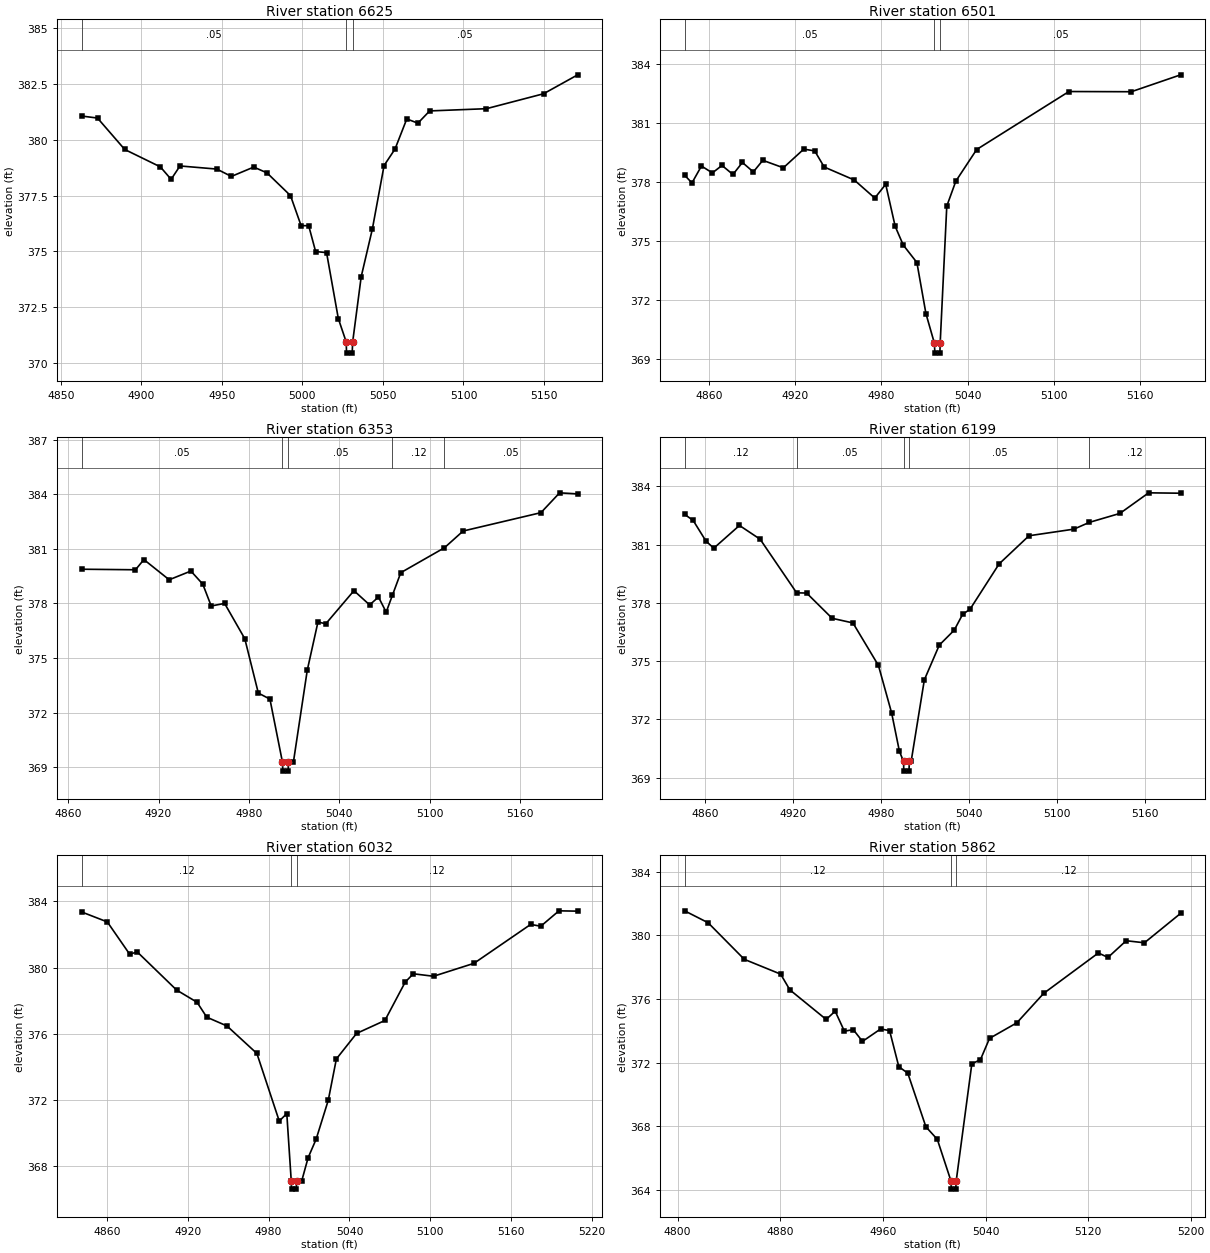
Type RM Length L Ch R = 1,6625,124,124,124
BEGIN DESCRIPTION:
Lacy 197 612
END DESCRIPTION:
XS GIS Cut Line= 3
      2676011.79      6808279.97      2676139.54      6808220.42
      2676261.49      6808106.40
#Sta/Elev= 30
  4863.0  381.07  4872.8  380.98  4889.7  379.57  4911.8  378.79  4918.5  378.23
  4924.0  378.83  4946.9  378.69  4955.9  378.36  4969.8  378.78  4978.0  378.52
  4992.6  377.50  4999.2  376.15  5003.9  376.15  5008.2  374.99  5015.0  374.94
  5022.3  371.98  5027.2  370.93  5027.4  370.43  5030.9  370.43  5031.2  370.93
  5036.5  373.86  5043.4  375.99  5050.7  378.85  5057.5  379.59  5064.8  380.94
  5071.7  380.75  5079.0  381.30  5114.2  381.40  5149.7  382.07  5170.9  382.92
#Mann=3,-1,0
  4863.0    0.05       0  5027.2    0.03       0  5031.2    0.05       0
Bank Sta=5027.2,5031.2
Exp/Cntr=0.3,0.1

Type RM Length L Ch R = 1,6501,148,148,148
BEGIN DESCRIPTION:
Lacy 197 613
END DESCRIPTION:
XS GIS Cut Line= 3
      2676117.34      6808429.46      2676218.37      6808313.92
      2676369.42      6808196.02
#Sta/Elev= 30
  4843.1  378.35  4848.2  377.96  4854.8  378.82  4862.4  378.47  4869.1  378.85
  4876.7  378.39  4883.3  379.00  4890.9  378.52  4897.5  379.11  4911.8  378.73
  4926.0  379.68  4933.6  379.59  4940.2  378.77  4961.1  378.11  4975.4  377.19
  4983.0  377.89  4989.6  375.75  4995.2  374.80  5004.7  373.91  5011.0  371.31
  5016.9  369.80  5017.2  369.30  5020.7  369.30  5020.9  369.80  5025.5  376.78
  5031.8  378.05  5046.3  379.66  5110.5  382.61  5153.9  382.60  5188.2  383.46
#Mann=3,-1,0
  4843.1    0.05       0  5016.9    0.05       0  5020.9    0.05       0
Bank Sta=5016.9,5020.9
Exp/Cntr=0.3,0.1

Type RM Length L Ch R = 1,6353,154,154,154
BEGIN DESCRIPTION:
Lacy 197 614
END DESCRIPTION:
XS GIS Cut Line= 3
      2676161.27      6808503.18      2676283.22      6808441.75
      2676469.58      6808392.13
#Sta/Elev= 30
  4869.0  379.88  4904.7  379.85  4910.3  380.41  4927.1  379.30  4941.5  379.78
  4949.4  379.06  4955.0  377.86  4963.9  378.00  4977.3  376.06  4986.3  373.07
  4994.0  372.74  5002.3  369.28  5002.6  368.78  5006.1  368.78  5006.3  369.28
  5009.6  369.28  5018.8  374.33  5025.9  376.98  5031.1  376.88  5049.8  378.70
  5060.2  377.92  5066.1  378.35  5071.2  377.52  5075.4  378.46  5080.9  379.69
  5109.9  381.06  5122.3  381.98  5174.0  382.99  5186.4  384.08  5198.4  384.02
#Mann=5,-1,0
  4869.0    0.05       0  5002.3    0.05       0  5006.3    0.05       0
  5075.4    0.12       0  5109.9    0.05       0
Bank Sta=5002.3,5006.3
Exp/Cntr=0.3,0.1

Type RM Length L Ch R = 1,6199,167,167,167
BEGIN DESCRIPTION:
Lacy 197 611
END DESCRIPTION:
XS GIS Cut Line= 3
      2676180.54      6808631.74      2676327.19      6808582.98
      2676507.41      6808547.07
#Sta/Elev= 30
  4846.1  382.56  4851.9  382.25  4860.7  381.18  4866.0  380.82  4883.5  381.99
  4897.6  381.28  4922.5  378.52  4929.3  378.51  4946.7  377.21  4960.9  376.97
  4978.3  374.78  4987.3  372.33  4992.6  370.36  4995.4  369.84  4995.6  369.34
  4999.1  369.34  4999.4  369.84  5000.6  369.84  5009.6  374.04  5019.8  375.83
  5030.0  376.60  5035.7  377.41  5040.8  377.68  5060.6  380.01  5081.0  381.46
  5111.6  381.80  5122.2  382.15  5143.0  382.61  5162.6  383.67  5184.4  383.65
#Mann=5,-1,0
  4846.1    0.12       0  4922.5    0.05       0  4995.4    0.05       0
  4999.4    0.05       0  5122.2    0.12       0
Bank Sta=4995.4,4999.4
Exp/Cntr=0.3,0.1

Type RM Length L Ch R = 1,6032,170,170,170
BEGIN DESCRIPTION:
Lacy 197 610
END DESCRIPTION:
XS GIS Cut Line= 3
      2676213.35      6808814.27      2676356.09      6808741.19
      2676528.80      6808625.74
#Sta/Elev= 30
  4841.3  383.36  4860.3  382.76  4876.9  380.81  4882.5  380.95  4911.7  378.65
  4926.9  377.91  4934.1  377.01  4949.1  376.48  4971.3  374.82  4987.9  370.74
  4993.5  371.19  4996.8  367.13  4997.0  366.63  5000.5  366.63  5000.8  367.13
  5004.6  367.13  5009.3  368.52  5015.3  369.65  5024.3  372.00  5030.3  374.49
  5045.3  376.03  5066.3  376.81  5081.4  379.13  5087.4  379.63  5102.4  379.48
  5132.4  380.26  5174.5  382.61  5182.0  382.50  5195.5  383.43  5209.4  383.41
#Mann=3,-1,0
  4841.3    0.12       0  4996.8    0.07       0  5000.8    0.12       0
Bank Sta=4996.8,5000.8
Exp/Cntr=0.3,0.1

Type RM Length L Ch R = 1,5862,217,217,217
BEGIN DESCRIPTION:
Lacy 197 607
END DESCRIPTION:
XS GIS Cut Line= 3
      2676304.52      6809015.42      2676445.74      6808878.22
      2676586.71      6808751.43
#Sta/Elev= 30
  4805.5  381.55  4823.8  380.80  4852.0  378.50  4880.3  377.57  4887.5  376.58
  4915.8  374.72  4922.8  375.24  4930.0  373.98  4936.9  374.08  4944.1  373.34
  4958.2  374.12  4965.2  374.02  4972.4  371.75  4979.4  371.34  4993.5  367.97
  5002.4  367.18  5013.1  364.55  5013.3  364.05  5016.8  364.05  5017.1  364.55
  5029.3  371.93  5036.0  372.19  5043.1  373.53  5064.4  374.51  5085.3  376.36
  5127.9  378.90  5135.4  378.62  5149.6  379.67  5163.8  379.54  5192.0  381.39
#Mann=3,-1,0
  4805.5    0.12       0  5013.1    0.07       0  5017.1    0.12       0
Bank Sta=5013.1,5017.1
Exp/Cntr=0.3,0.1

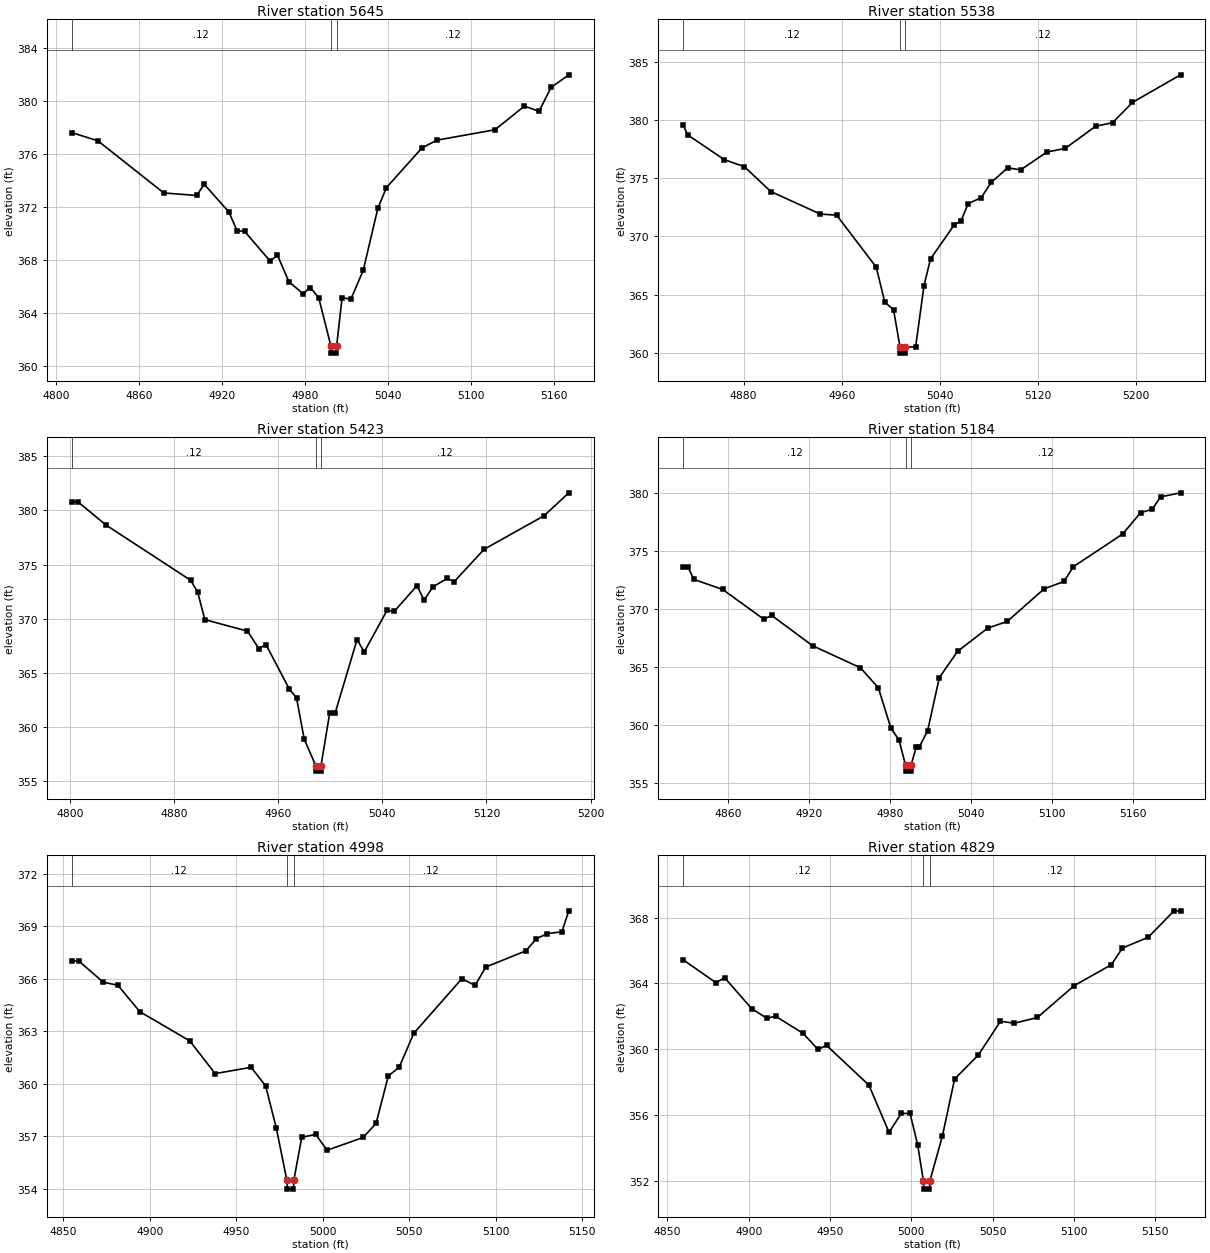
Type RM Length L Ch R = 1,5645,107,107,107
BEGIN DESCRIPTION:
Lacy 197 608
END DESCRIPTION:
XS GIS Cut Line= 3
      2676401.11      6809102.39      2676582.18      6809026.67
      2676736.30      6808972.88
#Sta/Elev= 30
  4811.2  377.60  4830.3  376.97  4877.9  373.04  4901.7  372.85  4907.1  373.70
  4924.9  371.61  4930.9  370.19  4936.3  370.15  4954.7  367.91  4960.1  368.34
  4968.3  366.35  4978.5  365.45  4983.9  365.90  4989.9  365.14  4998.8  361.46
  4999.0  360.96  5002.5  360.96  5002.8  361.46  5006.8  365.13  5013.2  365.04
  5022.1  367.21  5032.7  371.90  5038.9  373.45  5064.5  376.43  5075.3  377.02
  5117.4  377.81  5138.6  379.59  5149.2  379.20  5157.9  381.00  5170.7  381.95
#Mann=3,-1,0
  4811.2    0.12       0  4998.8    0.07       0  5002.8    0.12       0
Bank Sta=4998.8,5002.8
Exp/Cntr=0.3,0.1

Type RM Length L Ch R = 1,5538,115,115,115
BEGIN DESCRIPTION:
Lacy 197 609
END DESCRIPTION:
XS GIS Cut Line= 3
      2676419.65      6809198.02      2676573.89      6809137.32
      2676797.79      6809052.15
#Sta/Elev= 30
  4830.8  379.55  4834.3  378.73  4864.1  376.60  4880.6  375.99  4902.1  373.86
  4942.6  371.92  4955.8  371.83  4988.1  367.36  4995.0  364.37  5002.2  363.69
  5007.5  360.48  5007.8  359.98  5011.3  359.98  5011.5  360.48  5020.2  360.53
  5027.0  365.78  5032.3  368.07  5051.7  371.00  5057.1  371.33  5063.0  372.81
  5073.7  373.34  5081.8  374.64  5095.1  375.89  5105.8  375.72  5127.2  377.25
  5142.1  377.56  5166.8  379.46  5180.7  379.77  5196.9  381.51  5236.1  383.88
#Mann=3,-1,0
  4830.8    0.12       0  5007.5    0.07       0  5011.5    0.12       0
Bank Sta=5007.5,5011.5
Exp/Cntr=0.3,0.1

Type RM Length L Ch R = 1,5423,239,239,239
BEGIN DESCRIPTION:
Lacy 197 606
END DESCRIPTION:
XS GIS Cut Line= 3
      2676442.07      6809314.55      2676624.68      6809235.40
      2676791.01      6809159.38
#Sta/Elev= 30
  4801.4  380.80  4806.3  380.80  4827.9  378.65  4892.9  373.54  4898.3  372.44
  4903.8  369.90  4936.5  368.84  4945.3  367.22  4950.7  367.60  4968.7  363.47
  4974.2  362.67  4980.1  358.85  4989.0  356.39  4989.2  355.89  4992.7  355.89
  4993.0  356.39  4999.7  361.28  5003.9  361.28  5020.7  368.06  5026.2  366.91
  5043.7  370.76  5049.2  370.66  5066.7  373.04  5072.2  371.70  5078.8  372.92
  5089.8  373.71  5095.3  373.42  5118.3  376.41  5164.3  379.51  5183.3  381.63
#Mann=3,-1,0
  4801.4    0.12       0  4989.0    0.07       0  4993.0    0.12       0
Bank Sta=4989,4993
Exp/Cntr=0.3,0.1

Type RM Length L Ch R = 1,5184,186,186,186
BEGIN DESCRIPTION:
Lacy 197 605
END DESCRIPTION:
XS GIS Cut Line= 3
      2676565.05      6809540.64      2676711.19      6809448.56
      2676871.01      6809336.00
#Sta/Elev= 30
  4826.9  373.60  4830.4  373.60  4834.8  372.55  4856.0  371.69  4886.5  369.12
  4892.4  369.44  4922.6  366.83  4958.0  364.93  4971.3  363.20  4980.7  359.69
  4986.6  358.70  4991.5  356.50  4991.7  356.00  4995.2  356.00  4995.5  356.50
  4999.5  358.12  5001.8  358.12  5007.8  359.48  5016.5  364.08  5030.0  366.34
  5052.2  368.34  5066.7  368.92  5094.1  371.74  5108.9  372.38  5115.6  373.64
  5152.3  376.48  5165.5  378.31  5174.2  378.62  5180.3  379.68  5195.1  380.03
#Mann=3,-1,0
  4826.9    0.12       0  4991.5    0.07       0  4995.5    0.12       0
Bank Sta=4991.5,4995.5
Exp/Cntr=0.3,0.1

Type RM Length L Ch R = 1,4998,169,169,169
BEGIN DESCRIPTION:
Lacy 197 604
END DESCRIPTION:
XS GIS Cut Line= 3
      2676694.25      6809685.44      2676807.84      6809601.33
      2676925.97      6809514.92
#Sta/Elev= 30
  4854.7  367.02  4858.9  367.02  4873.1  365.81  4881.5  365.64  4894.2  364.13
  4923.1  362.46  4937.8  360.59  4958.6  360.95  4967.0  359.89  4973.2  357.47
  4979.3  354.49  4979.6  353.99  4983.1  353.99  4983.3  354.49  4987.9  356.95
  4996.0  357.12  5002.5  356.21  5023.4  356.94  5030.9  357.75  5038.0  360.46
  5044.2  360.94  5052.7  362.89  5080.5  366.01  5088.2  365.63  5094.4  366.68
  5117.5  367.60  5123.7  368.30  5130.0  368.59  5138.4  368.69  5142.4  369.89
#Mann=3,-1,0
  4854.7    0.12       0  4979.3    0.07       0  4983.3    0.12       0
Bank Sta=4979.3,4983.3
Exp/Cntr=0.3,0.1

Type RM Length L Ch R = 1,4829,203,203,203
BEGIN DESCRIPTION:
Lacy 197 603
END DESCRIPTION:
XS GIS Cut Line= 3
      2676746.27      6809793.94      2676875.17      6809749.99
      2677028.23      6809677.13
#Sta/Elev= 30
  4859.8  365.43  4879.9  364.04  4885.2  364.35  4901.8  362.47  4911.2  361.88
  4916.5  362.01  4933.5  360.96  4942.6  359.99  4947.9  360.23  4973.9  357.82
  4986.3  354.95  4993.8  356.10  4999.2  356.10  5003.9  354.19  5007.4  352.00
  5007.6  351.50  5011.1  351.50  5011.4  352.00  5019.1  354.73  5026.6  358.19
  5041.2  359.65  5054.8  361.70  5063.4  361.58  5077.5  361.93  5100.2  363.87
  5122.9  365.13  5129.8  366.15  5145.6  366.80  5161.5  368.41  5165.5  368.41
#Mann=3,-1,0
  4859.8    0.12       0  5007.4    0.07       0  5011.4    0.12       0
Bank Sta=5007.4,5011.4
Exp/Cntr=0.3,0.1

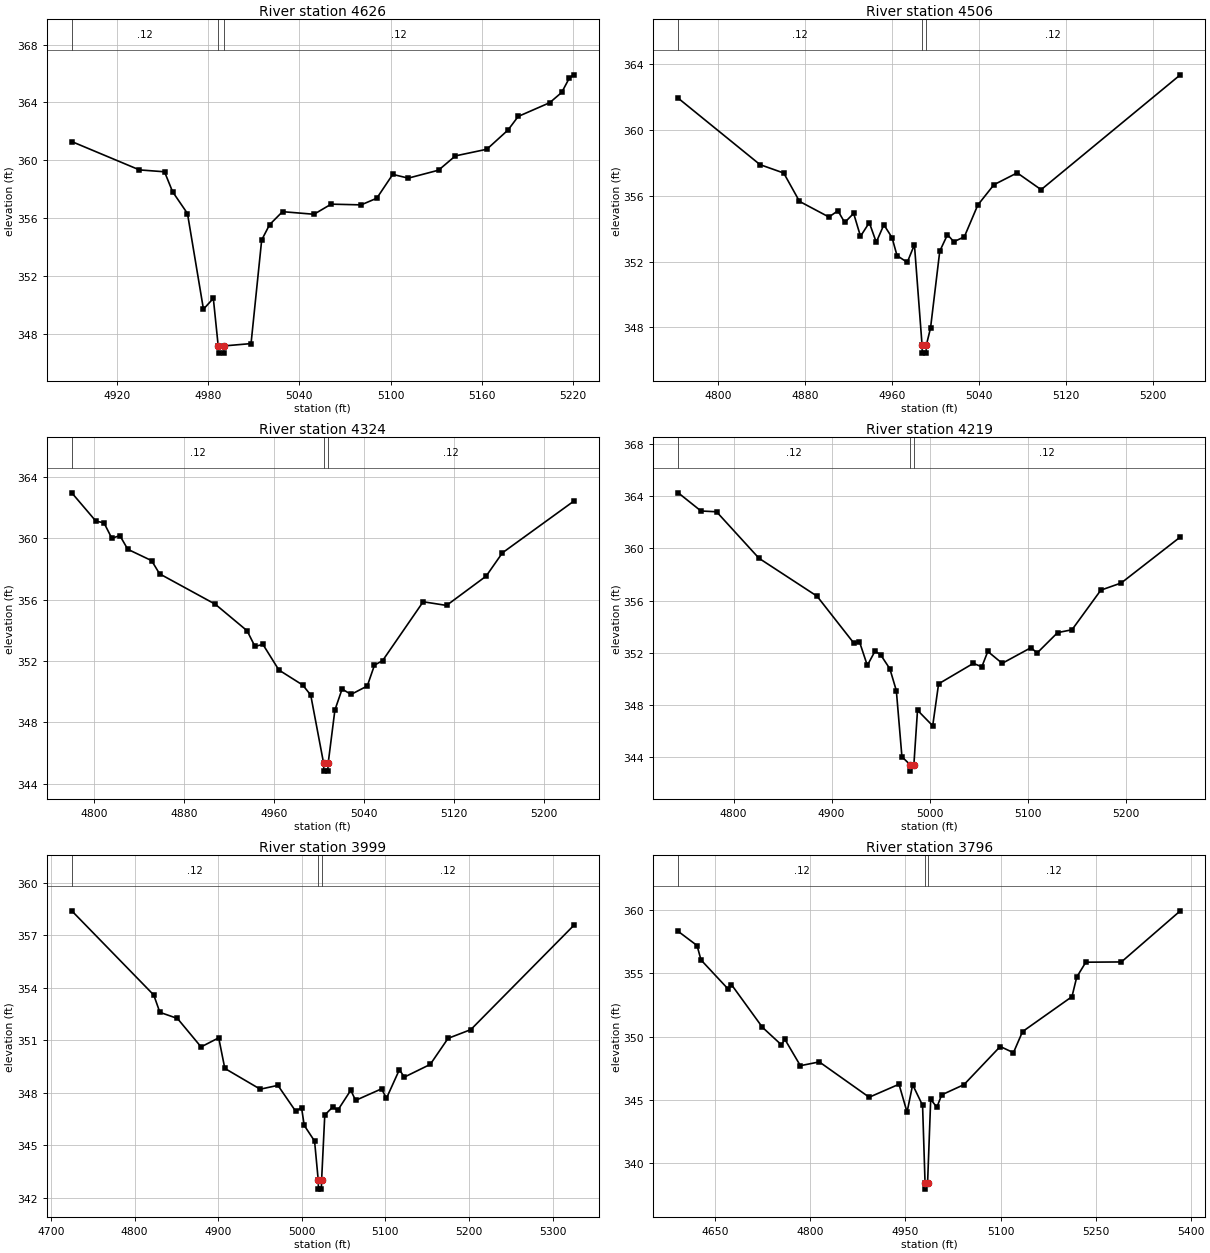
Type RM Length L Ch R = 1,4626,120,120,120
BEGIN DESCRIPTION:
Lacy 197 133
END DESCRIPTION:
XS GIS Cut Line= 3
      2676773.62      6809887.04      2676877.33      6809920.49
      2677091.39      6809864.66
#Sta/Elev= 30
  4890.3  361.29  4934.8  359.33  4951.3  359.20  4956.6  357.82  4966.4  356.31
  4976.9  349.69  4983.4  350.44  4986.6  347.15  4986.9  346.65  4990.4  346.65
  4990.6  347.15  5008.2  347.31  5015.2  354.48  5020.4  355.54  5028.9  356.44
  5049.6  356.26  5060.9  356.96  5080.6  356.91  5090.9  357.37  5101.4  359.02
  5111.6  358.76  5131.5  359.31  5142.6  360.30  5163.3  360.76  5177.2  362.09
  5183.9  363.03  5204.6  363.98  5212.5  364.69  5217.6  365.70  5220.5  365.91
#Mann=3,-1,0
  4890.3    0.12       0  4986.6    0.07       0  4990.6    0.12       0
Bank Sta=4986.6,4990.6
Exp/Cntr=0.3,0.1

Type RM Length L Ch R = 1,4506,182,182,182
BEGIN DESCRIPTION:
Lacy 197 132
END DESCRIPTION:
XS GIS Cut Line= 3
      2676769.79      6810200.38      2676895.33      6810038.64
      2677115.81      6809906.66
#Sta/Elev= 30
  4763.6  361.91  4838.8  357.88  4860.6  357.37  4875.1  355.65  4902.2  354.70
  4910.4  355.08  4916.7  354.37  4924.9  354.92  4931.2  353.53  4939.3  354.36
  4945.7  353.17  4952.7  354.23  4960.2  353.45  4964.8  352.36  4974.2  351.95
  4980.8  353.02  4987.8  346.94  4988.0  346.44  4991.5  346.44  4991.8  346.94
  4995.6  347.96  5004.1  352.63  5011.2  353.63  5017.0  353.20  5026.7  353.50
  5039.1  355.43  5053.9  356.66  5075.3  357.38  5097.3  356.36  5225.3  363.33
#Mann=3,-1,0
  4763.6    0.12       0  4987.8    0.07       0  4991.8    0.12       0
Bank Sta=4987.8,4991.8
Exp/Cntr=0.3,0.1

Type RM Length L Ch R = 1,4324,105,105,105
BEGIN DESCRIPTION:
Lacy 197 131
END DESCRIPTION:
XS GIS Cut Line= 3
      2676894.28      6810289.70      2677050.54      6810135.54
      2677191.82      6809957.87
#Sta/Elev= 30
  4780.3  362.96  4801.8  361.11  4808.9  361.01  4815.9  360.00  4823.1  360.17
  4830.1  359.28  4851.3  358.54  4858.4  357.68  4907.9  355.70  4936.2  353.97
  4943.2  352.95  4950.3  353.08  4964.5  351.41  4985.7  350.43  4992.8  349.78
  5004.3  345.32  5004.5  344.82  5008.0  344.82  5008.3  345.32  5014.3  348.80
  5020.7  350.17  5028.7  349.82  5043.1  350.37  5049.5  351.73  5056.7  352.02
  5092.8  355.86  5113.6  355.62  5148.8  357.53  5163.3  359.05  5226.8  362.42
#Mann=3,-1,0
  4780.3    0.12       0  5004.3    0.07       0  5008.3    0.12       0
Bank Sta=5004.3,5008.3
Exp/Cntr=0.3,0.1

Type RM Length L Ch R = 1,4219,220,220,220
BEGIN DESCRIPTION:
Lacy 197 601
END DESCRIPTION:
XS GIS Cut Line= 3
      2677001.14      6810428.96      2677127.31      6810205.75
      2677277.40      6809998.62
#Sta/Elev= 30
  4743.6  364.25  4766.8  362.86  4782.7  362.80  4826.0  359.24  4885.2  356.34
  4922.8  352.74  4928.5  352.85  4936.5  351.04  4944.4  352.14  4950.2  351.84
  4959.5  350.78  4966.1  349.11  4971.8  344.05  4980.0  343.45  4980.2  342.95
  4984.0  343.45  4987.7  347.61  5003.2  346.42  5009.2  349.63  5044.7  351.20
  5053.3  350.93  5059.4  352.11  5074.1  351.20  5103.5  352.40  5109.7  351.99
  5130.6  353.55  5145.3  353.77  5174.7  356.80  5195.5  357.35  5255.8  360.87
#Mann=3,-1,0
  4743.6    0.12       0  4980.0    0.07       0  4984.0    0.12       0
Bank Sta=4980,4984
Exp/Cntr=0.3,0.1

Type RM Length L Ch R = 1,3999,203,203,203
BEGIN DESCRIPTION:
Lacy 197 600
END DESCRIPTION:
XS GIS Cut Line= 3
      2677098.33      6810522.04      2677301.00      6810331.63
      2677467.66      6810055.39
#Sta/Elev= 30
  4724.8  358.41  4822.9  353.59  4830.2  352.60  4851.2  352.25  4879.5  350.62
  4900.6  351.14  4907.9  349.39  4950.3  348.20  4971.4  348.42  4992.8  346.93
  4999.7  347.15  5002.9  346.13  5015.3  345.23  5019.7  342.98  5019.9  342.48
  5023.4  342.48  5023.7  342.98  5027.5  346.72  5037.2  347.19  5043.0  346.99
  5058.6  348.14  5064.4  347.56  5095.4  348.22  5101.3  347.68  5116.8  349.32
  5122.6  348.89  5153.7  349.62  5175.0  351.11  5202.2  351.61  5325.5  357.58
#Mann=3,-1,0
  4724.8    0.12       0  5019.7    0.07       0  5023.7    0.12       0
Bank Sta=5019.7,5023.7
Exp/Cntr=0.3,0.1

Type RM Length L Ch R = 1,3796,264,264,264
BEGIN DESCRIPTION:
Lacy 197 130
END DESCRIPTION:
XS GIS Cut Line= 3
      2677082.72      6810596.56      2677453.82      6810450.60
      2677747.69      6810192.20
#Sta/Elev= 30
  4592.4  358.33  4622.0  357.21  4628.2  356.07  4670.8  353.77  4676.2  354.11
  4724.9  350.73  4754.8  349.34  4760.2  349.78  4784.6  347.69  4814.4  347.99
  4892.9  345.19  4939.8  346.22  4952.5  344.01  4961.3  346.18  4976.9  344.55
  4980.8  338.41  4981.0  337.91  4984.8  338.41  4989.7  345.02  4999.4  344.40
  5007.0  345.38  5042.1  346.19  5099.1  349.21  5119.9  348.72  5134.2  350.39
  5212.0  353.16  5219.5  354.71  5233.8  355.89  5289.8  355.91  5382.5  359.96
#Mann=3,-1,0
  4592.4    0.12       0  4980.8    0.07       0  4984.8    0.12       0
Bank Sta=4980.8,4984.8
Exp/Cntr=0.3,0.1

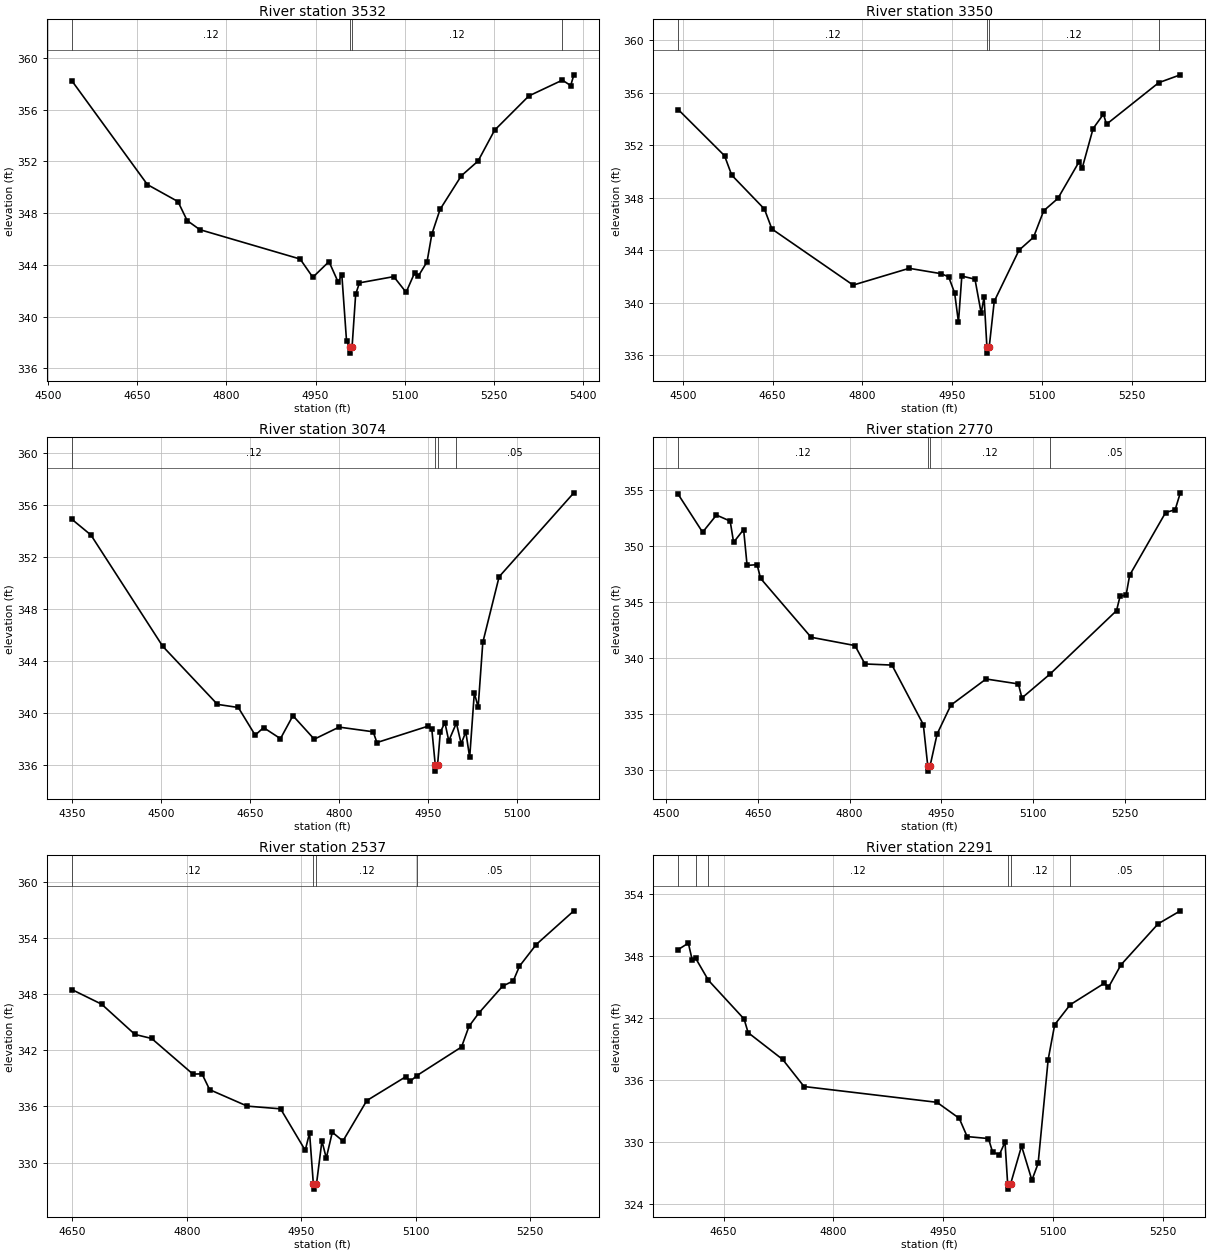
Type RM Length L Ch R = 1,3532,182,182,182
BEGIN DESCRIPTION:
Lacy 197 599
END DESCRIPTION:
XS GIS Cut Line= 3
      2677299.19      6811019.96      2677539.45      6810622.57
      2677776.70      6810324.94
#Sta/Elev= 30
  4539.7  358.23  4667.0  350.20  4718.4  348.89  4733.9  347.42  4755.2  346.72
  4924.0  344.45  4945.4  343.04  4972.6  344.25  4988.1  342.66  4994.2  343.24
  5002.1  338.14  5007.5  337.68  5007.8  337.18  5011.5  337.68  5017.5  341.73
  5023.9  342.61  5081.6  343.09  5102.4  341.88  5116.8  343.39  5123.2  343.15
  5137.6  344.23  5145.7  346.37  5159.5  348.28  5195.3  350.88  5223.5  352.02
  5251.3  354.40  5309.0  357.05  5365.4  358.27  5379.4  357.85  5384.7  358.68
#Mann=4,-1,0
  4539.7    0.12       0  5007.5    0.07       0  5011.5    0.12       0
  5365.4    0.05       0
Bank Sta=5007.5,5011.5
Exp/Cntr=0.3,0.1

Type RM Length L Ch R = 1,3350,276,276,276
BEGIN DESCRIPTION:
Lacy 197 598
END DESCRIPTION:
XS GIS Cut Line= 3
      2677471.49      6811109.39      2677710.72      6810657.49
      2677792.64      6810339.80
#Sta/Elev= 30
  4492.1  354.73  4569.5  351.21  4581.5  349.73  4636.2  347.14  4648.7  345.62
  4784.5  341.34  4878.2  342.62  4931.6  342.21  4944.2  341.97  4954.2  340.74
  4960.6  338.51  4966.2  342.03  4988.2  341.79  4998.6  339.20  5003.4  340.43
  5008.1  336.65  5008.4  336.15  5012.1  336.65  5020.4  340.10  5061.8  344.00
  5086.1  344.99  5103.1  347.01  5126.8  347.95  5162.3  350.75  5167.5  350.27
  5185.7  353.28  5203.0  354.38  5208.1  353.61  5295.4  356.78  5331.5  357.38
#Mann=4,-1,0
  4492.1    0.12       0  5008.1    0.07       0  5012.1    0.12       0
  5295.4    0.05       0
Bank Sta=5008.1,5012.1
Exp/Cntr=0.3,0.1

Type RM Length L Ch R = 1,3074,304,304,304
BEGIN DESCRIPTION:
Lacy 197 597
END DESCRIPTION:
XS GIS Cut Line= 3
      2677481.99      6811133.03      2677857.66      6810795.77
      2678076.10      6810534.51
#Sta/Elev= 30
  4350.0  354.91  4382.3  353.69  4503.2  345.12  4595.3  340.65  4630.4  340.41
  4658.8  338.28  4673.0  338.86  4701.4  338.01  4722.4  339.78  4758.3  337.97
  4800.1  338.90  4857.5  338.54  4863.8  337.71  4949.7  338.97  4956.2  338.76
  4962.0  336.01  4962.3  335.51  4966.0  336.01  4970.5  338.50  4978.3  339.25
  4984.8  337.84  4997.6  339.21  5005.7  337.62  5013.5  338.53  5020.0  336.56
  5027.8  341.53  5034.3  340.44  5042.1  345.42  5069.6  350.48  5195.4  356.94
#Mann=4,-1,0
  4350.0    0.12       0  4962.0    0.03       0  4966.0    0.12       0
  4997.6    0.05       0
Bank Sta=4962,4966
Exp/Cntr=0.3,0.1

Type RM Length L Ch R = 1,2770,233,233,233
BEGIN DESCRIPTION:
Lacy 197 596
END DESCRIPTION:
XS GIS Cut Line= 3
      2677500.66      6811187.98      2677924.52      6810966.08
      2678221.28      6810793.54
#Sta/Elev= 30
  4519.6  354.59  4559.5  351.22  4582.1  352.75  4604.6  352.21  4610.2  350.32
  4626.6  351.46  4632.3  348.26  4648.7  348.33  4654.3  347.11  4737.0  341.86
  4808.8  341.12  4825.2  339.48  4869.4  339.38  4920.7  334.08  4927.9  330.43
  4928.2  329.93  4931.9  330.43  4943.3  333.24  4965.8  335.81  5023.4  338.14
  5076.3  337.70  5082.1  336.45  5128.3  338.59  5236.9  344.23  5242.7  345.51
  5252.6  345.63  5258.4  347.39  5317.2  352.97  5332.9  353.23  5341.3  354.73
#Mann=4,-1,0
  4519.6    0.12       0  4927.9    0.07       0  4931.9    0.12       0
  5128.3    0.05       0
Bank Sta=4927.9,4931.9
Exp/Cntr=0.3,0.1

Type RM Length L Ch R = 1,2537,246,246,246
BEGIN DESCRIPTION:
Lacy 197 594
END DESCRIPTION:
XS GIS Cut Line= 3
      2677942.56      6811350.92      2678110.30      6811042.87
      2678252.99      6810770.66
#Sta/Elev= 30
  4649.1  348.49  4688.3  346.92  4731.9  343.69  4753.8  343.26  4807.9  339.45
  4819.8  339.48  4829.8  337.79  4879.1  336.03  4922.8  335.74  4955.1  331.31
  4960.8  333.16  4965.8  327.66  4966.1  327.16  4969.8  327.66  4977.0  332.31
  4982.7  330.48  4990.6  333.24  5004.5  332.30  5035.8  336.62  5087.1  339.18
  5092.7  338.67  5101.0  339.27  5160.0  342.35  5169.7  344.55  5182.6  345.97
  5213.8  348.85  5227.8  349.41  5235.9  350.98  5257.9  353.30  5307.2  356.90
#Mann=4,-1,0
  4649.1    0.12       0  4965.8    0.07       0  4969.8    0.12       0
  5101.0    0.05       0
Bank Sta=4965.8,4969.8
Exp/Cntr=0.3,0.1

Type RM Length L Ch R = 1,2291,191,191,191
BEGIN DESCRIPTION:
Lacy 197 595
END DESCRIPTION:
XS GIS Cut Line= 3
      2678163.49      6811433.72      2678326.22      6811052.79
      2678444.06      6810808.56
#Sta/Elev= 30
  4588.1  348.62  4601.9  349.24  4607.3  347.57  4612.0  347.76  4629.3  345.64
  4678.0  341.89  4683.5  340.57  4730.7  337.97  4759.8  335.35  4941.3  333.82
  4971.7  332.27  4982.5  330.50  5011.6  330.31  5017.2  329.01  5026.5  328.74
  5034.2  329.97  5037.8  325.91  5038.0  325.41  5041.8  325.91  5056.8  329.58
  5070.9  326.28  5079.4  327.90  5093.1  337.96  5102.0  341.34  5123.1  343.27
  5169.9  345.36  5175.4  344.96  5192.5  347.14  5243.2  351.11  5273.5  352.37
#Mann=6,-1,0
  4588.1    0.12       0  4612.0    0.05       0  4629.3    0.12       0
  5037.8    0.07       0  5041.8    0.12       0  5123.1    0.05       0
Bank Sta=5037.8,5041.8
Exp/Cntr=0.3,0.1

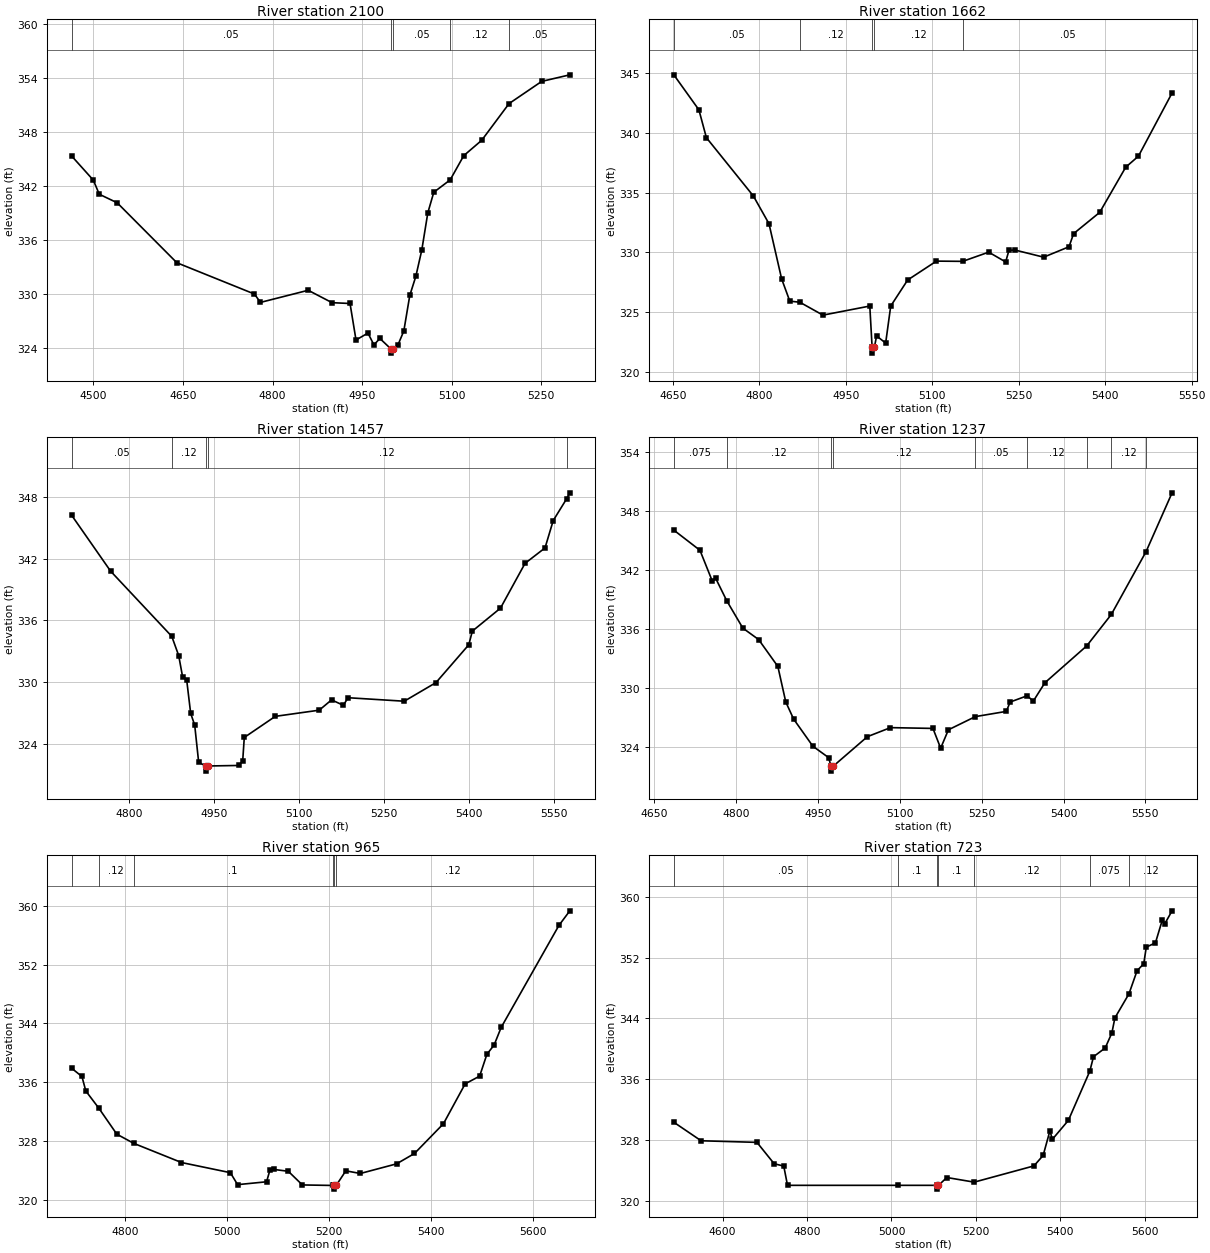
Type RM Length L Ch R = 1,2100,438,438,438
BEGIN DESCRIPTION:
Lacy 197 589
END DESCRIPTION:
XS GIS Cut Line= 3
      2678491.09      6811547.39      2678499.75      6811017.63
      2678471.32      6810714.09
#Sta/Elev= 30
  4463.3  345.37  4499.7  342.68  4509.7  341.11  4539.7  340.16  4639.7  333.49
  4769.7  330.01  4779.7  329.08  4859.7  330.43  4899.7  329.05  4929.8  328.96
  4939.8  324.90  4959.8  325.67  4969.8  324.36  4979.8  325.07  4997.8  323.94
  4998.0  323.44  5001.8  323.94  5009.8  324.31  5019.9  325.90  5029.9  329.86
  5040.0  331.97  5050.0  334.90  5060.1  339.04  5070.1  341.33  5097.6  342.71
  5120.3  345.40  5150.4  347.11  5196.2  351.19  5250.9  353.66  5298.0  354.39
#Mann=5,-1,0
  4463.3    0.05       0  4997.8    0.03       0  5001.8    0.05       0
  5097.6    0.12       0  5196.2    0.05       0
Bank Sta=4997.8,5001.8
Exp/Cntr=0.3,0.1

Type RM Length L Ch R = 1,1662,205,205,205
BEGIN DESCRIPTION:
Lacy 197 590
END DESCRIPTION:
XS GIS Cut Line= 3
      2678542.69      6811607.38      2678737.41      6811310.30
      2679186.73      6811070.74
#Sta/Elev= 30
  4651.6  344.85  4695.1  341.92  4708.1  339.59  4789.6  334.71  4816.7  332.39
  4838.6  327.78  4852.8  325.91  4870.2  325.82  4910.3  324.74  4991.6  325.50
  4995.6  322.06  4995.8  321.56  4999.6  322.06  5003.4  323.00  5019.1  322.40
  5027.9  325.50  5057.3  327.68  5107.2  329.26  5152.8  329.24  5197.9  330.01
  5227.3  329.19  5233.0  330.16  5243.2  330.19  5293.2  329.59  5337.2  330.46
  5345.2  331.56  5390.5  333.34  5435.6  337.12  5457.6  338.04  5516.0  343.33
#Mann=5,-1,0
  4651.6    0.05       0  4870.2    0.12       0  4995.6    0.07       0
  4999.6    0.12       0  5152.8    0.05       0
Bank Sta=4995.6,4999.6
Exp/Cntr=0.3,0.1

Type RM Length L Ch R = 1,1457,220,220,220
BEGIN DESCRIPTION:
Lacy 197 588
END DESCRIPTION:
XS GIS Cut Line= 3
      2678596.39      6811708.94      2678812.83      6811492.05
      2679264.59      6811138.29
#Sta/Elev= 30
  4698.1  346.21  4767.1  340.77  4875.1  334.44  4887.3  332.58  4894.3  330.49
  4901.4  330.23  4908.5  326.96  4915.6  325.82  4922.6  322.22  4934.8  321.85
  4935.0  321.35  4938.8  321.85  4993.3  321.90  5000.4  322.34  5003.2  324.62
  5058.0  326.67  5135.6  327.27  5157.4  328.27  5178.3  327.74  5186.4  328.48
  5285.8  328.14  5341.9  329.95  5399.8  333.62  5406.1  334.95  5455.8  337.18
  5499.2  341.53  5534.5  343.03  5549.0  345.69  5572.9  347.82  5578.3  348.38
#Mann=5,-1,0
  4698.1    0.05       0  4875.1    0.12       0  4934.8    0.07       0
  4938.8    0.12       0  5572.9    0.05       0
Bank Sta=4934.8,4938.8
Exp/Cntr=0.3,0.1

Type RM Length L Ch R = 1,1237,272,272,272
BEGIN DESCRIPTION:
Lacy 197 125
END DESCRIPTION:
XS GIS Cut Line= 3
      2678688.33      6811861.63      2678936.70      6811666.16
      2679360.55      6811245.96
#Sta/Elev= 30
  4686.0  346.08  4733.9  344.03  4756.4  340.91  4762.8  341.17  4783.1  338.89
  4812.5  336.12  4841.4  334.96  4876.6  332.23  4891.1  328.62  4905.5  326.88
  4940.8  324.12  4969.7  322.96  4974.0  322.09  4974.3  321.59  4978.0  322.09
  5040.6  325.09  5083.0  326.01  5160.8  325.93  5174.9  323.92  5189.1  325.79
  5238.5  327.13  5295.2  327.66  5302.2  328.61  5333.5  329.25  5344.6  328.70
  5365.9  330.57  5442.4  334.31  5487.6  337.51  5551.3  343.90  5598.9  349.87
#Mann=9,-1,0
  4686.0   0.075       0  4783.1    0.12       0  4974.0    0.07       0
  4978.0    0.12       0  5238.5    0.05       0  5333.5    0.12       0
  5442.4    0.05       0  5487.6    0.12       0  5551.3    0.05       0
Bank Sta=4974,4978
Exp/Cntr=0.3,0.1

Type RM Length L Ch R = 1,965,242,242,242
BEGIN DESCRIPTION:
Lacy 197 57
END DESCRIPTION:
XS GIS Cut Line= 3
      2678825.96      6811911.01      2679126.00      6811861.00
      2679576.03      6811360.97
#Sta/Elev= 30
  4694.7  337.90  4715.0  336.77  4722.6  334.80  4748.1  332.46  4783.4  328.92
  4816.6  327.67  4910.2  325.06  5006.0  323.68  5020.2  322.05  5077.0  322.44
  5083.7  324.05  5091.2  324.12  5119.6  323.87  5147.2  322.01  5206.7  321.94
  5209.5  321.94  5209.8  321.44  5213.5  321.94  5232.4  323.93  5260.9  323.57
  5331.9  324.88  5367.0  326.29  5423.8  330.34  5466.4  335.77  5494.8  336.82
  5509.0  339.79  5523.2  341.06  5537.0  343.45  5650.3  357.34  5671.6  359.32
#Mann=6,-1,0
  4694.7    0.05       0  4748.1    0.12       0  4816.6     0.1       0
  5206.7    0.12       0  5209.5    0.07       0  5213.5    0.12       0
Bank Sta=5209.5,5213.5
Exp/Cntr=0.3,0.1

Type RM Length L Ch R = 1,723,0,0,0
BEGIN DESCRIPTION:
Lacy 197 591
END DESCRIPTION:
XS GIS Cut Line= 3
      2678840.12      6812126.45      2679329.87      6811964.91
      2679650.36      6811382.23
#Sta/Elev= 30
  4484.3  330.31  4549.0  327.87  4681.3  327.66  4722.1  324.84  4744.8  324.54
  4753.7  322.00  5014.4  322.00  5107.5  322.00  5107.7  321.50  5111.5  322.00
  5131.3  323.03  5196.1  322.42  5337.7  324.56  5359.5  325.94  5375.6  329.19
  5381.3  328.06  5419.2  330.55  5470.1  337.04  5478.8  338.94  5506.6  340.10
  5522.4  342.08  5529.5  344.05  5562.9  347.23  5582.1  350.27  5597.9  351.19
  5603.9  353.38  5625.6  353.94  5641.7  356.91  5647.4  356.42  5665.0  358.16
#Mann=7,-1,0
  4484.3    0.05       0  5014.4     0.1       0  5107.5    0.03       0
  5111.5     0.1       0  5196.1    0.12       0  5470.1   0.075       0
  5562.9    0.12       0
Bank Sta=5107.5,5111.5
Exp/Cntr=0.3,0.1

Chan Stop Cuts=-1