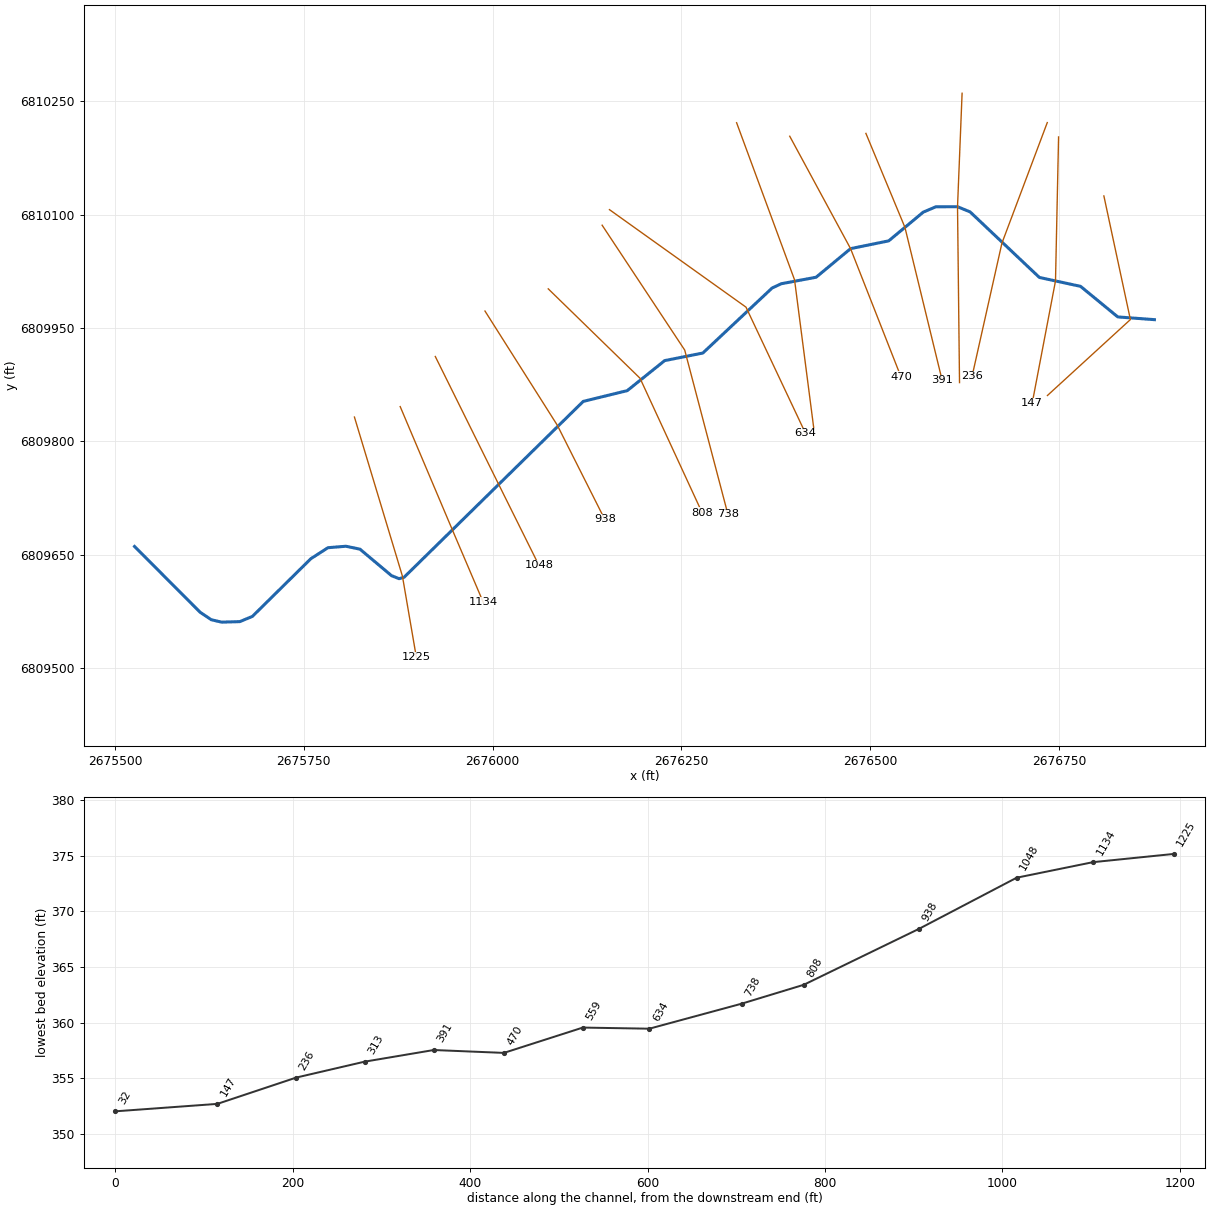
--- Lacy 198.prj (project) ---

Proj Title=Lacy 198 Base Level Engineering
Current Plan=p01
Default Exp/Contr=0.3,0.1
English Units
Geom File=g01
Flow File=f01
Plan File=p01
Y Axis Title=Elevation
X Axis Title(PF)=Main Channel Distance
X Axis Title(XS)=Station
BEGIN DESCRIPTION:
Lacy 198
END DESCRIPTION:
DSS Export Rating Curves= 0
DSS Export Rating Curve Sorted= 0
DSS Export Volume Flow Curves= 0
DXF OffsetX= 0
DXF OffsetY= 0
DXF ScaleX= 1
DXF ScaleY= 10

--- Lacy 198.p01 (plan) ---

Plan Title=Multiple Run
Short Identifier=Multiple
Geom File=g01
Flow File=f01
Subcritical Flow
K Sum by GR= 0
Std Step Tol= 0.01
Critical Tol= 0.01
Num of Std Step Trials= 20
Max Error Tol= 0.3
Flow Tol Ratio= 0.001
Split Flow NTrial= 30
Split Flow Tol= 0.02
Split Flow Ratio= 0.02
Log Output Level= 0
Friction Slope Method= 1
Unsteady Friction Slope Method= 2
Unsteady Bridges Friction Slope Method= 1
Parabolic Critical Depth
Global Vel Dist=  1 , 1 , 1
Global Log Level= 0
CheckData=True
Encroach Param= -1, 0, 0, 0
BEGIN DESCRIPTION:
Multiple Run
END DESCRIPTION:

--- Lacy 198.f01 (steady flow) ---

Flow Title=Multiple
Number of Profiles=7
Profile Names=10-year,25-year,50-year,1pct_min,100-year,1pct_plu,500-year
River Rch & RM= Lacy 198,Reach-1,1225
     133     161     182     103     205     409     258
Boundary for River Rch & Prof#=Lacy 198,Reach-1,1
Up Type=0
Dn Type=3
Dn Slope=0.005
Boundary for River Rch & Prof#=Lacy 198,Reach-1,2
Up Type=0
Dn Type=3
Dn Slope=0.005
Boundary for River Rch & Prof#=Lacy 198,Reach-1,3
Up Type=0
Dn Type=3
Dn Slope=0.005
Boundary for River Rch & Prof#=Lacy 198,Reach-1,4
Up Type=0
Dn Type=3
Dn Slope=0.005
Boundary for River Rch & Prof#=Lacy 198,Reach-1,5
Up Type=0
Dn Type=3
Dn Slope=0.005
Boundary for River Rch & Prof#=Lacy 198,Reach-1,6
Up Type=0
Dn Type=3
Dn Slope=0.005
Boundary for River Rch & Prof#=Lacy 198,Reach-1,7
Up Type=0
Dn Type=3
Dn Slope=0.005

--- Lacy 198.g01 (geometry) ---

Geom Title=Existing Conditions
Program Version=4.10

River Reach=Lacy 198        ,Reach-1
Reach XY= 30
        2675526.        6809661.      2675612.76      6809573.99
      2675627.63      6809564.02      2675641.36      6809560.85
      2675665.36      6809561.54      2675682.04      6809568.48
      2675759.34      6809644.73      2675782.05      6809659.33
      2675805.84      6809661.24      2675824.35      6809657.41
      2675866.13      6809622.39      2675876.09      6809618.35
      2675882.73      6809620.15      2676119.94      6809852.86
      2676178.19       6809867.1      2676227.73      6809906.81
      2676278.29      6809916.85      2676369.95      6810002.84
      2676382.04      6810008.49      2676428.19       6810017.1
       2676473.8      6810054.92      2676524.28      6810065.22
      2676570.07      6810103.25       2676586.7       6810110.3
      2676615.37       6810110.4      2676632.05       6810103.5
       2676723.7      6810016.83      2676778.24      6810005.03
      2676827.49       6809964.6        2676876.        6809961.

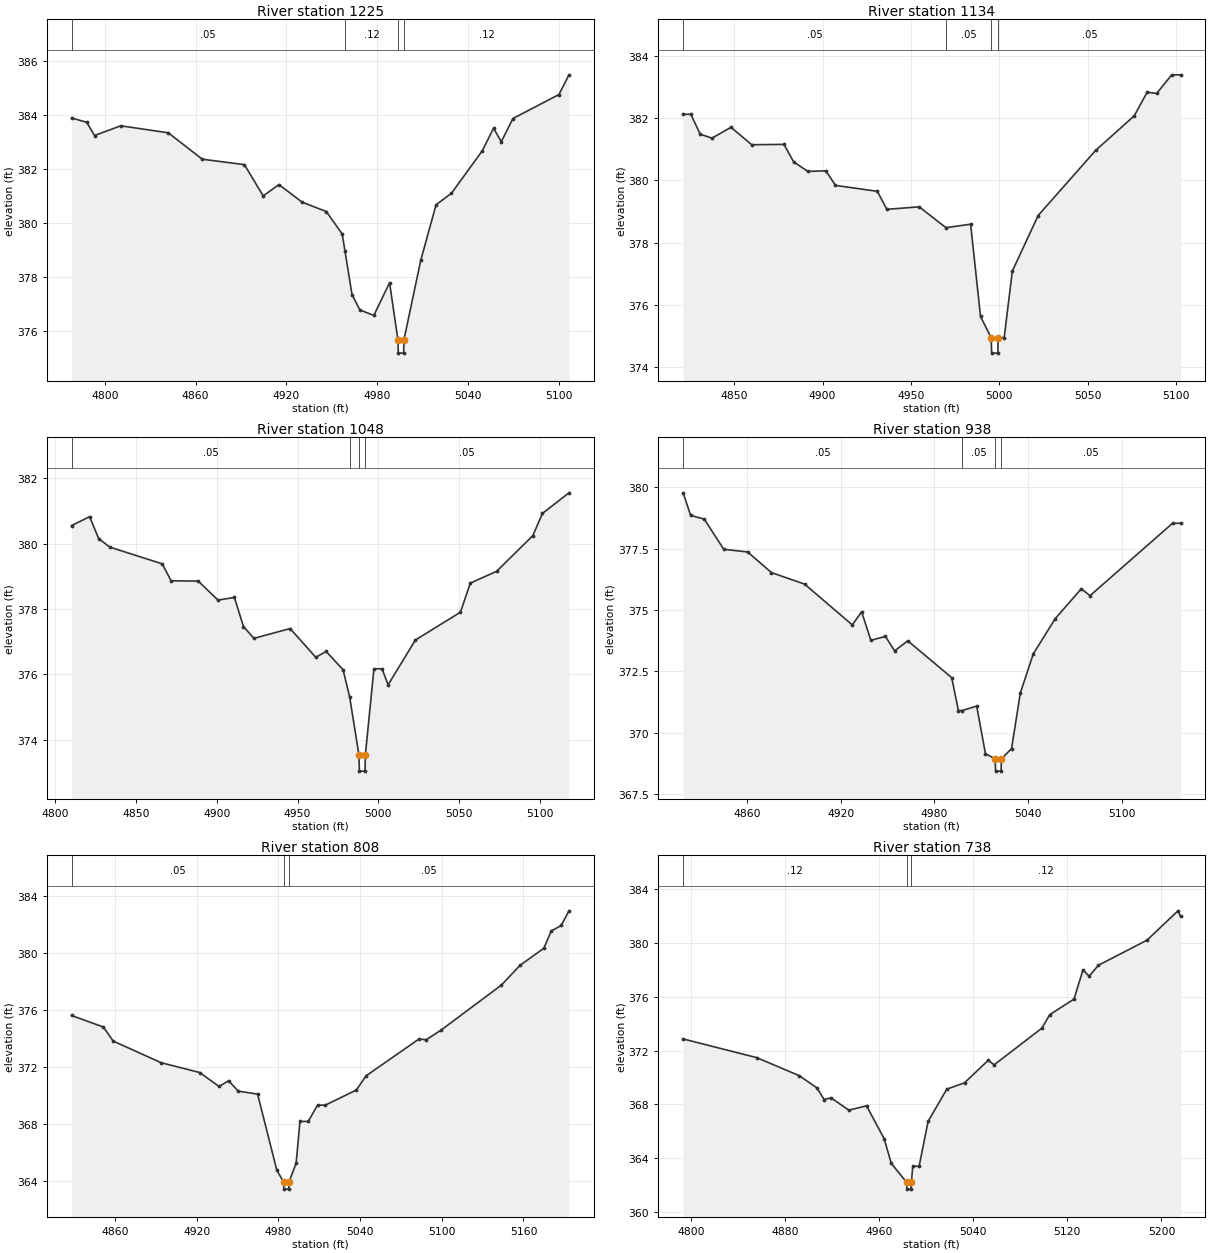
Type RM Length L Ch R = 1 ,1225    ,91,91,91
BEGIN DESCRIPTION:
Lacy 198 140
END DESCRIPTION:
XS GIS Cut Line= 3
      2675817.07      6809832.16      2675880.62      6809621.61
      2675899.01      6809514.51
#Sta/Elev= 30
  4778.1   383.9  4788.1  383.74  4793.3  383.25  4810.6  383.61    4842  383.35
  4864.5  382.37  4892.3  382.17  4904.7  381.01  4915.1  381.43  4930.4  380.78
  4946.4  380.43  4956.9   379.6  4958.7  378.98  4963.4  377.35  4968.6  376.78
  4977.8  376.58  4988.2  377.79  4993.7  375.68    4994  375.18  4997.5  375.18
  4997.7  375.68  5008.8  378.62  5018.9  380.68  5029.1  381.11  5049.4  382.68
  5056.9  383.52    5062  383.02  5069.7  383.88  5100.1  384.77  5106.7   385.5
#Mann= 4 ,-1 , 0
  4778.1     .05       0  4958.7     .12       0  4993.7     .07       0
  4997.7     .12       0
Bank Sta=4993.7,4997.7
XS Rating Curve= 0 ,0
Exp/Cntr=0.3,0.1

Type RM Length L Ch R = 1 ,1134    ,86,86,86
BEGIN DESCRIPTION:
Lacy 198 602
END DESCRIPTION:
XS GIS Cut Line= 3
      2675877.65      6809845.99      2675947.41      6809681.26
       2675987.7      6809586.89
#Sta/Elev= 30
  4821.1  382.13  4825.4  382.13  4830.8  381.49  4837.4  381.36  4848.2  381.71
  4859.9  381.15  4878.2  381.16  4883.6   380.6  4891.7  380.29  4901.9  380.31
  4907.3  379.84    4931  379.65  4936.4  379.07  4954.7  379.15  4969.8  378.48
  4983.8  378.59  4989.4  375.62  4995.4  374.94  4995.7  374.44  4999.2  374.44
  4999.4  374.94  5002.8  374.94  5007.4  377.08    5022  378.87  5054.6  380.97
  5076.4  382.08  5083.7  382.84  5089.1   382.8  5097.6   383.4  5102.6   383.4
#Mann= 4 ,-1 , 0
  4821.1     .05       0  4969.8     .05       0  4995.4     .07       0
  4999.4     .05       0
Bank Sta=4995.4,4999.4
XS Rating Curve= 0 ,0
Exp/Cntr=0.3,0.1

Type RM Length L Ch R = 1 ,1048    ,110,110,110
BEGIN DESCRIPTION:
Lacy 198 139
END DESCRIPTION:
XS GIS Cut Line= 3
      2675924.11      6809912.26      2676008.09      6809742.92
      2676061.14      6809636.31
#Sta/Elev= 30
    4810  380.55  4821.2  380.82  4826.8  380.15  4833.7  379.89  4866.1  379.38
  4871.7  378.86  4888.5  378.85  4900.7  378.27  4910.9  378.35  4916.5  377.46
    4923   377.1  4945.4   377.4  4961.3  376.52  4967.7   376.7  4978.2  376.14
  4982.3   375.3    4988  373.54  4988.3  373.04  4991.8  373.04    4992  373.54
  4997.3  376.17  5002.3  376.17  5006.1  375.68    5023  377.05  5050.9   377.9
    5057  378.79  5073.3  379.15  5095.7  380.24  5101.7  380.92  5118.1  381.55
#Mann= 4 ,-1 , 0
    4810     .05       0  4982.3     .08       0    4988     .07       0
    4992     .05       0
Bank Sta=4988,4992
XS Rating Curve= 0 ,0
Exp/Cntr=0.3,0.1

Type RM Length L Ch R = 1 ,938     ,130,130,130
BEGIN DESCRIPTION:
Lacy 198 138
END DESCRIPTION:
XS GIS Cut Line= 3
      2675989.87       6809972.4      2676085.68      6809821.24
      2676148.36      6809696.91
#Sta/Elev= 30
  4819.2  379.78    4824  378.86  4832.7  378.71  4845.2  377.48  4860.5  377.37
  4875.7  376.53  4896.9  376.06  4927.4   374.4  4933.4  374.93  4939.3  373.77
  4948.6  373.93  4954.5  373.34  4962.9  373.75    4991  372.25  4995.3  370.91
  4997.8  370.91    5007  371.09  5012.6  369.15  5018.8  368.94  5019.1  368.44
  5022.6  368.44  5022.8  368.94  5029.3  369.36  5034.9  371.62  5043.2  373.22
  5057.2  374.65  5073.9  375.87  5079.5  375.59  5132.3  378.54  5137.4  378.54
#Mann= 4 ,-1 , 0
  4819.2     .05       0  4997.8     .05       0  5018.8     .07       0
  5022.8     .05       0
Bank Sta=5018.8,5022.8
XS Rating Curve= 0 ,0
Exp/Cntr=0.3,0.1

Type RM Length L Ch R = 1 ,808     ,70,70,70
BEGIN DESCRIPTION:
Lacy 198 137
END DESCRIPTION:
XS GIS Cut Line= 3
      2676073.63      6810001.74      2676195.12      6809883.48
      2676277.19      6809705.87
#Sta/Elev= 30
  4828.2  375.61  4851.6   374.8  4858.8  373.81    4894  372.29  4922.3   371.6
  4936.5  370.62  4943.5  371.02  4950.6  370.29  4964.8  370.08  4978.9  364.74
  4983.9   363.9  4984.1   363.4  4987.6   363.4  4987.9   363.9  4993.1  365.23
  4995.9  368.16  5001.9  368.16  5008.9  369.31  5014.4   369.3  5037.3  370.37
  5044.5  371.37  5083.2  373.95  5088.7  373.91  5099.6  374.59  5143.7  377.74
  5157.5  379.14  5174.9  380.33  5180.4  381.55  5187.7  381.94  5193.4  382.97
#Mann= 3 ,-1 , 0
  4828.2     .05       0  4983.9     .07       0  4987.9     .05       0
Bank Sta=4983.9,4987.9
XS Rating Curve= 0 ,0
Exp/Cntr=0.3,0.1

Type RM Length L Ch R = 1 ,738     ,104,104,104
BEGIN DESCRIPTION:
Lacy 198 136
END DESCRIPTION:
XS GIS Cut Line= 3
      2676144.95      6810085.93      2676254.28      6809920.69
      2676311.46      6809703.43
#Sta/Elev= 30
  4793.4  372.86    4856  371.47  4892.1  370.13  4907.2  369.22  4913.2  368.36
  4919.2  368.48  4934.2  367.57  4949.3  367.89  4964.3  365.44  4970.3  363.62
  4983.4   362.2  4983.6   361.7  4987.1   361.7  4987.4   362.2  4988.6   363.4
    4994   363.4  5001.6  366.73  5017.5  369.13  5032.6   369.6  5052.7  371.27
  5057.8  370.94  5098.2  373.65    5105  374.66  5125.6  375.82  5133.3  377.99
  5138.5  377.52  5146.3  378.33  5187.7   380.2    5214  382.38  5216.2  381.97
#Mann= 3 ,-1 , 0
  4793.4     .12       0  4983.4     .07       0  4987.4     .12       0
Bank Sta=4983.4,4987.4
XS Rating Curve= 0 ,0
Exp/Cntr=0.3,0.1

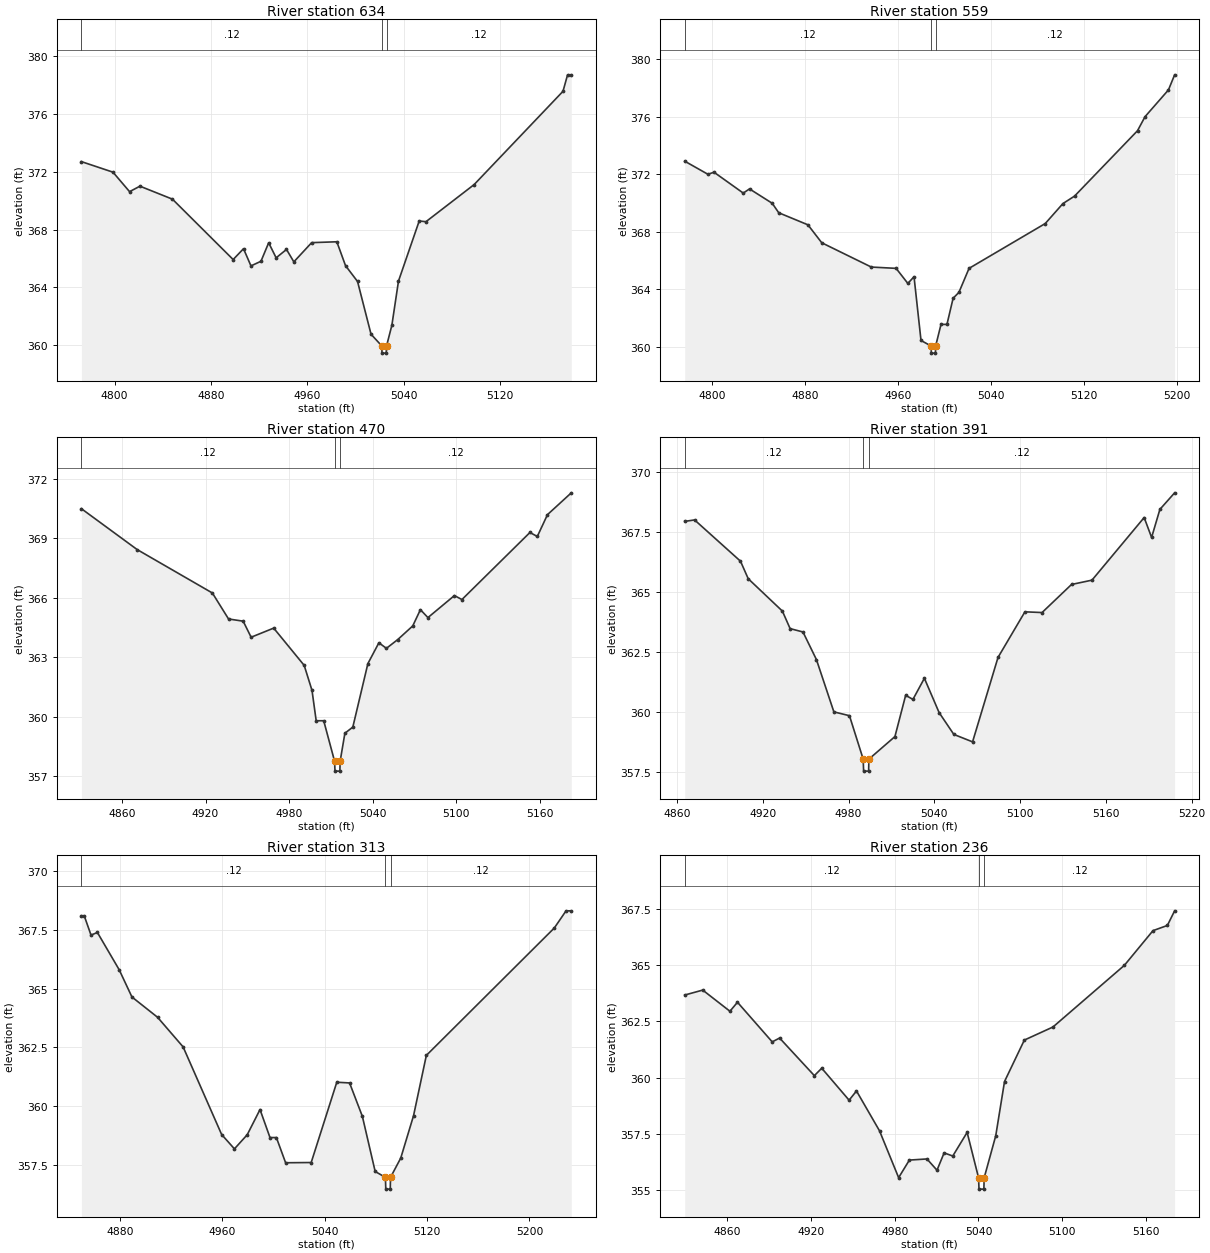
Type RM Length L Ch R = 1 ,634     ,75,75,75
BEGIN DESCRIPTION:
Lacy 198 135
END DESCRIPTION:
XS GIS Cut Line= 3
      2676154.64      6810106.51      2676335.38      6809977.53
      2676414.25      6809810.45
#Sta/Elev= 30
  4772.5  372.71  4798.7  371.98  4812.5  370.63  4821.1  371.01  4848.1  370.11
  4898.5  365.93  4907.1  366.68  4913.3  365.49  4921.6  365.81    4928  367.09
  4934.2  366.05  4942.8  366.63  4948.9  365.77  4963.7   367.1  4984.6  367.16
  4991.8  365.51  5001.8  364.41    5013  360.76  5021.9  359.95  5022.1  359.45
  5025.6  359.45  5025.9  359.95  5030.3  361.38  5035.8  364.44    5053   368.6
  5058.6  368.55  5098.6  371.12  5172.4  377.58  5176.2  378.72  5179.3  378.72
#Mann= 3 ,-1 , 0
  4772.5     .12       0  5021.9     .07       0  5025.9     .12       0
Bank Sta=5021.9,5025.9
XS Rating Curve= 0 ,0
Exp/Cntr=0.3,0.1

Type RM Length L Ch R = 1 ,559     ,89,89,89
BEGIN DESCRIPTION:
Lacy 198 134
END DESCRIPTION:
XS GIS Cut Line= 3
      2676322.94       6810221.5      2676399.65      6810013.66
      2676425.29      6809815.76
#Sta/Elev= 30
  4776.6  372.91  4796.5     372  4801.8  372.14  4826.9  370.69  4832.3  370.98
  4851.8  369.98  4857.4  369.32  4882.5  368.48  4894.4  367.23    4937  365.54
  4958.3  365.45  4968.4   364.4  4973.7  364.87  4979.7  360.43  4988.3  360.05
  4988.6  359.55  4992.1  359.55  4992.3  360.05  4996.9  361.55    5002  361.55
  5007.3  363.37  5012.3  363.78    5021  365.45  5086.5  368.57  5101.7  369.96
  5111.7  370.48  5165.8  375.03  5172.3  376.01  5192.4  377.87  5197.7  378.92
#Mann= 3 ,-1 , 0
  4776.6     .12       0  4988.3     .07       0  4992.3     .12       0
Bank Sta=4988.3,4992.3
XS Rating Curve= 0 ,0
Exp/Cntr=0.3,0.1

Type RM Length L Ch R = 1 ,470     ,79,79,79
BEGIN DESCRIPTION:
Lacy 198 617
END DESCRIPTION:
XS GIS Cut Line= 3
      2676393.27      6810203.62       2676473.8      6810054.92
      2676540.61      6809885.09
#Sta/Elev= 30
  4830.9   370.5  4870.9  368.44  4924.9  366.25  4936.5  364.94    4947  364.83
  4952.7  364.02  4968.9  364.48  4990.8   362.6  4996.4  361.34  4999.4  359.81
  5004.8  359.81  5012.6  357.77  5012.9  357.27  5016.4  357.27  5016.6  357.77
    5020  359.18  5025.7  359.49  5036.5  362.69  5044.4  363.74  5049.8  363.46
  5057.9   363.9  5068.7  364.59  5074.2  365.41  5079.6  365.01  5098.6  366.12
    5104  365.92  5152.8   369.3  5158.1   369.1  5165.4   370.2  5182.5   371.3
#Mann= 3 ,-1 , 0
  4830.9     .12       0  5012.6     .07       0  5016.6     .12       0
Bank Sta=5012.6,5016.6
XS Rating Curve= 0 ,0
Exp/Cntr=0.3,0.1

Type RM Length L Ch R = 1 ,391     ,78,78,78
BEGIN DESCRIPTION:
Lacy 198 143
END DESCRIPTION:
XS GIS Cut Line= 3
      2676494.11      6810207.36      2676545.75      6810083.06
      2676594.97      6809880.97
#Sta/Elev= 30
  4865.4  367.94  4872.3     368  4904.4  366.28  4909.8  365.55  4933.7   364.2
  4939.1  363.47  4948.1  363.33  4957.5  362.18  4969.7     360  4980.6  359.84
  4990.2  358.03  4990.5  357.53    4994  357.53  4994.2  358.03  5012.4  358.97
  5019.9  360.69    5025  360.52    5033   361.4  5043.3  359.97  5053.6  359.06
  5066.7  358.75  5084.5  362.27  5103.3  364.17  5115.3  364.14  5135.9  365.31
  5150.2  365.49  5186.7   368.1  5191.9  367.27  5197.7  368.44    5208  369.13
#Mann= 3 ,-1 , 0
  4865.4     .12       0  4990.2     .07       0  4994.2     .12       0
Bank Sta=4990.2,4994.2
XS Rating Curve= 0 ,0
Exp/Cntr=0.3,0.1

Type RM Length L Ch R = 1 ,313     ,77,77,77
BEGIN DESCRIPTION:
Lacy 198 616
END DESCRIPTION:
XS GIS Cut Line= 3
      2676621.42      6810260.48      2676615.37       6810110.4
      2676618.01      6809877.72
#Sta/Elev= 30
  4849.8  368.09    4852  368.09  4857.3  367.27  4862.3  367.38  4879.3   365.8
  4889.3  364.64  4909.3  363.78  4929.3  362.52  4959.4   358.8  4969.4  358.19
  4979.4  358.79  4989.4  359.86  4997.2  358.67  5002.2  358.67  5009.4   357.6
  5029.4  357.61  5049.4  361.02  5059.4  360.99  5069.4  359.57  5079.4  357.23
  5087.4  356.98  5087.7  356.48  5091.2  356.48  5091.4  356.98  5099.4   357.8
  5109.4   359.6  5119.4  362.16  5219.4  367.57  5228.6   368.3  5232.7   368.3
#Mann= 3 ,-1 , 0
  4849.8     .12       0  5087.4     .07       0  5091.4     .12       0
Bank Sta=5087.4,5091.4
XS Rating Curve= 0 ,0
Exp/Cntr=0.3,0.1

Type RM Length L Ch R = 1 ,236     ,89,89,89
BEGIN DESCRIPTION:
Lacy 198 142
END DESCRIPTION:
XS GIS Cut Line= 3
      2676734.18      6810221.69      2676674.12      6810062.12
      2676634.59       6809885.9
#Sta/Elev= 30
  4829.5  363.67  4842.4  363.89  4861.9  362.95  4867.3  363.35  4892.2  361.59
  4897.5  361.76  4922.4  360.09  4927.7  360.42  4947.3     359  4952.6  359.41
  4969.1  357.64  4982.8  355.56  4990.5  356.34  5003.1  356.39  5010.3  355.89
  5015.4  356.66  5021.6  356.52  5031.9  357.57  5040.1  355.55  5040.4  355.05
  5043.9  355.05  5044.1  355.55  5052.4  357.42  5058.7  359.83  5072.9  361.67
  5093.4  362.25  5144.6  364.99  5165.1  366.53  5175.4  366.76  5180.6  367.41
#Mann= 3 ,-1 , 0
  4829.5     .12       0  5040.1     .07       0  5044.1     .12       0
Bank Sta=5040.1,5044.1
XS Rating Curve= 0 ,0
Exp/Cntr=0.3,0.1

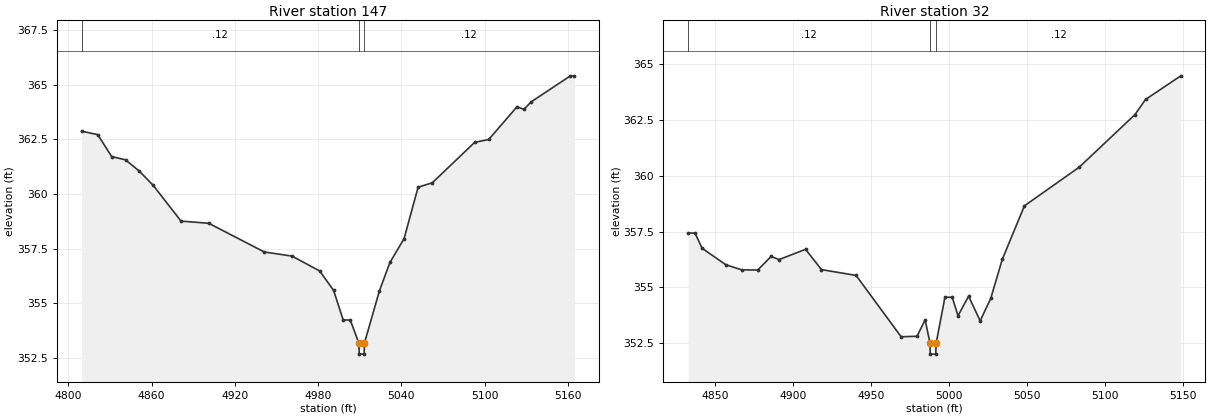
Type RM Length L Ch R = 1 ,147     ,115,115,115
BEGIN DESCRIPTION:
Lacy 198 615
END DESCRIPTION:
XS GIS Cut Line= 3
      2676749.13      6810202.66      2676745.06      6810012.21
      2676714.19      6809850.43
#Sta/Elev= 30
  4809.5  362.87  4821.2  362.71  4831.2  361.71  4841.2  361.56  4851.2  361.04
  4861.2  360.39  4881.2  358.76  4901.2  358.66  4941.2  357.35  4961.2  357.16
  4981.2  356.48  4991.2  355.59  4998.1  354.24  5003.2  354.24  5009.4  353.18
  5009.7  352.68  5013.2  352.68  5013.4  353.18  5024.2  355.57  5031.8  356.87
    5042  357.96  5052.1  360.31  5062.3  360.51  5092.9  362.36    5103  362.49
  5123.3  363.98  5128.4  363.87  5133.6  364.21  5161.9   365.4  5164.7   365.4
#Mann= 3 ,-1 , 0
  4809.5     .12       0  5009.4     .07       0  5013.4     .12       0
Bank Sta=5009.4,5013.4
XS Rating Curve= 0 ,0
Exp/Cntr=0.3,0.1

Type RM Length L Ch R = 1 ,32      ,0,0,0
BEGIN DESCRIPTION:
Lacy 198 141
END DESCRIPTION:
XS GIS Cut Line= 3
      2676809.09      6810124.67      2676844.19       6809961.1
      2676734.38      6809860.68
#Sta/Elev= 30
  4832.7  357.44  4837.2  357.44  4841.7  356.76  4856.9  356.02  4867.1  355.79
  4877.4  355.78    4886  356.39  4891.1  356.25  4908.1  356.71  4918.3   355.8
  4940.5  355.54  4969.4  352.79  4979.6  352.81  4984.8  353.55  4987.9  352.51
  4988.1  352.01  4991.6  352.01  4991.9  352.51  4997.5  354.56  5002.2  354.56
  5005.9  353.73  5012.7  354.61  5020.1   353.5  5026.9  354.51  5034.3  356.26
  5048.5  358.66  5083.6  360.39  5119.4  362.75  5126.2  363.43  5148.8  364.49
#Mann= 3 ,-1 , 0
  4832.7     .12       0  4987.9     .07       0  4991.9     .12       0
Bank Sta=4987.9,4991.9
XS Rating Curve= 0 ,0
Exp/Cntr=0.3,0.1

Chan Stop Cuts=-1
Use User Specified Reach Order=0
Composite Channel Slope=5