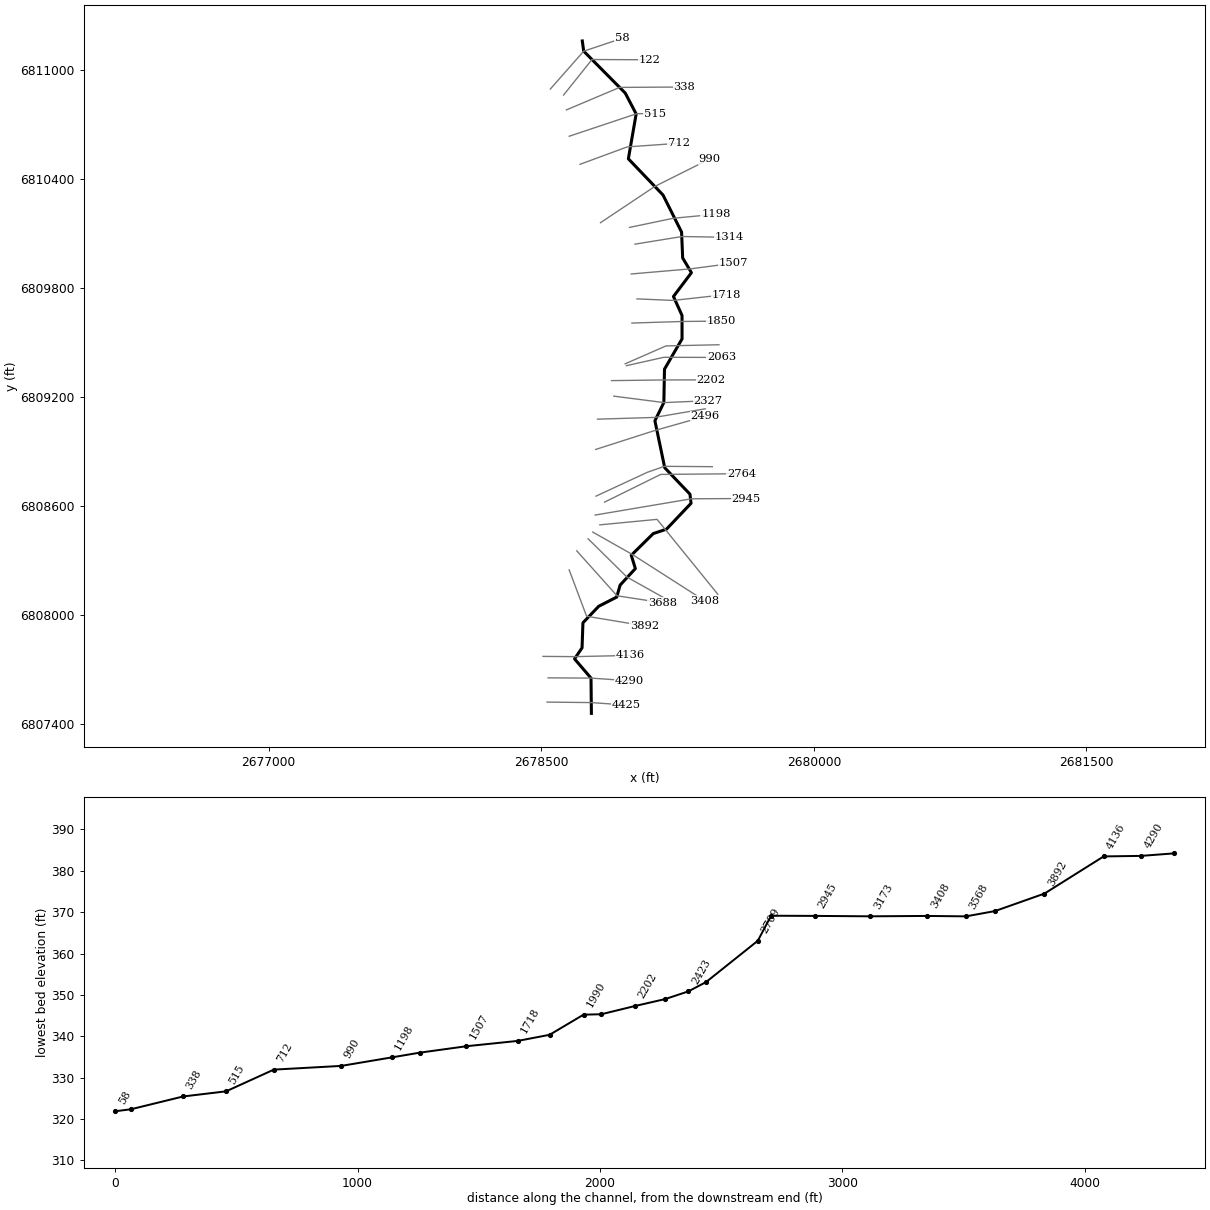
--- Lacy 199.prj (project) ---

Proj Title=Lacy 199 Base Level Engineering
Current Plan=p01
Default Exp/Contr=0.3,0.1
English Units
Geom File=g01
Flow File=f01
Plan File=p01
Y Axis Title=Elevation
X Axis Title(PF)=Main Channel Distance
X Axis Title(XS)=Station
BEGIN DESCRIPTION:
Lacy 199
END DESCRIPTION:
DSS Export Rating Curves= 0
DSS Export Rating Curve Sorted= 0
DSS Export Volume Flow Curves= 0
DXF OffsetX= 0
DXF OffsetY= 0
DXF ScaleX= 1
DXF ScaleY= 10

--- Lacy 199.p01 (plan) ---

Plan Title=Multiple Run
Short Identifier=Multiple
Geom File=g01
Flow File=f01
Subcritical Flow
K Sum by GR= 0
Std Step Tol= 0.01
Critical Tol= 0.01
Num of Std Step Trials= 20
Max Error Tol= 0.3
Flow Tol Ratio= 0.001
Split Flow NTrial= 30
Split Flow Tol= 0.02
Split Flow Ratio= 0.02
Log Output Level= 0
Friction Slope Method= 1
Unsteady Friction Slope Method= 2
Unsteady Bridges Friction Slope Method= 1
Parabolic Critical Depth
Global Vel Dist=  1 , 1 , 1
Global Log Level= 0
CheckData=True
Encroach Param= -1, 0, 0, 0
BEGIN DESCRIPTION:
Multiple Run
END DESCRIPTION:

--- Lacy 199.f01 (steady flow) ---

Flow Title=Multiple
Number of Profiles=7
Profile Names=10-year,25-year,50-year,1pct_min,100-year,1pct_plu,500-year
River Rch & RM= Lacy 199,Reach-1,4425
     244     311     363     211     422     841     566
Boundary for River Rch & Prof#=Lacy 199,Reach-1,1
Up Type=0
Dn Type=3
Dn Slope=0.005
Boundary for River Rch & Prof#=Lacy 199,Reach-1,2
Up Type=0
Dn Type=3
Dn Slope=0.005
Boundary for River Rch & Prof#=Lacy 199,Reach-1,3
Up Type=0
Dn Type=3
Dn Slope=0.005
Boundary for River Rch & Prof#=Lacy 199,Reach-1,4
Up Type=0
Dn Type=3
Dn Slope=0.005
Boundary for River Rch & Prof#=Lacy 199,Reach-1,5
Up Type=0
Dn Type=3
Dn Slope=0.005
Boundary for River Rch & Prof#=Lacy 199,Reach-1,6
Up Type=0
Dn Type=3
Dn Slope=0.005
Boundary for River Rch & Prof#=Lacy 199,Reach-1,7
Up Type=0
Dn Type=3
Dn Slope=0.005

--- Lacy 199.g01 (geometry) ---

Geom Title=Existing Conditions
Program Version=4.10

River Reach=Lacy 199        ,Reach-1
Reach XY= 30
        2678776.        6807461.      2678773.93      6807655.15
      2678683.33       6807760.9       2678724.6      6807821.44
      2678729.54      6807959.54      2678816.31      6808050.22
      2678915.35        6808101.       2678934.2      6808167.03
      2679017.98      6808257.67      2678995.37        6808331.
      2679116.32      6808450.22      2679189.21      6808474.63
      2679324.42      6808617.05      2679318.54      6808667.05
      2679179.61       6808812.5       2679125.5      6809071.17
      2679174.78      6809171.51      2679178.24      6809355.07
      2679274.81       6809521.5      2679274.77       6809650.5
      2679227.63      6809754.96      2679326.49      6809885.96
       2679278.3      6809966.93      2679272.24      6810109.44
      2679170.17       6810313.3      2678979.46       6810512.5
      2679022.33      6810759.42      2678962.38      6810874.22
      2678733.76      6811104.79        2678726.        6811161.

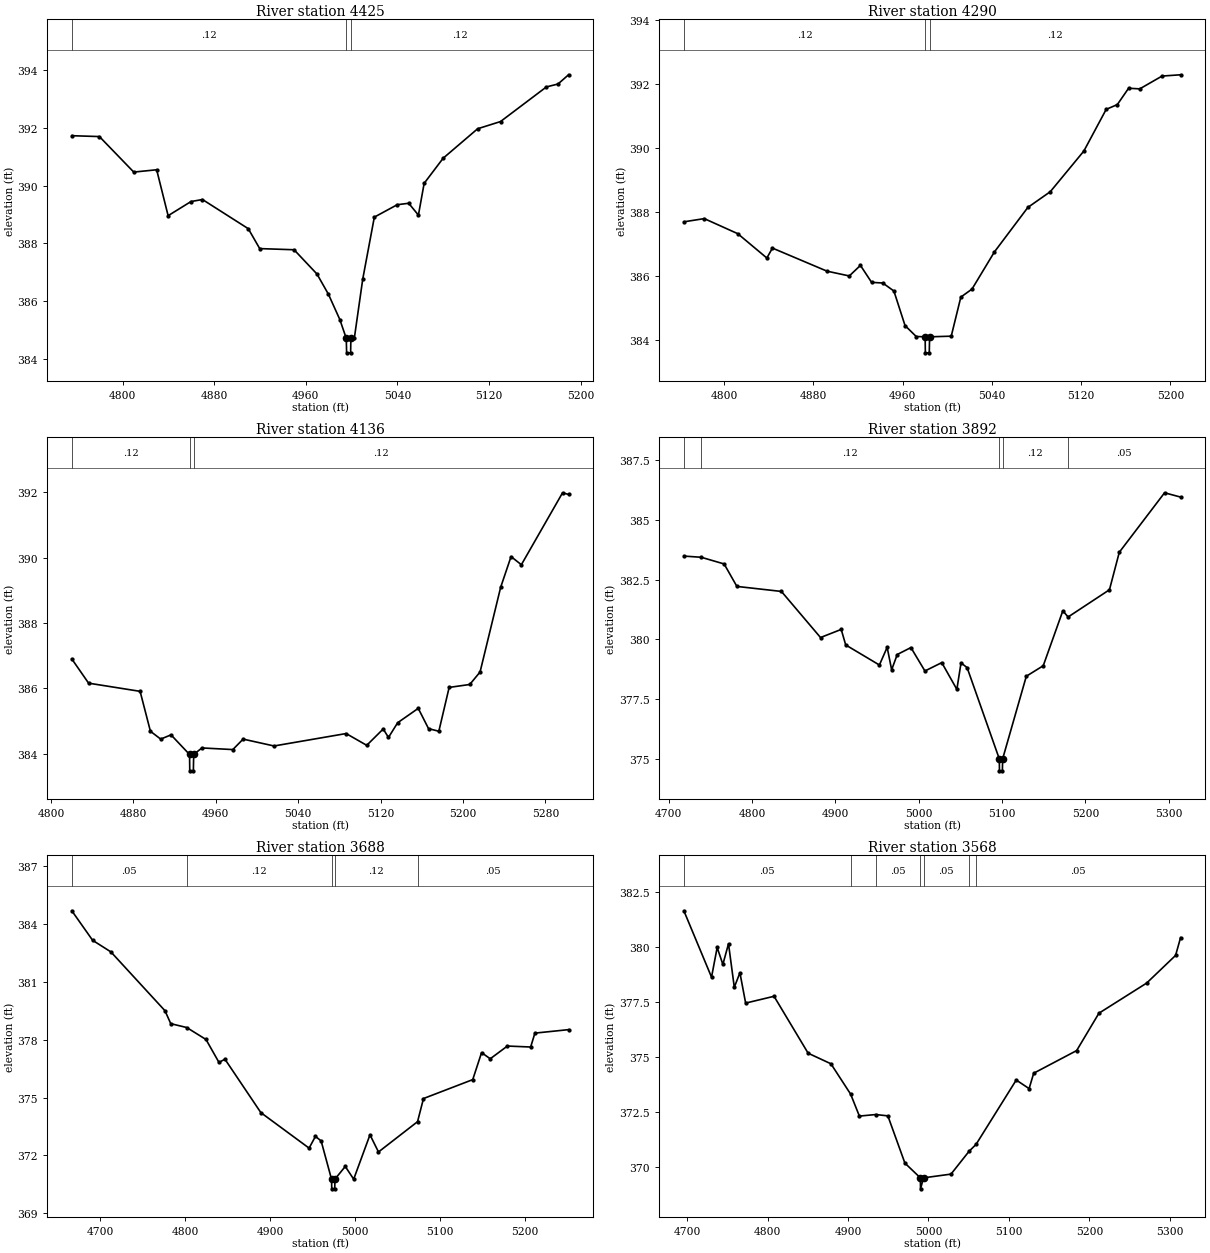
Type RM Length L Ch R = 1 ,4425    ,135,135,135
BEGIN DESCRIPTION:
Lacy 199 127
END DESCRIPTION:
XS GIS Cut Line= 3
       2678531.9      6807523.05      2678776.18      6807520.39
       2678965.2      6807506.92
#Sta/Elev= 30
  4755.7  391.73  4779.8   391.7  4809.8  390.47  4829.8  390.55  4839.8  388.96
  4859.8  389.45  4869.8  389.52  4909.8  388.51  4919.8  387.82  4949.8  387.78
  4969.8  386.94  4979.8  386.24  4989.8  385.36  4995.4  384.71  4995.7  384.21
  4999.2  384.21  4999.4  384.71  5002.4  384.71  5009.8  386.77  5019.9  388.91
  5039.9  389.34  5049.9  389.39  5058.4  388.98  5063.4  390.08    5080  390.95
  5110.1  391.97  5130.1  392.22  5170.2  393.42  5180.3  393.52  5189.5  393.84
#Mann= 3 ,-1 , 0
  4755.7     .12       0  4995.4     .07       0  4999.4     .12       0
Bank Sta=4995.4,4999.4
XS Rating Curve= 0 ,0
Exp/Cntr=0.3,0.1

Type RM Length L Ch R = 1 ,4290    ,154,154,154
BEGIN DESCRIPTION:
Lacy 199 126
END DESCRIPTION:
XS GIS Cut Line= 3
      2678537.74       6807656.4      2678773.93      6807655.15
      2678982.53      6807640.65
#Sta/Elev= 30
  4763.8   387.7  4782.1   387.8  4812.1  387.33  4838.2  386.57  4843.2  386.88
  4892.1  386.16  4912.1  386.01  4922.1  386.34  4932.1  385.81  4942.1  385.79
  4952.1  385.54  4962.1  384.46  4972.1  384.12  4980.1  384.11  4980.3  383.61
  4983.8  383.61  4984.1  384.11  5003.5  384.13  5012.1  385.35  5022.1   385.6
  5042.2  386.76  5072.2  388.15  5092.3  388.64  5122.4  389.91  5142.4  391.21
  5152.4  391.36  5162.5  391.87  5172.5  391.85  5192.5  392.25  5209.1  392.29
#Mann= 3 ,-1 , 0
  4763.8     .12       0  4980.1     .07       0  4984.1     .12       0
Bank Sta=4980.1,4984.1
XS Rating Curve= 0 ,0
Exp/Cntr=0.3,0.1

Type RM Length L Ch R = 1 ,4136    ,244,244,244
BEGIN DESCRIPTION:
Lacy 199 117
END DESCRIPTION:
XS GIS Cut Line= 3
      2678509.71      6807774.56      2678686.21      6807773.22
      2678991.84      6807779.91
#Sta/Elev= 30
  4820.3   386.9  4836.6  386.16  4886.6  385.91  4896.6  384.69  4906.6  384.45
  4916.6  384.58  4934.6  383.98  4934.8  383.48  4938.3  383.48  4938.6  383.98
  4946.6  384.18  4976.6  384.13  4986.6  384.45  5016.6  384.24  5086.6  384.62
  5106.6  384.26  5122.6  384.76  5127.7   384.5  5136.6  384.95  5156.6  385.39
  5166.6  384.77  5176.6  384.69  5186.6  386.03  5206.6  386.12  5216.6   386.5
  5236.6  389.09  5246.7  390.03  5256.7  389.78  5296.7  391.98  5302.5  391.93
#Mann= 3 ,-1 , 0
  4820.3     .12       0  4934.6     .07       0  4938.6     .12       0
Bank Sta=4934.6,4938.6
XS Rating Curve= 0 ,0
Exp/Cntr=0.3,0.1

Type RM Length L Ch R = 1 ,3892    ,204,204,204
BEGIN DESCRIPTION:
Lacy 199 120
END DESCRIPTION:
XS GIS Cut Line= 3
      2678653.69       6808250.5      2678749.72      6807995.41
      2679068.52      6807942.64
#Sta/Elev= 30
  4718.4  383.49  4739.3  383.44  4766.7  383.16    4782  382.22  4835.4  382.01
  4882.3  380.08  4907.1  380.42  4912.5  379.77  4952.9  378.93  4962.2  379.67
  4967.6  378.73  4974.3  379.37  4990.7  379.66  5007.5  378.68  5027.7  379.03
  5045.8  377.91  5050.8  379.02  5058.1  378.82  5096.7     375  5096.9   374.5
  5100.4   374.5  5100.7     375  5129.1  378.46  5149.4   378.9  5172.9   381.2
  5179.2  380.94  5228.8  382.08  5240.6  383.65  5294.9  386.14  5314.1  385.96
#Mann= 5 ,-1 , 0
  4718.4     .05       0  4739.3     .12       0  5096.7     .07       0
  5100.7     .12       0  5179.2     .05       0
Bank Sta=5096.7,5100.7
XS Rating Curve= 0 ,0
Exp/Cntr=0.3,0.1

Type RM Length L Ch R = 1 ,3688    ,120,120,120
BEGIN DESCRIPTION:
Lacy 199 119
END DESCRIPTION:
XS GIS Cut Line= 3
      2678695.55      6808355.26      2678917.09      6808108.17
      2679167.15      6808069.49
#Sta/Elev= 30
  4666.3  384.68  4690.8  383.15  4712.3  382.55    4776   379.5  4782.8  378.83
  4801.6  378.63  4824.3  378.01  4839.6  376.82  4846.6  376.99  4888.9  374.22
  4945.7  372.38  4953.2  372.99  4959.9  372.75  4972.1  370.77  4972.4  370.27
  4975.9  370.27  4976.1  370.77  4988.3  371.43  4998.2  370.77  5017.4  373.07
  5027.4  372.18  5073.4  373.75  5080.4  374.95  5138.4  375.93  5148.8  377.33
    5159  377.01  5179.2  377.67  5206.6  377.62  5211.6  378.34  5251.2  378.52
#Mann= 5 ,-1 , 0
  4666.3     .05       0  4801.6     .12       0  4972.1     .07       0
  4976.1     .12       0  5073.4     .05       0
Bank Sta=4972.1,4976.1
XS Rating Curve= 0 ,0
Exp/Cntr=0.3,0.1

Type RM Length L Ch R = 1 ,3568    ,160,160,160
BEGIN DESCRIPTION:
Lacy 199 118
END DESCRIPTION:
XS GIS Cut Line= 4
      2678758.02      6808421.61      2678972.19      6808210.68
      2679217.82       6808073.2      2679246.94      6808053.05
#Sta/Elev= 30
  4695.9  381.64  4730.3  378.62  4737.3  379.97  4744.4   379.2  4751.4  380.14
  4758.6  378.16  4765.6  378.82  4772.7  377.44    4808  377.75  4850.4  375.16
  4878.7  374.68  4903.2   373.3  4914.1   372.3  4934.5  372.37  4949.5  372.31
  4970.7  370.16  4989.9  369.49  4990.1  368.99  4993.9  369.49    5028  369.66
  5050.5   370.7  5059.1  371.01  5109.1  373.94  5125.1  373.55  5130.8  374.25
  5184.2  375.28  5211.9  376.98  5271.2  378.35  5307.2  379.61  5313.4  380.42
#Mann= 7 ,-1 , 0
  4695.9     .05       0  4903.2     .12       0  4934.5     .05       0
  4989.9     .03       0  4993.9     .05       0  5050.5     .12       0
  5059.1     .05       0
Bank Sta=4989.9,4993.9
XS Rating Curve= 0 ,0
Exp/Cntr=0.3,0.1

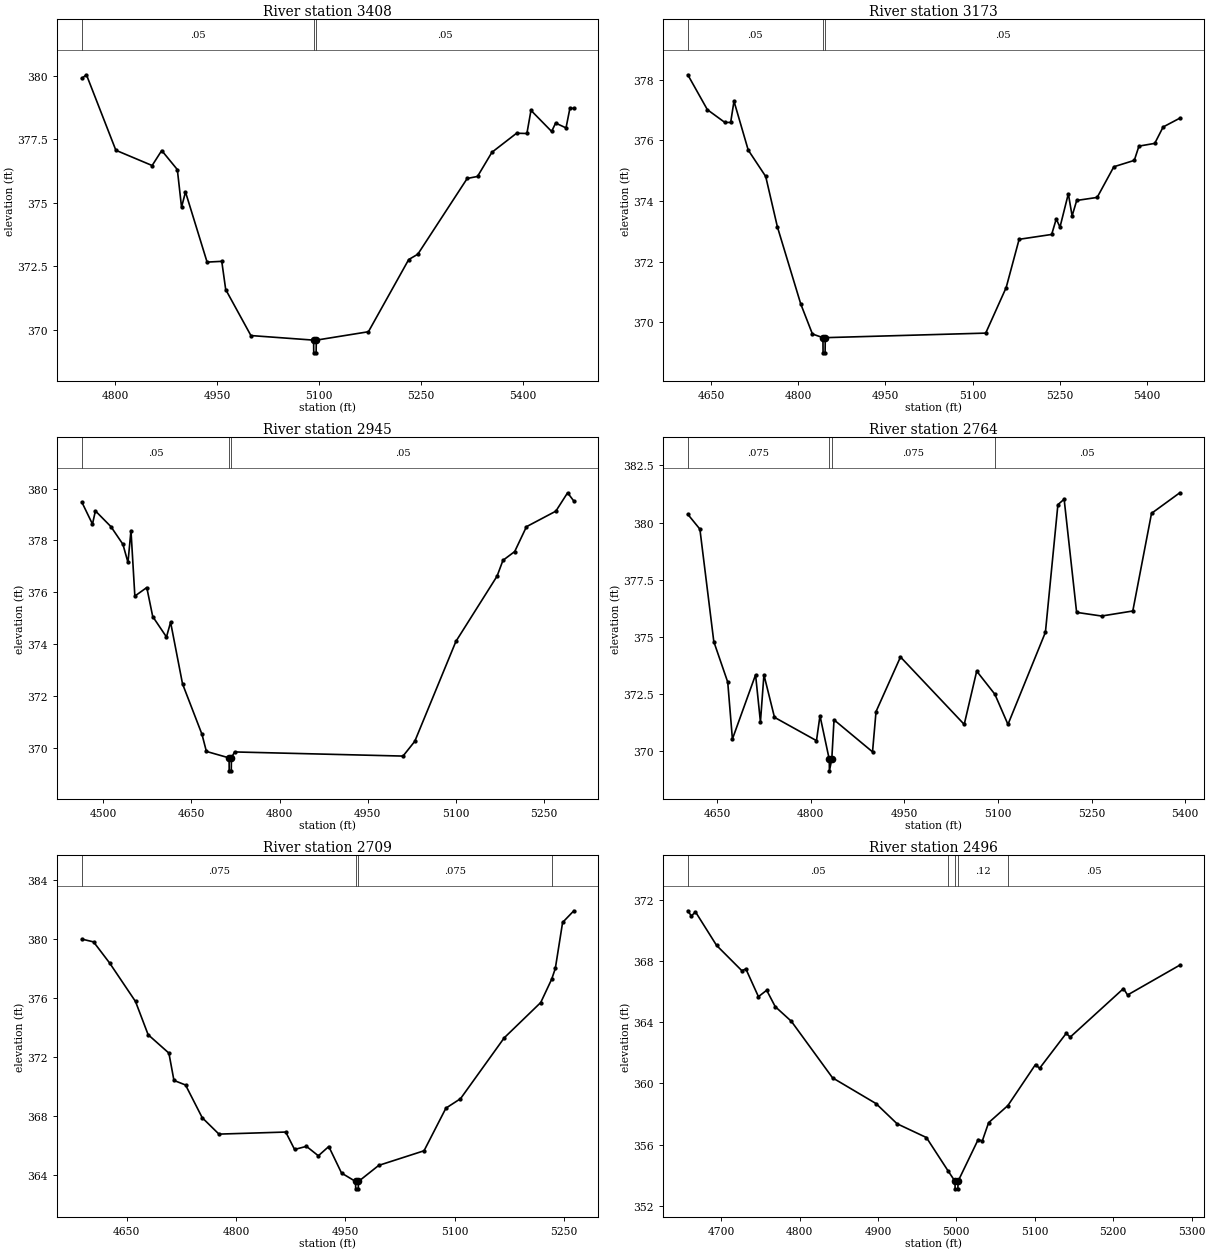
Type RM Length L Ch R = 1 ,3408    ,235,235,235
BEGIN DESCRIPTION:
Lacy 199 123
END DESCRIPTION:
XS GIS Cut Line= 4
      2678783.66      6808458.54      2679000.33      6808335.98
      2679385.09      6808089.85      2679400.76      6808079.79
#Sta/Elev= 30
    4751  379.89  4757.8  380.03  4801.1  377.06  4854.5  376.46  4868.6  377.05
  4891.6   376.3  4897.8  374.82  4903.6  375.42  4935.4  372.66    4957  372.69
  4962.8  371.58  4999.9  369.77  5092.2  369.59  5092.4  369.09  5095.9  369.09
  5096.2  369.59  5172.9  369.92  5232.2  372.76  5245.6  372.97  5318.3  375.95
  5333.5  376.03  5354.7  376.98    5391  377.73  5406.2  377.72  5412.2  378.63
  5442.6   377.8  5448.5  378.13  5463.8  377.94  5469.5  378.71  5475.3  378.71
#Mann= 3 ,-1 , 0
    4751     .05       0  5092.2     .03       0  5096.2     .05       0
Bank Sta=5092.2,5096.2
XS Rating Curve= 0 ,0
Exp/Cntr=0.3,0.1

Type RM Length L Ch R = 1 ,3173    ,228,228,228
BEGIN DESCRIPTION:
Lacy 199 122
END DESCRIPTION:
XS GIS Cut Line= 3
      2678822.49      6808498.33      2679137.27      6808528.61
      2679471.51      6808116.68
#Sta/Elev= 30
  4609.8  378.16  4643.5  377.01  4673.6  376.59  4683.6  376.59  4689.3  377.29
  4713.8  375.68  4743.9  374.81    4764  373.15  4804.2  370.61  4824.3  369.62
  4842.4   369.5  4842.6     369  4846.1     369  4846.4   369.5  5122.5  369.65
  5157.7  371.15    5180  372.74    5236   372.9  5243.9  373.41  5250.3  373.14
  5264.7  374.24  5271.2  373.51  5279.1  374.02  5314.3  374.12    5343  375.13
  5378.2  375.34  5386.2  375.81  5413.4   375.9  5427.8  376.44  5456.5  376.73
#Mann= 3 ,-1 , 0
  4609.8     .05       0  4842.4     .03       0  4846.4     .05       0
Bank Sta=4842.4,4846.4
XS Rating Curve= 0 ,0
Exp/Cntr=0.3,0.1

Type RM Length L Ch R = 1 ,2945    ,181,181,181
BEGIN DESCRIPTION:
Lacy 199 121
END DESCRIPTION:
XS GIS Cut Line= 3
      2678797.08      6808552.33      2679326.68      6808641.85
      2679626.56      6808643.23
#Sta/Elev= 30
  4463.7  379.48  4481.8  378.63  4486.8  379.14  4513.3  378.53  4533.6  377.85
  4542.2  377.15  4547.3  378.38  4553.9  375.85  4574.2  376.18  4584.3  375.06
  4607.7  374.27  4614.7  374.84    4635  372.46  4668.1  370.51  4675.6  369.85
  4714.2   369.6  4714.4   369.1  4717.9   369.1  4718.2   369.6  4723.5  369.83
  5010.1  369.67  5030.1  370.24  5100.1   374.1  5170.1  376.62  5180.1  377.23
  5200.1  377.57  5220.1  378.53  5270.1  379.13  5290.1  379.84  5300.7  379.52
#Mann= 3 ,-1 , 0
  4463.7     .05       0  4714.2     .03       0  4718.2     .05       0
Bank Sta=4714.2,4718.2
XS Rating Curve= 0 ,0
Exp/Cntr=0.3,0.1

Type RM Length L Ch R = 1 ,2764    ,55,55,55
BEGIN DESCRIPTION:
Lacy 199 124
END DESCRIPTION:
XS GIS Cut Line= 3
       2678848.6      6808623.48       2679157.4      6808775.84
      2679601.34      6808779.81
#Sta/Elev= 30
    4603  380.36  4622.4  379.71  4644.7  374.79    4667  373.02  4674.5  370.53
  4711.6  373.34  4719.4  371.28    4725  373.34  4741.9  371.48  4809.2  370.46
  4814.8  371.55  4829.7  369.64  4829.9  369.14  4833.7  369.64  4837.3  371.37
    4899  369.97  4904.6  371.73  4943.8  374.12  5045.9  371.17  5065.9   373.5
    5095  372.49    5116  371.17    5176   375.2    5196  380.78    5206  381.02
    5226  376.07    5266  375.91    5316  376.13    5346   380.4  5391.3   381.3
#Mann= 4 ,-1 , 0
    4603    .075       0  4829.7     .07       0  4833.7    .075       0
    5095     .05       0
Bank Sta=4829.7,4833.7
XS Rating Curve= 0 ,0
Exp/Cntr=0.3,0.1

Type RM Length L Ch R = 1 ,2709    ,213,213,213
BEGIN DESCRIPTION:
Lacy 199 116
END DESCRIPTION:
XS GIS Cut Line= 4
      2678801.43      6808656.33      2679083.08      6808787.18
      2679177.19      6808820.41      2679441.42      6808818.42
#Sta/Elev= 30
  4588.7  380.01  4604.8  379.82  4626.8  378.39  4662.3  375.78  4679.6  373.53
  4708.1  372.28    4715  370.43  4730.9  370.12  4753.8   367.9  4776.7  366.79
  4868.3  366.93  4880.4  365.75  4896.7  365.96    4913  365.32  4927.3  365.95
  4944.8  364.15    4964  363.58  4964.2  363.08  4967.7  363.08    4968  363.58
  4995.8  364.67  5057.9  365.66  5087.9  368.55  5107.9  369.19  5167.9  373.32
  5217.9  375.71  5232.9  377.29  5237.9  378.02  5247.9  381.14  5263.3  381.93
#Mann= 4 ,-1 , 0
  4588.7    .075       0    4964     .07       0    4968    .075       0
  5232.9     .05       0
Bank Sta=4964,4968
XS Rating Curve= 0 ,0
Exp/Cntr=0.3,0.1

Type RM Length L Ch R = 1 ,2496    ,73,73,73
BEGIN DESCRIPTION:
Lacy 199 110
END DESCRIPTION:
XS GIS Cut Line= 3
       2678800.2      6808913.46      2679122.17      6809016.62
      2679400.53      6809095.45
#Sta/Elev= 30
  4657.5  371.28  4662.1  370.94  4667.3  371.21  4694.2  369.02  4726.4  367.37
  4731.6  367.48  4747.6  365.67  4758.1  366.09    4769  365.02  4789.6  364.06
  4842.1  360.37  4897.5  358.69  4924.4  357.37  4961.8  356.47  4989.7  354.27
  4998.2  353.62  4998.4  353.12  5001.9  353.12  5002.2  353.62  5027.8  356.34
    5033  356.24  5041.1  357.44  5065.7  358.56  5100.9  361.24  5106.1  360.99
    5140  363.27  5145.2  363.03  5213.1   366.2  5218.3  365.78  5284.9  367.73
#Mann= 5 ,-1 , 0
  4657.5     .05       0  4989.7     .12       0  4998.2     .07       0
  5002.2     .12       0  5065.7     .05       0
Bank Sta=4998.2,5002.2
XS Rating Curve= 0 ,0
Exp/Cntr=0.3,0.1

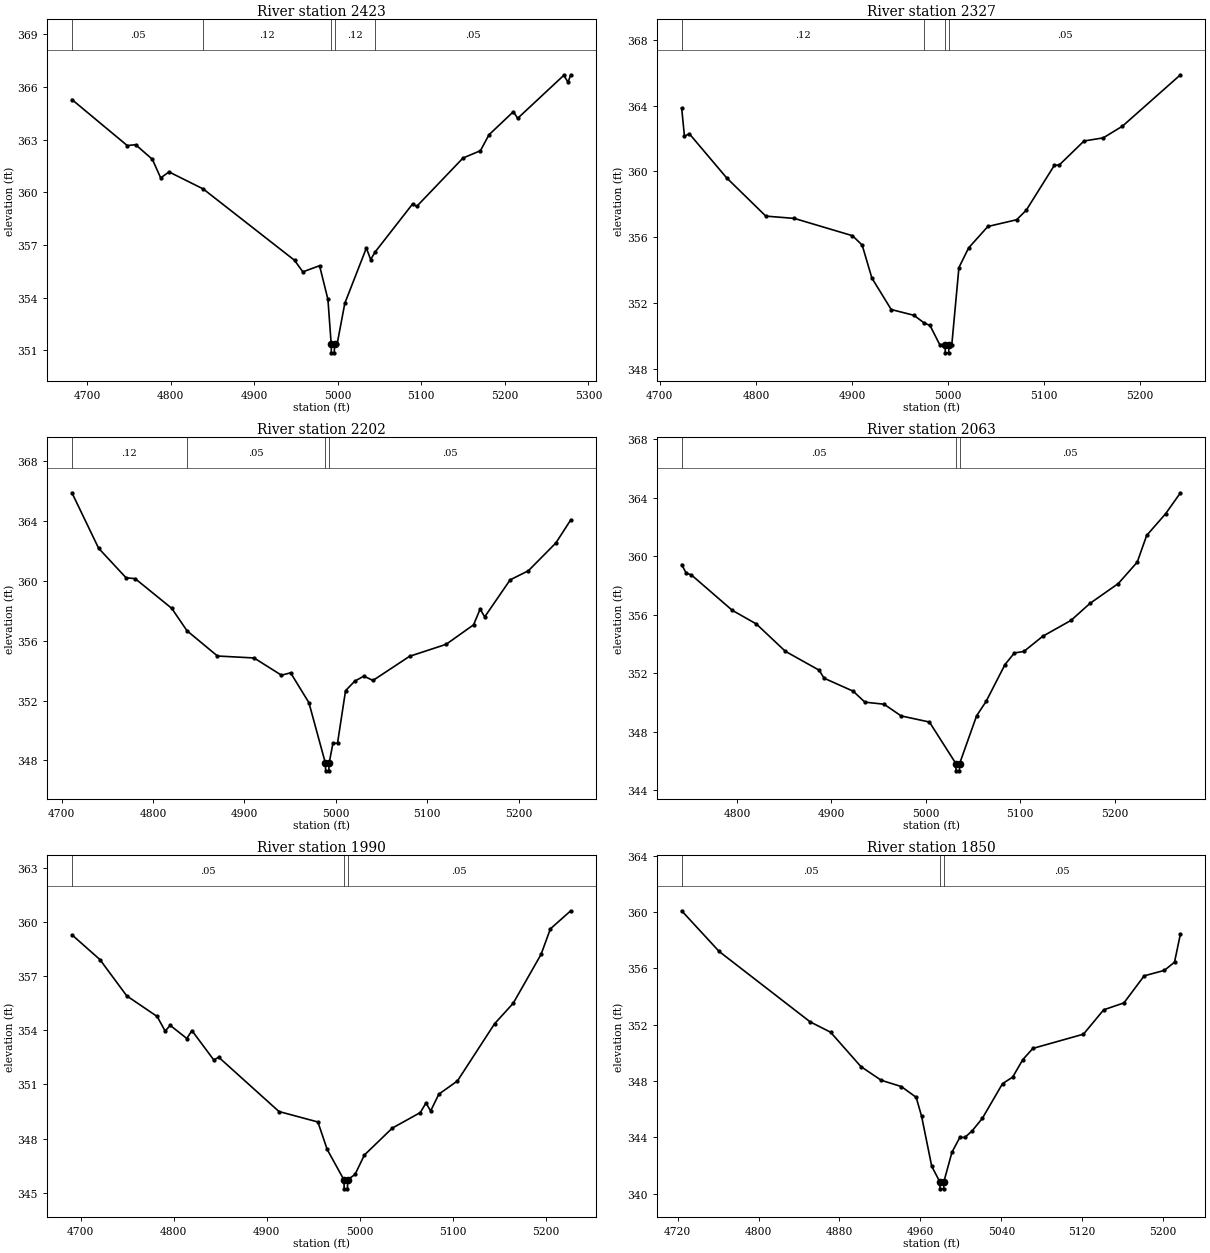
Type RM Length L Ch R = 1 ,2423    ,96,96,96
BEGIN DESCRIPTION:
Lacy 199 115
END DESCRIPTION:
XS GIS Cut Line= 3
      2678809.84      6809079.92      2679122.78      6809089.37
       2679402.5      6809136.83
#Sta/Elev= 30
    4682  365.28  4748.2  362.66  4758.2  362.71  4778.2  361.88  4788.2  360.82
  4798.2  361.16  4839.1  360.19  4948.3  356.13  4958.3  355.47  4978.3  355.82
  4988.3   353.9  4992.2  351.36  4992.4  350.86  4995.9  350.86  4996.2  351.36
  4999.3  351.36  5008.5  353.68  5034.3  356.83  5039.4  356.17  5044.9  356.61
  5089.5  359.33  5094.6   359.2  5149.9  361.95  5170.8  362.37  5180.9  363.27
  5210.2  364.59  5215.3  364.21  5270.5  366.66  5275.6  366.27  5278.8  366.69
#Mann= 5 ,-1 , 0
    4682     .05       0  4839.1     .12       0  4992.2     .07       0
  4996.2     .12       0  5044.9     .05       0
Bank Sta=4992.2,4996.2
XS Rating Curve= 0 ,0
Exp/Cntr=0.3,0.1

Type RM Length L Ch R = 1 ,2327    ,125,125,125
BEGIN DESCRIPTION:
Lacy 199 114
END DESCRIPTION:
XS GIS Cut Line= 3
      2678899.63      6809206.57      2679176.13      6809171.06
      2679416.33      6809181.52
#Sta/Elev= 30
  4722.7  363.86  4725.6  362.14  4730.7  362.29  4769.4  359.62  4810.3  357.29
    4840  357.15  4900.5   356.1  4910.6  355.53  4920.7  353.53  4940.8  351.62
  4964.4  351.27  4975.2   350.8  4981.2  350.65  4991.3  349.49  4996.9  349.49
  4997.1  348.99  5000.6  348.99  5000.9  349.49  5003.9  349.49  5011.3  354.17
  5021.4  355.36  5041.4  356.66  5071.4  357.07  5081.4  357.65  5110.7  360.38
  5115.7  360.39  5141.5  361.85  5161.5  362.04  5181.5  362.75  5241.9  365.87
#Mann= 4 ,-1 , 0
  4722.7     .12       0  4975.2     .05       0  4996.9     .03       0
  5000.9     .05       0
Bank Sta=4996.9,5000.9
XS Rating Curve= 0 ,0
Exp/Cntr=0.3,0.1

Type RM Length L Ch R = 1 ,2202    ,139,139,139
BEGIN DESCRIPTION:
Lacy 199 112
END DESCRIPTION:
XS GIS Cut Line= 3
      2678886.77        6809292.       2679173.4      6809295.68
      2679432.35      6809296.19
#Sta/Elev= 30
  4711.3  365.86  4740.5  362.16  4770.5  360.19  4780.5  360.13  4820.5  358.15
  4837.1  356.66  4870.5  354.97  4910.5  354.84  4940.5  353.69  4950.5  353.85
  4970.5  351.86  4988.6  347.81  4988.8  347.31  4992.3  347.31  4992.6  347.81
  4996.8  349.15  5001.8  349.15  5010.6  352.66  5020.6  353.29  5030.6  353.63
  5040.6  353.34  5080.6  354.95  5120.6  355.75  5150.6  357.05  5157.8   358.1
  5162.8  357.58  5190.6  360.05  5210.6  360.66  5240.6  362.51  5256.9  364.05
#Mann= 4 ,-1 , 0
  4711.3     .12       0  4837.1     .05       0  4988.6     .03       0
  4992.6     .05       0
Bank Sta=4988.6,4992.6
XS Rating Curve= 0 ,0
Exp/Cntr=0.3,0.1

Type RM Length L Ch R = 1 ,2063    ,73,73,73
BEGIN DESCRIPTION:
Lacy 199 113
END DESCRIPTION:
XS GIS Cut Line= 3
      2678968.81      6809374.34      2679175.08      6809420.41
      2679491.82      6809419.57
#Sta/Elev= 30
  4741.5  359.44  4746.4  358.84  4751.6  358.74    4795  356.31  4820.6  355.37
  4851.3   353.5    4887  352.21  4892.3  351.66  4923.1  350.77  4935.5  350.02
  4955.8  349.88  4973.8  349.08  5003.8  348.66  5031.8  345.82    5032  345.32
  5035.5  345.32  5035.8  345.82  5053.8  349.09  5063.8  350.07  5083.8  352.59
  5093.8  353.39  5103.8  353.49  5123.8  354.53  5153.8  355.62  5173.8  356.78
  5203.8  358.14  5223.8   359.6  5233.8  361.43  5253.8  362.91  5269.6  364.35
#Mann= 3 ,-1 , 0
  4741.5     .05       0  5031.8     .03       0  5035.8     .05       0
Bank Sta=5031.8,5035.8
XS Rating Curve= 0 ,0
Exp/Cntr=0.3,0.1

Type RM Length L Ch R = 1 ,1990    ,140,140,140
BEGIN DESCRIPTION:
Lacy 199 111
END DESCRIPTION:
XS GIS Cut Line= 3
      2678961.96      6809384.58      2679186.94      6809483.01
      2679477.91      6809489.38
#Sta/Elev= 30
  4690.4  359.28  4720.5  357.91  4749.4   355.9  4782.1  354.76  4790.7  353.95
  4796.1  354.27    4814  353.54  4819.5  353.98  4842.9  352.36  4848.4   352.5
  4913.1   349.5    4955  348.92    4965   347.4    4983  345.72  4983.3  345.22
  4986.8  345.22    4987  345.72    4995  346.02    5005  347.09    5035  348.58
  5065.1  349.44  5071.3  349.97  5076.3  349.53  5085.1  350.46  5105.1  351.19
  5145.1  354.36  5165.1  355.49  5195.1   358.2  5205.1  359.61    5227  360.61
#Mann= 3 ,-1 , 0
  4690.4     .05       0    4983     .03       0    4987     .05       0
Bank Sta=4983,4987
XS Rating Curve= 0 ,0
Exp/Cntr=0.3,0.1

Type RM Length L Ch R = 1 ,1850    ,132,132,132
BEGIN DESCRIPTION:
Lacy 199 109
END DESCRIPTION:
XS GIS Cut Line= 3
      2678998.92      6809608.77      2679276.63      6809617.45
      2679491.87      6809619.58
#Sta/Elev= 30
    4724  360.09  4761.1   357.2  4851.1   352.2  4871.2  351.47  4901.2  349.03
  4921.2  348.06  4941.2  347.61  4955.8  346.85  4961.2   345.5  4971.2  341.95
  4979.2  340.85  4979.5  340.35    4983  340.35  4983.2  340.85  4991.2  342.95
    4999     344    5004     344  5011.2  344.47  5021.2  345.35  5041.2  347.82
  5051.2  348.28  5061.2  349.52  5071.2  350.32  5121.2  351.33  5141.2  353.06
  5161.2  353.55  5181.2  355.47  5201.2  355.86  5211.2  356.44  5217.1  358.46
#Mann= 3 ,-1 , 0
    4724     .05       0  4979.2     .05       0  4983.2     .05       0
Bank Sta=4979.2,4983.2
XS Rating Curve= 0 ,0
Exp/Cntr=0.3,0.1

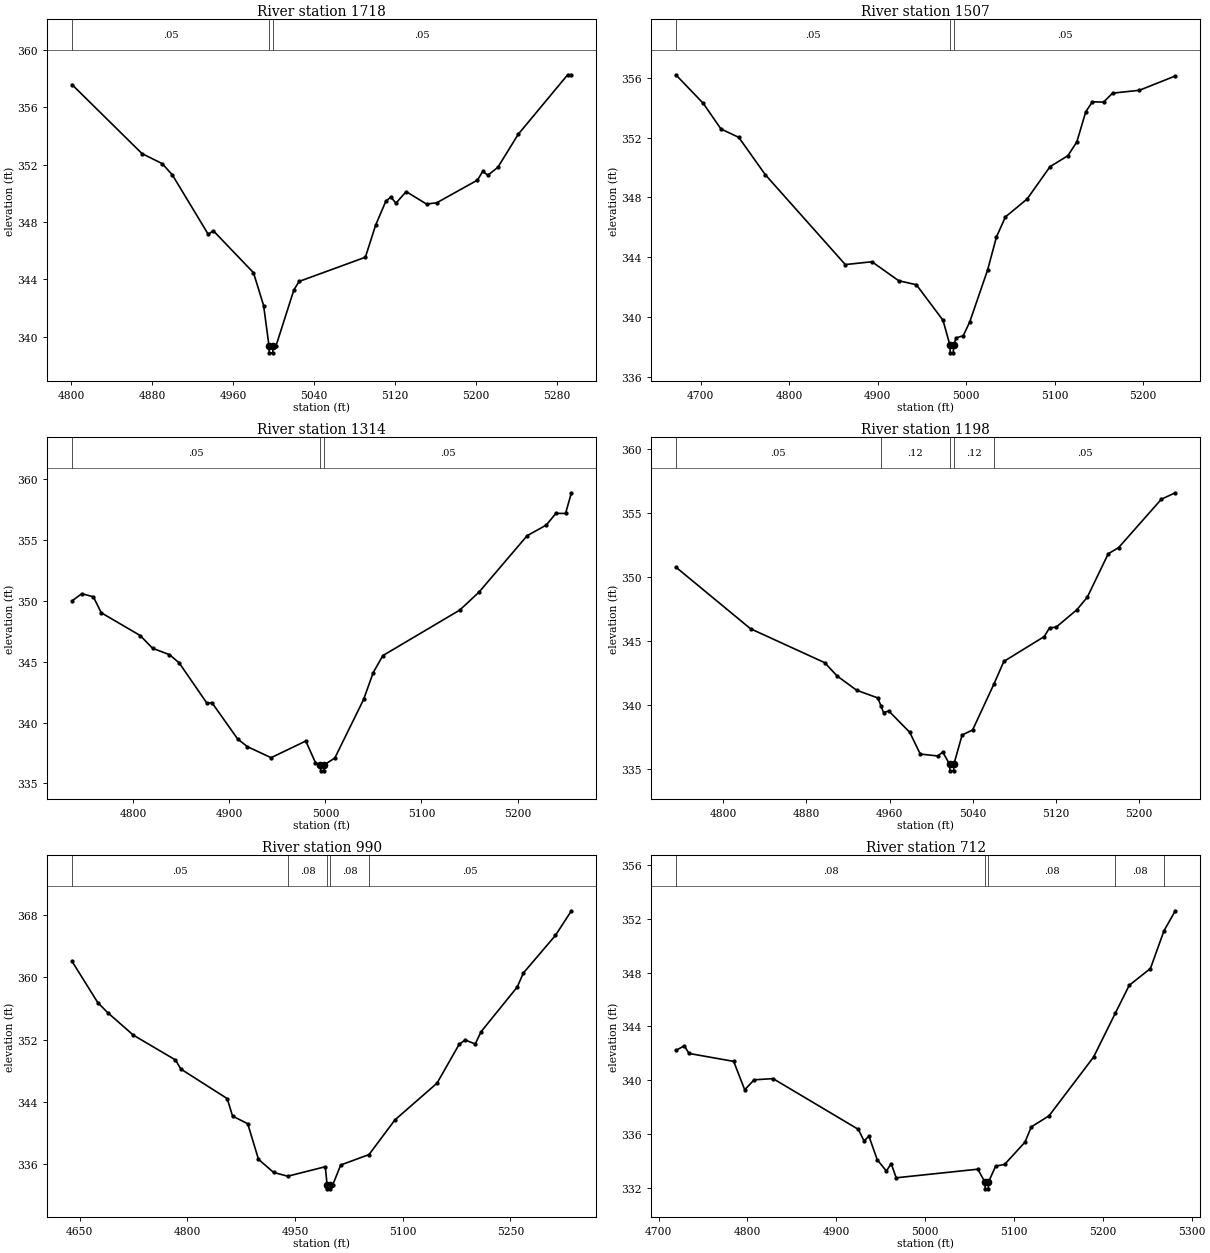
Type RM Length L Ch R = 1 ,1718    ,211,211,211
BEGIN DESCRIPTION:
Lacy 199 107
END DESCRIPTION:
XS GIS Cut Line= 3
       2679026.9      6809741.86      2679225.57      6809733.22
      2679518.23      6809765.61
#Sta/Elev= 30
  4800.9  357.59  4870.1  352.77  4890.1  352.07  4900.1  351.28  4935.5  347.14
  4940.5  347.39  4980.2  344.46  4990.2  342.17  4995.5  339.37  4995.7  338.87
  4999.2  338.87  4999.5  339.37  5002.5  339.37  5020.1  343.26  5025.2  343.85
  5090.7  345.54  5100.8  347.77  5110.9  349.45  5115.9  349.74  5120.9  349.31
    5131  350.12  5151.1  349.25  5161.2  349.34  5201.4  350.92  5206.6  351.53
  5211.7  351.26  5221.5  351.81  5241.7  354.12  5290.5  358.27  5294.2  358.27
#Mann= 3 ,-1 , 0
  4800.9     .05       0  4995.5     .03       0  4999.5     .05       0
Bank Sta=4995.5,4999.5
XS Rating Curve= 0 ,0
Exp/Cntr=0.3,0.1

Type RM Length L Ch R = 1 ,1507    ,193,193,193
BEGIN DESCRIPTION:
Lacy 199 108
END DESCRIPTION:
XS GIS Cut Line= 3
      2678995.17      6809878.83      2679318.81      6809906.71
      2679556.34      6809937.89
#Sta/Elev= 30
    4672  356.21  4702.9   354.3    4723  352.58  4743.1  352.02  4773.2  349.51
  4863.5   343.5  4893.6  343.69  4923.8  342.42  4943.8  342.15  4973.9  339.77
  4981.8  338.09    4982  337.59  4985.5  337.59  4985.8  338.09  4988.8  338.59
  4996.8  338.74  5004.1  339.66  5024.3  343.14  5034.3  345.35  5044.4  346.69
  5068.9  347.89  5094.9  350.06    5115  350.79  5125.1  351.71  5135.2  353.73
  5142.7   354.4  5155.4  354.38  5165.5  354.98  5195.7  355.17  5236.4  356.13
#Mann= 3 ,-1 , 0
    4672     .05       0  4981.8     .03       0  4985.8     .05       0
Bank Sta=4981.8,4985.8
XS Rating Curve= 0 ,0
Exp/Cntr=0.3,0.1

Type RM Length L Ch R = 1 ,1314    ,116,116,116
BEGIN DESCRIPTION:
Lacy 199 106
END DESCRIPTION:
XS GIS Cut Line= 3
      2679015.87      6810042.93      2679275.21      6810084.98
      2679532.14      6810080.27
#Sta/Elev= 30
  4736.3  349.99  4746.6  350.59  4758.6  350.33  4766.8  349.02  4807.3  347.15
  4820.2   346.1  4837.7  345.58  4847.9   344.9  4876.8  341.58  4881.9  341.64
  4908.7  338.65  4918.8  338.02  4943.5  337.11  4979.6  338.48  4989.7   336.7
  4994.9  336.53  4995.1  336.03  4998.6  336.03  4998.9  336.53  5009.8  337.08
  5039.8   341.9  5049.8  344.11  5059.8   345.5  5139.8  349.24  5159.8  350.71
  5209.9  355.35  5229.9  356.23  5239.9  357.19  5249.9  357.18    5256  358.88
#Mann= 3 ,-1 , 0
  4736.3     .05       0  4994.9     .03       0  4998.9     .05       0
Bank Sta=4994.9,4998.9
XS Rating Curve= 0 ,0
Exp/Cntr=0.3,0.1

Type RM Length L Ch R = 1 ,1198    ,208,208,208
BEGIN DESCRIPTION:
Lacy 199 105
END DESCRIPTION:
XS GIS Cut Line= 3
       2678985.6      6810134.93      2679225.59       6810185.2
      2679460.32      6810207.66
#Sta/Elev= 30
  4754.2  350.78  4826.1  345.97  4897.6  343.32  4909.4  342.29  4928.3  341.17
  4948.7  340.57  4951.6  339.97  4954.2  339.43  4959.3  339.55  4979.4  337.89
  4989.6  336.19  5006.3  336.04  5011.3  336.34  5017.9  335.38  5018.2  334.88
  5021.7  334.88  5021.9  335.38  5029.9  337.68    5040  338.07  5060.5  341.65
  5070.1  343.42    5109  345.36  5114.1  346.04  5120.4  346.09  5140.4  347.45
  5150.5  348.44  5170.6  351.82  5180.6   352.3  5221.8  356.08  5235.2  356.58
#Mann= 5 ,-1 , 0
  4754.2     .05       0  4951.6     .12       0  5017.9     .07       0
  5021.9     .12       0  5060.5     .05       0
Bank Sta=5017.9,5021.9
XS Rating Curve= 0 ,0
Exp/Cntr=0.3,0.1

Type RM Length L Ch R = 1 ,990     ,278,278,278
BEGIN DESCRIPTION:
Lacy 199 81
END DESCRIPTION:
XS GIS Cut Line= 3
      2678826.02      6810161.01        2679126.        6810361.
      2679425.96      6810510.98
#Sta/Elev= 30
  4639.2  362.05  4675.2  356.74  4688.8  355.47  4724.8  352.56  4783.4  349.38
  4790.9  348.21  4855.5  344.42    4863  342.17  4884.1  341.19  4899.1  336.62
  4920.1  334.94  4939.8  334.45  4992.2  335.67  4994.7  333.33    4995  332.83
  4998.5  332.83  4998.7  333.33  5002.5  333.33  5013.7  335.89  5053.1  337.23
  5089.2  341.68  5147.9   346.4  5178.6  351.37    5187  351.95    5201  351.42
  5209.4  353.02  5259.7  358.75  5268.1  360.53  5312.8  365.36  5335.1  368.53
#Mann= 5 ,-1 , 0
  4639.2     .05       0  4939.8     .08       0  4994.7     .07       0
  4998.7     .08       0  5053.1     .05       0
Bank Sta=4994.7,4998.7
XS Rating Curve= 0 ,0
Exp/Cntr=0.3,0.1

Type RM Length L Ch R = 1 ,712     ,197,197,197
BEGIN DESCRIPTION:
Lacy 199 104
END DESCRIPTION:
XS GIS Cut Line= 3
      2678713.33      6810482.24      2678972.92      6810577.96
      2679257.74      6810598.06
#Sta/Elev= 30
  4719.4  342.21  4728.9  342.56  4734.2  341.99  4784.5   341.4  4796.9  339.29
  4807.5  340.03  4828.8  340.12  4924.8  336.35  4931.3  335.48  4936.7  335.85
  4946.1  334.09  4956.4  333.25  4961.8  333.81  4967.4  332.75  5059.3  333.39
  5067.3  332.43  5067.6  331.93  5071.1  331.93  5071.3  332.43  5079.4  333.62
  5089.4  333.74  5112.4   335.4  5119.5  336.53  5139.5  337.36  5189.6  341.72
    5214  344.97  5229.7  347.05  5253.6   348.3  5268.9  351.11  5281.6  352.59
#Mann= 5 ,-1 , 0
  4719.4     .08       0  5067.3     .08       0  5071.3     .08       0
    5214     .08       0  5268.9     .12       0
Bank Sta=5067.3,5071.3
XS Rating Curve= 0 ,0
Exp/Cntr=0.3,0.1

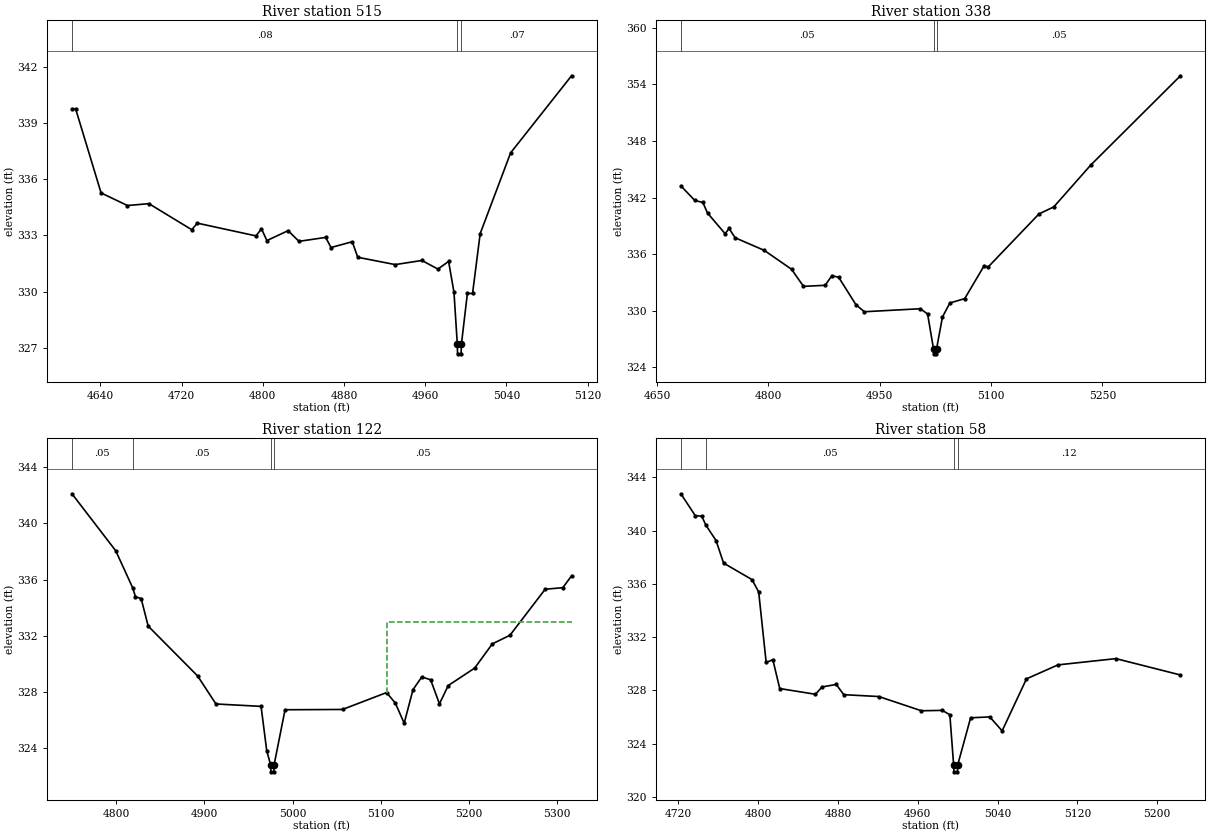
Type RM Length L Ch R = 1 ,515     ,177,177,177
BEGIN DESCRIPTION:
Lacy 199 80
END DESCRIPTION:
XS GIS Cut Line= 3
      2678654.08       6810636.8        2679026.        6810761.
      2679125.99        6810761.
#Sta/Elev= 30
    4612  339.75  4615.6  339.75  4640.7  335.26  4666.7  334.59  4687.8  334.69
    4730   333.3  4735.5  333.65  4793.3  332.97  4798.7  333.35    4804  332.72
  4824.9  333.25  4835.6  332.68  4861.9  332.89  4867.2  332.35  4888.1  332.66
  4893.5  331.83  4930.4  331.44  4956.7  331.66  4972.5   331.2    4983  331.61
  4988.3  329.96  4991.6  327.18  4991.8  326.68  4995.3  326.68  4995.6  327.18
  5001.5   329.9  5006.6   329.9  5014.1  333.09  5044.1   337.4  5104.1  341.51
#Mann= 3 ,-1 , 0
    4612     .08       0  4991.6     .04       0  4995.6     .07       0
Bank Sta=4991.6,4995.6
XS Rating Curve= 0 ,0
Exp/Cntr=0.3,0.1

Type RM Length L Ch R = 1 ,338     ,216,216,216
BEGIN DESCRIPTION:
Lacy 199 593
END DESCRIPTION:
XS GIS Cut Line= 3
       2678638.7      6810781.69      2678931.41      6810905.45
      2679286.61      6810907.58
#Sta/Elev= 30
  4682.2  343.24    4701  341.69  4711.8  341.48  4718.1  340.36  4741.8  338.17
  4747.2  338.72  4755.3  337.74  4794.6   336.4  4831.3   334.4  4847.4  332.59
  4876.6   332.7  4885.6  333.72  4894.8  333.55  4918.1  330.64  4929.4   329.9
  5004.8  330.22  5014.6  329.66  5022.6  325.94  5022.8  325.44  5026.3  325.44
  5026.6  325.94  5034.6  329.34  5044.6  330.83  5064.6  331.29  5090.9  334.79
  5095.9  334.62  5164.6  340.26  5184.6  341.01  5234.6  345.46  5355.2   354.9
#Mann= 3 ,-1 , 0
  4682.2     .05       0  5022.6     .05       0  5026.6     .05       0
Bank Sta=5022.6,5026.6
XS Rating Curve= 0 ,0
Exp/Cntr=0.3,0.1

Type RM Length L Ch R = 1 ,122     ,64,64,64
BEGIN DESCRIPTION:
Lacy 199 103
END DESCRIPTION:
XS GIS Cut Line= 3
      2678622.99      6810863.37       2678779.3      6811058.86
       2679095.9       6811057.5
#Sta/Elev= 30
  4749.7  342.09  4799.4  338.04  4818.7   335.4  4821.8  334.77  4828.2  334.65
  4836.2  332.69  4892.3  329.15  4913.1  327.16  4964.3  326.99  4970.7  323.85
  4975.1  322.84  4975.4  322.34  4978.9  322.34  4979.1  322.84  4991.5  326.75
  5056.7  326.77  5106.7  327.97  5116.7  327.22  5126.7  325.79  5136.7  328.18
  5146.7  329.08  5156.7  328.88  5166.7  327.17  5176.7  328.47  5206.7  329.71
  5226.7  331.43  5246.7  332.04  5286.7  335.31  5306.7  335.42  5316.6  336.26
#Mann= 4 ,-1 , 0
  4749.7     .05       0  4818.7     .05       0  4975.1     .03       0
  4979.1     .05       0
#XS Ineff= 2 , 0
       0                    5107       0     333
Permanent Ineff=
       F       F
Bank Sta=4975.1,4979.1
XS Rating Curve= 0 ,0
Exp/Cntr=0.3,0.1

Type RM Length L Ch R = 1 ,58      ,0,0,0
BEGIN DESCRIPTION:
Lacy 199 592
END DESCRIPTION:
XS GIS Cut Line= 3
       2678550.2      6810896.67      2678733.76      6811104.79
      2678945.48      6811175.45
#Sta/Elev= 30
  4722.5  342.77  4736.9  341.13  4743.5  341.08  4747.6  340.41  4757.8  339.25
  4765.3  337.56  4793.8  336.32  4800.5  335.39    4808  330.09  4814.7   330.3
  4821.6  328.13  4857.4   327.7    4864  328.25  4878.2  328.44  4885.8  327.67
  4920.9  327.53  4963.6  326.46  4984.5  326.49  4992.1  326.16  4995.9  322.37
  4996.2  321.87  4999.7  321.87  4999.9  322.37  5012.9  325.93  5032.1     326
  5044.5  324.95  5068.9  328.86  5100.5  329.91  5158.5  330.38  5223.2  329.15
#Mann= 4 ,-1 , 0
  4722.5     .05       0  4747.6     .05       0  4995.9     .08       0
  4999.9     .12       0
Bank Sta=4995.9,4999.9
XS Rating Curve= 0 ,0
Exp/Cntr=0.3,0.1

Chan Stop Cuts=-1
Use User Specified Reach Order=0
Composite Channel Slope=5