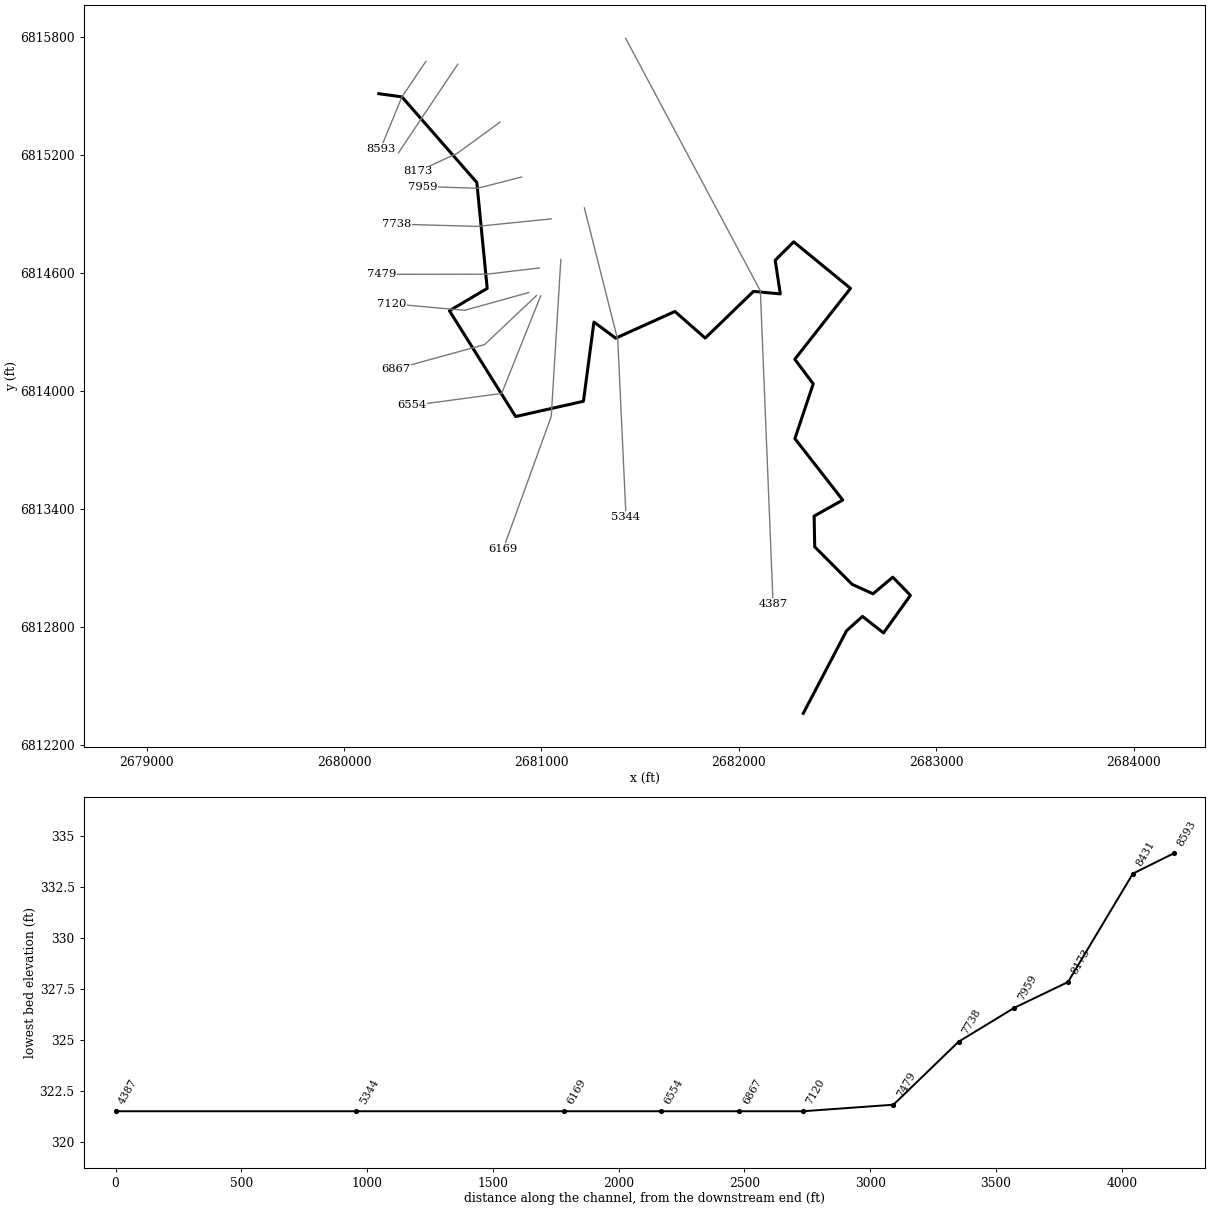
--- Lacy 200.prj (project) ---

Proj Title=Lacy 200 Base Level Engineering
Current Plan=p01
Default Exp/Contr=0.3,0.1
English Units
Geom File=g01
Flow File=f01
Plan File=p01
BEGIN DESCRIPTION:
Lacy 200
END DESCRIPTION:

--- Lacy 200.p01 (plan) ---

Plan Title=Multiple Run
Short Identifier=Multiple
Geom File=g01
Flow File=f01
Subcritical Flow
K Sum by GR= 0
Std Step Tol= 0.01
Critical Tol= 0.01
Num of Std Step Trials= 20
Max Error Tol= 0.3
Flow Tol Ratio= 0.001
Split Flow NTrial= 30
Split Flow Tol= 0.02
Split Flow Ratio= 0.02
Log Output Level= 0
Friction Slope Method= 1
Unsteady Friction Slope Method= 2
Unsteady Bridges Friction Slope Method= 1
Parabolic Critical Depth
Global Vel Dist=  1 , 1 , 1
Global Log Level= 0
CheckData=True
Encroach Param= -1, 0, 0, 0
BEGIN DESCRIPTION:
Multiple Run
END DESCRIPTION:

--- Lacy 200.f01 (steady flow) ---

Flow Title=Multiple
Number of Profiles=7
Profile Names=10-year,25-year,50-year,1pct_min,100-year,1pct_plu,500-year
River Rch & RM= Lacy 200,Reach-1,8593
     212     266     306     175     350     698     456
River Rch & RM= Lacy 200,Reach-1,6169
     325     413     479     276     551    1099     727
Boundary for River Rch & Prof#=Lacy 200,Reach-1,1
Up Type=0
Dn Type=3
Dn Slope=0.005
Boundary for River Rch & Prof#=Lacy 200,Reach-1,2
Up Type=0
Dn Type=3
Dn Slope=0.005
Boundary for River Rch & Prof#=Lacy 200,Reach-1,3
Up Type=0
Dn Type=3
Dn Slope=0.005
Boundary for River Rch & Prof#=Lacy 200,Reach-1,4
Up Type=0
Dn Type=3
Dn Slope=0.005
Boundary for River Rch & Prof#=Lacy 200,Reach-1,5
Up Type=0
Dn Type=3
Dn Slope=0.005
Boundary for River Rch & Prof#=Lacy 200,Reach-1,6
Up Type=0
Dn Type=3
Dn Slope=0.005
Boundary for River Rch & Prof#=Lacy 200,Reach-1,7
Up Type=0
Dn Type=3
Dn Slope=0.005

--- Lacy 200.g01 (geometry) ---

Geom Title=Existing Conditions

River Reach=Lacy 200,Reach-1
Reach XY= 30
      2680176.00      6815511.00      2680293.18      6815494.74
      2680672.53      6815059.50      2680725.07      6814521.15
      2680533.76      6814407.62      2680869.05      6813869.85
      2681212.54      6813947.43      2681265.63      6814350.19
      2681376.00      6814268.12      2681676.00      6814403.92
      2681829.33      6814268.59      2682073.71      6814505.88
      2682209.61      6814493.36      2682183.79      6814664.43
      2682277.68      6814757.90      2682565.20      6814521.37
      2682283.10      6814161.00      2682376.48      6814036.03
      2682283.60      6813757.65      2682525.97      6813445.46
      2682381.11      6813363.83      2682383.99      6813207.66
      2682573.71      6813016.80      2682679.41      6812968.80
      2682779.36      6813053.39      2682868.72      6812961.11
      2682732.68      6812769.96      2682625.98      6812853.90
      2682545.37      6812781.09      2682326.00      6812361.00

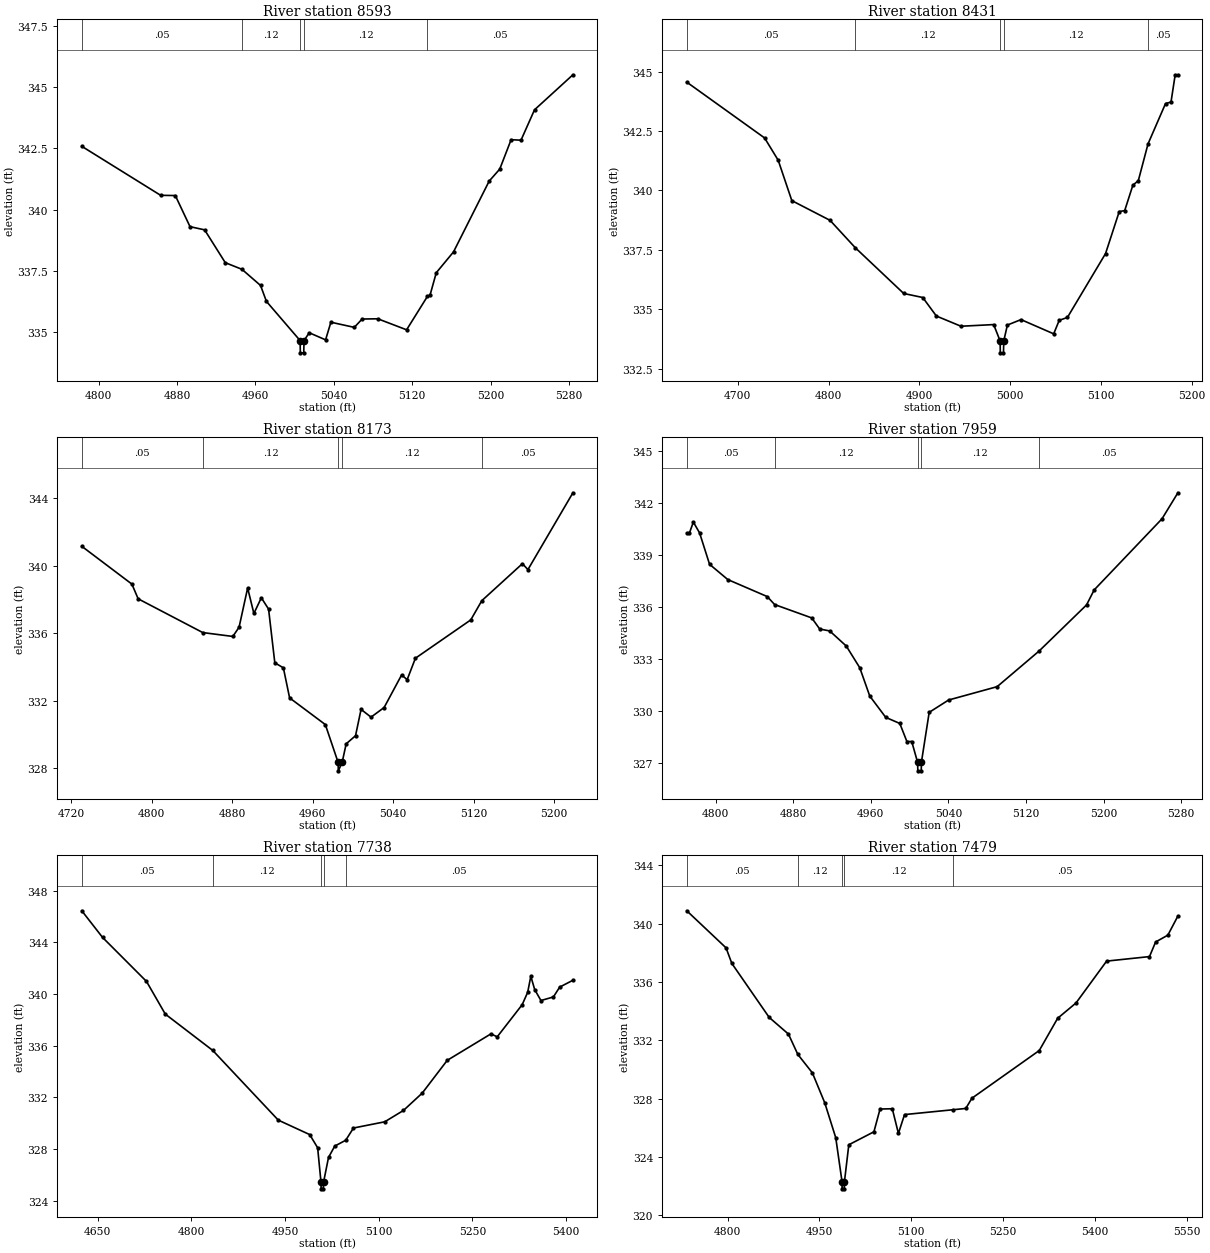
Type RM Length L Ch R = 1,8593,162,162,162
BEGIN DESCRIPTION:
Lacy 200 92
END DESCRIPTION:
XS GIS Cut Line= 3
      2680414.46      6815675.04      2680293.18      6815494.74
      2680185.22      6815231.95
#Sta/Elev= 30
  4782.7  342.58  4863.2  340.58  4878.2  340.57  4893.2  339.30  4908.1  339.17
  4929.2  337.83  4946.2  337.56  4965.2  336.90  4971.2  336.25  5005.6  334.65
  5005.8  334.15  5009.3  334.15  5009.6  334.65  5014.9  334.97  5031.6  334.68
  5037.0  335.40  5060.9  335.19  5068.9  335.53  5084.9  335.54  5114.3  335.09
  5135.5  336.45  5138.2  336.50  5144.6  337.42  5162.2  338.27  5198.6  341.16
  5209.4  341.65  5221.0  342.85  5231.1  342.83  5244.9  344.07  5284.1  345.50
#Mann=5,-1,0
  4782.7    0.05       0  4946.2    0.12       0  5005.6    0.07       0
  5009.6    0.12       0  5135.5    0.05       0
Bank Sta=5005.6,5009.6
Exp/Cntr=0.3,0.1

Type RM Length L Ch R = 1,8431,258,258,258
BEGIN DESCRIPTION:
Lacy 200 60
END DESCRIPTION:
XS GIS Cut Line= 3
      2680576.01      6815661.02      2680376.00      6815361.00
      2680275.98      6815210.97
#Sta/Elev= 30
  4643.9  344.56  4729.6  342.21  4744.6  341.27  4759.6  339.57  4801.7  338.74
  4829.4  337.59  4882.8  335.66  4903.8  335.49  4918.8  334.71  4945.9  334.28
  4981.9  334.35  4989.0  333.66  4989.2  333.16  4992.7  333.16  4993.0  333.66
  4997.0  334.33  5012.0  334.56  5048.0  333.96  5054.1  334.53  5063.1  334.65
  5105.1  337.34  5120.2  339.11  5126.2  339.15  5135.2  340.22  5141.2  340.41
  5151.9  341.96  5171.2  343.66  5177.2  343.72  5181.8  344.87  5184.8  344.87
#Mann=5,-1,0
  4643.9    0.05       0  4829.4    0.12       0  4989.0    0.07       0
  4993.0    0.12       0  5151.9    0.05       0
Bank Sta=4989,4993
Exp/Cntr=0.3,0.1

Type RM Length L Ch R = 1,8173,214,214,214
BEGIN DESCRIPTION:
Lacy 200 100
END DESCRIPTION:
XS GIS Cut Line= 3
      2680789.85      6815366.40      2680574.97      6815208.86
      2680374.06      6815115.49
#Sta/Elev= 30
  4730.6  341.14  4780.4  338.90  4786.6  338.03  4850.8  336.03  4880.7  335.80
  4886.9  336.35  4895.4  338.67  4901.6  337.16  4909.0  338.09  4916.2  337.42
  4922.4  334.24  4930.9  333.94  4937.1  332.16  4972.6  330.58  4985.3  328.34
  4985.5  327.84  4989.3  328.34  4993.3  329.44  5002.6  329.92  5008.1  331.48
  5018.0  331.02  5031.0  331.59  5048.4  333.52  5053.9  333.24  5062.1  334.51
  5117.1  336.78  5128.1  337.92  5168.4  340.11  5173.9  339.76  5218.6  344.31
#Mann=5,-1,0
  4730.6    0.05       0  4850.8    0.12       0  4985.3    0.07       0
  4989.3    0.12       0  5128.1    0.05       0
Bank Sta=4985.3,4989.3
Exp/Cntr=0.3,0.1

Type RM Length L Ch R = 1,7959,221,221,221
BEGIN DESCRIPTION:
Lacy 200 101
END DESCRIPTION:
XS GIS Cut Line= 3
      2680898.80      6815087.36      2680676.99      6815030.31
      2680399.65      6815039.06
#Sta/Elev= 30
  4770.2  340.27  4772.9  340.27  4777.0  340.90  4783.4  340.28  4793.7  338.47
  4812.5  337.59  4853.2  336.61  4860.8  336.15  4899.1  335.38  4907.3  334.74
  4917.6  334.63  4934.7  333.76  4948.6  332.51  4958.9  330.88  4975.4  329.65
  4989.9  329.30  4997.2  328.26  5002.2  328.26  5008.2  327.07  5008.5  326.57
  5012.0  326.57  5012.2  327.07  5020.2  329.94  5040.2  330.65  5090.3  331.42
  5133.5  333.47  5182.5  336.13  5190.3  336.99  5260.3  341.09  5276.7  342.59
#Mann=5,-1,0
  4770.2    0.05       0  4860.8    0.12       0  5008.2    0.07       0
  5012.2    0.12       0  5133.5    0.05       0
Bank Sta=5008.2,5012.2
Exp/Cntr=0.3,0.1

Type RM Length L Ch R = 1,7738,259,259,259
BEGIN DESCRIPTION:
Lacy 200 99
END DESCRIPTION:
XS GIS Cut Line= 3
      2681049.04      6814874.47      2680673.34      6814836.40
      2680264.83      6814847.94
#Sta/Elev= 30
  4624.7  346.44  4657.9  344.38  4728.3  340.97  4758.4  338.44  4834.3  335.63
  4939.3  330.23  4989.6  329.11  5002.3  328.09  5007.7  325.41  5007.9  324.91
  5011.4  324.91  5011.7  325.41  5019.7  327.34  5029.7  328.22  5047.2  328.67
  5059.7  329.62  5109.7  330.10  5139.7  330.98  5169.7  332.32  5209.8  334.86
  5279.8  336.91  5289.8  336.68  5329.8  339.17  5338.6  340.13  5343.6  341.37
  5349.8  340.34  5359.8  339.49  5379.8  339.77  5389.8  340.53  5411.0  341.06
#Mann=5,-1,0
  4624.7    0.05       0  4834.3    0.12       0  5007.7    0.07       0
  5011.7    0.12       0  5047.2    0.05       0
Bank Sta=5007.7,5011.7
Exp/Cntr=0.3,0.1

Type RM Length L Ch R = 1,7479,359,359,359
BEGIN DESCRIPTION:
Lacy 200 98
END DESCRIPTION:
XS GIS Cut Line= 3
      2680989.68      6814625.29      2680722.98      6814593.33
      2680189.59      6814592.78
#Sta/Elev= 30
  4733.4  340.88  4797.5  338.34  4807.0  337.27  4868.0  333.57  4899.4  332.43
  4914.8  331.03  4938.5  329.77  4958.7  327.72  4976.7  325.32  4986.9  322.32
  4987.1  321.82  4990.6  321.82  4990.9  322.32  4998.0  324.84  5039.0  325.73
  5049.0  327.29  5069.0  327.31  5079.0  325.62  5089.0  326.91  5167.7  327.24
  5189.0  327.33  5199.0  328.03  5309.0  331.30  5339.0  333.51  5369.0  334.56
  5419.0  337.43  5489.0  337.74  5499.0  338.74  5519.0  339.21  5535.4  340.52
#Mann=5,-1,0
  4733.4    0.05       0  4914.8    0.12       0  4986.9    0.07       0
  4990.9    0.12       0  5167.7    0.05       0
Bank Sta=4986.9,4990.9
Exp/Cntr=0.3,0.1

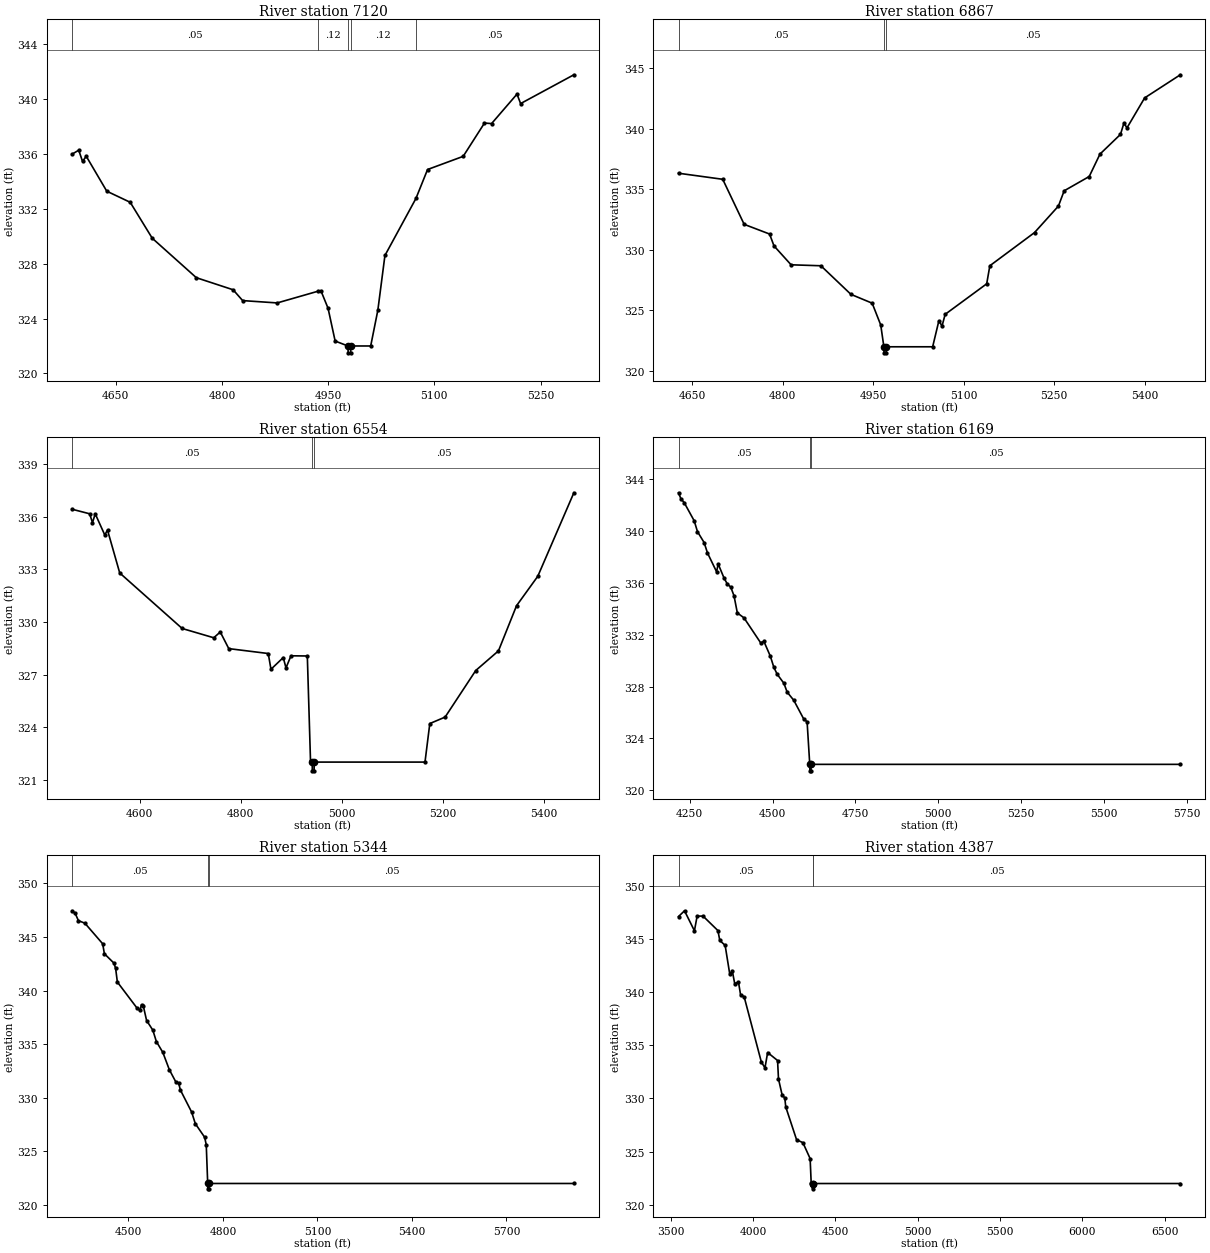
Type RM Length L Ch R = 1,7120,253,253,253
BEGIN DESCRIPTION:
Lacy 200 97
END DESCRIPTION:
XS GIS Cut Line= 3
      2680935.07      6814500.02      2680610.71      6814409.78
      2680240.28      6814443.12
#Sta/Elev= 30
  4588.4  335.99  4597.8  336.28  4603.2  335.46  4608.4  335.84  4637.4  333.29
  4670.5  332.48  4701.6  329.86  4763.9  326.98  4815.8  326.10  4829.3  325.31
  4878.1  325.14  4936.1  326.00  4939.8  326.03  4949.9  324.75  4959.9  322.36
  4978.0  322.00  4978.3  321.50  4981.8  321.50  4982.0  322.00  5010.1  322.00
  5020.2  324.61  5030.2  328.60  5074.0  332.76  5090.4  334.87  5140.7  335.83
  5170.8  338.26  5180.8  338.22  5216.7  340.37  5221.8  339.68  5297.0  341.78
#Mann=5,-1,0
  4588.4    0.05       0  4936.1    0.12       0  4978.0    0.07       0
  4982.0    0.12       0  5074.0    0.05       0
Bank Sta=4978,4982
Exp/Cntr=0.3,0.1

Type RM Length L Ch R = 1,6867,313,313,313
BEGIN DESCRIPTION:
Lacy 200 96
END DESCRIPTION:
XS GIS Cut Line= 3
      2680975.15      6814485.34      2680711.57      6814235.36
      2680260.49      6814111.28
#Sta/Elev= 30
  4627.8  336.33  4701.0  335.83  4736.5  332.11  4778.6  331.31  4785.9  330.33
  4814.2  328.77  4863.6  328.69  4913.3  326.33  4948.5  325.60  4962.7  323.80
  4967.9  322.00  4968.2  321.50  4971.7  321.50  4971.9  322.00  5048.7  322.00
  5059.0  324.15  5064.2  323.71  5069.4  324.68  5138.2  327.20  5143.4  328.69
  5217.4  331.43  5257.0  333.62  5266.5  334.88  5308.0  336.06  5325.8  337.91
  5359.8  339.54  5365.4  340.46  5370.6  340.08  5399.8  342.55  5458.9  344.46
#Mann=3,-1,0
  4627.8    0.05       0  4967.9    0.03       0  4971.9    0.05       0
Bank Sta=4967.9,4971.9
Exp/Cntr=0.3,0.1

Type RM Length L Ch R = 1,6554,385,385,385
BEGIN DESCRIPTION:
Lacy 200 95
END DESCRIPTION:
XS GIS Cut Line= 3
      2680996.06      6814483.30      2680798.30      6813987.39
      2680343.61      6813925.98
#Sta/Elev= 30
  4466.3  336.44  4501.1  336.18  4506.7  335.67  4512.1  336.18  4531.0  334.97
  4536.4  335.25  4560.6  332.80  4684.1  329.63  4746.6  329.10  4759.5  329.43
  4776.3  328.48  4854.4  328.20  4859.8  327.30  4884.1  327.97  4889.5  327.38
  4899.4  328.07  4931.7  328.06  4938.0  322.08  4941.4  322.00  4941.6  321.50
  4945.1  321.50  4945.4  322.00  5164.5  322.00  5174.0  324.20  5204.3  324.57
  5264.9  327.23  5309.8  328.35  5345.6  330.93  5387.6  332.61  5459.0  337.38
#Mann=3,-1,0
  4466.3    0.05       0  4941.4    0.03       0  4945.4    0.05       0
Bank Sta=4941.4,4945.4
Exp/Cntr=0.3,0.1

Type RM Length L Ch R = 1,6169,825,825,825
BEGIN DESCRIPTION:
Lacy 200 94
END DESCRIPTION:
XS GIS Cut Line= 3
      2681098.13      6814668.09      2681049.49      6813870.47
      2680806.96      6813198.40
#Sta/Elev= 30
  4216.4  342.95  4223.5  342.49  4233.5  342.19  4263.6  340.79  4273.6  339.95
  4293.6  339.11  4303.7  338.31  4331.1  336.86  4336.1  337.45  4353.7  336.37
  4363.8  335.90  4373.8  335.68  4383.8  335.00  4393.8  333.68  4413.9  333.30
  4464.0  331.38  4474.0  331.48  4493.4  330.34  4504.0  329.48  4514.0  328.95
  4534.1  328.26  4544.1  327.57  4564.1  326.94  4594.2  325.49  4604.2  325.29
  4612.2  322.00  4612.5  321.50  4616.0  321.50  4616.2  322.00  5730.0  322.00
#Mann=3,-1,0
  4216.4    0.05       0  4612.2    0.03       0  4616.2    0.05       0
Bank Sta=4612.2,4616.2
Exp/Cntr=0.3,0.1

Type RM Length L Ch R = 1,5344,957,957,957
BEGIN DESCRIPTION:
Lacy 200 93
END DESCRIPTION:
XS GIS Cut Line= 3
      2681217.33      6814930.48      2681386.45      6814258.85
      2681428.27      6813359.32
#Sta/Elev= 30
  4321.0  347.45  4330.8  347.22  4341.1  346.53  4361.7  346.29  4418.2  344.37
  4423.6  343.44  4454.1  342.56  4459.3  342.07  4464.8  340.80  4526.7  338.39
  4536.3  338.16  4541.5  338.69  4547.3  338.55  4557.6  337.21  4577.4  336.31
  4588.6  335.25  4609.2  334.23  4629.8  332.62  4650.5  331.47  4659.6  331.34
  4664.8  330.73  4700.7  328.66  4712.3  327.58  4741.8  326.32  4747.0  325.62
  4751.6  322.00  4751.8  321.50  4755.3  321.50  4755.6  322.00  5914.1  322.00
#Mann=3,-1,0
  4321.0    0.05       0  4751.6    0.03       0  4755.6    0.05       0
Bank Sta=4751.6,4755.6
Exp/Cntr=0.3,0.1

Type RM Length L Ch R = 1,4387,0,0,0
BEGIN DESCRIPTION:
Lacy 200 90
END DESCRIPTION:
XS GIS Cut Line= 3
      2681426.25      6815792.31      2682108.69      6814508.51
      2682173.11      6812916.72
#Sta/Elev= 30
  3547.4  347.09  3583.7  347.63  3643.9  345.75  3660.3  347.13  3696.1  347.13
  3786.5  345.77  3798.0  344.84  3830.4  344.38  3858.1  341.71  3874.4  341.94
  3888.6  340.78  3911.3  340.94  3924.0  339.75  3946.0  339.54  4050.2  333.42
  4072.2  332.87  4088.5  334.31  4148.7  333.56  4154.4  331.82  4176.4  330.33
  4192.7  330.04  4198.4  329.20  4264.3  326.11  4302.6  325.84  4346.5  324.34
  4353.0  322.01  4360.9  322.00  4361.1  321.50  4364.9  322.00  6594.4  322.00
#Mann=3,-1,0
  3547.4    0.05       0  4360.9    0.03       0  4364.9    0.05       0
Bank Sta=4360.9,4364.9
Exp/Cntr=0.3,0.1

Chan Stop Cuts=-1