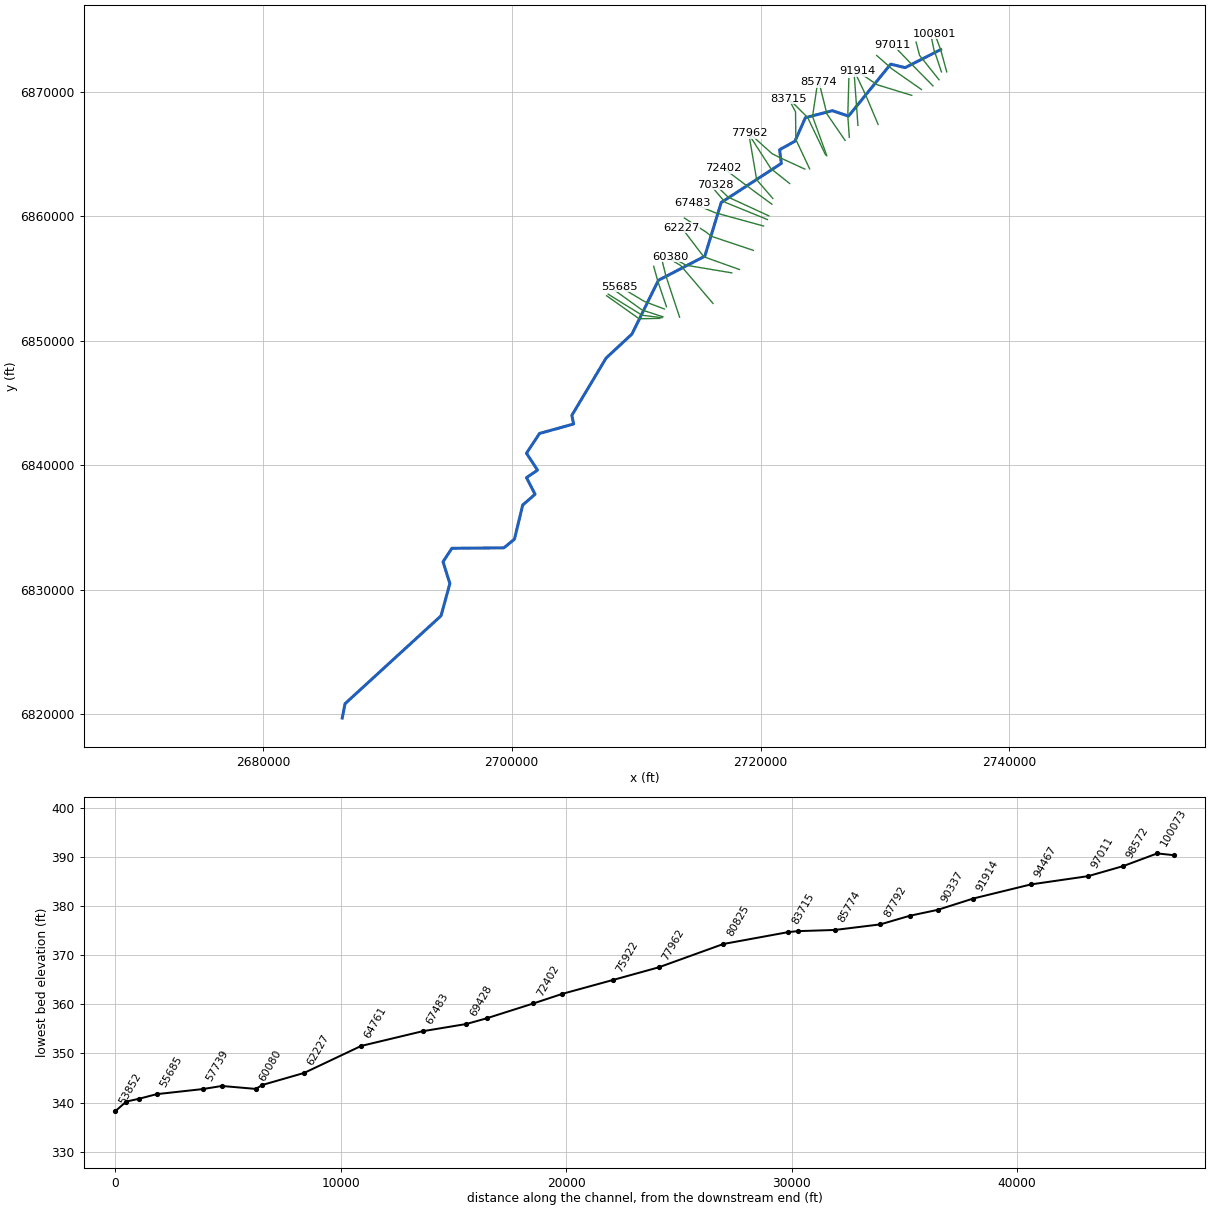
--- Lacy Fork.prj (project) ---

Proj Title=Lacy Fork Base Level Engineering
Current Plan=p01
Default Exp/Contr=0.3,0.1
English Units
Geom File=g01
Flow File=f01
Plan File=p01
BEGIN DESCRIPTION:
Lacy Fork
END DESCRIPTION:

--- Lacy Fork.p01 (plan) ---

Plan Title=Multiple Run
Short Identifier=Multiple
Geom File=g01
Flow File=f01
Subcritical Flow
K Sum by GR= 0
Std Step Tol= 0.01
Critical Tol= 0.01
Num of Std Step Trials= 20
Max Error Tol= 0.3
Flow Tol Ratio= 0.001
Split Flow NTrial= 30
Split Flow Tol= 0.02
Split Flow Ratio= 0.02
Log Output Level= 0
Friction Slope Method= 1
Unsteady Friction Slope Method= 2
Unsteady Bridges Friction Slope Method= 1
Parabolic Critical Depth
Global Vel Dist=  1 , 1 , 1
Global Log Level= 0
CheckData=True
Encroach Param= -1, 0, 0, 0
BEGIN DESCRIPTION:
Multiple Run
END DESCRIPTION:

--- Lacy Fork.f01 (steady flow) ---

Flow Title=Multiple
Number of Profiles=7
Profile Names=10-year,25-year,50-year,1pct_min,100-year,1pct_plu,500-year
River Rch & RM= Lacy Fork,Reach-1,100801
    6961   10052   12729    7927   15816   31557   24413
River Rch & RM= Lacy Fork,Reach-1,94467
    6986   10084   12767    7949   15860   31644   24468
River Rch & RM= Lacy Fork,Reach-1,90337
    7927   11469   14544    9068   18092   36099   27986
River Rch & RM= Lacy Fork,Reach-1,85774
    8196   11864   15051    9387   18729   37369   28988
River Rch & RM= Lacy Fork,Reach-1,84133
    8274   11974   15188    9470   18896   37702   29235
River Rch & RM= Lacy Fork,Reach-1,83715
    8465   12258   15554    9703   19359   38627   29973
River Rch & RM= Lacy Fork,Reach-1,77962
    8256   11954   15165    9456   18867   37645   29199
River Rch & RM= Lacy Fork,Reach-1,72402
    8433   12218   15506    9673   19300   38509   29894
River Rch & RM= Lacy Fork,Reach-1,70328
    8223   11869   15024    9347   18650   37211   28730
River Rch & RM= Lacy Fork,Reach-1,67483
    8461   12220   15475    9631   19216   38341   29623
River Rch & RM= Lacy Fork,Reach-1,60380
    8451   12191   15427    9593   19140   38190   29456
River Rch & RM= Lacy Fork,Reach-1,60080
    8613   12434   15742    9794   19542   38991   30105
River Rch & RM= Lacy Fork,Reach-1,54337
    8804   12703   16078    9999   19951   39808   30711
River Rch & RM= Lacy Fork,Reach-1,52042
    8669   12518   15850    9862   19678   39263   30322
River Rch & RM= Lacy Fork,Reach-1,45044
    8693   12526   15838    9840   19633   39172   30158
River Rch & RM= Lacy Fork,Reach-1,40446
    9766   14085   17823   11080   22107   44109   33992
River Rch & RM= Lacy Fork,Reach-1,31906
    9884   14232   17989   11169   22286   44466   34182
River Rch & RM= Lacy Fork,Reach-1,16332
    9888   14218   17954   11136   22220   44335   34011
River Rch & RM= Lacy Fork,Reach-1,12195
    9447   13568   17116   10604   21158   42215   32321
River Rch & RM= Lacy Fork,Reach-1,8205
    9500   13644   17211   10663   21276   42451   32502
River Rch & RM= Lacy Fork,Reach-1,2131
    9444   13547   17074   10569   21088   42075   32156
Boundary for River Rch & Prof#=Lacy Fork,Reach-1,1
Up Type=0
Dn Type=3
Dn Slope=0.005
Boundary for River Rch & Prof#=Lacy Fork,Reach-1,2
Up Type=0
Dn Type=3
Dn Slope=0.005
Boundary for River Rch & Prof#=Lacy Fork,Reach-1,3
Up Type=0
Dn Type=3
Dn Slope=0.005
Boundary for River Rch & Prof#=Lacy Fork,Reach-1,4
Up Type=0
Dn Type=3
Dn Slope=0.005
Boundary for River Rch & Prof#=Lacy Fork,Reach-1,5
Up Type=0
Dn Type=3
Dn Slope=0.005
Boundary for River Rch & Prof#=Lacy Fork,Reach-1,6
Up Type=0
Dn Type=3
Dn Slope=0.005
Boundary for River Rch & Prof#=Lacy Fork,Reach-1,7
Up Type=0
Dn Type=3
Dn Slope=0.005

--- Lacy Fork.g01 (geometry) ---

Geom Title=Existing Conditions

River Reach=Lacy Fork,Reach-1
Reach XY= 30
      2734476.00      6873411.00      2731620.58      6871962.65
      2730458.99      6872244.98      2727070.56      6868066.19
      2725776.01      6868503.93      2723606.07      6867941.82
      2722765.23      6866051.30      2721531.41      6865363.42
      2721671.05      6864266.11      2716836.39      6861121.22
      2715518.35      6856804.39      2711784.14      6854867.06
      2709665.58      6850551.15      2707586.77      6848620.70
      2704830.97      6844013.58      2704972.91      6843318.55
      2702233.59      6842557.82      2701183.67      6840967.52
      2702072.40      6839609.51      2701183.10      6839011.00
      2701875.30      6837670.78      2700879.32      6836802.95
      2700218.25      6834054.81      2699366.41      6833362.20
      2695192.12      6833328.05      2694476.23      6832246.90
      2695026.40      6830490.86      2694315.24      6827901.32
      2686599.01      6820834.47      2686375.47      6819681.43

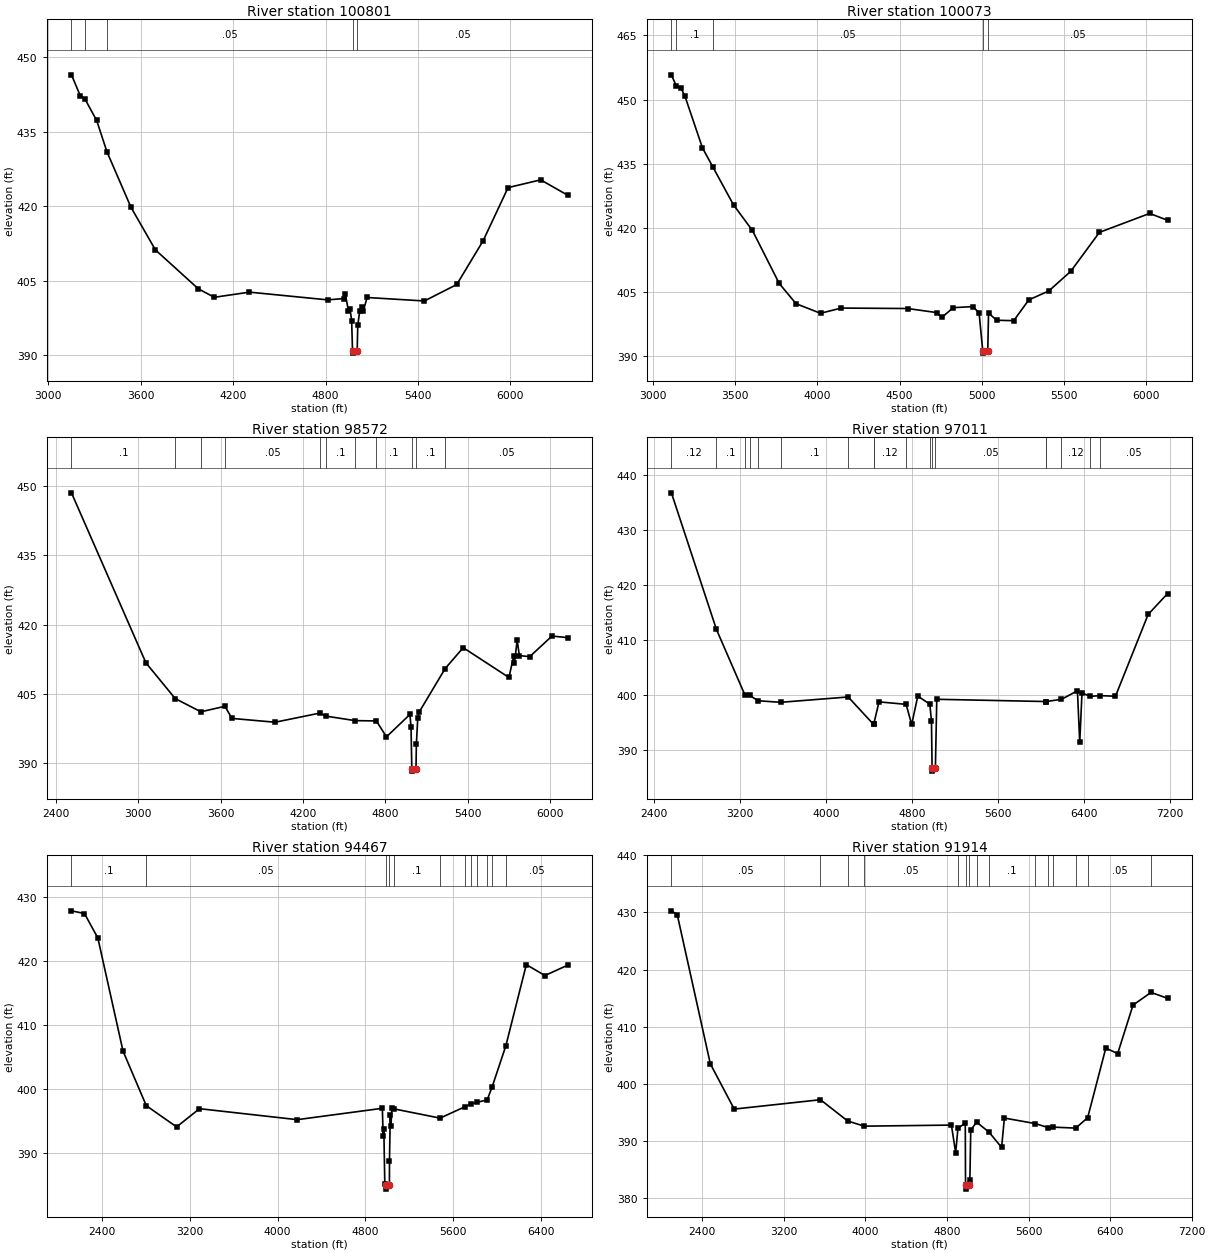
Type RM Length L Ch R = 1,100801,728,728,728
BEGIN DESCRIPTION:
Lacy Fork 1799
END DESCRIPTION:
XS GIS Cut Line= 3
      2734963.72      6871626.45      2734475.19      6873410.99
      2733994.05      6874694.79
#Sta/Elev= 30
  3149.8  446.48  3206.4  442.30  3238.3  441.55  3313.4  437.28  3379.9  430.99
  3535.9  419.80  3694.6  411.21  3973.6  403.35  4077.3  401.65  4305.4  402.69
  4813.4  401.13  4917.1  401.40  4927.4  402.33  4948.2  398.92  4958.5  399.28
  4968.9  396.95  4974.4  390.90  4977.4  390.40  5004.8  390.90  5008.6  396.02
  5021.4  398.88  5038.9  399.68  5044.3  398.87  5069.2  401.61  5441.3  400.91
  5651.4  404.23  5822.3  413.03  5984.3  423.75  6196.1  425.32  6371.0  422.23
#Mann=5,-1,0
  3149.8    0.12       0  3238.3     0.1       0  3379.9    0.05       0
  4974.4    0.04       0  5004.8    0.05       0
Bank Sta=4974.4,5004.8
Exp/Cntr=0.3,0.1

Type RM Length L Ch R = 1,100073,1501,1501,1501
BEGIN DESCRIPTION:
Lacy Fork 1801
END DESCRIPTION:
XS GIS Cut Line= 3
      2734540.01      6871622.91      2733930.48      6873426.88
      2733706.86      6874517.53
#Sta/Elev= 30
  3112.4  455.78  3141.1  453.24  3170.1  452.73  3194.8  450.78  3301.2  438.72
  3363.2  434.34  3490.4  425.38  3605.2  419.41  3767.7  407.06  3870.4  402.31
  4019.3  400.07  4145.2  401.29  4548.8  401.18  4725.4  400.24  4757.0  399.10
  4826.6  401.38  4947.0  401.63  4983.8  400.13  5006.0  391.26  5008.9  390.76
  5036.5  391.26  5041.2  400.08  5092.2  398.44  5194.3  398.34  5286.2  403.20
  5407.9  405.29  5541.4  409.88  5715.5  418.97  6021.2  423.40  6129.9  421.80
#Mann=5,-1,0
  3112.4    0.12       0  3141.1     0.1       0  3363.2    0.05       0
  5006.0    0.04       0  5036.5    0.05       0
Bank Sta=5006,5036.5
Exp/Cntr=0.3,0.1

Type RM Length L Ch R = 1,98572,1561,1561,1561
BEGIN DESCRIPTION:
Lacy Fork 1802
END DESCRIPTION:
XS GIS Cut Line= 3
      2734345.87      6870988.41      2732780.46      6872951.62
      2732502.26      6874016.26
#Sta/Elev= 30
  2514.5  448.58  3056.5  411.68  3269.5  403.94  3456.5  401.06  3631.3  402.26
  3682.6  399.63  3996.5  398.80  4321.8  400.78  4365.5  400.13  4578.8  399.15
  4733.8  399.08  4807.2  395.63  4978.1  400.49  4986.2  397.74  4991.7  388.69
  4994.7  388.19  5022.2  388.69  5025.0  394.00  5035.1  399.76  5045.4  401.01
  5234.6  410.45  5365.9  414.98  5698.7  408.51  5734.0  413.25  5739.2  411.64
  5758.6  416.61  5774.5  413.26  5850.2  413.03  6012.0  417.50  6125.8  417.16
#Mann=11,-1,0
  2514.5     0.1       0  3269.5    0.05       0  3456.5     0.1       0
  3631.3    0.05       0  4321.8    0.12       0  4365.5     0.1       0
  4578.8    0.12       0  4733.8     0.1       0  4991.7    0.07       0
  5022.2     0.1       0  5234.6    0.05       0
Bank Sta=4991.7,5022.2
Exp/Cntr=0.3,0.1

Type RM Length L Ch R = 1,97011,2544,2544,2544
BEGIN DESCRIPTION:
Lacy Fork 1798
END DESCRIPTION:
XS GIS Cut Line= 3
      2733862.16      6870496.38      2732136.78      6872241.55
      2730636.80      6873796.64
#Sta/Elev= 30
  2559.6  436.72  2978.4  411.89  3243.4  399.97  3286.4  399.91  3366.1  398.92
  3574.9  398.64  4204.1  399.61  4440.2  394.61  4442.4  394.75  4490.6  398.72
  4742.7  398.27  4794.6  394.61  4851.2  399.76  4962.9  398.32  4978.5  395.28
  4984.4  386.63  4987.4  386.13  5015.0  386.63  5027.9  399.19  6041.2  398.78
  6044.3  398.78  6187.4  399.18  6336.3  400.73  6357.6  391.34  6378.7  400.38
  6452.4  399.71  6545.8  399.86  6690.0  399.74  6994.1  414.62  7174.3  418.40
#Mann=18,-1,0
  2559.6    0.12       0  2978.4     0.1       0  3243.4    0.05       0
  3286.4     0.1       0  3366.1    0.05       0  3574.9     0.1       0
  4204.1    0.12       0  4440.2     0.1       0  4442.4    0.12       0
  4742.7     0.1       0  4962.9    0.05       0  4984.4    0.04       0
  5015.0    0.05       0  6041.2     0.1       0  6044.3    0.05       0
  6187.4    0.12       0  6452.4     0.1       0  6545.8    0.05       0
Bank Sta=4984.4,5015
Exp/Cntr=0.3,0.1

Type RM Length L Ch R = 1,94467,2553,2553,2553
BEGIN DESCRIPTION:
Lacy Fork 1797
END DESCRIPTION:
XS GIS Cut Line= 3
      2732927.81      6870208.04      2730555.05      6871866.59
      2729335.48      6872941.92
#Sta/Elev= 30
  2121.8  427.79  2240.2  427.37  2362.3  423.55  2591.6  405.94  2803.5  397.44
  3080.0  394.13  3288.4  396.97  4178.9  395.26  4954.6  397.03  4962.0  392.68
  4968.1  393.74  4976.9  385.31  4988.4  385.14  4991.4  384.44  5019.4  385.14
  5019.5  388.77  5026.6  395.94  5033.2  394.23  5040.8  397.01  5057.8  396.95
  5480.6  395.50  5706.8  397.27  5765.6  397.72  5820.2  397.97  5909.8  398.34
  5955.0  400.36  6080.2  406.78  6266.5  419.41  6436.3  417.71  6642.7  419.32
#Mann=12,-1,0
  2121.8     0.1       0  2803.5    0.05       0  4988.4    0.05       0
  5019.4    0.05       0  5057.8     0.1       0  5480.6    0.05       0
  5706.8    0.12       0  5765.6     0.1       0  5820.2    0.12       0
  5909.8    0.05       0  5955.0    0.12       0  6080.2    0.05       0
Bank Sta=4988.4,5019.4
Exp/Cntr=0.3,0.1

Type RM Length L Ch R = 1,91914,1577,1577,1577
BEGIN DESCRIPTION:
Lacy Fork 1259
END DESCRIPTION:
XS GIS Cut Line= 3
      2732150.98      6869736.01      2729376.53      6870585.87
      2727751.01      6871685.99
#Sta/Elev= 30
  2098.3  430.28  2155.8  429.59  2480.0  403.50  2714.1  395.58  3559.9  397.22
  3826.3  393.50  3987.8  392.59  4843.7  392.78  4885.5  387.93  4908.0  392.25
  4979.6  393.09  4982.2  382.27  4985.2  381.57  5013.2  382.27  5024.8  383.20
  5033.4  391.90  5090.6  393.29  5212.1  391.55  5336.0  388.87  5363.0  394.01
  5667.0  393.04  5795.6  392.33  5842.1  392.42  6062.6  392.25  6179.6  394.07
  6357.6  406.26  6473.8  405.29  6624.3  413.78  6800.9  416.00  6962.8  414.97
#Mann=15,-1,0
  2098.3    0.05       0  3559.9    0.12       0  3826.3     0.1       0
  3987.8    0.05       0  4908.0     0.1       0  4982.2    0.07       0
  5013.2     0.1       0  5090.6    0.12       0  5212.1     0.1       0
  5667.0    0.05       0  5795.6     0.1       0  5842.1    0.05       0
  6062.6    0.12       0  6179.6    0.05       0  6800.9    0.12       0
Bank Sta=4982.2,5013.2
Exp/Cntr=0.3,0.1

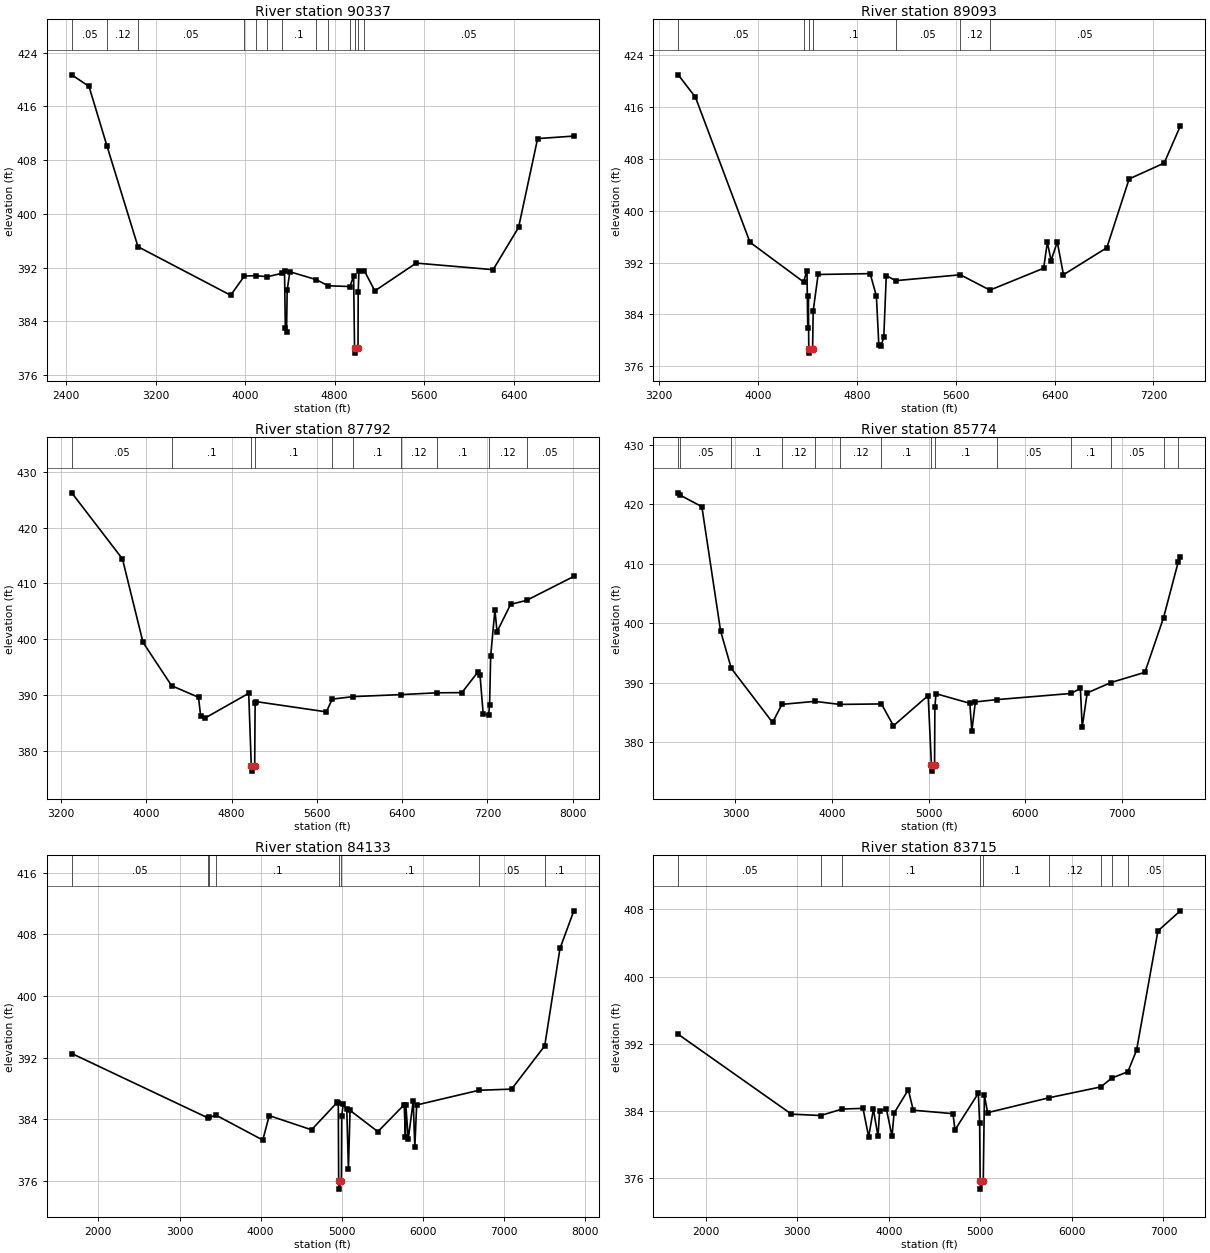
Type RM Length L Ch R = 1,90337,1244,1244,1244
BEGIN DESCRIPTION:
Lacy Fork 1258
END DESCRIPTION:
XS GIS Cut Line= 3
      2729450.30      6867392.61      2728449.77      6869761.17
      2727630.17      6871493.67
#Sta/Elev= 30
  2450.1  420.71  2604.1  418.98  2764.4  410.13  3042.0  395.11  3870.4  387.88
  3992.9  390.74  4094.2  390.80  4199.5  390.64  4325.4  391.14  4351.8  391.47
  4358.9  382.99  4369.8  382.41  4375.5  388.62  4399.2  391.38  4634.5  390.21
  4742.2  389.29  4936.0  389.18  4969.5  390.74  4977.7  379.96  4980.7  379.26
  5008.7  379.96  5010.3  388.37  5016.9  391.55  5066.5  391.48  5159.1  388.53
  5528.7  392.67  6216.2  391.69  6443.8  397.98  6614.1  411.21  6937.9  411.59
#Mann=13,-1,0
  2450.1    0.05       0  2764.4    0.12       0  3042.0    0.05       0
  3992.9     0.1       0  4094.2    0.05       0  4199.5    0.12       0
  4325.4     0.1       0  4634.5    0.12       0  4742.2     0.1       0
  4936.0    0.12       0  4977.7    0.07       0  5008.7    0.12       0
  5066.5    0.05       0
Bank Sta=4977.7,5008.7
Exp/Cntr=0.3,0.1

Type RM Length L Ch R = 1,89093,1301,1301,1301
BEGIN DESCRIPTION:
Lacy Fork 1257
END DESCRIPTION:
XS GIS Cut Line= 3
      2727828.13      6867322.06      2727707.06      6868964.45
      2727531.32      6871374.00
#Sta/Elev= 30
  3354.6  420.90  3493.9  417.45  3935.1  395.12  4368.5  389.02  4396.4  390.75
  4402.6  381.85  4407.6  386.92  4410.9  378.75  4413.9  378.05  4441.9  378.75
  4446.5  384.54  4486.6  390.16  4907.7  390.29  4957.9  386.86  4977.9  379.28
  4997.2  379.21  5018.0  380.55  5038.1  389.99  5113.8  389.21  5637.8  390.11
  5876.8  387.75  6311.5  391.12  6341.5  395.13  6371.6  392.29  6421.8  395.18
  6471.9  390.12  6822.8  394.28  7003.3  404.87  7286.7  407.31  7417.4  413.02
#Mann=7,-1,0
  3354.6    0.05       0  4368.5     0.1       0  4410.9    0.07       0
  4441.9     0.1       0  5113.8    0.05       0  5637.8    0.12       0
  5876.8    0.05       0
Bank Sta=4410.9,4441.9
Exp/Cntr=0.3,0.1

Type RM Length L Ch R = 1,87792,2018,2018,2018
BEGIN DESCRIPTION:
Lacy Fork 1256
END DESCRIPTION:
XS GIS Cut Line= 3
      2727134.99      6866364.23      2727011.92      6868093.10
      2727098.10      6871071.61
#Sta/Elev= 30
  3299.0  426.22  3774.8  414.36  3967.5  399.40  4236.3  391.62  4488.8  389.55
  4508.8  386.14  4548.9  385.81  4960.0  390.26  4983.9  377.30  4987.2  376.30
  5016.2  377.30  5020.1  388.56  5028.7  388.77  5688.6  386.93  5743.9  389.22
  5943.6  389.67  6392.4  390.03  6727.8  390.35  6961.0  390.38  7111.0  394.06
  7131.0  393.57  7161.0  386.54  7211.6  386.40  7221.1  388.09  7231.1  396.89
  7271.1  405.22  7291.1  401.31  7418.4  406.22  7568.5  406.93  8012.0  411.23
#Mann=10,-1,0
  3299.0    0.05       0  4236.3     0.1       0  4983.9    0.07       0
  5016.2     0.1       0  5743.9    0.12       0  5943.6     0.1       0
  6392.4    0.12       0  6727.8     0.1       0  7211.6    0.12       0
  7568.5    0.05       0
Bank Sta=4983.9,5016.2
Exp/Cntr=0.3,0.1

Type RM Length L Ch R = 1,85774,1641,1641,1641
BEGIN DESCRIPTION:
Lacy Fork 1255
END DESCRIPTION:
XS GIS Cut Line= 3
      2726792.12      6866118.06      2725329.47      6868248.56
      2724701.67      6870787.13
#Sta/Elev= 30
  2407.6  421.92  2422.0  421.58  2652.3  419.59  2846.5  398.68  2956.8  392.43
  3384.5  383.34  3481.7  386.38  3823.1  386.88  4079.3  386.37  4512.0  386.45
  4636.4  382.78  4995.7  387.86  5029.7  376.16  5033.0  375.16  5062.1  376.16
  5065.1  385.88  5076.8  388.17  5427.0  386.56  5448.2  381.93  5484.5  386.79
  5711.0  387.18  6475.1  388.21  6572.0  389.07  6591.1  382.55  6642.6  388.30
  6889.7  390.05  7240.0  391.76  7433.1  400.93  7586.5  410.38  7606.9  411.12
#Mann=14,-1,0
  2407.6    0.12       0  2422.0    0.05       0  2956.8     0.1       0
  3481.7    0.12       0  3823.1     0.1       0  4079.3    0.12       0
  4512.0     0.1       0  5029.7    0.07       0  5062.1     0.1       0
  5711.0    0.05       0  6475.1     0.1       0  6889.7    0.05       0
  7433.1     0.1       0  7586.5    0.05       0
Bank Sta=5029.7,5062.1
Exp/Cntr=0.3,0.1

Type RM Length L Ch R = 1,84133,418,418,418
BEGIN DESCRIPTION:
Lacy Fork 1254
END DESCRIPTION:
XS GIS Cut Line= 3
      2725325.56      6864882.37      2724178.50      6868037.68
      2724599.28      6870840.02
#Sta/Elev= 30
  1671.5  392.52  3351.0  384.16  3361.4  384.23  3454.2  384.50  4026.6  381.29
  4106.7  384.46  4628.0  382.62  4947.3  386.21  4957.8  386.06  4962.5  375.92
  4966.0  374.92  4995.9  375.92  5000.5  384.43  5019.0  385.95  5062.5  385.26
  5082.8  377.51  5103.0  385.14  5445.8  382.38  5770.4  385.87  5786.0  381.75
  5791.1  385.79  5820.9  381.44  5881.6  386.32  5901.8  380.34  5924.1  385.84
  6693.4  387.75  7095.1  387.90  7503.2  393.51  7691.7  406.16  7862.6  411.04
#Mann=8,-1,0
  1671.5    0.05       0  3351.0     0.1       0  3361.4    0.05       0
  3454.2     0.1       0  4962.5    0.07       0  4995.9     0.1       0
  6693.4    0.05       0  7503.2     0.1       0
Bank Sta=4962.5,4995.9
Exp/Cntr=0.3,0.1

Type RM Length L Ch R = 1,83715,2890,2890,2890
BEGIN DESCRIPTION:
Lacy Fork 1253
END DESCRIPTION:
XS GIS Cut Line= 3
      2725222.95      6864955.67      2723786.00      6867952.76
      2722255.19      6869475.71
#Sta/Elev= 30
  1700.9  393.13  2937.8  383.64  3256.1  383.48  3492.0  384.25  3718.7  384.33
  3780.6  380.94  3832.0  384.22  3882.8  381.00  3899.9  383.99  3973.5  384.27
  4035.7  381.02  4057.9  383.76  4213.1  386.54  4268.0  384.11  4701.1  383.70
  4723.3  381.77  4978.3  386.13  4992.5  382.60  4998.2  375.73  5001.8  374.73
  5032.0  375.73  5044.6  385.87  5080.0  383.82  5750.4  385.59  6315.9  386.88
  6435.4  387.93  6611.2  388.68  6706.3  391.24  6939.7  405.42  7184.0  407.81
#Mann=9,-1,0
  1700.9    0.05       0  3256.1    0.12       0  3492.0     0.1       0
  4998.2    0.07       0  5032.0     0.1       0  5750.4    0.12       0
  6315.9    0.05       0  6435.4    0.12       0  6611.2    0.05       0
Bank Sta=4998.2,5032
Exp/Cntr=0.3,0.1

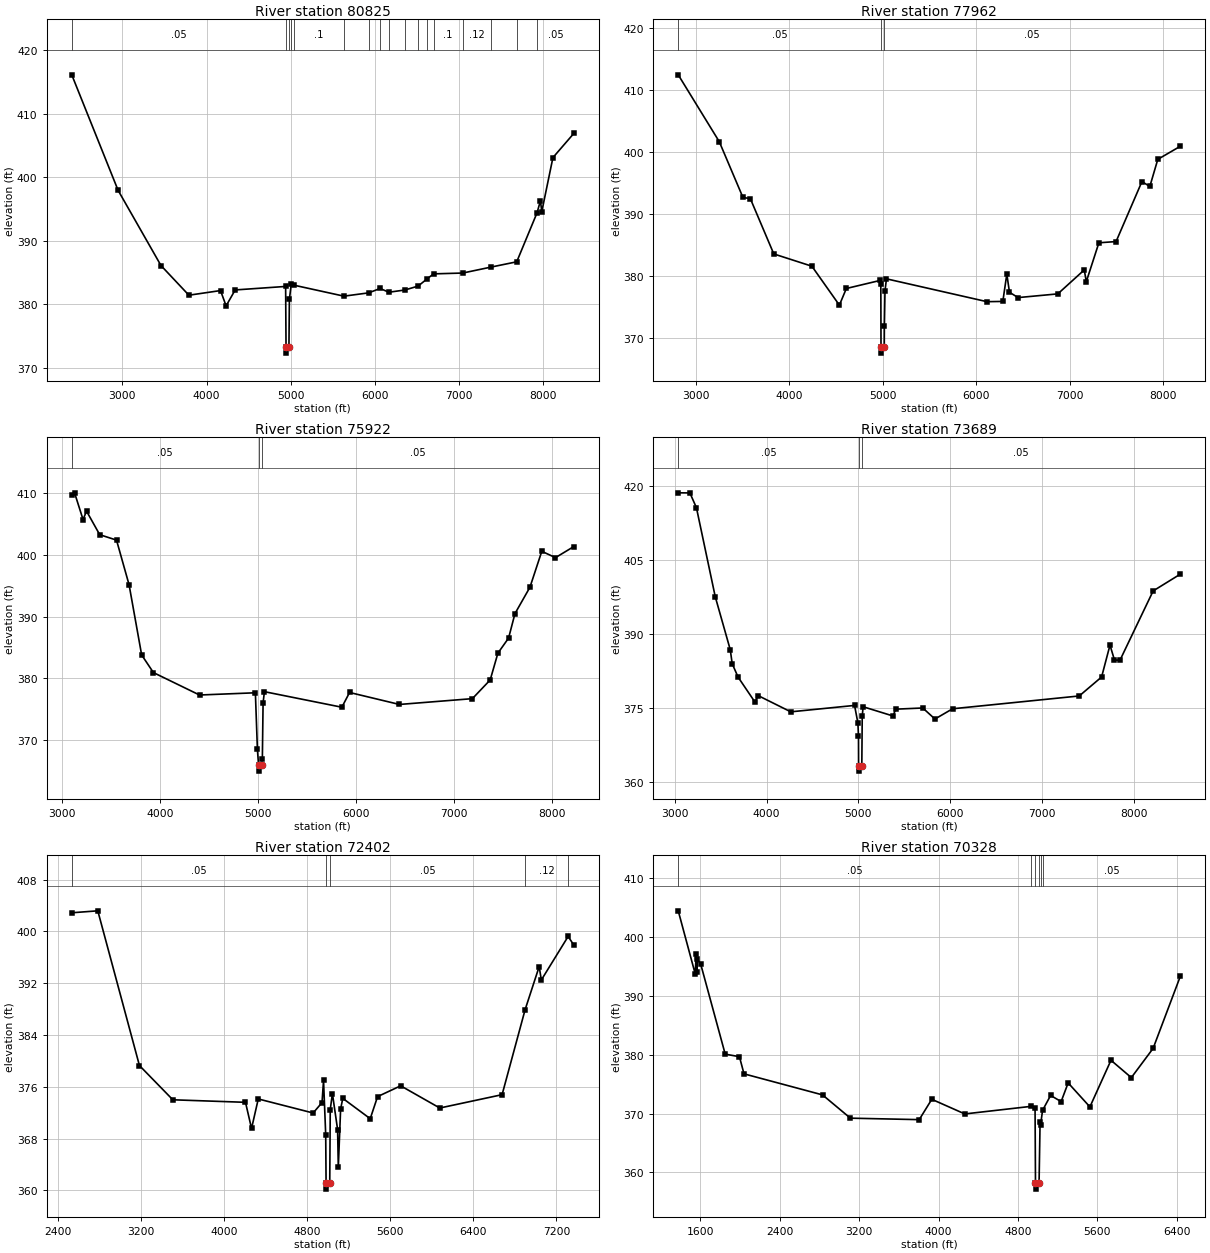
Type RM Length L Ch R = 1,80825,2863,2863,2863
BEGIN DESCRIPTION:
Lacy Fork 1252
END DESCRIPTION:
XS GIS Cut Line= 4
      2723946.57      6863821.91      2722836.33      6866188.03
      2722812.52      6868405.62      2722285.35      6869406.06
#Sta/Elev= 30
  2399.1  416.12  2949.3  397.93  3458.5  386.09  3789.9  381.42  4165.5  382.15
  4231.8  379.74  4339.6  382.25  4938.7  382.80  4943.5  373.30  4947.3  372.30
  4978.0  373.30  4983.3  380.76  5006.0  383.24  5044.0  382.98  5631.3  381.27
  5924.9  381.79  6060.3  382.48  6164.6  381.89  6355.4  382.24  6512.2  382.86
  6622.3  384.03  6695.7  384.78  7042.1  384.91  7375.1  385.84  7683.0  386.68
  7925.3  394.43  7964.3  396.29  7980.7  394.59  8112.9  403.09  8361.3  406.90
#Mann=17,-1,0
  2399.1    0.05       0  4943.5    0.04       0  4978.0    0.05       0
  5006.0    0.12       0  5044.0     0.1       0  5631.3    0.12       0
  5924.9     0.1       0  6060.3    0.12       0  6164.6     0.1       0
  6355.4    0.12       0  6512.2     0.1       0  6622.3    0.12       0
  6695.7     0.1       0  7042.1    0.12       0  7375.1    0.05       0
  7683.0    0.12       0  7925.3    0.05       0
Bank Sta=4943.5,4978
Exp/Cntr=0.3,0.1

Type RM Length L Ch R = 1,77962,2040,2040,2040
BEGIN DESCRIPTION:
Lacy Fork 945
END DESCRIPTION:
XS GIS Cut Line= 4
      2723564.31      6863804.62      2721575.94      6864719.44
      2720929.52      6865045.02      2719101.00      6866686.00
#Sta/Elev= 30
  2810.8  412.50  3249.8  401.70  3502.4  392.71  3582.3  392.49  3832.7  383.57
  4239.9  381.59  4534.2  375.30  4608.6  377.99  4969.6  379.29  4977.4  378.78
  4979.3  368.55  4983.1  367.55  5014.2  368.55  5015.2  371.88  5021.9  377.57
  5037.5  379.55  6112.5  375.86  6282.2  375.90  6324.8  380.32  6353.2  377.38
  6445.2  376.52  6870.1  377.12  7153.1  380.99  7174.8  379.09  7309.3  385.37
  7493.2  385.57  7769.8  395.26  7854.3  394.47  7939.5  398.85  8180.2  400.96
#Mann=3,-1,0
  2810.8    0.05       0  4979.3    0.04       0  5014.2    0.05       0
Bank Sta=4979.3,5014.2
Exp/Cntr=0.3,0.1

Type RM Length L Ch R = 1,75922,2233,2233,2233
BEGIN DESCRIPTION:
Lacy Fork 943
END DESCRIPTION:
XS GIS Cut Line= 3
      2722336.03      6862650.37      2720832.92      6863844.95
      2719101.00      6866536.01
#Sta/Elev= 30
  3099.2  409.69  3127.7  410.04  3214.2  405.71  3249.5  407.08  3384.1  403.26
  3555.5  402.38  3683.6  395.15  3811.8  383.78  3931.9  380.92  4402.1  377.29
  4971.6  377.65  4992.4  368.48  5004.0  365.96  5007.9  364.96  5039.1  365.96
  5042.7  366.87  5050.2  376.00  5063.8  377.83  5853.6  375.31  5932.1  377.70
  6440.6  375.76  7184.7  376.70  7366.3  379.73  7444.9  384.07  7553.8  386.51
  7618.8  390.47  7771.7  394.75  7892.5  400.57  8031.9  399.54  8219.4  401.34
#Mann=3,-1,0
  3099.2    0.05       0  5004.0    0.04       0  5039.1    0.05       0
Bank Sta=5004,5039.1
Exp/Cntr=0.3,0.1

Type RM Length L Ch R = 1,73689,1287,1287,1287
BEGIN DESCRIPTION:
Lacy Fork 942
END DESCRIPTION:
XS GIS Cut Line= 3
      2720983.95      6861449.99      2719686.56      6862952.46
      2719101.00      6866385.98
#Sta/Elev= 30
  3037.5  418.61  3164.4  418.59  3235.7  415.59  3440.8  397.52  3604.2  386.77
  3625.1  383.96  3688.7  381.24  3873.0  376.16  3909.2  377.46  4263.5  374.18
  4957.9  375.48  4994.1  371.93  5000.7  369.19  5001.7  363.15  5005.6  362.15
  5036.8  363.15  5041.4  373.32  5051.1  375.21  5376.2  373.34  5406.6  374.72
  5700.8  374.96  5833.4  372.72  6025.4  374.80  7405.1  377.40  7648.5  381.25
  7739.8  387.72  7788.7  384.68  7848.9  384.66  8209.9  398.71  8505.7  402.11
#Mann=3,-1,0
  3037.5    0.05       0  5001.7    0.04       0  5036.8    0.05       0
Bank Sta=5001.7,5036.8
Exp/Cntr=0.3,0.1

Type RM Length L Ch R = 1,72402,2074,2074,2074
BEGIN DESCRIPTION:
Lacy Fork 941
END DESCRIPTION:
XS GIS Cut Line= 3
      2720904.81      6860988.71      2718905.27      6862458.12
      2717024.00      6863876.92
#Sta/Elev= 30
  2530.4  402.88  2781.2  403.18  3182.4  379.28  3504.2  373.99  4204.3  373.60
  4262.6  369.56  4327.4  374.12  4856.0  371.95  4941.7  373.56  4956.3  376.98
  4977.2  368.59  4980.8  361.19  4984.8  360.19  5016.1  361.19  5021.0  372.49
  5041.8  374.95  5091.8  369.39  5098.6  363.54  5120.9  372.58  5141.8  374.21
  5406.1  371.07  5476.9  374.48  5699.7  376.15  6076.5  372.72  6676.7  374.78
  6898.5  387.91  7034.1  394.57  7054.9  392.50  7313.0  399.22  7368.1  397.89
#Mann=5,-1,0
  2530.4    0.05       0  4980.8    0.04       0  5016.1    0.05       0
  6898.5    0.12       0  7313.0    0.05       0
Bank Sta=4980.8,5016.1
Exp/Cntr=0.3,0.1

Type RM Length L Ch R = 1,70328,900,900,900
BEGIN DESCRIPTION:
Lacy Fork 940
END DESCRIPTION:
XS GIS Cut Line= 3
      2720671.55      6860048.62      2717391.98      6861557.21
      2716349.73      6862562.24
#Sta/Elev= 30
  1378.0  404.50  1549.2  393.76  1558.9  397.09  1564.5  394.12  1571.2  396.25
  1604.3  395.44  1851.1  380.12  1994.5  379.69  2040.4  376.77  2831.5  373.19
  3112.3  369.23  3805.7  368.98  3932.2  372.44  4264.8  369.95  4933.1  371.24
  4972.5  370.98  4976.9  358.16  4981.0  357.16  5012.9  358.16  5023.2  368.66
  5028.1  368.09  5048.2  370.56  5129.2  373.10  5235.2  372.05  5305.9  375.23
  5525.1  371.15  5737.4  379.08  5942.4  376.13  6161.8  381.10  6435.8  393.36
#Mann=6,-1,0
  1378.0    0.05       0  4933.1    0.12       0  4976.9    0.07       0
  5012.9    0.12       0  5028.1     0.1       0  5048.2    0.05       0
Bank Sta=4976.9,5012.9
Exp/Cntr=0.3,0.1

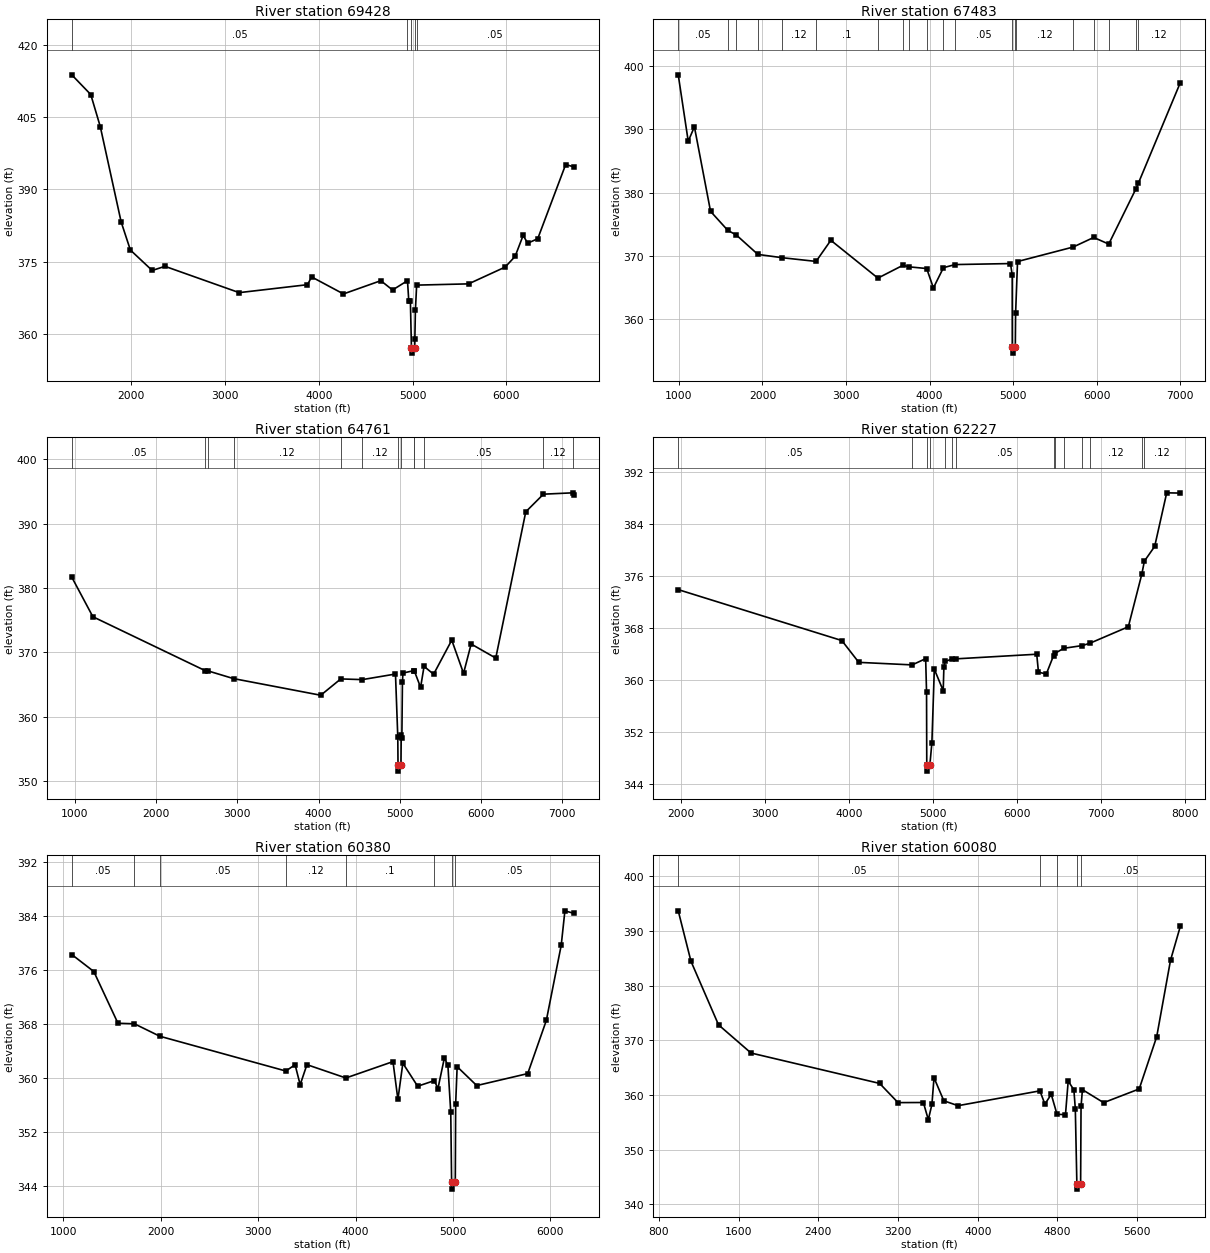
Type RM Length L Ch R = 1,69428,1945,1945,1945
BEGIN DESCRIPTION:
Lacy Fork 939
END DESCRIPTION:
XS GIS Cut Line= 3
      2720553.57      6859751.52      2717159.48      6861136.22
      2716059.15      6862417.11
#Sta/Elev= 30
  1364.2  413.74  1566.8  409.65  1668.3  402.99  1890.8  383.22  1989.2  377.39
  2221.7  373.15  2358.1  374.01  3149.4  368.55  3878.0  370.20  3922.0  371.81
  4261.5  368.28  4659.9  371.03  4785.2  369.10  4944.4  371.03  4958.0  366.90
  4975.3  366.84  4986.7  357.00  4990.8  356.00  5022.7  357.00  5022.8  358.84
  5028.8  364.88  5042.1  370.11  5595.9  370.37  5985.5  373.85  6091.9  376.06
  6177.5  380.41  6226.9  378.81  6333.4  379.74  6631.3  395.13  6718.5  394.64
#Mann=5,-1,0
  1364.2    0.05       0  4944.4    0.12       0  4986.7    0.07       0
  5022.7    0.12       0  5042.1    0.05       0
Bank Sta=4986.7,5022.7
Exp/Cntr=0.3,0.1

Type RM Length L Ch R = 1,67483,2722,2722,2722
BEGIN DESCRIPTION:
Lacy Fork 938
END DESCRIPTION:
XS GIS Cut Line= 3
      2720242.63      6859233.41      2716364.09      6860295.26
      2714525.99      6861058.15
#Sta/Elev= 30
   991.6  398.67  1111.2  388.13  1185.1  390.43  1378.5  377.01  1584.6  374.00
  1687.9  373.25  1945.2  370.18  2234.5  369.66  2641.7  369.07  2818.6  372.42
  3382.2  366.42  3682.9  368.46  3754.0  368.21  3966.3  367.94  4046.7  364.86
  4167.2  368.08  4307.3  368.57  4969.4  368.73  4990.2  366.95  4991.1  355.52
  4995.3  354.52  5027.4  355.52  5030.9  360.81  5054.1  369.05  5720.0  371.35
  5965.9  372.87  6146.0  371.82  6469.6  380.53  6501.2  381.49  7003.0  397.43
#Mann=20,-1,0
   991.6    0.05       0  1584.6     0.1       0  1687.9    0.12       0
  1945.2     0.1       0  2234.5    0.12       0  2641.7     0.1       0
  3382.2    0.12       0  3682.9    0.05       0  3754.0     0.1       0
  3966.3    0.05       0  4167.2    0.12       0  4307.3    0.05       0
  4991.1    0.04       0  5027.4    0.05       0  5030.9    0.12       0
  5720.0    0.12       0  5965.9     0.1       0  6146.0    0.12       0
  6469.6     0.1       0  6501.2    0.12       0
Bank Sta=4991.1,5027.4
Exp/Cntr=0.3,0.1

Type RM Length L Ch R = 1,64761,2534,2534,2534
BEGIN DESCRIPTION:
Lacy Fork 937
END DESCRIPTION:
XS GIS Cut Line= 4
      2719421.75      6857274.81      2716018.37      6858416.98
      2715677.22      6858707.63      2713879.45      6859873.29
#Sta/Elev= 30
   961.9  381.70  1221.7  375.54  2603.6  367.16  2640.6  367.11  2952.9  365.92
  4026.9  363.33  4273.5  365.87  4538.0  365.76  4946.9  366.63  4975.3  356.84
  4978.1  352.53  4982.3  351.53  5014.5  352.53  5017.4  357.11  5025.3  356.64
  5032.5  365.39  5038.5  366.78  5170.0  367.15  5178.8  367.12  5256.0  364.55
  5298.7  367.82  5416.2  366.60  5639.7  371.90  5784.7  366.74  5878.4  371.30
  6181.3  369.11  6550.8  391.86  6768.4  394.60  7129.4  394.81  7142.6  394.49
#Mann=13,-1,0
   961.9    0.05       0  2603.6    0.12       0  2640.6     0.1       0
  2952.9    0.12       0  4273.5     0.1       0  4538.0    0.12       0
  4978.1    0.07       0  5014.5    0.12       0  5170.0    0.05       0
  5178.8    0.12       0  5298.7    0.05       0  6768.4    0.12       0
  7129.4    0.05       0
Bank Sta=4978.1,5014.5
Exp/Cntr=0.3,0.1

Type RM Length L Ch R = 1,62227,1847,1847,1847
BEGIN DESCRIPTION:
Lacy Fork 912
END DESCRIPTION:
XS GIS Cut Line= 3
      2718301.08      6855735.73      2715436.20      6856760.55
      2713653.65      6859096.18
#Sta/Elev= 30
  1965.1  373.92  3914.1  366.09  4115.8  362.74  4751.9  362.35  4912.4  363.31
  4923.0  358.15  4925.6  347.02  4930.0  346.02  4962.9  347.02  4986.7  350.40
  5015.5  361.69  5121.5  358.39  5129.8  362.09  5144.9  362.88  5226.4  363.25
  5275.1  363.28  6235.4  363.99  6256.3  361.23  6349.7  360.95  6436.0  363.78
  6454.2  364.13  6557.0  364.90  6778.4  365.32  6869.1  365.68  7326.6  368.21
  7487.1  376.29  7517.9  378.30  7640.4  380.56  7783.8  388.80  7945.9  388.76
#Mann=14,-1,0
  1965.1    0.05       0  4751.9    0.12       0  4925.6    0.07       0
  4962.9    0.12       0  5144.9     0.1       0  5226.4    0.12       0
  5275.1    0.05       0  6436.0    0.12       0  6454.2    0.05       0
  6557.0    0.12       0  6778.4     0.1       0  6869.1    0.12       0
  7487.1    0.05       0  7517.9    0.12       0
Bank Sta=4925.6,4962.9
Exp/Cntr=0.3,0.1

Type RM Length L Ch R = 1,60380,300,300,300
BEGIN DESCRIPTION:
Lacy Fork 913
END DESCRIPTION:
XS GIS Cut Line= 3
      2717679.57      6855468.07      2714020.30      6856078.52
      2712749.95      6856769.61
#Sta/Elev= 30
  1085.1  378.26  1311.2  375.75  1559.4  368.10  1728.2  368.02  1989.4  366.18
  3283.5  361.04  3378.4  361.97  3430.6  359.01  3500.0  361.98  3900.1  360.01
  4383.6  362.43  4434.3  356.83  4485.0  362.19  4637.1  358.79  4808.5  359.62
  4845.4  358.44  4911.6  362.98  4947.8  361.87  4977.1  354.92  4985.9  344.58
  4990.4  343.58  5023.6  344.58  5027.5  356.22  5042.7  361.68  5243.8  358.89
  5767.5  360.66  5958.4  368.51  6111.3  379.62  6149.3  384.72  6241.1  384.35
#Mann=8,-1,0
  1085.1    0.05       0  1728.2    0.12       0  1989.4    0.05       0
  3283.5    0.12       0  3900.1     0.1       0  4808.5    0.05       0
  4985.9    0.05       0  5023.6    0.05       0
Bank Sta=4985.9,5023.6
Exp/Cntr=0.3,0.1

Type RM Length L Ch R = 1,60080,1502,1502,1502
BEGIN DESCRIPTION:
Lacy Fork 12
END DESCRIPTION:
XS GIS Cut Line= 3
      2716175.97      6853011.04      2713577.11      6856062.25
      2712687.32      6856586.64
#Sta/Elev= 30
   992.9  393.66  1120.8  384.43  1397.5  372.81  1723.6  367.66  3015.0  362.10
  3199.5  358.59  3454.2  358.61  3503.6  355.47  3539.9  358.26  3560.8  363.14
  3659.6  358.92  3802.4  358.03  4623.9  360.74  4674.2  358.32  4737.9  360.10
  4795.9  356.45  4880.7  356.39  4908.1  362.53  4965.2  360.92  4979.5  357.46
  4995.1  343.77  4999.6  342.77  5032.8  343.77  5037.0  357.88  5051.0  360.96
  5263.8  358.58  5621.0  361.09  5796.7  370.64  5935.3  384.62  6033.7  390.82
#Mann=5,-1,0
   992.9    0.05       0  4623.9    0.12       0  4795.9    0.05       0
  4995.1    0.05       0  5032.8    0.05       0
Bank Sta=4995.1,5032.8
Exp/Cntr=0.3,0.1

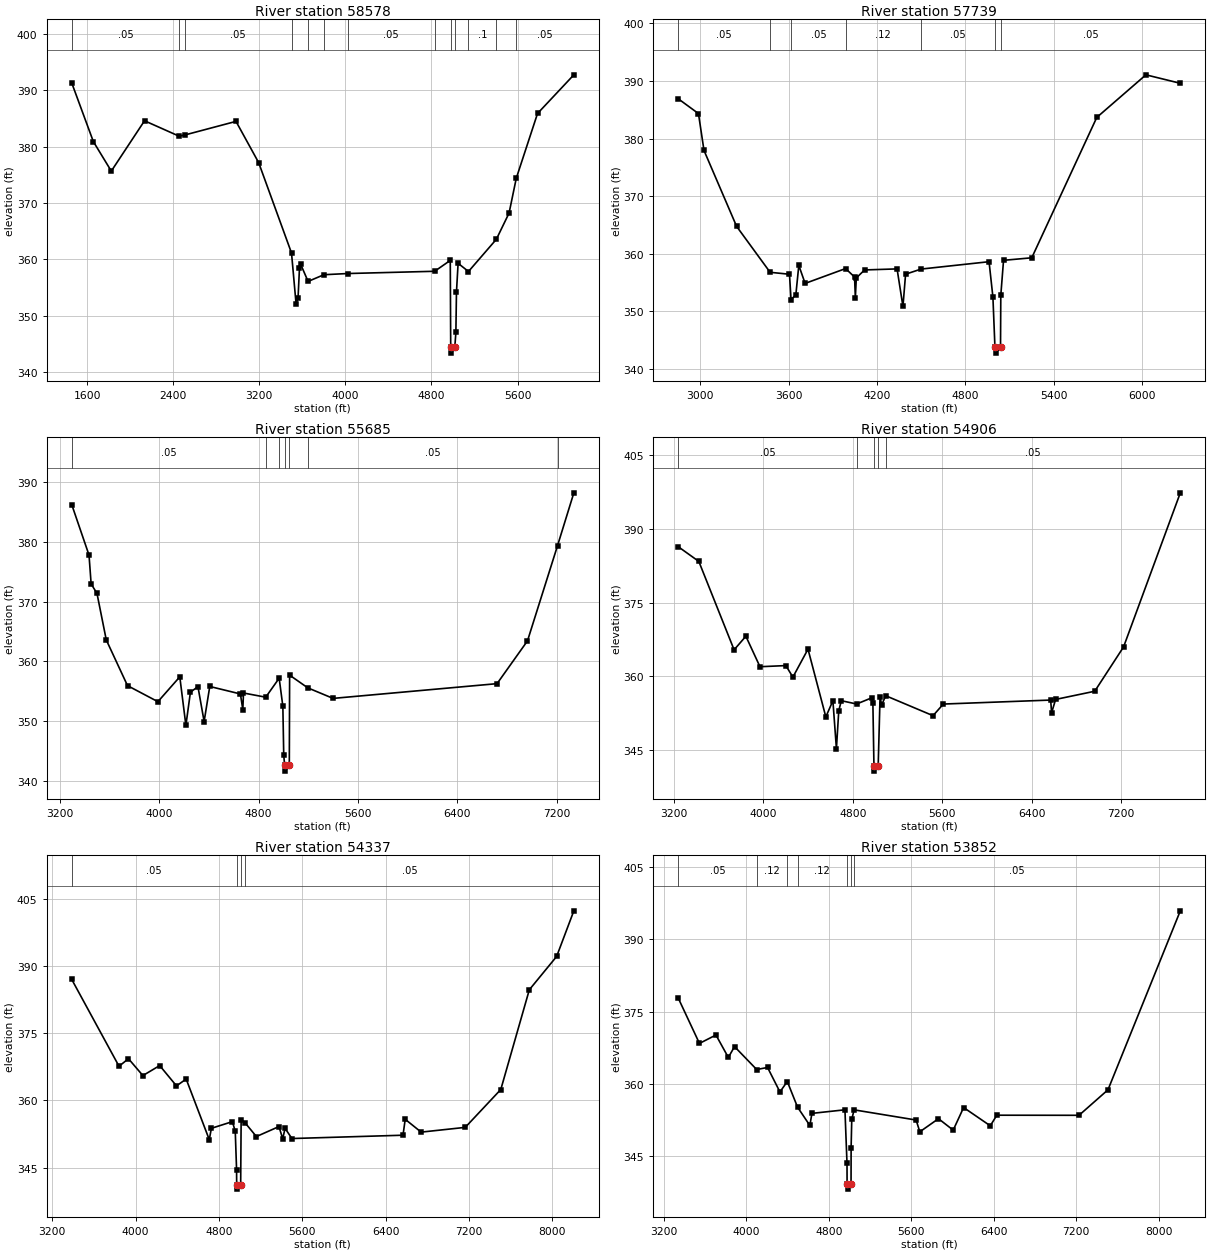
Type RM Length L Ch R = 1,58578,839,839,839
BEGIN DESCRIPTION:
Lacy Fork 900
END DESCRIPTION:
XS GIS Cut Line= 3
      2713492.89      6851902.36      2712377.30      6855270.97
      2712110.93      6856355.50
#Sta/Elev= 30
  1458.0  391.29  1658.4  380.90  1825.3  375.66  2134.0  384.59  2455.0  381.86
  2510.6  382.08  2984.0  384.48  3194.7  377.16  3499.9  361.13  3542.3  352.09
  3560.7  353.19  3573.9  358.49  3584.5  359.15  3653.8  356.09  3800.9  357.28
  4023.1  357.49  4830.1  357.89  4975.0  359.82  4979.1  344.37  4983.6  343.37
  5016.9  344.37  5027.2  347.05  5032.6  354.20  5047.8  359.30  5144.2  357.85
  5403.4  363.57  5521.4  368.22  5588.2  374.38  5785.8  385.88  6123.3  392.74
#Mann=13,-1,0
  1458.0    0.05       0  2455.0    0.12       0  2510.6    0.05       0
  3499.9    0.12       0  3653.8     0.1       0  3800.9    0.12       0
  4023.1    0.05       0  4830.1    0.12       0  4979.1    0.07       0
  5016.9    0.12       0  5144.2     0.1       0  5403.4    0.12       0
  5588.2    0.05       0
Bank Sta=4979.1,5016.9
Exp/Cntr=0.3,0.1

Type RM Length L Ch R = 1,57739,2054,2054,2054
BEGIN DESCRIPTION:
Lacy Fork 879
END DESCRIPTION:
XS GIS Cut Line= 3
      2712434.70      6852745.40      2711745.33      6854790.36
      2711409.35      6855994.85
#Sta/Elev= 30
  2849.9  386.92  2987.2  384.35  3024.7  377.95  3246.3  364.75  3473.6  356.78
  3605.1  356.44  3615.7  352.05  3648.3  352.86  3668.4  357.98  3711.3  354.85
  3986.1  357.43  4047.0  355.95  4052.3  352.34  4058.8  355.81  4115.3  357.19
  4335.6  357.37  4375.4  350.84  4393.3  356.45  4498.6  357.34  4960.0  358.62
  4986.2  352.47  5000.0  343.74  5004.5  342.74  5037.8  343.74  5039.7  352.78
  5058.3  358.86  5250.0  359.30  5691.3  383.68  6024.9  391.08  6258.4  389.61
#Mann=7,-1,0
  2849.9    0.05       0  3473.6    0.12       0  3615.7    0.05       0
  3986.1    0.12       0  4498.6    0.05       0  5000.0    0.04       0
  5037.8    0.05       0
Bank Sta=5000,5037.8
Exp/Cntr=0.3,0.1

Type RM Length L Ch R = 1,55685,779,779,779
BEGIN DESCRIPTION:
Lacy Fork 11
END DESCRIPTION:
XS GIS Cut Line= 3
      2712276.01      6852560.99      2710676.00      6853161.00
      2708676.00      6854361.00
#Sta/Elev= 30
  3296.1  386.17  3435.0  377.75  3451.9  372.95  3499.0  371.36  3573.8  363.60
  3744.7  355.97  3989.4  353.29  4165.6  357.44  4214.6  349.34  4251.1  354.87
  4311.6  355.81  4361.4  349.98  4406.8  355.83  4653.4  354.58  4672.9  351.96
  4678.3  354.74  4857.3  354.04  4965.4  357.21  4995.1  352.53  5002.2  344.37
  5009.3  342.70  5013.8  341.70  5047.1  342.70  5049.6  357.72  5195.7  355.60
  5399.5  353.84  6719.2  356.30  6964.1  363.44  7206.1  379.34  7337.3  388.15
#Mann=7,-1,0
  3296.1    0.05       0  4857.3     0.1       0  4965.4    0.12       0
  5009.3    0.07       0  5047.1    0.12       0  5195.7    0.05       0
  7206.1    0.12       0
Bank Sta=5009.3,5047.1
Exp/Cntr=0.3,0.1

Type RM Length L Ch R = 1,54906,569,569,569
BEGIN DESCRIPTION:
Lacy Fork 10
END DESCRIPTION:
XS GIS Cut Line= 3
      2712151.04      6851935.99      2710475.75      6852480.96
      2708261.75      6854074.24
#Sta/Elev= 30
  3238.3  386.33  3422.4  383.34  3737.8  365.39  3843.0  368.15  3969.2  361.96
  4200.5  362.19  4263.6  359.85  4398.6  365.53  4558.1  351.77  4621.2  355.06
  4652.7  345.33  4673.7  353.02  4696.5  355.06  4833.3  354.39  4968.2  355.64
  4978.7  354.66  4988.3  341.76  4992.8  340.76  5026.1  341.76  5042.8  355.81
  5057.6  354.23  5093.6  356.07  5516.6  352.02  5608.7  354.38  6568.5  355.19
  6576.7  352.61  6612.7  355.32  6962.5  356.98  7220.3  365.98  7727.7  397.27
#Mann=5,-1,0
  3238.3    0.05       0  4833.3    0.12       0  4988.3    0.07       0
  5026.1    0.12       0  5093.6    0.05       0
Bank Sta=4988.3,5026.1
Exp/Cntr=0.3,0.1

Type RM Length L Ch R = 1,54337,485,485,485
BEGIN DESCRIPTION:
Lacy Fork 9
END DESCRIPTION:
XS GIS Cut Line= 3
      2712076.05      6851860.99      2710476.00      6852061.00
      2707750.55      6853753.09
#Sta/Elev= 30
  3386.8  386.97  3840.4  367.61  3931.1  369.29  4069.6  365.53  4230.9  367.76
  4392.1  363.23  4485.3  364.75  4707.0  351.23  4727.2  353.76  4928.8  355.25
  4956.5  353.08  4969.1  344.52  4970.0  341.19  4974.7  340.19  5008.4  341.19
  5012.9  355.69  5053.6  354.91  5159.3  351.92  5376.0  354.15  5412.0  351.43
  5434.8  353.75  5500.6  351.48  6567.0  352.22  6588.3  355.77  6741.3  352.91
  7164.6  353.97  7505.9  362.42  7779.9  384.68  8042.1  392.11  8207.3  402.29
#Mann=4,-1,0
  3386.8    0.05       0  4970.0    0.07       0  5008.4    0.05       0
  5053.6    0.05       0
Bank Sta=4970,5008.4
Exp/Cntr=0.3,0.1

Type RM Length L Ch R = 1,53852,1059,1059,1059
BEGIN DESCRIPTION:
Lacy Fork 873
END DESCRIPTION:
XS GIS Cut Line= 3
      2711901.55      6851807.53      2710239.85      6851776.38
      2707624.76      6853628.46
#Sta/Elev= 30
  3341.3  377.79  3546.9  368.40  3706.9  370.14  3826.9  365.49  3886.9  367.74
  4101.7  362.99  4207.0  363.42  4327.0  358.35  4398.5  360.51  4497.5  355.21
  4617.1  351.40  4637.1  353.91  4957.1  354.65  4977.1  343.58  4977.9  339.22
  4982.6  338.22  5016.3  339.22  5017.0  346.82  5023.2  352.66  5046.0  354.64
  5647.1  352.53  5682.8  350.09  5863.7  352.81  6006.4  350.44  6107.4  355.12
  6365.8  351.34  6429.5  353.53  7226.0  353.51  7506.6  358.79  8207.8  395.86
#Mann=7,-1,0
  3341.3    0.05       0  4101.7    0.12       0  4398.5     0.1       0
  4497.5    0.12       0  4977.9    0.07       0  5016.3    0.12       0
  5046.0    0.05       0
Bank Sta=4977.9,5016.3
Exp/Cntr=0.3,0.1