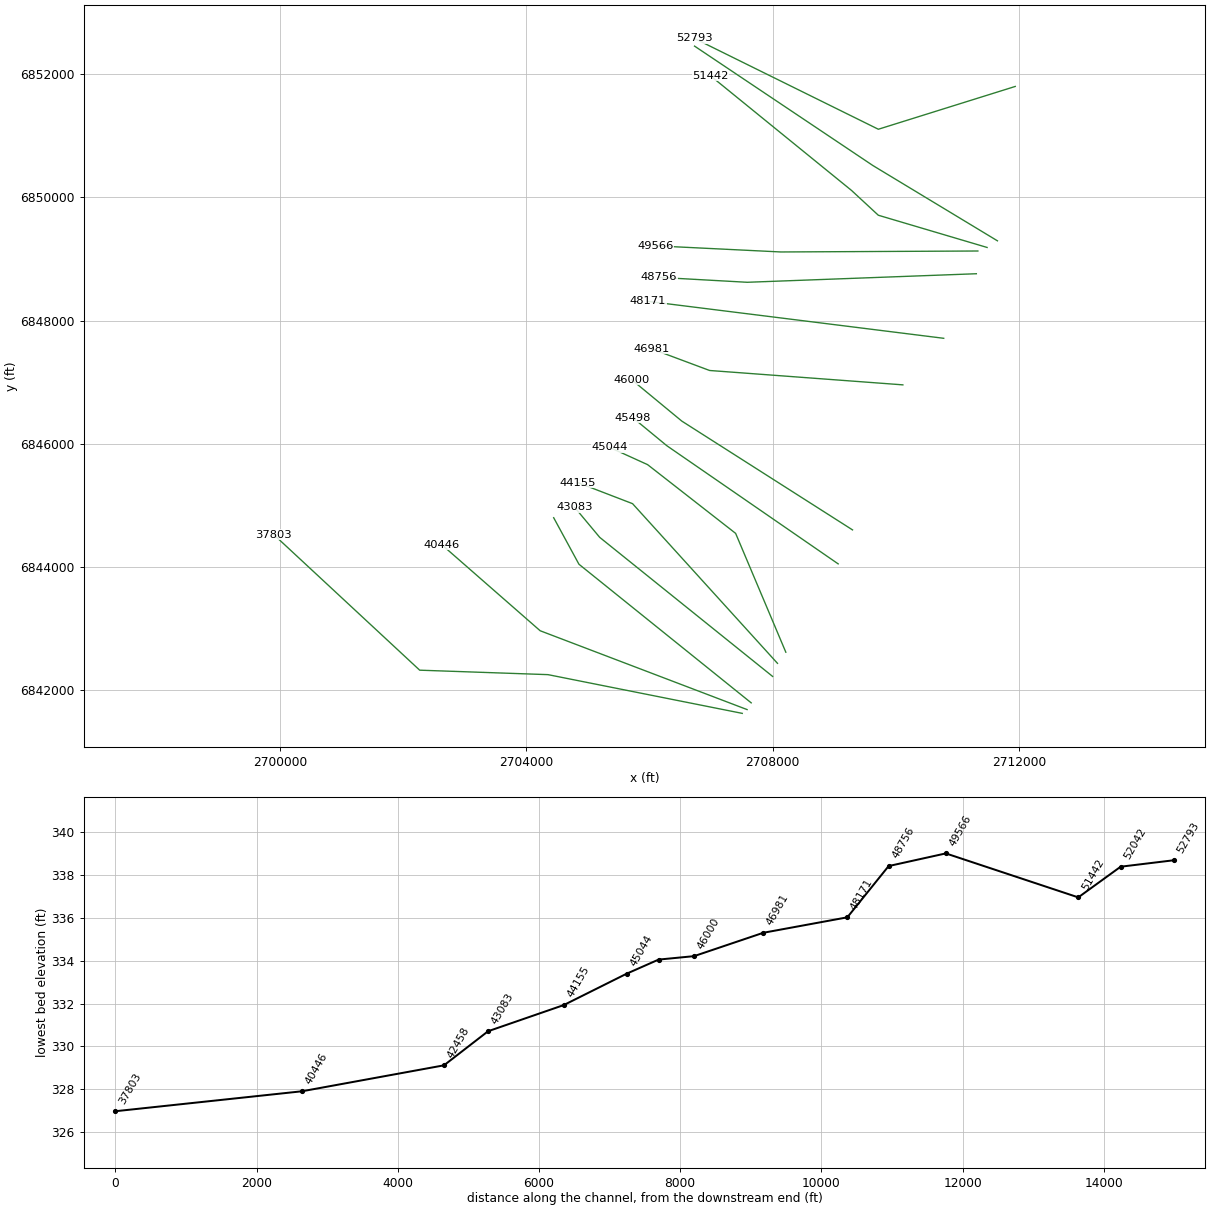
HEC-RAS study Lacy Fork.prj: Lacy Fork Base Level Engineering

--- Lacy Fork.g01 (geometry) --- (continued)

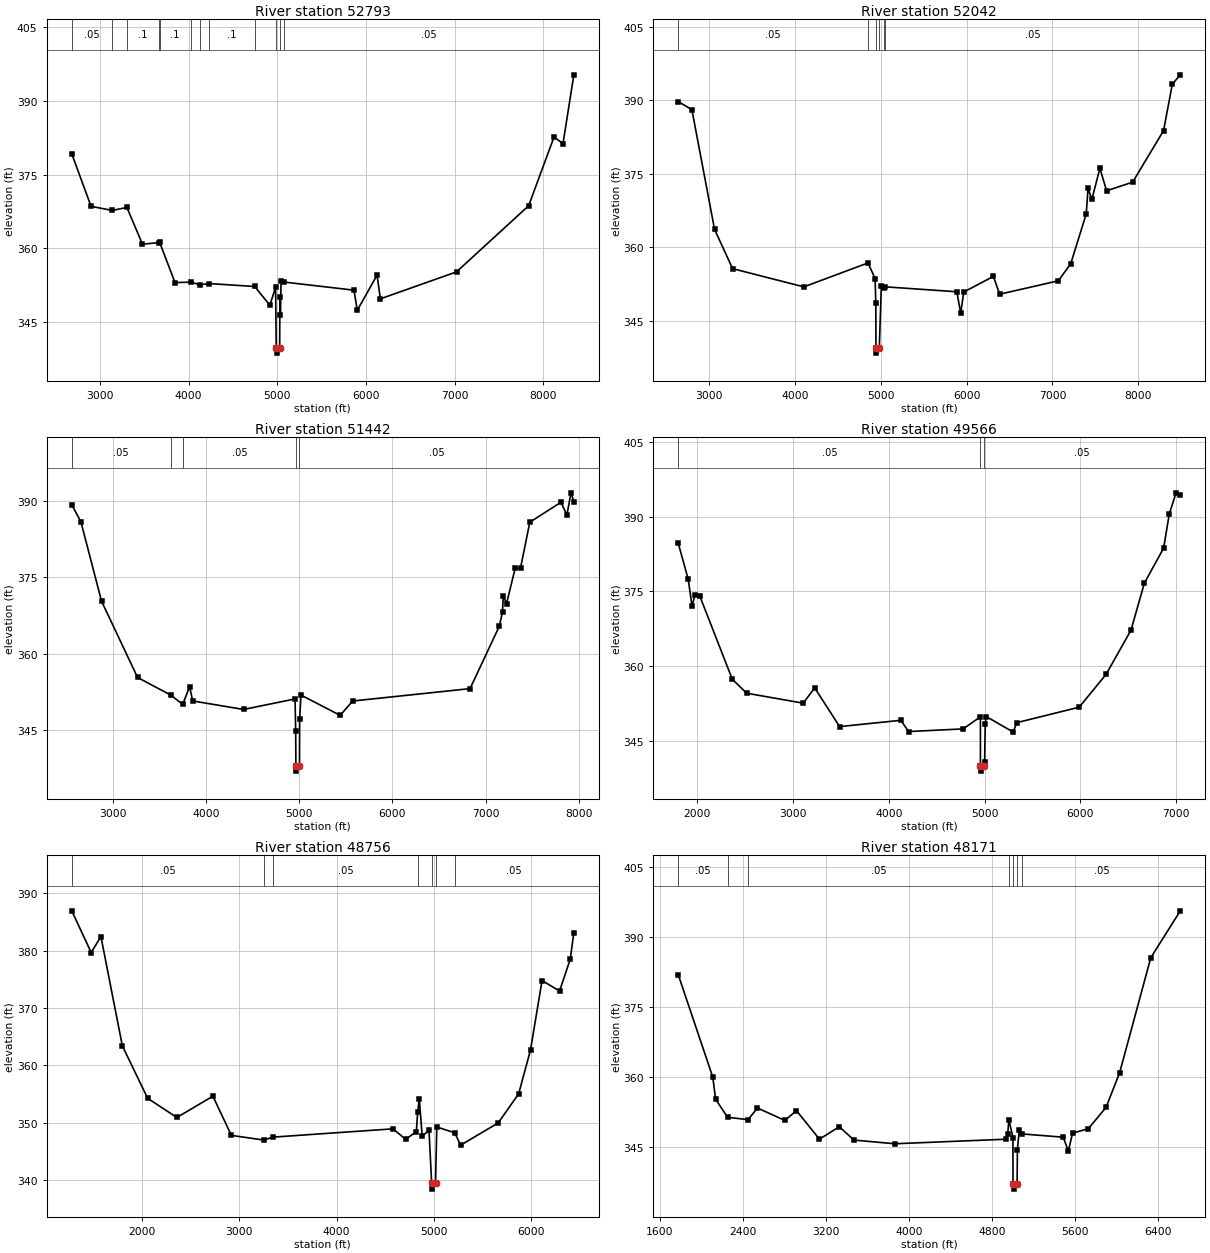
Type RM Length L Ch R = 1,52793,751,751,751
BEGIN DESCRIPTION:
Lacy Fork 872
END DESCRIPTION:
XS GIS Cut Line= 3
      2711936.91      6851801.42      2709714.76      6851106.30
      2706726.36      6852582.81
#Sta/Elev= 30
  2683.5  379.27  2900.9  368.58  3140.1  367.74  3305.2  368.35  3480.8  360.86
  3668.9  361.20  3674.0  361.27  3847.5  353.05  4025.8  353.13  4128.8  352.61
  4231.7  352.85  4746.5  352.25  4916.9  348.44  4981.8  352.06  4989.4  339.68
  4994.0  338.68  5027.8  339.68  5030.5  350.03  5036.0  346.49  5043.9  353.47
  5074.7  353.16  5866.4  351.50  5902.8  347.39  6125.9  354.56  6163.7  349.74
  7022.1  355.23  7835.5  368.70  8121.7  382.70  8222.8  381.34  8345.1  395.36
#Mann=12,-1,0
  2683.5    0.05       0  3140.1    0.12       0  3305.2     0.1       0
  3668.9    0.12       0  3674.0     0.1       0  4025.8    0.05       0
  4128.8    0.12       0  4231.7     0.1       0  4746.5    0.12       0
  4989.4    0.07       0  5027.8    0.12       0  5074.7    0.05       0
Bank Sta=4989.4,5027.8
Exp/Cntr=0.3,0.1

Type RM Length L Ch R = 1,52042,600,600,600
BEGIN DESCRIPTION:
Lacy Fork 871
END DESCRIPTION:
XS GIS Cut Line= 3
      2711647.80      6849294.14      2709628.41      6850515.52
      2706731.71      6852456.51
#Sta/Elev= 30
  2641.6  389.74  2800.6  388.10  3064.4  363.66  3274.8  355.63  4104.6  351.91
  4851.6  356.80  4934.3  353.60  4942.4  348.65  4944.4  339.38  4949.1  338.38
  4983.0  339.38  5006.5  352.04  5039.5  351.72  5050.9  351.92  5886.0  350.91
  5931.0  346.56  5967.0  350.86  6312.2  354.05  6384.3  350.41  7068.7  353.15
  7212.7  356.66  7392.8  366.80  7413.9  372.00  7458.9  369.79  7551.9  376.12
  7630.0  371.53  7933.2  373.29  8293.4  383.81  8395.4  393.30  8488.5  395.21
#Mann=6,-1,0
  2641.6    0.05       0  4851.6    0.12       0  4944.4    0.07       0
  4983.0    0.12       0  5039.5     0.1       0  5050.9    0.05       0
Bank Sta=4944.4,4983
Exp/Cntr=0.3,0.1

Type RM Length L Ch R = 1,51442,1876,1876,1876
BEGIN DESCRIPTION:
Lacy Fork 870
END DESCRIPTION:
XS GIS Cut Line= 4
      2711479.94      6849186.37      2709714.39      6849709.73
      2709279.29      6850112.70      2706992.91      6851972.35
#Sta/Elev= 30
  2563.2  389.25  2661.2  385.91  2882.0  370.34  3268.5  355.34  3621.8  351.91
  3752.7  350.07  3826.4  353.52  3859.6  350.73  4404.7  349.06  4956.5  351.13
  4963.3  344.80  4965.5  337.95  4970.2  336.95  5004.1  337.95  5005.7  347.15
  5020.0  351.89  5440.2  347.90  5574.5  350.72  6832.4  353.15  7145.3  365.38
  7180.5  368.22  7188.4  371.37  7223.6  369.85  7316.3  376.81  7373.7  376.85
  7472.8  385.83  7806.8  389.75  7870.7  387.24  7913.8  391.60  7944.9  389.88
#Mann=5,-1,0
  2563.2    0.05       0  3621.8    0.12       0  3752.7    0.05       0
  4965.5    0.04       0  5004.1    0.05       0
Bank Sta=4965.5,5004.1
Exp/Cntr=0.3,0.1

Type RM Length L Ch R = 1,49566,810,810,810
BEGIN DESCRIPTION:
Lacy Fork 407
END DESCRIPTION:
XS GIS Cut Line= 3
      2711330.48      6849128.80      2708132.11      6849113.18
      2706091.76      6849213.21
#Sta/Elev= 30
  1801.6  384.64  1906.1  377.41  1946.1  372.02  1976.1  374.35  2026.1  374.09
  2366.1  357.40  2516.1  354.61  3106.1  352.61  3226.1  355.68  3486.1  347.92
  4126.1  349.18  4206.1  346.93  4776.1  347.46  4956.1  349.88  4956.4  340.00
  4961.3  339.00  4995.9  340.00  5000.0  340.90  5006.1  348.36  5016.1  349.94
  5296.5  346.85  5336.5  348.71  5987.3  351.81  6267.6  358.37  6527.9  367.24
  6668.1  376.68  6868.4  383.67  6928.4  390.58  6998.5  394.75  7042.8  394.26
#Mann=3,-1,0
  1801.6    0.05       0  4956.4    0.04       0  4995.9    0.05       0
Bank Sta=4956.4,4995.9
Exp/Cntr=0.3,0.1

Type RM Length L Ch R = 1,48756,585,585,585
BEGIN DESCRIPTION:
Lacy Fork 406
END DESCRIPTION:
XS GIS Cut Line= 3
      2711305.48      6848759.57      2707586.77      6848620.70
      2706149.51      6848700.92
#Sta/Elev= 30
  1278.7  386.93  1478.3  379.66  1578.4  382.44  1798.5  363.39  2058.7  354.25
  2358.9  350.90  2729.2  354.61  2919.3  347.78  3250.7  346.97  3349.6  347.48
  4580.5  348.92  4710.6  347.09  4820.6  348.43  4834.3  351.88  4850.7  354.15
  4880.7  347.64  4950.7  348.64  4978.1  339.41  4983.0  338.41  5017.6  339.41
  5030.8  349.24  5215.5  348.23  5275.4  346.07  5661.8  349.95  5872.1  355.02
  5994.8  362.73  6112.5  374.77  6292.8  372.95  6403.0  378.53  6439.5  383.15
#Mann=7,-1,0
  1278.7    0.05       0  3250.7    0.12       0  3349.6    0.05       0
  4834.3     0.1       0  4978.1    0.07       0  5017.6     0.1       0
  5215.5    0.05       0
Bank Sta=4978.1,5017.6
Exp/Cntr=0.3,0.1

Type RM Length L Ch R = 1,48171,1190,1190,1190
BEGIN DESCRIPTION:
Lacy Fork 8
END DESCRIPTION:
XS GIS Cut Line= 3
      2710775.98      6847711.00      2707576.00      6848111.00
      2705976.04      6848311.00
#Sta/Elev= 30
  1775.6  381.97  2108.2  360.03  2135.9  355.30  2250.5  351.41  2448.6  350.91
  2539.0  353.40  2803.5  350.73  2914.4  352.85  3136.1  346.72  3327.6  349.39
  3468.7  346.53  3861.7  345.74  4929.9  346.71  4950.1  347.78  4961.0  350.93
  5000.5  347.02  5000.9  337.02  5005.8  336.02  5040.4  337.02  5043.3  344.50
  5061.0  348.60  5091.2  347.84  5484.2  347.15  5534.6  344.21  5574.9  348.03
  5726.1  348.95  5897.4  353.54  6028.4  360.97  6328.2  385.59  6612.9  395.65
#Mann=7,-1,0
  1775.6    0.05       0  2250.5    0.12       0  2448.6    0.05       0
  4961.0     0.1       0  5000.9    0.07       0  5040.4     0.1       0
  5091.2    0.05       0
Bank Sta=5000.9,5040.4
Exp/Cntr=0.3,0.1

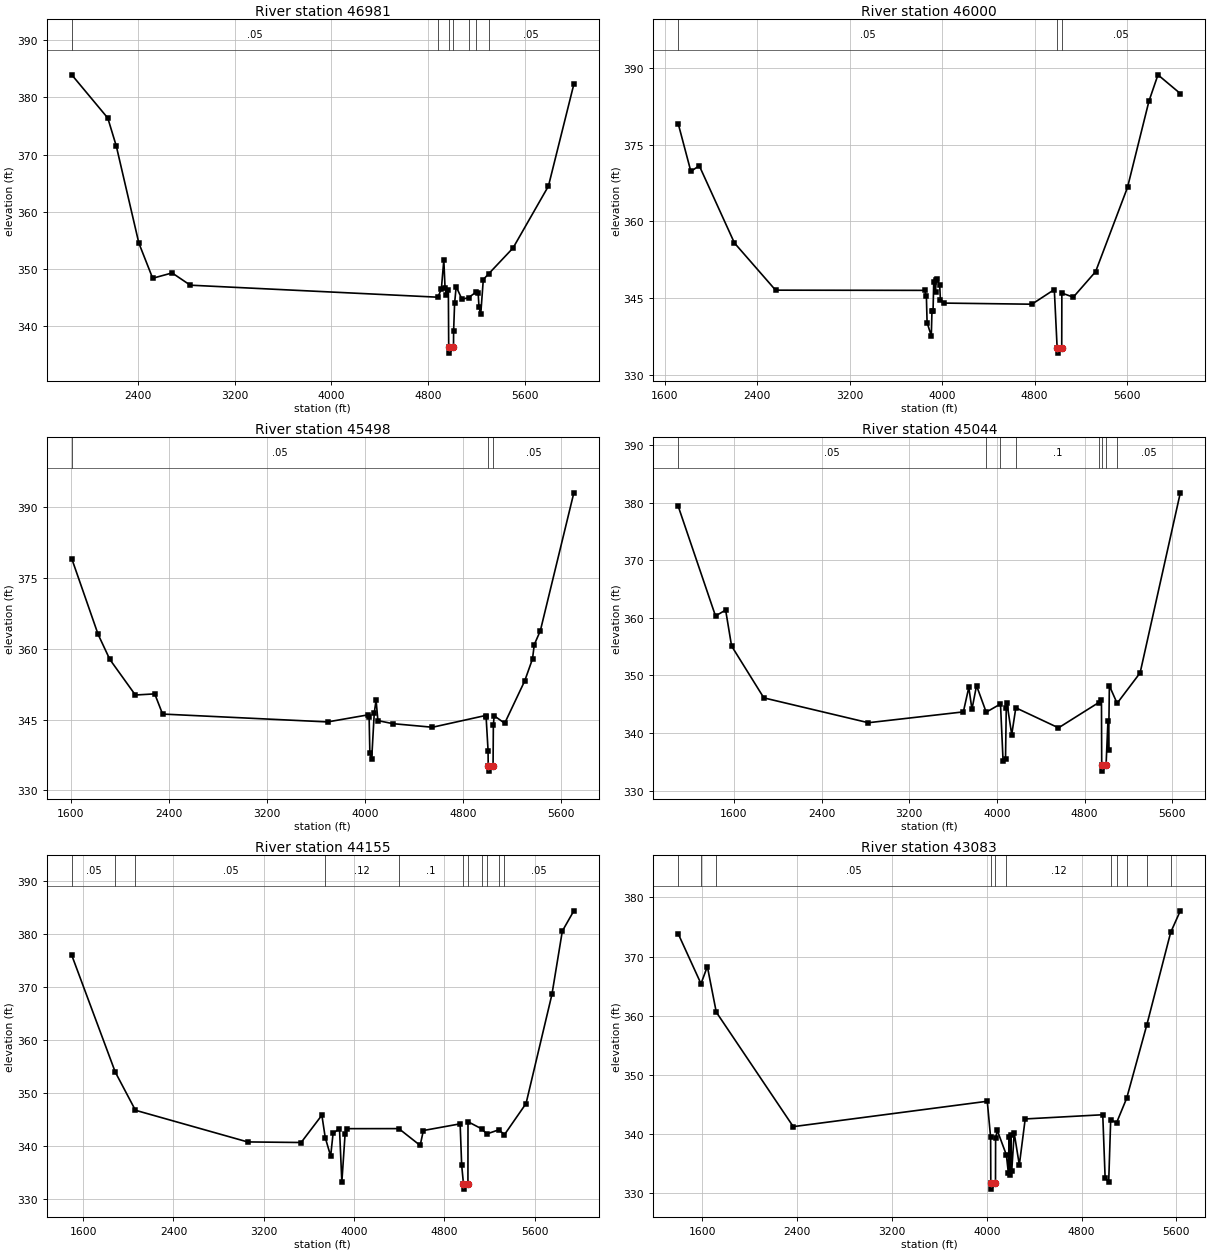
Type RM Length L Ch R = 1,46981,981,981,981
BEGIN DESCRIPTION:
Lacy Fork 405
END DESCRIPTION:
XS GIS Cut Line= 3
      2710112.91      6846954.78      2706976.09      6847188.24
      2706034.90      6847539.78
#Sta/Elev= 30
  1854.5  383.92  2152.2  376.37  2222.4  371.49  2408.9  354.53  2523.3  348.38
  2684.0  349.31  2834.1  347.17  4881.5  345.07  4909.8  346.56  4929.9  351.58
  4939.9  346.76  4950.0  345.53  4967.4  346.32  4970.3  336.30  4975.2  335.30
  5009.9  336.30  5010.8  339.13  5019.1  344.02  5032.1  346.92  5079.8  344.71
  5134.5  344.99  5192.8  345.91  5213.6  345.82  5220.6  343.36  5234.9  342.07
  5256.3  348.16  5299.4  349.13  5501.8  353.66  5794.6  364.48  6004.7  382.28
#Mann=7,-1,0
  1854.5    0.05       0  4881.5     0.1       0  4970.3    0.07       0
  5009.9     0.1       0  5134.5     0.1       0  5192.8    0.12       0
  5299.4    0.05       0
Bank Sta=4970.3,5009.9
Exp/Cntr=0.3,0.1

Type RM Length L Ch R = 1,46000,502,502,502
BEGIN DESCRIPTION:
Lacy Fork 404
END DESCRIPTION:
XS GIS Cut Line= 3
      2709295.73      6844599.06      2706525.05      6846365.96
      2705711.33      6847038.66
#Sta/Elev= 30
  1717.6  379.13  1826.7  369.80  1899.5  370.91  2203.6  355.78  2559.4  346.54
  3848.5  346.50  3863.7  345.32  3869.6  340.20  3906.0  337.58  3911.9  342.42
  3921.2  342.46  3927.2  348.22  3942.4  346.18  3948.3  348.55  3957.6  348.70
  3978.8  347.48  3984.7  344.68  4015.2  344.01  4776.0  343.79  4969.8  346.66
  4994.4  335.21  4999.3  334.21  5034.0  335.21  5035.1  345.97  5134.0  345.17
  5326.9  350.16  5603.0  366.68  5788.0  383.53  5866.2  388.71  6059.5  385.04
#Mann=3,-1,0
  1717.6    0.05       0  4994.4    0.04       0  5034.0    0.05       0
Bank Sta=4994.4,5034
Exp/Cntr=0.3,0.1

Type RM Length L Ch R = 1,45498,454,454,454
BEGIN DESCRIPTION:
Lacy Fork 403
END DESCRIPTION:
XS GIS Cut Line= 3
      2709062.68      6844047.31      2706282.91      6845965.45
      2705731.00      6846420.27
#Sta/Elev= 30
  1610.0  379.12  1824.9  363.05  1920.2  357.75  2128.4  350.20  2286.3  350.44
  2350.2  346.16  3695.7  344.49  4024.9  345.99  4033.7  345.58  4039.7  337.98
  4054.6  336.57  4075.6  346.39  4090.5  349.13  4105.3  344.77  4227.7  344.12
  4550.2  343.36  4982.4  345.85  4987.3  345.57  5003.3  338.42  5004.4  335.05
  5009.3  334.05  5044.0  335.05  5046.4  343.76  5052.8  345.80  5138.8  344.21
  5301.7  353.17  5365.6  357.87  5379.9  360.89  5429.4  363.84  5702.5  393.10
#Mann=3,-1,0
  1610.0    0.05       0  5004.4    0.04       0  5044.0    0.05       0
Bank Sta=5004.4,5044
Exp/Cntr=0.3,0.1

Type RM Length L Ch R = 1,45044,889,889,889
BEGIN DESCRIPTION:
Lacy Fork 402
END DESCRIPTION:
XS GIS Cut Line= 4
      2708213.17      6842612.53      2707398.56      6844542.56
      2705969.82      6845658.81      2705356.70      6845937.78
#Sta/Elev= 30
  1092.0  379.34  1432.1  360.31  1524.5  361.34  1578.8  355.10  1873.2  346.10
  2827.0  341.79  3693.7  343.67  3743.5  347.91  3772.4  344.13  3814.0  348.23
  3902.2  343.62  4032.7  345.04  4056.4  335.10  4078.5  335.43  4085.3  344.34
  4091.7  345.18  4135.1  339.72  4172.5  344.38  4562.0  340.90  4929.2  345.29
  4954.1  345.79  4956.4  334.39  4961.3  333.39  4996.0  334.39  5013.5  342.17
  5019.0  337.04  5026.2  348.21  5096.9  345.16  5306.7  350.44  5673.6  381.68
#Mann=8,-1,0
  1092.0    0.05       0  3902.2     0.1       0  4032.7    0.12       0
  4172.5     0.1       0  4929.2    0.12       0  4956.4    0.07       0
  4996.0    0.12       0  5096.9    0.05       0
Bank Sta=4956.4,4996
Exp/Cntr=0.3,0.1

Type RM Length L Ch R = 1,44155,1072,1072,1072
BEGIN DESCRIPTION:
Lacy Fork 401
END DESCRIPTION:
XS GIS Cut Line= 3
      2708077.69      6842431.68      2705725.36      6845025.20
      2704840.69      6845365.89
#Sta/Elev= 30
  1498.6  376.02  1883.8  354.01  2062.7  346.80  3056.8  340.83  3531.2  340.72
  3715.0  345.87  3744.7  341.66  3792.8  338.16  3814.4  342.45  3871.1  343.34
  3892.1  333.27  3920.5  342.25  3941.4  343.33  4396.7  343.34  4586.1  340.17
  4614.5  342.98  4940.3  344.24  4953.8  336.48  4969.8  332.93  4974.7  331.93
  5009.4  332.93  5010.0  344.64  5131.3  343.29  5176.6  342.33  5283.7  343.12
  5332.9  342.19  5524.4  348.07  5754.1  368.67  5845.9  380.58  5948.0  384.40
#Mann=11,-1,0
  1498.6    0.05       0  1883.8    0.12       0  2062.7    0.05       0
  3744.7    0.12       0  4396.7     0.1       0  4969.8    0.07       0
  5009.4     0.1       0  5131.3    0.12       0  5176.6     0.1       0
  5283.7    0.12       0  5332.9    0.05       0
Bank Sta=4969.8,5009.4
Exp/Cntr=0.3,0.1

Type RM Length L Ch R = 1,43083,625,625,625
BEGIN DESCRIPTION:
Lacy Fork 400
END DESCRIPTION:
XS GIS Cut Line= 3
      2707998.81      6842219.19      2705192.43      6844477.84
      2704786.97      6844963.68
#Sta/Elev= 30
  1397.6  373.85  1589.6  365.42  1643.2  368.33  1718.5  360.62  2367.9  341.27
  4004.4  345.56  4032.7  339.44  4034.2  331.71  4039.1  330.71  4073.8  331.71
  4074.8  339.37  4089.2  340.62  4165.6  336.49  4182.0  333.49  4188.4  339.57
  4196.4  333.11  4202.8  339.80  4210.8  333.79  4231.6  340.20  4274.8  334.79
  4324.4  342.57  4978.6  343.28  4998.5  332.66  5028.6  331.89  5045.6  342.45
  5094.8  341.91  5180.2  346.06  5350.7  358.50  5551.6  374.10  5632.8  377.74
#Mann=11,-1,0
  1397.6    0.05       0  1589.6    0.12       0  1718.5    0.05       0
  4034.2    0.07       0  4073.8    0.05       0  4165.6    0.12       0
  5045.6     0.1       0  5094.8    0.12       0  5180.2    0.05       0
  5350.7    0.12       0  5551.6    0.05       0
Bank Sta=4034.2,4073.8
Exp/Cntr=0.3,0.1

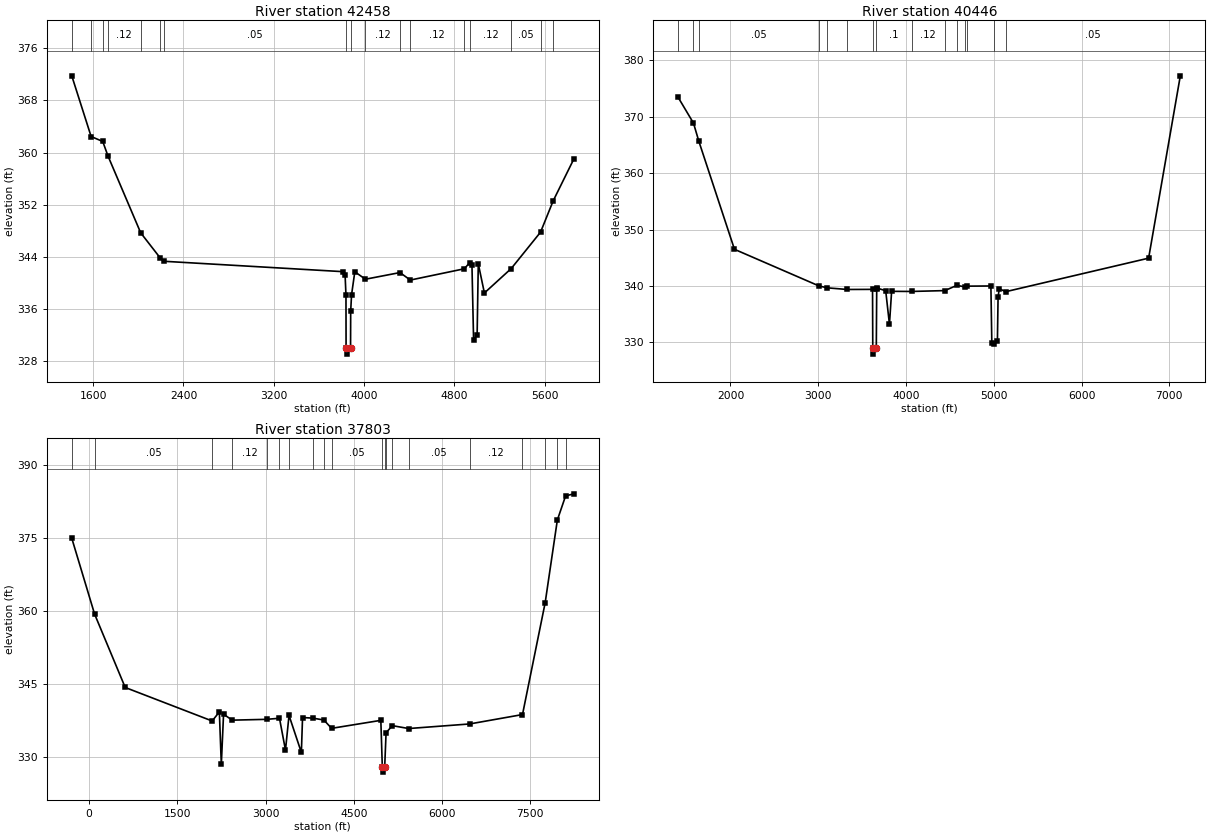
Type RM Length L Ch R = 1,42458,2012,2012,2012
BEGIN DESCRIPTION:
Lacy Fork 399
END DESCRIPTION:
XS GIS Cut Line= 3
      2707651.16      6841789.97      2704855.25      6844041.53
      2704445.06      6844796.95
#Sta/Elev= 30
  1410.2  371.77  1581.7  362.47  1684.6  361.71  1731.0  359.49  2021.0  347.71
  2196.2  343.81  2226.6  343.35  3811.4  341.76  3832.2  341.30  3840.2  338.16
  3841.1  330.12  3846.1  329.12  3880.8  330.12  3882.0  335.70  3889.7  338.22
  3918.5  341.74  4012.7  340.60  4318.9  341.62  4410.2  340.47  4888.8  342.20
  4935.0  343.10  4956.7  342.72  4971.1  331.28  5002.5  332.05  5012.7  342.97
  5066.9  338.49  5304.8  342.24  5564.4  347.81  5676.2  352.60  5859.6  359.03
#Mann=17,-1,0
  1410.2    0.05       0  1581.7    0.12       0  1684.6    0.05       0
  1731.0    0.12       0  2021.0    0.05       0  2196.2    0.12       0
  2226.6    0.05       0  3841.1    0.07       0  3880.8    0.05       0
  4012.7    0.12       0  4318.9     0.1       0  4410.2    0.12       0
  4888.8    0.05       0  4935.0    0.12       0  5304.8    0.05       0
  5564.4    0.12       0  5676.2    0.05       0
Bank Sta=3841.1,3880.8
Exp/Cntr=0.3,0.1

Type RM Length L Ch R = 1,40446,2643,2643,2643
BEGIN DESCRIPTION:
Lacy Fork 7
END DESCRIPTION:
XS GIS Cut Line= 3
      2707584.55      6841680.79      2704226.00      6842961.00
      2702626.00      6844361.00
#Sta/Elev= 30
  1405.1  373.40  1578.7  368.86  1640.1  365.63  2045.7  346.49  3009.8  339.99
  3103.6  339.66  3329.5  339.37  3618.8  339.39  3621.6  328.91  3626.6  327.91
  3661.6  328.91  3666.4  339.40  3672.3  339.61  3768.7  339.15  3811.5  333.21
  3836.2  339.04  4062.8  339.02  4442.7  339.17  4579.9  340.10  4670.4  339.83
  4700.7  339.96  4967.3  339.99  4978.0  329.81  5001.4  329.71  5041.6  330.32
  5049.2  338.10  5063.4  339.52  5134.1  338.97  6764.3  344.92  7125.4  377.24
#Mann=15,-1,0
  1405.1    0.05       0  1578.7    0.12       0  1640.1    0.05       0
  3009.8    0.12       0  3103.6    0.05       0  3329.5     0.1       0
  3621.6    0.07       0  3661.6     0.1       0  4062.8    0.12       0
  4442.7     0.1       0  4579.9    0.12       0  4670.4     0.1       0
  4700.7    0.12       0  5001.4     0.1       0  5134.1    0.05       0
Bank Sta=3621.6,3661.6
Exp/Cntr=0.3,0.1

Type RM Length L Ch R = 1,37803,2091,2091,2091
BEGIN DESCRIPTION:
Lacy Fork 5
END DESCRIPTION:
XS GIS Cut Line= 4
      2707506.25      6841619.17      2704352.71      6842248.27
      2702270.40      6842320.71      2699900.91      6844523.38
#Sta/Elev= 30
  -293.5  375.01    93.7  359.45   614.9  344.36  2093.0  337.48  2215.2  339.35
  2248.5  328.56  2286.6  338.87  2433.8  337.65  3018.9  337.82  3237.3  338.04
  3339.1  331.50  3399.4  338.62  3609.3  331.01  3629.3  338.19  3802.8  338.07
  3991.9  337.68  4122.7  335.97  4960.1  337.61  4985.4  327.98  4990.4  326.98
  5025.4  327.98  5049.1  335.08  5156.6  336.52  5433.0  335.93  6469.1  336.87
  7368.1  338.80  7753.2  361.75  7960.6  378.75  8100.8  383.69  8240.9  384.12
#Mann=20,-1,0
  -293.5    0.12       0    93.7    0.05       0  2093.0     0.1       0
  2433.8    0.12       0  3018.9    0.05       0  3237.3     0.1       0
  3399.4    0.12       0  3802.8     0.1       0  3991.9    0.12       0
  4122.7    0.05       0  4985.4    0.04       0  5025.4    0.05       0
  5049.1     0.1       0  5156.6    0.12       0  5433.0    0.05       0
  6469.1    0.12       0  7368.1     0.1       0  7753.2     0.1       0
  7960.6    0.12       0  8100.8    0.05       0
Bank Sta=4985.4,5025.4
Exp/Cntr=0.3,0.1