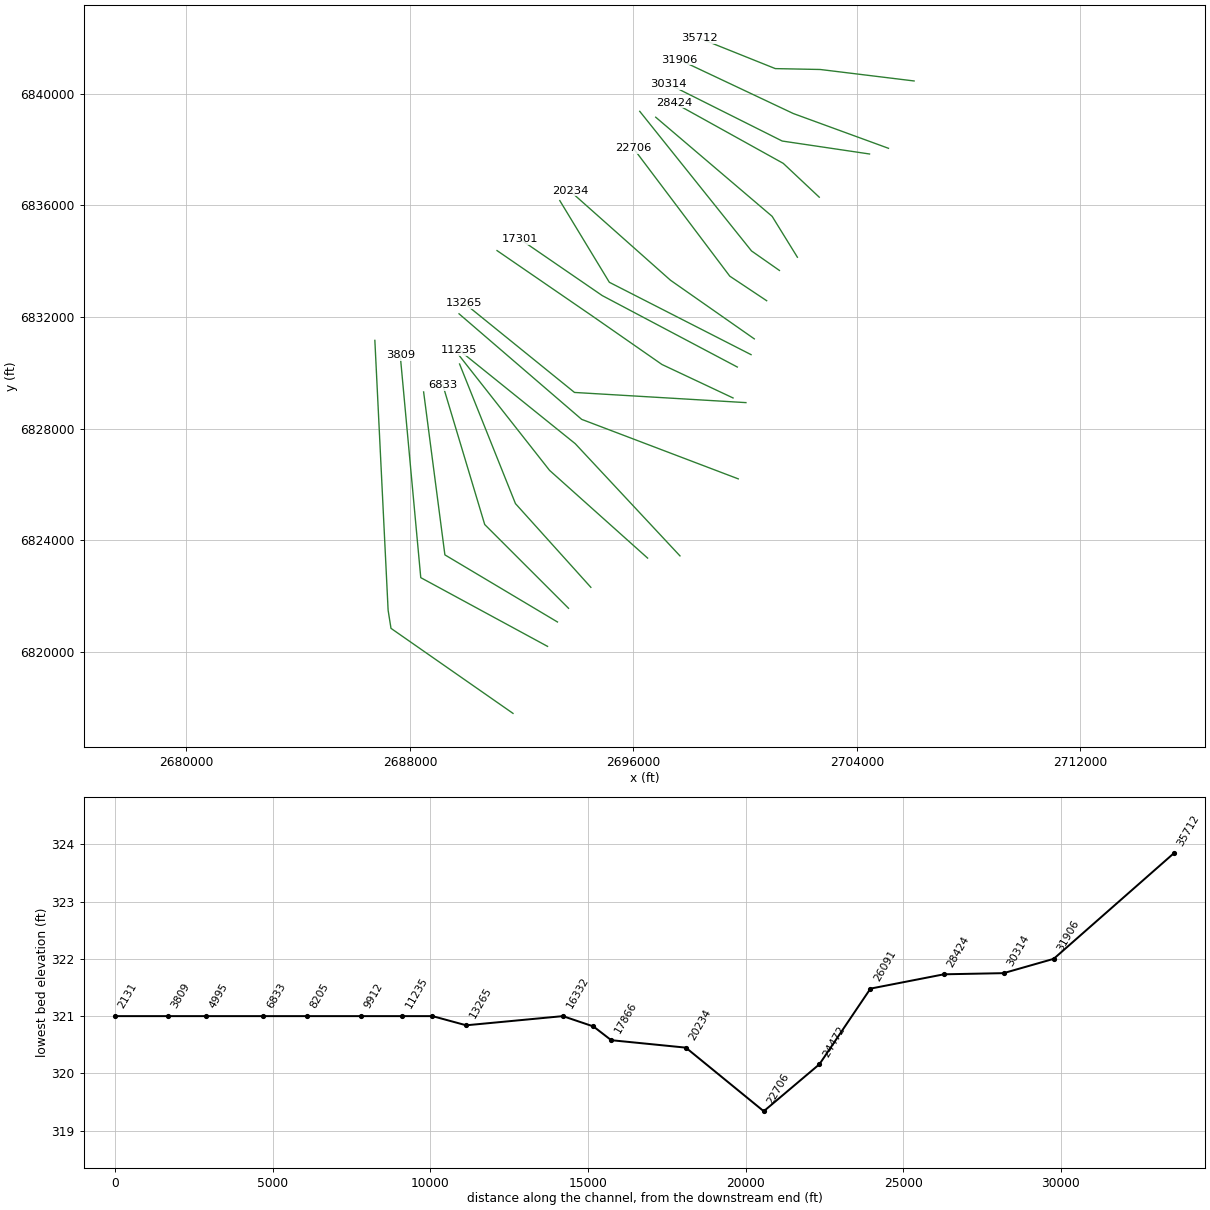
HEC-RAS study Lacy Fork.prj: Lacy Fork Base Level Engineering

--- Lacy Fork.g01 (geometry) --- (continued)

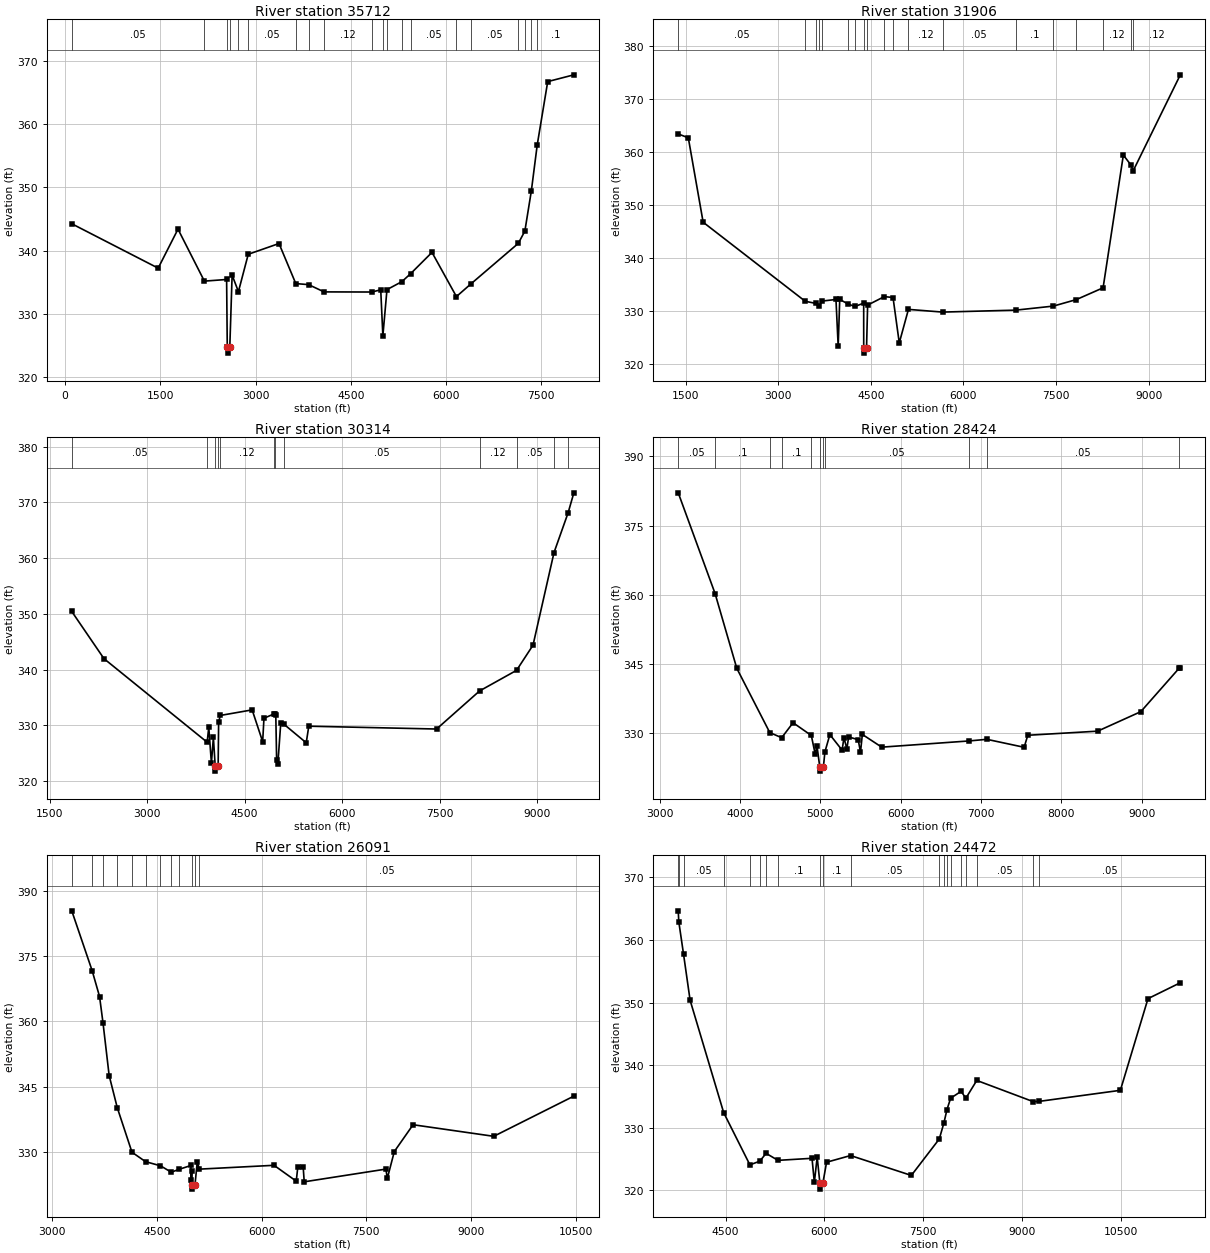
Type RM Length L Ch R = 1,35712,3806,3806,3806
BEGIN DESCRIPTION:
Lacy Fork 4
END DESCRIPTION:
XS GIS Cut Line= 4
      2706046.60      6840449.21      2702687.72      6840860.12
      2701077.49      6840892.06      2698373.93      6841976.18
#Sta/Elev= 30
   104.4  344.27  1465.1  337.26  1777.4  343.42  2193.0  335.21  2543.1  335.47
  2553.3  324.84  2558.2  323.84  2593.3  324.84  2629.8  336.16  2729.1  333.55
  2883.7  339.45  3368.1  341.15  3632.6  334.82  3833.4  334.66  4078.1  333.51
  4829.7  333.49  4970.3  333.84  5003.9  326.57  5068.6  333.87  5303.4  335.13
  5442.5  336.40  5777.5  339.75  6162.4  332.77  6389.2  334.76  7136.5  341.17
  7240.2  343.11  7342.4  349.46  7434.8  356.71  7600.1  366.72  8011.7  367.79
#Mann=20,-1,0
   104.4    0.05       0  2193.0     0.1       0  2553.3    0.07       0
  2593.3     0.1       0  2729.1     0.1       0  2883.7    0.05       0
  3632.6     0.1       0  3833.4    0.05       0  4078.1    0.12       0
  4829.7     0.1       0  5003.9    0.12       0  5068.6    0.05       0
  5303.4    0.12       0  5442.5    0.05       0  6162.4    0.12       0
  6389.2    0.05       0  7136.5     0.1       0  7240.2    0.12       0
  7342.4     0.1       0  7434.8     0.1       0
Bank Sta=2553.3,2593.3
Exp/Cntr=0.3,0.1

Type RM Length L Ch R = 1,31906,1592,1592,1592
BEGIN DESCRIPTION:
Lacy Fork 398
END DESCRIPTION:
XS GIS Cut Line= 3
      2705129.42      6838037.11      2701725.78      6839281.25
      2697643.53      6841209.17
#Sta/Elev= 30
  1376.1  363.34  1539.4  362.61  1779.8  346.69  3434.5  331.78  3602.3  331.39
  3657.5  330.83  3708.7  331.82  3932.9  332.12  3968.8  323.29  3994.0  332.13
  4133.9  331.23  4240.2  330.80  4382.2  331.43  4382.6  323.00  4387.0  322.00
  4428.5  323.00  4446.1  331.06  4716.4  332.66  4857.8  332.49  4959.0  323.93
  5107.5  330.25  5661.6  329.74  6848.9  330.11  7456.1  330.87  7829.6  332.10
  8262.9  334.32  8591.2  359.36  8716.5  357.44  8749.9  356.37  9514.6  374.49
#Mann=19,-1,0
  1376.1    0.05       0  3434.5    0.12       0  3602.3     0.1       0
  3657.5    0.12       0  3708.7     0.1       0  4133.9    0.12       0
  4240.2     0.1       0  4382.6    0.07       0  4428.5     0.1       0
  4716.4    0.12       0  4857.8     0.1       0  5107.5    0.12       0
  5661.6    0.05       0  6848.9     0.1       0  7456.1    0.12       0
  7829.6    0.05       0  8262.9    0.12       0  8716.5     0.1       0
  8749.9    0.12       0
Bank Sta=4382.6,4428.5
Exp/Cntr=0.3,0.1

Type RM Length L Ch R = 1,30314,1890,1890,1890
BEGIN DESCRIPTION:
Lacy Fork 397
END DESCRIPTION:
XS GIS Cut Line= 3
      2704451.13      6837833.23      2701325.93      6838297.48
      2697244.31      6840343.00
#Sta/Elev= 30
  1840.5  350.42  2335.9  341.95  3923.4  326.94  3948.5  329.64  3989.0  323.15
  4019.3  327.81  4046.9  322.75  4051.3  321.75  4092.8  322.75  4100.2  330.57
  4126.4  331.75  4615.8  332.75  4777.5  327.04  4797.7  331.25  4957.4  332.05
  4962.3  331.92  4979.7  331.78  4992.4  323.80  5011.1  323.00  5055.8  330.36
  5105.2  330.17  5448.0  326.84  5487.1  329.82  7453.5  329.31  8115.1  336.15
  8684.1  339.85  8937.2  344.37  9260.3  361.00  9477.7  368.16  9565.5  371.73
#Mann=12,-1,0
  1840.5    0.05       0  3923.4     0.1       0  4046.9    0.07       0
  4092.8     0.1       0  4126.4    0.12       0  4957.4     0.1       0
  4962.3    0.12       0  5105.2    0.05       0  8115.1    0.12       0
  8684.1    0.05       0  9260.3    0.12       0  9477.7    0.05       0
Bank Sta=4046.9,4092.8
Exp/Cntr=0.3,0.1

Type RM Length L Ch R = 1,28424,2333,2333,2333
BEGIN DESCRIPTION:
Lacy Fork 396
END DESCRIPTION:
XS GIS Cut Line= 3
      2702650.98      6836286.02      2701362.70      6837497.60
      2697446.76      6839672.14
#Sta/Elev= 30
  3231.5  382.10  3690.0  360.25  3960.2  344.03  4370.8  330.09  4518.6  328.98
  4660.5  332.23  4887.7  329.46  4936.5  325.34  4957.5  327.25  4992.1  322.73
  4996.5  321.73  5038.5  322.73  5056.6  325.90  5118.3  329.65  5270.7  326.28
  5293.6  329.00  5330.0  326.55  5351.7  329.15  5470.7  328.55  5499.5  325.84
  5522.4  329.69  5763.6  326.93  6852.7  328.28  7071.5  328.63  7535.8  326.90
  7581.3  329.51  8450.6  330.40  8987.6  334.63  9469.0  344.14  9479.2  344.08
#Mann=11,-1,0
  3231.5    0.05       0  3690.0     0.1       0  4370.8    0.05       0
  4518.6     0.1       0  4887.7    0.12       0  4992.1    0.07       0
  5038.5    0.12       0  5056.6    0.05       0  6852.7    0.12       0
  7071.5    0.05       0  9469.0     0.1       0
Bank Sta=4992.1,5038.5
Exp/Cntr=0.3,0.1

Type RM Length L Ch R = 1,26091,1619,1619,1619
BEGIN DESCRIPTION:
Lacy Fork 395
END DESCRIPTION:
XS GIS Cut Line= 3
      2701868.99      6834135.04      2700964.90      6835599.55
      2696797.38      6839151.02
#Sta/Elev= 30
  3278.9  385.40  3571.1  371.65  3677.2  365.71  3727.3  359.58  3814.7  347.57
  3930.8  340.20  4141.6  329.96  4336.1  327.79  4550.4  326.84  4705.1  325.37
  4818.5  326.03  4986.2  326.91  4992.1  323.66  4997.9  325.75  4998.6  322.48
  5003.0  321.48  5045.0  322.48  5077.8  327.77  5106.6  326.07  6178.1  326.95
  6496.5  323.31  6518.5  326.53  6596.4  326.45  6610.7  323.16  7781.2  326.08
  7802.1  323.95  7902.0  330.11  8171.0  336.27  9327.3  333.61 10475.5  342.84
#Mann=12,-1,0
  3278.9    0.05       0  3571.1     0.1       0  3727.3    0.05       0
  3930.8     0.1       0  4141.6    0.12       0  4336.1     0.1       0
  4550.4    0.05       0  4705.1     0.1       0  4818.5    0.12       0
  4998.6    0.07       0  5045.0    0.12       0  5106.6    0.05       0
Bank Sta=4998.6,5045
Exp/Cntr=0.3,0.1

Type RM Length L Ch R = 1,24472,1766,1766,1766
BEGIN DESCRIPTION:
Lacy Fork 3
END DESCRIPTION:
XS GIS Cut Line= 3
      2701225.98      6833661.01      2700226.00      6834361.00
      2696225.97      6839361.03
#Sta/Elev= 30
  3779.7  364.66  3788.1  362.92  3860.8  357.69  3959.7  350.37  4469.4  332.40
  4867.8  324.04  5018.2  324.63  5113.6  325.88  5294.9  324.76  5811.1  325.09
  5846.3  321.24  5889.6  325.28  5930.3  321.16  5934.7  320.16  5976.8  321.16
  6032.0  324.46  6396.5  325.53  7319.1  322.35  7743.7  328.18  7814.0  330.75
  7860.6  332.89  7916.0  334.70  8075.3  335.80  8146.9  334.69  8312.7  337.54
  9167.4  334.16  9259.0  334.19 10493.4  335.96 10912.8  350.62 11403.5  353.16
#Mann=20,-1,0
  3779.7    0.05       0  3788.1     0.1       0  3860.8    0.05       0
  4469.4     0.1       0  4867.8    0.12       0  5018.2     0.1       0
  5113.6    0.12       0  5294.9     0.1       0  5930.3    0.07       0
  5976.8     0.1       0  6396.5    0.05       0  7743.7     0.1       0
  7814.0    0.12       0  7860.6     0.1       0  7916.0    0.12       0
  8075.3     0.1       0  8146.9    0.12       0  8312.7    0.05       0
  9167.4    0.12       0  9259.0    0.05       0
Bank Sta=5930.3,5976.8
Exp/Cntr=0.3,0.1

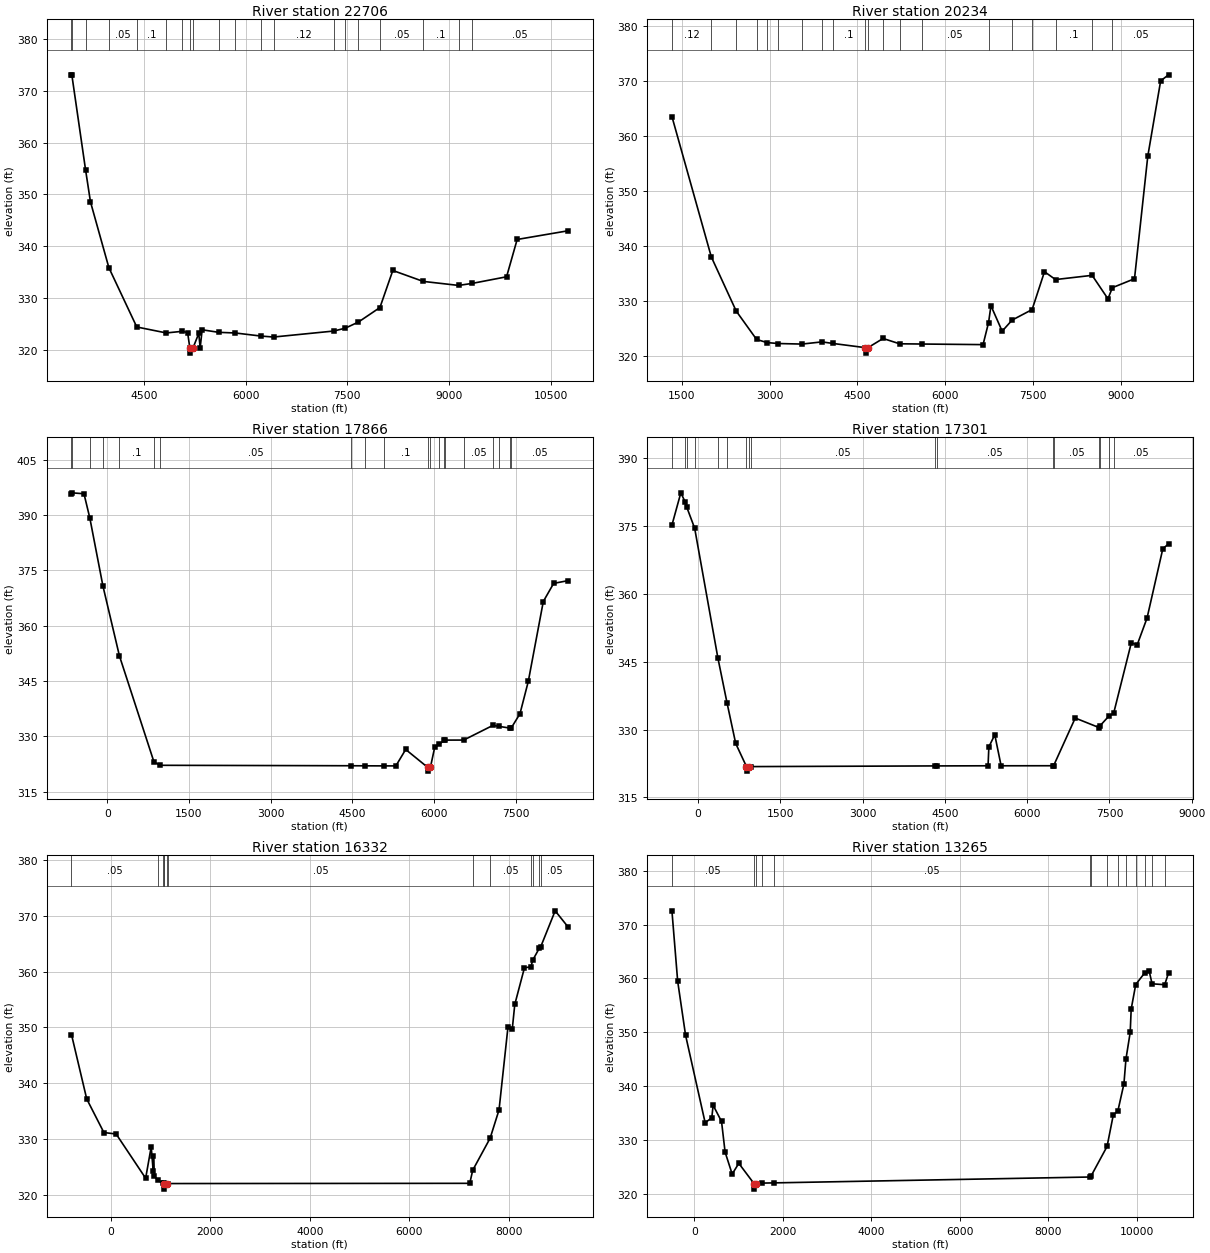
Type RM Length L Ch R = 1,22706,2472,2472,2472
BEGIN DESCRIPTION:
Lacy Fork 394
END DESCRIPTION:
XS GIS Cut Line= 3
      2700769.10      6832577.63      2699448.88      6833457.00
      2695995.91      6838042.04
#Sta/Elev= 30
  3430.4  373.11  3435.3  373.11  3637.4  354.80  3710.3  348.57  3981.8  335.85
  4393.5  324.39  4829.2  323.24  5061.4  323.55  5143.4  323.32  5176.3  320.34
  5180.7  319.34  5222.9  320.34  5307.9  323.14  5328.7  320.36  5357.8  323.85
  5601.5  323.36  5848.8  323.23  6223.5  322.64  6411.4  322.45  7300.9  323.61
  7470.8  324.17  7662.7  325.34  7980.6  328.15  8170.8  335.31  8618.2  333.20
  9141.2  332.42  9341.1  332.81  9849.0  334.09 10005.2  341.30 10756.5  342.98
#Mann=20,-1,0
  3430.4     0.1       0  3435.3    0.12       0  3637.4     0.1       0
  3981.8    0.05       0  4393.5     0.1       0  4829.2    0.12       0
  5061.4     0.1       0  5176.3    0.07       0  5222.9     0.1       0
  5601.5    0.12       0  5848.8     0.1       0  6223.5     0.1       0
  6411.4    0.12       0  7300.9    0.12       0  7470.8    0.12       0
  7662.7    0.12       0  7980.6    0.05       0  8618.2     0.1       0
  9141.2    0.12       0  9341.1    0.05       0
Bank Sta=5176.3,5222.9
Exp/Cntr=0.3,0.1

Type RM Length L Ch R = 1,20234,2368,2368,2368
BEGIN DESCRIPTION:
Lacy Fork 2
END DESCRIPTION:
XS GIS Cut Line= 3
      2700326.00      6831211.00      2697326.00      6833311.00
      2693726.00      6836511.00
#Sta/Elev= 30
  1332.9  363.58  2005.3  337.99  2430.3  328.12  2777.9  322.95  2956.4  322.37
  3150.1  322.20  3553.3  322.10  3894.9  322.50  4084.1  322.21  4633.7  321.45
  4638.1  320.45  4680.3  321.45  4938.0  323.12  5220.7  322.15  5595.4  322.11
  6645.1  322.00  6739.3  326.03  6779.8  329.09  6971.3  324.45  7140.8  326.47
  7482.6  328.39  7693.8  335.29  7882.1  333.86  8507.4  334.63  8777.5  330.35
  8853.1  332.38  9230.7  334.01  9457.4  356.33  9677.3  370.08  9811.5  371.18
#Mann=20,-1,0
  1332.9    0.12       0  2005.3     0.1       0  2430.3    0.12       0
  2777.9    0.12       0  2956.4     0.1       0  3150.1    0.12       0
  3553.3     0.1       0  3894.9    0.12       0  4084.1     0.1       0
  4633.7    0.07       0  4680.3     0.1       0  4938.0     0.1       0
  5220.7     0.1       0  5595.4    0.05       0  6739.3    0.12       0
  7140.8     0.1       0  7482.6    0.05       0  7882.1     0.1       0
  8507.4    0.05       0  8853.1    0.05       0
Bank Sta=4633.7,4680.3
Exp/Cntr=0.3,0.1

Type RM Length L Ch R = 1,17866,565,565,565
BEGIN DESCRIPTION:
Lacy Fork 393
END DESCRIPTION:
XS GIS Cut Line= 3
      2700210.14      6830645.80      2695137.53      6833237.56
      2693364.01      6836163.45
#Sta/Elev= 30
  -655.8  395.83  -650.3  396.02  -426.6  395.77  -318.5  389.14   -78.9  370.78
   223.9  351.84   857.9  323.09   970.5  322.16  4484.0  322.04  4724.7  322.02
  5077.2  322.00  5300.0  322.00  5480.3  326.45  5886.1  321.58  5890.3  320.58
  5933.8  321.58  6013.5  327.07  6097.4  327.83  6180.3  328.90  6199.7  328.99
  6545.3  329.00  7083.2  332.99  7193.7  332.71  7392.6  332.25  7421.8  332.37
  7578.3  336.12  7731.5  344.91  8006.9  366.56  8196.9  371.47  8462.0  372.22
#Mann=20,-1,0
  -655.8    0.05       0  -650.3     0.1       0  -318.5     0.1       0
   -78.9    0.12       0   223.9     0.1       0   857.9    0.12       0
   970.5    0.05       0  4484.0    0.12       0  4724.7    0.05       0
  5077.2     0.1       0  5886.1    0.03       0  5933.8     0.1       0
  6097.4    0.12       0  6180.3    0.05       0  6199.7    0.12       0
  6545.3    0.05       0  7083.2    0.12       0  7193.7    0.05       0
  7392.6    0.12       0  7421.8    0.05       0
Bank Sta=5886.1,5933.8
Exp/Cntr=0.3,0.1

Type RM Length L Ch R = 1,17301,969,969,969
BEGIN DESCRIPTION:
Lacy Fork 358
END DESCRIPTION:
XS GIS Cut Line= 3
      2699718.20      6830202.04      2694885.05      6832760.29
      2691930.73      6834789.43
#Sta/Elev= 30
  -475.7  375.12  -313.4  382.25  -231.8  380.17  -206.3  379.12   -61.0  374.43
   360.8  345.89   529.5  335.85   686.8  326.93   883.3  321.82   887.5  320.82
   931.0  321.82   969.8  321.82  4313.4  321.97  4353.8  321.97  5287.1  322.00
  5302.0  326.17  5409.6  328.84  5525.4  322.00  6475.4  322.01  6482.0  322.01
  6876.6  332.54  7317.6  330.40  7332.4  330.88  7484.7  332.90  7576.6  333.59
  7898.3  349.13  8005.9  348.70  8185.2  354.60  8473.4  369.93  8576.8  370.96
#Mann=17,-1,0
  -475.7     0.1       0  -231.8    0.12       0  -206.3     0.1       0
   -61.0    0.05       0   360.8    0.12       0   529.5     0.1       0
   883.3    0.05       0   931.0     0.1       0   969.8    0.05       0
  4313.4     0.1       0  4353.8    0.05       0  6475.4   0.075       0
  6482.0    0.05       0  7317.6    0.12       0  7332.4    0.05       0
  7484.7    0.12       0  7576.6    0.05       0
Bank Sta=883.3,931
Exp/Cntr=0.3,0.1

Type RM Length L Ch R = 1,16332,3067,3067,3067
BEGIN DESCRIPTION:
Lacy Fork 357
END DESCRIPTION:
XS GIS Cut Line= 4
      2699565.45      6829094.36      2697022.01      6830292.60
      2694534.18      6832025.10      2691116.95      6834373.18
#Sta/Elev= 30
  -794.9  348.73  -488.8  337.18  -143.3  331.15   103.0  330.89   696.8  322.95
   808.7  328.60   848.7  324.23   854.3  326.91   871.5  323.30   940.3  322.59
  1038.0  322.12  1062.1  322.03  1070.8  322.00  1075.0  321.00  1118.7  322.00
  1148.7  322.00  7216.8  322.04  7276.0  324.39  7626.4  330.14  7805.5  335.21
  7984.7  350.03  8071.4  349.68  8122.1  354.12  8316.3  360.69  8446.4  360.89
  8484.5  362.09  8612.7  364.17  8643.2  364.45  8934.7  370.92  9194.5  368.02
#Mann=13,-1,0
  -794.9    0.05       0   940.3    0.12       0  1038.0     0.1       0
  1062.1    0.12       0  1070.8    0.03       0  1118.7    0.12       0
  1148.7    0.05       0  7276.0    0.12       0  7626.4    0.05       0
  8446.4   0.075       0  8484.5    0.05       0  8612.7   0.075       0
  8643.2    0.05       0
Bank Sta=1070.8,1118.7
Exp/Cntr=0.3,0.1

Type RM Length L Ch R = 1,13265,1070,1070,1070
BEGIN DESCRIPTION:
Lacy Fork 356
END DESCRIPTION:
XS GIS Cut Line= 3
      2700026.15      6828927.51      2693890.02      6829291.86
      2689940.14      6832493.30
#Sta/Elev= 30
  -510.0  372.56  -379.6  359.45  -201.2  349.43   241.5  333.18   391.7  334.10
   421.8  336.43   612.1  333.41   692.3  327.73   852.5  323.64  1002.8  325.63
  1349.2  321.84  1353.4  320.84  1397.7  321.84  1522.5  321.96  1791.4  322.00
  8936.5  323.09  8973.4  323.33  9331.5  328.77  9471.3  334.58  9577.6  335.43
  9712.7  340.40  9758.6  345.00  9854.9  349.98  9877.1  354.30  9979.6  358.86
 10181.8  361.02 10281.7  361.44 10349.7  359.00 10635.0  358.83 10721.3  361.01
#Mann=14,-1,0
  -510.0    0.05       0  1349.2    0.03       0  1397.7    0.05       0
  1522.5    0.12       0  1791.4    0.05       0  8936.5    0.12       0
  8973.4     0.1       0  9331.5    0.12       0  9577.6    0.05       0
  9758.6     0.1       0  9979.6    0.05       0 10181.8     0.1       0
 10349.7    0.05       0 10635.0     0.1       0
Bank Sta=1349.2,1397.7
Exp/Cntr=0.3,0.1

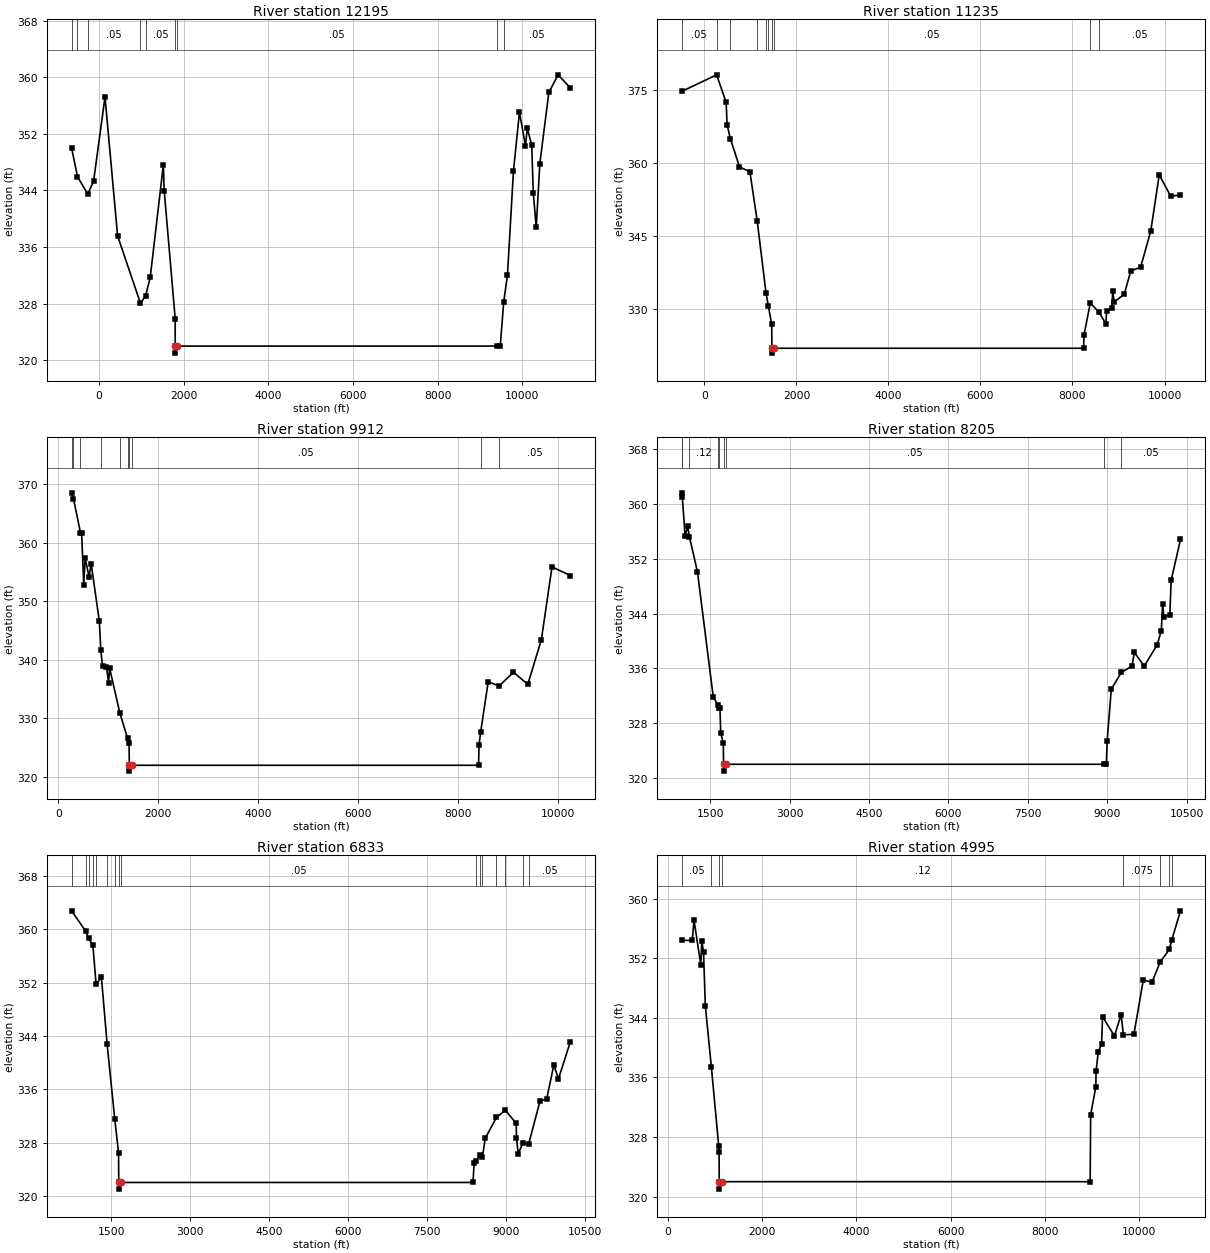
Type RM Length L Ch R = 1,12195,960,960,960
BEGIN DESCRIPTION:
Lacy Fork 355
END DESCRIPTION:
XS GIS Cut Line= 3
      2699751.79      6826196.21      2694146.72      6828327.83
      2689756.84      6832108.95
#Sta/Elev= 30
  -650.4  350.00  -511.3  345.94  -268.2  343.48  -130.7  345.31   139.4  357.20
   436.4  337.58   977.1  328.05  1098.9  329.09  1208.9  331.74  1518.7  347.61
  1538.2  343.98  1798.5  325.87  1799.0  322.00  1803.1  321.00  1847.6  322.00
  9409.6  322.00  9482.8  322.00  9565.5  328.27  9652.8  331.99  9795.0  346.73
  9937.0  355.05 10078.5  350.32 10121.3  352.75 10227.7  350.40 10262.9  343.65
 10334.2  338.82 10418.7  347.79 10631.5  357.85 10850.9  360.33 11140.1  358.48
#Mann=9,-1,0
  -650.4    0.05       0  -511.3    0.12       0  -268.2    0.05       0
   977.1    0.12       0  1098.9    0.05       0  1799.0    0.03       0
  1847.6    0.05       0  9409.6    0.12       0  9565.5    0.05       0
Bank Sta=1799,1847.6
Exp/Cntr=0.3,0.1

Type RM Length L Ch R = 1,11235,1323,1323,1323
BEGIN DESCRIPTION:
Lacy Fork 354
END DESCRIPTION:
XS GIS Cut Line= 3
      2697666.08      6823436.67      2693916.38      6827456.81
      2689756.36      6830810.13
#Sta/Elev= 30
  -493.6  374.77   265.1  378.18   471.6  372.51   493.1  367.89   562.7  365.08
   761.8  359.27   988.5  358.24  1147.4  348.14  1337.7  333.40  1386.8  330.78
  1462.4  326.91  1466.3  322.00  1470.4  321.00  1515.2  322.00  8242.4  322.00
  8250.3  324.73  8386.4  331.27  8571.8  329.49  8727.0  327.01  8741.3  329.73
  8854.9  330.22  8875.7  333.83  8904.5  331.51  9125.2  333.09  9267.6  337.92
  9480.3  338.64  9701.0  346.08  9885.2  357.62 10134.5  353.25 10347.1  353.49
#Mann=10,-1,0
  -493.6    0.05       0   265.1    0.12       0   562.7     0.1       0
  1147.4    0.12       0  1337.7     0.1       0  1386.8    0.05       0
  1466.3    0.03       0  1515.2    0.05       0  8386.4   0.075       0
  8571.8    0.05       0
Bank Sta=1466.3,1515.2
Exp/Cntr=0.3,0.1

Type RM Length L Ch R = 1,9912,1707,1707,1707
BEGIN DESCRIPTION:
Lacy Fork 359
END DESCRIPTION:
XS GIS Cut Line= 3
      2696506.66      6823358.71      2692997.20      6826501.12
      2689745.82      6830636.33
#Sta/Elev= 30
   267.0  368.52   303.8  367.53   444.8  361.70   467.7  361.63   509.5  352.81
   537.9  357.39   616.4  354.17   658.3  356.42   821.3  346.60   850.7  341.68
   885.3  338.90   963.3  338.86  1006.0  336.12  1026.9  338.58  1231.1  330.93
  1387.3  326.59  1416.4  325.87  1420.3  322.00  1424.4  321.00  1469.3  322.00
  8403.7  322.00  8411.8  325.41  8446.4  327.76  8596.2  336.27  8813.2  335.53
  9101.4  337.89  9386.9  335.82  9658.0  343.41  9871.3  355.87 10238.1  354.40
#Mann=10,-1,0
   267.0    0.05       0   303.8     0.1       0   444.8    0.12       0
   850.7     0.1       0  1231.1    0.12       0  1387.3    0.05       0
  1420.3    0.03       0  1469.3    0.05       0  8446.4    0.12       0
  8813.2    0.05       0
Bank Sta=1420.3,1469.3
Exp/Cntr=0.3,0.1

Type RM Length L Ch R = 1,8205,1372,1372,1372
BEGIN DESCRIPTION:
Lacy Fork 1
END DESCRIPTION:
XS GIS Cut Line= 3
      2694476.00      6822311.00      2691776.00      6825311.00
      2689776.02      6830310.96
#Sta/Elev= 30
   963.6  361.63   973.9  361.02  1027.5  355.35  1076.8  356.72  1108.0  355.25
  1260.7  350.09  1558.2  331.88  1647.7  330.61  1670.5  330.23  1686.0  330.16
  1700.2  326.50  1749.5  325.12  1753.3  322.00  1757.3  321.00  1802.6  322.00
  8943.5  322.00  8984.7  322.00  8999.5  325.37  9077.6  332.96  9266.8  335.40
  9469.4  336.34  9513.8  338.33  9699.6  336.33  9944.6  339.44 10022.7  341.50
 10046.9  345.45 10071.2  343.57 10184.2  343.85 10208.5  348.84 10384.8  354.82
#Mann=9,-1,0
   963.6    0.12       0   973.9     0.1       0  1108.0    0.12       0
  1647.7     0.1       0  1670.5    0.05       0  1753.3    0.03       0
  1802.6    0.05       0  8943.5    0.12       0  9266.8    0.05       0
Bank Sta=1753.3,1802.6
Exp/Cntr=0.3,0.1

Type RM Length L Ch R = 1,6833,1838,1838,1838
BEGIN DESCRIPTION:
Lacy Fork 0
END DESCRIPTION:
XS GIS Cut Line= 3
      2693675.99      6821561.01      2690676.00      6824561.00
      2689175.99      6829561.02
#Sta/Elev= 30
   752.1  362.80  1020.7  359.72  1072.8  358.66  1156.0  357.62  1216.2  351.78
  1317.8  352.80  1426.5  342.75  1569.6  331.60  1643.0  326.47  1646.7  322.00
  1650.7  321.00  1696.0  322.00  8366.9  322.00  8390.4  324.91  8426.2  325.20
  8496.5  326.10  8547.7  325.87  8599.2  328.61  8812.9  331.78  8982.9  332.84
  9187.4  330.88  9192.6  328.65  9225.7  326.35  9320.4  327.98  9421.9  327.73
  9638.0  334.19  9765.9  334.55  9901.7  339.66  9989.5  337.56 10214.9  343.13
#Mann=16,-1,0
   752.1    0.12       0  1020.7    0.05       0  1072.8    0.12       0
  1156.0    0.05       0  1216.2     0.1       0  1426.5    0.12       0
  1569.6    0.05       0  1646.7    0.03       0  1696.0    0.05       0
  8426.2    0.12       0  8496.5    0.05       0  8547.7    0.12       0
  8812.9    0.05       0  8982.9     0.1       0  9320.4    0.12       0
  9421.9    0.05       0
Bank Sta=1646.7,1696
Exp/Cntr=0.3,0.1

Type RM Length L Ch R = 1,4995,1186,1186,1186
BEGIN DESCRIPTION:
Lacy Fork 353
END DESCRIPTION:
XS GIS Cut Line= 3
      2693280.26      6821069.78      2689250.80      6823473.69
      2688489.20      6829310.05
#Sta/Elev= 30
   297.7  354.40   521.3  354.38   558.3  357.10   702.3  351.10   723.7  354.31
   760.7  352.79   797.7  345.64   926.9  337.37  1082.8  326.73  1089.6  325.99
  1093.1  322.00  1097.2  321.00  1142.4  322.00  8960.4  322.00  8970.5  330.98
  9080.3  334.73  9085.3  336.87  9131.9  339.40  9202.5  340.47  9222.6  344.16
  9475.2  341.55  9616.0  344.42  9666.2  341.70  9888.2  341.79 10086.9  349.08
 10271.5  348.76 10440.7  351.43 10640.6  353.20 10693.0  354.48 10875.6  358.36
#Mann=8,-1,0
   297.7    0.05       0   926.9    0.12       0  1093.1    0.03       0
  1142.4    0.12       0  9666.2   0.075       0 10440.7    0.05       0
 10640.6    0.12       0 10693.0    0.05       0
Bank Sta=1093.1,1142.4
Exp/Cntr=0.3,0.1

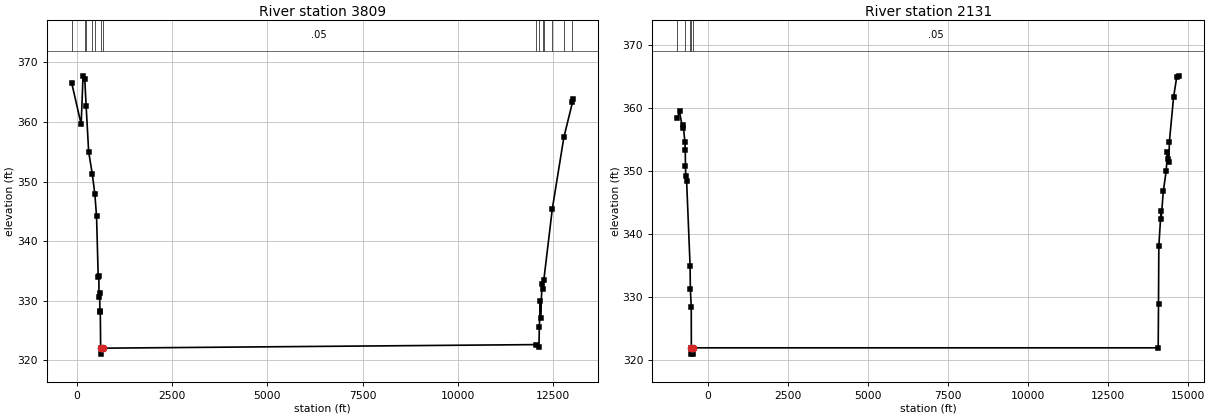
Type RM Length L Ch R = 1,3809,1678,1678,1678
BEGIN DESCRIPTION:
Lacy Fork 350
END DESCRIPTION:
XS GIS Cut Line= 3
      2692924.98      6820195.96      2688387.05      6822657.90
      2687651.81      6830624.91
#Sta/Elev= 30
  -136.3  366.54   111.3  359.59   160.7  367.76   206.4  367.15   242.2  362.63
   308.0  355.00   403.1  351.27   470.4  347.90   515.3  344.13   559.0  333.96
   575.2  334.13   580.9  330.63   597.0  331.34   602.7  328.00   613.2  328.27
   622.7  322.00   626.7  321.00   672.4  322.00 12041.2  322.60 12129.6  322.28
 12139.3  325.56 12165.2  329.92 12170.2  327.15 12209.9  332.71 12237.4  332.01
 12256.4  333.41 12480.5  345.44 12783.5  357.44 13008.7  363.30 13027.3  363.89
#Mann=14,-1,0
  -136.3    0.05       0   206.4     0.1       0   242.2    0.05       0
   403.1     0.1       0   470.4    0.05       0   622.7    0.03       0
   672.4    0.05       0 12041.2    0.12       0 12139.3     0.1       0
 12237.4    0.12       0 12256.4     0.1       0 12480.5    0.12       0
 12783.5     0.1       0 13008.7    0.05       0
Bank Sta=622.7,672.4
Exp/Cntr=0.3,0.1

Type RM Length L Ch R = 1,2131,0,0,0
BEGIN DESCRIPTION:
Lacy Fork 352
END DESCRIPTION:
XS GIS Cut Line= 4
      2691688.58      6817795.92      2687321.28      6820841.92
      2687218.75      6821489.05      2686743.70      6831157.48
#Sta/Elev= 30
  -949.2  358.54  -885.2  359.51  -792.7  356.87  -771.8  357.42  -716.0  354.62
  -706.3  353.32  -700.2  350.88  -691.5  349.31  -664.5  348.52  -555.9  335.04
  -547.5  331.30  -519.3  328.54  -516.7  322.00  -512.7  321.00  -470.7  321.00
  -466.7  322.00 14063.4  322.00 14073.5  329.02 14083.5  338.15 14151.5  343.65
 14156.5  342.50 14223.6  346.86 14313.7  350.09 14353.5  353.08 14358.5  352.03
 14393.8  351.46 14413.9  354.74 14544.0  361.78 14644.1  365.05 14710.7  365.17
#Mann=5,-1,0
  -949.2    0.05       0  -716.0    0.12       0  -547.5    0.05       0
  -516.7    0.03       0  -466.7    0.05       0
Bank Sta=-516.7,-466.7
Exp/Cntr=0.3,0.1

Chan Stop Cuts=-1