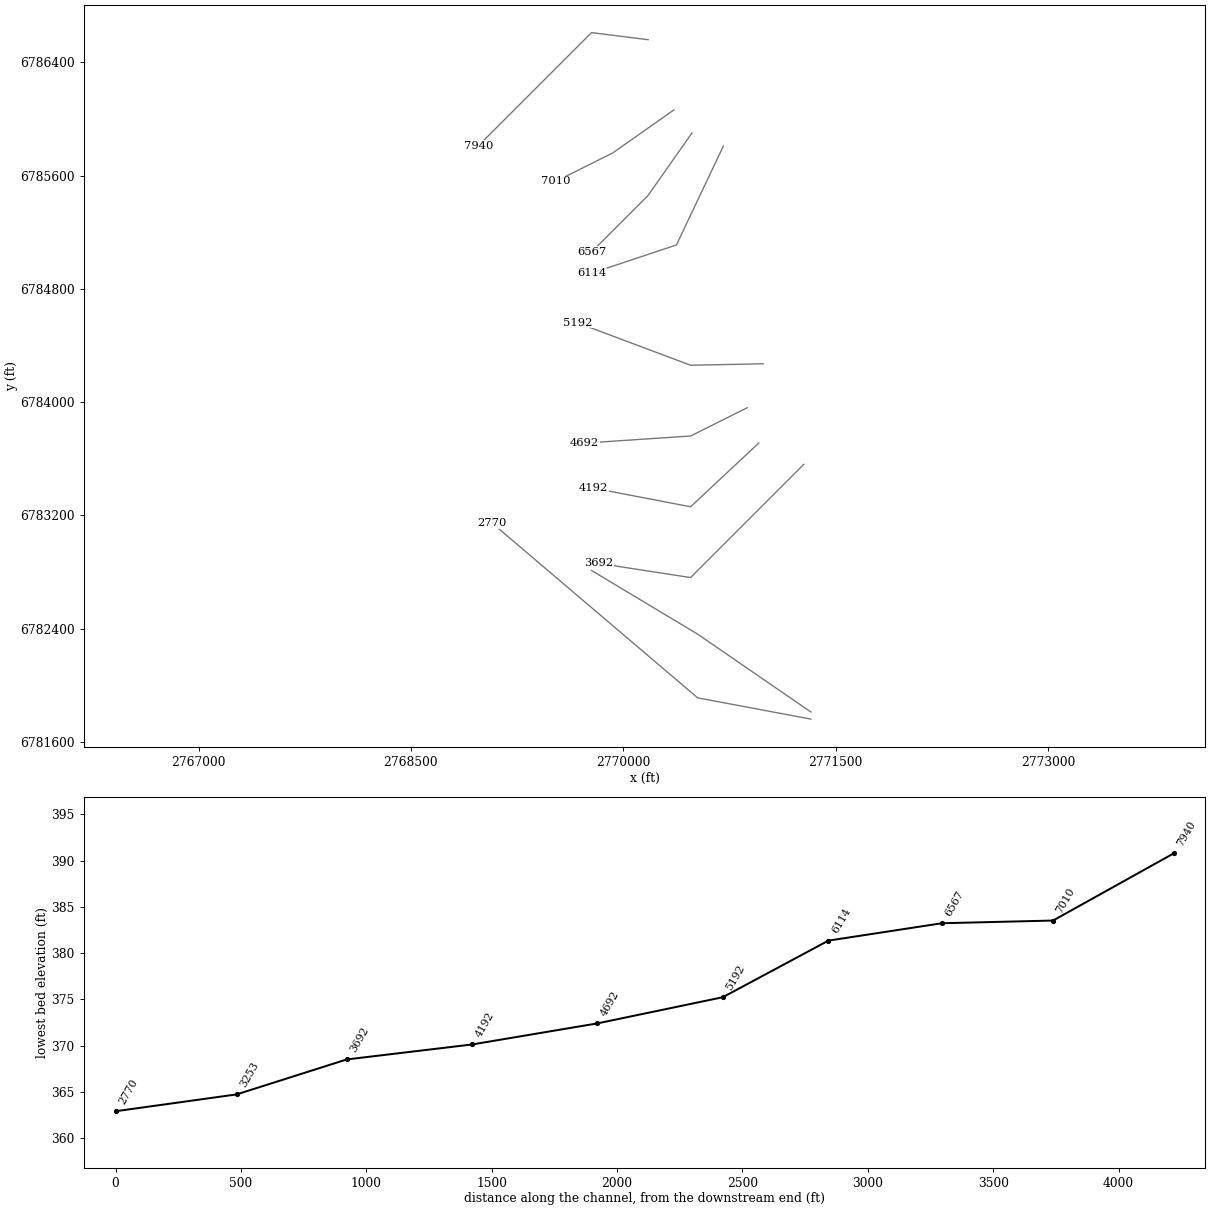
HEC-RAS study Larue Branch.prj: Larue Branch Base Level Engineering

--- Larue Branch.g02 (geometry) --- (continued)

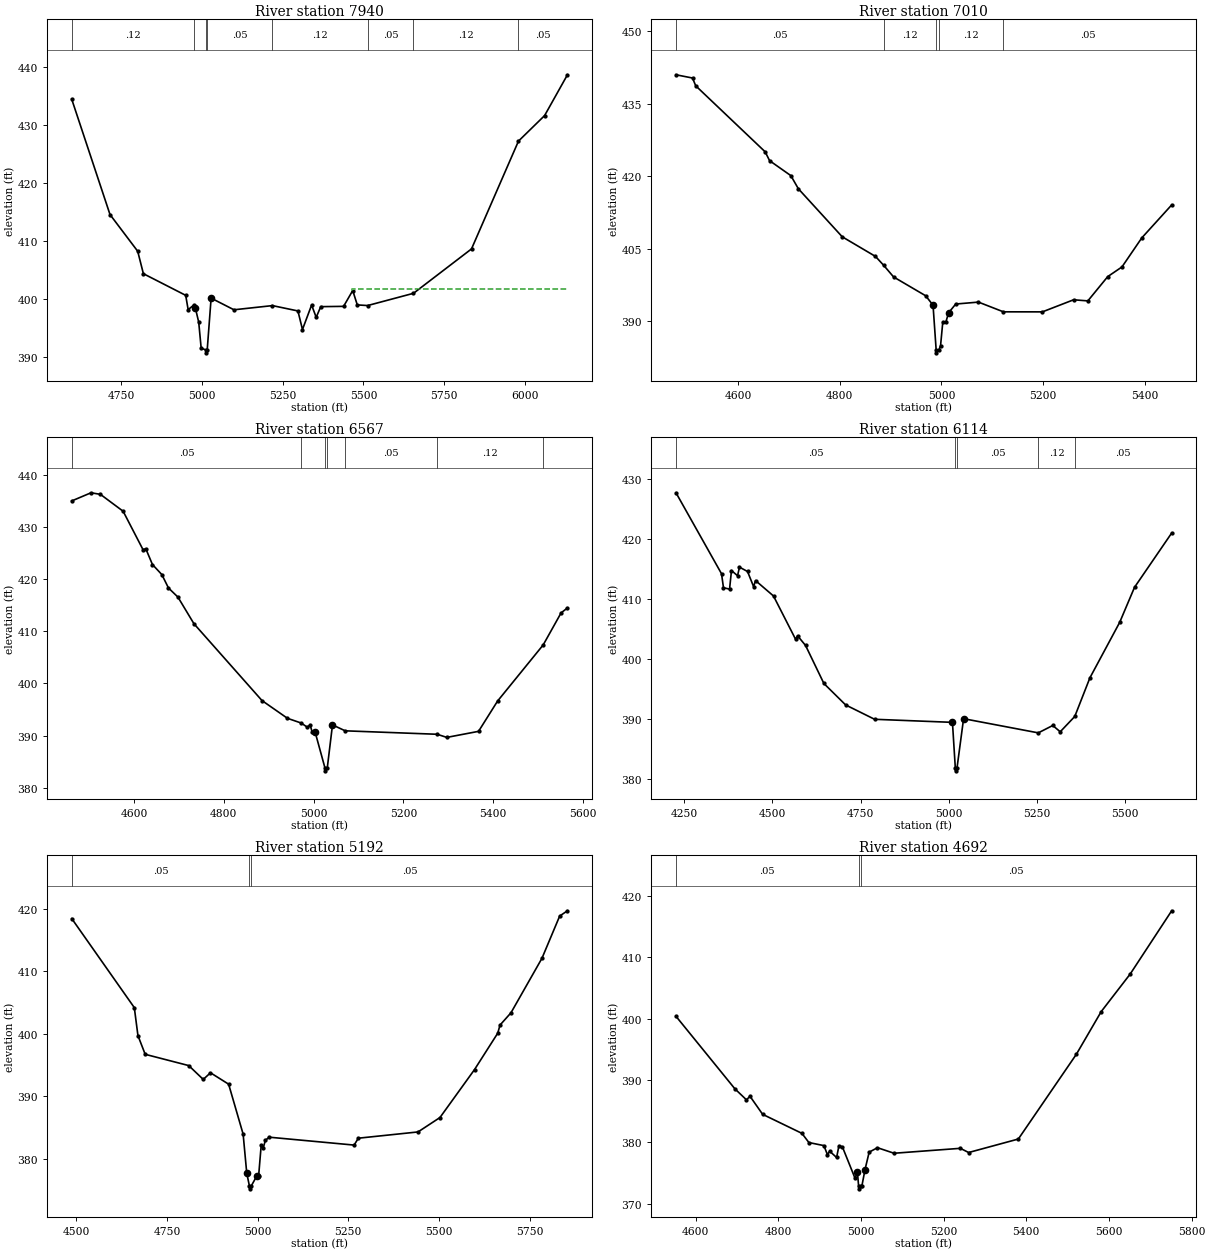
Type RM Length L Ch R = 1 ,7940    ,481,481,481
BEGIN DESCRIPTION:
Larue Branch 14.0
END DESCRIPTION:
XS GIS Cut Line= 3
      2770175.99        6786561.        2769776.        6786611.
      2768975.98      6785810.98
#Sta/Elev= 30
  4596.9  434.47  4715.3  414.61    4801  408.29  4818.6  404.42  4949.6  400.69
  4957.2  398.22  4975.1  399.04  4979.8  398.44  4989.9  396.07  4997.5  391.58
  5012.1  391.28  5012.4  390.78  5016.2  391.28  5028.3  400.21    5099   398.2
  5218.2  398.92    5297     398  5311.1   394.8  5339.4  399.02  5353.6   396.9
  5367.7  398.74  5438.4  398.79  5466.7  401.52  5480.8  399.04  5512.8  398.93
  5654.8  401.04  5834.4  408.69  5979.8  427.27  6060.7  431.67  6131.4   438.7
#Mann= 8 ,-1 , 0
  4596.9     .12       0  4975.1     .05       0  5012.1     .05       0
  5016.2     .05       0  5218.2     .12       0  5512.8     .05       0
  5654.8     .12       0  5979.8     .05       0
#XS Ineff= 2 , 0
                         5465.06           401.7
Permanent Ineff=
       F       F
Bank Sta=4979.8,5028.3
XS Rating Curve= 0 ,0
Exp/Cntr=0.3,0.1

Type RM Length L Ch R = 1 ,7010    ,443,443,443
BEGIN DESCRIPTION:
Larue Branch 12.0
END DESCRIPTION:
XS GIS Cut Line= 3
      2770357.73       6786064.6        2769926.        6785761.
        2769526.        6785561.
#Sta/Elev= 30
  4477.8  441.01  4510.3  440.34  4516.6  438.73  4653.2  425.08  4661.9  423.25
  4703.7  420.16  4718.5  417.44  4804.8  407.51  4870.1  403.46  4886.2  401.63
  4905.8  399.21  4968.9  395.32  4983.4  393.37  4989.6  384.02  4990.2  383.52
  4994.5  384.02  4998.2  385.01  5002.5   389.8  5008.4   389.8    5014   391.8
    5028  393.61  5072.7  394.01  5121.8     392  5198.5  391.99  5259.9  394.49
  5287.9  394.26    5327  399.28    5355  401.28  5394.1   407.3  5452.8   414.1
#Mann= 5 ,-1 , 0
  4477.8     .05       0  4886.2     .12       0  4989.6     .07       0
  4994.5     .12       0  5121.8     .05       0
Bank Sta=4983.4,5014
XS Rating Curve= 0 ,0
Exp/Cntr=0.3,0.1

Type RM Length L Ch R = 1 ,6567    ,453,453,453
BEGIN DESCRIPTION:
Larue Branch 11.0
END DESCRIPTION:
XS GIS Cut Line= 3
      2770485.38      6785901.51        2770176.        6785461.
      2769775.99      6785060.99
#Sta/Elev= 30
  4461.5  434.97  4504.4  436.53  4525.3  436.23  4575.9  432.99  4620.3  425.61
  4626.4   425.8  4641.2  422.78  4662.1  420.85  4676.9  418.28  4697.9  416.54
  4733.6  411.43  4885.2   396.7  4941.9   393.3  4972.6  392.39  4986.3  391.58
  4992.4  392.04  4996.7  390.73  5003.3  390.73  5025.6  383.73  5026.2  383.23
  5030.5  383.73  5042.2  392.04  5070.5   390.9  5275.3  390.24  5296.8  389.64
  5367.5   390.8  5409.9  396.61  5511.5  407.37  5551.3   413.5  5565.5  414.46
#Mann= 7 ,-1 , 0
  4461.5     .05       0  4972.6     .12       0  5025.6     .07       0
  5030.5     .12       0  5070.5     .05       0  5275.3     .12       0
  5511.5     .05       0
Bank Sta=5003.3,5042.2
XS Rating Curve= 0 ,0
Exp/Cntr=0.3,0.1

Type RM Length L Ch R = 1 ,6114    ,421,421,421
BEGIN DESCRIPTION:
Larue Branch 10.0
END DESCRIPTION:
XS GIS Cut Line= 3
      2770707.63      6785809.98        2770376.        6785111.
      2769776.02      6784911.01
#Sta/Elev= 30
  4226.3  427.63  4355.4  414.16    4361  411.83  4378.2  411.59  4383.7  414.69
  4400.9  413.82  4406.4  415.25  4429.2  414.53  4446.4  412.01  4451.9  413.02
  4502.9  410.45  4565.6  403.24  4571.1  403.83  4593.8  402.22  4645.8  395.89
  4707.5  392.32  4789.7  389.93  5010.5  389.42  5018.6  381.85  5019.2  381.35
  5023.5  381.85  5042.1  390.03    5254  387.67  5295.1   388.9  5316.2  387.85
  5357.5   390.4  5400.5  396.84  5484.8  406.05    5527   411.9  5632.4  420.93
#Mann= 5 ,-1 , 0
  4226.3     .05       0  5018.6     .04       0  5023.5     .05       0
    5254     .12       0  5357.5     .05       0
Bank Sta=5010.5,5042.1
XS Rating Curve= 0 ,0
Exp/Cntr=0.3,0.1

Type RM Length L Ch R = 1 ,5192    ,500,500,500
BEGIN DESCRIPTION:
Larue Branch 8.0
END DESCRIPTION:
XS GIS Cut Line= 3
       2770988.5      6784271.26        2770476.        6784261.
        2769676.        6784561.
#Sta/Elev= 30
  4487.4   418.4  4659.9  404.18  4669.9  399.71  4689.9  396.72    4810  394.92
    4850  392.71    4870  393.77    4920  391.95    4960  383.97    4970  377.72
  4977.2  375.73    4978  375.23  4982.8  375.73  4997.5  377.27  5002.7  377.27
  5009.8  382.18  5015.1  381.69  5021.4  382.99    5032  383.48  5266.1  382.22
  5277.7  383.32  5442.3  384.32  5502.8  386.62  5598.1  394.28  5662.2   400.1
  5668.4  401.39  5698.6  403.35  5784.1  412.06    5833  418.81  5854.4  419.65
#Mann= 3 ,-1 , 0
  4487.4     .05       0  4977.2     .04       0  4982.8     .05       0
Bank Sta=4970,4997.5
XS Rating Curve= 0 ,0
Exp/Cntr=0.3,0.1

Type RM Length L Ch R = 1 ,4692    ,500,500,500
BEGIN DESCRIPTION:
Larue Branch 7.0
END DESCRIPTION:
XS GIS Cut Line= 3
      2770875.99      6783960.99        2770476.        6783761.
      2769725.96        6783711.
#Sta/Elev= 30
  4552.8  400.42  4695.3  388.64  4723.3  386.85  4731.7  387.44  4762.4   384.5
  4857.4  381.41  4874.2  379.92  4910.6  379.42  4918.9  377.97  4924.5  378.51
  4941.3  377.49  4946.9  379.41  4955.3  379.21    4986  374.09  4991.6  375.13
  4994.4   372.9  4995.3   372.4    5000   372.9  5002.5   372.9    5010  375.53
    5020  378.36  5040.1  379.08  5080.2  378.18  5240.5  378.98  5260.6   378.3
  5380.8  380.49  5521.2  394.26  5581.3  401.19  5651.4  407.29  5751.7  417.56
#Mann= 3 ,-1 , 0
  4552.8     .05       0  4994.4     .04       0    5000     .05       0
Bank Sta=4991.6,5010
XS Rating Curve= 0 ,0
Exp/Cntr=0.3,0.1

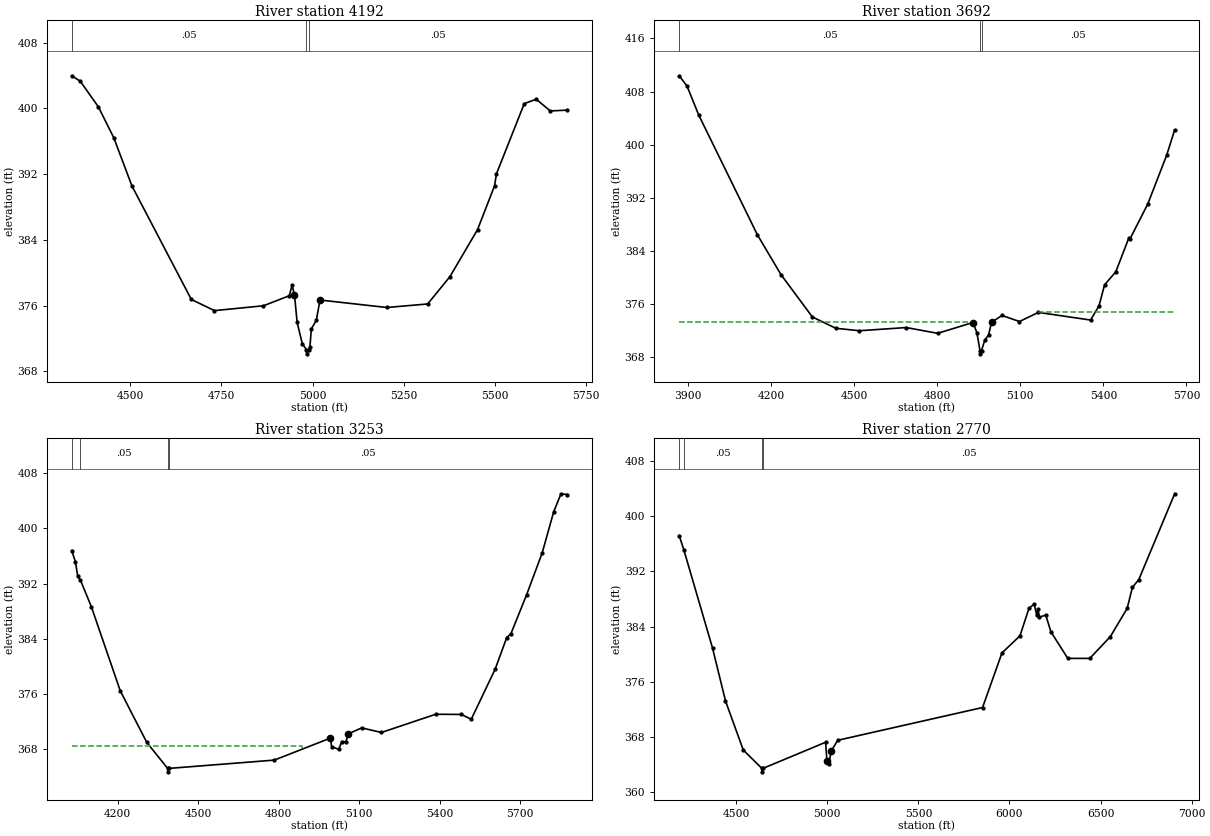
Type RM Length L Ch R = 1 ,4192    ,500,500,500
BEGIN DESCRIPTION:
Larue Branch 6.0
END DESCRIPTION:
XS GIS Cut Line= 3
      2770958.15      6783711.99        2770476.        6783261.
       2769790.2      6783392.55
#Sta/Elev= 30
  4339.8  403.96  4363.2   403.3  4412.6  400.19  4455.1  396.41  4504.9  390.54
  4667.6  376.74  4731.1  375.38  4865.4  375.97  4936.3  377.19  4943.6  378.45
  4950.4  377.33  4957.7  373.95  4971.9  371.35  4983.3  370.62  4984.1  370.12
  4988.9  370.62  4992.9  370.99  4996.6  373.15  5010.2  374.18  5020.4  376.67
  5203.6  375.76  5315.6  376.19  5376.7  379.52  5452.2  385.23  5498.9  390.56
  5504.2  392.03  5580.4  400.57  5613.2  401.11  5651.7  399.68  5698.3  399.78
#Mann= 3 ,-1 , 0
  4339.8     .05       0  4983.3     .04       0  4988.9     .05       0
Bank Sta=4950.4,5020.4
XS Rating Curve= 0 ,0
Exp/Cntr=0.3,0.1

Type RM Length L Ch R = 1 ,3692    ,439,439,439
BEGIN DESCRIPTION:
Larue Branch 5.0
END DESCRIPTION:
XS GIS Cut Line= 3
      2771275.97      6783560.97        2770476.        6782761.
      2769825.97        6782861.
#Sta/Elev= 30
  3868.6  410.38  3896.8  408.85  3939.3  404.46  4151.4   386.4  4236.3  380.43
  4349.4  374.06  4434.2  372.35  4519.1  371.98  4688.8  372.46  4801.9  371.59
  4929.2  373.22  4943.4  371.71  4954.7     369  4955.5   368.5  4960.3     369
  4971.6  370.51  4985.8  371.36  4996.4  373.25  5034.1  374.28  5097.3  373.37
  5165.6  374.74    5354  373.59  5384.4  375.73  5404.6   378.9  5445.1  380.86
  5491.9  385.93    5497  385.87  5560.2  391.04  5628.5  398.39  5657.6  402.23
#Mann= 3 ,-1 , 0
  3868.6     .05       0  4954.7     .04       0  4960.3     .05       0
#XS Ineff= 2 , 0
       0 4915.08   373.3 5165.77       0  374.81
Permanent Ineff=
       T       F
Bank Sta=4929.2,4996.4
XS Rating Curve= 0 ,0
Exp/Cntr=0.3,0.1

Type RM Length L Ch R = 1 ,3253    ,483,483,483
BEGIN DESCRIPTION:
Larue Branch 4.0
END DESCRIPTION:
XS GIS Cut Line= 3
      2771326.01      6781810.99        2770526.        6782361.
      2769775.99      6782811.01
#Sta/Elev= 30
  4029.2  396.79  4042.7  395.18  4051.6  393.06  4061.5  392.51    4102  388.68
  4209.9  376.46  4308.6  368.99  4386.3  365.22  4387.2  364.72  4391.9  365.22
  4783.5  366.42  4992.6  369.61    4997  368.39  5023.4  367.97    5035  369.11
  5050.6  369.06  5058.3  370.21  5108.9  371.09  5182.7  370.43  5384.9  373.07
  5480.1  373.04  5517.1  372.34  5606.5  379.64  5649.2  384.18  5664.8  384.74
  5723.1  390.37  5781.4  396.47  5824.1  402.42  5851.4  405.03  5874.7  404.92
#Mann= 4 ,-1 , 0
  4029.2     .12       0  4061.5     .05       0  4386.3     .04       0
  4391.9     .05       0
#XS Ineff= 2 , 0
       0 4885.83  368.47               0
Permanent Ineff=
       T       F
Bank Sta=4992.6,5058.3
XS Rating Curve= 0 ,0
Exp/Cntr=0.3,0.1

Type RM Length L Ch R = 1 ,2770    ,0,0,0
BEGIN DESCRIPTION:
Larue Branch 3.0
END DESCRIPTION:
XS GIS Cut Line= 3
      2771326.04      6781760.99        2770526.        6781911.
       2769073.6      6783145.89
#Sta/Elev= 30
  4186.4  397.21    4212  395.14  4369.6  380.87  4440.8   373.2  4538.3  366.07
  4640.6   363.4  4641.5   362.9  4646.2   363.4  4990.2  367.19  4997.8  364.53
  5007.5  364.03  5021.8  365.95  5056.9  367.48  5852.1  372.24  5958.6  380.16
  6057.5  382.65  6106.9  386.64  6135.4  387.25  6149.7  385.65  6156.3  386.56
    6164  385.37  6199.1  385.65  6227.7  383.22  6319.9  379.37  6440.8  379.37
  6553.9  382.54  6646.1  386.64  6674.7  389.69  6709.8  390.81  6906.8  403.27
#Mann= 4 ,-1 , 0
  4186.4     .12       0    4212     .05       0  4640.6     .04       0
  4646.2     .05       0
#XS Ineff= 2 , 0
       0 4979.65  366.72               0
Permanent Ineff=
       T       F
Bank Sta=4997.8,5021.8
XS Rating Curve= 0 ,0
Exp/Cntr=0.3,0.1

--- Larue Branch.g03 (geometry) ---

Geom Title=Existing Conditions - updated
Program Version=4.10

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
River Reach=Larue Branch    ,Reach-1

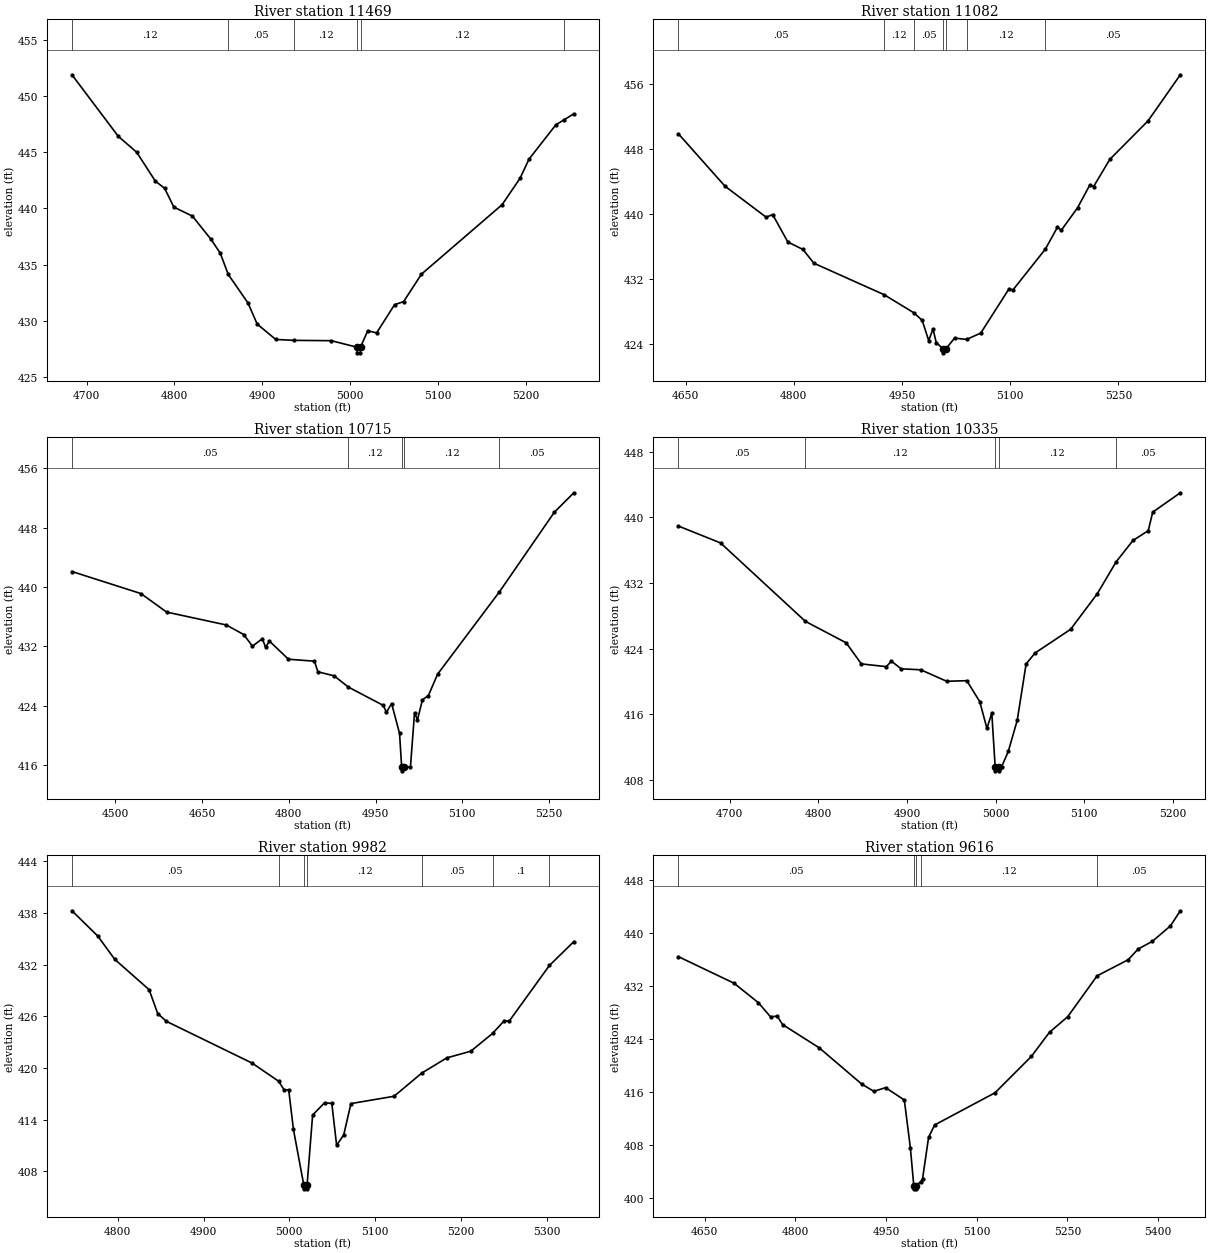
Type RM Length L Ch R = 1 ,11469   ,387,387,387
BEGIN DESCRIPTION:
Larue Branch 23.0
END DESCRIPTION:
XS GIS Cut Line= 3
      2769476.02      6789811.01        2769176.        6789711.
        2768926.        6789661.
#Sta/Elev= 30
  4683.4  451.88  4736.1  446.41  4757.2  444.98  4778.3  442.42  4788.8  441.79
  4799.4  440.11  4820.5  439.31  4841.5  437.26  4852.1  436.03  4861.3  434.12
  4883.7  431.59  4894.2  429.71  4915.3  428.34  4936.5  428.26  4978.6  428.23
  5007.8  427.65  5008.1  427.15  5011.6  427.15  5011.8  427.65    5020  429.11
  5030.2  428.93  5050.6  431.44  5060.8   431.7  5081.2  434.15    5173  440.33
  5193.4  442.68  5203.6  444.38  5234.2  447.44  5243.8  447.89  5254.6  448.41
#Mann= 6 ,-1 , 0
  4683.4     .12       0  4861.3     .05       0  4936.5     .12       0
  5007.8     .07       0  5011.8     .12       0  5243.8     .05       0
Bank Sta=5007.8,5011.8
XS Rating Curve= 0 ,0
Exp/Cntr=0.3,0.1

Type RM Length L Ch R = 1 ,11082   ,367,367,367
BEGIN DESCRIPTION:
Larue Branch 22.0
END DESCRIPTION:
XS GIS Cut Line= 3
      2769575.97      6789560.98        2769276.        6789361.
      2768976.02      6789211.01
#Sta/Elev= 30
    4640  449.88  4704.6  443.44  4761.6  439.63  4770.7  439.95  4791.7  436.58
  4812.7  435.66  4827.8  433.97  4925.2   430.1  4966.7  427.86    4978  426.94
    4987  424.46    4993  425.88  4997.5  424.21  5006.9  423.45  5007.2  422.95
  5010.9  423.45  5022.9  424.76  5039.6   424.6  5059.2  425.38  5098.3  430.81
  5103.9  430.69  5148.9  435.72  5165.4  438.38    5171  438.04  5193.4  440.78
  5210.1  443.54  5215.7   443.4  5238.1  446.73  5291.2  451.48  5335.9  457.14
#Mann= 7 ,-1 , 0
    4640     .05       0  4925.2     .12       0  4966.7     .05       0
  5006.9     .04       0  5010.9     .05       0  5039.6     .12       0
  5148.9     .05       0
Bank Sta=5006.9,5010.9
XS Rating Curve= 0 ,0
Exp/Cntr=0.3,0.1

Type RM Length L Ch R = 1 ,10715   ,380,380,380
BEGIN DESCRIPTION:
Larue Branch 21.0
END DESCRIPTION:
XS GIS Cut Line= 3
      2769843.25      6789261.01        2769326.        6789011.
      2769043.42      6788934.72
#Sta/Elev= 30
  4425.5  442.09  4544.6  439.12  4589.1  436.62  4692.2  434.88  4722.3  433.59
  4737.4  432.02  4754.4  433.03    4760  431.89  4766.8   432.7  4799.6  430.26
  4844.5     430  4850.4  428.57  4878.5  428.02  4903.2   426.5  4963.3  424.04
  4968.9  423.11  4977.8  424.29  4991.5  420.27  4995.2  415.71  4995.5  415.21
  4999.2  415.71  5010.4  415.75  5017.4  423.05  5022.5   422.1  5031.1  424.79
  5041.4  425.37  5057.3  428.25  5164.1  439.35    5259  450.09  5292.7  452.71
#Mann= 5 ,-1 , 0
  4425.5     .05       0  4903.2     .12       0  4995.2     .07       0
  4999.2     .12       0  5164.1     .05       0
Bank Sta=4995.2,4999.2
XS Rating Curve= 0 ,0
Exp/Cntr=0.3,0.1

Type RM Length L Ch R = 1 ,10335   ,353,353,353
BEGIN DESCRIPTION:
Larue Branch 20.0
END DESCRIPTION:
XS GIS Cut Line= 3
      2769752.61      6788817.12        2769426.        6788661.
       2769222.8        6788643.
#Sta/Elev= 30
  4642.3  438.95  4689.8  436.89  4785.5  427.32  4831.5   424.7  4848.6  422.13
  4876.8  421.79  4882.4  422.47  4893.5  421.53  4915.6  421.41  4944.8  420.01
  4967.5  420.08  4982.1  417.53  4990.2  414.26  4995.7  416.12  4999.5  409.58
  4999.8  409.08  5003.3  409.08  5003.5  409.58  5006.8  409.58  5014.3  411.45
  5024.4  415.25  5034.4  422.13  5044.5  423.46  5084.6  426.35  5114.7   430.7
  5135.9  434.58  5154.9  437.19  5172.1  438.38  5177.2  440.65  5208.3  443.01
#Mann= 5 ,-1 , 0
  4642.3     .05       0  4785.5     .12       0  4999.5     .07       0
  5003.5     .12       0  5135.9     .05       0
Bank Sta=4999.5,5003.5
XS Rating Curve= 0 ,0
Exp/Cntr=0.3,0.1

Type RM Length L Ch R = 1 ,9982    ,366,366,366
BEGIN DESCRIPTION:
Larue Branch 19.0
END DESCRIPTION:
XS GIS Cut Line= 3
      2769825.96        6788361.        2769576.        6788361.
      2769275.97      6788511.01
#Sta/Elev= 30
  4746.5  438.26  4776.5  435.34  4796.5  432.61  4836.5   429.1  4846.5  426.33
  4856.5  425.43  4956.5  420.58  4987.5  418.47    4994  417.47  4999.3  417.47
  5004.8  412.89  5016.8  406.47  5017.1  405.97  5020.6  405.97  5020.8  406.47
  5027.2  414.54  5041.2  415.97  5049.6  415.89  5055.2  411.03  5063.5  412.24
  5071.9  415.87  5122.2  416.72  5154.5  419.41  5183.7  421.18  5211.7  421.95
  5237.1  424.02  5250.8   425.5  5256.4  425.43  5303.4  431.91  5331.9  434.68
#Mann= 7 ,-1 , 0
  4746.5     .05       0  4987.5     .12       0  5016.8     .07       0
  5020.8     .12       0  5154.5     .05       0  5237.1      .1       0
  5303.4     .05       0
Bank Sta=5016.8,5020.8
XS Rating Curve= 0 ,0
Exp/Cntr=0.3,0.1

Type RM Length L Ch R = 1 ,9616    ,366,366,366
BEGIN DESCRIPTION:
Larue Branch 18.0
END DESCRIPTION:
XS GIS Cut Line= 3
      2769867.43      6788102.99        2769476.        6788061.
      2769039.71      6788066.92
#Sta/Elev= 30
  4606.7  436.41  4698.6   432.4  4738.9  429.46    4759  427.32    4770  427.42
  4779.1  426.14  4839.5  422.64  4909.9  417.15    4930  416.06  4949.3  416.62
  4980.3  414.75  4990.3  407.51  4995.9  401.83  4996.1  401.33  4999.6  401.33
  4999.9  401.83  5007.1  402.39  5010.4  402.83  5020.4   409.1  5030.4  410.98
  5130.4  415.85  5190.4  421.34  5220.4  424.99  5250.4  427.33  5299.1  433.51
  5350.4  435.94    5367  437.56  5390.4  438.72  5420.4  441.06  5436.7  443.34
#Mann= 5 ,-1 , 0
  4606.7     .05       0  4995.9     .04       0  4999.9     .05       0
  5007.1     .12       0  5299.1     .05       0
Bank Sta=4995.9,4999.9
XS Rating Curve= 0 ,0
Exp/Cntr=0.3,0.1

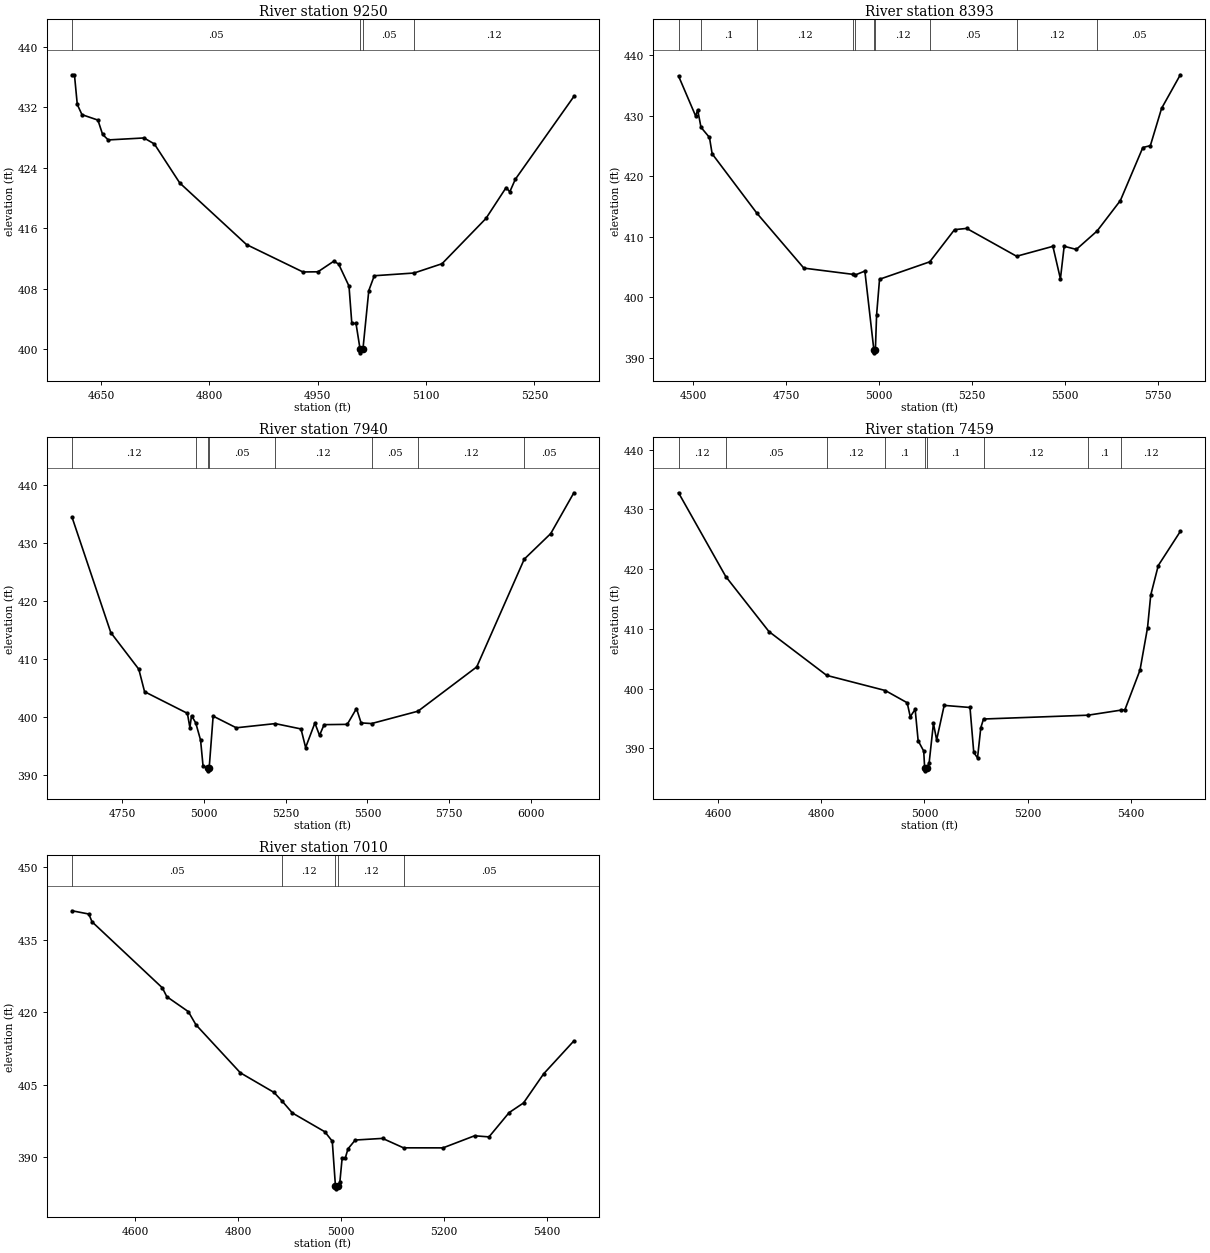
Type RM Length L Ch R = 1 ,9250    ,857,857,857
BEGIN DESCRIPTION:
Larue Branch 17.0
END DESCRIPTION:
XS GIS Cut Line= 3
      2769826.01      6787961.01        2769526.        6787711.
      2769225.97      6787660.99
#Sta/Elev= 30
    4610  436.29  4613.3  436.29  4617.2  432.37  4623.7  431.02  4645.8   430.3
  4652.3   428.4  4660.1  427.68  4709.6  427.94  4723.9  427.15  4759.1  421.99
  4851.5  413.85  4929.6  410.23  4950.4  410.25  4972.5  411.66  4979.1  411.26
  4993.4  408.36  4997.3  403.42  5003.1  403.42  5008.7  400.04  5008.9  399.54
  5012.7  400.04  5020.8  407.77  5028.4  409.73  5083.5  410.09  5122.2  411.32
    5183   417.3  5210.9  421.38    5216  420.82  5223.6  422.47  5304.7  433.42
#Mann= 4 ,-1 , 0
    4610     .05       0  5008.7     .04       0  5012.7     .05       0
  5083.5     .12       0
Bank Sta=5008.7,5012.7
XS Rating Curve= 0 ,0
Exp/Cntr=0.3,0.1

Type RM Length L Ch R = 1 ,8393    ,453,453,453
BEGIN DESCRIPTION:
Larue Branch 15.0
END DESCRIPTION:
XS GIS Cut Line= 3
      2770141.81       6787181.5        2769626.        6787011.
      2768825.98        6786911.
#Sta/Elev= 30
  4460.7  436.53  4506.9  429.89  4512.1  430.95  4521.1  428.05  4543.9  426.37
  4551.1  423.67  4671.6  413.84  4797.7  404.78  4928.6  403.76  4934.8  403.62
  4961.8  404.29    4986  391.28  4986.3  390.78  4990.1  391.28  4993.4  397.09
  5001.3  402.94  5136.3  405.82    5203  411.14  5235.7  411.34  5369.9  406.74
  5467.5  408.38  5487.7  403.01  5497.8  408.39  5530.5  407.87  5586.3  410.91
  5648.9  415.94  5709.4  424.71  5729.6  425.02  5759.8  431.18  5810.2  436.73
#Mann= 10 ,-1 , 0
  4460.7     .12       0  4521.1      .1       0  4671.6     .12       0
  4928.6      .1       0  4934.8     .12       0    4986     .07       0
  4990.1     .12       0  5136.3     .05       0  5369.9     .12       0
  5586.3     .05       0
Bank Sta=4986,4990.1
XS Rating Curve= 0 ,0
Exp/Cntr=0.3,0.1

Type RM Length L Ch R = 1 ,7940    ,481,481,481
BEGIN DESCRIPTION:
Larue Branch 14.0
END DESCRIPTION:
XS GIS Cut Line= 3
      2770175.99        6786561.        2769776.        6786611.
      2768975.98      6785810.98
#Sta/Elev= 30
  4596.9  434.47  4715.3  414.61    4801  408.29  4818.6  404.42  4949.6  400.69
  4957.2  398.22  4962.2  400.29  4975.1  399.04  4989.9  396.07  4997.5  391.58
  5012.1  391.28  5012.4  390.78  5016.2  391.28  5028.3  400.21    5099   398.2
  5218.2  398.92    5297     398  5311.1   394.8  5339.4  399.02  5353.6   396.9
  5367.7  398.74  5438.4  398.79  5466.7  401.52  5480.8  399.04  5512.8  398.93
  5654.8  401.06  5834.4  408.69  5979.8  427.27  6060.7  431.67  6131.4   438.7
#Mann= 8 ,-1 , 0
  4596.9     .12       0  4975.1     .05       0  5012.1     .05       0
  5016.2     .05       0  5218.2     .12       0  5512.8     .05       0
  5654.8     .12       0  5979.8     .05       0
Bank Sta=5012.1,5016.2
XS Rating Curve= 0 ,0
Exp/Cntr=0.3,0.1

Type RM Length L Ch R = 1 ,7459    ,449,449,449
BEGIN DESCRIPTION:
Larue Branch 13.0
END DESCRIPTION:
XS GIS Cut Line= 3
      2770176.01      6786411.01        2769776.        6786161.
      2769376.01      6785861.01
#Sta/Elev= 30
  4523.8  432.76  4615.3  418.74  4698.9  409.54  4810.7  402.21  4924.1  399.68
  4966.6  397.63  4972.5  395.29    4982  396.53  4987.8  391.28  4998.6  389.54
  5000.4  386.74    5001  386.24  5005.2  386.74  5009.1  387.58  5017.4  394.18
  5023.6  391.42  5038.2  397.19  5088.2  396.84  5095.5  389.32  5102.8   388.4
  5109.1  393.45  5114.4  394.91  5316.8  395.55    5380  396.39  5388.2  396.46
  5417.4  403.09    5432  410.19  5438.2  415.64  5452.8  420.59  5495.5   426.3
#Mann= 9 ,-1 , 0
  4523.8     .12       0  4615.3     .05       0  4810.7     .12       0
  4924.1      .1       0  5000.4     .07       0  5005.2      .1       0
  5114.4     .12       0  5316.8      .1       0    5380     .12       0
Bank Sta=5000.4,5005.2
XS Rating Curve= 0 ,0
Exp/Cntr=0.3,0.1

Type RM Length L Ch R = 1 ,7010    ,443,443,443
BEGIN DESCRIPTION:
Larue Branch 12.0
END DESCRIPTION:
XS GIS Cut Line= 3
      2770357.73       6786064.6        2769926.        6785761.
        2769526.        6785561.
#Sta/Elev= 30
  4477.8  441.01  4510.3  440.34  4516.6  438.73  4653.2  425.08  4661.9  423.25
  4703.7  420.16  4718.5  417.44  4804.8  407.51  4870.1  403.46  4886.2  401.63
  4905.8  399.21  4968.9  395.32  4983.4  393.37  4989.6  384.02  4990.2  383.52
  4994.5  384.02  4998.2  385.01  5002.5   389.8  5008.4   389.8    5014   391.8
    5028  393.61  5081.1  393.95  5121.8     392  5198.5  391.99  5259.9  394.49
  5287.9  394.26    5327  399.28    5355  401.28  5394.1   407.3  5452.8   414.1
#Mann= 5 ,-1 , 0
  4477.8     .05       0  4886.2     .12       0  4989.6     .07       0
  4994.5     .12       0  5121.8     .05       0
Bank Sta=4989.6,4994.5
XS Rating Curve= 0 ,0
Exp/Cntr=0.3,0.1