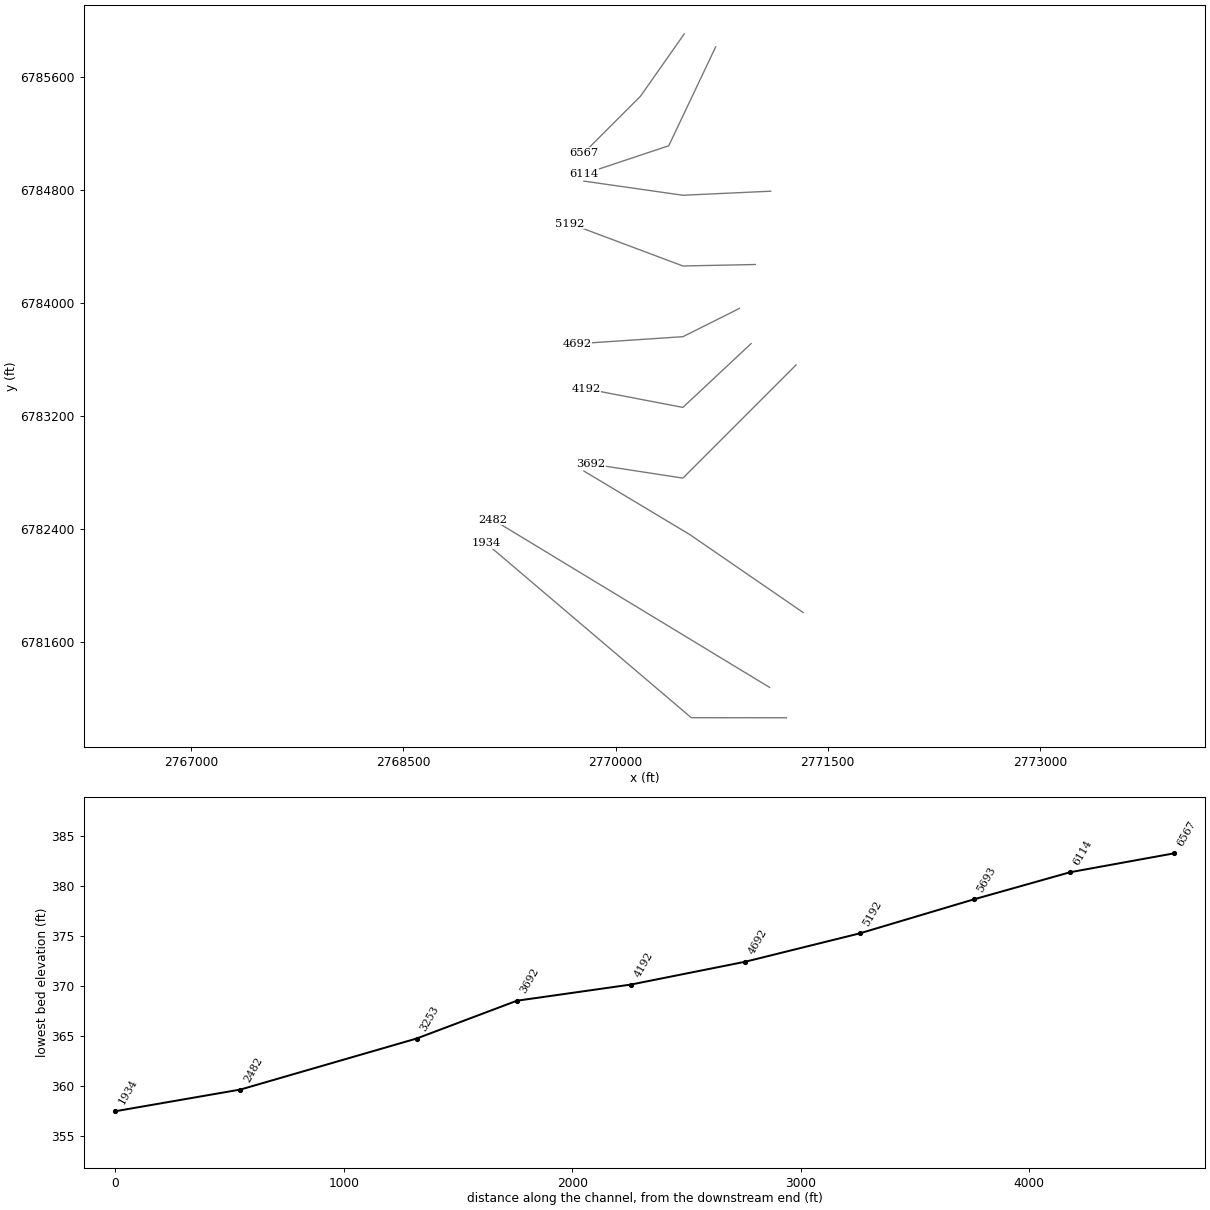
HEC-RAS study Larue Branch.prj: Larue Branch Base Level Engineering

--- Larue Branch.g03 (geometry) --- (continued)

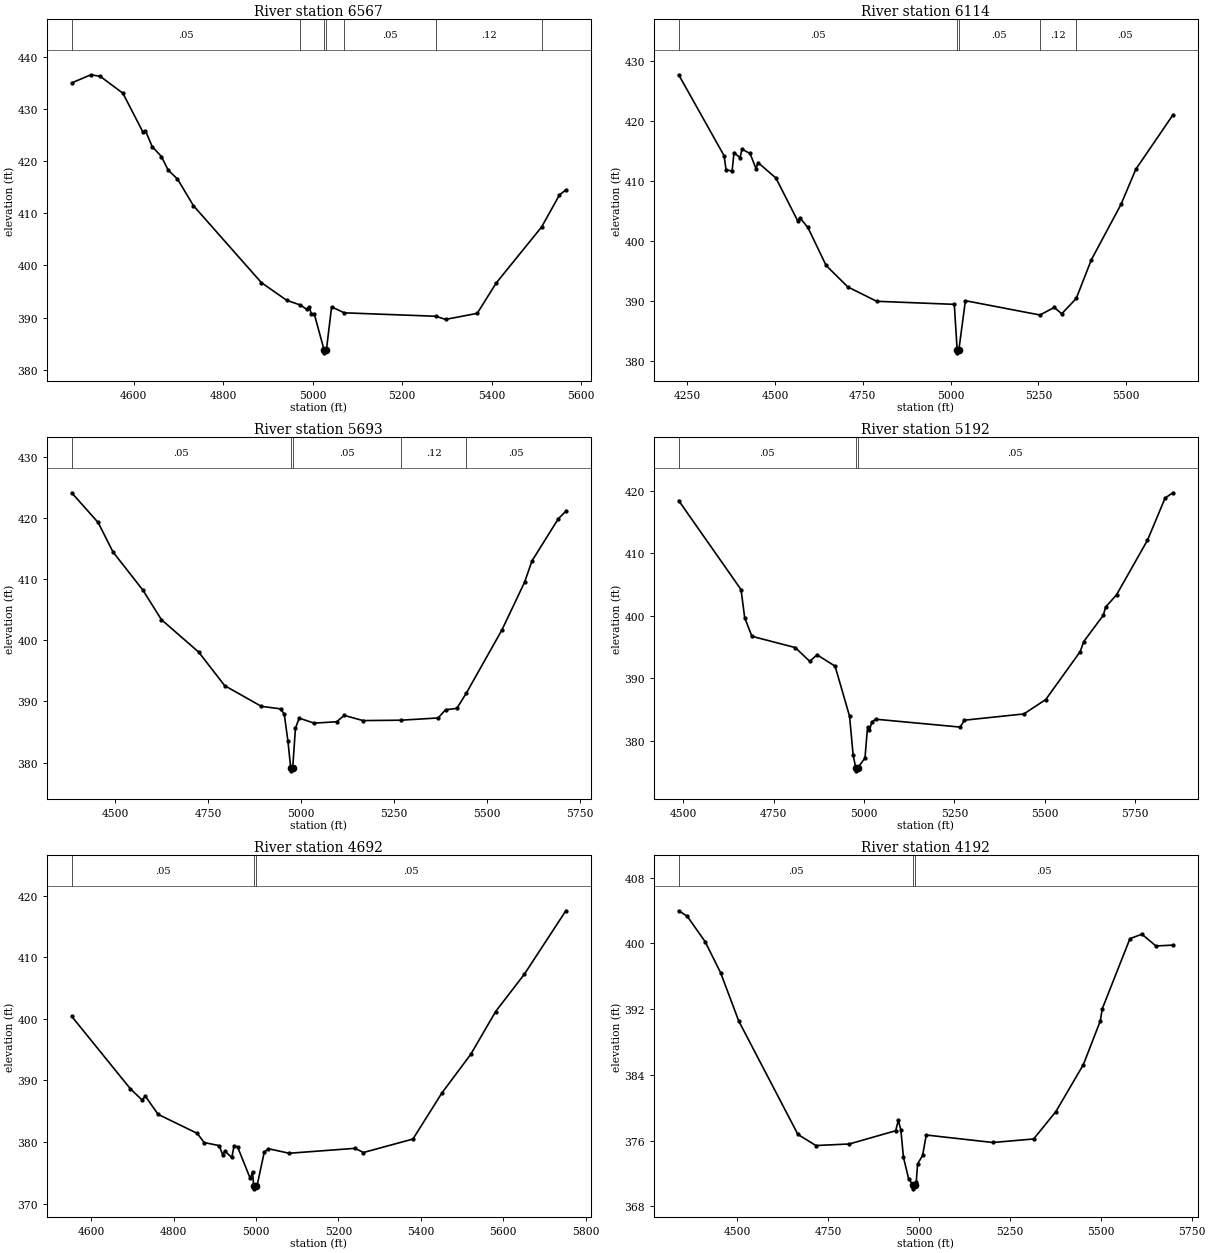
Type RM Length L Ch R = 1 ,6567    ,453,453,453
BEGIN DESCRIPTION:
Larue Branch 11.0
END DESCRIPTION:
XS GIS Cut Line= 3
      2770485.38      6785901.51        2770176.        6785461.
      2769775.99      6785060.99
#Sta/Elev= 30
  4461.5  434.97  4504.4  436.53  4525.3  436.23  4575.9  432.99  4620.3  425.61
  4626.4   425.8  4641.2  422.78  4662.1  420.85  4676.9  418.28  4697.9  416.54
  4733.6  411.43  4885.2   396.7  4941.9   393.3  4972.6  392.39  4986.3  391.58
  4992.4  392.04  4996.7  390.73  5003.3  390.73  5025.6  383.73  5026.2  383.23
  5030.5  383.73  5042.2  392.04  5070.5   390.9  5275.3  390.24  5296.8  389.64
  5367.5   390.8  5409.9  396.61  5511.5  407.37  5551.3   413.5  5565.5  414.46
#Mann= 7 ,-1 , 0
  4461.5     .05       0  4972.6     .12       0  5025.6     .07       0
  5030.5     .12       0  5070.5     .05       0  5275.3     .12       0
  5511.5     .05       0
Bank Sta=5025.6,5030.5
XS Rating Curve= 0 ,0
Exp/Cntr=0.3,0.1

Type RM Length L Ch R = 1 ,6114    ,421,421,421
BEGIN DESCRIPTION:
Larue Branch 10.0
END DESCRIPTION:
XS GIS Cut Line= 3
      2770707.63      6785809.98        2770376.        6785111.
      2769776.02      6784911.01
#Sta/Elev= 30
  4226.3  427.63  4355.4  414.16    4361  411.83  4378.2  411.59  4383.7  414.69
  4400.9  413.82  4406.4  415.25  4429.2  414.53  4446.4  412.01  4451.9  413.02
  4502.9  410.45  4565.6  403.24  4571.1  403.83  4593.8  402.22  4645.8  395.89
  4707.5  392.32  4789.7  389.93  5010.5  389.42  5018.6  381.85  5019.2  381.35
  5023.5  381.85  5042.1  390.03    5254  387.65  5295.1   388.9  5316.2  387.85
  5357.5   390.4  5400.5  396.84  5484.8  406.05    5527   411.9  5632.4  420.93
#Mann= 5 ,-1 , 0
  4226.3     .05       0  5018.6     .04       0  5023.5     .05       0
    5254     .12       0  5357.5     .05       0
Bank Sta=5018.6,5023.5
XS Rating Curve= 0 ,0
Exp/Cntr=0.3,0.1

Type RM Length L Ch R = 1 ,5693    ,501,501,501
BEGIN DESCRIPTION:
Larue Branch 9.0
END DESCRIPTION:
XS GIS Cut Line= 3
      2771097.02       6784789.7        2770476.        6784761.
      2769775.99        6784861.
#Sta/Elev= 30
    4383  424.12  4454.1  419.26  4494.1  414.44  4574.2  408.22  4624.3  403.37
  4724.4  398.07  4794.5  392.57    4893  389.19  4944.6  388.78  4954.6  387.92
  4964.6  383.45  4971.9  379.14  4972.7  378.64  4977.4  379.14  4984.7  385.61
  4994.7  387.26    5035  386.44  5095.6  386.67  5115.8  387.71  5166.3  386.86
  5267.9  386.92  5368.3  387.29  5388.5  388.63  5418.8  388.86  5444.2  391.35
  5540.1   401.7  5600.7  409.47  5620.9  412.99  5691.6  419.87  5711.8  421.09
#Mann= 5 ,-1 , 0
    4383     .05       0  4971.9     .03       0  4977.4     .05       0
  5267.9     .12       0  5444.2     .05       0
Bank Sta=4971.9,4977.4
XS Rating Curve= 0 ,0
Exp/Cntr=0.3,0.1

Type RM Length L Ch R = 1 ,5192    ,500,500,500
BEGIN DESCRIPTION:
Larue Branch 8.0
END DESCRIPTION:
XS GIS Cut Line= 3
       2770988.5      6784271.26        2770476.        6784261.
        2769676.        6784561.
#Sta/Elev= 30
  4487.4   418.4  4659.9  404.18  4669.9  399.71  4689.9  396.72    4810  394.92
    4850  392.71    4870  393.77    4920  391.95    4960  383.97    4970  377.72
  4977.2  375.73    4978  375.23  4982.8  375.73  5002.7  377.27  5009.8  382.18
  5015.1  381.69  5021.4  382.99    5032  383.48  5266.1  382.22  5277.7  383.32
  5442.3  384.32  5502.8  386.62  5598.1  394.28  5607.9  395.88  5662.2   400.1
  5668.4  401.39  5698.6  403.35  5784.1  412.06    5833  418.81  5854.4  419.65
#Mann= 3 ,-1 , 0
  4487.4     .05       0  4977.2     .04       0  4982.8     .05       0
Bank Sta=4977.2,4982.8
XS Rating Curve= 0 ,0
Exp/Cntr=0.3,0.1

Type RM Length L Ch R = 1 ,4692    ,500,500,500
BEGIN DESCRIPTION:
Larue Branch 7.0
END DESCRIPTION:
XS GIS Cut Line= 3
      2770875.99      6783960.99        2770476.        6783761.
      2769725.96        6783711.
#Sta/Elev= 30
  4552.8  400.42  4695.3  388.64  4723.3  386.85  4731.7  387.44  4762.4   384.5
  4857.4  381.41  4874.2  379.92  4910.6  379.42  4918.9  377.97  4924.5  378.51
  4941.3  377.49  4946.9  379.41  4955.3  379.21    4986  374.09  4991.6  375.13
  4994.4   372.9  4995.3   372.4    5000   372.9  5002.5   372.9    5020  378.36
  5030.1  378.92  5080.2  378.18  5240.5  378.98  5260.6   378.3  5380.8  380.49
    5451  387.97  5521.2  394.26  5581.3  401.19  5651.4  407.29  5751.7  417.56
#Mann= 3 ,-1 , 0
  4552.8     .05       0  4994.4     .04       0    5000     .05       0
Bank Sta=4994.4,5000
XS Rating Curve= 0 ,0
Exp/Cntr=0.3,0.1

Type RM Length L Ch R = 1 ,4192    ,500,500,500
BEGIN DESCRIPTION:
Larue Branch 6.0
END DESCRIPTION:
XS GIS Cut Line= 3
      2770958.15      6783711.99        2770476.        6783261.
       2769790.2      6783392.55
#Sta/Elev= 30
  4339.8  403.96  4363.2   403.3  4412.6  400.19  4455.1  396.41  4504.9  390.54
  4667.6  376.74  4716.9  375.39  4808.8  375.58  4936.3  377.19  4943.6  378.45
  4950.4  377.33  4957.7  373.95  4971.9  371.35  4983.3  370.62  4984.1  370.12
  4988.9  370.62  4992.9  370.99  4996.6  373.15  5010.2  374.18  5020.4  376.67
  5203.6  375.76  5315.6  376.19  5376.7  379.52  5452.2  385.23  5498.9  390.56
  5504.2  392.03  5580.4  400.57  5613.2  401.11  5651.7  399.68  5698.3  399.78
#Mann= 3 ,-1 , 0
  4339.8     .05       0  4983.3     .04       0  4988.9     .05       0
Bank Sta=4983.3,4988.9
XS Rating Curve= 0 ,0
Exp/Cntr=0.3,0.1

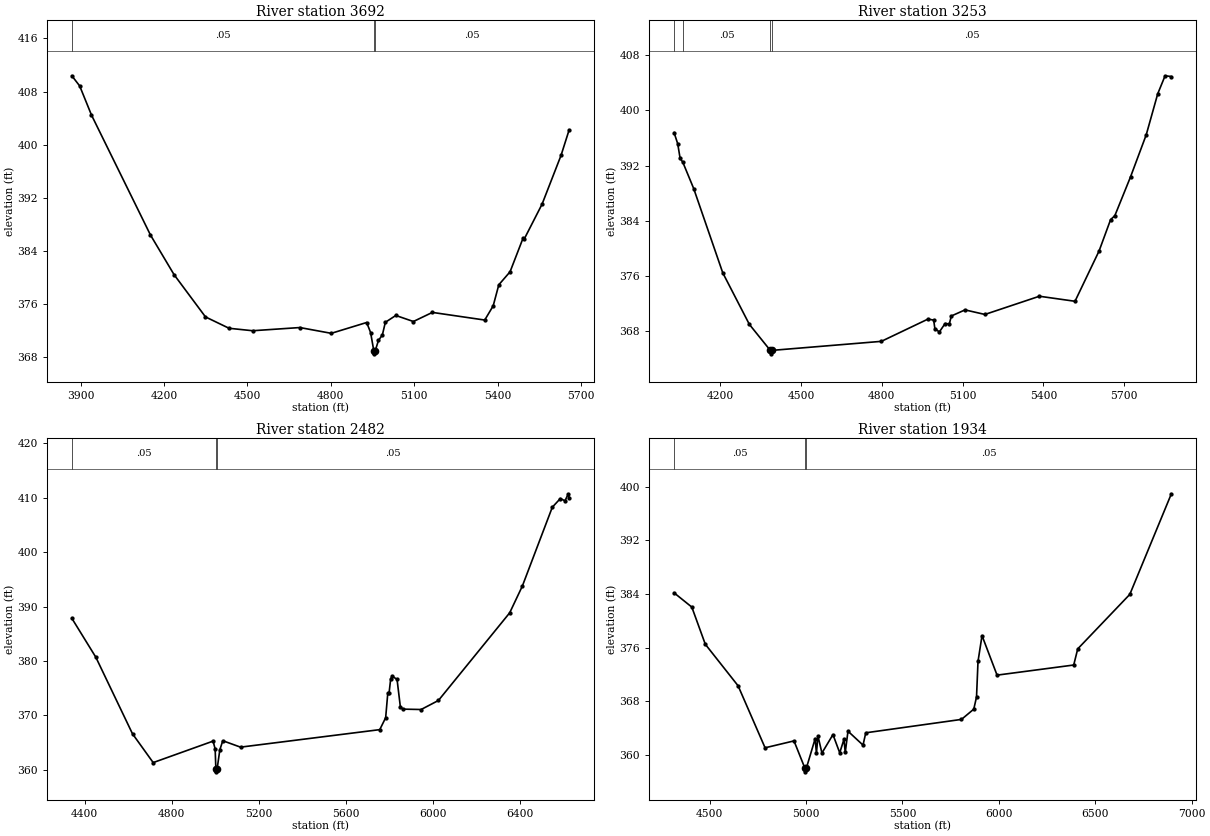
Type RM Length L Ch R = 1 ,3692    ,439,439,439
BEGIN DESCRIPTION:
Larue Branch 5.0
END DESCRIPTION:
XS GIS Cut Line= 3
      2771275.97      6783560.97        2770476.        6782761.
      2769825.97        6782861.
#Sta/Elev= 30
  3868.6  410.38  3896.8  408.85  3939.3  404.46  4151.4   386.4  4236.3  380.43
  4349.4  374.06  4434.2  372.35  4519.1  371.98  4688.8  372.46  4801.9  371.59
  4929.2  373.22  4943.4  371.71  4954.7     369  4955.5   368.5  4960.3     369
  4971.6  370.51  4985.8  371.36  4996.4  373.25  5034.1  374.28  5097.3  373.37
  5165.6  374.74    5354  373.59  5384.4  375.73  5404.6   378.9  5445.1  380.86
  5491.9  385.93    5497  385.87  5560.2  391.04  5628.5  398.39  5657.6  402.23
#Mann= 3 ,-1 , 0
  3868.6     .05       0  4954.7     .04       0  4960.3     .05       0
Bank Sta=4954.7,4960.3
XS Rating Curve= 0 ,0
Exp/Cntr=0.3,0.1

Type RM Length L Ch R = 1 ,3253    ,771,771,771
BEGIN DESCRIPTION:
Larue Branch 4.0
END DESCRIPTION:
XS GIS Cut Line= 3
      2771326.01      6781810.99        2770526.        6782361.
      2769775.99      6782811.01
#Sta/Elev= 30
  4029.2  396.79  4042.7  395.18  4051.6  393.06  4061.5  392.51    4102  388.68
  4209.9  376.46  4308.6  368.99  4386.3  365.22  4387.2  364.72  4391.9  365.22
  4798.4  366.53  4971.6  369.76  4992.6  369.61    4997  368.39  5013.6  367.89
    5035  369.11  5050.6  369.06  5058.3  370.21  5108.9  371.09  5182.7  370.43
  5384.9  373.07  5517.1  372.34  5606.5  379.64  5649.2  384.18  5664.8  384.74
  5723.1  390.37  5781.4  396.47  5824.1  402.42  5851.4  405.03  5874.7  404.92
#Mann= 4 ,-1 , 0
  4029.2     .12       0  4061.5     .05       0  4386.3     .04       0
  4391.9     .05       0
Bank Sta=4386.3,4391.9
XS Rating Curve= 0 ,0
Exp/Cntr=0.3,0.1

Type RM Length L Ch R = 1 ,2482    ,548,548,548
BEGIN DESCRIPTION:
Mapping XS 18993cec
END DESCRIPTION:
XS GIS Cut Line= 2
       2771089.2      6781281.29      2769134.88      6782466.07
#Sta/Elev= 30
  4341.4  387.85  4451.6   380.7  4620.2  366.61  4715.2  361.32  4990.6  365.27
    5000  363.81  5003.3  360.12  5004.1  359.62  5008.9  360.12  5021.6  363.68
  5035.1  365.34  5116.6  364.16  5756.5  367.38  5783.6  369.57  5793.3  374.05
  5799.1  374.06  5806.9  376.77  5814.6  377.19    5836  376.61  5851.5  371.46
  5865.4  371.15  5946.5  371.08    6026  372.74  6353.6  388.86  6411.8  393.78
  6549.5  408.28  6586.3  409.87  6607.7  409.46  6623.2  410.75  6626.8     410
#Mann= 3 ,-1 , 0
  4341.4     .05       0  5003.3     .04       0  5008.9     .05       0
Bank Sta=5003.3,5008.9
XS Rating Curve= 0 ,0
Exp/Cntr=0.3,0.1

Type RM Length L Ch R = 1 ,1934    ,0,0,0
BEGIN DESCRIPTION:
Larue Branch 3.0
END DESCRIPTION:
XS GIS Cut Line= 3
      2771208.02      6781066.65      2770535.23      6781067.15
      2769082.75      6782302.09
#Sta/Elev= 30
  4315.5  384.18  4407.5  382.05  4477.5   376.5  4647.5   370.3  4787.5  361.04
  4937.5  362.07  4994.6  357.95  4995.7  357.45  5001.1  357.95  5047.3  362.41
  5053.9   360.2  5061.6  362.82  5082.4  360.26  5139.6  363.01  5174.7  360.29
  5196.7  362.31  5203.3  360.34  5217.5  363.52  5295.5  361.44  5309.8  363.28
  5806.2  365.28  5869.9  366.81  5884.2  368.62  5891.9  373.93  5912.7  377.79
  5990.7  371.89  6388.3   373.4  6409.1  375.81  6679.3  383.95  6894.8  398.97
#Mann= 3 ,-1 , 0
  4315.5     .05       0  4994.6     .03       0  5001.1     .05       0
Bank Sta=4994.6,5001.1
XS Rating Curve= 0 ,0
Exp/Cntr=0.3,0.1