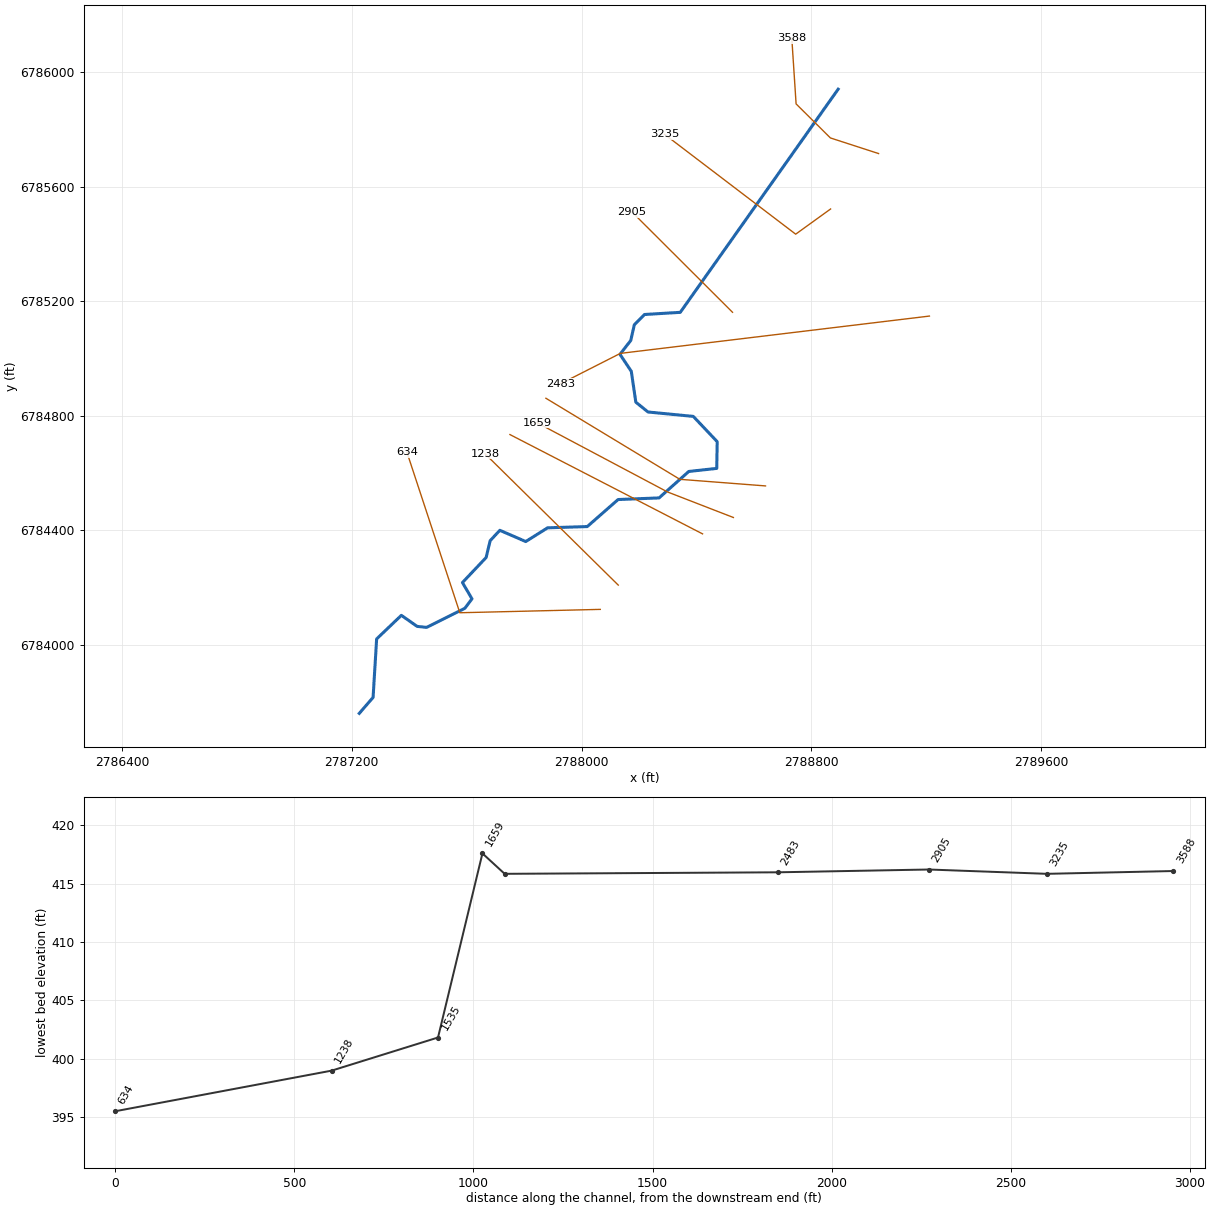
--- Lee Lake.prj (project) ---

Proj Title=Lee Lake Base Level Engineering
Current Plan=p01
Default Exp/Contr=0.3,0.1
English Units
Geom File=g01
Flow File=f01
Plan File=p01
BEGIN DESCRIPTION:
Lee Lake
END DESCRIPTION:

--- Lee Lake.p01 (plan) ---

Plan Title=Multiple Run
Short Identifier=Multiple
Geom File=g01
Flow File=f01
Subcritical Flow
K Sum by GR= 0
Std Step Tol= 0.01
Critical Tol= 0.01
Num of Std Step Trials= 20
Max Error Tol= 0.3
Flow Tol Ratio= 0.001
Split Flow NTrial= 30
Split Flow Tol= 0.02
Split Flow Ratio= 0.02
Log Output Level= 0
Friction Slope Method= 1
Unsteady Friction Slope Method= 2
Unsteady Bridges Friction Slope Method= 1
Parabolic Critical Depth
Global Vel Dist=  1 , 1 , 1
Global Log Level= 0
CheckData=True
Encroach Param= -1, 0, 0, 0
BEGIN DESCRIPTION:
Multiple Run
END DESCRIPTION:

--- Lee Lake.f01 (steady flow) ---

Flow Title=Multiple
Number of Profiles=7
Profile Names=10-year,25-year,50-year,1pct_min,100-year,1pct_plu,500-year
River Rch & RM= Lee Lake,Reach-1,3588
     479     642     774     465     928    1852    1336
Boundary for River Rch & Prof#=Lee Lake,Reach-1,1
Up Type=0
Dn Type=3
Dn Slope=0.005
Boundary for River Rch & Prof#=Lee Lake,Reach-1,2
Up Type=0
Dn Type=3
Dn Slope=0.005
Boundary for River Rch & Prof#=Lee Lake,Reach-1,3
Up Type=0
Dn Type=3
Dn Slope=0.005
Boundary for River Rch & Prof#=Lee Lake,Reach-1,4
Up Type=0
Dn Type=3
Dn Slope=0.005
Boundary for River Rch & Prof#=Lee Lake,Reach-1,5
Up Type=0
Dn Type=3
Dn Slope=0.005
Boundary for River Rch & Prof#=Lee Lake,Reach-1,6
Up Type=0
Dn Type=3
Dn Slope=0.005
Boundary for River Rch & Prof#=Lee Lake,Reach-1,7
Up Type=0
Dn Type=3
Dn Slope=0.005

--- Lee Lake.g01 (geometry) ---

Geom Title=Existing Conditions

River Reach=Lee Lake,Reach-1
Reach XY= 30
      2788894.01      6785939.99      2788344.00      6785160.85
      2788219.52      6785153.31      2788183.98      6785117.38
      2788171.53      6785062.68      2788134.04      6785014.32
      2788173.44      6784955.10      2788189.23      6784847.27
      2788231.65      6784812.98      2788389.35      6784797.64
      2788472.58      6784709.44      2788471.05      6784616.11
      2788373.65      6784605.43      2788270.14      6784513.08
      2788127.47      6784507.44      2788020.14      6784413.08
      2787881.93      6784408.70      2787805.79      6784360.79
      2787715.63      6784400.02      2787681.85      6784363.85
      2787667.80      6784304.99      2787585.32      6784217.65
      2787618.53      6784160.79      2787593.53      6784127.64
      2787460.59      6784061.14      2787427.63      6784064.62
      2787372.58      6784103.19      2787286.48      6784020.85
      2787274.11      6783816.78      2787226.00      6783761.00

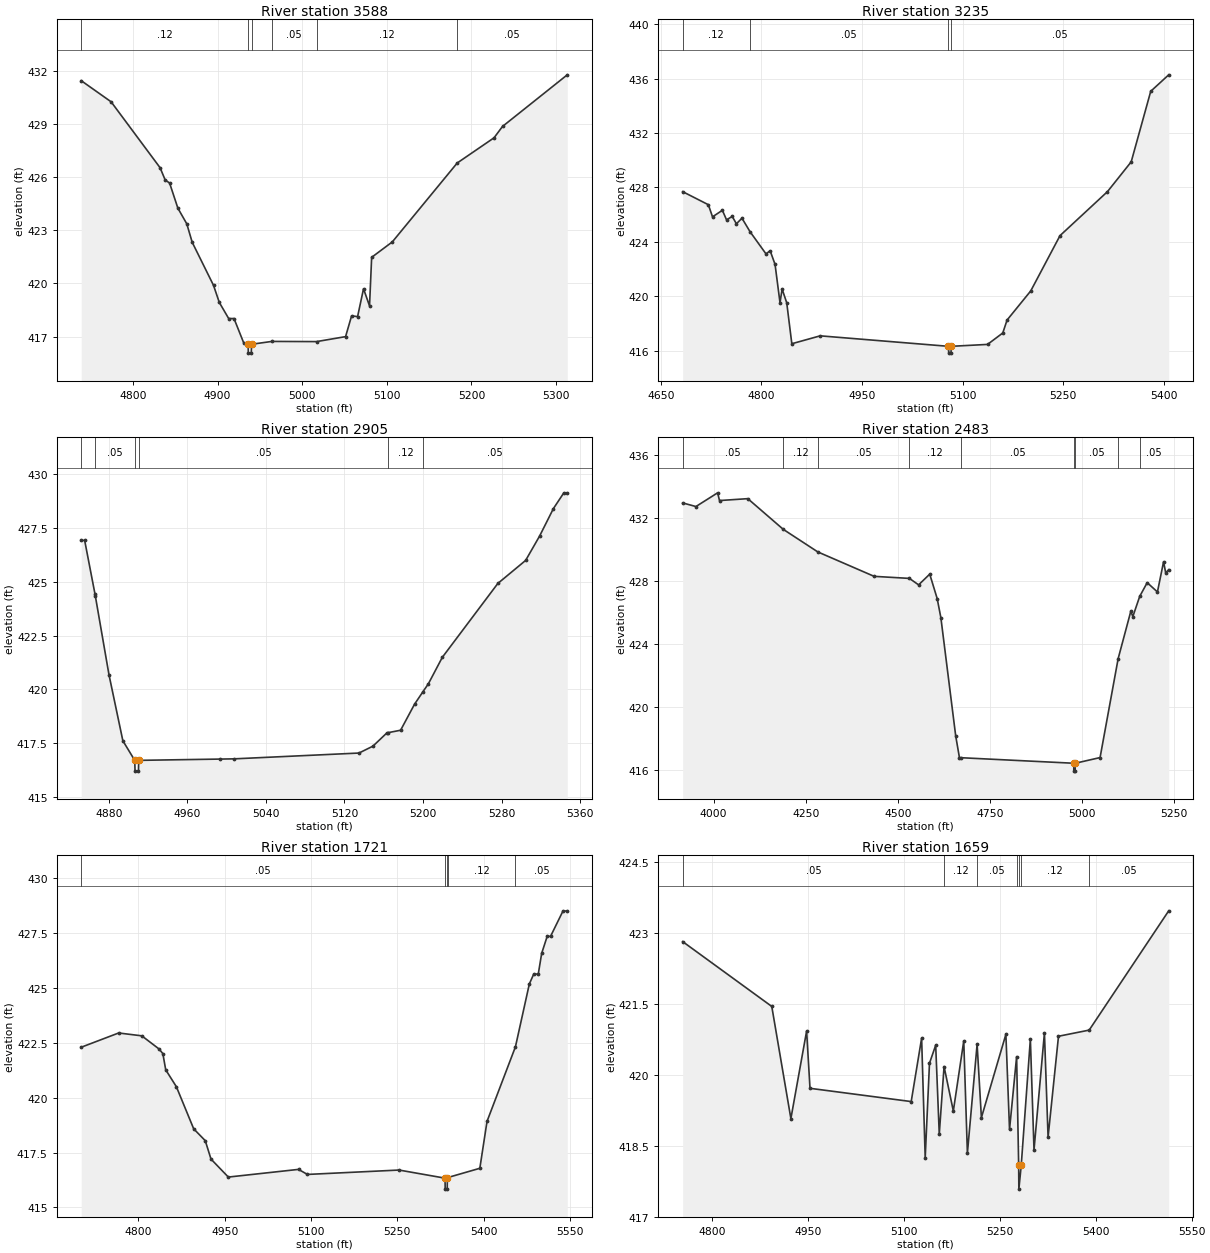
Type RM Length L Ch R = 1,3588,353,353,353
BEGIN DESCRIPTION:
2490
END DESCRIPTION:
XS GIS Cut Line= 4
      2789034.62      6785715.13      2788866.89      6785769.62
      2788747.43      6785888.42      2788732.46      6786117.29
#Sta/Elev= 30
  4739.0  431.43  4774.3  430.24  4832.2  426.52  4838.2  425.83  4843.4  425.66
  4853.2  424.24  4863.7  423.36  4870.1  422.32  4895.3  419.89  4902.1  418.93
  4913.2  418.02  4919.5  418.02  4931.1  416.63  4936.2  416.57  4936.4  416.07
  4939.9  416.07  4940.2  416.57  4964.3  416.73  5017.0  416.72  5051.3  417.00
  5058.4  418.17  5065.5  418.13  5072.5  419.70  5079.6  418.73  5082.1  421.47
  5106.5  422.34  5183.2  426.79  5226.7  428.21  5236.7  428.85  5313.2  431.76
#Mann=6,-1,0
  4739.0    0.12       0  4936.2    0.03       0  4940.2    0.12       0
  4964.3    0.05       0  5017.0    0.12       0  5183.2    0.05       0
Bank Sta=4936.2,4940.2
Exp/Cntr=0.3,0.1

Type RM Length L Ch R = 1,3235,330,330,330
BEGIN DESCRIPTION:
2489
END DESCRIPTION:
XS GIS Cut Line= 3
      2788867.63      6785521.65      2788745.97      6785433.72
      2788289.44      6785782.12
#Sta/Elev= 30
  4682.6  427.69  4720.9  426.73  4727.1  425.84  4741.8  426.32  4748.0  425.62
  4756.5  425.87  4762.7  425.33  4771.0  425.74  4783.0  424.75  4806.8  423.12
  4813.0  423.35  4820.3  422.35  4827.7  419.53  4830.8  420.54  4837.7  419.53
  4845.3  416.52  4887.6  417.10  5078.8  416.33  5079.1  415.83  5082.6  415.83
  5082.8  416.33  5137.0  416.47  5159.7  417.31  5166.1  418.26  5201.4  420.40
  5245.0  424.46  5315.7  427.69  5351.1  429.88  5380.2  435.06  5407.0  436.27
#Mann=4,-1,0
  4682.6    0.12       0  4783.0    0.05       0  5078.8    0.03       0
  5082.8    0.05       0
Bank Sta=5078.8,5082.8
Exp/Cntr=0.3,0.1

Type RM Length L Ch R = 1,2905,422,422,422
BEGIN DESCRIPTION:
1624
END DESCRIPTION:
XS GIS Cut Line= 3
      2788525.98      6785161.02      2788476.00      6785211.00
      2788176.03      6785510.97
#Sta/Elev= 27
  4852.0  426.92  4855.5  426.92  4866.1  424.41  4866.4  424.33  4880.3  420.67
  4894.4  417.61  4906.5  416.70  4906.8  416.20  4910.3  416.20  4910.5  416.70
  4993.4  416.76  5007.5  416.77  5134.8  417.04  5149.0  417.36  5163.1  417.97
  5164.8  417.99  5177.2  418.10  5191.4  419.31  5199.8  419.88  5205.5  420.26
  5219.7  421.49  5276.2  424.92  5304.5  425.99  5318.7  427.12  5332.8  428.40
  5343.4  429.13  5346.9  429.13
#Mann=6,-1,0
  4852.0    0.12       0  4866.4    0.05       0  4906.5    0.03       0
  4910.5    0.05       0  5164.8    0.12       0  5199.8    0.05       0
Bank Sta=4906.5,4910.5
Exp/Cntr=0.3,0.1

Type RM Length L Ch R = 1,2483,762,762,762
BEGIN DESCRIPTION:
1623
END DESCRIPTION:
XS GIS Cut Line= 3
      2789211.76      6785147.82      2788135.41      6785017.62
      2787925.99      6784911.00
#Sta/Elev= 30
  3915.8  432.98  3951.8  432.75  4010.7  433.62  4015.8  433.13  4092.6  433.25
  4189.0  431.30  4282.6  429.87  4435.5  428.32  4531.2  428.19  4556.2  427.78
  4586.4  428.46  4606.6  426.91  4616.6  425.70  4656.9  418.19  4667.0  416.82
  4672.2  416.81  4977.3  416.46  4977.5  415.96  4981.0  415.96  4981.3  416.46
  5048.7  416.82  5097.8  423.10  5132.1  426.10  5137.7  425.77  5156.3  427.05
  5176.6  427.92  5204.4  427.33  5221.1  429.25  5226.7  428.55  5235.0  428.74
#Mann=9,-1,0
  3915.8    0.05       0  4189.0    0.12       0  4282.6    0.05       0
  4531.2    0.12       0  4672.2    0.05       0  4977.3    0.04       0
  4981.3    0.05       0  5097.8    0.12       0  5156.3    0.05       0
Bank Sta=4977.3,4981.3
Exp/Cntr=0.3,0.1

Type RM Length L Ch R = 1,1721,62,62,62
BEGIN DESCRIPTION:
1622
END DESCRIPTION:
XS GIS Cut Line= 3
      2788640.94      6784554.95      2788342.53      6784578.02
      2787876.04      6784860.98
#Sta/Elev= 30
  4700.7  422.30  4765.8  422.95  4806.0  422.82  4836.0  422.22  4842.6  422.01
  4847.6  421.27  4866.1  420.50  4896.2  418.58  4916.3  418.04  4926.3  417.20
  4956.4  416.38  5078.4  416.73  5093.9  416.50  5253.2  416.70  5333.1  416.33
  5333.4  415.83  5336.9  415.83  5337.1  416.33  5338.1  416.36  5393.6  416.78
  5406.1  418.92  5455.5  422.32  5479.7  425.19  5487.2  425.63  5495.2  425.64
  5501.1  426.58  5510.6  427.35  5516.6  427.36  5537.9  428.50  5545.6  428.52
#Mann=5,-1,0
  4700.7    0.05       0  5333.1    0.03       0  5337.1    0.05       0
  5338.1    0.12       0  5455.5    0.05       0
Bank Sta=5333.1,5337.1
Exp/Cntr=0.3,0.1

Type RM Length L Ch R = 1,1659,124,124,124
BEGIN DESCRIPTION:
1621
END DESCRIPTION:
XS GIS Cut Line= 3
      2788528.99      6784444.73      2788299.51      6784533.91
      2787845.57      6784775.24
#Sta/Elev= 30
  4753.8  422.81  4893.2  421.44  4923.1  419.07  4947.7  420.92  4953.0  419.71
  5111.3  419.43  5127.6  420.77  5133.2  418.24  5139.9  420.24  5149.6  420.62
  5155.2  418.74  5162.7  420.17  5177.2  419.23  5193.5  420.71  5199.2  418.34
  5214.4  420.64  5221.1  419.09  5259.4  420.85  5265.1  418.84  5276.2  420.38
  5279.4  418.08  5279.7  417.58  5283.4  418.08  5297.7  420.75  5303.4  418.41
  5319.7  420.88  5325.4  418.68  5341.7  420.81  5389.7  420.94  5514.1  423.46
#Mann=7,-1,0
  4753.8    0.05       0  5162.7    0.12       0  5214.4    0.05       0
  5276.2    0.12       0  5279.4    0.04       0  5283.4    0.12       0
  5389.7    0.05       0
Bank Sta=5279.4,5283.4
Exp/Cntr=0.3,0.1

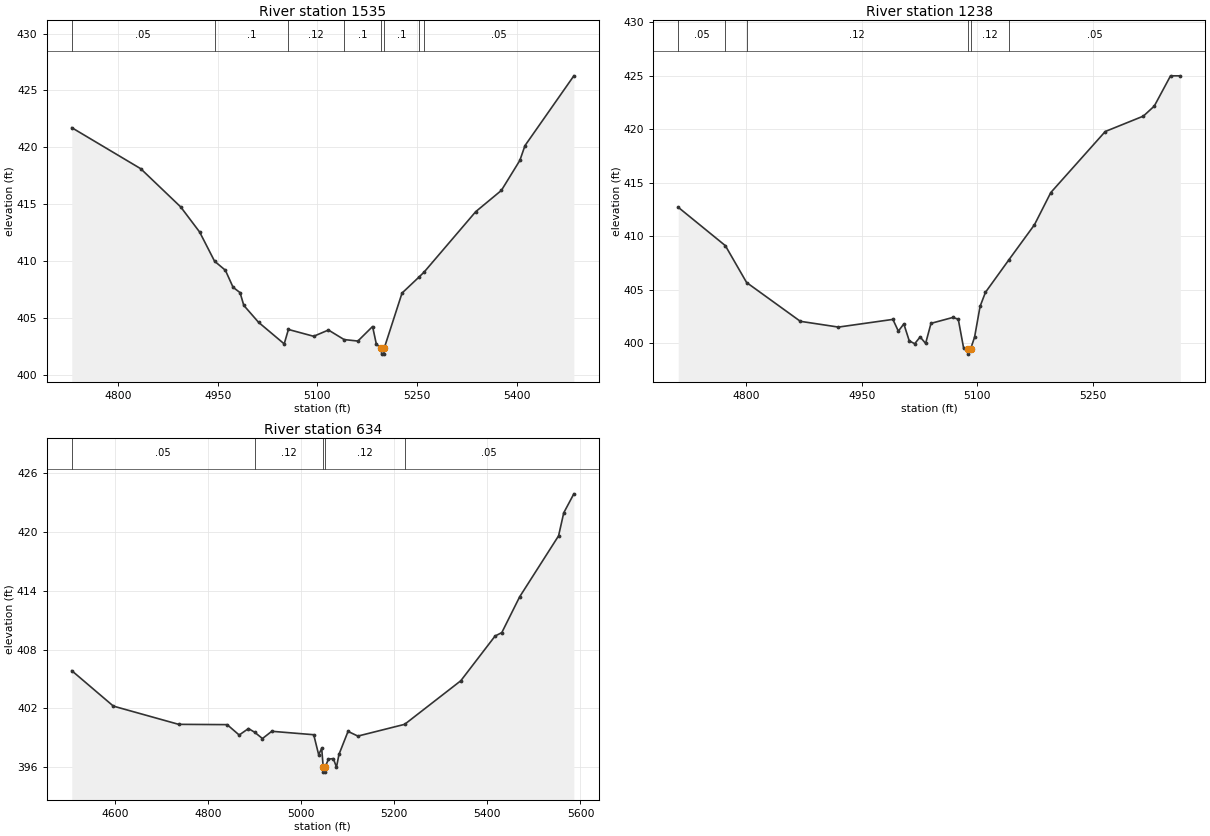
Type RM Length L Ch R = 1,1535,297,297,297
BEGIN DESCRIPTION:
2456
END DESCRIPTION:
XS GIS Cut Line= 2
      2788421.55      6784387.58      2787750.72      6784734.23
#Sta/Elev= 30
  4730.6  421.72  4834.3  418.11  4894.4  414.75  4922.9  412.54  4945.4  409.97
  4961.6  409.18  4973.2  407.68  4983.7  407.21  4989.3  406.09  5011.5  404.60
  5050.1  402.70  5056.4  403.97  5094.4  403.37  5116.6  403.92  5140.2  403.08
  5160.9  402.95  5183.0  404.23  5188.7  402.67  5196.4  402.30  5196.6  401.80
  5200.1  401.80  5200.4  402.30  5227.3  407.17  5253.0  408.59  5260.4  409.01
  5338.1  414.33  5376.7  416.20  5404.5  418.84  5412.2  420.14  5485.7  426.28
#Mann=8,-1,0
  4730.6    0.05       0  4945.4     0.1       0  5056.4    0.12       0
  5140.2     0.1       0  5196.4    0.07       0  5200.4     0.1       0
  5253.0    0.12       0  5260.4    0.05       0
Bank Sta=5196.4,5200.4
Exp/Cntr=0.3,0.1

Type RM Length L Ch R = 1,1238,604,604,604
BEGIN DESCRIPTION:
2457
END DESCRIPTION:
XS GIS Cut Line= 2
      2788128.03      6784208.71      2787664.16      6784667.04
#Sta/Elev= 30
  4711.7  412.70  4772.9  409.11  4800.5  405.66  4870.3  402.03  4919.8  401.49
  4990.5  402.21  4997.6  401.11  5004.7  401.79  5011.7  400.21  5018.8  399.93
  5025.9  400.57  5033.0  399.96  5040.0  401.84  5068.3  402.39  5075.4  402.23
  5082.4  399.51  5087.5  399.46  5087.8  398.96  5091.5  399.46  5096.6  400.55
  5103.7  403.42  5110.7  404.74  5141.0  407.77  5174.4  411.07  5195.6  414.08
  5266.3  419.79  5315.8  421.23  5330.0  422.17  5351.1  425.00  5363.8  425.00
#Mann=6,-1,0
  4711.7    0.05       0  4772.9     0.1       0  4800.5    0.12       0
  5087.5    0.07       0  5091.5    0.12       0  5141.0    0.05       0
Bank Sta=5087.5,5091.5
Exp/Cntr=0.3,0.1

Type RM Length L Ch R = 1,634,0,0,0
BEGIN DESCRIPTION:
1620
END DESCRIPTION:
XS GIS Cut Line= 3
      2788065.40      6784124.01      2787576.19      6784112.24
      2787392.25      6784671.62
#Sta/Elev= 30
  4507.6  405.84  4597.0  402.22  4737.1  400.36  4841.3  400.33  4867.1  399.27
  4887.1  399.93  4900.4  399.55  4917.1  398.91  4937.1  399.65  5027.2  399.30
  5037.8  397.26  5044.3  397.91  5047.6  395.98  5047.8  395.48  5051.3  395.48
  5051.6  395.98  5058.8  396.81  5069.3  396.86  5076.1  395.99  5081.4  397.29
  5100.9  399.64  5122.0  399.16  5222.4  400.36  5343.0  404.81  5416.7  409.38
  5431.1  409.73  5469.4  413.38  5553.0  419.61  5564.1  421.96  5585.8  423.90
#Mann=5,-1,0
  4507.6    0.05       0  4900.4    0.12       0  5047.6    0.07       0
  5051.6    0.12       0  5222.4    0.05       0
Bank Sta=5047.6,5051.6
Exp/Cntr=0.3,0.1

Chan Stop Cuts=-1